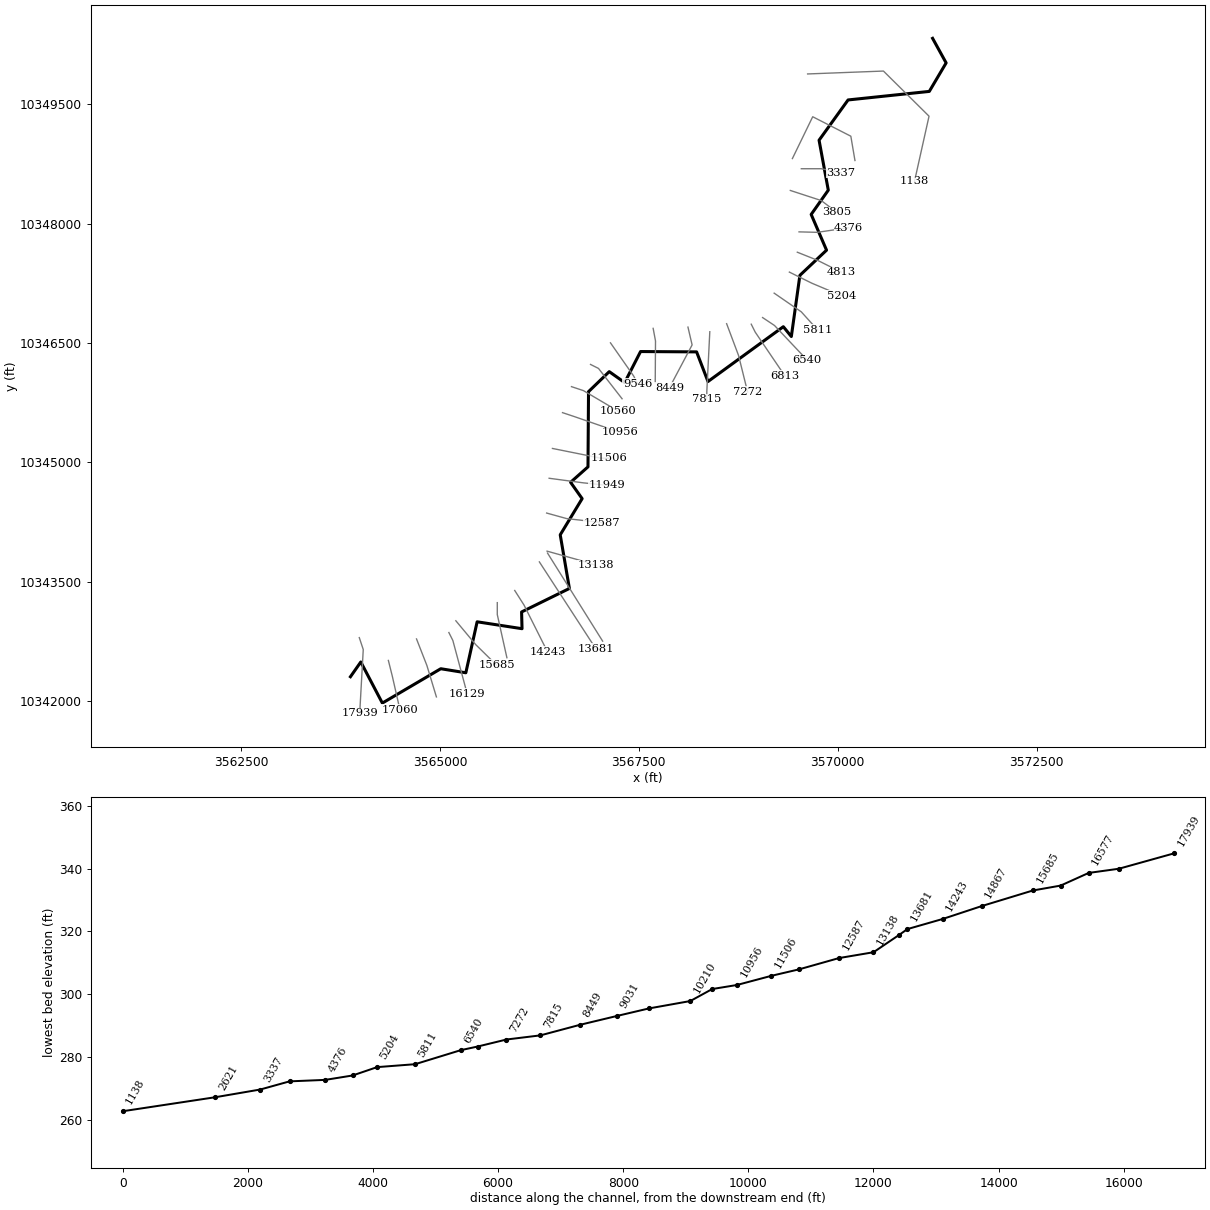
--- BEE BRANCH EAST.prj (project) ---

Proj Title=BEE BRANCH EAST Base Level Engineering
Current Plan=p01
Default Exp/Contr=0.3,0.1
English Units
Geom File=g01
Flow File=f01
Plan File=p01
Y Axis Title=Elevation
X Axis Title(PF)=Main Channel Distance
X Axis Title(XS)=Station
BEGIN DESCRIPTION:
BEE BRANCH EAST
END DESCRIPTION:
DSS Export Rating Curves= 0
DSS Export Rating Curve Sorted= 0
DSS Export Volume Flow Curves= 0
DXF OffsetX= 0
DXF OffsetY= 0
DXF ScaleX= 1
DXF ScaleY= 10

--- BEE BRANCH EAST.p01 (plan) ---

Plan Title=Multiple Run
Short Identifier=Multiple
Geom File=g01
Flow File=f01
Subcritical Flow
K Sum by GR= 0
Std Step Tol= 0.01
Critical Tol= 0.01
Num of Std Step Trials= 20
Max Error Tol= 0.3
Flow Tol Ratio= 0.001
Split Flow NTrial= 30
Split Flow Tol= 0.02
Split Flow Ratio= 0.02
Log Output Level= 0
Friction Slope Method= 1
Unsteady Friction Slope Method= 2
Unsteady Bridges Friction Slope Method= 1
Parabolic Critical Depth
Global Vel Dist=  1 , 1 , 1
Global Log Level= 0
CheckData=True
Encroach Param= -1, 0, 0, 0
BEGIN DESCRIPTION:
Multiple Run
END DESCRIPTION:

--- BEE BRANCH EAST.f01 (steady flow) ---

Flow Title=Multiple
Number of Profiles=7
Profile Names=10-year,25-year,50-year,1pct_min,100-year,1pct_plu,500-year
River Rch & RM= BEE BRANCH EAST,Reach-1,17939
     632     863    1055     945    1278    1728    1880
River Rch & RM= BEE BRANCH EAST,Reach-1,15685
     903    1251    1541    1390    1880    2542    2804
Boundary for River Rch & Prof#=BEE BRANCH EAST,Reach-1,1
Up Type=0
Dn Type=3
Dn Slope=0.005
Boundary for River Rch & Prof#=BEE BRANCH EAST,Reach-1,2
Up Type=0
Dn Type=3
Dn Slope=0.005
Boundary for River Rch & Prof#=BEE BRANCH EAST,Reach-1,3
Up Type=0
Dn Type=3
Dn Slope=0.005
Boundary for River Rch & Prof#=BEE BRANCH EAST,Reach-1,4
Up Type=0
Dn Type=3
Dn Slope=0.005
Boundary for River Rch & Prof#=BEE BRANCH EAST,Reach-1,5
Up Type=0
Dn Type=3
Dn Slope=0.005
Boundary for River Rch & Prof#=BEE BRANCH EAST,Reach-1,6
Up Type=0
Dn Type=3
Dn Slope=0.005
Boundary for River Rch & Prof#=BEE BRANCH EAST,Reach-1,7
Up Type=0
Dn Type=3
Dn Slope=0.005

--- BEE BRANCH EAST.g01 (geometry) ---

Geom Title=Existing Conditions
Program Version=4.10

River Reach=BEE BRANCH EAST ,Reach-1
Reach XY= 30
      3563875.93     10342302.52      3564006.01     10342488.14
      3564276.86     10341971.15      3565011.21     10342403.15
      3565325.88     10342352.15      3565468.03     10342993.43
      3566032.26     10342906.62      3566026.84     10343117.13
      3566627.54     10343412.55      3566512.36     10344087.45
       3566787.7     10344542.38      3566642.52     10344747.81
      3566861.18     10344942.22      3566867.95     10345887.81
      3567128.32     10346139.68      3567322.36     10346002.03
      3567521.88     10346392.34      3568226.19      10346388.2
      3568369.25     10346015.28      3569316.23     10346704.95
       3569416.8     10346581.15      3569524.38     10347351.04
      3569859.33     10347667.35      3569666.24     10348116.76
       3569881.2       10348422.      3569765.34      10349050.3
      3570129.84     10349556.71      3571150.59      10349664.1
      3571362.24     10350022.56      3571192.11     10350331.64

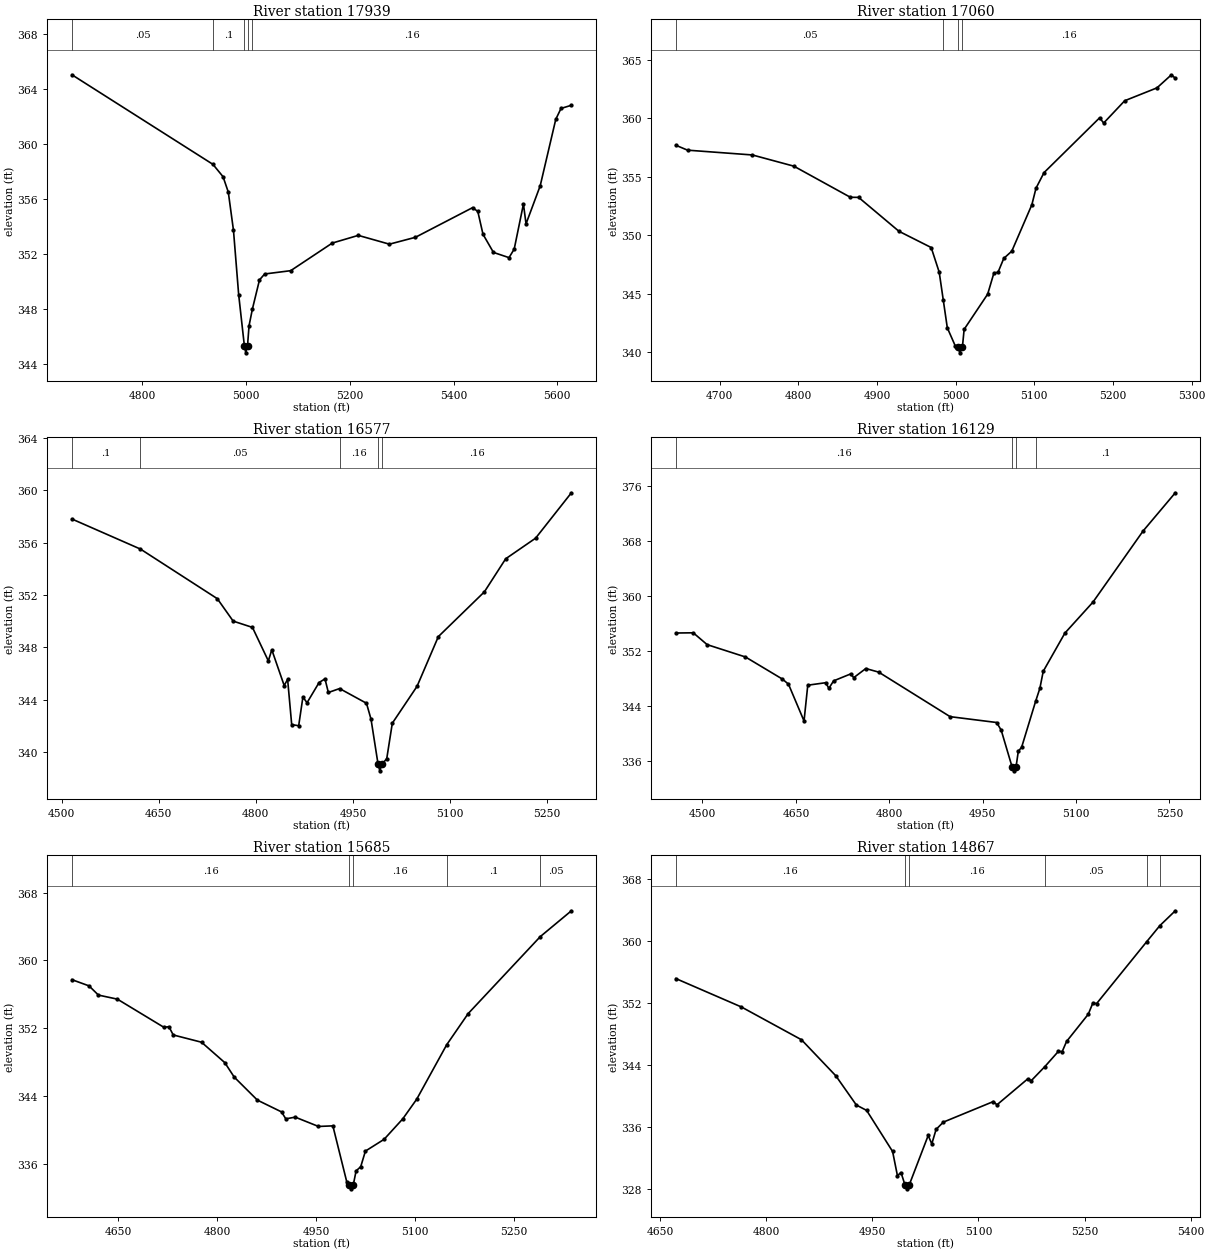
Type RM Length L Ch R = 1 ,17939   ,879,879,879
BEGIN DESCRIPTION:
BEE BRANCH EAST 35.0
END DESCRIPTION:
XS GIS Cut Line= 3
      3563986.92     10342794.47      3564036.92     10342644.47
      3563992.11     10341841.63
#Sta/Elev= 30
  4664.9  365.04  4936.5  358.52    4956  357.62  4966.1   356.5  4976.1  353.71
  4986.1  349.03  4997.1   345.3  4999.8   344.8  5003.1   345.3  5006.1  346.78
  5012.6     348  5026.2  350.11  5036.2  350.54  5086.3  350.78  5166.4  352.79
  5216.5  353.35  5276.5  352.71  5326.6  353.21  5436.8  355.37  5446.8  355.09
  5456.8  353.43  5476.9  352.11  5506.9  351.73  5516.9  352.35  5534.7  355.63
  5539.7  354.19    5567  356.96    5597   361.8  5607.1  362.59  5627.1  362.82
#Mann= 5 ,-1 , 0
  4664.9     .05       0  4936.5      .1       0  4997.1     .07       0
  5003.1      .1       0  5012.6     .16       0
Bank Sta=4997.1,5003.1
XS Rating Curve= 0 ,0
Exp/Cntr=0.3,0.1

Type RM Length L Ch R = 1 ,17060   ,483,483,483
BEGIN DESCRIPTION:
BEE BRANCH EAST 33.0
END DESCRIPTION:
XS GIS Cut Line= 3
      3564352.53     10342507.22      3564402.52     10342307.27
      3564497.51     10341888.92
#Sta/Elev= 30
  4644.1  357.69    4659  357.27  4741.4  356.86  4794.2   355.9    4866  353.24
  4876.5  353.23  4927.8  350.33  4968.8  348.94    4979  346.83  4984.2  344.43
  4989.3  342.07  4999.5  340.51  5002.5  340.43  5005.3  339.93  5008.5  340.43
  5010.7  341.94  5040.6  344.95  5048.6  346.77  5053.7  346.81  5061.1  348.01
  5071.3  348.63  5096.8   352.6  5102.1  354.02  5112.3  355.35    5183  360.04
  5188.1  359.59  5214.9   361.5  5255.9   362.6  5274.3  363.72  5279.2  363.42
#Mann= 4 ,-1 , 0
  4644.1     .05       0  4984.2     .16       0  5002.5     .07       0
  5008.5     .16       0
Bank Sta=5002.5,5008.5
XS Rating Curve= 0 ,0
Exp/Cntr=0.3,0.1

Type RM Length L Ch R = 1 ,16577   ,448,448,448
BEGIN DESCRIPTION:
BEE BRANCH EAST 32.0
END DESCRIPTION:
XS GIS Cut Line= 3
      3564706.24     10342777.82      3564836.45     10342444.47
      3564956.23     10342048.68
#Sta/Elev= 30
  4516.1  357.79  4621.9   355.5  4740.6  351.72  4765.1  350.01  4794.9  349.53
  4819.4  346.98  4824.8  347.82  4843.9   345.1  4849.2  345.57  4855.5  342.12
  4866.3  342.04  4872.8  344.22  4879.2  343.79  4897.8  345.33  4906.9  345.61
  4912.1  344.57  4929.5  344.87    4971  343.75    4978  342.54  4988.9   339.1
  4991.6   338.6  4994.9   339.1  5002.3  339.53  5010.9  342.23  5049.1  345.04
    5082  348.83  5153.1  352.24    5186  354.76  5232.2  356.33  5287.5  359.79
#Mann= 5 ,-1 , 0
  4516.1      .1       0  4621.9     .05       0  4929.5     .16       0
  4988.9     .07       0  4994.9     .16       0
Bank Sta=4988.9,4994.9
XS Rating Curve= 0 ,0
Exp/Cntr=0.3,0.1

Type RM Length L Ch R = 1 ,16129   ,444,444,444
BEGIN DESCRIPTION:
BEE BRANCH EAST 31.0
END DESCRIPTION:
XS GIS Cut Line= 3
      3565112.92     10342858.34      3565162.94     10342758.31
      3565342.12      10342091.6
#Sta/Elev= 30
  4457.2   354.6  4485.2  354.63  4507.5  352.91    4569  351.12  4628.3  347.91
  4638.1  347.17  4663.1  341.82  4669.1  347.02  4697.8  347.38    4703  346.57
  4710.6  347.65  4737.8  348.65    4743  348.12  4762.3  349.44    4783  348.92
  4897.7  342.45  4972.5   341.6  4979.8  340.48  4997.5  335.08  5000.2  334.58
  5003.5  335.08  5007.3  337.45  5012.5  337.98    5035  344.66  5041.9  346.57
  5047.3  349.04  5082.1  354.59  5127.2  359.09  5207.6  369.41  5259.4  374.97
#Mann= 4 ,-1 , 0
  4457.2     .16       0  4997.5     .07       0  5003.5     .16       0
    5035      .1       0
Bank Sta=4997.5,5003.5
XS Rating Curve= 0 ,0
Exp/Cntr=0.3,0.1

Type RM Length L Ch R = 1 ,15685   ,818,818,818
BEGIN DESCRIPTION:
BEE BRANCH EAST 30.0
END DESCRIPTION:
XS GIS Cut Line= 3
      3565200.41     10343006.26      3565450.44     10342706.23
      3565711.42     10342449.71
#Sta/Elev= 30
  4580.1  357.73  4605.9     357  4620.2  355.91  4648.9  355.43  4719.2  352.11
    4727  352.17  4733.5   351.2  4776.4  350.34  4811.6  347.93  4825.9  346.22
    4861   343.5  4897.5  342.11    4904  341.29  4918.3  341.49  4953.5  340.39
  4975.3  340.46  4996.3  333.86  5000.3  333.52  5003.1  333.02  5006.3  333.52
  5010.5  335.14  5017.5  335.64  5024.6  337.48  5052.9  338.87  5081.2  341.29
  5102.3  343.61  5147.7  350.04  5180.2  353.72  5289.5  362.82  5336.6  365.87
#Mann= 5 ,-1 , 0
  4580.1     .16       0  5000.3     .07       0  5006.3     .16       0
  5147.7      .1       0  5289.5     .05       0
Bank Sta=5000.3,5006.3
XS Rating Curve= 0 ,0
Exp/Cntr=0.3,0.1

Type RM Length L Ch R = 1 ,14867   ,624,624,624
BEGIN DESCRIPTION:
BEE BRANCH EAST 29.0
END DESCRIPTION:
XS GIS Cut Line= 3
      3565721.27     10343234.34      3565721.27     10343084.35
      3565842.11     10342541.63
#Sta/Elev= 30
  4672.2  355.15  4764.9  351.49  4849.8  347.27  4898.4  342.62  4927.4  338.86
  4941.9  338.17  4978.6  332.88  4985.4  329.78  4990.5  330.17  4996.1  328.57
  4998.9  328.07  5002.1  328.57  5028.9  334.94    5034  333.86  5040.1  335.73
  5050.3  336.66    5121  339.31  5126.1  338.89  5169.6  342.23  5174.8  342.02
  5193.9  343.82  5213.1  345.79  5218.3  345.74  5224.5  347.05  5255.2  350.56
  5261.8  352.03  5266.9  351.92  5337.7  359.89  5356.3  361.96  5378.2  363.88
#Mann= 6 ,-1 , 0
  4672.2     .16       0  4996.1     .07       0  5002.1     .16       0
  5193.9     .05       0  5337.7      .1       0  5356.3     .05       0
Bank Sta=4996.1,5002.1
XS Rating Curve= 0 ,0
Exp/Cntr=0.3,0.1

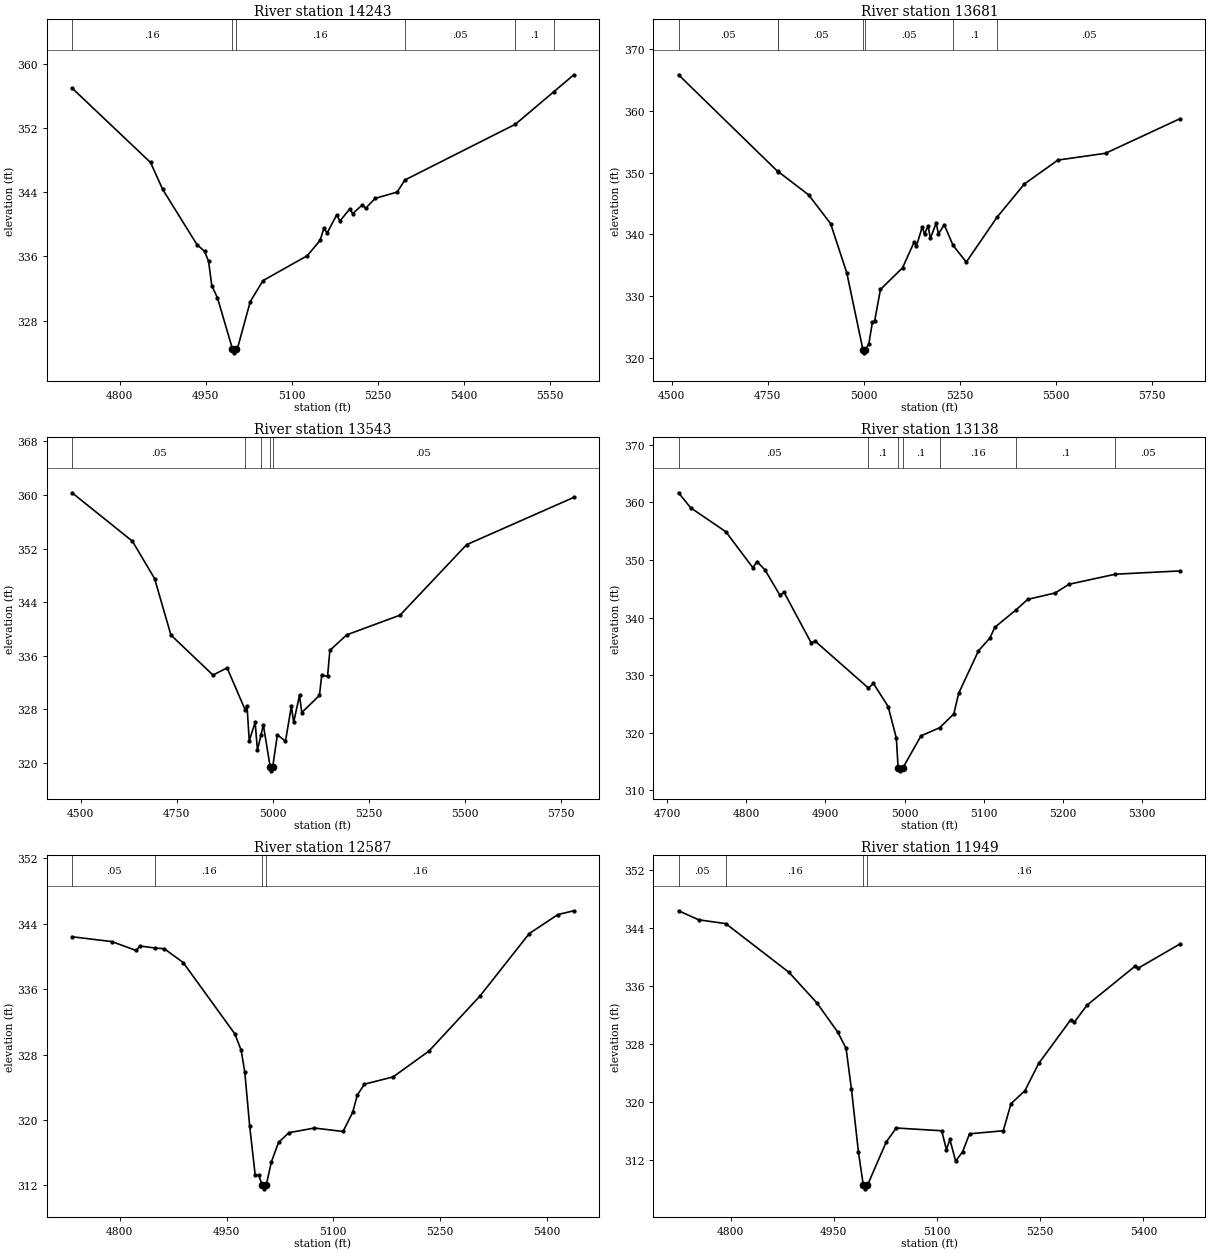
Type RM Length L Ch R = 1 ,14243   ,562,562,562
BEGIN DESCRIPTION:
BEE BRANCH EAST 28.0
END DESCRIPTION:
XS GIS Cut Line= 3
      3565940.61      10343387.2      3566057.73      10343203.1
      3566352.01     10342616.47
#Sta/Elev= 30
  4716.9  357.02  4853.7  347.73  4874.8  344.37  4934.5  337.49  4947.9  336.63
  4954.8  335.39  4960.4  332.35  4970.3  330.83  4996.4  324.47  4999.2  323.97
  5002.4  324.47    5005  324.48  5027.4  330.36  5049.7  332.99  5126.9   336.1
  5149.3  338.02  5155.8  339.55  5161.4  338.92  5178.1   341.2  5183.7  340.42
  5200.5   341.9  5206.1  341.35  5222.8  342.46  5228.4  342.01  5245.2  343.25
  5283.5  344.04  5296.8  345.54  5489.6  352.51  5556.4  356.56  5591.4  358.68
#Mann= 6 ,-1 , 0
  4716.9     .16       0  4996.4     .07       0  5002.4     .16       0
  5296.8     .05       0  5489.6      .1       0  5556.4     .05       0
Bank Sta=4996.4,5002.4
XS Rating Curve= 0 ,0
Exp/Cntr=0.3,0.1

Type RM Length L Ch R = 1 ,13681   ,138,138,138
BEGIN DESCRIPTION:
BEE BRANCH EAST 27.0
END DESCRIPTION:
XS GIS Cut Line= 2
      3566250.17     10343746.72      3566961.95     10342651.26
#Sta/Elev= 30
  4517.9  365.89    4776  350.21  4778.1  350.14  4856.5  346.41  4913.8  341.73
    4956  333.74    4998  321.27  5000.7  320.77    5004  321.27  5013.3   322.2
  5022.5   325.7  5028.5  325.94  5043.6  331.06    5101  334.56  5131.3  338.73
  5137.2  338.08  5152.4  341.21  5158.3  340.03  5167.5  341.39  5173.5  339.35
  5188.6  341.81  5194.6  340.07  5209.7  341.55  5232.8  338.19    5267  335.49
  5346.9  342.76  5418.4  348.18  5505.6  352.05  5629.5  353.15  5824.3  358.79
#Mann= 7 ,-1 , 0
  4517.9     .05       0    4776     .16       0  4778.1     .05       0
    4998     .04       0    5004     .05       0  5232.8      .1       0
  5346.9     .05       0
Bank Sta=4998,5004
XS Rating Curve= 0 ,0
Exp/Cntr=0.3,0.1

Type RM Length L Ch R = 1 ,13543   ,405,405,405
BEGIN DESCRIPTION:
Mapping XS c51a4e19
END DESCRIPTION:
XS GIS Cut Line= 2
      3566352.55      10343857.9       3567045.3     10342750.19
#Sta/Elev= 30
  4477.5  360.32  4634.6   353.1  4692.4  347.52  4734.9   339.1  4844.5  333.13
  4881.1  334.21  4928.3  327.93    4933  328.57  4938.8  323.33  4954.2  326.09
  4960.1  321.94  4969.4  324.18  4975.4  325.74  4993.6  319.35  4996.4  318.85
  4999.6  319.35    5012  324.22  5033.2  323.28  5048.5  328.48  5054.4  326.07
  5069.7  330.11  5075.6  327.54  5121.6   330.1  5127.5  333.11  5142.8  332.94
  5148.7  336.81  5192.6  339.13  5331.5  342.07  5504.8  352.58    5784  359.64
#Mann= 5 ,-1 , 0
  4477.5     .05       0  4928.3      .1       0  4969.4     .05       0
  4993.6     .04       0  4999.6     .05       0
Bank Sta=4993.6,4999.6
XS Rating Curve= 0 ,0
Exp/Cntr=0.3,0.1

Type RM Length L Ch R = 1 ,13138   ,551,551,551
BEGIN DESCRIPTION:
BEE BRANCH EAST 25.0
END DESCRIPTION:
XS GIS Cut Line= 3
      3566346.85     10343881.98      3566805.65     10343754.14
      3566955.66     10343704.14
#Sta/Elev= 30
  4714.3  361.67  4729.6  359.07  4774.1  354.91  4808.3  348.66  4813.5  349.73
  4823.6  348.28  4842.5  343.88  4847.7   344.4  4881.9  335.65  4887.1  335.91
  4954.4  327.78  4960.7  328.58  4979.3  324.57  4989.7  319.07  4991.9  313.91
  4994.7  313.41  4997.9  313.91  5020.8  319.48  5044.5   320.9  5062.3  323.28
  5068.5  326.88  5093.5  334.24  5107.9  336.45  5114.2  338.33  5140.5  341.29
  5155.8  343.17  5190.6  344.29  5207.9  345.79  5266.7  347.54  5348.7  348.11
#Mann= 7 ,-1 , 0
  4714.3     .05       0  4954.4      .1       0  4991.9     .07       0
  4997.9      .1       0  5044.5     .16       0  5140.5      .1       0
  5266.7     .05       0
Bank Sta=4991.9,4997.9
XS Rating Curve= 0 ,0
Exp/Cntr=0.3,0.1

Type RM Length L Ch R = 1 ,12587   ,638,638,638
BEGIN DESCRIPTION:
BEE BRANCH EAST 24.0
END DESCRIPTION:
XS GIS Cut Line= 3
      3566341.69     10344361.13      3566592.11     10344291.64
      3567034.38     10344241.34
#Sta/Elev= 30
  4732.9  342.41  4788.7  341.82    4823  340.73  4828.2  341.28  4849.8  341.03
  4862.5  340.94    4889  339.26  4961.6  330.52  4970.5  328.52  4975.6  325.82
  4982.4  319.26  4990.2  313.22  4995.3  313.22  4999.8  312.06  5002.6  311.56
  5005.8  312.06  5012.9  314.85    5023  317.24  5037.5  318.43  5073.3     319
  5113.6  318.58  5127.1  320.91  5133.7  323.04  5143.7  324.37    5184  325.26
  5234.3  328.42  5306.2  335.18  5375.2   342.8  5415.5  345.13  5437.9  345.59
#Mann= 4 ,-1 , 0
  4732.9     .05       0  4849.8     .16       0  4999.8     .07       0
  5005.8     .16       0
Bank Sta=4999.8,5005.8
XS Rating Curve= 0 ,0
Exp/Cntr=0.3,0.1

Type RM Length L Ch R = 1 ,11949   ,443,443,443
BEGIN DESCRIPTION:
BEE BRANCH EAST 23.0
END DESCRIPTION:
XS GIS Cut Line= 3
      3566372.89     10344798.64      3566799.99     10344741.34
      3567096.83      10344710.1
#Sta/Elev= 30
  4724.4  346.33  4753.9  345.08  4793.1  344.56  4884.9  337.84  4925.4  333.64
  4955.7  329.61  4967.9  327.37  4975.8  321.69  4985.9  313.05    4993  308.48
  4995.8  307.98    4999  308.48  5026.3  314.44  5040.8  316.37    5107  315.99
  5113.8  313.37  5118.8  314.79  5127.2   311.8  5137.3  313.09  5147.4  315.57
  5196.4  315.99  5207.7  319.73  5227.8   321.5  5247.9  325.27  5294.5   331.3
  5299.5  330.95  5318.3  333.32  5387.5  338.65  5392.5  338.41  5453.8  341.78
#Mann= 4 ,-1 , 0
  4724.4     .05       0  4793.1     .16       0    4993     .07       0
    4999     .16       0
Bank Sta=4993,4999
XS Rating Curve= 0 ,0
Exp/Cntr=0.3,0.1

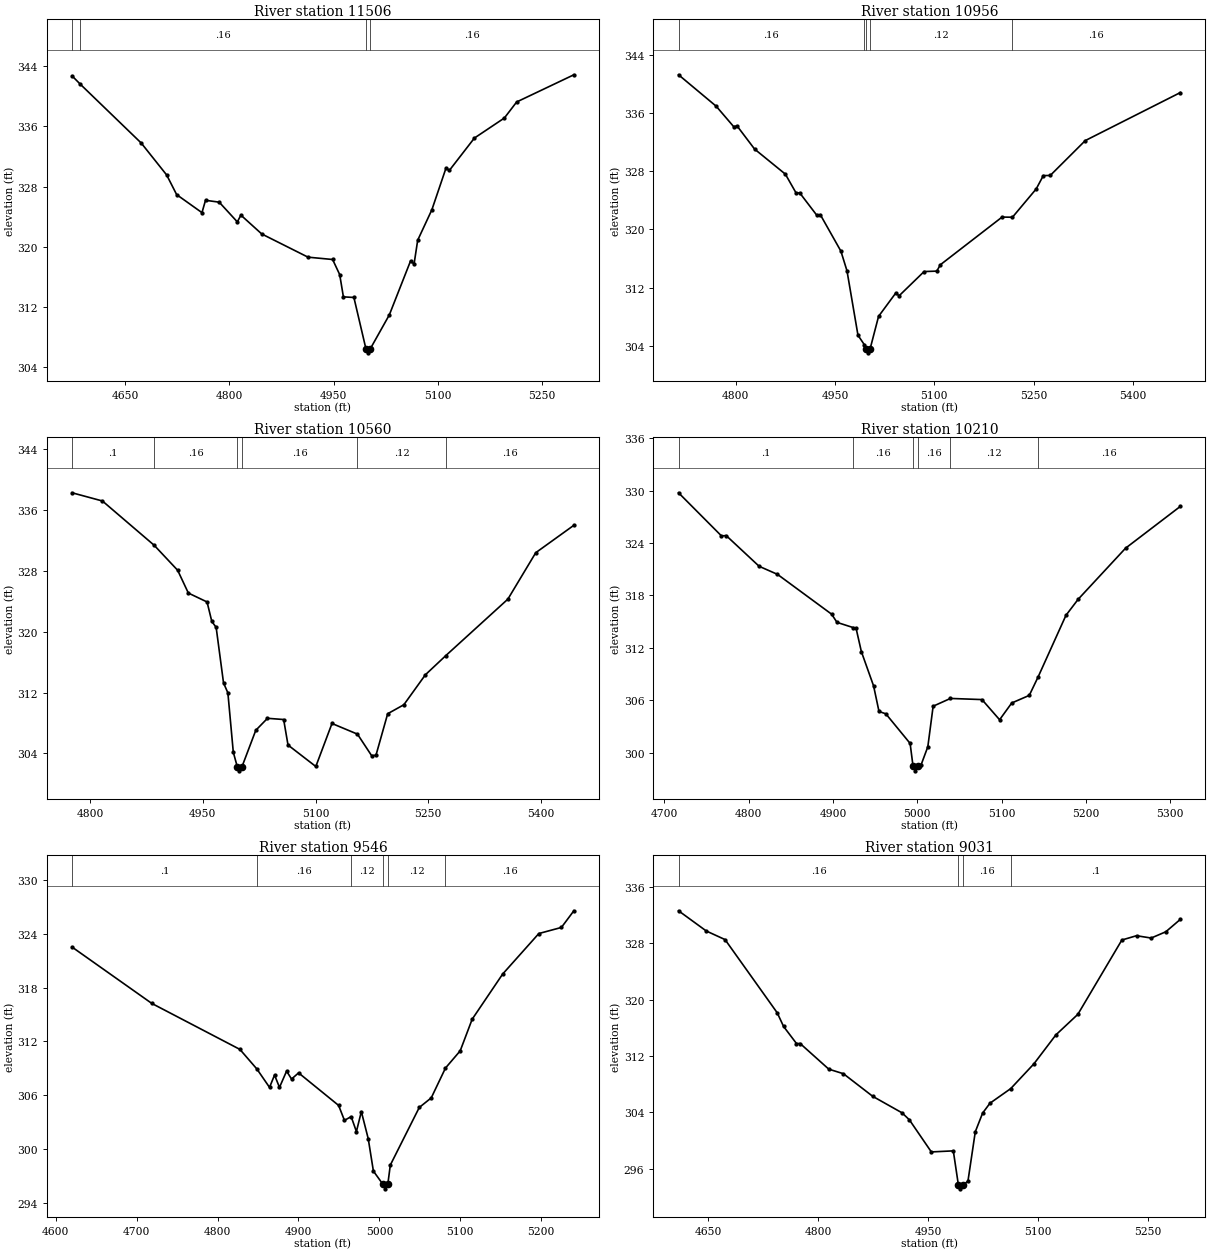
Type RM Length L Ch R = 1 ,11506   ,550,550,550
BEGIN DESCRIPTION:
BEE BRANCH EAST 22.0
END DESCRIPTION:
XS GIS Cut Line= 3
      3566414.56     10345173.64       3567024.4     10345051.02
      3567124.36     10345051.02
#Sta/Elev= 30
  4573.8  342.68  4585.4   341.6  4673.3  333.77  4709.9  329.53  4724.3  326.92
  4760.7  324.53  4765.8  326.17  4785.5  325.92  4811.6   323.3  4816.7   324.2
  4846.7   321.7  4913.3  318.62  4948.7  318.31  4958.9   316.3  4964.2  313.35
  4979.3  313.27  4996.7  306.42  4999.4  305.92  5002.7  306.42  5030.3  310.96
  5060.8  318.11  5065.9  317.72  5071.1  320.87  5091.5  324.91  5111.7  330.41
  5116.8  330.15  5152.7  334.43  5195.8  337.09  5213.5  339.22  5295.8  342.83
#Mann= 4 ,-1 , 0
  4573.8     .05       0  4585.4     .16       0  4996.7     .07       0
  5002.7     .16       0
Bank Sta=4996.7,5002.7
XS Rating Curve= 0 ,0
Exp/Cntr=0.3,0.1

Type RM Length L Ch R = 1 ,10956   ,396,396,396
BEGIN DESCRIPTION:
BEE BRANCH EAST 21.0
END DESCRIPTION:
XS GIS Cut Line= 3
      3566541.03     10345623.95      3566691.06     10345573.93
      3567257.75     10345376.96
#Sta/Elev= 30
  4713.7  341.29  4770.6  336.96    4797  334.15  4802.2  334.24  4828.6  331.06
  4875.1  327.61  4891.4     325  4896.7  325.04  4922.6  321.95  4927.9  322.03
    4959  317.01  4968.2   314.3  4984.8  305.43  4994.4  304.13    4997  303.51
  4999.7  303.01    5003  303.51  5015.9  308.03  5041.7  311.22    5047  310.87
  5084.7   314.2  5103.9  314.26  5109.2  315.13  5202.5   321.7  5218.2  321.68
  5254.1  325.58  5264.8  327.41  5275.3  327.43  5328.2  332.23  5471.8  338.84
#Mann= 5 ,-1 , 0
  4713.7     .16       0  4994.4     .12       0    4997     .07       0
    5003     .12       0  5218.2     .16       0
Bank Sta=4997,5003
XS Rating Curve= 0 ,0
Exp/Cntr=0.3,0.1

Type RM Length L Ch R = 1 ,10560   ,350,350,350
BEGIN DESCRIPTION:
BEE BRANCH EAST 20.0
END DESCRIPTION:
XS GIS Cut Line= 3
       3566653.6     10345951.01      3566803.56     10345901.02
      3567242.12     10345641.63
#Sta/Elev= 30
  4776.1  338.24  4816.5  337.16  4885.4  331.34  4916.6  328.06  4930.8  325.07
  4955.7   323.9    4962  321.35  4967.8  320.56  4977.6  313.27  4983.4  311.96
  4990.6  304.17    4996  302.22  4998.8  301.72    5002  302.22  5020.5  307.04
  5036.1  308.62  5057.6  308.46  5063.4  305.11  5100.4  302.29  5121.9  307.94
  5155.8  306.54  5174.6  303.72  5180.4  303.76    5196  309.22  5217.5   310.4
  5246.2  314.34  5273.3  316.85  5355.9  324.27    5393  330.37  5443.7  333.97
#Mann= 6 ,-1 , 0
  4776.1      .1       0  4885.4     .16       0    4996     .07       0
    5002     .16       0  5155.8     .12       0  5273.3     .16       0
Bank Sta=4996,5002
XS Rating Curve= 0 ,0
Exp/Cntr=0.3,0.1

Type RM Length L Ch R = 1 ,10210   ,664,664,664
BEGIN DESCRIPTION:
BEE BRANCH EAST 19.0
END DESCRIPTION:
XS GIS Cut Line= 3
      3566893.13     10346230.19      3566993.15     10346180.18
      3567289.58     10345798.63
#Sta/Elev= 30
  4716.9  329.75  4767.8  324.81  4773.4  324.85  4812.5  321.33  4834.2  320.41
  4898.4  315.85  4904.8  314.91  4923.8  314.32  4927.4  314.24  4933.7  311.56
  4948.2  307.63  4954.6  304.71  4962.7  304.44  4991.5  301.05    4995  298.41
  4997.7  297.91    5001  298.41  5004.3  298.54  5012.5  300.67  5018.8  305.31
  5039.3   306.2  5076.7  306.07  5097.6  303.76    5112  305.68  5132.8  306.55
  5143.5  308.71  5176.3  315.72  5190.8  317.56  5246.9   323.4  5311.9  328.19
#Mann= 6 ,-1 , 0
  4716.9      .1       0  4923.8     .16       0    4995     .07       0
    5001     .16       0  5039.3     .12       0  5143.5     .16       0
Bank Sta=4995,5001
XS Rating Curve= 0 ,0
Exp/Cntr=0.3,0.1

Type RM Length L Ch R = 1 ,9546    ,515,515,515
BEGIN DESCRIPTION:
BEE BRANCH EAST 18.0
END DESCRIPTION:
XS GIS Cut Line= 3
      3567143.72      10346501.8      3567435.86     10346083.31
      3567485.02     10345984.98
#Sta/Elev= 30
  4620.1  322.53  4718.7  316.24  4827.6  311.11  4848.6  308.92  4864.2  306.87
  4870.4  308.25  4876.5  306.87  4885.3  308.69  4891.4   307.8  4900.1  308.49
  4949.6  304.86  4956.8  303.19  4965.1  303.61  4971.6  301.94  4977.7  304.17
  4986.2  301.15  4992.6  297.53  5004.4  296.05  5007.2  295.55  5010.4  296.05
  5013.5   298.2  5049.3  304.63  5064.1   305.7  5081.7  309.03  5099.9  310.95
  5114.7  314.48  5152.4  319.52  5197.1  324.04    5225  324.72  5240.4  326.58
#Mann= 6 ,-1 , 0
  4620.1      .1       0  4848.6     .16       0  4965.1     .12       0
  5004.4     .07       0  5010.4     .12       0  5081.7     .16       0
Bank Sta=5004.4,5010.4
XS Rating Curve= 0 ,0
Exp/Cntr=0.3,0.1

Type RM Length L Ch R = 1 ,9031    ,582,582,582
BEGIN DESCRIPTION:
BEE BRANCH EAST 16.0
END DESCRIPTION:
XS GIS Cut Line= 3
       3567680.2     10346684.05      3567709.81     10346524.98
      3567706.24     10346001.79
#Sta/Elev= 30
  4609.3  332.61  4647.2  329.74  4672.8  328.52    4744  318.13  4752.7  316.19
  4770.3  313.77  4775.3  313.77  4814.4  310.13  4834.4  309.48  4874.4  306.27
  4914.4  303.93  4924.4  302.94  4954.4  298.38  4984.4  298.53  4991.4  293.64
  4994.2  293.14  4997.4  293.64  5004.4  294.24  5014.4  301.24  5024.4  303.89
  5034.4  305.29  5062.8  307.37  5094.4  310.88  5124.4  314.99  5154.4  317.91
  5214.5  328.46  5234.5  329.07  5254.5  328.74  5274.5  329.63  5294.3  331.39
#Mann= 4 ,-1 , 0
  4609.3     .16       0  4991.4     .07       0  4997.4     .16       0
  5062.8      .1       0
Bank Sta=4991.4,4997.4
XS Rating Curve= 0 ,0
Exp/Cntr=0.3,0.1

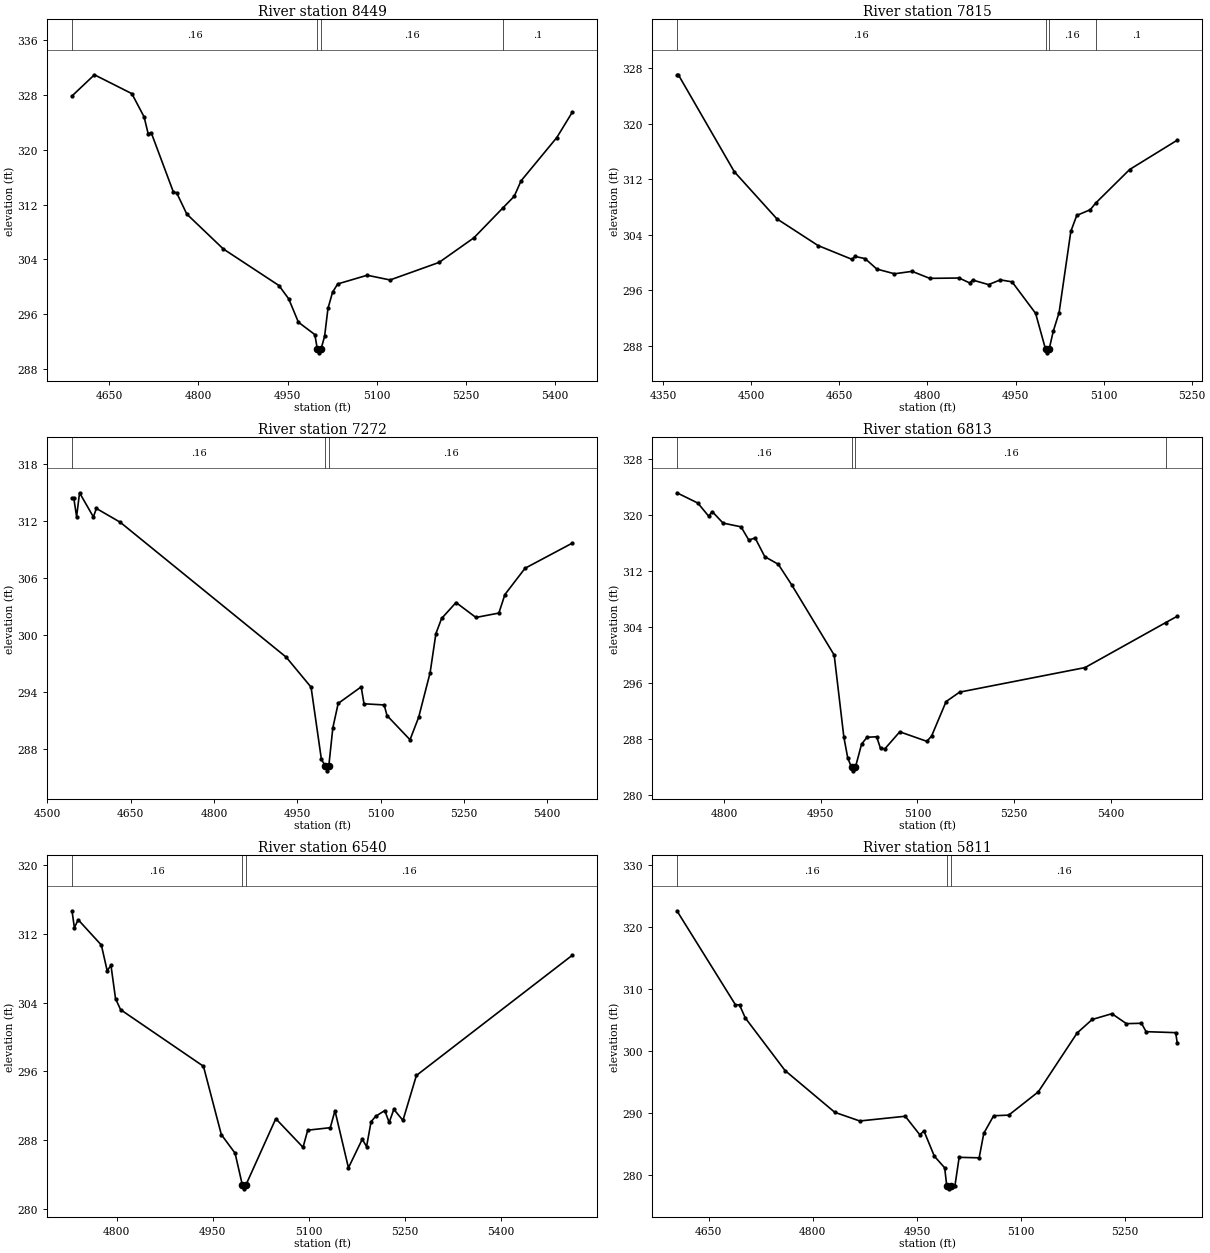
Type RM Length L Ch R = 1 ,8449    ,634,634,634
BEGIN DESCRIPTION:
BEE BRANCH EAST 15.0
END DESCRIPTION:
XS GIS Cut Line= 3
      3568117.71     10346699.65      3568169.79     10346475.72
      3567884.01     10345935.34
#Sta/Elev= 30
  4587.5  327.84  4625.2  330.93  4688.1  328.18  4708.7  324.79  4715.5  322.35
  4720.7  322.48  4758.1  313.79  4763.3  313.74  4780.5  310.61  4841.8  305.53
  4935.4  300.19  4951.8  298.25  4968.1  294.84  4995.8  293.03    5000  290.87
  5002.8  290.37    5006  290.87  5012.2  292.79  5017.8  296.84  5025.6  299.22
  5034.2  300.42  5083.8  301.69  5122.2     301  5204.6  303.56  5263.2  307.15
  5311.7  311.49    5331  313.21  5342.4  315.45  5402.6  321.78  5428.7  325.49
#Mann= 4 ,-1 , 0
  4587.5     .16       0    5000     .07       0    5006     .16       0
  5311.7      .1       0
Bank Sta=5000,5006
XS Rating Curve= 0 ,0
Exp/Cntr=0.3,0.1

Type RM Length L Ch R = 1 ,7815    ,543,543,543
BEGIN DESCRIPTION:
BEE BRANCH EAST 14.0
END DESCRIPTION:
XS GIS Cut Line= 3
      3568392.11     10346641.65      3568354.61      10345890.6
      3568354.61     10345790.58
#Sta/Elev= 30
  4373.4  327.07  4375.9  327.07  4471.1  313.11  4543.6  306.32  4613.7  302.47
  4671.5  300.48  4676.5   300.9  4693.8  300.59  4713.8  299.08  4743.9   298.4
  4773.9  298.75  4803.9  297.74    4854  297.79  4871.9  297.08  4876.9   297.5
  4904.1  296.84  4924.1  297.52  4944.1  297.24  4984.2   292.7  5001.2  287.51
  5003.9  287.01  5007.2  287.51  5014.2   290.1  5024.2  292.82  5044.2  304.52
  5054.3  306.81  5077.3  307.63  5086.2  308.56  5144.3  313.42  5225.4  317.65
#Mann= 4 ,-1 , 0
  4373.4     .16       0  5001.2     .07       0  5007.2     .16       0
  5086.2      .1       0
Bank Sta=5001.2,5007.2
XS Rating Curve= 0 ,0
Exp/Cntr=0.3,0.1

Type RM Length L Ch R = 1 ,7272    ,459,459,459
BEGIN DESCRIPTION:
BEE BRANCH EAST 13.0
END DESCRIPTION:
XS GIS Cut Line= 3
      3568603.56     10346742.69      3568753.56     10346342.68
       3568867.4     10345883.18
#Sta/Elev= 30
  4544.6  314.37  4547.8  314.37  4552.9  312.42  4558.2  314.93  4583.1  312.39
  4588.5  313.28  4631.2  311.84  4930.2  297.64  4974.9  294.49  4993.5  286.89
  5000.8  286.19  5003.5  285.69  5006.8  286.19  5014.1  290.22  5023.7  292.78
  5065.1  294.52  5070.2  292.74  5106.5  292.62  5111.6   291.5    5153  288.96
  5168.6  291.33  5189.2  296.02  5199.6  300.12  5209.8  301.71  5235.8  303.39
  5271.6  301.82  5312.9  302.28  5323.8  304.23    5360  306.99  5445.2  309.64
#Mann= 3 ,-1 , 0
  4544.6     .16       0  5000.8     .07       0  5006.8     .16       0
Bank Sta=5000.8,5006.8
XS Rating Curve= 0 ,0
Exp/Cntr=0.3,0.1

Type RM Length L Ch R = 1 ,6813    ,273,273,273
BEGIN DESCRIPTION:
BEE BRANCH EAST 12.0
END DESCRIPTION:
XS GIS Cut Line= 3
      3568912.93     10346736.44      3568962.94     10346636.43
      3569335.91     10346085.89
#Sta/Elev= 30
  4726.5  323.22    4759  321.75  4775.8  319.88  4781.4  320.53  4798.1  318.89
  4826.1  318.35  4838.2  316.45  4847.9  316.77  4862.9  314.09  4883.9     313
  4904.9  310.03  4970.7  300.02  4985.7   288.3  4991.7  285.32  4997.6  283.97
  5000.4  283.47  5003.6  283.97  5013.2  287.28  5021.6  288.27  5036.6  288.34
  5042.6  286.68  5049.4  286.62  5072.5  289.05  5114.5  287.69  5121.9  288.44
  5144.4  293.37  5165.4  294.72  5360.1  298.23  5485.5  304.67  5503.3  305.57
#Mann= 4 ,-1 , 0
  4726.5     .16       0  4997.6     .07       0  5003.6     .16       0
  5485.5     .05       0
Bank Sta=4997.6,5003.6
XS Rating Curve= 0 ,0
Exp/Cntr=0.3,0.1

Type RM Length L Ch R = 1 ,6540    ,729,729,729
BEGIN DESCRIPTION:
BEE BRANCH EAST 11.0
END DESCRIPTION:
XS GIS Cut Line= 3
      3569055.62     10346819.79      3569205.65     10346719.77
      3569617.38     10346283.35
#Sta/Elev= 30
  4730.5  314.72  4734.2  312.76  4740.2  313.67  4776.3  310.72  4785.3  307.75
  4791.3  308.34  4798.4  304.47  4806.3  303.19  4935.5  296.59  4963.4  288.62
  4984.8  286.46    4996   282.8  4998.7   282.3    5002   282.8  5048.3  290.48
  5090.8  287.14  5098.1  289.14  5133.3  289.43  5140.6  291.41  5161.6  284.75
  5183.1  288.08  5189.9  287.23  5196.9  290.13  5204.1  290.76  5218.3  291.43
  5225.1  290.04  5232.4  291.57  5246.6  290.28  5267.6  295.52  5510.8  309.54
#Mann= 3 ,-1 , 0
  4730.5     .16       0    4996     .07       0    5002     .16       0
Bank Sta=4996,5002
XS Rating Curve= 0 ,0
Exp/Cntr=0.3,0.1

Type RM Length L Ch R = 1 ,5811    ,607,607,607
BEGIN DESCRIPTION:
BEE BRANCH EAST 10.0
END DESCRIPTION:
XS GIS Cut Line= 3
      3569201.04     10347126.76      3569542.11     10346891.64
       3569747.5     10346663.68
#Sta/Elev= 30
  4604.1  322.59  4688.4  307.48  4694.4  307.44  4702.6  305.36    4760  296.88
  4831.7  290.16  4867.6  288.77  4933.2  289.53  4954.1  286.56  4960.2  287.15
  4975.1  283.11    4990  281.23    4993  278.35  4995.8  277.85    4999  278.35
  5004.8  278.35  5010.9  282.92  5039.7  282.84  5046.4  286.79  5060.6  289.61
  5082.3  289.71  5124.9  293.45  5180.9  302.93  5202.6   305.1    5231  306.03
  5251.9  304.43  5273.6  304.49  5280.3  303.14  5322.9  302.98  5325.2   301.3
#Mann= 3 ,-1 , 0
  4604.1     .16       0    4993     .07       0    4999     .16       0
Bank Sta=4993,4999
XS Rating Curve= 0 ,0
Exp/Cntr=0.3,0.1

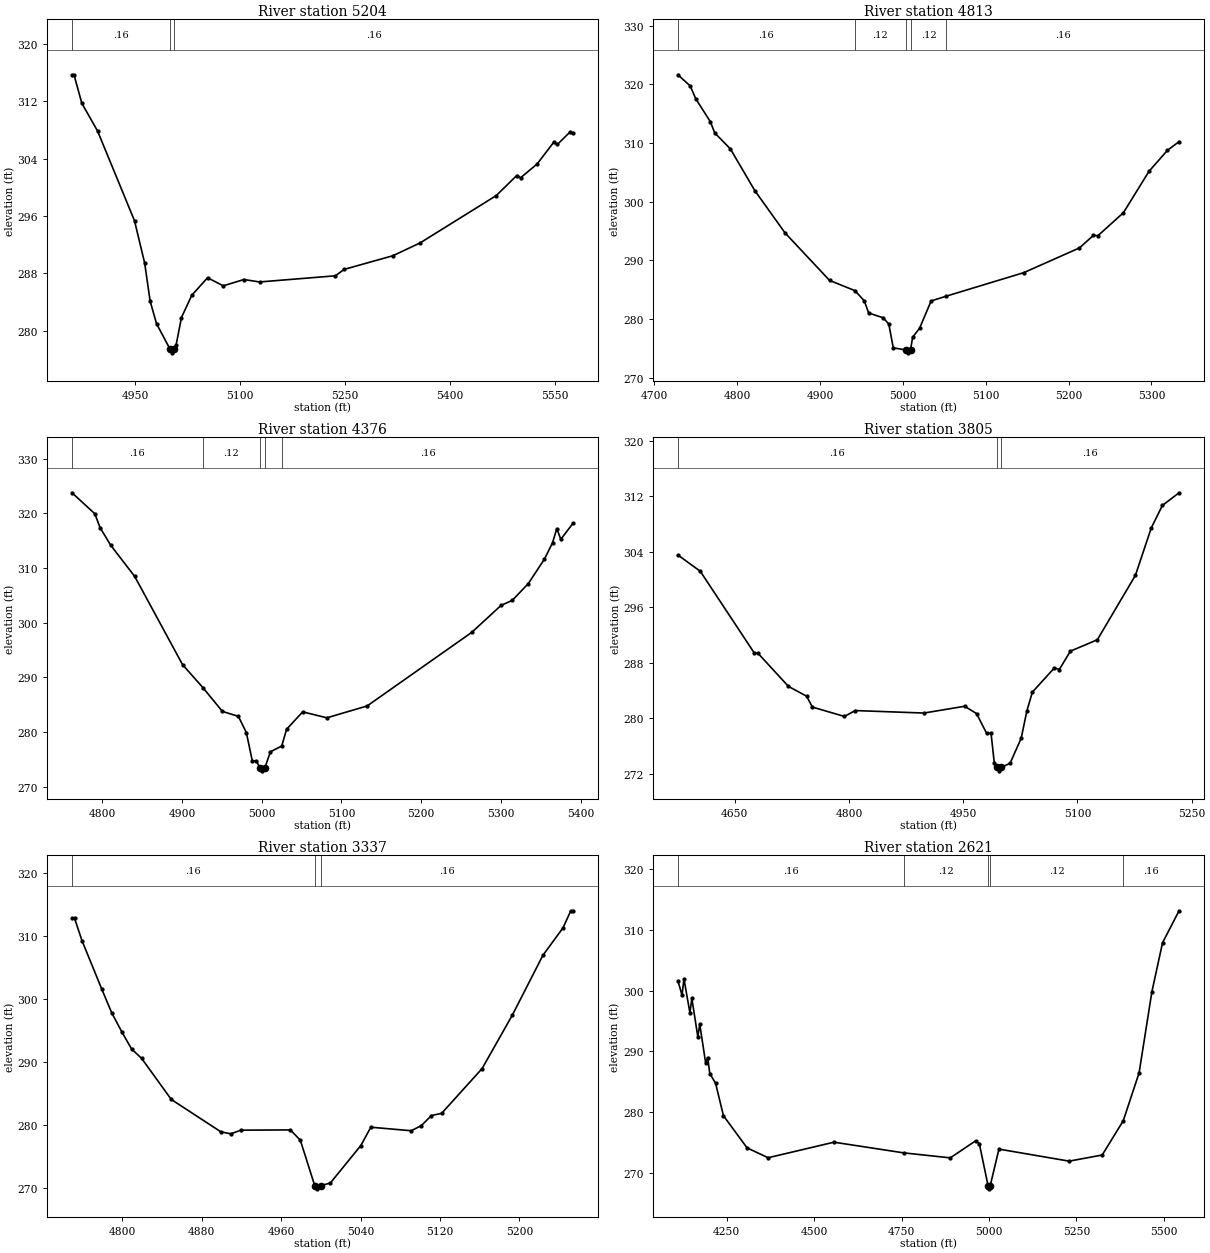
Type RM Length L Ch R = 1 ,5204    ,391,391,391
BEGIN DESCRIPTION:
BEE BRANCH EAST 9.0
END DESCRIPTION:
XS GIS Cut Line= 3
      3569392.11     10347391.64      3569674.99     10347251.76
      3570043.48     10347096.06
#Sta/Elev= 30
    4860  315.72  4862.8  315.72    4874  311.74  4896.4  307.88  4949.2  295.35
  4963.7  289.44  4971.5  284.14  4980.6  280.99    5000  277.42  5002.8  276.92
    5006  277.42  5008.6  278.01  5016.2  281.84    5031  284.96  5053.5   287.4
  5075.9  286.27  5105.4  287.15  5127.7  286.81  5236.1  287.67  5248.4  288.56
  5318.1  290.47    5357  292.26  5465.6  298.86  5494.9  301.66  5500.3  301.34
    5524  303.27  5547.7   306.3  5553.1  306.01  5571.4  307.77  5575.6  307.62
#Mann= 3 ,-1 , 0
    4860     .16       0    5000     .07       0    5006     .16       0
Bank Sta=5000,5006
XS Rating Curve= 0 ,0
Exp/Cntr=0.3,0.1

Type RM Length L Ch R = 1 ,4813    ,437,437,437
BEGIN DESCRIPTION:
BEE BRANCH EAST 8.0
END DESCRIPTION:
XS GIS Cut Line= 3
      3569492.08     10347641.65      3569742.11     10347541.64
      3570042.11     10347391.64
#Sta/Elev= 30
  4728.6  321.63  4743.4  319.75  4750.2  317.55  4767.7  313.66  4773.1  311.73
  4791.9  309.02  4821.5  301.89  4857.9   294.7  4911.7   286.6  4942.3  284.86
  4953.5  283.13  4958.8  281.06  4976.3  280.24  4983.1  279.18  4988.5  275.12
  5003.3  274.77    5006  274.27  5009.3  274.77  5011.9  276.94  5020.2  278.45
  5034.2  283.11  5052.6  283.93    5146  287.93  5213.1  292.14  5229.9  294.27
  5235.5  294.23  5266.2  298.14    5297  305.18  5319.3  308.76  5333.3  310.24
#Mann= 5 ,-1 , 0
  4728.6     .16       0  4942.3     .12       0  5003.3     .07       0
  5009.3     .12       0  5052.6     .16       0
Bank Sta=5003.3,5009.3
XS Rating Curve= 0 ,0
Exp/Cntr=0.3,0.1

Type RM Length L Ch R = 1 ,4376    ,571,571,571
BEGIN DESCRIPTION:
BEE BRANCH EAST 7.0
END DESCRIPTION:
XS GIS Cut Line= 3
      3569513.55     10347897.59      3569742.11     10347891.64
      3570137.86     10347949.58
#Sta/Elev= 30
  4762.2  323.79  4790.8  319.94  4797.3  317.42  4810.8  314.16  4840.8  308.47
  4900.8  292.32  4926.2  288.13  4950.8  283.75  4970.8  282.85  4980.8  279.88
  4988.3  274.69  4993.4  274.69  4997.9  273.37  5000.7  272.87  5003.9  273.37
    5011  276.35  5025.2  277.42  5031.3  280.49  5051.5  283.67  5081.8  282.58
  5132.3  284.75  5263.7  298.25  5300.3  303.17  5314.2  304.07  5334.5  307.17
  5354.7  311.65  5364.8  314.63  5370.2  317.23  5375.2  315.27  5390.8  318.26
#Mann= 5 ,-1 , 0
  4762.2     .16       0  4926.2     .12       0  4997.9     .07       0
  5003.9     .12       0  5025.2     .16       0
Bank Sta=4997.9,5003.9
XS Rating Curve= 0 ,0
Exp/Cntr=0.3,0.1

Type RM Length L Ch R = 1 ,3805    ,468,468,468
BEGIN DESCRIPTION:
BEE BRANCH EAST 6.0
END DESCRIPTION:
XS GIS Cut Line= 3
      3569404.13     10348418.44      3569792.11     10348291.64
      3569992.13     10348141.63
#Sta/Elev= 30
  4575.2  303.55  4604.6  301.21  4675.3  289.45  4680.5  289.36  4720.4  284.59
  4744.3  283.17  4751.9   281.6    4794  280.25  4808.1   281.1  4898.4  280.74
  4951.8  281.72  4967.4  280.67  4980.7  277.81  4986.5  277.81  4990.7  273.58
  4993.9   272.9  4996.7   272.4  4999.9   272.9  5011.5  273.49  5026.1  277.11
  5033.4  280.97  5040.7  283.75  5069.8  287.27  5076.1  287.02  5090.7  289.67
  5126.1  291.32  5176.1  300.62  5196.9  307.45  5211.5   310.7  5233.4  312.53
#Mann= 3 ,-1 , 0
  4575.2     .16       0  4993.9     .07       0  4999.9     .16       0
Bank Sta=4993.9,4999.9
XS Rating Curve= 0 ,0
Exp/Cntr=0.3,0.1

Type RM Length L Ch R = 1 ,3337    ,716,716,716
BEGIN DESCRIPTION:
BEE BRANCH EAST 5.0
END DESCRIPTION:
XS GIS Cut Line= 3
      3569542.14     10348691.64      3569792.11     10348691.64
      3570042.09     10348641.65
#Sta/Elev= 30
  4749.4  312.85  4751.9  312.85  4759.4  309.29  4779.4  301.55  4789.4  297.79
  4799.4  294.82  4809.4  292.04  4819.4  290.58  4849.4  284.02  4899.4  278.87
  4909.4  278.56  4919.4  279.14  4969.4  279.18  4979.4  277.53  4993.9  270.31
  4996.6  269.81  4999.9  270.31  5009.6  270.74  5040.2  276.67  5050.4  279.61
  5091.1  279.05  5101.3  279.87  5111.5  281.47  5121.7  281.81  5162.5  288.94
  5193.1  297.48  5223.7  306.94  5244.1  311.34  5251.8  314.03  5254.3  314.03
#Mann= 3 ,-1 , 0
  4749.4     .16       0  4993.9     .07       0  4999.9     .16       0
Bank Sta=4993.9,4999.9
XS Rating Curve= 0 ,0
Exp/Cntr=0.3,0.1

Type RM Length L Ch R = 1 ,2621    ,1483,1483,1483
BEGIN DESCRIPTION:
BEE BRANCH EAST 1.0
END DESCRIPTION:
XS GIS Cut Line= 4
      3569430.19     10348819.45      3569685.41     10349345.51
      3570164.58     10349100.72      3570216.38     10348795.06
#Sta/Elev= 30
  4110.6  301.64  4122.5  299.27  4128.1  301.93  4145.1  296.35  4150.6  298.72
  4167.7  292.41  4173.2  294.46  4190.2  288.05  4195.8  288.98    4202  286.33
  4218.4  284.77  4240.9  279.41  4308.6  274.11  4368.7  272.49  4556.9  275.05
  4756.5  273.29  4889.4  272.47  4961.7  275.27  4972.3  274.83  4997.5  267.87
  5000.2  267.37  5003.5  267.87  5028.5  273.91  5229.2  271.93  5323.7  272.94
  5383.8  278.57  5429.1  286.45  5465.7  299.81  5496.2  307.89  5543.4  313.15
#Mann= 5 ,-1 , 0
  4110.6     .16       0  4756.5     .12       0  4997.5     .07       0
  5003.5     .12       0  5383.8     .16       0
Bank Sta=4997.5,5003.5
XS Rating Curve= 0 ,0
Exp/Cntr=0.3,0.1

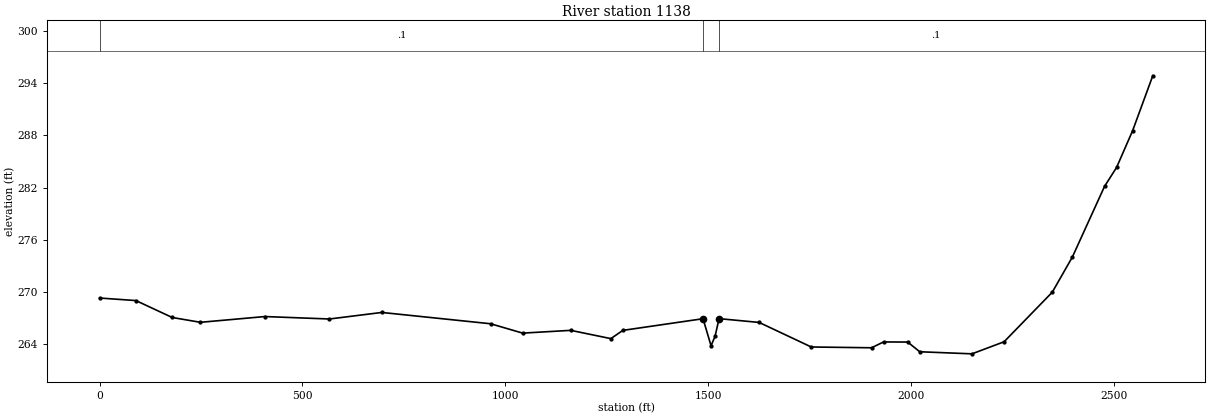
Type RM Length L Ch R = 1 ,1138    ,0,0,0
XS GIS Cut Line= 4
     3569621.316    10349883.677     3570574.441    10349920.135
     3571147.358    10349352.427     3570965.066    10348534.719
#Sta/Elev= 30
       0269.323989.41955269.0311178.8391267.0883248.3876266.5345407.3557267.1951
566.3238266.9145695.4854267.6664963.6346266.36791042.681265.29121161.251265.6096
1260.059264.65911289.701265.60591487.318266.94641507.079263.8371 1516.96264.9238
1526.841266.95561625.649266.51921754.099 263.6981902.644263.60751932.353264.2782
1991.771264.2635 2021.48263.14982150.219262.91062229.443264.29942348.279269.9997
2397.794274.04512477.018282.15282506.727284.33232546.339288.56652595.854294.8618
#Mann= 3 , 0 , 0
       0      .1       01487.318     .05       01526.841      .1       0
Bank Sta=1487.318,1526.841
XS Rating Curve= 0 ,0
Exp/Cntr=0.3,0.1

Chan Stop Cuts=-1
Use User Specified Reach Order=0
Composite Channel Slope=5