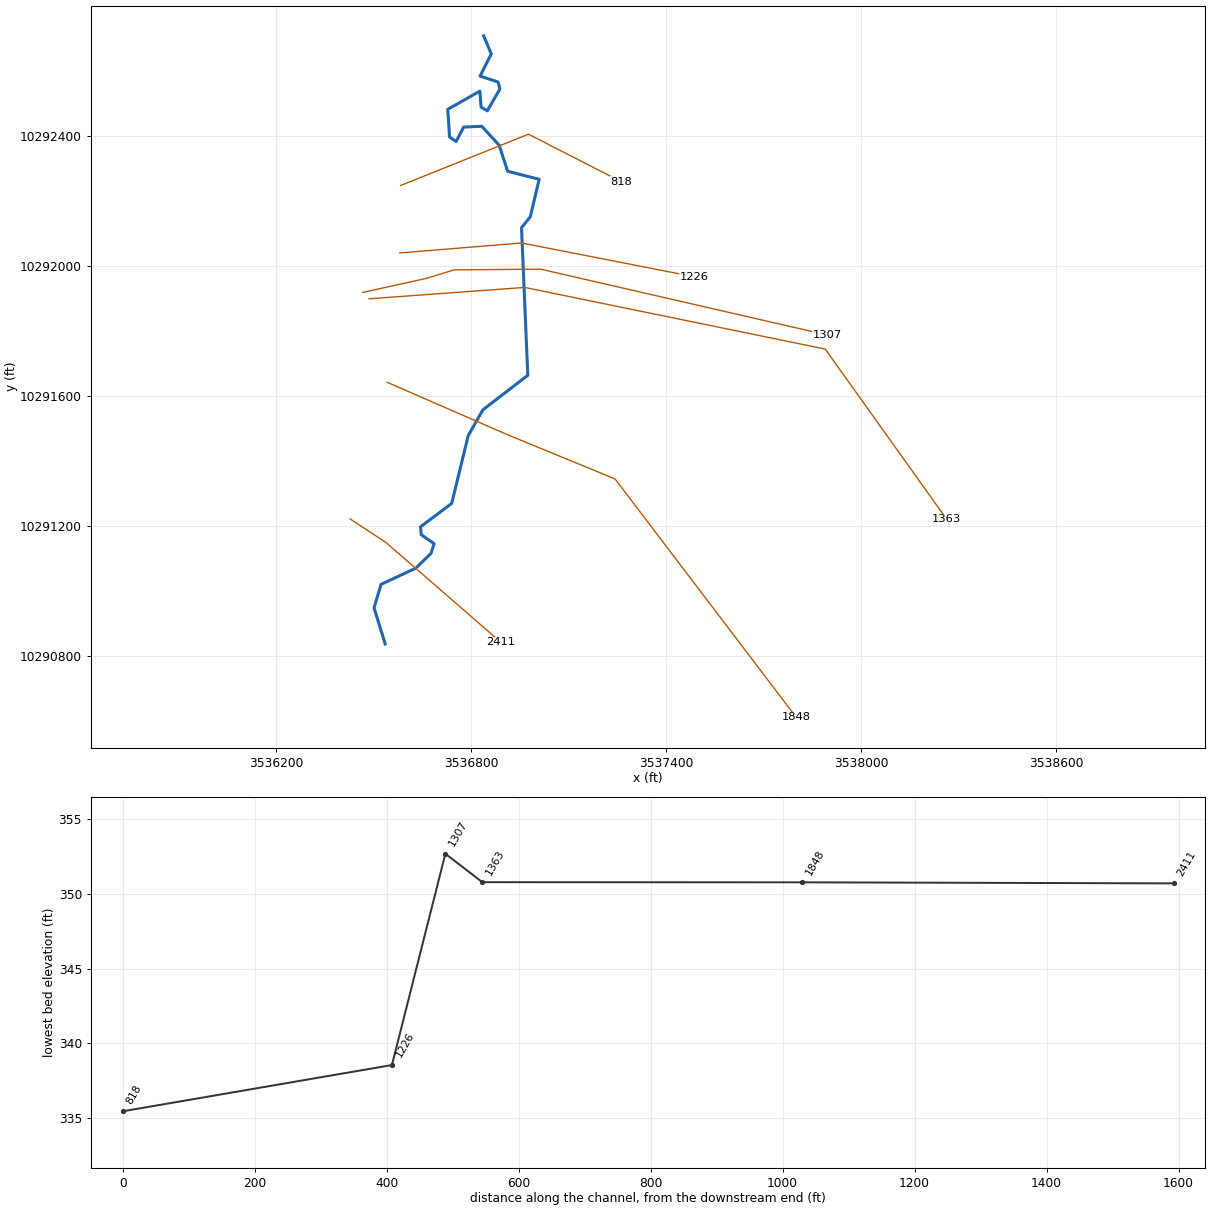
--- BEE CREEK NORTH TRIB 11.prj (project) ---

Proj Title=BEE CREEK NORTH TRIB 11 Base Level Engineering
Current Plan=p01
Default Exp/Contr=0.3,0.1
English Units
Geom File=g01
Flow File=f01
Plan File=p01
Y Axis Title=Elevation
X Axis Title(PF)=Main Channel Distance
X Axis Title(XS)=Station
BEGIN DESCRIPTION:
BEE CREEK NORTH TRIB 11
END DESCRIPTION:
DSS Export Rating Curves= 0
DSS Export Rating Curve Sorted= 0
DSS Export Volume Flow Curves= 0
DXF OffsetX= 0
DXF OffsetY= 0
DXF ScaleX= 1
DXF ScaleY= 10

--- BEE CREEK NORTH TRIB 11.p01 (plan) ---

Plan Title=Multiple Run
Short Identifier=Multiple
Geom File=g01
Flow File=f01
Subcritical Flow
K Sum by GR= 0
Std Step Tol= 0.01
Critical Tol= 0.01
Num of Std Step Trials= 20
Max Error Tol= 0.3
Flow Tol Ratio= 0.001
Split Flow NTrial= 30
Split Flow Tol= 0.02
Split Flow Ratio= 0.02
Log Output Level= 0
Friction Slope Method= 1
Unsteady Friction Slope Method= 2
Unsteady Bridges Friction Slope Method= 1
Parabolic Critical Depth
Global Vel Dist=  1 , 1 , 1
Global Log Level= 0
CheckData=True
Encroach Param= -1, 0, 0, 0
BEGIN DESCRIPTION:
Multiple Run
END DESCRIPTION:

--- BEE CREEK NORTH TRIB 11.f01 (steady flow) ---

Flow Title=Multiple
Number of Profiles=7
Profile Names=10-year,25-year,50-year,1pct_min,100-year,1pct_plu,500-year
River Rch & RM= BEE CREEK NORTH ,Reach-1,2411
     333     437     520     455     616     832     862
Boundary for River Rch & Prof#=BEE CREEK NORTH ,Reach-1,1
Up Type=0
Dn Type=3
Dn Slope=0.005
Boundary for River Rch & Prof#=BEE CREEK NORTH ,Reach-1,2
Up Type=0
Dn Type=3
Dn Slope=0.005
Boundary for River Rch & Prof#=BEE CREEK NORTH ,Reach-1,3
Up Type=0
Dn Type=3
Dn Slope=0.005
Boundary for River Rch & Prof#=BEE CREEK NORTH ,Reach-1,4
Up Type=0
Dn Type=3
Dn Slope=0.005
Boundary for River Rch & Prof#=BEE CREEK NORTH ,Reach-1,5
Up Type=0
Dn Type=3
Dn Slope=0.005
Boundary for River Rch & Prof#=BEE CREEK NORTH ,Reach-1,6
Up Type=0
Dn Type=3
Dn Slope=0.005
Boundary for River Rch & Prof#=BEE CREEK NORTH ,Reach-1,7
Up Type=0
Dn Type=3
Dn Slope=0.005

--- BEE CREEK NORTH TRIB 11.g01 (geometry) ---

Geom Title=Existing Conditions

River Reach=BEE CREEK NORTH ,Reach-1
Reach XY= 30
      3536535.68     10290837.12      3536501.47     10290947.98
      3536523.00     10291020.20      3536629.94     10291070.20
      3536676.47     10291115.34      3536686.19     10291145.20
      3536646.61     10291172.98      3536644.53     10291197.29
      3536740.36     10291269.51      3536791.05     10291477.84
      3536836.19     10291557.01      3536974.24     10291663.20
      3536955.00     10292117.18      3536982.08     10292151.04
      3537009.17     10292266.14      3536912.29     10292290.62
      3536886.25     10292370.83      3536832.60     10292429.16
      3536776.87     10292426.56      3536753.96     10292382.29
      3536733.65     10292396.35      3536728.11     10292481.18
      3536826.83     10292537.07      3536830.60     10292488.09
      3536849.76     10292476.68      3536888.33     10292543.33
      3536883.08     10292565.10      3536827.57     10292583.39
      3536861.92     10292651.59      3536838.60     10292707.07

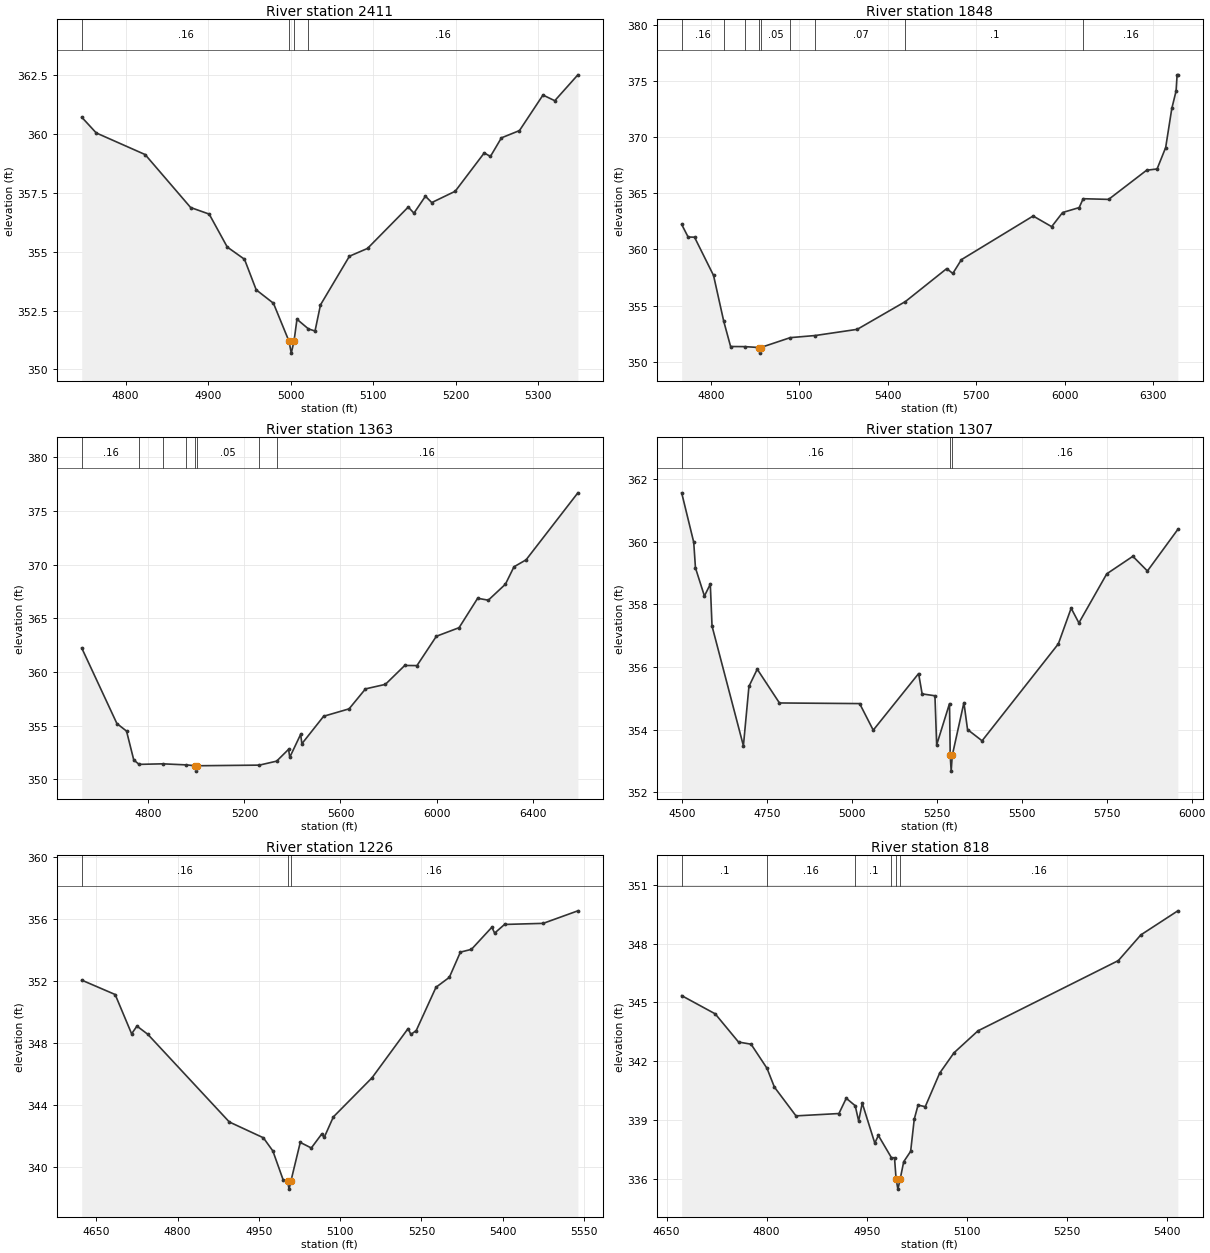
Type RM Length L Ch R = 1,2411,563,563,563
BEGIN DESCRIPTION:
BEE CREEK NORTH TRIB 11 4.0
END DESCRIPTION:
XS GIS Cut Line= 3
      3536427.42     10291221.92      3536538.15     10291148.89
      3536892.14     10290841.61
#Sta/Elev= 30
  4746.8  360.72  4764.4  360.05  4823.7  359.13  4878.8  356.88  4901.3  356.60
  4923.2  355.20  4944.1  354.68  4958.3  353.38  4979.2  352.81  4998.1  351.19
  5000.8  350.69  5004.1  351.19  5007.7  352.13  5021.6  351.72  5029.6  351.63
  5036.2  352.74  5071.3  354.81  5093.2  355.14  5142.6  356.90  5149.5  356.64
  5163.4  357.36  5171.1  357.09  5199.5  357.57  5234.7  359.20  5242.2  359.05
  5255.5  359.84  5277.4  360.15  5305.9  361.66  5320.2  361.42  5348.2  362.52
#Mann=4,-1,0
  4746.8    0.16       0  4998.1    0.07       0  5004.1    0.16       0
  5021.6    0.16       0
Bank Sta=4998.1,5004.1
Exp/Cntr=0.3,0.1

Type RM Length L Ch R = 1,1848,485,485,485
BEGIN DESCRIPTION:
BEE CREEK NORTH TRIB 11 3.0
END DESCRIPTION:
XS GIS Cut Line= 4
      3536542.12     10291641.64      3536910.43     10291481.11
      3537242.65     10291344.45      3537799.99     10290611.11
#Sta/Elev= 30
  4700.9  362.23  4722.7  361.11  4744.5  361.09  4809.0  357.68  4843.7  353.58
  4866.8  351.35  4915.0  351.34  4962.9  351.26  4965.7  350.76  4968.9  351.26
  5069.1  352.14  5154.1  352.33  5296.1  352.88  5459.6  355.36  5599.4  358.29
  5620.2  357.86  5649.3  359.09  5892.5  362.98  5955.3  362.03  5992.4  363.29
  6048.6  363.73  6062.1  364.52  6148.4  364.46  6277.3  367.06  6312.7  367.17
  6341.8  369.08  6362.6  372.56  6377.1  374.12  6380.6  375.56  6383.0  375.56
#Mann=9,-1,0
  4700.9    0.16       0  4843.7    0.07       0  4915.0    0.05       0
  4962.9   0.033       0  4968.9    0.05       0  5069.1    0.16       0
  5154.1    0.07       0  5459.6     0.1       0  6062.1    0.16       0
Bank Sta=4962.9,4968.9
Exp/Cntr=0.3,0.1

Type RM Length L Ch R = 1,1363,56,56,56
BEGIN DESCRIPTION:
BEE CREEK NORTH TRIB 11 2.2
END DESCRIPTION:
XS GIS Cut Line= 4
      3536485.97     10291898.52      3536964.62     10291933.49
      3537888.99     10291743.89      3538262.26     10291220.88
#Sta/Elev= 30
  4522.5  362.24  4669.0  355.20  4709.1  354.50  4739.2  351.81  4761.3  351.40
  4860.0  351.45  4958.8  351.35  4995.7  351.27  4998.4  350.77  5001.7  351.27
  5262.4  351.33  5334.2  351.70  5383.8  352.80  5388.9  352.06  5434.2  354.20
  5439.3  353.32  5529.9  355.88  5635.8  356.57  5704.2  358.43  5787.0  358.85
  5867.6  360.61  5918.6  360.60  5999.3  363.33  6093.9  364.13  6171.3  366.87
  6215.6  366.69  6286.9  368.18  6322.5  369.80  6372.9  370.45  6588.6  376.69
#Mann=8,-1,0
  4522.5    0.16       0  4761.3    0.05       0  4860.0    0.07       0
  4958.8    0.05       0  4995.7   0.033       0  5001.7    0.05       0
  5262.4    0.07       0  5334.2    0.16       0
Bank Sta=4995.7,5001.7
Exp/Cntr=0.3,0.1

Type RM Length L Ch R = 1,1307,81,81,81
BEGIN DESCRIPTION:
BEE CREEK NORTH TRIB 11 2.1
END DESCRIPTION:
XS GIS Cut Line= 5
      3536466.67     10291918.05      3536663.06     10291961.46
      3536747.70     10291987.50      3537013.54     10291989.67
      3537896.03     10291786.98
#Sta/Elev= 30
  4498.3  361.57  4533.8  359.99  4538.9  359.17  4565.3  358.27  4582.6  358.65
  4587.7  357.31  4680.1  353.48  4696.4  355.38  4720.8  355.93  4786.2  354.85
  5022.4  354.83  5062.4  353.98  5196.0  355.79  5206.4  355.14  5244.1  355.08
  5249.2  353.51  5287.0  354.83  5289.1  353.17  5291.9  352.67  5295.1  353.17
  5329.4  354.86  5340.1  354.00  5382.9  353.64  5607.5  356.74  5645.2  357.88
  5668.0  357.41  5750.1  358.98  5826.9  359.54  5869.8  359.07  5959.3  360.40
#Mann=3,-1,0
  4498.3    0.16       0  5289.1    0.07       0  5295.1    0.16       0
Bank Sta=5289.1,5295.1
Exp/Cntr=0.3,0.1

Type RM Length L Ch R = 1,1226,408,408,408
BEGIN DESCRIPTION:
BEE CREEK NORTH TRIB 11 2.0
END DESCRIPTION:
XS GIS Cut Line= 3
      3536580.57     10292039.52      3536955.20     10292070.15
      3537484.89     10291966.57
#Sta/Elev= 30
  4623.2  352.06  4684.9  351.13  4715.3  348.59  4725.1  349.09  4745.1  348.56
  4895.6  342.89  4958.4  341.87  4975.9  341.02  4995.0  339.14  5003.1  339.05
  5005.9  338.55  5009.1  339.05  5026.5  341.57  5046.9  341.21  5065.8  342.10
  5070.9  341.91  5087.6  343.22  5159.0  345.75  5225.5  348.93  5230.6  348.55
  5240.5  348.80  5277.0  351.60  5301.6  352.24  5322.0  353.87  5342.4  354.05
  5380.1  355.48  5385.2  355.10  5403.5  355.66  5474.8  355.73  5538.8  356.54
#Mann=3,-1,0
  4623.2    0.16       0  5003.1    0.07       0  5009.1    0.16       0
Bank Sta=5003.1,5009.1
Exp/Cntr=0.3,0.1

Type RM Length L Ch R = 1,818,0,0,0
BEGIN DESCRIPTION:
BEE CREEK NORTH TRIB 11 1.0
END DESCRIPTION:
XS GIS Cut Line= 3
      3536582.97     10292246.89      3536976.40     10292404.73
      3537261.53     10292258.63
#Sta/Elev= 30
  4672.5  345.34  4722.8  344.41  4757.8  342.97  4776.6  342.86  4800.5  341.63
  4811.6  340.67  4844.0  339.20  4908.4  339.32  4919.4  340.10  4932.8  339.72
  4938.0  338.94  4943.4  339.85  4962.2  337.81  4967.6  338.20  4987.1  337.07
  4991.8  337.06  4994.2  335.96  4996.9  335.46  5000.2  335.96  5005.6  336.86
  5016.0  337.39  5021.4  339.03  5027.1  339.75  5037.9  339.67  5059.5  341.38
  5081.0  342.42  5116.9  343.54  5327.6  347.13  5361.3  348.44  5416.8  349.67
#Mann=6,-1,0
  4672.5     0.1       0  4800.5    0.16       0  4932.8     0.1       0
  4987.1    0.16       0  4994.2    0.07       0  5000.2    0.16       0
Bank Sta=4994.2,5000.2
Exp/Cntr=0.3,0.1

Chan Stop Cuts=-1