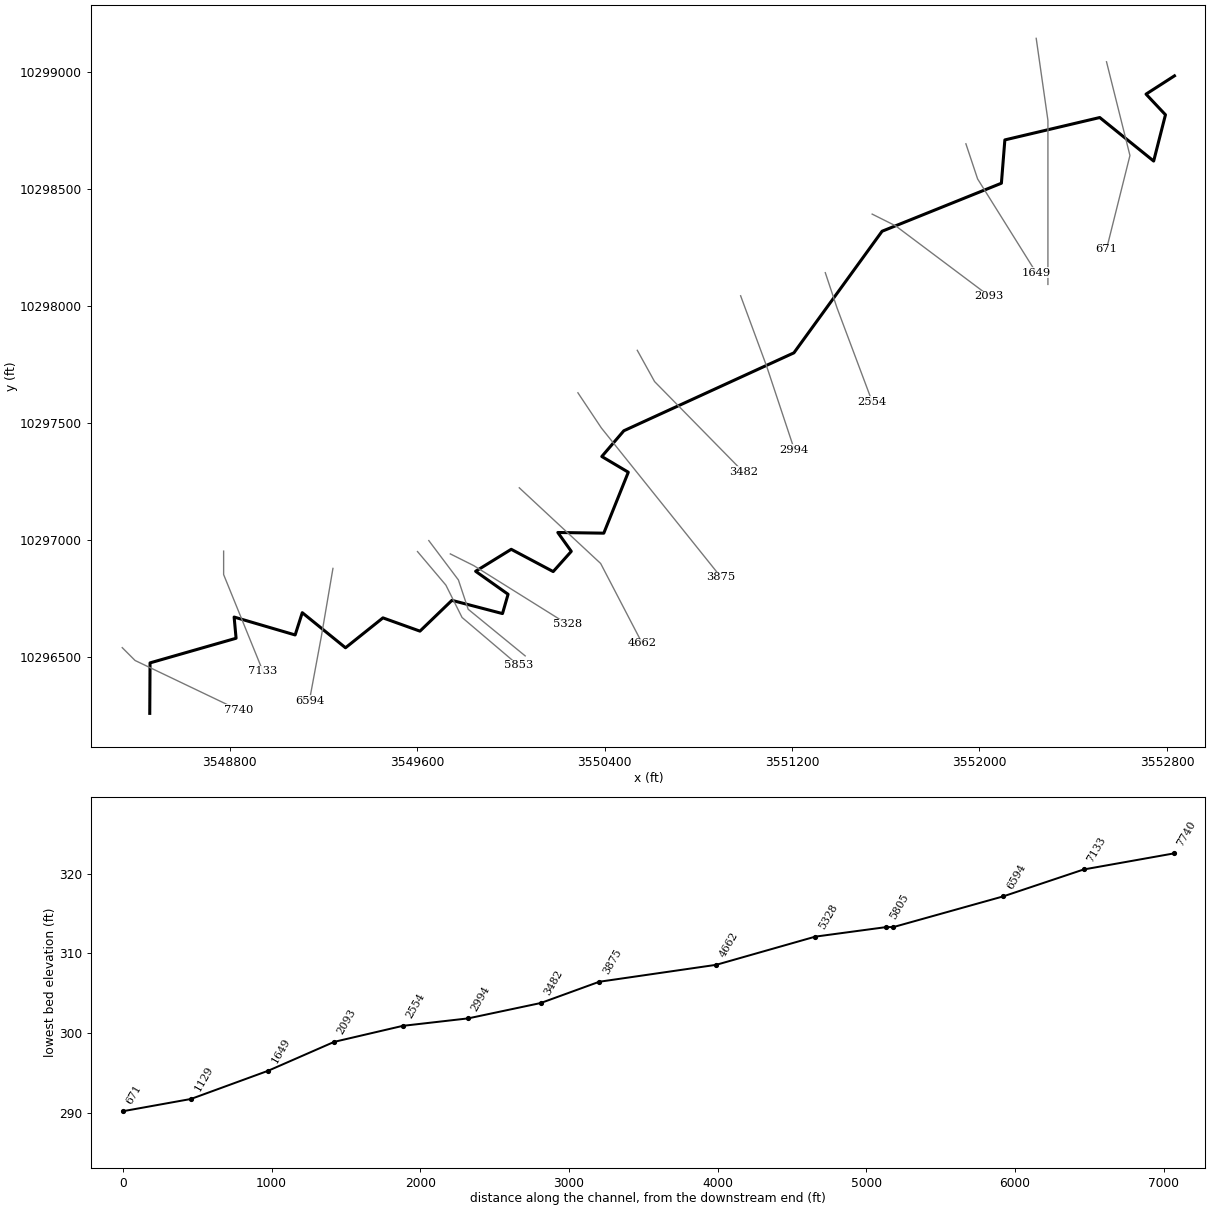
--- BEE CREEK NORTH TRIB 7.prj (project) ---

Proj Title=BEE CREEK NORTH TRIB 7 Base Level Engineering
Current Plan=p01
Default Exp/Contr=0.3,0.1
English Units
Geom File=g01
Flow File=f01
Plan File=p01
BEGIN DESCRIPTION:
BEE CREEK NORTH TRIB 7
END DESCRIPTION:

--- BEE CREEK NORTH TRIB 7.p01 (plan) ---

Plan Title=Multiple Run
Short Identifier=Multiple
Geom File=g01
Flow File=f01
Subcritical Flow
K Sum by GR= 0
Std Step Tol= 0.01
Critical Tol= 0.01
Num of Std Step Trials= 20
Max Error Tol= 0.3
Flow Tol Ratio= 0.001
Split Flow NTrial= 30
Split Flow Tol= 0.02
Split Flow Ratio= 0.02
Log Output Level= 0
Friction Slope Method= 1
Unsteady Friction Slope Method= 2
Unsteady Bridges Friction Slope Method= 1
Parabolic Critical Depth
Global Vel Dist=  1 , 1 , 1
Global Log Level= 0
CheckData=True
Encroach Param= -1, 0, 0, 0
BEGIN DESCRIPTION:
Multiple Run
END DESCRIPTION:

--- BEE CREEK NORTH TRIB 7.f01 (steady flow) ---

Flow Title=Multiple
Number of Profiles=7
Profile Names=10-year,25-year,50-year,1pct_min,100-year,1pct_plu,500-year
River Rch & RM= BEE CREEK NORTH ,Reach-1,7740
     640     870    1059     944    1277    1727    1861
Boundary for River Rch & Prof#=BEE CREEK NORTH ,Reach-1,1
Up Type=0
Dn Type=3
Dn Slope=0.005
Boundary for River Rch & Prof#=BEE CREEK NORTH ,Reach-1,2
Up Type=0
Dn Type=3
Dn Slope=0.005
Boundary for River Rch & Prof#=BEE CREEK NORTH ,Reach-1,3
Up Type=0
Dn Type=3
Dn Slope=0.005
Boundary for River Rch & Prof#=BEE CREEK NORTH ,Reach-1,4
Up Type=0
Dn Type=3
Dn Slope=0.005
Boundary for River Rch & Prof#=BEE CREEK NORTH ,Reach-1,5
Up Type=0
Dn Type=3
Dn Slope=0.005
Boundary for River Rch & Prof#=BEE CREEK NORTH ,Reach-1,6
Up Type=0
Dn Type=3
Dn Slope=0.005
Boundary for River Rch & Prof#=BEE CREEK NORTH ,Reach-1,7
Up Type=0
Dn Type=3
Dn Slope=0.005

--- BEE CREEK NORTH TRIB 7.g01 (geometry) ---

Geom Title=Existing Conditions

River Reach=BEE CREEK NORTH ,Reach-1
Reach XY= 30
      3548459.52     10296261.18      3548460.74     10296476.62
      3548827.89     10296581.75      3548819.53     10296672.19
      3549079.95     10296595.80      3549110.33     10296690.85
      3549294.79     10296541.11      3549454.52     10296668.72
      3549612.50     10296612.08      3549748.85     10296743.47
      3549964.71     10296687.02      3549988.51     10296769.42
      3549849.99     10296867.53      3550001.98     10296961.31
      3550181.04     10296866.25      3550258.24     10296952.53
      3550200.73     10297033.07      3550396.94     10297030.16
      3550501.51     10297290.23      3550388.45     10297357.29
      3550482.42     10297467.10      3551208.22     10297799.63
      3551584.47     10298318.52      3552093.59     10298523.38
      3552108.36     10298708.24      3552513.29     10298803.76
      3552743.33     10298618.00      3552793.68     10298815.48
      3552710.78     10298903.59      3552832.11     10298981.64

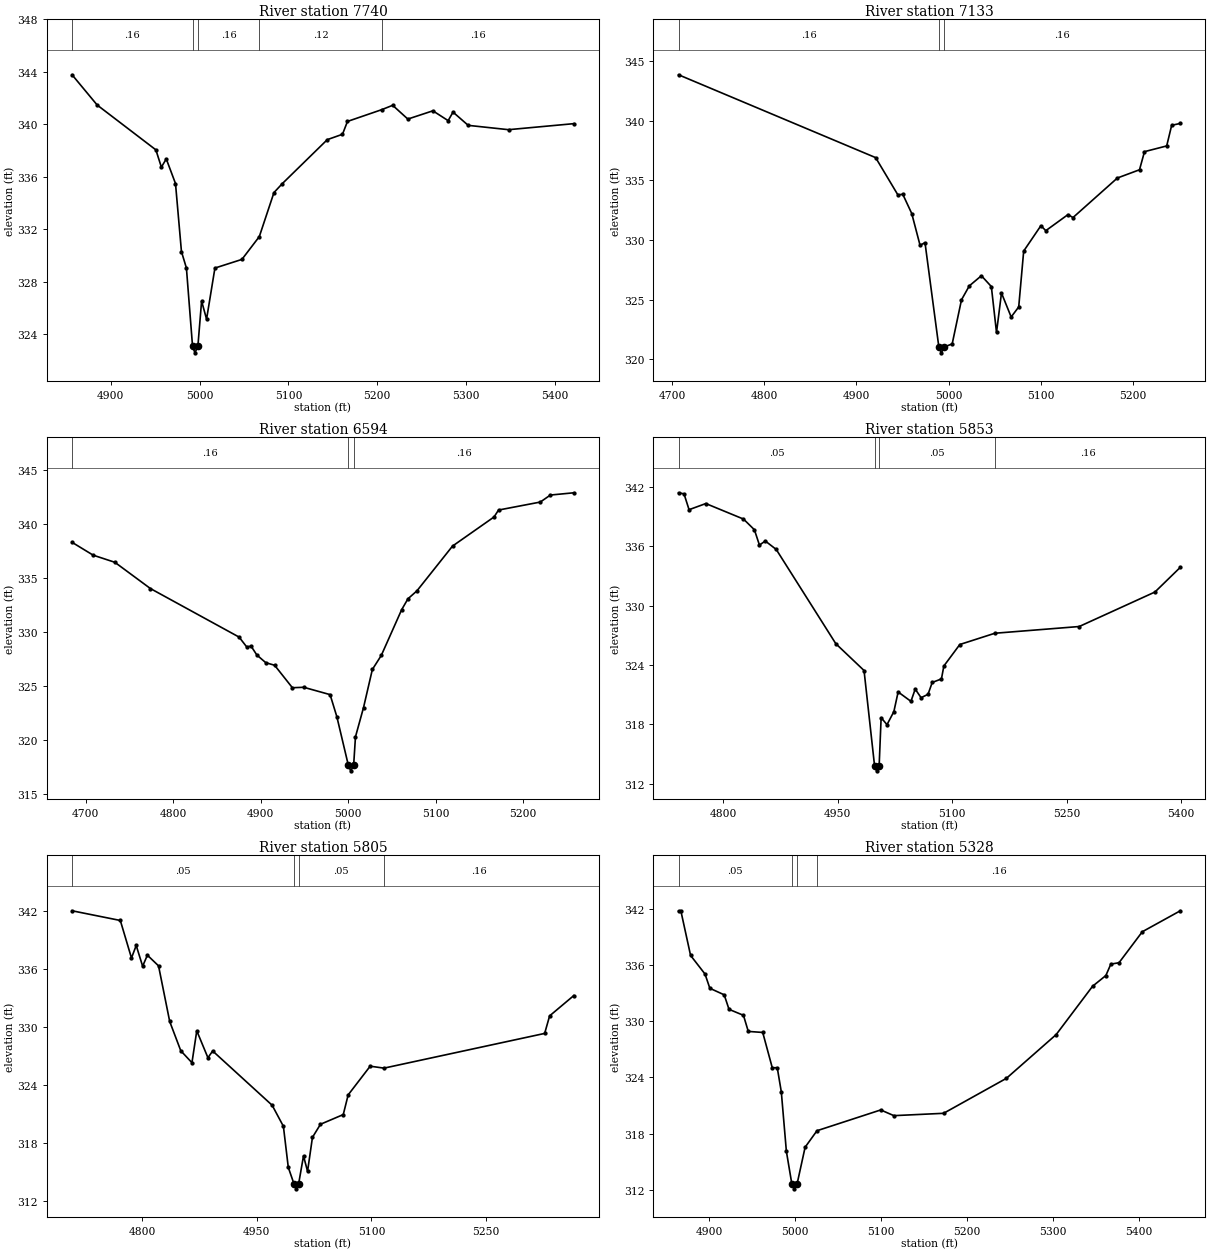
Type RM Length L Ch R = 1,7740,607,607,607
BEGIN DESCRIPTION:
BEE CREEK NORTH TRIB 7 13.0
END DESCRIPTION:
XS GIS Cut Line= 3
      3548342.09     10296541.66      3548396.84     10296486.91
      3548836.89     10296276.50
#Sta/Elev= 30
  4856.3  343.78  4884.6  341.47  4950.7  338.05  4956.9  336.73  4962.4  337.36
  4972.8  335.48  4979.5  330.29  4985.1  329.03  4992.0  323.06  4994.7  322.56
  4998.0  323.06  5002.2  326.51  5007.8  325.13  5017.2  329.03  5047.6  329.69
  5067.2  331.43  5083.7  334.79  5092.9  335.46  5143.8  338.83  5160.9  339.24
  5166.5  340.22  5205.2  341.12  5217.4  341.45  5234.5  340.40  5262.7  341.03
  5279.9  340.28  5285.4  340.93  5302.5  339.92  5347.9  339.59  5421.5  340.05
#Mann=5,-1,0
  4856.3    0.16       0  4992.0    0.07       0  4998.0    0.16       0
  5067.2    0.12       0  5205.2    0.16       0
Bank Sta=4992,4998
Exp/Cntr=0.3,0.1

Type RM Length L Ch R = 1,7133,539,539,539
BEGIN DESCRIPTION:
BEE CREEK NORTH TRIB 7 12.0
END DESCRIPTION:
XS GIS Cut Line= 3
      3548774.74     10296953.48      3548774.74     10296853.45
      3548942.12     10296441.60
#Sta/Elev= 30
  4706.9  343.87  4920.8  336.92  4944.9  333.80  4950.3  333.84  4960.0  332.23
  4969.0  329.57  4974.4  329.78  4989.4  321.04  4992.1  320.54  4995.4  321.04
  5003.9  321.29  5014.0  324.99  5022.5  326.16  5035.6  327.01  5046.4  326.10
  5052.0  322.25  5057.4  325.56  5067.9  323.55  5076.1  324.39  5081.5  329.08
  5100.2  331.21  5105.5  330.79  5129.6  332.14  5135.0  331.89  5183.2  335.21
  5207.2  335.90  5212.6  337.42  5236.7  337.90  5242.1  339.63  5251.5  339.79
#Mann=3,-1,0
  4706.9    0.16       0  4989.4    0.07       0  4995.4    0.16       0
Bank Sta=4989.4,4995.4
Exp/Cntr=0.3,0.1

Type RM Length L Ch R = 1,6594,741,741,741
BEGIN DESCRIPTION:
BEE CREEK NORTH TRIB 7 11.0
END DESCRIPTION:
XS GIS Cut Line= 3
      3549241.23     10296879.87      3549192.11     10296591.64
      3549140.79     10296315.25
#Sta/Elev= 30
  4684.3  338.34  4708.4  337.15  4733.2  336.49  4773.8  334.06  4875.2  329.56
  4883.9  328.65  4888.9  328.72  4895.5  327.90  4905.7  327.19  4915.8  326.95
  4936.1  324.87  4949.1  324.91  4979.2  324.23  4986.9  322.19  5000.1  317.67
  5002.8  317.17  5006.1  317.67  5008.2  320.32  5017.4  323.03  5027.5  326.56
  5037.7  327.86  5061.0  332.10  5068.2  333.11  5078.4  333.84  5119.1  337.99
  5166.6  340.69  5171.7  341.33  5219.4  342.07  5231.0  342.72  5257.8  342.93
#Mann=3,-1,0
  4684.3    0.16       0  5000.1    0.07       0  5006.1    0.16       0
Bank Sta=5000.1,5006.1
Exp/Cntr=0.3,0.1

Type RM Length L Ch R = 1,5853,48,48,48
BEGIN DESCRIPTION:
Mapping XS 270448f5
END DESCRIPTION:
XS GIS Cut Line= 4
      3549602.04     10296951.65      3549723.14     10296808.41
      3549792.15     10296670.39      3550033.15     10296465.67
#Sta/Elev= 30
  4741.1  341.43  4748.3  341.32  4754.9  339.72  4776.9  340.34  4826.3  338.77
  4840.6  337.69  4847.2  336.14  4854.9  336.55  4869.2  335.70  4947.4  326.16
  4984.4  323.45  4998.2  313.80  5000.9  313.30  5004.2  313.80  5006.8  318.68
  5014.5  317.97  5023.5  319.29  5029.1  321.28  5045.9  320.33  5051.5  321.57
  5059.2  320.70  5068.3  321.04  5073.8  322.24  5085.9  322.60  5089.1  323.91
  5110.0  326.08  5156.0  327.22  5266.6  327.90  5365.9  331.39  5399.2  333.89
#Mann=4,-1,0
  4741.1    0.05       0  4998.2    0.03       0  5004.2    0.05       0
  5156.0    0.16       0
Bank Sta=4998.2,5004.2
Exp/Cntr=0.3,0.1

Type RM Length L Ch R = 1,5805,477,477,477
BEGIN DESCRIPTION:
Mapping XS f37c4832
END DESCRIPTION:
XS GIS Cut Line= 4
      3549650.24     10296998.50      3549776.53     10296830.54
      3549818.20     10296705.54      3550061.53     10296506.46
#Sta/Elev= 30
  4708.5  341.98  4771.6  340.98  4786.2  337.11  4792.4  338.40  4800.8  336.26
  4807.0  337.40  4821.6  336.30  4836.2  330.56  4850.7  327.54  4865.3  326.31
  4871.6  329.60  4886.2  326.82  4892.4  327.52  4970.2  321.92  4984.9  319.75
  4991.3  315.51  4998.8  313.80  5001.6  313.30  5004.8  313.80  5011.2  316.70
  5016.5  315.10  5022.9  318.61  5033.4  319.96  5063.2  320.96  5069.6  322.99
  5098.4  325.95  5116.5  325.75  5326.6  329.33  5333.1  331.14  5364.8  333.24
#Mann=4,-1,0
  4708.5    0.05       0  4998.8    0.03       0  5004.8    0.05       0
  5116.5    0.16       0
Bank Sta=4998.8,5004.8
Exp/Cntr=0.3,0.1

Type RM Length L Ch R = 1,5328,666,666,666
BEGIN DESCRIPTION:
BEE CREEK NORTH TRIB 7 10.0
END DESCRIPTION:
XS GIS Cut Line= 3
      3549742.08     10296941.65      3549842.11     10296891.64
      3550242.08     10296641.66
#Sta/Elev= 30
  4864.4  341.76  4867.2  341.76  4878.4  337.04  4895.2  335.05  4900.8  333.53
  4917.5  332.83  4923.1  331.28  4939.9  330.64  4945.5  328.92  4962.3  328.81
  4973.4  325.04  4979.2  325.04  4983.9  322.47  4989.8  316.11  4996.2  312.60
  4999.0  312.10  5002.2  312.60  5011.6  316.55  5025.4  318.31  5099.5  320.53
  5114.8  319.92  5172.6  320.17  5245.7  323.91  5303.5  328.58  5345.9  333.75
  5361.3  334.89  5367.1  336.11  5376.6  336.26  5403.7  339.57  5447.9  341.81
#Mann=4,-1,0
  4864.4    0.05       0  4996.2    0.03       0  5002.2    0.05       0
  5025.4    0.16       0
Bank Sta=4996.2,5002.2
Exp/Cntr=0.3,0.1

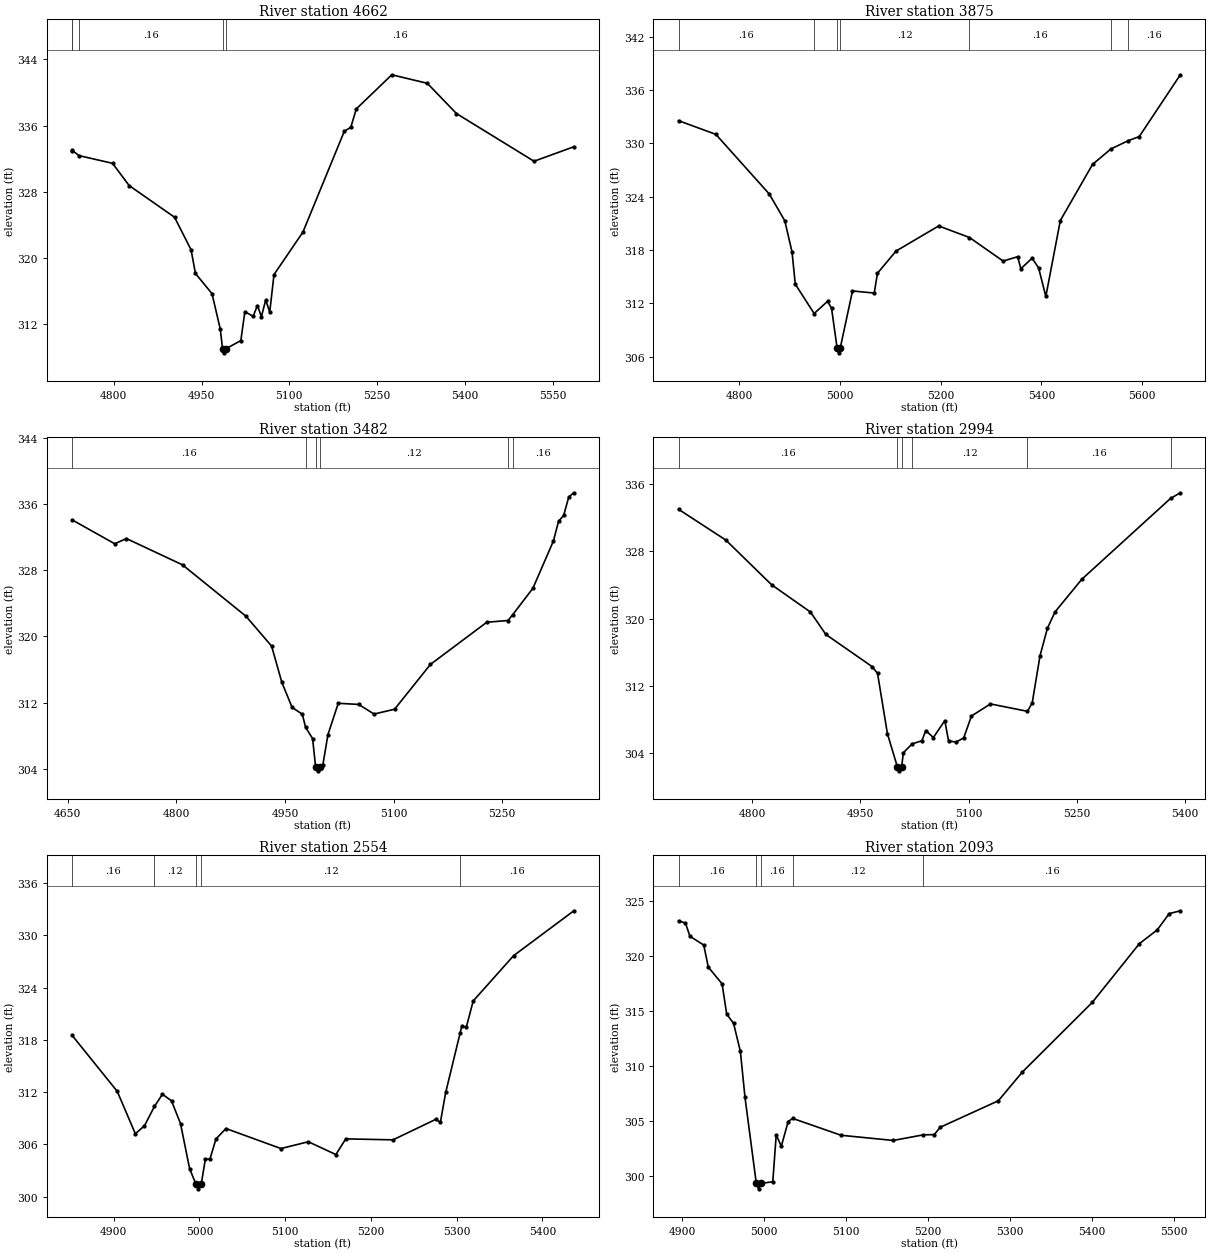
Type RM Length L Ch R = 1,4662,787,787,787
BEGIN DESCRIPTION:
BEE CREEK NORTH TRIB 7 9.0
END DESCRIPTION:
XS GIS Cut Line= 3
      3550036.38     10297223.66      3550383.60     10296900.75
      3550560.70     10296560.44
#Sta/Elev= 30
  4728.7  333.01  4729.4  332.97  4740.6  332.37  4797.9  331.44  4826.2  328.76
  4903.9  324.93  4932.2  320.99  4939.6  318.14  4967.9  315.71  4982.1  311.41
  4985.9  309.06  4988.6  308.56  4991.9  309.06  5017.2  310.04  5024.1  313.53
  5038.2  312.97  5045.6  314.27  5052.4  312.92  5059.7  314.95  5066.6  313.48
  5073.9  318.01  5123.3  323.13  5194.1  335.31  5205.2  335.79  5214.6  338.01
  5275.3  342.13  5336.0  341.10  5385.8  337.45  5518.4  331.69  5586.5  333.44
#Mann=5,-1,0
  4728.7    0.16       0  4729.4    0.05       0  4740.6    0.16       0
  4985.9    0.07       0  4991.9    0.16       0
Bank Sta=4985.9,4991.9
Exp/Cntr=0.3,0.1

Type RM Length L Ch R = 1,3875,393,393,393
BEGIN DESCRIPTION:
BEE CREEK NORTH TRIB 7 8.0
END DESCRIPTION:
XS GIS Cut Line= 3
      3550286.55     10297629.15      3550386.55     10297479.14
      3550897.29     10296841.96
#Sta/Elev= 30
  4679.1  332.54  4753.2  331.00  4859.4  324.29  4890.2  321.28  4904.6  317.77
  4911.0  314.16  4948.5  310.85  4975.1  312.22  4983.1  311.45  4994.2  306.93
  4996.9  306.43  5000.2  306.93  5024.7  313.39  5067.9  313.15  5074.3  315.38
  5111.1  317.87  5195.9  320.70  5257.1  319.40  5324.0  316.75  5352.8  317.24
  5359.2  315.89  5381.6  317.08  5394.5  315.97  5408.8  312.77  5437.6  321.31
  5501.6  327.62  5537.9  329.35  5572.1  330.28  5594.4  330.75  5676.0  337.70
#Mann=7,-1,0
  4679.1    0.16       0  4948.5    0.12       0  4994.2    0.07       0
  5000.2    0.12       0  5257.1    0.16       0  5537.9     0.1       0
  5572.1    0.16       0
Bank Sta=4994.2,5000.2
Exp/Cntr=0.3,0.1

Type RM Length L Ch R = 1,3482,488,488,488
BEGIN DESCRIPTION:
BEE CREEK NORTH TRIB 7 7.0
END DESCRIPTION:
XS GIS Cut Line= 3
      3550539.85     10297810.48      3550613.63     10297677.06
      3550992.08     10297291.67
#Sta/Elev= 30
  4656.2  334.08  4715.1  331.19  4731.2  331.82  4808.7  328.64  4896.3  322.43
  4931.6  318.83  4945.7  314.46  4959.9  311.42  4974.0  310.60  4978.5  309.02
  4988.2  307.66  4992.3  304.26  4995.1  303.76  4998.3  304.26  5002.3  304.45
  5009.4  308.14  5023.6  311.92  5051.9  311.78  5073.0  310.62  5101.3  311.20
  5150.9  316.62  5228.6  321.71  5257.9  321.92  5264.2  322.60  5292.3  325.82
  5320.6  331.53  5327.6  333.89  5334.8  334.63  5341.8  336.86  5348.8  337.35
#Mann=6,-1,0
  4656.2    0.16       0  4978.5    0.12       0  4992.3    0.07       0
  4998.3    0.12       0  5257.9     0.1       0  5264.2    0.16       0
Bank Sta=4992.3,4998.3
Exp/Cntr=0.3,0.1

Type RM Length L Ch R = 1,2994,440,440,440
BEGIN DESCRIPTION:
BEE CREEK NORTH TRIB 7 6.0
END DESCRIPTION:
XS GIS Cut Line= 3
      3550980.82     10298043.12      3551092.11     10297741.64
      3551209.98     10297386.87
#Sta/Elev= 30
  4698.1  333.03  4763.6  329.36  4827.0  324.03  4880.9  320.77  4902.2  318.10
  4966.2  314.27  4973.8  313.46  4987.5  306.26  5001.2  302.33  5004.0  301.83
  5007.2  302.33  5009.6  303.99  5021.6  305.04  5035.3  305.42  5040.6  306.64
  5051.1  305.80  5067.0  307.82  5072.2  305.40  5082.7  305.26  5093.2  305.76
  5103.9  308.37  5130.3  309.81  5181.5  308.93  5188.1  309.93  5198.9  315.56
  5209.1  318.82  5219.7  320.79  5256.9  324.69  5379.8  334.33  5393.3  335.00
#Mann=6,-1,0
  4698.1    0.16       0  5001.2    0.07       0  5007.2    0.16       0
  5021.6    0.12       0  5181.5    0.16       0  5379.8     0.1       0
Bank Sta=5001.2,5007.2
Exp/Cntr=0.3,0.1

Type RM Length L Ch R = 1,2554,461,461,461
BEGIN DESCRIPTION:
BEE CREEK NORTH TRIB 7 5.0
END DESCRIPTION:
XS GIS Cut Line= 3
      3551342.10     10298141.67      3551392.11     10297991.64
      3551542.09     10297591.68
#Sta/Elev= 30
  4851.4  318.53  4904.1  312.09  4925.2  307.22  4935.8  308.13  4947.5  310.36
  4956.8  311.76  4967.4  311.00  4977.9  308.38  4988.5  303.21  4996.0  301.39
  4998.8  300.89  5002.0  301.39  5006.9  304.31  5012.2  304.31  5019.3  306.63
  5030.9  307.82  5095.0  305.52  5127.0  306.30  5159.1  304.83  5170.6  306.63
  5225.8  306.52  5275.7  308.88  5281.0  308.53  5287.2  311.96  5304.1  318.82
  5305.9  319.55  5311.3  319.49  5319.3  322.48  5366.4  327.68  5436.7  332.84
#Mann=5,-1,0
  4851.4    0.16       0  4947.5    0.12       0  4996.0    0.07       0
  5002.0    0.12       0  5304.1    0.16       0
Bank Sta=4996,5002
Exp/Cntr=0.3,0.1

Type RM Length L Ch R = 1,2093,444,444,444
BEGIN DESCRIPTION:
BEE CREEK NORTH TRIB 7 4.0
END DESCRIPTION:
XS GIS Cut Line= 3
      3551542.13     10298391.63      3551642.11     10298341.64
      3552042.12     10298041.63
#Sta/Elev= 30
  4895.6  323.20  4904.0  323.00  4909.5  321.80  4926.3  321.00  4931.9  319.00
  4948.7  317.48  4954.3  314.74  4962.7  313.89  4971.0  311.35  4976.6  307.20
  4990.4  299.38  4993.2  298.88  4996.4  299.38  5010.5  299.52  5014.7  303.78
  5020.9  302.74  5029.3  304.99  5034.8  305.27  5093.8  303.74  5157.4  303.27
  5194.0  303.78  5207.4  303.80  5214.7  304.47  5285.5  306.87  5314.7  309.47
  5400.1  315.80  5457.4  321.12  5479.3  322.38  5493.8  323.85  5507.4  324.11
#Mann=5,-1,0
  4895.6    0.16       0  4990.4    0.07       0  4996.4    0.16       0
  5034.8    0.12       0  5194.0    0.16       0
Bank Sta=4990.4,4996.4
Exp/Cntr=0.3,0.1

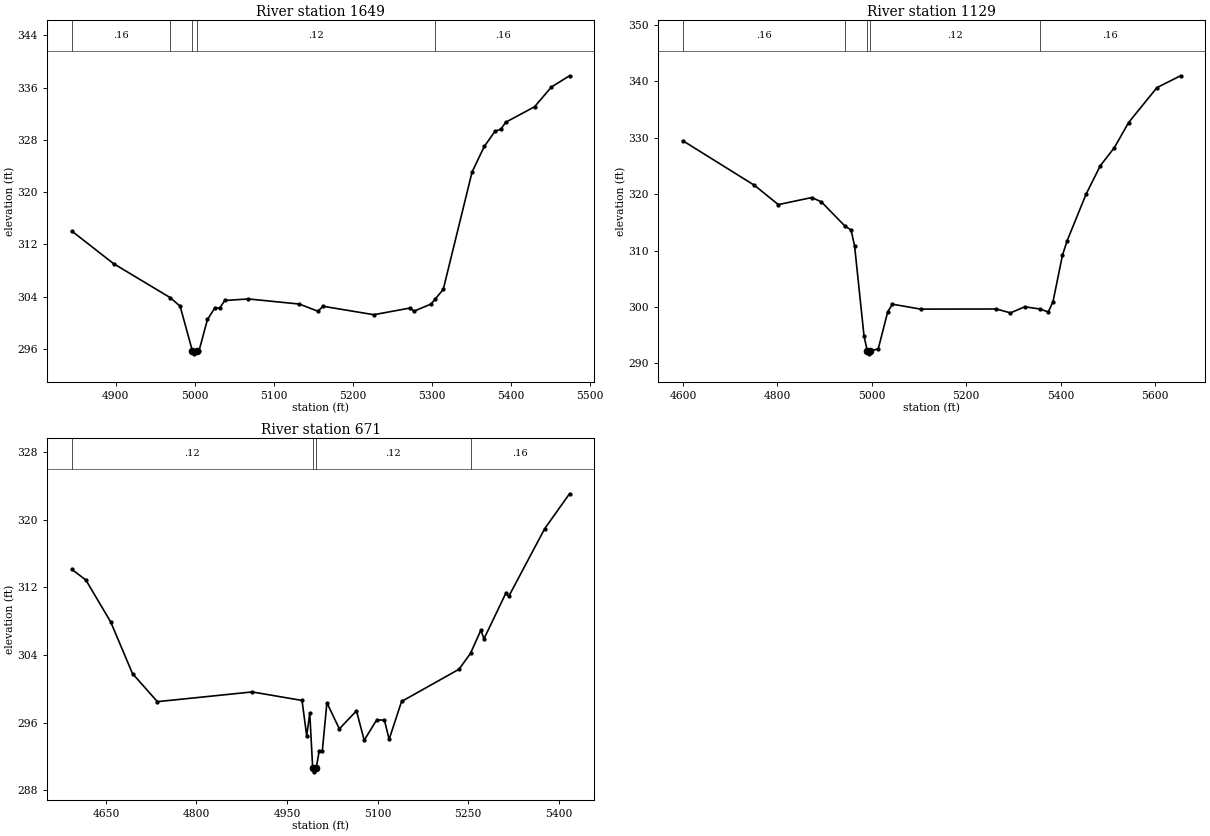
Type RM Length L Ch R = 1,1649,520,520,520
BEGIN DESCRIPTION:
BEE CREEK NORTH TRIB 7 3.0
END DESCRIPTION:
XS GIS Cut Line= 3
      3551942.12     10298691.61      3551992.11     10298541.64
      3552242.12     10298141.62
#Sta/Elev= 30
  4844.6  314.04  4897.3  309.06  4969.1  303.85  4981.6  302.54  4997.0  295.75
  4999.8  295.25  5003.0  295.75  5005.6  295.75  5016.2  300.51  5025.7  302.31
  5031.6  302.24  5038.1  303.42  5068.1  303.65  5132.4  302.87  5156.0  301.77
  5162.5  302.53  5226.7  301.24  5272.1  302.25  5278.0  301.80  5299.3  302.88
  5304.7  303.68  5314.6  305.11  5351.1  323.09  5366.5  326.99  5380.0  329.30
  5387.7  329.66  5393.6  330.69  5430.2  333.07  5451.4  336.08  5474.4  337.81
#Mann=5,-1,0
  4844.6    0.16       0  4969.1    0.12       0  4997.0    0.07       0
  5003.0    0.12       0  5304.7    0.16       0
Bank Sta=4997,5003
Exp/Cntr=0.3,0.1

Type RM Length L Ch R = 1,1129,458,458,458
BEGIN DESCRIPTION:
BEE CREEK NORTH TRIB 7 2.0
END DESCRIPTION:
XS GIS Cut Line= 3
      3552242.10     10299141.67      3552292.11     10298791.64
      3552292.11     10298091.62
#Sta/Elev= 30
  4600.0  329.48  4751.5  321.58  4802.1  318.16  4872.8  319.41  4893.0  318.66
  4943.4  314.33  4956.1  313.66  4963.6  310.78  4983.6  294.80  4990.6  292.20
  4993.3  291.70  4996.6  292.20  5013.6  292.58  5033.6  299.13  5043.6  300.50
  5103.6  299.63  5263.6  299.65  5293.6  298.96  5323.6  300.04  5355.9  299.65
  5373.6  299.12  5383.6  300.94  5403.6  309.18  5413.6  311.77  5453.6  320.00
  5483.6  325.04  5513.6  328.27  5543.6  332.70  5603.6  338.90  5653.6  341.00
#Mann=5,-1,0
  4600.0    0.16       0  4943.4    0.12       0  4990.6    0.07       0
  4996.6    0.12       0  5355.9    0.16       0
Bank Sta=4990.6,4996.6
Exp/Cntr=0.3,0.1

Type RM Length L Ch R = 1,671,0,0,0
BEGIN DESCRIPTION:
BEE CREEK NORTH TRIB 7 1.0
END DESCRIPTION:
XS GIS Cut Line= 3
      3552542.11     10299041.62      3552642.11     10298641.64
      3552542.10     10298241.64
#Sta/Elev= 30
  4593.5  314.13  4616.7  312.87  4657.9  307.90  4694.0  301.79  4735.2  298.47
  4892.4  299.62  4974.9  298.61  4982.6  294.43  4987.7  297.08  4992.5  290.66
  4995.2  290.16  4998.5  290.66  5003.2  292.58  5008.4  292.58  5016.1  298.34
  5036.7  295.25  5065.1  297.38  5077.9  293.90  5098.6  296.31  5111.4  296.28
  5119.2  294.01  5139.8  298.49  5235.1  302.31  5254.1  304.20  5271.2  306.93
  5276.4  305.91  5312.4  311.28  5317.6  310.96  5376.9  318.94  5418.1  323.08
#Mann=4,-1,0
  4593.5    0.12       0  4992.5    0.07       0  4998.5    0.12       0
  5254.1    0.16       0
Bank Sta=4992.5,4998.5
Exp/Cntr=0.3,0.1

Chan Stop Cuts=-1