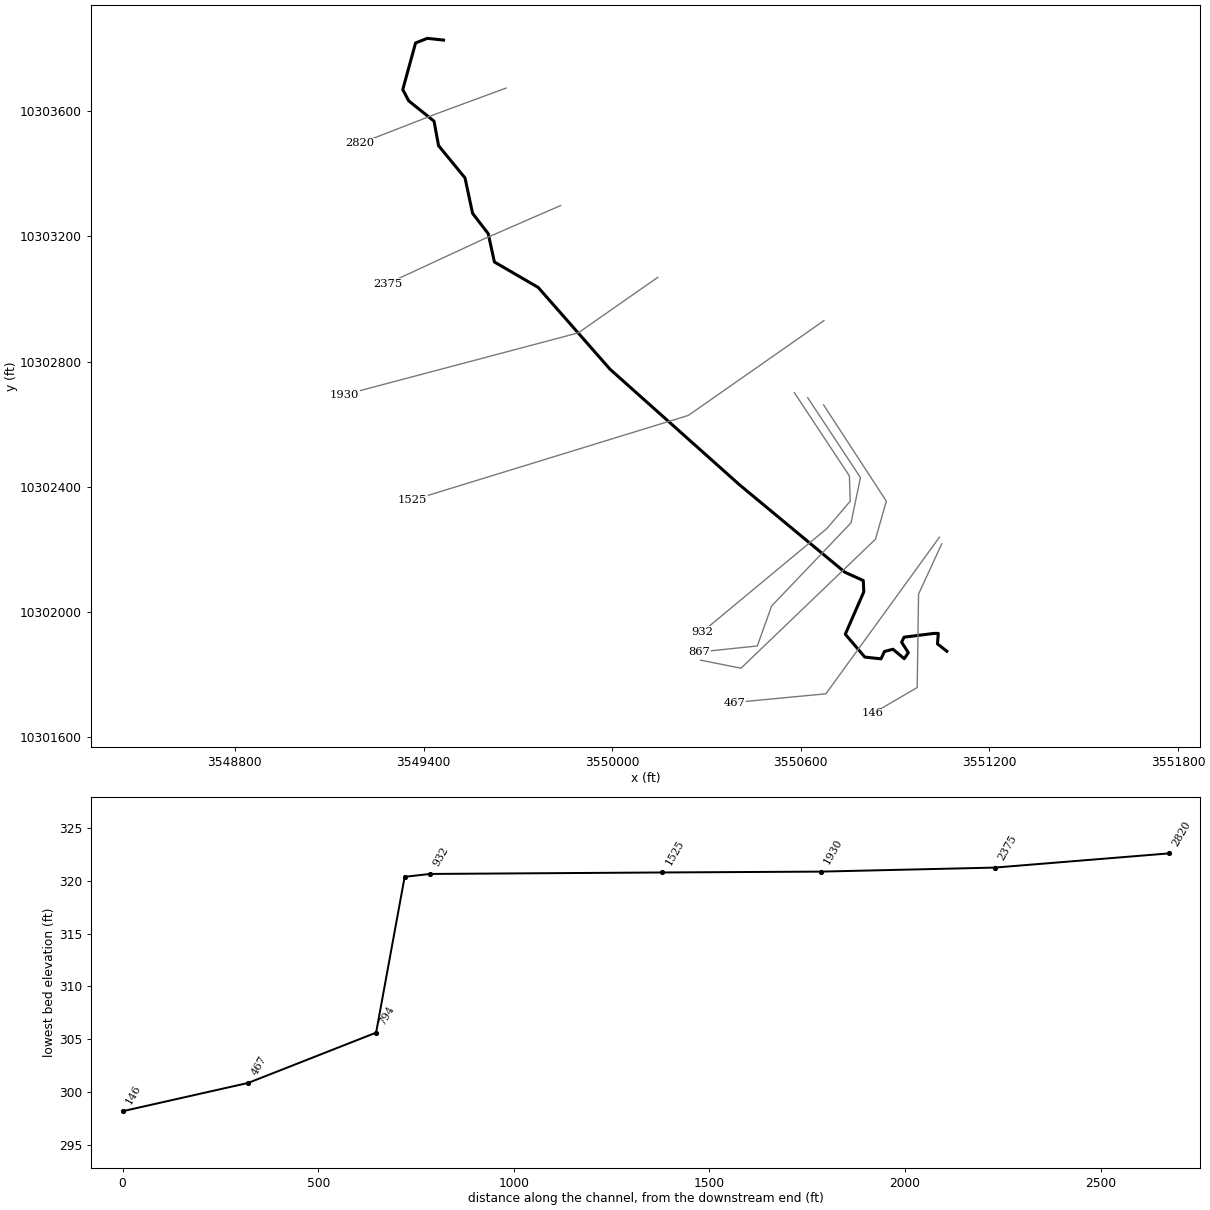
--- BEE CREEK NORTH TRIB 8 1.prj (project) ---

Proj Title=BEE CREEK NORTH TRIB 8 1 Base Level Engineering
Current Plan=p01
Default Exp/Contr=0.3,0.1
English Units
Geom File=g01
Flow File=f01
Plan File=p01
Y Axis Title=Elevation
X Axis Title(PF)=Main Channel Distance
X Axis Title(XS)=Station
BEGIN DESCRIPTION:
BEE CREEK NORTH TRIB 8 1
END DESCRIPTION:
DSS Export Rating Curves= 0
DSS Export Rating Curve Sorted= 0
DSS Export Volume Flow Curves= 0
DXF OffsetX= 0
DXF OffsetY= 0
DXF ScaleX= 1
DXF ScaleY= 10

--- BEE CREEK NORTH TRIB 8 1.p01 (plan) ---

Plan Title=Multiple Run
Short Identifier=Multiple
Geom File=g01
Flow File=f01
Subcritical Flow
K Sum by GR= 0
Std Step Tol= 0.01
Critical Tol= 0.01
Num of Std Step Trials= 20
Max Error Tol= 0.3
Flow Tol Ratio= 0.001
Split Flow NTrial= 30
Split Flow Tol= 0.02
Split Flow Ratio= 0.02
Log Output Level= 0
Friction Slope Method= 1
Unsteady Friction Slope Method= 2
Unsteady Bridges Friction Slope Method= 1
Parabolic Critical Depth
Global Vel Dist=  1 , 1 , 1
Global Log Level= 0
CheckData=True
Encroach Param= -1, 0, 0, 0
BEGIN DESCRIPTION:
Multiple Run
END DESCRIPTION:

--- BEE CREEK NORTH TRIB 8 1.f01 (steady flow) ---

Flow Title=Multiple
Program Version=4.10
Number of Profiles= 7
Profile Names=10-year,25-year,50-year,1pct_min,100-year,1pct_plu,500-year
River Rch & RM=BEE CREEK NORTH,Reach-1         ,2820
     224     285     333     286     387     523     521
Boundary for River Rch & Prof#=BEE CREEK NORTH,Reach-1         , 1
Up Type= 0
Dn Type= 3
Dn Slope=0.0145
Boundary for River Rch & Prof#=BEE CREEK NORTH,Reach-1         , 2
Up Type= 0
Dn Type= 3
Dn Slope=0.0145
Boundary for River Rch & Prof#=BEE CREEK NORTH,Reach-1         , 3
Up Type= 0
Dn Type= 3
Dn Slope=0.0145
Boundary for River Rch & Prof#=BEE CREEK NORTH,Reach-1         , 4
Up Type= 0
Dn Type= 3
Dn Slope=0.0145
Boundary for River Rch & Prof#=BEE CREEK NORTH,Reach-1         , 5
Up Type= 0
Dn Type= 3
Dn Slope=0.0145
Boundary for River Rch & Prof#=BEE CREEK NORTH,Reach-1         , 6
Up Type= 0
Dn Type= 3
Dn Slope=0.0145
Boundary for River Rch & Prof#=BEE CREEK NORTH,Reach-1         , 7
Up Type= 0
Dn Type= 3
Dn Slope=0.0145
DSS Import GetInterval= 0
DSS Import GetPeak= 0
DSS Import FillOption= 0

--- BEE CREEK NORTH TRIB 8 1.g01 (geometry) ---

Geom Title=Existing Conditions
Program Version=4.10

River Reach=BEE CREEK NORTH ,Reach-1
Reach XY= 30
      3549463.63     10303826.44      3549411.98     10303832.08
      3549374.65     10303817.33       3549333.9     10303668.53
      3549352.86     10303632.47      3549433.41     10303567.54
      3549447.75     10303489.39      3549531.86     10303386.54
        3549556.     10303273.25      3549605.69     10303208.41
      3549625.47     10303117.96      3549764.74     10303036.74
      3549993.38     10302775.43      3550405.24     10302406.49
      3550740.45     10302127.36      3550798.87     10302100.83
      3550800.44     10302064.89      3550741.58     10301929.48
      3550803.56     10301856.56      3550855.12     10301850.83
      3550866.06     10301874.27      3550893.14     10301881.56
      3550929.08     10301851.35       3550942.1     10301870.62
      3550920.75     10301903.96      3550928.56      10301920.1
      3551023.35     10301932.08      3551037.41     10301932.08
      3551034.81     10301898.75      3551064.62     10301875.05

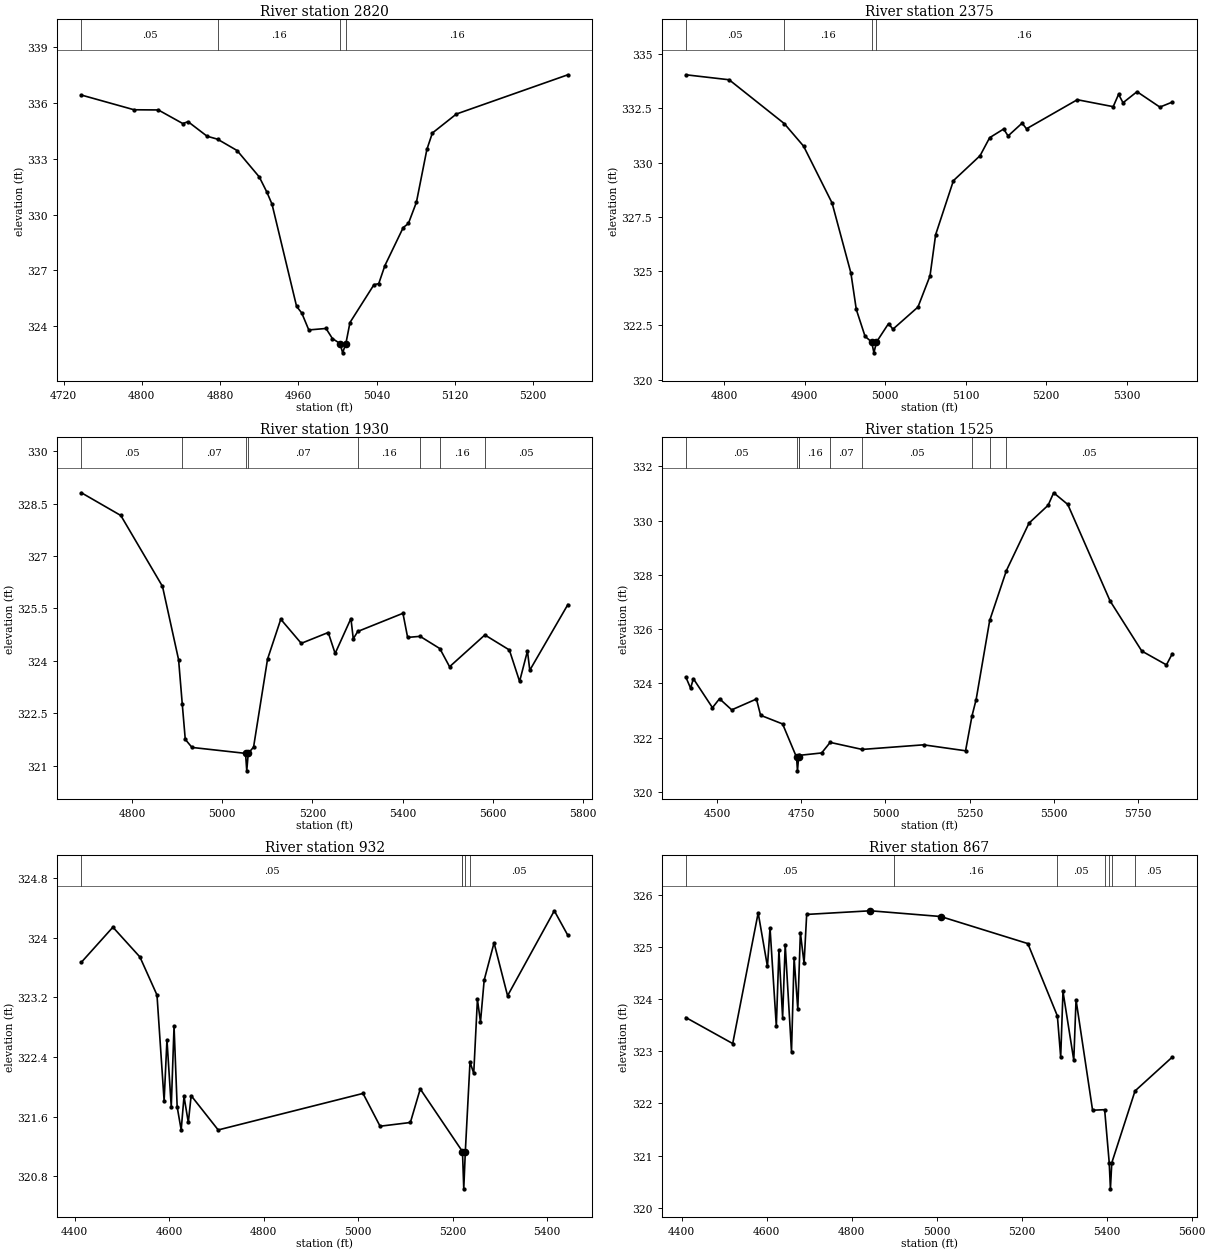
Type RM Length L Ch R = 1 ,2820    ,445,445,445
BEGIN DESCRIPTION:
BEE CREEK NORTH TRIB 8.1 6.0
END DESCRIPTION:
XS GIS Cut Line= 3
      3549662.55     10303673.27      3549442.11     10303591.64
      3549197.89     10303496.43
#Sta/Elev= 30
  4738.3  336.42  4792.1  335.63  4816.9  335.62  4841.9  334.89  4847.3  334.99
  4866.7  334.21  4877.4  334.05  4897.4  333.44  4920.1  332.02  4927.8  331.21
  4933.1  330.56  4958.2  325.07  4963.5  324.71  4970.7   323.8  4988.3  323.88
  4994.8  323.34  5002.6  323.07  5005.3  322.57  5008.6  323.07  5012.8   324.2
  5037.3  326.23  5042.2  326.29  5048.5  327.26  5067.2   329.3  5072.5  329.52
  5080.7  330.66  5091.4   333.5    5097  334.38  5121.5   335.4  5235.5  337.51
#Mann= 4 ,-1 , 0
  4738.3     .05       0  4877.4     .16       0  5002.6     .07       0
  5008.6     .16       0
Bank Sta=5002.6,5008.6
XS Rating Curve= 0 ,0
Exp/Cntr=0.3,0.1

Type RM Length L Ch R = 1 ,2375    ,445,445,445
BEGIN DESCRIPTION:
BEE CREEK NORTH TRIB 8.1 5.0
END DESCRIPTION:
XS GIS Cut Line= 3
      3549836.15     10303298.26      3549592.11     10303191.64
       3549285.6     10303048.98
#Sta/Elev= 30
  4752.4  334.05  4806.2  333.82  4874.7   331.8  4898.7  330.76  4934.1  328.14
  4957.5  324.91  4964.2  323.23  4975.1  321.99  4983.3  321.73  4986.1  321.23
  4989.3  321.73  5004.3  322.58  5009.7  322.32  5040.8  323.34  5055.8  324.78
  5062.8  326.68  5084.9  329.17    5118  330.32  5129.9  331.15  5147.3  331.55
  5152.8  331.23  5170.2  331.82  5175.7  331.56  5238.8   332.9  5283.4  332.58
  5290.1  333.15  5295.6  332.76    5313  333.27  5341.4  332.56  5356.8  332.79
#Mann= 4 ,-1 , 0
  4752.4     .05       0  4874.7     .16       0  4983.3     .07       0
  4989.3     .16       0
Bank Sta=4983.3,4989.3
XS Rating Curve= 0 ,0
Exp/Cntr=0.3,0.1

Type RM Length L Ch R = 1 ,1930    ,405,405,405
BEGIN DESCRIPTION:
BEE CREEK NORTH TRIB 8.1 4.0
END DESCRIPTION:
XS GIS Cut Line= 3
      3550145.22     10303069.12      3549892.11     10302891.64
      3549148.73     10302694.12
#Sta/Elev= 30
  4687.9  328.81  4775.2  328.16  4867.6  326.13  4903.3  324.03  4911.5  322.75
  4918.1  321.75    4933  321.52  5051.7  321.35  5054.4  320.85  5057.7  321.35
  5069.5  321.53  5100.5  324.05  5129.8  325.19  5175.2   324.5    5235  324.81
  5250.3  324.21  5285.3  325.21  5290.5  324.63  5300.4  324.84  5400.6  325.36
    5411  324.67  5438.7   324.7  5482.4  324.35    5504  323.83  5582.2  324.74
  5636.5  324.31  5659.2  323.41  5676.6  324.28  5681.8  323.73  5766.2  325.61
#Mann= 8 ,-1 , 0
  4687.9     .05       0  4911.5     .07       0  5051.7     .07       0
  5057.7     .07       0  5300.4     .16       0  5438.7     .05       0
  5482.4     .16       0  5582.2     .05       0
Bank Sta=5051.7,5057.7
XS Rating Curve= 0 ,0
Exp/Cntr=0.3,0.1

Type RM Length L Ch R = 1 ,1525    ,593,593,593
BEGIN DESCRIPTION:
BEE CREEK NORTH TRIB 8.1 3.0
END DESCRIPTION:
XS GIS Cut Line= 3
      3550673.66     10302930.75      3550242.44     10302628.14
      3549365.58      10302357.8
#Sta/Elev= 30
  4407.3  324.23  4421.4  323.82  4429.7  324.17  4486.4   323.1  4507.3  323.43
  4543.6  323.02  4616.9  323.42  4629.3  322.82  4694.6   322.5  4736.1  321.27
  4738.8  320.77  4742.1  321.27  4743.1  321.34  4810.6  321.43  4835.9  321.82
  4930.9  321.56  5113.2  321.73  5237.9  321.51  5257.1   322.8  5269.3   323.4
  5309.6  326.32  5359.2  328.16  5426.3  329.91  5483.1  330.57  5499.5  331.03
  5541.4   330.6    5667  327.04  5761.2  325.19  5834.4  324.68  5851.7  325.09
#Mann= 9 ,-1 , 0
  4407.3     .05       0  4736.1    .033       0  4742.1     .05       0
  4743.1     .16       0  4835.9     .07       0  4930.9     .05       0
  5257.1     .07       0  5309.6     .16       0  5359.2     .05       0
Bank Sta=4736.1,4742.1
XS Rating Curve= 0 ,0
Exp/Cntr=0.3,0.1

Type RM Length L Ch R = 1 ,932     ,65,65,65
BEGIN DESCRIPTION:
BEE CREEK NORTH TRIB 8.1 2.2
END DESCRIPTION:
XS GIS Cut Line= 5
      3550579.53     10302700.78      3550754.67     10302434.97
      3550757.27     10302354.24      3550683.06       10302267.
      3550286.72     10301936.95
#Sta/Elev= 30
  4414.6  323.67  4481.2  324.14  4538.4  323.74  4574.5  323.23  4589.6  321.81
  4595.6  322.63  4604.7  321.73  4610.6  322.81  4617.2  321.73  4625.7  321.42
  4631.7  321.87  4640.8  321.52  4646.8  321.88    4704  321.42  5010.5  321.91
  5046.6  321.47  5110.7  321.52  5131.6  321.97    5221  321.13  5223.7  320.63
    5227  321.13  5236.9  322.33  5244.8  322.18  5252.6  323.17  5259.1  322.87
  5266.9  323.43  5287.8  323.93  5316.4  323.22  5415.3  324.36    5444  324.03
#Mann= 5 ,-1 , 0
  4414.6     .05       0    5221     .16       0    5221    .033       0
    5227     .16       0  5236.9     .05       0
Bank Sta=5221,5227
XS Rating Curve= 0 ,0
Exp/Cntr=0.3,0.1

Type RM Length L Ch R = 1 ,867     ,73,73,73
BEGIN DESCRIPTION:
BEE CREEK NORTH TRIB 8.1 2.1
END DESCRIPTION:
XS GIS Cut Line= 6
      3550621.84       10302685.      3550789.83     10302429.77
      3550759.88     10302285.23      3550507.27     10302019.61
       3550461.7       10301892.      3550277.64      10301872.8
#Sta/Elev= 30
    4410  323.65  4520.3  323.15  4580.2  325.66    4602  324.63  4608.1  325.37
  4622.9  323.48    4629  324.94  4637.7  323.65  4643.8  325.05  4658.6  322.99
  4664.7   324.8  4673.4  323.81  4679.5  325.28  4688.2  324.69  4694.3  325.63
  4844.2   325.7  5009.5  325.59  5214.6  325.07  5284.1  323.68  5291.9  322.89
  5297.3  324.15  5322.7  322.83    5328  323.99  5366.9  321.87  5395.3  321.88
  5406.1  320.86  5408.9  320.36  5412.1  320.86  5466.8  322.24  5554.4  322.89
#Mann= 7 ,-1 , 0
    4410     .05       0    4900     .16       0  5284.1     .05       0
  5395.3     .16       0  5406.1     .07       0  5412.1     .16       0
  5466.8     .05       0
Bank Sta=4844.2,5009.5
XS Rating Curve= 0 ,0
Exp/Cntr=0.3,0.1

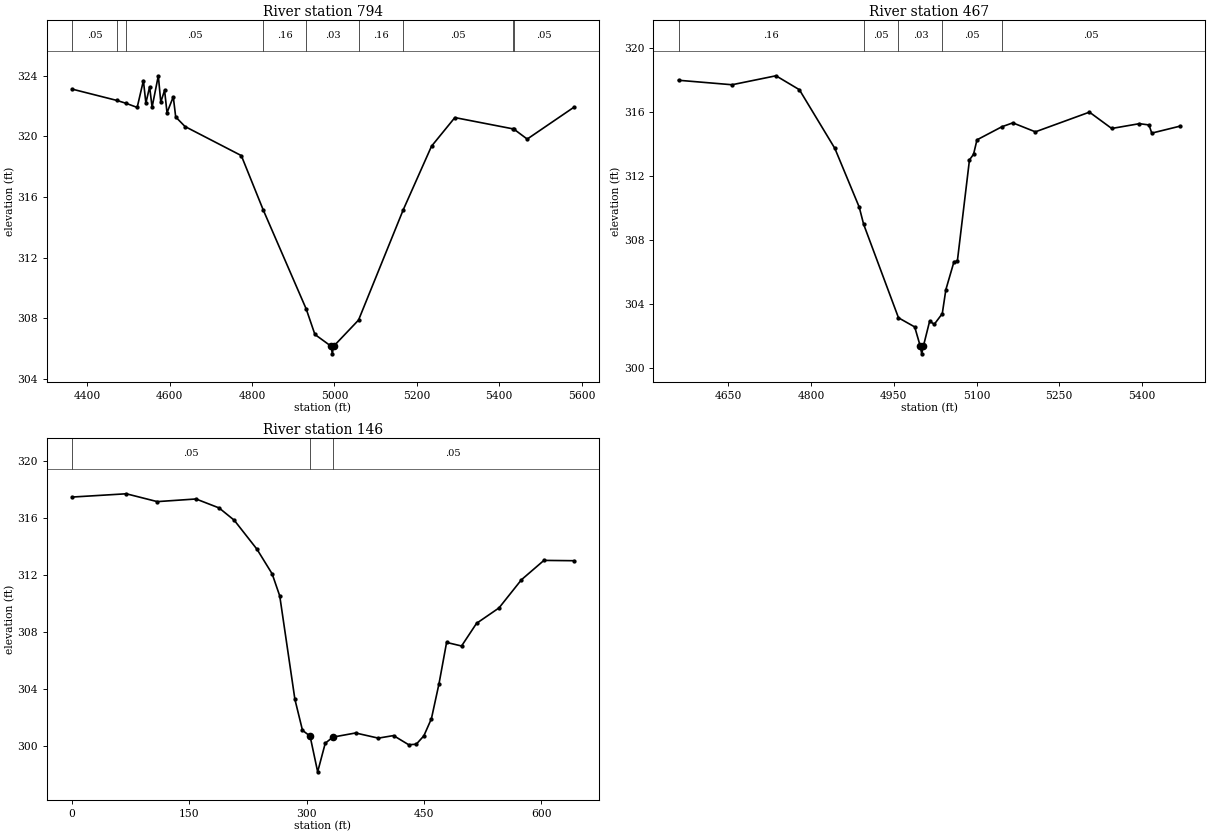
Type RM Length L Ch R = 1 ,794     ,327,327,327
BEGIN DESCRIPTION:
BEE CREEK NORTH TRIB 8.1 2.0
END DESCRIPTION:
XS GIS Cut Line= 5
      3550672.64     10302661.53       3550872.2     10302354.29
      3550837.48     10302232.77      3550409.76     10301820.93
      3550281.12      10301846.7
#Sta/Elev= 30
  4363.3  323.12  4472.3  322.37  4494.5  322.18  4521.3  321.91  4536.4  323.68
  4542.4   322.2  4551.5  323.27  4557.5  321.93  4572.6     324  4578.6  322.26
  4587.8  323.04  4593.7  321.56  4608.9  322.61  4614.8  321.28  4637.4  320.65
    4774  318.73  4826.9  315.16  4931.5   308.6  4952.6  306.92    4992  306.14
  4994.8  305.64    4998  306.14  5058.5  307.87  5167.1  315.16  5235.6  319.35
  5292.2  321.24  5432.3   320.5  5435.3  320.48  5467.8  319.82    5581  321.92
#Mann= 9 ,-1 , 0
  4363.3     .05       0  4472.3     .16       0  4494.5     .05       0
  4826.9     .16       0  4931.5     .03       0  5058.5     .16       0
  5167.1     .05       0  5432.3     .16       0  5435.3     .05       0
Bank Sta=4992,4998
XS Rating Curve= 0 ,0
Exp/Cntr=0.3,0.1

Type RM Length L Ch R = 1 ,467     ,321,321,321
BEGIN DESCRIPTION:
BEE CREEK NORTH TRIB 8.1 1.0
END DESCRIPTION:
XS GIS Cut Line= 3
      3551041.06     10302239.27      3550679.94     10301739.25
      3550388.25     10301711.47
#Sta/Elev= 30
  4559.7  317.97  4656.7  317.69  4736.4  318.25  4778.8  317.38  4843.2  313.71
  4887.3  310.05  4895.3  308.98  4958.5  303.14  4987.9  302.57  4997.8  301.39
  5000.6  300.89  5003.8  301.39  5014.9  302.92  5023.5  302.74  5037.9   303.4
  5044.4   304.9  5059.1  306.64  5065.2  306.67  5087.2     313  5094.6  313.35
  5100.8  314.25  5146.1  315.07  5165.8  315.31  5206.7  314.75  5304.7  315.98
  5345.1  314.96  5395.3  315.26  5412.7  315.18  5417.7  314.67  5469.5  315.11
#Mann= 5 ,-1 , 0
  4559.7     .16       0  4895.3     .05       0  4958.5     .03       0
  5037.9     .05       0  5146.1     .05       0
Bank Sta=4997.8,5003.8
XS Rating Curve= 0 ,0
Exp/Cntr=0.3,0.1

Type RM Length L Ch R = 1 ,146     ,0,0,0
XS GIS Cut Line= 4
     3551048.443    10302218.221     3550974.658    10302057.631
     3550970.318    10301759.236     3550829.259    10301676.771
#Sta/Elev= 30
       0 317.44769.32286317.6766108.9359317.1276158.4523317.3129187.9554316.6861
207.3487315.8248236.4386313.7942255.8318312.0715265.5285310.5255284.9217303.2868
294.6183301.1192 304.315300.7151314.0116298.2163323.7083300.2161333.4049300.6459
362.4948300.9361391.5847300.5753410.9779300.7539430.3712300.1143440.0678300.1487
449.7645300.7334459.4611 301.938469.1577304.3836478.8543307.2736497.9984 307.023
517.1424308.6086545.8585309.6871574.5745311.6613603.2905313.0143641.5786312.9921
#Mann= 3 ,-1 , 0
       0     .05       0 304.315     .03       0333.4049     .05       0
Bank Sta=304.315,333.4049
XS Rating Curve= 0 ,0
Exp/Cntr=0.3,0.1

Chan Stop Cuts=-1
Use User Specified Reach Order=0
Composite Channel Slope=5