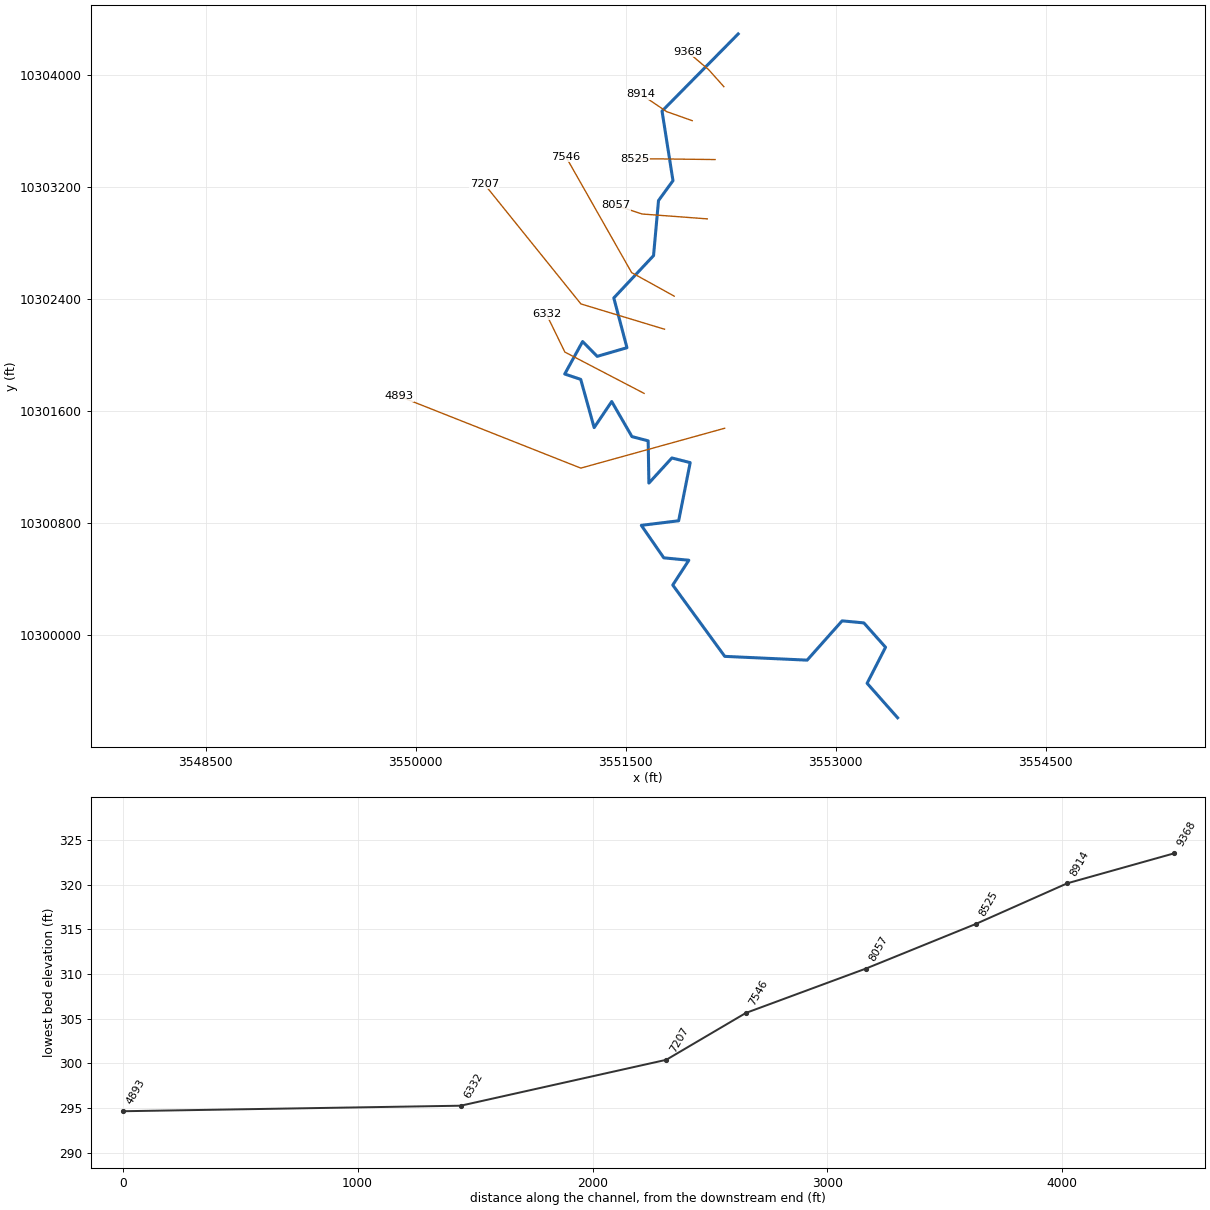
--- BEE CREEK NORTH TRIBUTARY 8.prj (project) ---

Proj Title=BEE CREEK NORTH TRIBUTARY 8 Base Level Engineering
Current Plan=p01
Default Exp/Contr=0.3,0.1
English Units
Geom File=g01
Flow File=f01
Plan File=p01
Y Axis Title=Elevation
X Axis Title(PF)=Main Channel Distance
X Axis Title(XS)=Station
BEGIN DESCRIPTION:
BEE CREEK NORTH TRIBUTARY 8
END DESCRIPTION:
DSS Export Rating Curves= 0
DSS Export Rating Curve Sorted= 0
DSS Export Volume Flow Curves= 0
DXF OffsetX= 0
DXF OffsetY= 0
DXF ScaleX= 1
DXF ScaleY= 10

--- BEE CREEK NORTH TRIBUTARY 8.p01 (plan) ---

Plan Title=Multiple Run
Short Identifier=Multiple
Geom File=g01
Flow File=f01
Subcritical Flow
K Sum by GR= 0
Std Step Tol= 0.01
Critical Tol= 0.01
Num of Std Step Trials= 20
Max Error Tol= 0.3
Flow Tol Ratio= 0.001
Split Flow NTrial= 30
Split Flow Tol= 0.02
Split Flow Ratio= 0.02
Log Output Level= 0
Friction Slope Method= 1
Unsteady Friction Slope Method= 2
Unsteady Bridges Friction Slope Method= 1
Parabolic Critical Depth
Global Vel Dist=  1 , 1 , 1
Global Log Level= 0
CheckData=True
Encroach Param= -1, 0, 0, 0
BEGIN DESCRIPTION:
Multiple Run
END DESCRIPTION:

--- BEE CREEK NORTH TRIBUTARY 8.f01 (steady flow) ---

Flow Title=Multiple
Program Version=4.10
Number of Profiles= 7
Profile Names=10-year,25-year,50-year,1pct_min,100-year,1pct_plu,500-year
River Rch & RM=BEE CREEK NORTH,Reach-1         ,9368
     300     391     463     403     546     738     757
River Rch & RM=BEE CREEK NORTH,Reach-1         ,4893
     480     640     769     678     916    1239    1303
Boundary for River Rch & Prof#=BEE CREEK NORTH,Reach-1         , 1
Up Type= 0
Dn Type= 3
Dn Slope=0.005
Boundary for River Rch & Prof#=BEE CREEK NORTH,Reach-1         , 2
Up Type= 0
Dn Type= 3
Dn Slope=0.005
Boundary for River Rch & Prof#=BEE CREEK NORTH,Reach-1         , 3
Up Type= 0
Dn Type= 3
Dn Slope=0.005
Boundary for River Rch & Prof#=BEE CREEK NORTH,Reach-1         , 4
Up Type= 0
Dn Type= 3
Dn Slope=0.005
Boundary for River Rch & Prof#=BEE CREEK NORTH,Reach-1         , 5
Up Type= 0
Dn Type= 3
Dn Slope=0.005
Boundary for River Rch & Prof#=BEE CREEK NORTH,Reach-1         , 6
Up Type= 0
Dn Type= 3
Dn Slope=0.005
Boundary for River Rch & Prof#=BEE CREEK NORTH,Reach-1         , 7
Up Type= 0
Dn Type= 3
Dn Slope=0.005
DSS Import GetInterval= 0
DSS Import GetPeak= 0
DSS Import FillOption= 0

--- BEE CREEK NORTH TRIBUTARY 8.g01 (geometry) ---

Geom Title=Existing Conditions

River Reach=BEE CREEK NORTH ,Reach-1
Reach XY= 30
      3552303.38     10304296.32      3551759.50     10303745.08
      3551837.58     10303248.20      3551734.20     10303105.85
      3551698.76     10302712.70      3551414.91     10302410.47
      3551508.86     10302055.05      3551296.36     10301993.25
      3551192.19     10302099.15      3551064.42     10301867.06
      3551178.62     10301828.78      3551274.52     10301484.31
      3551399.96     10301670.51      3551544.49     10301420.07
      3551660.38     10301389.69      3551665.58     10301088.04
      3551829.65     10301267.29      3551960.72     10301234.31
      3551878.26     10300818.94      3551611.50     10300786.04
      3551771.92     10300554.10      3551951.00     10300536.83
      3551835.98     10300359.74      3552207.59     10299850.25
      3552796.00     10299823.33      3553045.80     10300103.93
      3553201.14     10300089.28      3553355.99     10299915.31
      3553224.27     10299658.01      3553442.11     10299411.64

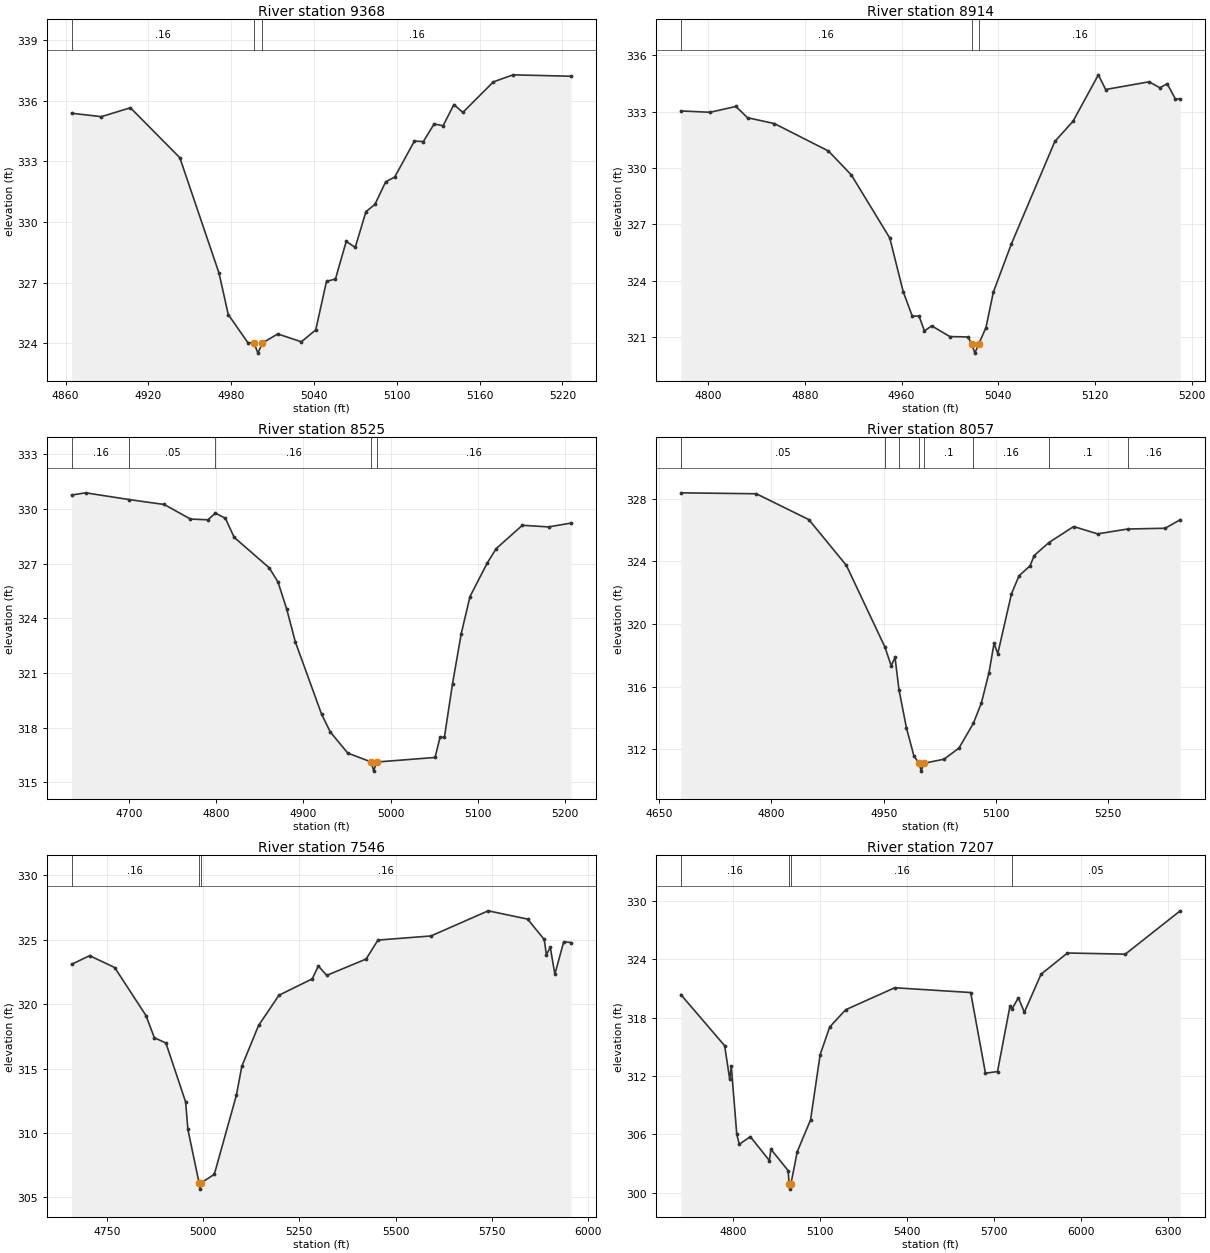
Type RM Length L Ch R = 1,9368,454,454,454
BEGIN DESCRIPTION:
BEE CREEK NORTH TRIBUTARY 8 9.0
END DESCRIPTION:
XS GIS Cut Line= 3
      3552200.76     10303919.81      3552092.11     10304041.64
      3551940.33     10304169.82
#Sta/Elev= 30
  4864.4  335.38  4885.9  335.21  4907.0  335.65  4942.8  333.18  4971.2  327.47
  4977.9  325.42  4992.1  324.03  4996.6  324.01  4999.4  323.51  5002.6  324.01
  5013.8  324.46  5030.9  324.07  5041.3  324.66  5049.1  327.06  5055.6  327.18
  5063.4  329.04  5069.9  328.74  5077.7  330.51  5084.2  330.87  5092.0  331.99
  5098.5  332.22  5112.8  334.00  5119.3  333.98  5127.1  334.85  5133.6  334.76
  5141.4  335.81  5147.9  335.42  5170.0  336.93  5184.3  337.28  5226.3  337.21
#Mann=3,-1,0
  4864.4    0.16       0  4996.6    0.07       0  5002.6    0.16       0
Bank Sta=4996.6,5002.6
Exp/Cntr=0.3,0.1

Type RM Length L Ch R = 1,8914,389,389,389
BEGIN DESCRIPTION:
BEE CREEK NORTH TRIBUTARY 8 8.0
END DESCRIPTION:
XS GIS Cut Line= 3
      3551975.05     10303676.76      3551792.11     10303741.64
      3551610.52     10303864.23
#Sta/Elev= 30
  4777.3  333.03  4801.6  332.96  4822.9  333.27  4832.5  332.67  4854.7  332.36
  4899.5  330.90  4918.4  329.63  4950.2  326.28  4961.3  323.43  4968.8  322.13
  4974.4  322.13  4978.9  321.34  4984.9  321.61  4999.9  321.04  5014.9  321.02
  5017.9  320.66  5020.6  320.16  5023.9  320.66  5029.8  321.52  5035.9  323.40
  5050.8  325.96  5086.8  331.41  5101.8  332.48  5122.8  334.95  5128.8  334.17
  5164.8  334.58  5173.7  334.26  5179.7  334.48  5186.5  333.67  5190.5  333.67
#Mann=3,-1,0
  4777.3    0.16       0  5017.9    0.07       0  5023.9    0.16       0
Bank Sta=5017.9,5023.9
Exp/Cntr=0.3,0.1

Type RM Length L Ch R = 1,8525,468,468,468
BEGIN DESCRIPTION:
BEE CREEK NORTH TRIBUTARY 8 7.0
END DESCRIPTION:
XS GIS Cut Line= 3
      3552138.24     10303398.97      3551715.72     10303404.14
      3551566.37     10303404.14
#Sta/Elev= 30
  4634.6  330.76  4650.7  330.88  4700.5  330.51  4740.7  330.24  4770.7  329.44
  4790.7  329.40  4799.3  329.77  4810.7  329.48  4820.7  328.44  4860.8  326.77
  4870.8  326.00  4880.8  324.52  4890.8  322.70  4920.8  318.74  4930.8  317.76
  4950.8  316.60  4977.8  316.11  4980.5  315.61  4983.8  316.11  5050.8  316.36
  5056.5  317.47  5061.5  317.47  5070.8  320.41  5080.8  323.16  5090.8  325.19
  5110.8  327.05  5120.8  327.82  5150.8  329.10  5180.8  329.01  5206.5  329.22
#Mann=5,-1,0
  4634.6    0.16       0  4700.5    0.05       0  4799.3    0.16       0
  4977.8    0.07       0  4983.8    0.16       0
Bank Sta=4977.8,4983.8
Exp/Cntr=0.3,0.1

Type RM Length L Ch R = 1,8057,511,511,511
BEGIN DESCRIPTION:
BEE CREEK NORTH TRIBUTARY 8 6.0
END DESCRIPTION:
XS GIS Cut Line= 3
      3552082.71     10302975.36      3551617.44     10303010.08
      3551426.75     10303072.49
#Sta/Elev= 30
  4679.0  328.37  4779.9  328.31  4850.1  326.66  4900.2  323.74  4951.7  318.53
  4960.1  317.33  4965.2  317.87  4970.5  315.81  4980.4  313.38  4990.5  311.57
  4997.5  311.11  5000.2  310.61  5003.5  311.11  5030.6  311.37  5050.6  312.08
  5069.9  313.66  5080.7  314.98  5090.7  316.88  5097.5  318.76  5102.5  318.11
  5120.8  321.93  5130.9  323.08  5145.6  323.71  5151.2  324.37  5170.6  325.19
  5203.9  326.22  5235.8  325.75  5275.9  326.06  5326.1  326.11  5346.2  326.65
#Mann=8,-1,0
  4679.0    0.05       0  4951.7    0.16       0  4970.5     0.1       0
  4997.5    0.07       0  5003.5     0.1       0  5069.9    0.16       0
  5170.6     0.1       0  5275.9    0.16       0
Bank Sta=4997.5,5003.5
Exp/Cntr=0.3,0.1

Type RM Length L Ch R = 1,7546,339,339,339
BEGIN DESCRIPTION:
BEE CREEK NORTH TRIBUTARY 8 5.0
END DESCRIPTION:
XS GIS Cut Line= 3
      3551846.56     10302423.30      3551542.11     10302591.64
      3551073.21     10303418.20
#Sta/Elev= 30
  4658.0  323.09  4704.7  323.76  4769.9  322.84  4851.3  319.11  4873.0  317.39
  4903.1  316.98  4954.4  312.40  4960.2  310.27  4989.2  306.14  4991.9  305.64
  4995.2  306.14  5028.9  306.79  5086.4  312.94  5100.4  315.17  5143.9  318.34
  5197.0  320.69  5283.5  321.96  5299.4  322.96  5321.1  322.23  5423.5  323.50
  5454.3  324.97  5592.2  325.29  5740.8  327.24  5843.2  326.60  5886.5  325.02
  5892.2  323.83  5902.3  324.41  5914.2  322.32  5937.2  324.84  5956.2  324.78
#Mann=3,-1,0
  4658.0    0.16       0  4989.2    0.07       0  4995.2    0.16       0
Bank Sta=4989.2,4995.2
Exp/Cntr=0.3,0.1

Type RM Length L Ch R = 1,7207,875,875,875
BEGIN DESCRIPTION:
BEE CREEK NORTH TRIBUTARY 8 4.0
END DESCRIPTION:
XS GIS Cut Line= 3
      3551777.12     10302187.18      3551179.94     10302367.72
      3550488.99     10303225.33
#Sta/Elev= 30
  4618.1  320.37  4769.6  315.12  4787.1  311.67  4792.4  313.04  4811.4  306.04
  4820.1  305.00  4858.3  305.78  4924.2  303.32  4929.4  304.49  4989.0  302.29
  4992.3  300.89  4995.0  300.39  4998.3  300.89  5020.3  304.23  5066.4  307.51
  5099.4  314.19  5132.3  317.03  5187.5  318.81  5357.1  321.07  5619.5  320.58
  5670.6  312.30  5712.2  312.46  5755.4  319.21  5761.9  318.87  5784.2  320.04
  5805.0  318.56  5862.6  322.46  5953.8  324.64  6153.7  324.52  6343.3  328.97
#Mann=4,-1,0
  4618.1    0.16       0  4992.3    0.07       0  4998.3    0.16       0
  5761.9    0.05       0
Bank Sta=4992.3,4998.3
Exp/Cntr=0.3,0.1

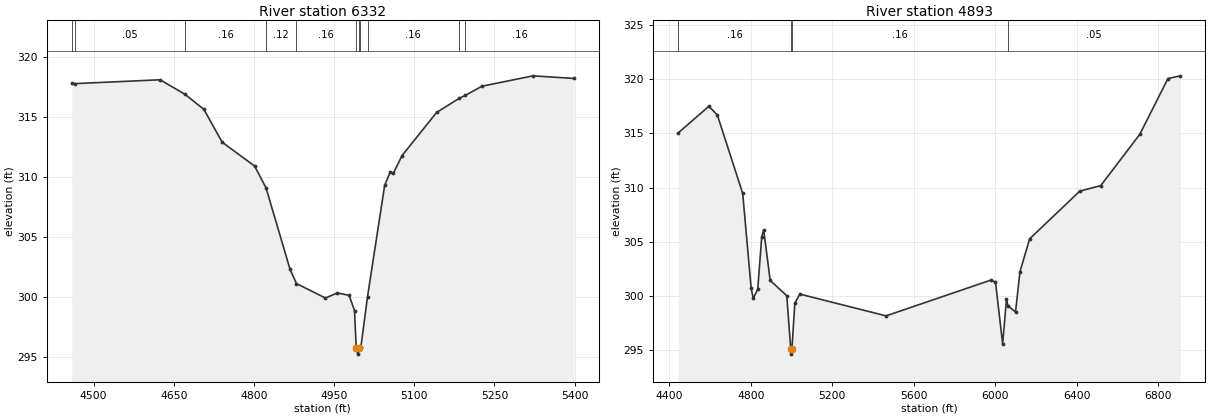
Type RM Length L Ch R = 1,6332,1439,1439,1439
BEGIN DESCRIPTION:
BEE CREEK NORTH TRIBUTARY 8 3.0
END DESCRIPTION:
XS GIS Cut Line= 3
      3551631.29     10301728.85      3551065.35     10302023.97
      3550933.42     10302294.78
#Sta/Elev= 30
  4459.0  317.83  4464.9  317.82  4624.4  318.14  4671.2  316.92  4706.2  315.67
  4740.5  312.93  4801.2  310.94  4822.5  309.12  4867.4  302.33  4879.4  301.14
  4933.7  299.93  4955.8  300.35  4977.9  300.16  4988.1  298.89  4991.3  295.75
  4994.1  295.25  4997.3  295.75  4998.5  295.79  5000.0  295.85  5012.4  300.03
  5044.5  309.33  5055.0  310.45  5060.6  310.33  5077.1  311.82  5141.8  315.42
  5183.9  316.59  5195.4  316.84  5226.4  317.60  5322.1  318.47  5398.5  318.25
#Mann=11,-1,0
  4459.0    0.16       0  4464.9    0.05       0  4671.2    0.16       0
  4822.5    0.12       0  4879.4    0.16       0  4991.3    0.07       0
  4997.3    0.16       0  4998.5    0.12       0  5012.4    0.16       0
  5183.9    0.12       0  5195.4    0.16       0
Bank Sta=4991.3,4997.3
Exp/Cntr=0.3,0.1

Type RM Length L Ch R = 1,4893,0,0,0
BEGIN DESCRIPTION:
BEE CREEK NORTH TRIBUTARY 8 1.0
END DESCRIPTION:
XS GIS Cut Line= 3
      3552206.86     10301479.71      3551179.07     10301194.98
      3549880.45     10301708.87
#Sta/Elev= 30
  4444.2  315.04  4594.4  317.50  4635.9  316.70  4760.5  309.46  4801.9  300.71
  4812.3  299.77  4834.2  300.62  4853.8  305.46  4863.4  306.10  4895.3  301.43
  4976.6  300.02  4996.1  295.13  4998.8  294.63  5002.1  295.13  5016.1  299.33
  5040.6  300.17  5463.9  298.16  5976.2  301.45  6000.6  301.28  6035.7  295.58
  6054.6  299.71  6061.3  299.11  6098.9  298.51  6120.4  302.22  6168.1  305.27
  6414.1  309.67  6516.9  310.18  6708.8  314.92  6846.6  320.06  6907.3  320.31
#Mann=4,-1,0
  4444.2    0.16       0  4996.1    0.07       0  5002.1    0.16       0
  6061.3    0.05       0
Bank Sta=4996.1,5002.1
Exp/Cntr=0.3,0.1

Chan Stop Cuts=-1