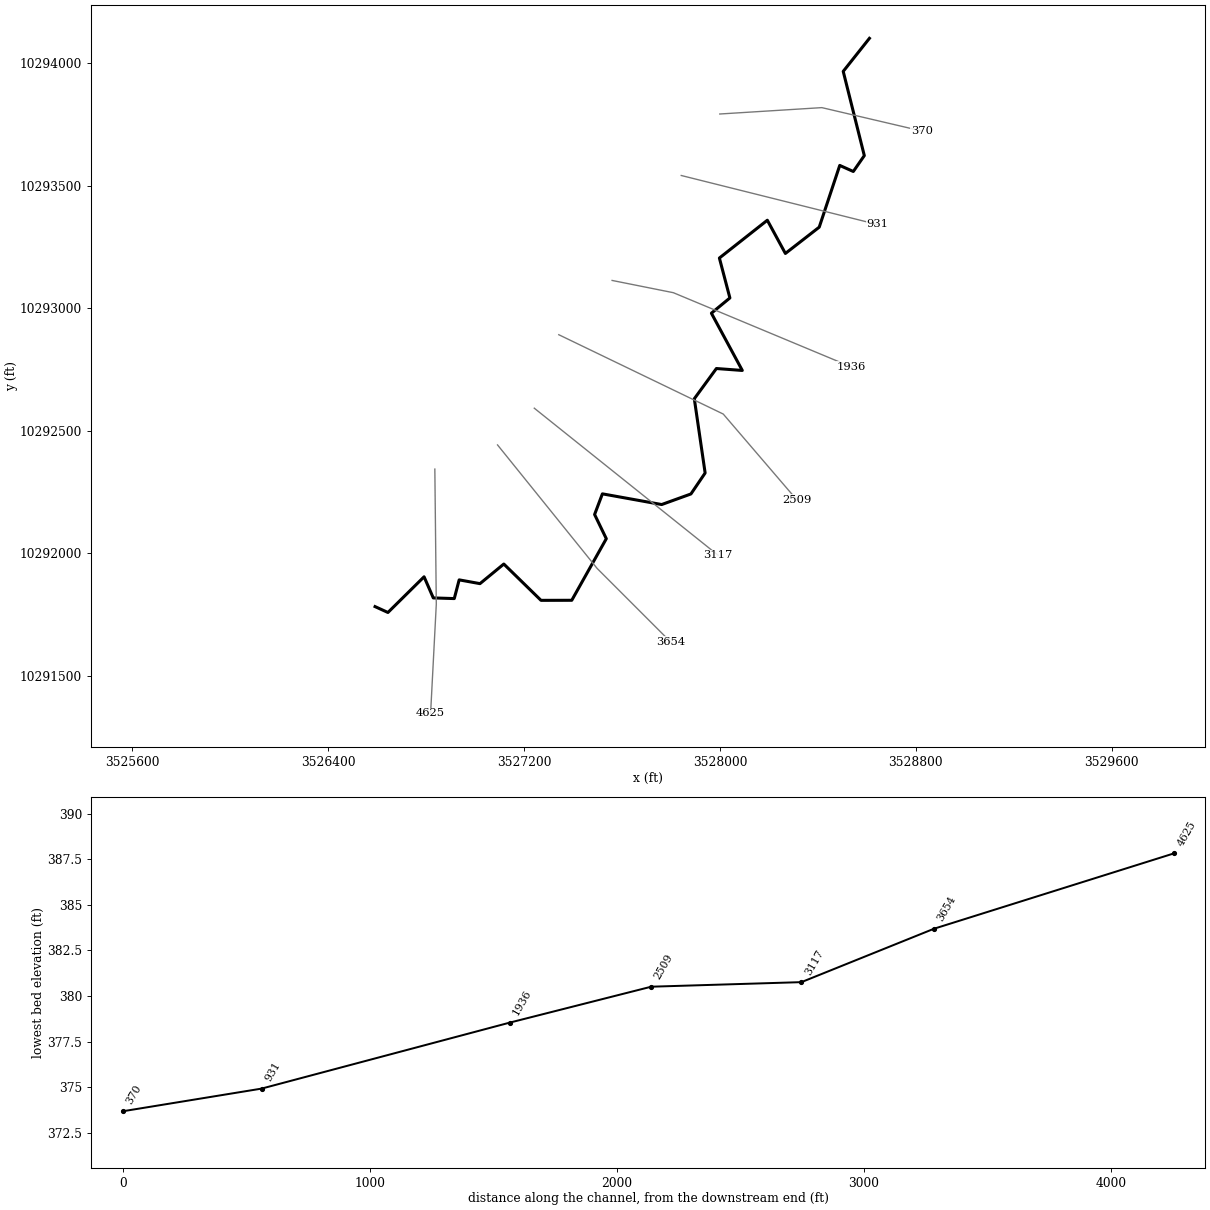
--- BEE CREEK TRIBUTARY 1.prj (project) ---

Proj Title=BEE CREEK TRIBUTARY 1 Base Level Engineering
Current Plan=p01
Default Exp/Contr=0.3,0.1
English Units
Geom File=g01
Flow File=f01
Plan File=p01
BEGIN DESCRIPTION:
BEE CREEK TRIBUTARY 1
END DESCRIPTION:

--- BEE CREEK TRIBUTARY 1.p01 (plan) ---

Plan Title=Multiple Run
Short Identifier=Multiple
Geom File=g01
Flow File=f01
Subcritical Flow
K Sum by GR= 0
Std Step Tol= 0.01
Critical Tol= 0.01
Num of Std Step Trials= 20
Max Error Tol= 0.3
Flow Tol Ratio= 0.001
Split Flow NTrial= 30
Split Flow Tol= 0.02
Split Flow Ratio= 0.02
Log Output Level= 0
Friction Slope Method= 1
Unsteady Friction Slope Method= 2
Unsteady Bridges Friction Slope Method= 1
Parabolic Critical Depth
Global Vel Dist=  1 , 1 , 1
Global Log Level= 0
CheckData=True
Encroach Param= -1, 0, 0, 0
BEGIN DESCRIPTION:
Multiple Run
END DESCRIPTION:

--- BEE CREEK TRIBUTARY 1.f01 (steady flow) ---

Flow Title=Multiple
Number of Profiles=7
Profile Names=10-year,25-year,50-year,1pct_min,100-year,1pct_plu,500-year
River Rch & RM= BEE CREEK TRIBUT,Reach-1,4625
     452     601     720     632     855    1157    1210
Boundary for River Rch & Prof#=BEE CREEK TRIBUT,Reach-1,1
Up Type=0
Dn Type=3
Dn Slope=0.005
Boundary for River Rch & Prof#=BEE CREEK TRIBUT,Reach-1,2
Up Type=0
Dn Type=3
Dn Slope=0.005
Boundary for River Rch & Prof#=BEE CREEK TRIBUT,Reach-1,3
Up Type=0
Dn Type=3
Dn Slope=0.005
Boundary for River Rch & Prof#=BEE CREEK TRIBUT,Reach-1,4
Up Type=0
Dn Type=3
Dn Slope=0.005
Boundary for River Rch & Prof#=BEE CREEK TRIBUT,Reach-1,5
Up Type=0
Dn Type=3
Dn Slope=0.005
Boundary for River Rch & Prof#=BEE CREEK TRIBUT,Reach-1,6
Up Type=0
Dn Type=3
Dn Slope=0.005
Boundary for River Rch & Prof#=BEE CREEK TRIBUT,Reach-1,7
Up Type=0
Dn Type=3
Dn Slope=0.005

--- BEE CREEK TRIBUTARY 1.g01 (geometry) ---

Geom Title=Existing Conditions

River Reach=BEE CREEK TRIBUT,Reach-1
Reach XY= 30
      3526592.11     10291781.64      3526644.63     10291757.61
      3526792.21     10291903.35      3526829.79     10291817.06
      3526915.47     10291814.38      3526935.44     10291890.76
      3527020.43     10291875.38      3527117.73     10291955.44
      3527269.56     10291807.16      3527395.16     10291807.42
      3527536.15     10292058.82      3527488.35     10292157.63
      3527520.20     10292241.94      3527762.18     10292198.28
      3527881.61     10292241.49      3527939.63     10292327.04
      3527895.44     10292630.21      3527985.58     10292753.58
      3528091.38     10292745.72      3527965.17     10292979.44
      3528040.68     10293041.71      3527997.82     10293204.65
      3528193.51     10293358.96      3528267.27     10293223.34
      3528405.42     10293330.70      3528489.17     10293582.74
      3528544.54     10293557.99      3528589.48     10293622.77
      3528503.35     10293966.68      3528610.31     10294101.57

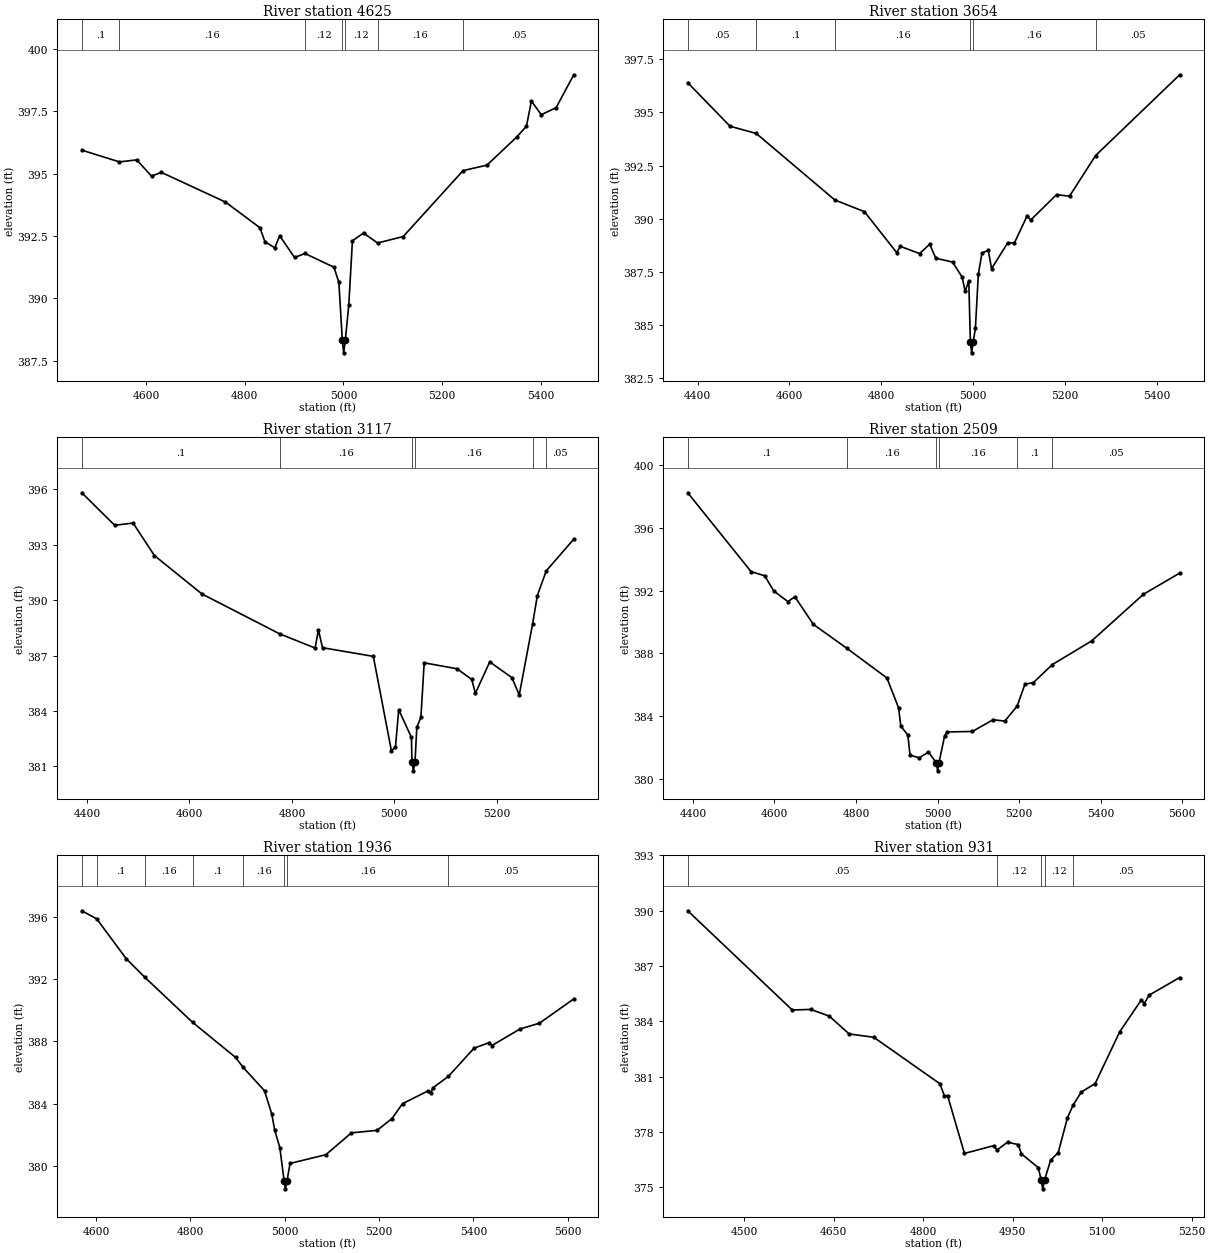
Type RM Length L Ch R = 1,4625,971,971,971
BEGIN DESCRIPTION:
BEE CREEK TRIBUTARY 1 9.0
END DESCRIPTION:
XS GIS Cut Line= 3
      3526836.14     10292342.99      3526842.11     10291791.64
      3526818.83     10291345.72
#Sta/Elev= 30
  4469.4  395.94  4545.6  395.47  4580.7  395.55  4610.8  394.90  4630.8  395.05
  4760.8  393.86  4830.8  392.83  4840.8  392.27  4860.8  392.03  4870.8  392.51
  4900.8  391.64  4922.0  391.80  4980.8  391.25  4990.8  390.64  4997.8  388.32
  5000.5  387.82  5003.8  388.32  5010.8  389.72  5018.3  392.31  5040.8  392.62
  5069.3  392.22  5121.3  392.48  5242.7  395.12  5291.1  395.34  5351.2  396.46
  5371.3  396.90  5381.3  397.91  5401.3  397.36  5431.3  397.64  5467.3  398.96
#Mann=7,-1,0
  4469.4     0.1       0  4545.6    0.16       0  4922.0    0.12       0
  4997.8    0.07       0  5003.8    0.12       0  5069.3    0.16       0
  5242.7    0.05       0
Bank Sta=4997.8,5003.8
Exp/Cntr=0.3,0.1

Type RM Length L Ch R = 1,3654,537,537,537
BEGIN DESCRIPTION:
BEE CREEK TRIBUTARY 1 7.0
END DESCRIPTION:
XS GIS Cut Line= 3
      3527092.12     10292441.63      3527498.70     10291937.48
      3527797.90     10291638.28
#Sta/Elev= 30
  4378.7  396.40  4470.7  394.35  4527.8  394.01  4698.9  390.88  4763.3  390.33
  4833.7  388.40  4841.2  388.70  4883.3  388.36  4905.4  388.80  4918.5  388.14
  4955.2  387.96  4976.0  387.25  4982.5  386.58  4990.4  387.08  4993.9  384.19
  4996.6  383.69  4999.9  384.19  5004.8  384.84  5011.2  387.39  5019.2  388.39
  5032.9  388.51  5040.0  387.65  5075.3  388.87  5089.5  388.85  5117.8  390.15
  5124.8  389.93  5181.4  391.13  5209.7  391.06  5266.4  392.97  5449.5  396.77
#Mann=6,-1,0
  4378.7    0.05       0  4527.8     0.1       0  4698.9    0.16       0
  4993.9    0.07       0  4999.9    0.16       0  5266.4    0.05       0
Bank Sta=4993.9,4999.9
Exp/Cntr=0.3,0.1

Type RM Length L Ch R = 1,3117,608,608,608
BEGIN DESCRIPTION:
BEE CREEK TRIBUTARY 1 6.0
END DESCRIPTION:
XS GIS Cut Line= 3
      3527242.08     10292591.66      3527742.11     10292191.64
      3527992.10     10291991.64
#Sta/Elev= 30
  4389.9  395.82  4454.0  394.06  4490.0  394.18  4531.6  392.42  4624.4  390.34
  4776.1  388.18  4845.4  387.41  4851.8  388.39  4859.8  387.43  4959.0  386.96
  4994.2  381.86  5002.2  382.04  5008.6  384.07  5033.4  382.57  5034.4  381.26
  5037.2  380.76  5040.4  381.26  5043.9  383.11  5051.9  383.66  5058.3  386.61
  5122.3  386.29  5151.1  385.71  5158.3  384.96  5186.3  386.66  5229.5  385.81
  5243.9  384.87  5270.0  388.72  5279.2  390.25  5296.6  391.59  5350.4  393.31
#Mann=6,-1,0
  4389.9     0.1       0  4776.1    0.16       0  5034.4    0.07       0
  5040.4    0.16       0  5270.0     0.1       0  5296.6    0.05       0
Bank Sta=5034.4,5040.4
Exp/Cntr=0.3,0.1

Type RM Length L Ch R = 1,2509,573,573,573
BEGIN DESCRIPTION:
BEE CREEK TRIBUTARY 1 5.0
END DESCRIPTION:
XS GIS Cut Line= 3
      3527342.12     10292891.64      3528013.63     10292567.68
      3528313.60     10292217.72
#Sta/Elev= 30
  4387.3  398.24  4542.7  393.21  4576.0  392.95  4598.2  391.98  4633.0  391.30
  4650.1  391.61  4695.3  389.85  4777.2  388.33  4875.8  386.43  4904.3  384.53
  4909.9  383.36  4927.0  382.80  4932.5  381.51  4955.1  381.34  4977.7  381.71
  4997.3  381.01  5000.1  380.51  5003.3  381.01  5017.4  382.75  5022.9  382.99
  5085.2  383.02  5136.2  383.77  5164.8  383.68  5195.0  384.63  5214.2  386.03
  5235.0  386.14  5281.7  387.29  5377.7  388.79  5505.0  391.77  5593.8  393.12
#Mann=6,-1,0
  4387.3     0.1       0  4777.2    0.16       0  4997.3    0.07       0
  5003.3    0.16       0  5195.0     0.1       0  5281.7    0.05       0
Bank Sta=4997.3,5003.3
Exp/Cntr=0.3,0.1

Type RM Length L Ch R = 1,1936,1005,1005,1005
BEGIN DESCRIPTION:
BEE CREEK TRIBUTARY 1 4.0
END DESCRIPTION:
XS GIS Cut Line= 3
      3527559.82     10293113.17      3527809.81     10293063.17
      3528537.34     10292759.75
#Sta/Elev= 30
  4569.7  396.37  4601.3  395.85  4663.8  393.30  4702.8  392.12  4804.4  389.22
  4895.6  386.97  4911.7  386.33  4957.1  384.83  4972.4  383.34  4978.8  382.29
  4989.6  381.18  4998.7  379.04  5001.4  378.54  5004.7  379.04  5011.3  380.17
  5087.2  380.73  5141.3  382.13  5195.5  382.29  5226.9  383.03  5249.7  384.00
  5303.8  384.82  5309.3  384.68  5314.7  385.03  5346.9  385.75  5401.4  387.56
  5433.8  387.92  5439.2  387.73  5498.9  388.79  5539.9  389.16  5612.9  390.72
#Mann=8,-1,0
  4569.7    0.05       0  4601.3     0.1       0  4702.8    0.16       0
  4804.4     0.1       0  4911.7    0.16       0  4998.7    0.07       0
  5004.7    0.16       0  5346.9    0.05       0
Bank Sta=4998.7,5004.7
Exp/Cntr=0.3,0.1

Type RM Length L Ch R = 1,931,561,561,561
BEGIN DESCRIPTION:
BEE CREEK TRIBUTARY 1 2.0
END DESCRIPTION:
XS GIS Cut Line= 3
      3527842.11     10293541.64      3528442.11     10293391.64
      3528642.09     10293341.65
#Sta/Elev= 30
  4405.3  390.00  4580.5  384.62  4611.4  384.65  4642.4  384.29  4675.9  383.32
  4717.1  383.14  4827.9  380.62  4835.6  379.96  4840.8  379.98  4869.1  376.84
  4918.1  377.26  4923.5  377.02  4941.3  377.45  4959.3  377.32  4964.5  376.82
  4992.8  376.07  4997.6  375.42  5000.3  374.92  5003.6  375.42  5013.5  376.47
  5026.3  376.89  5041.8  378.78  5051.1  379.45  5065.0  380.17  5088.2  380.63
  5129.4  383.44  5165.5  385.16  5170.6  384.97  5178.4  385.42  5229.9  386.38
#Mann=5,-1,0
  4405.3    0.05       0  4923.5    0.12       0  4997.6    0.07       0
  5003.6    0.12       0  5051.1    0.05       0
Bank Sta=4997.6,5003.6
Exp/Cntr=0.3,0.1

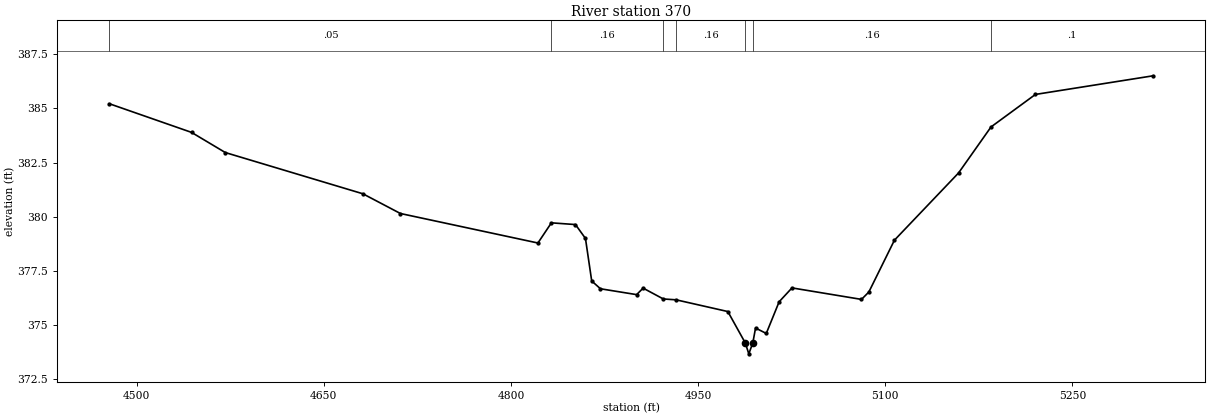
Type RM Length L Ch R = 1,370,0,0,0
BEGIN DESCRIPTION:
BEE CREEK TRIBUTARY 1 1.0
END DESCRIPTION:
XS GIS Cut Line= 3
      3527999.37     10293792.66      3528416.00     10293818.70
      3528824.03     10293723.20
#Sta/Elev= 30
  4478.2  385.21  4544.0  383.89  4571.1  382.96  4681.3  381.06  4711.4  380.15
  4821.6  378.79  4832.4  379.72  4851.7  379.64  4859.7  379.00  4864.7  377.04
  4871.7  376.68  4900.7  376.41  4905.9  376.71  4922.1  376.21  4932.4  376.17
  4973.8  375.63  4987.8  374.18  4990.6  373.68  4993.8  374.18  4996.0  374.87
  5004.6  374.62  5014.9  376.08  5025.2  376.72  5080.9  376.19  5086.8  376.53
  5107.3  378.92  5158.7  382.02  5184.7  384.14  5220.3  385.64  5314.7  386.50
#Mann=7,-1,0
  4478.2    0.05       0  4832.4    0.16       0  4922.1    0.05       0
  4932.4    0.16       0  4987.8    0.07       0  4993.8    0.16       0
  5184.7     0.1       0
Bank Sta=4987.8,4993.8
Exp/Cntr=0.3,0.1

Chan Stop Cuts=-1