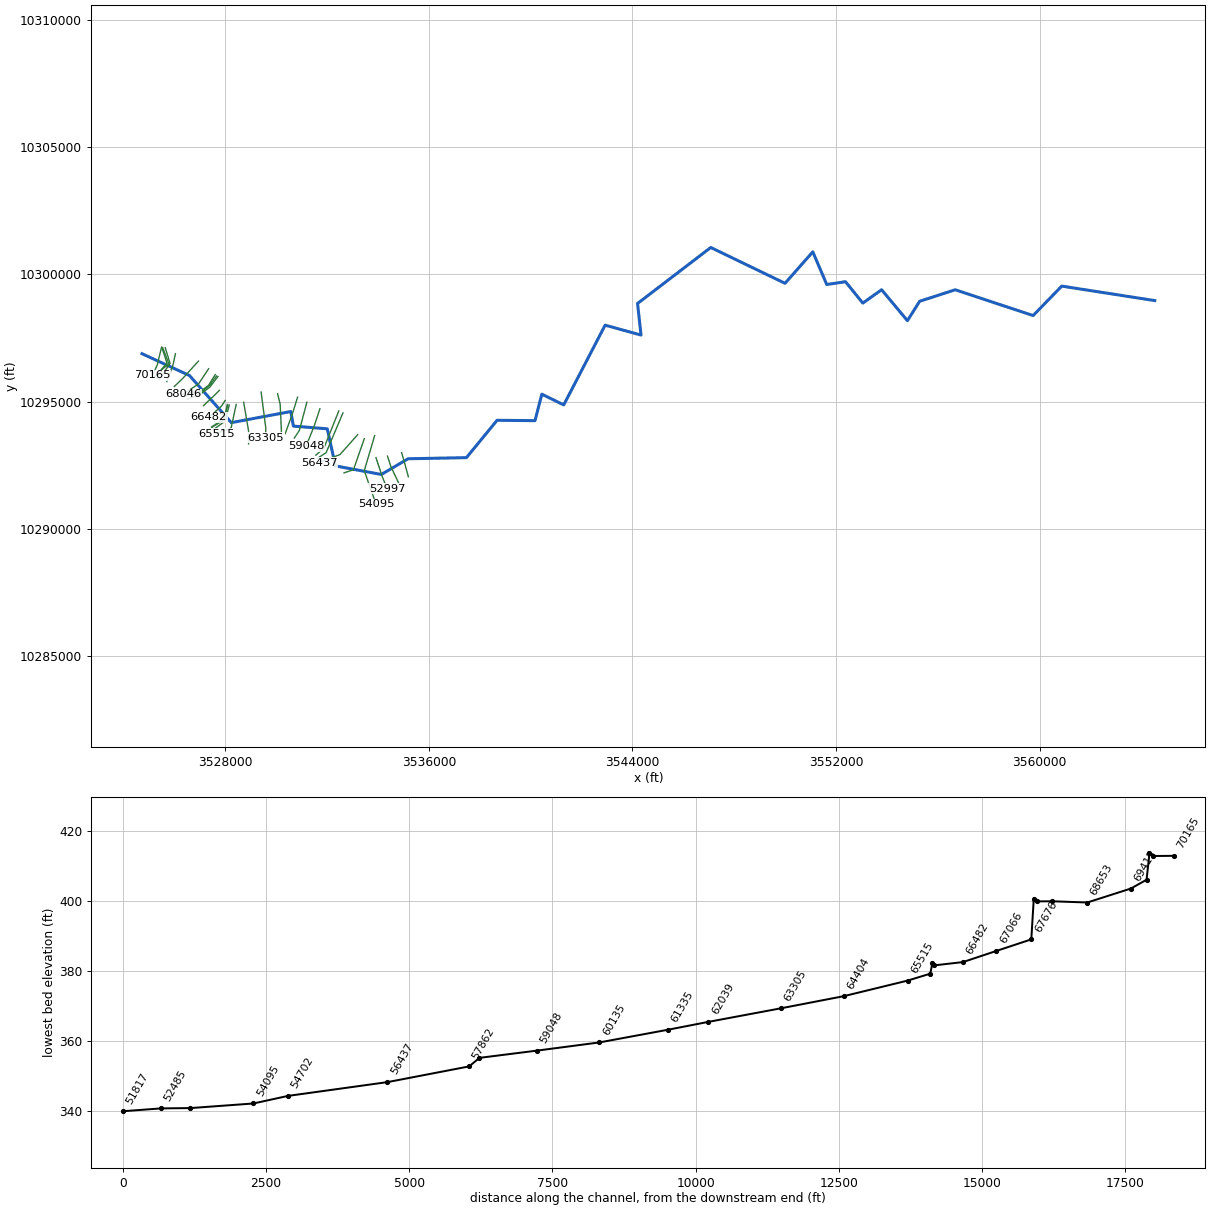
--- BEE CREEK.prj (project) ---

Proj Title=BEE CREEK Base Level Engineering
Current Plan=p01
Default Exp/Contr=0.3,0.1
English Units
Geom File=g01
Flow File=f01
Plan File=p01
Y Axis Title=Elevation
X Axis Title(PF)=Main Channel Distance
X Axis Title(XS)=Station
BEGIN DESCRIPTION:
BEE CREEK
END DESCRIPTION:
DSS Export Rating Curves= 0
DSS Export Rating Curve Sorted= 0
DSS Export Volume Flow Curves= 0
DXF OffsetX= 0
DXF OffsetY= 0
DXF ScaleX= 1
DXF ScaleY= 10

--- BEE CREEK.p01 (plan) ---

Plan Title=Multiple Run
Short Identifier=Multiple
Geom File=g01
Flow File=f01
Subcritical Flow
K Sum by GR= 0
Std Step Tol= 0.01
Critical Tol= 0.01
Num of Std Step Trials= 20
Max Error Tol= 0.3
Flow Tol Ratio= 0.001
Split Flow NTrial= 30
Split Flow Tol= 0.02
Split Flow Ratio= 0.02
Log Output Level= 0
Friction Slope Method= 1
Unsteady Friction Slope Method= 2
Unsteady Bridges Friction Slope Method= 1
Parabolic Critical Depth
Global Vel Dist=  1 , 1 , 1
Global Log Level= 0
CheckData=True
Encroach Param= -1, 0, 0, 0
BEGIN DESCRIPTION:
Multiple Run
END DESCRIPTION:

--- BEE CREEK.f01 (steady flow) ---

Flow Title=Multiple
Program Version=4.10
Number of Profiles= 7
Profile Names=10-year,25-year,50-year,1pct_min,100-year,1pct_plu,500-year
River Rch & RM=BEE CREEK,Reach-1         ,70165
     265     343     404     350     473     640     649
River Rch & RM=BEE CREEK,Reach-1         ,64404
     691     937    1137    1010    1366    1848    1978
River Rch & RM=BEE CREEK,Reach-1         ,54095
    1298    1818    2255    2043    2763    3737    4163
River Rch & RM=BEE CREEK,Reach-1         ,52997
    1298    1818    2255    2043    2763    3737    4163
River Rch & RM=BEE CREEK,Reach-1         ,48600
    1415    1988    2470    2241    3031    4099    4581
River Rch & RM=BEE CREEK,Reach-1         ,46201
    2368    3388    4263    3910    5287    7151    8166
River Rch & RM=BEE CREEK,Reach-1         ,37695
    2464    3530    4445    4080    5518    7462    8534
River Rch & RM=BEE CREEK,Reach-1         ,32767
    3094    4458    5638    5192    7022    9497   10934
River Rch & RM=BEE CREEK,Reach-1         ,28194
    3361    4844    6126    5640    7628   10316   11869
River Rch & RM=BEE CREEK,Reach-1         ,20400
    3522    5081    6431    5925    8013   10837   12485
River Rch & RM=BEE CREEK,Reach-1         ,18447
    3522    5081    6431    5925    8013   10837   12485
River Rch & RM=BEE CREEK,Reach-1         ,15833
    3641    5247    6637    6110    8263   11174   12851
River Rch & RM=BEE CREEK,Reach-1         ,8655
    3618    5201    6565    6031    8156   11031   12632
River Rch & RM=BEE CREEK,Reach-1         ,4552
    3650    5244    6618    6077    8219   11115   12720
Boundary for River Rch & Prof#=BEE CREEK,Reach-1         , 1
Up Type= 0
Dn Type= 3
Dn Slope=0.001
Boundary for River Rch & Prof#=BEE CREEK,Reach-1         , 2
Up Type= 0
Dn Type= 3
Dn Slope=0.001
Boundary for River Rch & Prof#=BEE CREEK,Reach-1         , 3
Up Type= 0
Dn Type= 3
Dn Slope=0.001
Boundary for River Rch & Prof#=BEE CREEK,Reach-1         , 4
Up Type= 0
Dn Type= 3
Dn Slope=0.001
Boundary for River Rch & Prof#=BEE CREEK,Reach-1         , 5
Up Type= 0
Dn Type= 3
Dn Slope=0.001
Boundary for River Rch & Prof#=BEE CREEK,Reach-1         , 6
Up Type= 0
Dn Type= 3
Dn Slope=0.001
Boundary for River Rch & Prof#=BEE CREEK,Reach-1         , 7
Up Type= 0
Dn Type= 3
Dn Slope=0.001
DSS Import GetInterval= 0
DSS Import GetPeak= 0
DSS Import FillOption= 0

--- BEE CREEK.g01 (geometry) ---

Geom Title=Existing Conditions
Program Version=4.10

River Reach=BEE CREEK       ,Reach-1
Reach XY= 30
      3524720.59     10296884.82      3526588.17      10296025.1
      3528234.69     10294171.12      3530570.55     10294608.73
      3530673.35     10294035.15      3532003.74     10293928.72
      3532326.16     10292469.66       3534129.3     10292132.74
      3535182.44     10292750.91      3537474.02     10292794.57
      3538678.36     10294264.03      3540168.76     10294249.28
       3540437.9     10295290.66      3541298.65     10294869.24
      3542925.49     10298005.32      3544335.29     10297616.15
      3544199.75     10298858.54      3547077.22     10301060.28
      3549995.78     10299651.41      3551087.75     10300889.74
      3551634.19     10299605.02      3552371.61      10299714.4
      3553053.02     10298872.57       3553790.9     10299398.51
      3554806.49     10298181.75      3555285.54     10298943.99
      3556683.77     10299397.91      3559745.94     10298382.72
      3560872.02     10299540.75      3564527.53     10298971.85

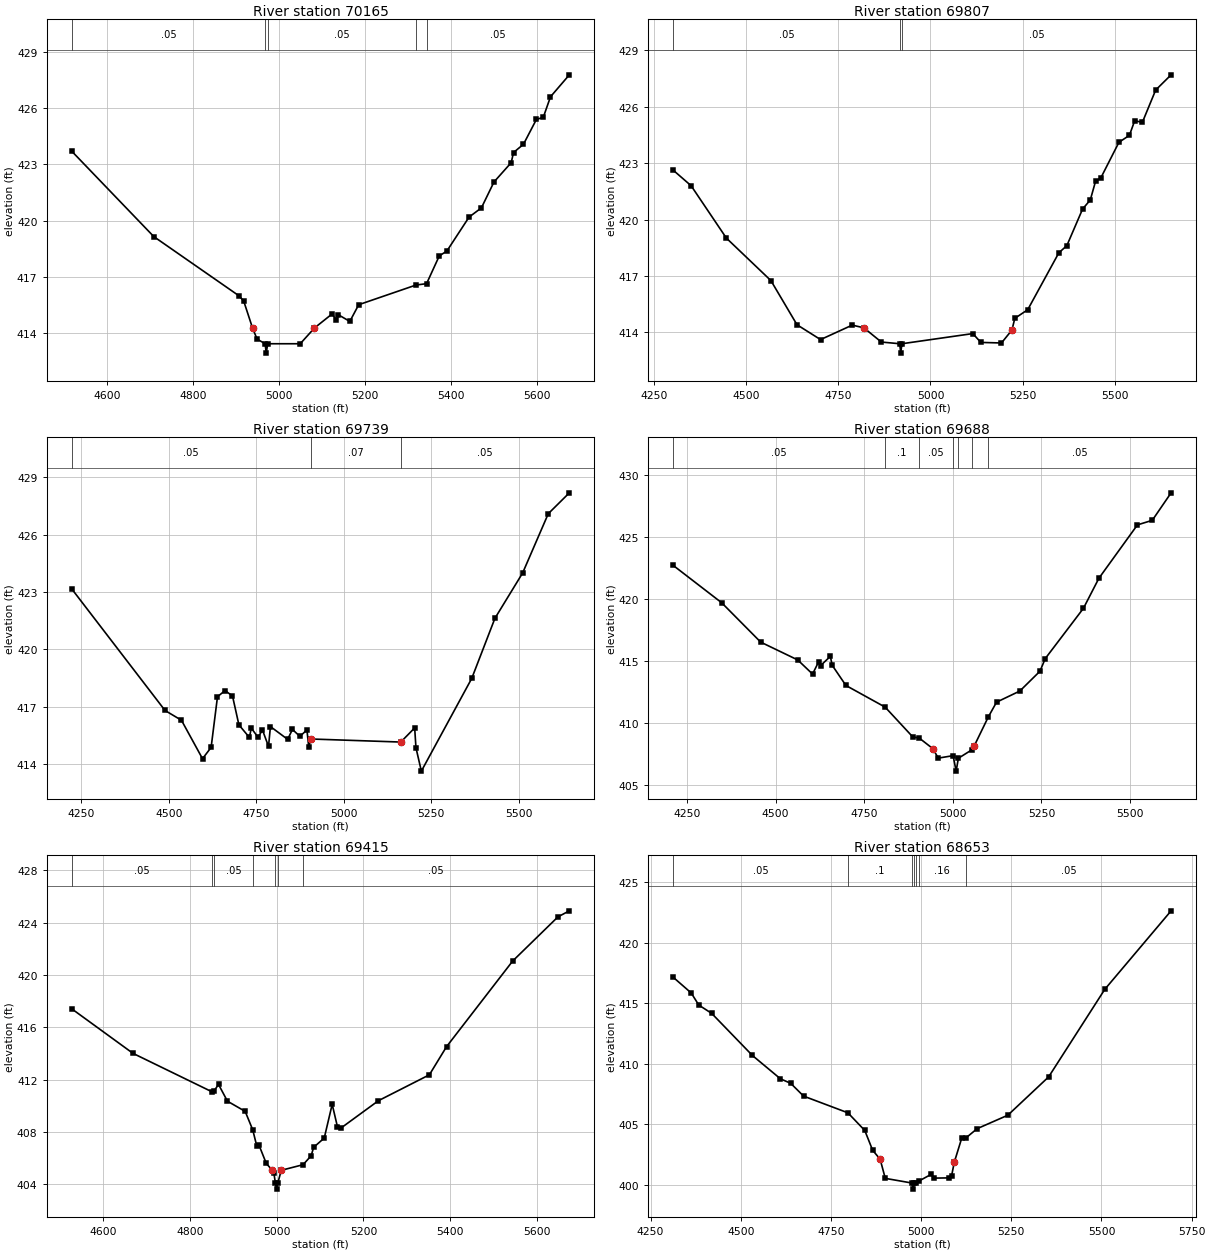
Type RM Length L Ch R = 1 ,70165   ,358,358,358
BEGIN DESCRIPTION:
BEE CREEK 80.0
END DESCRIPTION:
XS GIS Cut Line= 3
      3525492.11     10297141.68      3525325.72     10296448.91
      3525142.11     10296041.66
#Sta/Elev= 30
  4516.7  423.71  4708.2  419.15  4907.5  415.98  4917.8   415.7  4938.4  414.26
  4948.7  413.69  4967.4  413.44  4970.1  412.94  4973.4  413.44  5049.2  413.44
  5082.4  414.28  5123.5  415.03  5133.1   414.7  5138.3  414.98  5164.7  414.63
  5185.4  415.52    5319  416.57  5343.4  416.64    5373  418.12  5390.7  418.38
  5442.4  420.19  5471.1  420.68  5500.4  422.06  5540.5  423.09  5545.9  423.63
  5569.1  424.07  5599.1  425.39  5615.3  425.51    5632   426.6  5675.9  427.77
#Mann= 5 ,-1 , 0
  4516.7     .05       0  4967.4     .03       0  4973.4     .05       0
    5319      .1       0  5343.4     .05       0
Bank Sta=4938.4,5082.4
XS Rating Curve= 0 ,0
Exp/Cntr=0.3,0.1

Type RM Length L Ch R = 1 ,69807   ,68,68,68
BEGIN DESCRIPTION:
Mapping XS afbd6b0b
END DESCRIPTION:
XS GIS Cut Line= 3
      3525512.58     10297103.78      3525703.55     10296515.22
      3525222.68     10295961.44
#Sta/Elev= 30
  4301.4  422.62  4349.7   421.8  4445.6  419.01  4566.5  416.75  4637.4   414.4
  4701.4  413.61  4787.3  414.38  4818.8  414.24  4866.5  413.48  4916.4  413.39
  4919.2  412.89  4922.4  413.39    5115  413.93  5136.8  413.46  5192.8  413.43
  5221.3  414.12    5229  414.74  5264.1   415.2  5348.7  418.23  5370.4  418.61
  5413.2  420.56  5434.1  421.04  5448.3  422.03  5462.6  422.21  5511.9  424.11
  5540.4  424.48  5554.7  425.26  5575.5  425.17  5611.7  426.89  5653.6   427.7
#Mann= 3 ,-1 , 0
  4301.4     .05       0  4916.4     .03       0  4922.4     .05       0
Bank Sta=4818.8,5221.3
XS Rating Curve= 0 ,0
Exp/Cntr=0.3,0.1

Type RM Length L Ch R = 1 ,69739   ,51,51,51
BEGIN DESCRIPTION:
Mapping XS c8f87930
END DESCRIPTION:
XS GIS Cut Line= 5
      3525535.14     10297121.16      3525766.05      10296518.7
      3525743.48     10296440.57      3525540.36       10296293.
      3525305.96     10295914.49
#Sta/Elev= 30
  4222.3  423.17  4489.5   416.8  4536.4  416.29  4596.6  414.28  4621.2  414.87
  4639.4  417.52  4660.9  417.84  4682.3  417.56  4700.6  416.05  4730.6  415.39
    4736  415.88  4755.3   415.4    4768  415.78  4785.3  414.92  4790.7  415.96
    4840  415.29  4853.6  415.81  4874.8  415.45  4895.1  415.78  4900.3  414.88
  4906.1  415.31  5163.3  415.15    5203  415.89  5206.7  414.85  5222.1  413.63
  5366.2  418.48  5432.4  421.62  5511.6  423.99  5584.9  427.09  5645.1  428.18
#Mann= 3 , 0 , 0
  4222.3     .05       0  4906.1     .07       0  5163.3     .05       0
Bank Sta=4906.1,5163.3
XS Rating Curve= 0 ,0
Exp/Cntr=0.3,0.1

Type RM Length L Ch R = 1 ,69688   ,273,273,273
BEGIN DESCRIPTION:
Mapping XS e79f6d99
END DESCRIPTION:
XS GIS Cut Line= 3
      3525637.58     10297117.65      3525825.08      10296499.6
      3525396.69     10295873.49
#Sta/Elev= 30
  4211.3  422.73  4347.8  419.72  4457.9  416.54  4562.4   415.1  4604.2  413.96
  4621.5  414.96  4626.7  414.64  4654.4  415.39  4659.6  414.67  4698.3  413.04
    4809  411.29    4887  408.88  4904.8   408.8  4943.8  407.93  4958.8  407.17
  5000.7  407.37  5009.3  406.12  5015.6  407.16  5054.1  407.85  5060.4  408.16
  5100.1   410.5  5123.3  411.69    5189  412.59  5245.8  414.19  5260.7  415.21
  5368.4  419.27  5412.1   421.7  5520.8  426.01  5562.7  426.38  5615.8   428.6
#Mann= 7 ,-1 , 0
  4211.3     .05       0    4809      .1       0  4904.8     .05       0
  5000.7     .03       0  5015.6     .05       0  5054.1      .1       0
  5100.1     .05       0
Bank Sta=4943.8,5060.4
XS Rating Curve= 0 ,0
Exp/Cntr=0.3,0.1

Type RM Length L Ch R = 1 ,69415   ,762,762,762
BEGIN DESCRIPTION:
BEE CREEK 79.0
END DESCRIPTION:
XS GIS Cut Line= 3
      3526037.52     10296882.91      3525942.11     10296441.64
        3525699.     10295789.23
#Sta/Elev= 30
    4527  417.42  4668.7     414  4850.7  411.06    4856  411.15  4865.9  411.62
  4886.4  410.34  4927.3  409.56  4944.8  408.14  4953.8  406.94    4959  406.99
  4975.9  405.58  4988.3  405.11  4993.6  404.81  4996.8  404.11  4999.6  403.61
  5002.8  404.11  5010.5  405.05  5060.8  405.48  5079.3  406.16  5085.2  406.81
  5109.6  407.52  5127.9   410.1  5139.9   408.4  5149.2  408.31  5234.6  410.38
    5352  412.36  5391.5  414.51  5544.1  421.07  5648.5  424.45  5674.7  424.91
#Mann= 7 ,-1 , 0
    4527     .05       0  4850.7      .1       0    4856     .05       0
  4944.8      .1       0  4996.8     .07       0  5002.8      .1       0
  5060.8     .05       0
Bank Sta=4988.3,5010.5
XS Rating Curve= 0 ,0
Exp/Cntr=0.3,0.1

Type RM Length L Ch R = 1 ,68653   ,607,607,607
BEGIN DESCRIPTION:
BEE CREEK 77.0
END DESCRIPTION:
XS GIS Cut Line= 3
      3526942.08     10296591.62      3526332.67      10295919.4
       3525992.1     10295591.64
#Sta/Elev= 30
    4313  417.13  4362.6  415.84  4383.6  414.84  4419.4  414.15  4532.3  410.67
    4610  408.74  4638.4  408.37  4674.2  407.31    4797  405.93  4843.8  404.47
  4865.5  402.84  4886.4  402.09  4900.6  400.51  4975.3  400.12  4978.1  399.62
  4981.3  400.12  4986.5  400.15  4993.4  400.28  5028.3  400.85  5035.1  400.53
  5077.7  400.55  5084.4  400.71  5091.9  401.84  5112.8  403.86    5124  403.85
  5155.4  404.62  5240.3  405.73  5353.5   408.9  5509.2  416.14    5693  422.63
#Mann= 7 ,-1 , 0
    4313     .05       0    4797      .1       0  4975.3     .07       0
  4981.3      .1       0  4986.5     .07       0  4993.4     .16       0
    5124     .05       0
Bank Sta=4886.4,5091.9
XS Rating Curve= 0 ,0
Exp/Cntr=0.3,0.1

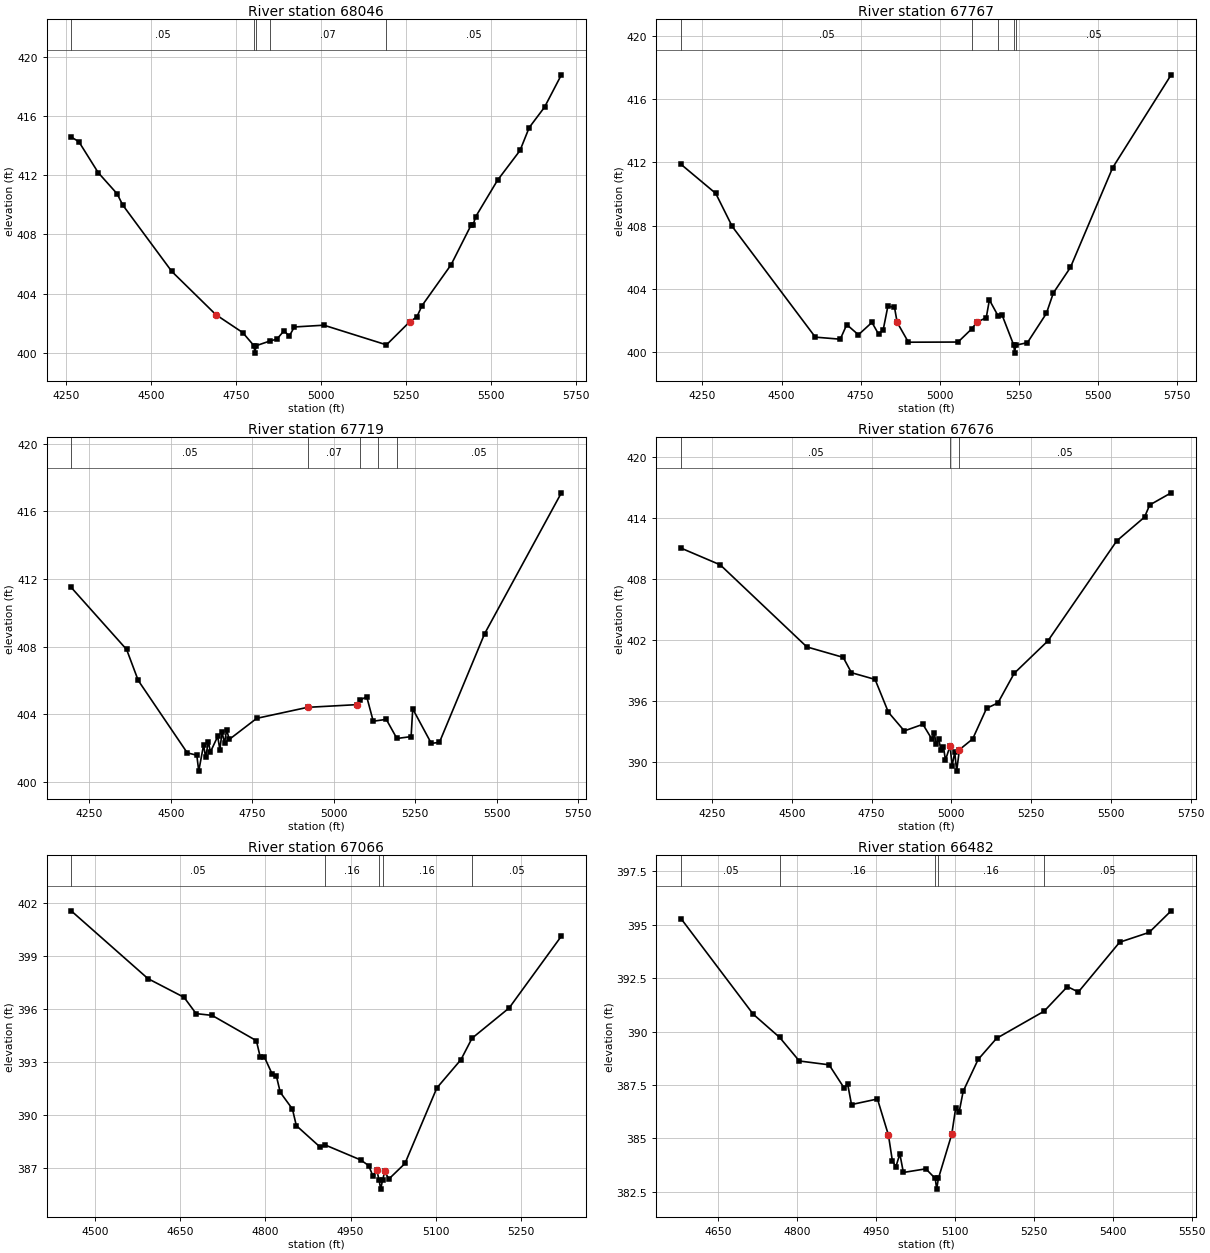
Type RM Length L Ch R = 1 ,68046   ,279,279,279
BEGIN DESCRIPTION:
BEE CREEK 76.0
END DESCRIPTION:
XS GIS Cut Line= 3
      3527342.09     10296291.62      3526942.11     10295691.64
       3526342.1     10295291.64
#Sta/Elev= 30
    4266  414.59  4288.5  414.28  4345.6  412.18  4401.2  410.75  4417.7  409.99
  4561.9   405.5 4691.82  402.57  4770.7  401.36  4803.8  400.47  4806.6  399.97
  4809.8  400.47  4850.7  400.79  4871.4  400.92  4892.4  401.49  4907.5  401.11
  4922.5  401.74  5009.6  401.86  5193.6  400.53    5262  402.09    5283  402.42
  5298.1  403.18  5383.7  405.95  5442.3  408.62  5448.3  408.63  5455.8  409.19
  5520.4  411.67  5586.5  413.68  5613.5  415.23  5658.6  416.61  5708.2   418.8
#Mann= 5 ,-1 , 0
    4266     .05       0  4803.8     .07       0  4809.8     .05       0
  4850.7     .07       0  5193.6     .05       0
Bank Sta=4691.82,5262
XS Rating Curve= 0 ,0
Exp/Cntr=0.3,0.1

Type RM Length L Ch R = 1 ,67767   ,48,48,48
BEGIN DESCRIPTION:
Mapping XS 05f20256
END DESCRIPTION:
XS GIS Cut Line= 5
      3527602.37     10296064.24      3527337.63     10295634.58
      3527020.79     10295404.55      3526747.35     10295398.04
      3526404.45     10295235.27
#Sta/Elev= 30
  4182.1  411.87  4292.1  410.03  4344.2  407.94  4606.8  400.95  4685.6  400.82
  4706.2  401.74    4743   401.1  4785.8  401.88  4806.7  401.14  4821.4  401.42
  4836.1   402.9    4857  402.84  4865.5  401.88    4901  400.63  5057.9  400.64
  5101.5  401.48    5117  401.89    5147  402.18    5157   403.3    5184  402.31
    5197  402.35    5234  400.44  5236.8  399.94    5240  400.44  5277.1   400.6
  5337.1  402.45  5359.1  403.74    5413  405.35  5546.5  411.65  5731.4  417.52
#Mann= 5 ,-1 , 0
  4182.1     .05       0  5101.5     .07       0    5184     .05       0
    5234    .033       0    5240     .05       0
Bank Sta=4865.5,5117
XS Rating Curve= 0 ,0
Exp/Cntr=0.3,0.1

Type RM Length L Ch R = 1 ,67719   ,43,43,43
BEGIN DESCRIPTION:
Mapping XS f62263c2
END DESCRIPTION:
XS GIS Cut Line= 5
      3527647.97     10296003.52      3527385.38     10295645.43
      3527070.71     10295376.33      3526821.14     10295363.31
      3526453.37      10295216.2
#Sta/Elev= 30
  4194.2  411.51  4364.3  407.84  4399.9  406.01  4550.4  401.73  4579.7  401.59
  4585.6  400.65  4600.5   402.2  4606.7  401.46  4615.2   402.4  4621.4  401.78
  4643.7   402.7  4650.5  401.92    4657  402.95  4664.7  402.31  4671.3  403.11
    4679  402.52  4763.5  403.77  4919.4  404.42  5070.9  404.58  5080.9  404.85
    5101  405.05    5121   403.6    5161  403.71  5193.6  402.58  5237.2  402.69
  5242.2  404.33  5299.2  402.29  5324.1  402.35  5462.7  408.77  5698.3   417.1
#Mann= 5 ,-1 , 0
  4194.2     .05       0  4919.4     .07       0  5080.9     .05       0
  5136.6     .07       0  5193.6     .05       0
Bank Sta=4919.4,5070.9
XS Rating Curve= 0 ,0
Exp/Cntr=0.3,0.1

Type RM Length L Ch R = 1 ,67676   ,610,610,610
BEGIN DESCRIPTION:
Mapping XS f0c07bc1
END DESCRIPTION:
XS GIS Cut Line= 4
       3527710.9     10295986.14      3527381.04      10295560.8
      3527001.26     10295274.34      3526508.64     10295098.56
#Sta/Elev= 30
  4152.2  411.06  4275.4  409.41  4546.9  401.33    4661   400.3  4686.8  398.79
  4760.9  398.13  4802.6   394.9  4852.5  393.06  4910.8  393.71  4939.6  392.22
  4946.2  392.89  4952.4   391.8  4960.7  392.24    4967   391.2  4975.3  391.48
  4981.6  390.19  4996.1  391.59  5002.4  389.62  5010.7  390.96  5016.7   389.1
  5025.3  391.21  5066.9  392.27  5110.6  395.29    5146  395.81  5197.1  398.73
    5303  401.93  5518.7  411.77  5605.8  414.11  5621.8   415.3  5689.2   416.5
#Mann= 3 , 0 , 0
  4152.2     .05       0  4996.1    .035       0  5025.3     .05       0
Bank Sta=4996.1,5025.3
XS Rating Curve= 0 ,0
Exp/Cntr=0.3,0.1

Type RM Length L Ch R = 1 ,67066   ,584,584,584
BEGIN DESCRIPTION:
BEE CREEK 74.0
END DESCRIPTION:
XS GIS Cut Line= 3
      3527763.65     10295441.31      3527563.63      10295241.3
      3527142.13     10294841.67
#Sta/Elev= 30
  4457.7  401.53  4592.9   397.7  4656.6  396.64  4677.8  395.72    4706  395.62
    4784  394.19  4790.9  393.25  4797.8  393.29    4812  392.29  4819.2   392.2
  4826.1  391.27  4847.5  390.33  4854.4  389.39  4896.9  388.16  4904.2  388.31
  4967.7  387.45  4981.9  387.13  4989.1  386.56    4996  386.89  5000.3   386.3
    5003   385.8  5006.3   386.3  5010.2   386.8  5017.4  386.37  5045.8  387.25
    5102  391.52  5144.5  393.12    5164  394.33  5229.4  396.04  5321.4   400.1
#Mann= 5 ,-1 , 0
  4457.7     .05       0  4904.2     .16       0  5000.3     .07       0
  5006.3     .16       0    5164     .05       0
Bank Sta=4996,5010.2
XS Rating Curve= 0 ,0
Exp/Cntr=0.3,0.1

Type RM Length L Ch R = 1 ,66482   ,512,512,512
BEGIN DESCRIPTION:
BEE CREEK 73.0
END DESCRIPTION:
XS GIS Cut Line= 3
      3527992.11     10295041.64      3527851.77     10294825.65
      3527349.62     10294375.44
#Sta/Elev= 30
    4579  395.29  4716.4  390.81  4766.8  389.72    4804  388.62  4860.7  388.44
  4889.1  387.36  4895.8  387.56  4903.3  386.58  4952.6  386.84  4973.5  385.15
    4981  383.94  4987.7  383.67  4995.2  384.27  5001.9   383.4  5044.6  383.57
  5062.5  383.12  5065.2  382.62  5068.5  383.12  5093.9  385.19  5101.4  386.42
  5108.1  386.25  5115.6   387.2    5144  388.69  5179.1  389.68  5269.5  390.95
  5313.7   392.1  5334.6  391.85  5413.1  394.18  5469.2  394.64    5511  395.65
#Mann= 5 ,-1 , 0
    4579     .05       0  4766.8     .16       0  5062.5     .07       0
  5068.5     .16       0  5269.5     .05       0
Bank Sta=4973.5,5093.9
XS Rating Curve= 0 ,0
Exp/Cntr=0.3,0.1

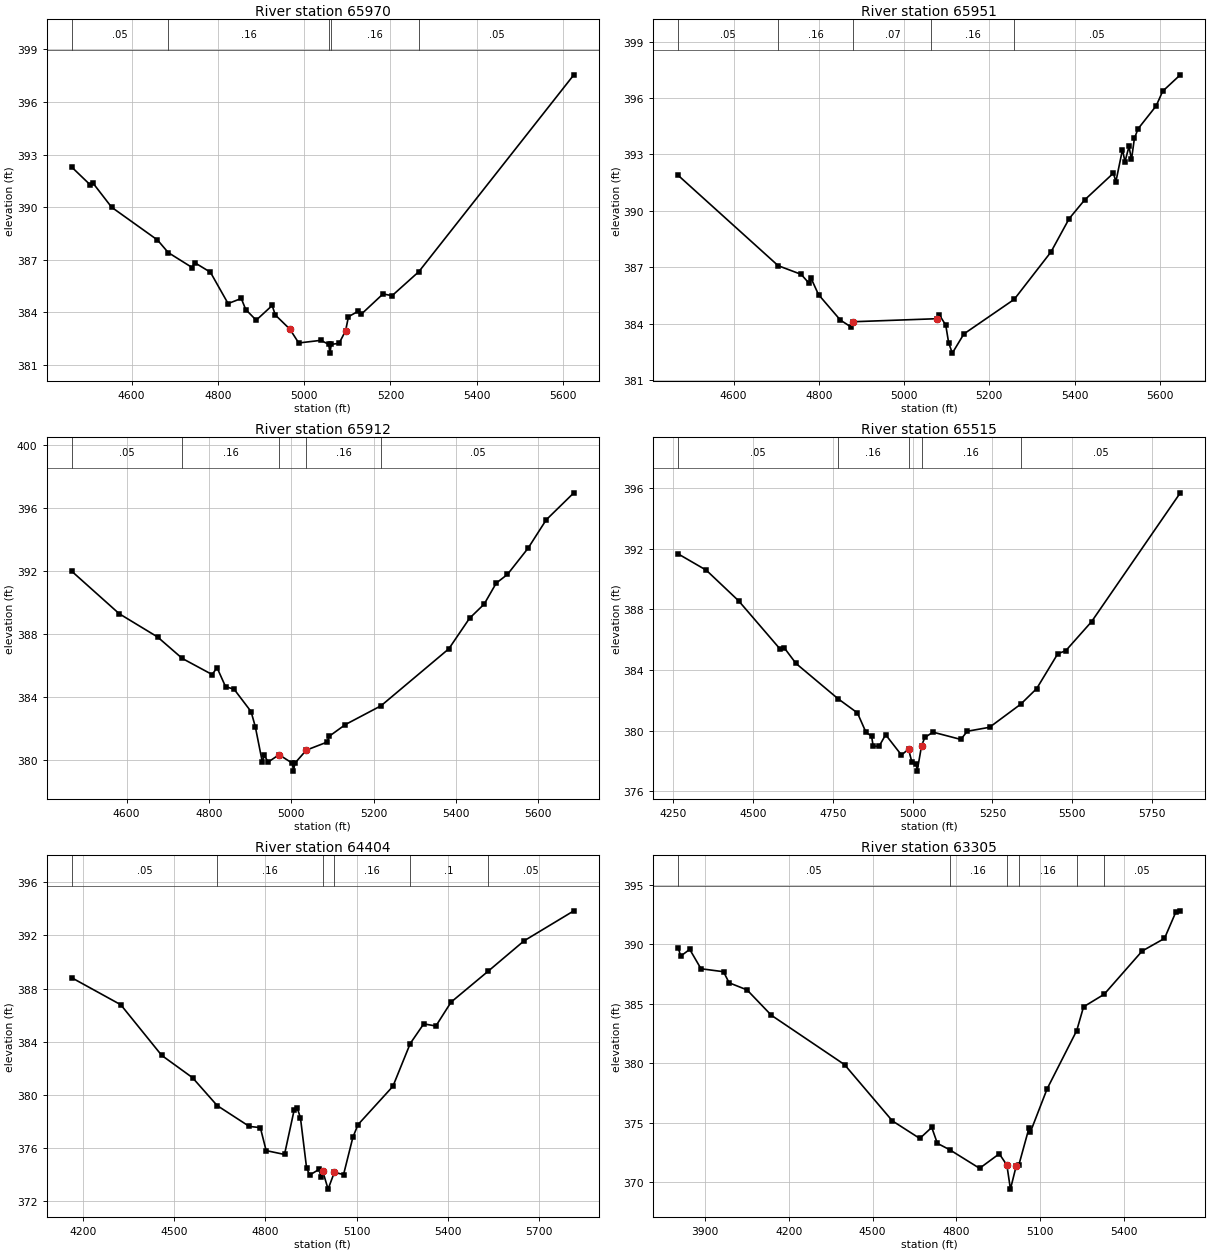
Type RM Length L Ch R = 1 ,65970   ,19,19,19
BEGIN DESCRIPTION:
Mapping XS 5753e84d
END DESCRIPTION:
XS GIS Cut Line= 3
      3528076.78     10294885.89      3527958.73     10294337.27
      3527458.75     10294000.49
#Sta/Elev= 30
  4461.3  392.28  4504.4  391.26  4509.5   391.4  4553.7  389.99    4660  388.12
    4685   387.4  4740.8  386.54    4746  386.83  4782.7  386.28  4823.7  384.49
  4854.3  384.78  4864.6  384.15  4888.9  383.54  4925.9  384.38  4933.1  383.84
  4966.9  383.03  4987.5  382.24    5039  382.39    5057  382.16  5059.8  381.66
    5063  382.16    5081  382.22    5096  382.93  5102.8  383.74  5125.9  384.06
    5132  383.87  5182.9  385.04  5203.9  384.94  5265.9  386.31  5625.3  397.55
#Mann= 5 ,-1 , 0
  4461.3     .05       0    4685     .16       0    5057     .07       0
    5063     .16       0  5265.9     .05       0
Bank Sta=4966.9,5096
XS Rating Curve= 0 ,0
Exp/Cntr=0.3,0.1

Type RM Length L Ch R = 1 ,65951   ,39,39,39
BEGIN DESCRIPTION:
Mapping XS 9fc5b18a
END DESCRIPTION:
XS GIS Cut Line= 3
      3528090.66      10294873.7      3527969.14     10294295.61
      3527470.61     10293985.75
#Sta/Elev= 30
  4470.3  391.88  4704.7  387.08  4758.5  386.62  4776.6  386.16  4781.7  386.42
  4799.4  385.54  4850.5  384.19  4876.3  383.81  4881.4   384.1  5076.6  384.26
  5082.5  384.47  5097.8  383.92  5104.6  382.98  5113.2  382.43  5140.3  383.45
  5258.4  385.29  5344.6  387.81  5387.2  389.58  5423.7  390.58    5491     392
  5496.9  391.55  5512.3  393.25  5518.2  392.61  5527.6  393.42  5533.5  392.73
  5540.3  393.85  5548.9  394.36  5591.4  395.58  5606.7  396.36    5648  397.23
#Mann= 5 ,-1 , 0
  4470.3     .05       0  4704.7     .16       0  4881.4     .07       0
  5063.5     .16       0  5258.4     .05       0
Bank Sta=4881.4,5076.6
XS Rating Curve= 0 ,0
Exp/Cntr=0.3,0.1

Type RM Length L Ch R = 1 ,65912   ,397,397,397
BEGIN DESCRIPTION:
Mapping XS 1555be20
END DESCRIPTION:
XS GIS Cut Line= 3
      3528153.16     10294863.29      3527989.98     10294231.37
      3527531.63     10293898.02
#Sta/Elev= 30
  4466.9  391.97  4582.2  389.28  4675.2  387.81  4735.2  386.45  4807.7  385.43
  4819.8  385.86  4840.4  384.66  4861.1   384.5  4902.4  383.08  4912.7  382.12
  4929.6   379.9  4934.8  380.31  4943.7  379.88  4970.3  380.35  5002.7  379.81
  5005.4  379.31  5008.7  379.81  5036.6  380.64  5087.1  381.15  5092.2  381.52
  5131.5  382.26    5218  383.45  5382.7  387.06  5432.9  388.99  5468.5  389.89
  5497.8  391.22    5525  391.77  5575.1  393.43  5619.2  395.23  5686.3  396.94
#Mann= 5 ,-1 , 0
  4466.9     .05       0  4735.2     .16       0  4970.3     .07       0
  5036.6     .16       0    5218     .05       0
Bank Sta=4970.3,5036.6
XS Rating Curve= 0 ,0
Exp/Cntr=0.3,0.1

Type RM Length L Ch R = 1 ,65515   ,1111,1111,1111
BEGIN DESCRIPTION:
BEE CREEK 71.0
END DESCRIPTION:
XS GIS Cut Line= 3
      3528424.69     10294886.42      3528225.03     10293957.59
      3527642.09     10293741.64
#Sta/Elev= 30
  4266.5  391.65  4354.2  390.58  4455.5  388.56  4585.7  385.37  4598.7  385.45
  4635.1  384.43  4766.9   382.1  4827.4  381.17  4854.4  379.88  4871.7  379.64
  4876.8  378.97  4895.3  378.97  4915.8  379.73  4965.3  378.39  4987.4  378.78
  4997.6  377.95  5011.6  377.83  5014.4  377.33  5028.3  379.01  5038.5  379.55
    5064   379.9    5151  379.42  5171.5  379.96    5241  380.22  5338.4  381.74
  5388.5  382.77  5454.6  385.07  5479.6  385.27  5560.2  387.18  5838.2  395.68
#Mann= 5 ,-1 , 0
  4266.5     .05       0  4766.9     .16       0  4987.4     .07       0
  5028.3     .16       0  5338.4     .05       0
Bank Sta=4987.4,5028.3
XS Rating Curve= 0 ,0
Exp/Cntr=0.3,0.1

Type RM Length L Ch R = 1 ,64404   ,1099,1099,1099
BEGIN DESCRIPTION:
BEE CREEK 70.0
END DESCRIPTION:
XS GIS Cut Line= 3
      3528719.81     10294973.26       3528911.9     10293837.82
       3528911.9     10293337.79
#Sta/Elev= 30
    4163  388.81  4324.2  386.78  4458.8  382.97  4560.2  381.29  4641.3  379.19
    4747  377.62  4783.3  377.53  4802.4   375.8  4862.8  375.51  4894.9  378.89
    4905  378.98  4915.2  378.28  4935.4   374.5  4945.6  373.96    4976  374.38
  4983.6  373.81  4988.7  374.24  5006.2   372.9  5026.7  374.16  5057.1     374
  5087.6  376.79  5104.4  377.75  5219.4  380.64  5276.4  383.86  5320.8  385.34
  5360.8  385.18  5410.8  386.98    5533  389.31  5650.8  391.59  5814.6  393.85
#Mann= 6 ,-1 , 0
    4163     .05       0  4641.3     .16       0  4988.7     .07       0
  5026.7     .16       0  5276.4      .1       0    5533     .05       0
#XS Ineff= 2 , 0
         4895.45  378.82
Permanent Ineff=
       F       F
Bank Sta=4988.7,5026.7
XS Rating Curve= 0 ,0
Exp/Cntr=0.3,0.1

Type RM Length L Ch R = 1 ,63305   ,1266,1266,1266
BEGIN DESCRIPTION:
BEE CREEK 68.0
END DESCRIPTION:
XS GIS Cut Line= 3
      3529405.59     10295372.48      3529585.51     10293983.31
      3529585.51     10293584.98
#Sta/Elev= 30
  3803.6  389.72  3812.4  389.02  3844.8  389.59  3885.1  387.96  3965.8  387.71
  3985.9  386.78  4050.2  386.18  4137.2  384.05  4399.4   379.9  4570.8  375.17
  4669.2  373.69    4712  374.62  4732.1  373.28  4776.5  372.74  4883.4  371.18
    4954   372.4  4981.2  371.45    4994  369.43  5014.5  371.36  5024.5  371.49
  5060.5  374.57  5065.5  374.23  5125.4  377.86  5231.5  382.76    5256  384.76
  5329.7  385.81    5466  389.45    5546  390.51    5586  392.69  5602.7  392.83
#Mann= 6 ,-1 , 0
  3803.6     .05       0  4776.5     .16       0  4981.2     .07       0
  5024.5     .16       0  5231.5      .1       0  5329.7     .05       0
Bank Sta=4981.2,5014.5
XS Rating Curve= 0 ,0
Exp/Cntr=0.3,0.1

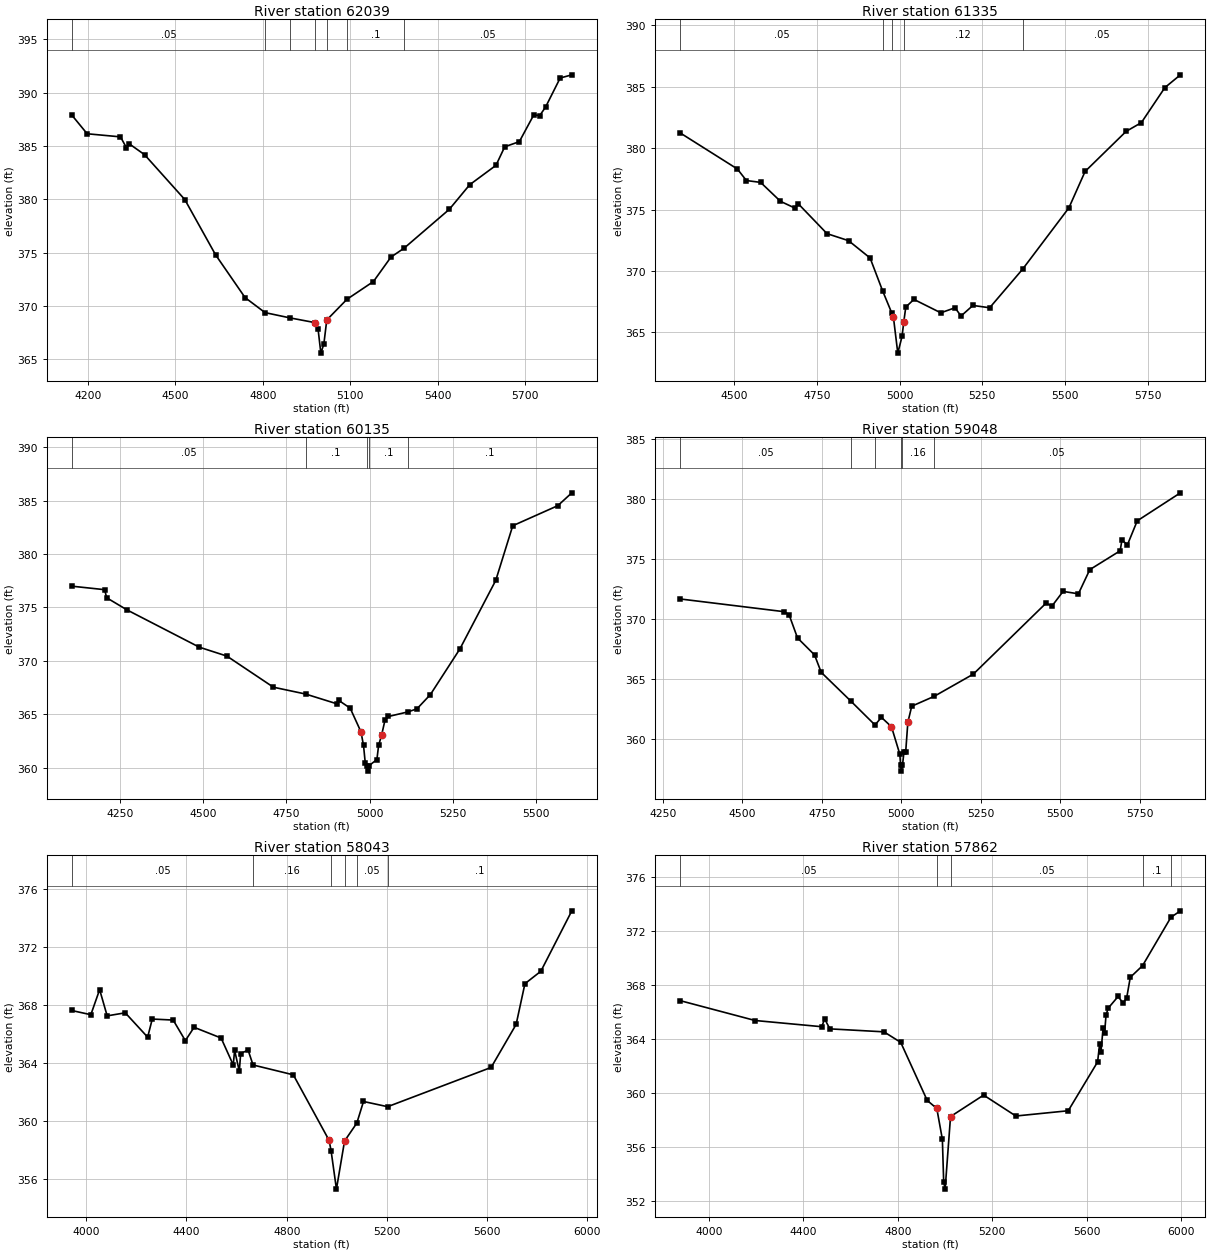
Type RM Length L Ch R = 1 ,62039   ,704,704,704
BEGIN DESCRIPTION:
BEE CREEK 66.0
END DESCRIPTION:
XS GIS Cut Line= 3
      3530053.22     10295304.14      3530153.22     10294904.14
      3530212.88     10293601.72
#Sta/Elev= 30
  4144.5  387.91  4197.6  386.14    4312  385.85  4332.6  384.82  4342.9  385.18
  4394.5  384.18  4532.6  379.97  4638.1  374.79  4739.5  370.77  4808.1  369.36
  4892.8  368.87  4979.8  368.42  4989.8  367.84  4999.5  365.56  5009.8  366.42
  5019.8  368.67    5089  370.61    5180  372.28    5240  374.57  5285.3  375.41
  5440.2  379.05  5510.3  381.36  5600.4  383.18  5630.4  384.92  5680.5   385.4
    5730  387.91  5750.6  387.85  5770.6  388.65  5820.6  391.37  5860.6  391.67
#Mann= 7 ,-1 , 0
  4144.5     .05       0  4808.1     .16       0  4892.8     .05       0
  4979.8     .07       0  5019.8     .05       0    5089      .1       0
  5285.3     .05       0
Bank Sta=4979.8,5019.8
XS Rating Curve= 0 ,0
Exp/Cntr=0.3,0.1

Type RM Length L Ch R = 1 ,61335   ,1200,1200,1200
BEGIN DESCRIPTION:
BEE CREEK 65.0
END DESCRIPTION:
XS GIS Cut Line= 3
      3530837.88     10295172.87      3530642.11     10294541.64
      3530351.78     10293740.62
#Sta/Elev= 30
  4336.6  381.23  4509.3   378.3  4536.7  377.36  4579.7  377.21  4639.7  375.67
  4683.4  375.12  4693.9  375.46  4780.5  373.04  4845.6  372.47  4910.8  371.06
  4949.1  368.36    4976  366.61  4981.2  366.29  4994.6  363.32  5007.5  364.68
  5012.8  365.88  5018.8  367.07  5043.4  367.69  5124.7   366.6  5167.7  367.01
  5185.9  366.34  5221.9   367.2  5272.5  367.01  5372.2  370.15  5512.2  375.14
  5561.2   378.1  5685.3  381.36  5731.4  382.07  5802.5  384.92  5849.5  385.96
#Mann= 5 ,-1 , 0
  4336.6     .05       0  4949.1     .12       0    4976     .07       0
  5012.8     .12       0  5372.2     .05       0
Bank Sta=4981.2,5012.8
XS Rating Curve= 0 ,0
Exp/Cntr=0.3,0.1

Type RM Length L Ch R = 1 ,60135   ,1087,1087,1087
BEGIN DESCRIPTION:
BEE CREEK 64.0
END DESCRIPTION:
XS GIS Cut Line= 3
      3531202.45     10294973.18      3530909.47     10293865.95
       3530709.9     10293566.61
#Sta/Elev= 30
  4103.7  376.99  4203.2  376.66  4208.7  375.91  4270.8  374.76    4488  371.28
  4570.8  370.45  4710.7  367.54  4807.7   366.9  4901.5  365.99  4906.7  366.32
  4941.8  365.58  4974.2  363.37    4982  362.09  4987.2  360.44  4991.9  360.19
  4994.6  359.69  4997.9  360.19  5022.2  360.77  5027.4   362.1  5036.3  363.05
  5046.6  364.46  5056.9   364.8  5115.7  365.23  5142.9  365.52  5183.2  366.85
  5271.8  371.11  5379.9  377.53    5431  382.64  5566.7  384.52  5608.8  385.72
#Mann= 5 ,-1 , 0
  4103.7     .05       0  4807.7      .1       0  4991.9     .07       0
  4997.9      .1       0  5115.7      .1       0
Bank Sta=4974.2,5036.3
XS Rating Curve= 0 ,0
Exp/Cntr=0.3,0.1

Type RM Length L Ch R = 1 ,59048   ,1005,1005,1005
BEGIN DESCRIPTION:
BEE CREEK 62.0
END DESCRIPTION:
XS GIS Cut Line= 3
      3531714.62     10294712.82      3531492.11     10294041.64
      3531167.73     10293237.08
#Sta/Elev= 30
  4304.1  371.68  4631.9  370.62  4646.8  370.36  4673.2  368.44  4726.8  367.03
  4747.8  365.58  4841.3  363.18  4917.1   361.2  4937.5  361.83  4969.1  361.05
  4995.4  358.76  4997.7  357.86  5000.4  357.36  5003.7  357.86  5008.6  358.99
  5013.9  358.99  5020.6  361.42  5032.8  362.76  5103.4  363.58  5226.8  365.43
  5455.6  371.33  5474.3  371.09  5509.3  372.31  5557.6  372.11  5593.4  374.12
  5689.1  375.69  5694.5  376.58    5712  376.19  5742.8  378.18  5878.7  380.51
#Mann= 6 ,-1 , 0
  4304.1     .05       0  4841.3      .1       0  4917.1     .16       0
  4997.7     .07       0  5003.7     .16       0  5103.4     .05       0
Bank Sta=4969.1,5020.6
XS Rating Curve= 0 ,0
Exp/Cntr=0.3,0.1

Type RM Length L Ch R = 1 ,58043   ,181,181,181
BEGIN DESCRIPTION:
BEE CREEK 60.0
END DESCRIPTION:
XS GIS Cut Line= 3
      3532457.28     10294633.27      3531871.34     10293166.26
       3531555.8     10292893.94
#Sta/Elev= 30
  3941.7  367.62  4018.2  367.33  4053.3  369.06  4083.4  367.25  4155.6  367.46
    4245  365.78  4263.4  367.03  4346.9  366.96  4395.4  365.54  4430.4  366.46
  4538.2  365.72  4586.7  363.86  4592.1  364.87  4610.9  363.43  4616.3  364.65
  4645.9  364.89  4665.7  363.86  4826.4  363.18  4969.2  358.66  4977.2  357.94
  4998.6  355.29    5031  358.61    5080  359.85  5106.6  361.34    5203  360.98
  5616.1  363.69  5715.9  366.66    5751  369.47  5814.6  370.33  5938.2   374.5
#Mann= 6 ,-1 , 0
  3941.7     .05       0  4665.7     .16       0  4977.2     .07       0
    5031     .16       0    5080     .05       0    5203      .1       0
Bank Sta=4969.2,5031
XS Rating Curve= 0 ,0
Exp/Cntr=0.3,0.1

Type RM Length L Ch R = 1 ,57862   ,1425,1425,1425
BEGIN DESCRIPTION:
Mapping XS 74866808
END DESCRIPTION:
XS GIS Cut Line= 3
      3532622.22     10294555.18      3531958.15     10292988.31
      3531606.88     10292762.81
#Sta/Elev= 30
  3878.3  366.82  4195.3  365.35  4477.4  364.89  4490.4  365.46  4512.1  364.73
  4741.3  364.51  4812.4  363.73  4924.8  359.42  4965.3  358.83  4988.9  356.54
  4994.4  353.41  5000.6  352.85  5023.5  358.23  5163.7  359.82  5300.2  358.27
  5522.2  358.66  5646.7  362.28  5654.9  363.58  5660.9  363.03  5670.1  364.83
  5676.1  364.39  5682.3  365.74  5691.3  366.26  5733.5  367.13  5754.7  366.64
  5769.9  367.03  5785.1  368.55  5836.9  369.41  5957.3     373  5997.5  373.48
#Mann= 5 ,-1 , 0
  3878.3     .05       0  4965.3     .07       0  5023.5     .05       0
  5836.9      .1       0  5957.3     .05       0
Bank Sta=4965.3,5023.5
XS Rating Curve= 0 ,0
Exp/Cntr=0.3,0.1

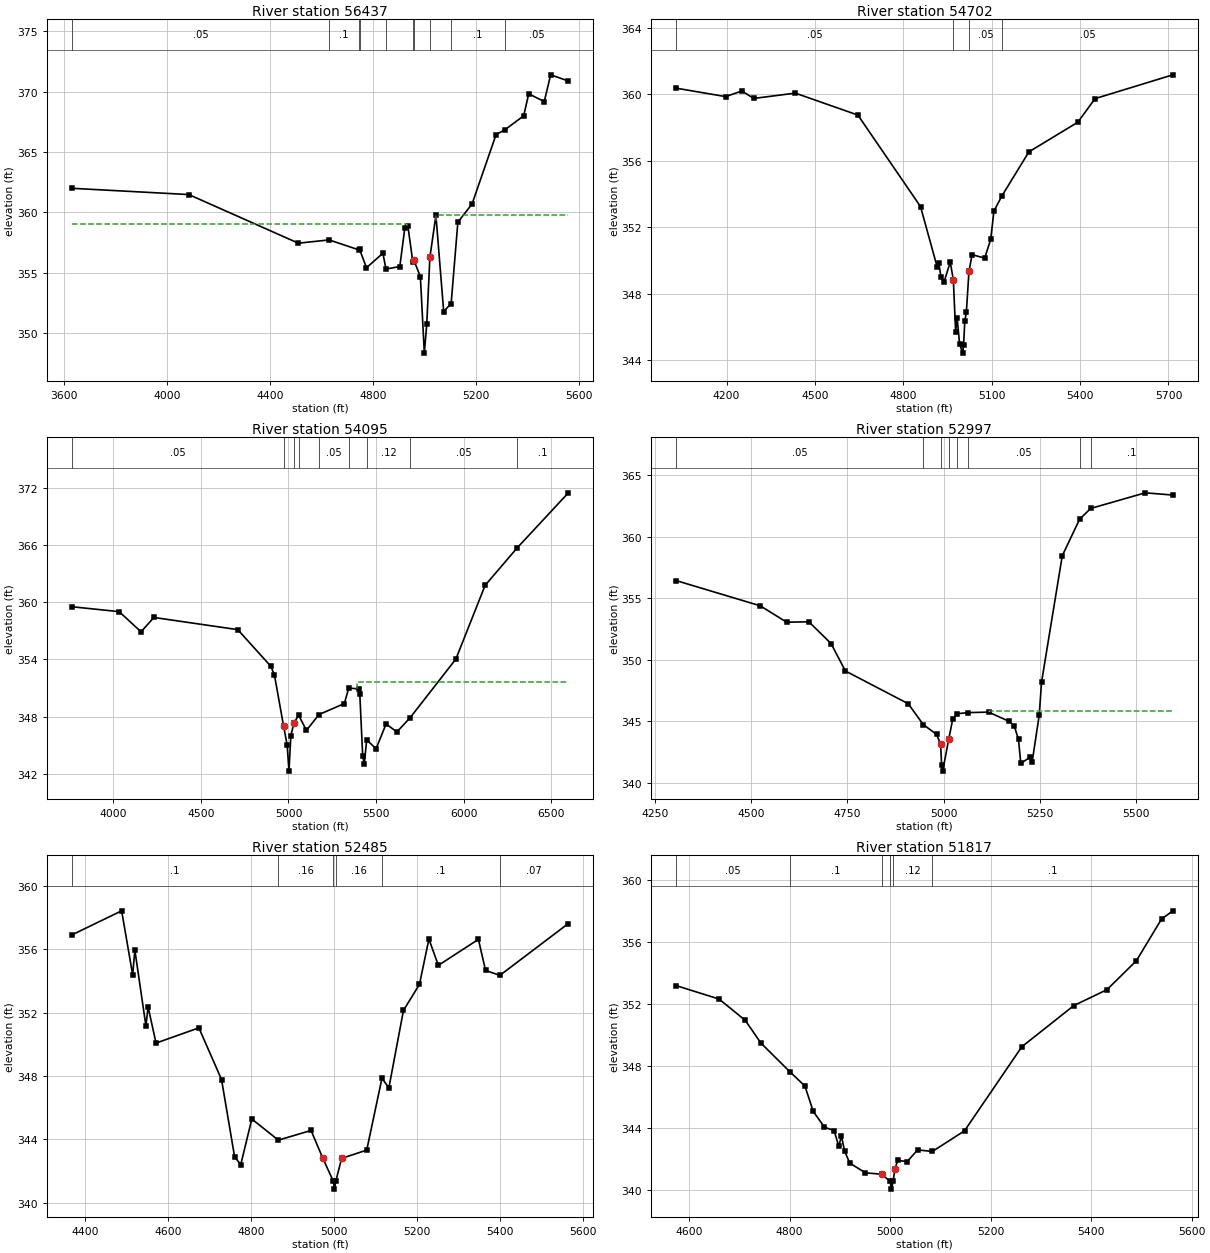
Type RM Length L Ch R = 1 ,56437   ,1735,1735,1735
BEGIN DESCRIPTION:
BEE CREEK 59.0
END DESCRIPTION:
XS GIS Cut Line= 3
        3533199.     10293697.19      3532504.54     10292915.92
      3531679.87     10292603.42
#Sta/Elev= 30
  3630.2     362  4085.2  361.48    4510  357.46  4629.4  357.73  4745.9   356.9
  4747.7  356.94  4774.4  355.43    4838  356.63  4849.9  355.32  4903.6  355.53
  4923.1  358.72  4934.8  358.89    4954  355.94  4958.6  356.03  4983.4  354.69
  4998.7  348.37  5008.2  350.78  5020.3   356.3  5043.7  359.76  5073.8  351.81
  5102.7  352.47  5128.8   359.2  5183.8   360.7    5277  366.44  5312.1  366.85
  5384.1  367.99  5403.6  369.81  5463.9  369.17  5488.7  371.38  5557.4  370.87
#Mann= 10 ,-1 , 0
  3630.2     .05       0  4629.4      .1       0  4745.9     .16       0
  4747.7      .1       0  4849.9     .12       0    4954     .16       0
  4958.6     .07       0  5020.3     .16       0  5102.7      .1       0
  5312.1     .05       0
#XS Ineff= 2 , 0
         4933.24  359.01 5045.45          359.79
Permanent Ineff=
       F       F
Bank Sta=4958.6,5020.3
XS Rating Curve= 0 ,0
Exp/Cntr=0.3,0.1

Type RM Length L Ch R = 1 ,54702   ,607,607,607
BEGIN DESCRIPTION:
BEE CREEK 57.0
END DESCRIPTION:
XS GIS Cut Line= 3
       3533459.4     10293540.92      3533034.06     10292316.96
       3532662.6     10292196.03
#Sta/Elev= 30
  4028.4  360.37    4197  359.86  4251.9   360.2  4292.3  359.75  4433.3  360.07
  4645.8  358.75  4858.3  353.25  4915.2   349.6  4920.5  349.85  4927.5  349.04
  4938.1  348.71  4959.3  349.92  4969.8  348.83  4977.5  345.73  4982.7  346.54
    4991  344.99  5001.4  344.44  5004.6  344.94  5008.6  346.37  5013.9  346.89
  5022.8  349.36  5033.4  350.36  5076.1  350.15  5096.6  351.28  5107.5  352.98
  5134.5  353.89  5226.3  356.54  5392.2  358.32  5450.8  359.74  5714.8  361.17
#Mann= 4 ,-1 , 0
  4028.4     .05       0  4969.8     .07       0  5022.8     .05       0
  5134.5     .05       0
Bank Sta=4969.8,5022.8
XS Rating Curve= 0 ,0
Exp/Cntr=0.3,0.1

Type RM Length L Ch R = 1 ,54095   ,1098,1098,1098
BEGIN DESCRIPTION:
BEE CREEK 56.0
END DESCRIPTION:
XS GIS Cut Line= 3
       3533867.4      10293662.5      3533459.41     10292282.24
      3533919.46     10290962.84
#Sta/Elev= 30
  3761.3  359.54  4033.3  359.02  4158.4   356.9  4231.4  358.41  4710.4  357.13
  4898.8  353.29  4919.7  352.38  4971.8  347.03  4992.2  345.04  5002.8  342.27
  5013.5     346  5030.7   347.3  5057.8  348.15  5102.5  346.55  5173.9  348.21
  5319.1  349.37  5343.9     351  5401.7   350.9    5407  350.42  5423.6  343.91
  5432.8  343.01  5446.5  345.55  5500.2  344.62    5557  347.22  5619.2  346.39
  5694.5  347.88  5955.7  354.04  6122.6  361.78  6304.2  365.69  6597.9   371.5
#Mann= 9 ,-1 , 0
  3761.3     .05       0  4971.8     .07       0  5030.7     .05       0
  5057.8      .1       0  5173.9     .05       0  5343.9      .1       0
  5446.5     .12       0  5694.5     .05       0  6304.2      .1       0
#XS Ineff= 2 , 0
                         5391.19          351.61
Permanent Ineff=
       F       F
Bank Sta=4971.8,5030.7
XS Rating Curve= 0 ,0
Exp/Cntr=0.3,0.1

Type RM Length L Ch R = 1 ,52997   ,512,512,512
BEGIN DESCRIPTION:
BEE CREEK 55.0
END DESCRIPTION:
XS GIS Cut Line= 3
      3533917.81     10292794.06       3534167.8     10292044.07
       3534353.5     10291579.14
#Sta/Elev= 30
  4304.4  356.43  4523.3  354.38  4591.8  353.05  4649.8  353.08  4707.5  351.31
  4744.6  349.09    4908  346.43  4946.9  344.74  4981.6  343.94  4992.1  343.14
  4994.6  341.46  4997.4  340.96  5013.2  343.55  5023.7  345.21  5035.5  345.62
    5063  345.71  5116.9  345.75  5170.8  344.99  5183.7  344.59  5194.5  343.53
  5200.4  341.59  5224.6  342.09    5230  341.71  5248.3   345.5  5254.3  348.17
  5308.2  358.44  5353.3  361.41    5382  362.28  5523.7  363.55  5595.6  363.37
#Mann= 8 ,-1 , 0
  4304.4     .05       0  4946.9      .1       0  4992.1     .07       0
  5013.2      .1       0  5035.5     .16       0    5063     .05       0
  5353.3     .16       0    5382      .1       0
#XS Ineff= 2 , 0
                         5117.95          345.82
Permanent Ineff=
       F       F
Bank Sta=4992.1,5013.2
XS Rating Curve= 0 ,0
Exp/Cntr=0.3,0.1

Type RM Length L Ch R = 1 ,52485   ,668,668,668
BEGIN DESCRIPTION:
BEE CREEK 54.0
END DESCRIPTION:
XS GIS Cut Line= 3
      3534370.86     10292855.16      3534509.75     10292429.81
      3534830.91     10291752.77
#Sta/Elev= 30
  4367.5  356.89  4488.2  358.42  4514.8  354.39  4520.1  355.94  4546.7  351.17
    4552  352.36  4571.1  350.08  4674.3  351.04  4728.9  347.78  4760.4   342.9
  4775.2  342.42  4801.8  345.29  4865.8  343.96  4944.5  344.57  4972.8  342.82
  4998.1  341.37  5000.8  340.87  5004.1  341.37  5018.2  342.81  5078.6  343.33
  5115.4  347.87  5131.9  347.25  5167.1  352.14  5205.6  353.78  5228.4  356.64
  5251.1  354.98  5347.6  356.62  5364.8  354.66  5399.3  354.35  5564.3  357.62
#Mann= 6 ,-1 , 0
  4367.5      .1       0  4865.8     .16       0  4998.1     .07       0
  5004.1     .16       0  5115.4      .1       0  5399.3     .07       0
Bank Sta=4972.8,5018.2
XS Rating Curve= 0 ,0
Exp/Cntr=0.3,0.1

Type RM Length L Ch R = 1 ,51817   ,598,598,598
BEGIN DESCRIPTION:
BEE CREEK 52.0
END DESCRIPTION:
XS GIS Cut Line= 3
      3534926.43     10292994.02      3535042.11     10292591.64
      3535192.12     10292041.61
#Sta/Elev= 30
  4573.8  353.19  4659.5  352.32  4711.5  350.95  4742.8  349.48  4800.1  347.64
  4830.4  346.71  4846.8  345.08  4869.3  344.05  4888.4  343.84  4897.8  342.82
    4903   343.5  4909.2  342.52  4919.6  341.74  4950.9  341.11  4983.4  341.02
  4999.8  340.56  5002.6  340.06  5005.8  340.56  5009.7  341.37  5014.9  341.91
  5033.9  341.84  5054.7  342.59  5084.1  342.49    5148  343.82    5262  349.24
  5365.6   351.9  5431.3  352.92    5490  354.79  5540.1  357.48  5562.6  358.01
#Mann= 6 ,-1 , 0
  4573.8     .05       0  4800.1      .1       0  4983.4     .12       0
  4999.8     .07       0  5005.8     .12       0  5084.1      .1       0
Bank Sta=4983.4,5009.7
XS Rating Curve= 0 ,0
Exp/Cntr=0.3,0.1