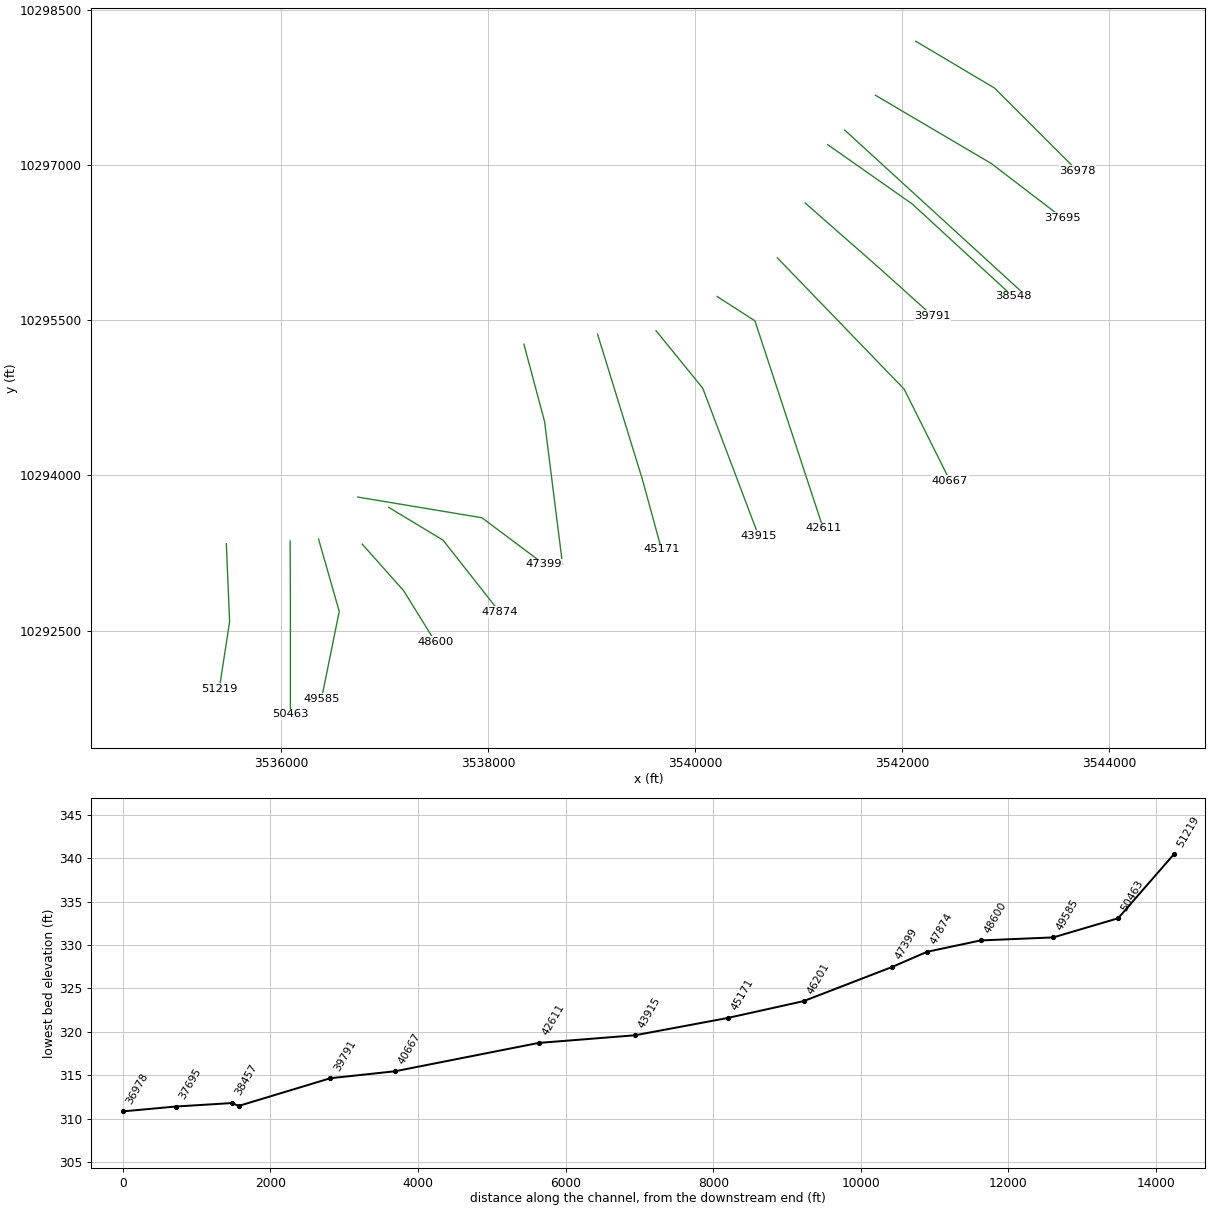
HEC-RAS study BEE CREEK.prj: BEE CREEK Base Level Engineering

--- BEE CREEK.g01 (geometry) --- (continued)

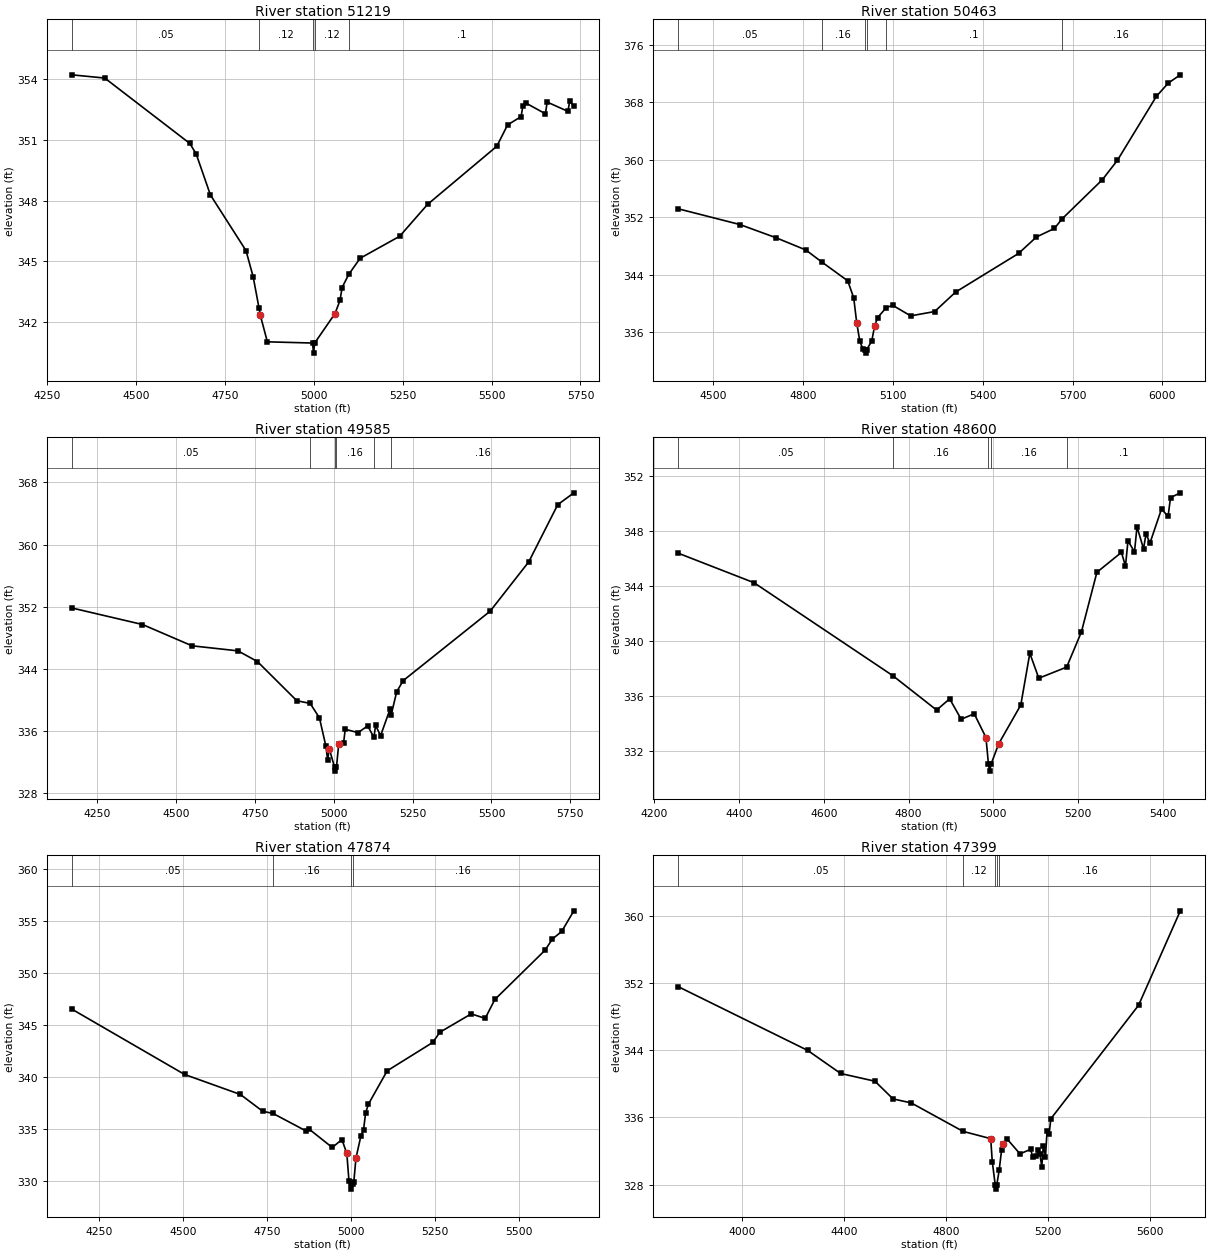
Type RM Length L Ch R = 1 ,51219   ,756,756,756
BEGIN DESCRIPTION:
BEE CREEK 51.0
END DESCRIPTION:
XS GIS Cut Line= 3
      3535473.29     10293341.25      3535504.95     10292587.48
      3535404.95     10291937.46
#Sta/Elev= 30
  4319.2  354.23  4411.9  354.07  4651.2  350.83  4669.1  350.31  4709.1  348.28
  4809.2  345.52  4829.3  344.23    4846  342.66  4849.3  342.33  4869.3     341
  4996.4  340.94  4999.2  340.44  5002.4  340.94  5059.5   342.4  5073.6  343.05
  5079.5  343.69  5098.1  344.34  5130.2  345.14  5241.4  346.23  5319.9  347.81
  5514.6  350.69    5545  351.75    5583  352.16    5588   352.7  5595.5  352.84
  5651.3   352.3  5656.3  352.88  5714.5  352.42  5719.6  352.91  5731.3   352.7
#Mann= 5 ,-1 , 0
  4319.2     .05       0    4846     .12       0  4996.4     .07       0
  5002.4     .12       0  5098.1      .1       0
Bank Sta=4849.3,5059.5
XS Rating Curve= 0 ,0
Exp/Cntr=0.3,0.1

Type RM Length L Ch R = 1 ,50463   ,878,878,878
BEGIN DESCRIPTION:
BEE CREEK 49.0
END DESCRIPTION:
XS GIS Cut Line= 3
      3536089.61     10293367.32      3536092.11     10292791.64
      3536092.11     10291691.63
#Sta/Elev= 30
  4383.9  353.17  4589.6  350.98  4709.6  349.15  4809.6  347.44  4862.1  345.79
  4949.6  343.14  4969.6  340.76  4979.6  337.29  4989.6   334.8  4999.6  333.68
  5006.6  333.57  5009.3  333.07  5012.6  333.57  5029.6  334.72  5039.6  336.91
  5049.6  338.03  5078.2  339.41  5099.6  339.73  5159.6  338.26  5239.6  338.86
  5309.6  341.57  5519.6  346.95  5579.6  349.25  5639.6  350.44  5664.6  351.75
  5799.6  357.23  5849.6  359.92  5979.6  368.82  6019.6  370.69  6059.6  371.83
#Mann= 6 ,-1 , 0
  4383.9     .05       0  4862.1     .16       0  5006.6     .07       0
  5012.6     .16       0  5078.2      .1       0  5664.6     .16       0
Bank Sta=4979.6,5039.6
XS Rating Curve= 0 ,0
Exp/Cntr=0.3,0.1

Type RM Length L Ch R = 1 ,49585   ,985,985,985
BEGIN DESCRIPTION:
BEE CREEK 48.0
END DESCRIPTION:
XS GIS Cut Line= 3
      3536363.62     10293387.16      3536563.63     10292687.13
       3536392.1      10291841.6
#Sta/Elev= 30
  4170.3  351.86  4394.4  349.73  4551.3  346.99  4696.9  346.34  4758.4  344.97
  4883.2  339.93  4925.6  339.58    4955  337.73  4975.4  334.09    4981   332.3
  4986.1  333.75    5003  331.37  5005.7  330.87    5009  331.37  5016.2  334.39
  5031.6   334.5  5036.7  336.26  5077.2  335.82    5108  336.69  5127.6   335.2
  5132.9  336.74  5148.8  335.43  5178.5  338.82  5182.6  338.14  5199.8  341.08
  5220.3  342.51  5495.8  351.44  5618.2  357.79    5710  365.14  5761.1  366.67
#Mann= 6 ,-1 , 0
  4170.3     .05       0  4925.6     .16       0    5003     .07       0
    5009     .16       0  5127.6      .1       0  5182.6     .16       0
Bank Sta=4986.1,5016.2
XS Rating Curve= 0 ,0
Exp/Cntr=0.3,0.1

Type RM Length L Ch R = 1 ,48600   ,726,726,726
BEGIN DESCRIPTION:
BEE CREEK 47.0
END DESCRIPTION:
XS GIS Cut Line= 3
      3536785.53      10293337.1      3537185.51     10292887.13
       3537492.1     10292391.65
#Sta/Elev= 30
  4256.5   346.4  4435.3  344.25  4762.6  337.48  4866.2  334.97    4897  335.79
  4924.1   334.3  4954.9   334.7  4982.6  332.97  4988.5  331.02  4991.3  330.52
  4994.5  331.02  5012.8  332.52  5064.8  335.34  5086.1  339.11  5107.3  337.29
    5173   338.1  5207.8  340.66  5244.4  345.01  5302.3  346.46  5311.8  345.46
  5317.7   347.3  5333.1   346.5    5339  348.33  5354.4  346.72  5360.2  347.79
  5369.7  347.15  5396.9  349.63  5412.3  349.08  5418.1  350.45  5441.2   350.8
#Mann= 5 ,-1 , 0
  4256.5     .05       0  4762.6     .16       0  4988.5     .07       0
  4994.5     .16       0    5173      .1       0
Bank Sta=4982.6,5012.8
XS Rating Curve= 0 ,0
Exp/Cntr=0.3,0.1

Type RM Length L Ch R = 1 ,47874   ,475,475,475
BEGIN DESCRIPTION:
BEE CREEK 45.0
END DESCRIPTION:
XS GIS Cut Line= 3
       3537042.1     10293691.64      3537565.31     10293375.99
       3538112.2     10292681.53
#Sta/Elev= 30
    4168  346.54  4503.8  340.25  4670.2  338.32  4736.8   336.7    4767   336.5
    4865  334.82  4873.1  335.03  4943.6  333.22  4972.5  333.98    4987  332.64
  4993.3  330.04    4998  329.71  5000.7  329.21    5004  329.71  5007.8  329.89
  5014.2   332.2  5028.6  334.28  5036.7   334.9    5043  336.54  5051.1  337.38
  5107.2   340.6  5242.8  343.33  5264.4  344.32  5357.4  346.08    5399  345.65
  5427.9  347.47    5577   352.2  5599.2  353.29  5626.7  354.01    5663     356
#Mann= 4 ,-1 , 0
    4168     .05       0    4767     .16       0    4998     .07       0
    5004     .16       0
Bank Sta=4987,5014.2
XS Rating Curve= 0 ,0
Exp/Cntr=0.3,0.1

Type RM Length L Ch R = 1 ,47399   ,1198,1198,1198
BEGIN DESCRIPTION:
BEE CREEK 44.0
END DESCRIPTION:
XS GIS Cut Line= 3
      3536742.08     10293791.65      3537942.11     10293591.64
      3538542.12     10293141.63
#Sta/Elev= 30
  3750.8  351.57  4257.7  343.98    4387  341.23  4521.3  340.31  4592.3   338.2
  4663.2  337.73  4866.2  334.34  4974.7  333.47  4980.9  330.72  4992.5  327.96
  4995.3  327.46  4998.5  327.96  5007.9  329.71  5017.4  332.13  5024.7  332.89
  5039.3  333.42  5089.3  331.66  5130.9   332.2  5139.3  331.33  5153.8  331.35
  5160.1  332.12  5167.4  331.65  5174.7  330.13  5180.9  332.63  5189.3  331.34
  5195.5  334.39  5203.8  334.07  5210.1  335.83  5553.8  349.35  5717.4   360.6
#Mann= 5 ,-1 , 0
  3750.8     .05       0  4866.2     .12       0  4992.5     .07       0
  4998.5     .12       0  5007.9     .16       0
Bank Sta=4974.7,5024.7
XS Rating Curve= 0 ,0
Exp/Cntr=0.3,0.1

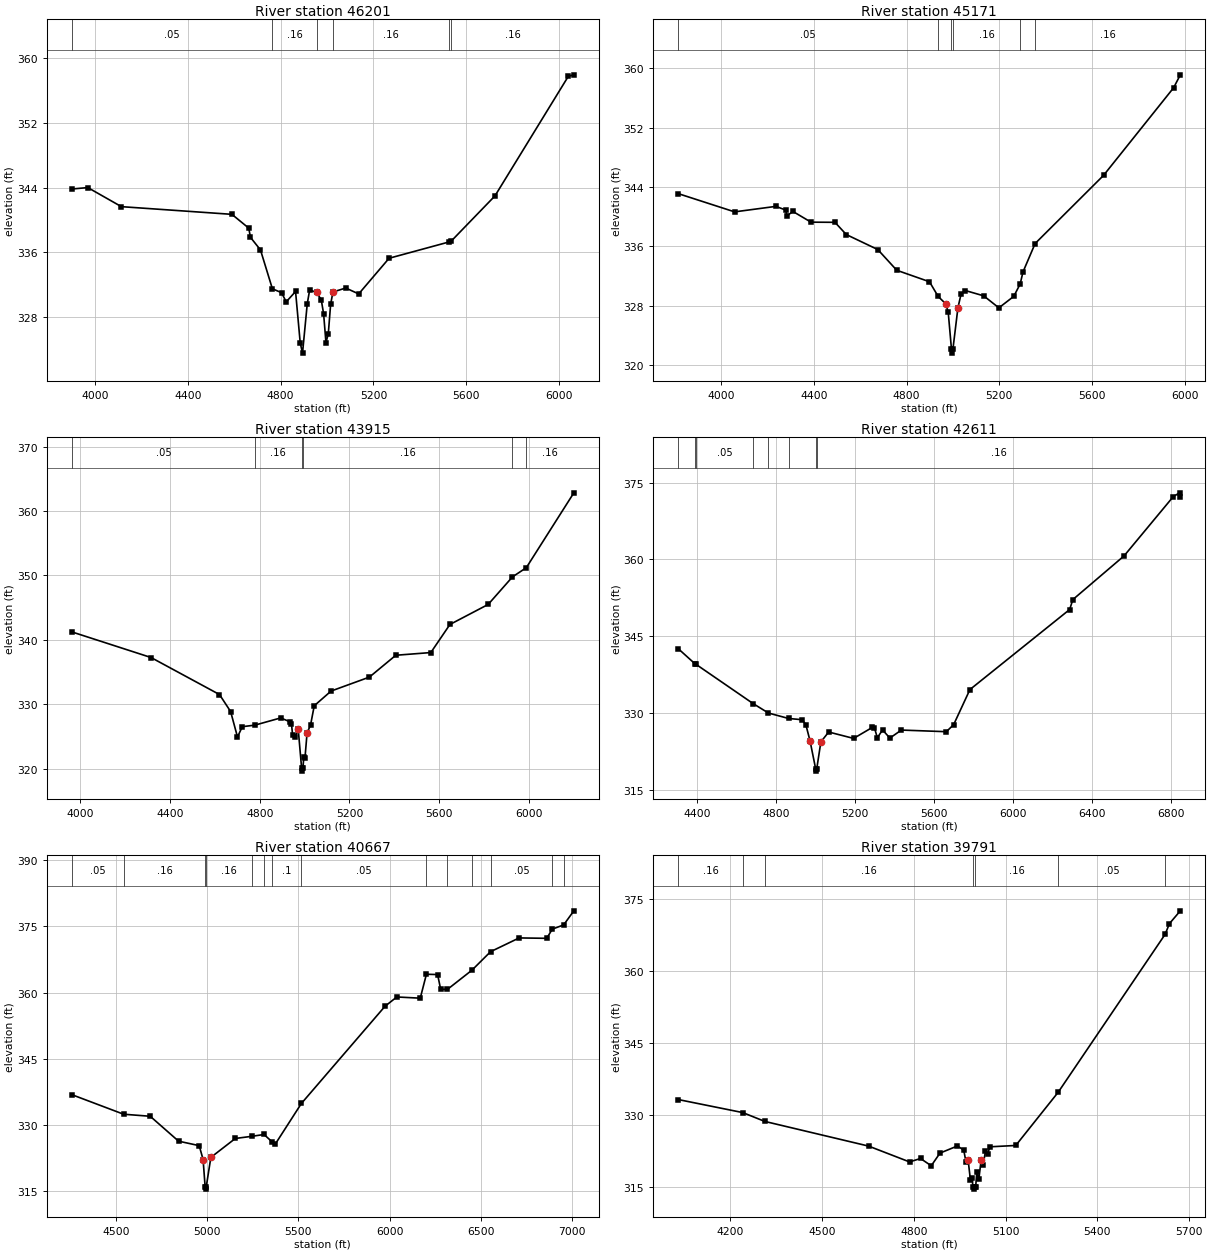
Type RM Length L Ch R = 1 ,46201   ,1030,1030,1030
BEGIN DESCRIPTION:
BEE CREEK 43.0
END DESCRIPTION:
XS GIS Cut Line= 3
      3538346.55     10295268.38      3538546.21     10294521.83
      3538719.82     10293141.59
#Sta/Elev= 30
    3900  343.82  3969.1     344    4114  341.64  4590.2  340.69  4662.6  338.99
  4670.3  337.84  4713.3  336.29  4764.7  331.48    4804  331.01  4824.2  329.87
  4864.5  331.15  4884.6   324.8  4894.5  323.53  4914.9  329.63  4925.2  331.33
  4955.2  331.05  4975.3  330.11  4985.4   328.4  4995.5  324.83  5005.6  325.93
  5015.7  329.57  5025.7  331.09  5080.9  331.58  5136.6  330.85  5267.6  335.26
  5526.6  337.28  5536.4  337.41  5723.9  342.97  6040.4  357.77  6063.9  357.94
#Mann= 6 ,-1 , 0
    3900     .05       0  4764.7     .16       0  4955.2     .07       0
  5025.7     .16       0  5526.6      .1       0  5536.4     .16       0
Bank Sta=4955.2,5025.7
XS Rating Curve= 0 ,0
Exp/Cntr=0.3,0.1

Type RM Length L Ch R = 1 ,45171   ,1256,1256,1256
BEGIN DESCRIPTION:
BEE CREEK 42.0
END DESCRIPTION:
XS GIS Cut Line= 3
      3539058.35     10295363.88      3539492.39     10293957.59
      3539674.69     10293289.15
#Sta/Elev= 30
  3815.7  343.11  4058.7  340.65  4236.7  341.39  4278.5   340.9    4285  340.11
  4309.9  340.71  4388.2  339.26  4491.4  339.24  4540.2  337.59  4676.2  335.56
  4757.8  332.77  4898.9  331.22  4936.2  329.24  4969.4  328.23  4979.7   327.1
  4993.8  322.09  4996.6  321.59  4999.8  322.09  5021.6  327.72  5034.7  329.51
    5053  330.04  5132.7  329.32    5198   327.7  5262.3  329.25    5290  330.93
  5302.1  332.55  5354.4  336.38  5649.3  345.57  5951.6   357.4  5980.3  359.14
#Mann= 6 ,-1 , 0
  3815.7     .05       0  4936.2     .16       0  4993.8     .07       0
  4999.8     .16       0    5290      .1       0  5354.4     .16       0
Bank Sta=4969.4,5021.6
XS Rating Curve= 0 ,0
Exp/Cntr=0.3,0.1

Type RM Length L Ch R = 1 ,43915   ,1304,1304,1304
BEGIN DESCRIPTION:
BEE CREEK 41.0
END DESCRIPTION:
XS GIS Cut Line= 3
      3539622.61     10295398.55      3540073.99     10294843.01
      3540612.17     10293419.44
#Sta/Elev= 30
  3962.4  341.22  4315.6  337.24  4620.8  331.49  4670.4  328.85    4701   324.9
  4722.4   326.5  4778.4  326.74  4893.5  327.86  4936.2  327.24  4941.6  326.91
  4946.9  325.15  4957.6  324.85  4971.7  326.09  4986.7   320.1  4989.4   319.6
  4992.7   320.1  4996.6  321.79  5001.9  321.71  5011.1  325.52  5026.7  326.77
  5043.1  329.75    5118  332.03    5289   334.2  5406.6  337.59  5562.7  338.01
  5647.8  342.37  5818.2  345.48  5926.6  349.76  5988.1  351.18  6200.1  362.81
#Mann= 6 ,-1 , 0
  3962.4     .05       0  4778.4     .16       0  4986.7     .07       0
  4992.7     .16       0  5926.6      .1       0  5988.1     .16       0
Bank Sta=4971.7,5011.1
XS Rating Curve= 0 ,0
Exp/Cntr=0.3,0.1

Type RM Length L Ch R = 1 ,42611   ,1944,1944,1944
BEGIN DESCRIPTION:
BEE CREEK 40.0
END DESCRIPTION:
XS GIS Cut Line= 3
      3540212.92      10295728.4      3540577.46     10295494.05
      3541237.15     10293488.95
#Sta/Elev= 30
  4303.5   342.6  4389.3  339.62  4392.4  339.58  4682.7   331.9  4760.6  330.05
  4862.7  328.99  4930.9  328.75    4950   327.8    4971  324.68  4999.6  319.22
  5002.3  318.72  5005.6  319.22  5026.3  324.42  5065.8  326.35  5192.1   325.1
  5286.8  327.24  5297.4  327.21  5312.4  325.23  5338.9  326.75    5376  325.17
  5434.2  326.73  5662.1  326.41  5699.2  327.79  5781.6  334.63  6286.9  350.24
  6303.2  352.18  6562.7   360.7  6811.8  372.25  6843.6     373  6847.7  372.23
#Mann= 8 ,-1 , 0
  4303.5     .05       0  4389.3      .1       0  4392.4     .05       0
  4682.7     .16       0  4760.6      .1       0  4862.7     .16       0
  4999.6     .07       0  5005.6     .16       0
Bank Sta=4971,5026.3
XS Rating Curve= 0 ,0
Exp/Cntr=0.3,0.1

Type RM Length L Ch R = 1 ,40667   ,876,876,876
BEGIN DESCRIPTION:
BEE CREEK 39.0
END DESCRIPTION:
XS GIS Cut Line= 3
      3540794.45     10296101.71      3542018.43     10294834.33
      3542461.16     10293948.87
#Sta/Elev= 30
  4258.5  336.87  4542.8  332.43  4688.4  331.97  4843.8  326.33    4957  325.31
  4978.3  322.17  4989.5  315.96  4992.2  315.46  4995.5  315.96  5020.8  322.65
    5155  326.94  5245.9  327.43  5312.5  327.84  5354.3  326.25  5374.2  325.68
  5517.2  334.88  5975.4  356.89    6040     359  6168.6  358.73  6202.3  364.15
  6263.6  364.08  6280.4  360.75  6317.3  360.71  6452.1  365.08  6553.9  369.26
  6710.8  372.38  6861.8  372.29  6892.3  374.37  6954.5  375.33  7010.4  378.52
#Mann= 14 ,-1 , 0
  4258.5     .05       0  4542.8     .16       0  4989.5     .07       0
  4995.5     .16       0  5245.9      .1       0  5312.5     .16       0
  5354.3      .1       0  5517.2     .05       0  6202.3      .1       0
  6317.3     .05       0  6452.1      .1       0  6553.9     .05       0
  6892.3      .1       0  6954.5     .05       0
Bank Sta=4978.3,5020.8
XS Rating Curve= 0 ,0
Exp/Cntr=0.3,0.1

Type RM Length L Ch R = 1 ,39791   ,1243,1243,1243
BEGIN DESCRIPTION:
BEE CREEK 38.0
END DESCRIPTION:
XS GIS Cut Line= 3
       3541063.6     10296631.18      3541792.11     10295991.64
      3542292.12     10295541.62
#Sta/Elev= 30
  4029.5  333.29  4240.5  330.58  4312.7  328.74  4652.1  323.61    4786  320.32
  4821.9  321.03    4857  319.52  4885.5  322.15  4942.4  323.63  4963.3  322.79
  4970.9   320.2  4977.5  320.75  4985.1  316.59  4991.8  316.91  4992.6  315.16
  4995.3  314.66  4998.6  315.16  5002.3  315.16    5006  318.19  5012.7  316.76
  5020.2   320.7  5026.9  319.71  5034.4  322.57  5041.1   321.9  5048.6  323.46
  5133.4  323.74  5272.3  334.82  5621.9  367.65  5636.1  369.89  5671.6  372.54
#Mann= 7 ,-1 , 0
  4029.5     .16       0  4240.5      .1       0  4312.7     .16       0
  4992.6     .07       0  4998.6     .16       0  5272.3     .05       0
  5621.9      .1       0
Bank Sta=4977.5,5020.2
XS Rating Curve= 0 ,0
Exp/Cntr=0.3,0.1

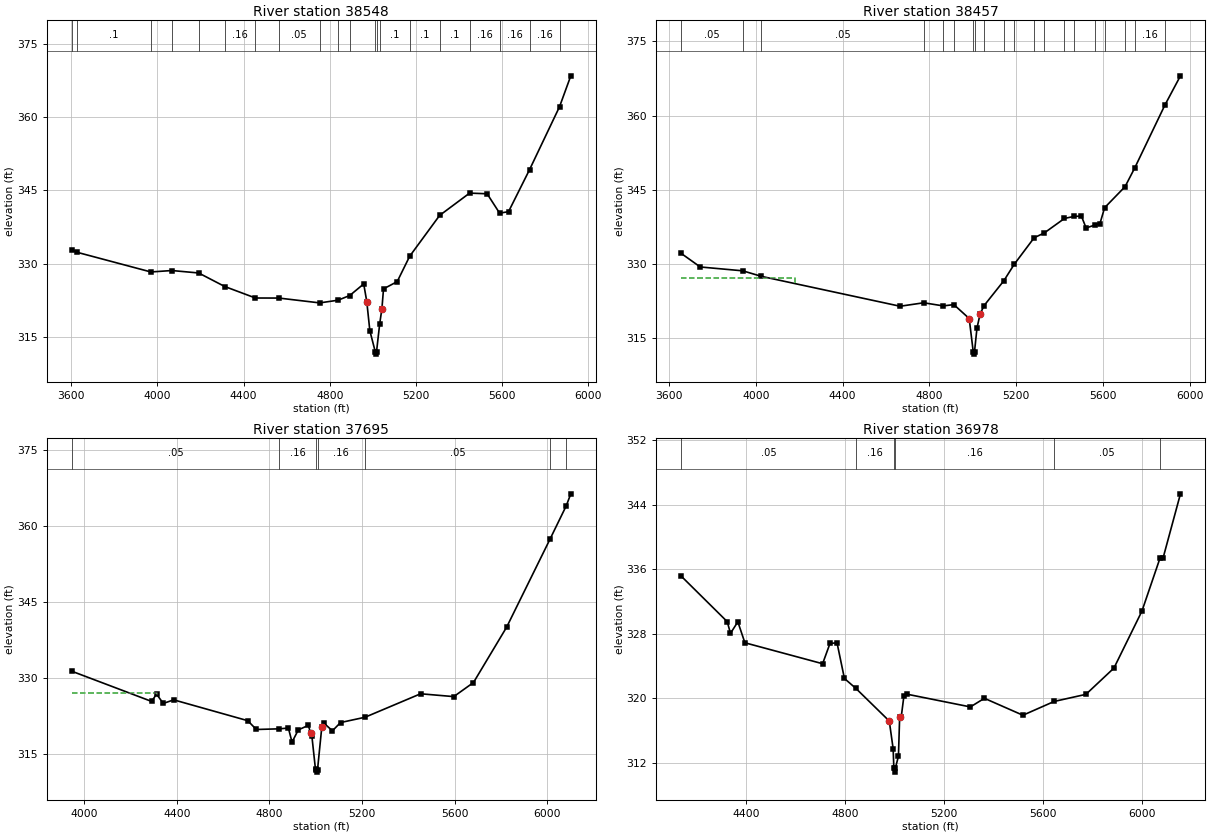
Type RM Length L Ch R = 1 ,38548   ,91,91,91
BEGIN DESCRIPTION:
BEE CREEK 37.0
END DESCRIPTION:
XS GIS Cut Line= 3
      3541280.58     10297195.44      3542096.56     10296622.52
      3543067.92     10295729.22
#Sta/Elev= 30
  3601.8   332.8  3624.7  332.33  3969.5  328.28  4067.2  328.57  4191.4  328.07
  4312.5   325.3  4454.9  322.95  4563.7  322.94  4753.3  321.95    4838   322.5
  4892.5  323.46  4957.4  325.83  4971.6  322.23  4985.8  316.27  5010.9  311.97
  5013.7  311.47  5016.9  311.97  5031.6  317.69  5041.9  320.78  5049.3  324.82
  5112.8   326.3  5170.7  331.49  5309.8  339.85  5448.9  344.41  5530.2  344.27
  5588.1  340.31  5629.5  340.61  5727.2  349.22  5866.3  362.09  5918.5   368.4
#Mann= 20 ,-1 , 0
  3601.8     .16       0  3624.7      .1       0  3969.5     .16       0
  4067.2      .1       0  4191.4     .05       0  4312.5     .16       0
  4454.9     .16       0  4563.7     .05       0  4753.3      .1       0
    4838     .05       0  4892.5     .16       0  5010.9     .04       0
  5016.9     .05       0  5031.6      .1       0  5170.7      .1       0
  5309.8      .1       0  5448.9     .16       0  5588.1     .16       0
  5727.2     .16       0  5866.3      .1       0
Bank Sta=4971.6,5041.9
XS Rating Curve= 0 ,0
Exp/Cntr=0.3,0.1

Type RM Length L Ch R = 1 ,38457   ,762,762,762
BEGIN DESCRIPTION:
Mapping XS 62b92805
END DESCRIPTION:
XS GIS Cut Line= 2
      3541443.97      10297336.8      3543140.22     10295785.88
#Sta/Elev= 30
  3657.2  332.15  3744.5  329.42  3940.3  328.64  4026.3  327.52  4664.7  321.48
  4773.3  322.18  4863.5  321.55  4912.2  321.81  4982.9     319  5001.4   312.3
  5004.2   311.8  5007.4   312.3  5018.6  317.03  5032.8  319.86    5051  321.59
  5142.5  326.64  5189.9  329.94    5282  335.33  5328.7   336.3  5421.6  339.23
  5467.6  339.66  5499.6  339.69  5521.2   337.3  5561.1  337.89  5584.8  338.18
  5606.4   341.4  5700.6  345.66  5745.3  349.46  5884.1  362.16  5955.6  368.06
#Mann= 20 ,-1 , 0
  3657.2     .05       0  3940.3      .1       0  4026.3     .05       0
  4773.3      .1       0  4863.5     .05       0  4912.2     .16       0
  5001.4     .07       0  5007.4     .16       0    5051     .16       0
  5142.5     .05       0  5189.9     .16       0    5282     .05       0
  5328.7     .16       0  5421.6     .05       0  5467.6     .16       0
  5561.1     .05       0  5606.4     .16       0  5700.6     .05       0
  5745.3     .16       0  5884.1      .1       0
#XS Ineff= 2 , 0
          4180.4   327.2
Permanent Ineff=
       F       F
Bank Sta=4982.9,5032.8
XS Rating Curve= 0 ,0
Exp/Cntr=0.3,0.1

Type RM Length L Ch R = 1 ,37695   ,717,717,717
BEGIN DESCRIPTION:
BEE CREEK 36.0
END DESCRIPTION:
XS GIS Cut Line= 3
      3541740.63     10297672.88      3542860.45     10297013.15
      3543542.12     10296491.63
#Sta/Elev= 30
  3944.7  331.36  4290.4  325.38  4311.8  326.82    4341  324.98    4386  325.69
  4706.1  321.57  4743.2  319.83  4841.9  319.96  4881.8  320.11  4897.5  317.33
  4924.7  319.75  4967.8  320.64  4977.5  319.22  4983.3  318.54    4999  311.92
  5001.8   311.9  5004.5   311.4  5007.8   311.9  5026.2   320.3  5036.1  321.05
  5072.2  319.57  5107.1   321.2  5213.1  322.25  5453.4  326.89  5596.7  326.33
  5681.9  329.11  5825.3  340.06  6012.7  357.45  6082.8  364.03  6102.7  366.42
#Mann= 7 ,-1 , 0
  3944.7     .05       0  4841.9     .16       0  5001.8     .07       0
  5007.8     .16       0  5213.1     .05       0  6012.7      .1       0
  6082.8     .05       0
#XS Ineff= 2 , 0
         4313.07  326.97
Permanent Ineff=
       F       F
Bank Sta=4977.5,5026.2
XS Rating Curve= 0 ,0
Exp/Cntr=0.3,0.1

Type RM Length L Ch R = 1 ,36978   ,2923,2923,2923
BEGIN DESCRIPTION:
BEE CREEK 35.0
END DESCRIPTION:
XS GIS Cut Line= 3
      3542131.28      10298193.7      3542892.11     10297741.64
      3543692.13     10296941.62
#Sta/Elev= 30
  4138.9  335.15  4324.5  329.51  4337.6  328.06  4367.4  329.49  4395.8  326.89
  4709.8  324.29  4739.5   326.8    4768  326.89  4797.9  322.46  4844.5  321.22
  4979.1  317.18  4994.7  313.75  4997.6  311.34  5000.4  310.84  5003.6  311.34
  5016.1   312.8    5021  317.69  5027.4  317.69    5038  320.24  5052.2   320.5
  5306.7  318.93  5363.3     320  5518.9   317.9  5645.2  319.61  5773.4  320.49
  5886.6  323.75  5999.7  330.82    6073  337.42  6084.6  337.35  6155.3  345.37
#Mann= 6 ,-1 , 0
  4138.9     .05       0  4844.5     .16       0  4997.6     .07       0
  5003.6     .16       0  5645.2     .05       0    6073     .16       0
Bank Sta=4979.1,5021
XS Rating Curve= 0 ,0
Exp/Cntr=0.3,0.1