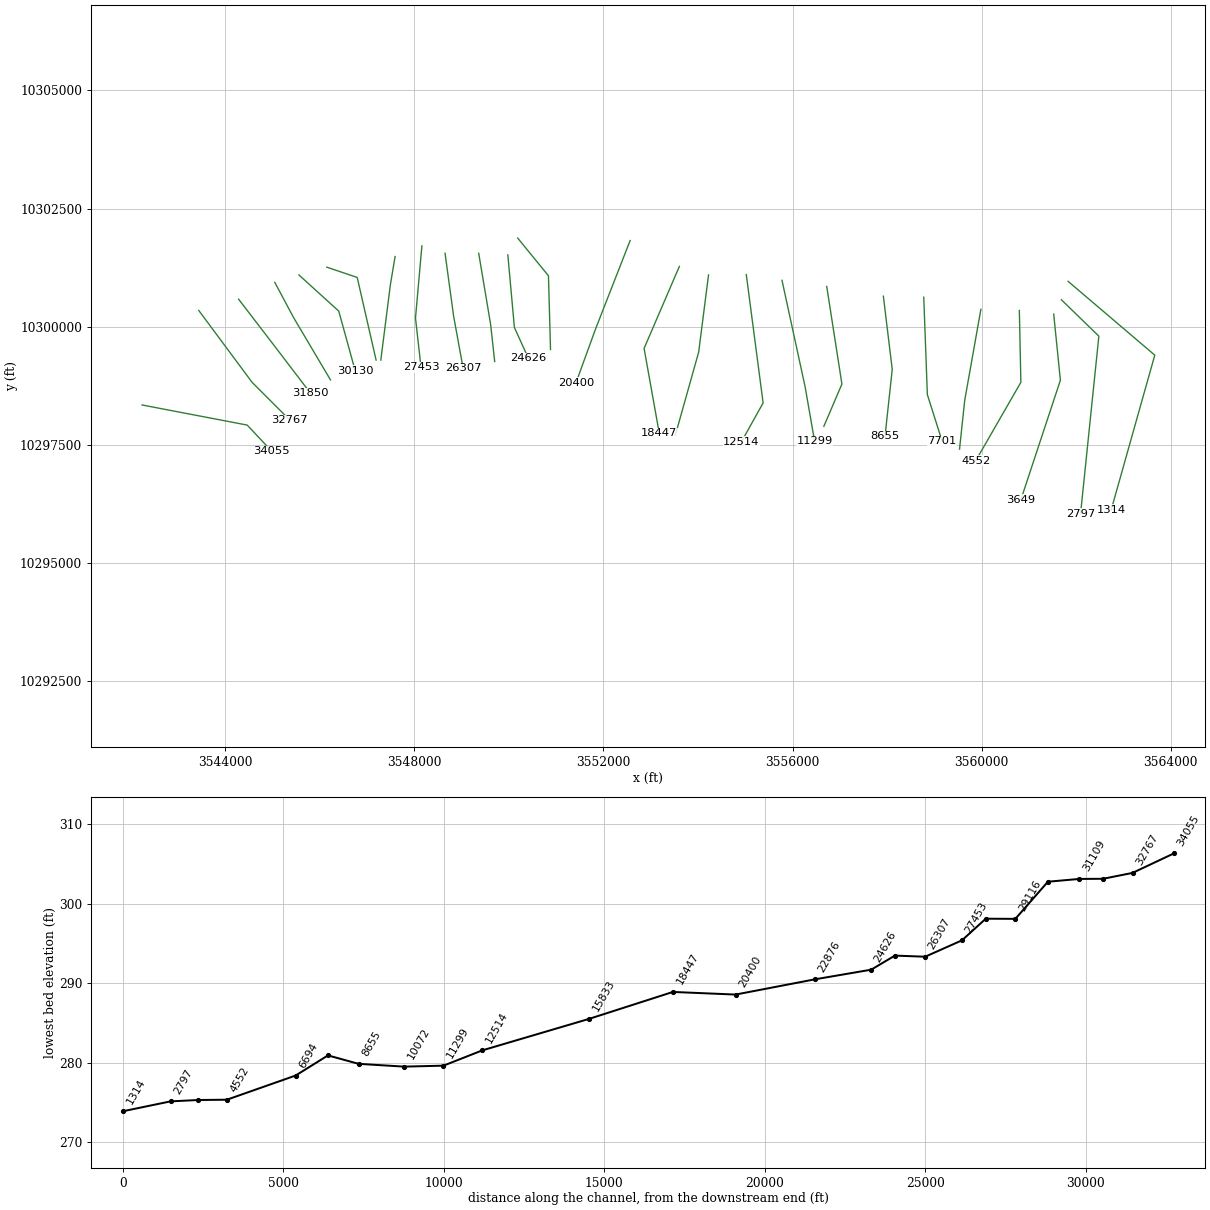
HEC-RAS study BEE CREEK.prj: BEE CREEK Base Level Engineering

--- BEE CREEK.g01 (geometry) --- (continued)

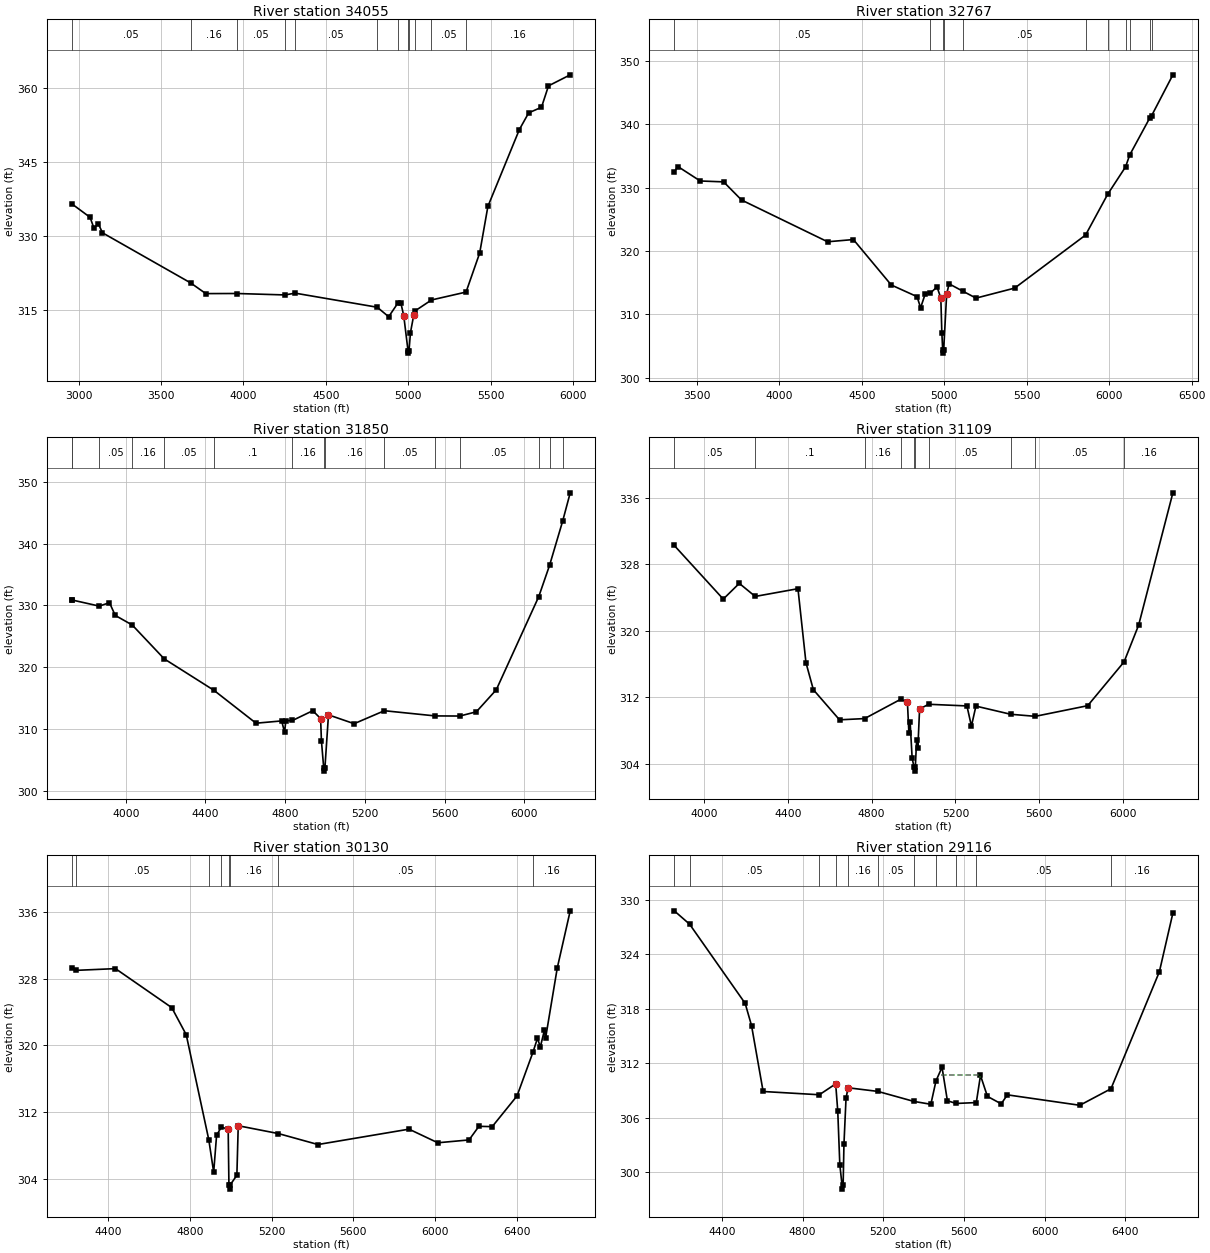
Type RM Length L Ch R = 1 ,34055   ,1288,1288,1288
BEGIN DESCRIPTION:
BEE CREEK 34.0
END DESCRIPTION:
XS GIS Cut Line= 3
      3542242.12     10298341.64      3544466.35     10297915.92
      3544987.16     10297360.39
#Sta/Elev= 30
    2957  336.58    3069  333.82  3092.2  331.67  3119.9  332.47  3144.3  330.69
  3679.6  320.55  3771.5  318.39  3960.5  318.41  4251.5  318.12  4313.8  318.48
  4812.1  315.63  4881.3  313.71  4938.4  316.53  4954.7  316.58  4972.9   313.9
  4998.7  306.85  5001.4  306.35  5004.7  306.85  5013.7  310.52    5034  314.13
  5039.7  314.85  5141.1   317.1  5350.9   318.7  5433.7   326.6  5483.5  336.03
  5674.5  351.57  5731.1  354.95  5808.8  356.08  5851.3  360.41  5983.1  362.64
#Mann= 12 ,-1 , 0
    2957     .05       0  3679.6     .16       0  3960.5     .05       0
  4251.5     .16       0  4313.8     .05       0  4812.1     .16       0
  4938.4     .05       0  4998.7    .035       0  5004.7     .05       0
  5039.7     .16       0  5141.1     .05       0  5350.9     .16       0
Bank Sta=4972.9,5034
XS Rating Curve= 0 ,0
Exp/Cntr=0.3,0.1

Type RM Length L Ch R = 1 ,32767   ,917,917,917
BEGIN DESCRIPTION:
BEE CREEK 32.0
END DESCRIPTION:
XS GIS Cut Line= 3
       3543442.1     10300341.65      3544569.88     10298820.11
      3545368.47     10298021.53
#Sta/Elev= 30
  3362.8  332.45  3384.7  333.31  3520.4  331.03  3662.2  330.89  3770.8  328.03
  4292.5  321.45    4449   321.8  4678.6  314.64    4835   312.8  4856.5  311.05
  4885.1  313.28  4915.7  313.36  4956.1  314.34  4979.1  312.58  4985.3  307.11
  4990.4   304.4  4993.2   303.9  4996.4   304.4  5014.5   313.2  5029.2  314.82
  5114.2  313.64  5192.6  312.57  5426.9  314.15  5856.8  322.51  5990.4  328.92
  6099.4  333.26    6124  335.11  6244.9  340.91  6257.6  341.34  6386.1  347.76
#Mann= 11 ,-1 , 0
  3362.8     .05       0  4915.7     .16       0  4990.4     .07       0
  4996.4     .16       0  5114.2     .05       0  5856.8      .1       0
  5990.4     .05       0  6099.4      .1       0    6124     .16       0
  6244.9      .1       0  6257.6     .16       0
Bank Sta=4979.1,5014.5
XS Rating Curve= 0 ,0
Exp/Cntr=0.3,0.1

Type RM Length L Ch R = 1 ,31850   ,741,741,741
BEGIN DESCRIPTION:
BEE CREEK 30.0
END DESCRIPTION:
XS GIS Cut Line= 3
      3544284.07     10300580.84      3545042.11     10299591.64
      3545803.14     10298593.02
#Sta/Elev= 30
  3728.6  330.87  3730.8  330.87  3867.3  329.88  3918.6  330.43  3947.7  328.37
  4032.8  326.82  4193.3  321.34  4442.5  316.25  4653.9  310.92  4782.7  311.29
  4797.2  309.43  4803.5  311.32  4836.9  311.36  4938.5  312.94    4978  311.68
  4982.1  308.07  4993.6  303.66  4996.4  303.16  4999.6  303.66  5017.5  312.27
  5146.3  310.84    5298  312.94    5553   312.1  5676.8  312.08  5759.6  312.77
  5859.4  316.33  6072.5  331.41  6127.1  336.51  6192.3  343.62  6230.4  348.22
#Mann= 15 ,-1 , 0
  3728.6     .05       0  3730.8      .1       0  3867.3     .05       0
  4032.8     .16       0  4193.3     .05       0  4442.5      .1       0
  4836.9     .16       0  4993.6     .07       0  4999.6     .16       0
    5298     .05       0    5553      .1       0  5676.8     .05       0
  6072.5      .1       0  6127.1     .05       0  6192.3      .1       0
Bank Sta=4978,5017.5
XS Rating Curve= 0 ,0
Exp/Cntr=0.3,0.1

Type RM Length L Ch R = 1 ,31109   ,979,979,979
BEGIN DESCRIPTION:
BEE CREEK 28.0
END DESCRIPTION:
XS GIS Cut Line= 3
      3545049.42     10300937.09       3545449.4     10300187.13
      3546227.79     10298871.98
#Sta/Elev= 30
  3858.7  330.28  4092.4  323.83  4168.9  325.72  4244.8  324.15  4448.7  325.08
  4486.9  316.18  4522.2  312.93  4646.9  309.31  4766.8  309.46  4937.9  311.77
  4970.7  311.47  4977.8  307.76  4983.6  309.09  4993.4  304.66  5002.5  303.64
  5005.3  303.14  5008.5  303.64  5014.8  306.94  5020.6   305.9  5028.8  310.61
  5071.9  311.18  5254.6  310.98  5276.1  308.56  5297.5  310.96  5462.8  309.98
  5580.6  309.73  5830.6  311.01  6004.1  316.28  6073.6   320.7  6236.9  336.61
#Mann= 10 ,-1 , 0
  3858.7     .05       0  4244.8      .1       0  4766.8     .16       0
  4937.9     .12       0  5002.5     .07       0  5008.5     .12       0
  5071.9     .05       0  5462.8      .1       0  5580.6     .05       0
  6004.1     .16       0
Bank Sta=4970.7,5028.8
XS Rating Curve= 0 ,0
Exp/Cntr=0.3,0.1

Type RM Length L Ch R = 1 ,30130   ,1014,1014,1014
BEGIN DESCRIPTION:
BEE CREEK 27.0
END DESCRIPTION:
XS GIS Cut Line= 3
      3545560.13     10301092.98      3546402.11     10300329.12
      3546749.33     10299070.47
#Sta/Elev= 30
  4219.9   329.3  4239.6  328.98  4434.8  329.19  4710.5  324.52  4781.4  321.28
  4891.9  308.71  4915.9  304.82  4930.1  309.22    4953  310.21  4986.9  309.97
  4990.6  303.29  4993.4  302.79  4996.6  303.29  5029.5  304.45  5036.2  310.38
  5233.2  309.44  5426.7  308.13  5872.8  309.97  6013.8  308.34  6166.8  308.68
  6215.1  310.31  6280.3  310.27  6401.9  313.95  6479.7  319.17    6502  320.85
    6516  319.81  6536.4  321.85  6541.6  320.85  6598.9  329.26  6662.4  336.11
#Mann= 8 ,-1 , 0
  4219.9      .1       0  4239.6     .05       0  4891.9      .1       0
    4953     .16       0  4990.6     .07       0  4996.6     .16       0
  5233.2     .05       0  6479.7     .16       0
Bank Sta=4986.9,5036.2
XS Rating Curve= 0 ,0
Exp/Cntr=0.3,0.1

Type RM Length L Ch R = 1 ,29116   ,922,922,922
BEGIN DESCRIPTION:
BEE CREEK 25.0
END DESCRIPTION:
XS GIS Cut Line= 3
      3546150.35     10301257.95      3546792.74     10301040.92
       3547192.1     10299291.69
#Sta/Elev= 30
  4163.9  328.79  4239.9  327.32  4515.5  318.59    4547  316.15  4604.6  308.88
  4883.2  308.52  4964.3  309.72  4974.6  306.71  4984.8  300.81    4998  298.12
  5001.3  298.62  5005.3  303.07  5015.6  308.14  5025.8  309.29  5173.3  308.89
  5351.4  307.79  5436.1  307.47  5461.8  310.06  5491.6  311.55  5518.2  307.86
  5561.6  307.56  5661.5  307.66  5682.3  310.65  5716.7  308.34  5784.9  307.52
  5815.7  308.51  6174.7  307.36  6329.2  309.18  6569.2  322.07  6636.2  328.54
#Mann= 11 ,-1 , 0
  4163.9     .16       0  4239.9     .05       0  4883.2     .16       0
  4964.3     .07       0  5025.8     .16       0  5173.3     .05       0
  5351.4     .16       0  5461.8     .05       0  5561.6      .1       0
  5661.5     .05       0  6329.2     .16       0
#XS Ineff= 1 ,-1
 5486.36 5680.68  310.68
Permanent Ineff=
       F
Bank Sta=4964.3,5025.8
XS Rating Curve= 0 ,0
Exp/Cntr=0.3,0.1

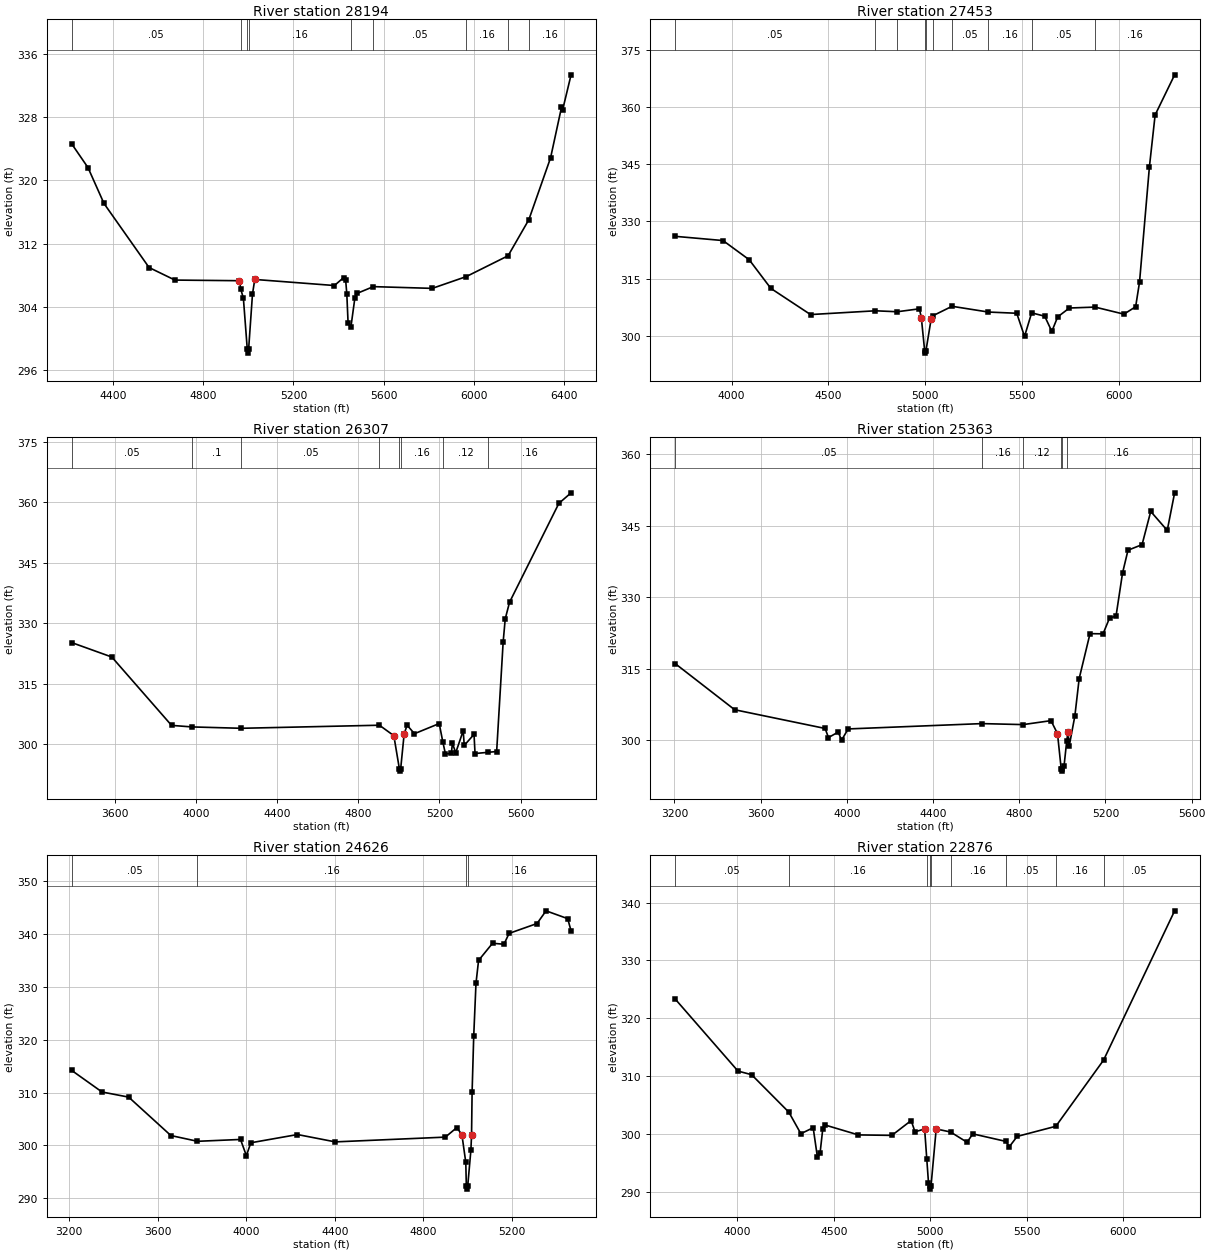
Type RM Length L Ch R = 1 ,28194   ,741,741,741
BEGIN DESCRIPTION:
BEE CREEK 24.0
END DESCRIPTION:
XS GIS Cut Line= 3
      3547593.84     10301482.95      3547493.84     10300882.96
      3547292.11     10299291.66
#Sta/Elev= 30
  4217.4  324.65  4289.7  321.64  4360.7  317.09  4560.4  308.98  4674.9  307.39
  4960.9  307.31  4966.5  306.24  4978.2  305.09  4995.4  298.64  4998.1  298.14
  5001.4  298.64  5018.5  305.62  5028.6  307.47  5381.4   306.7  5421.7  307.69
  5431.3  307.36  5436.3  305.64  5441.9  301.99  5454.3  301.41  5472.1  305.14
  5482.2  305.71  5553.8  306.56  5814.8  306.34  5965.3  307.83  6150.8  310.47
  6242.7  315.04    6339  322.88  6387.2  329.25  6392.2  328.93  6429.7  333.38
#Mann= 9 ,-1 , 0
  4217.4     .05       0  4966.5     .16       0  4995.4     .07       0
  5001.4     .16       0  5454.3     .12       0  5553.8     .05       0
  5965.3     .16       0  6150.8     .05       0  6242.7     .16       0
Bank Sta=4960.9,5028.6
XS Rating Curve= 0 ,0
Exp/Cntr=0.3,0.1

Type RM Length L Ch R = 1 ,27453   ,1146,1146,1146
BEGIN DESCRIPTION:
BEE CREEK 23.0
END DESCRIPTION:
XS GIS Cut Line= 3
      3548160.85     10301707.57      3548025.38     10300181.55
      3548142.11     10299141.61
#Sta/Elev= 30
  3708.6  326.07  3955.5  324.96  4090.6  319.93  4202.4  312.41  4407.3  305.54
  4742.2  306.53    4855  306.28  4969.5  307.05  4979.5  304.64  4996.8  295.92
  4999.5  295.42  5002.8  295.92  5029.7  304.26  5037.4  305.19    5138  307.71
  5325.5   306.2    5472  305.88  5512.2  299.81  5548.9  305.99  5616.3  305.11
  5653.1  301.12  5683.3  304.93  5743.7  307.26  5876.3   307.5  6025.4  305.65
  6085.8  307.59  6105.9  314.06  6156.9   344.3  6186.4  357.92  6287.1  368.45
#Mann= 10 ,-1 , 0
  3708.6     .05       0  4742.2     .16       0    4855     .05       0
  4996.8    .035       0  5002.8     .05       0  5037.4     .16       0
    5138     .05       0  5325.5     .16       0  5548.9     .05       0
  5876.3     .16       0
Bank Sta=4979.5,5029.7
XS Rating Curve= 0 ,0
Exp/Cntr=0.3,0.1

Type RM Length L Ch R = 1 ,26307   ,944,944,944
BEGIN DESCRIPTION:
BEE CREEK 22.0
END DESCRIPTION:
XS GIS Cut Line= 3
      3548650.38     10301553.08      3548832.67     10300216.27
      3549032.32     10299122.53
#Sta/Elev= 30
  3387.6   325.2  3585.6  321.62    3880  304.69  3979.9  304.31  4223.4  303.97
  4904.3  304.73  4975.3  302.14  5002.8  293.86  5005.5  293.36  5008.8  293.86
  5026.1  302.57  5040.6  304.74  5076.9  302.63  5198.9  305.14  5216.3  300.69
  5229.4  297.64  5258.8  297.74  5263.8  300.27  5280.2  297.91  5317.1  303.37
  5322.2  299.73  5370.4  302.46  5375.4  297.72  5439.8  298.02  5481.9  298.22
    5514  325.39  5524.2  331.07  5545.4  335.19  5788.5  359.68  5848.6  362.29
#Mann= 8 ,-1 , 0
  3387.6     .05       0  3979.9      .1       0  4223.4     .05       0
  4904.3     .16       0  5002.8     .07       0  5008.8     .16       0
  5216.3     .12       0  5439.8     .16       0
Bank Sta=4975.3,5026.1
XS Rating Curve= 0 ,0
Exp/Cntr=0.3,0.1

Type RM Length L Ch R = 1 ,25363   ,737,737,737
BEGIN DESCRIPTION:
BEE CREEK 21.0
END DESCRIPTION:
XS GIS Cut Line= 3
      3549362.18     10301553.09      3549613.92     10300051.34
      3549700.73      10299261.4
#Sta/Elev= 30
  3203.6  316.08  3479.6  306.39  3899.2  302.46  3914.8  300.55  3959.9   301.7
  3975.7  300.01  4006.1  302.36  4627.2  303.48  4817.7  303.27  4947.3   304.1
  4977.5  301.37  4994.6     294  4997.4   293.5  5000.6     294  5007.7   294.5
  5020.4  299.85  5026.5  301.79  5031.5  298.68    5058  305.06  5078.1  312.94
  5128.4  322.37  5188.8  322.33    5219  325.64  5249.1  326.06  5279.3   335.1
  5304.6  339.89  5369.9  341.06  5410.1  348.03  5486.7  344.05    5521  351.94
#Mann= 6 ,-1 , 0
  3203.6     .05       0  4627.2     .16       0  4817.7     .12       0
  4994.6     .07       0  5000.6     .12       0  5020.4     .16       0
Bank Sta=4977.5,5026.5
XS Rating Curve= 0 ,0
Exp/Cntr=0.3,0.1

Type RM Length L Ch R = 1 ,24626   ,1750,1750,1750
BEGIN DESCRIPTION:
BEE CREEK 20.0
END DESCRIPTION:
XS GIS Cut Line= 3
       3549978.5     10301518.38      3550117.39      10299981.9
      3550412.55     10299330.82
#Sta/Elev= 30
  3210.7   314.2    3348  310.11  3468.5  309.14  3659.3  301.87  3779.6  300.78
  3974.1  301.13  4000.6  298.06  4020.7   300.5  4231.6  302.06  4402.3  300.67
    4900  301.57  4951.7  303.37  4974.8  302.04  4992.4  296.78  4994.9  292.23
  4997.6  291.73  5000.9  292.23  5015.5  299.11 5018.47  302.02  5020.9  310.03
  5028.2  320.63  5038.5  330.69  5050.2  335.01  5113.3  338.25    5165  338.07
  5188.1  340.12  5314.5  341.99  5355.2  344.39    5453  342.91  5468.3  340.61
#Mann= 4 ,-1 , 0
  3210.7     .05       0  3779.6     .16       0  4994.9     .07       0
  5000.9     .16       0
Bank Sta=4974.8,5018.47
XS Rating Curve= 0 ,0
Exp/Cntr=0.3,0.1

Type RM Length L Ch R = 1 ,22876   ,2476,2476,2476
BEGIN DESCRIPTION:
BEE CREEK 18.0
END DESCRIPTION:
XS GIS Cut Line= 3
      3550186.86     10301874.22      3550837.88     10301075.65
      3550881.23     10299514.86
#Sta/Elev= 30
  3676.9  323.34  4002.8   310.9  4073.3  310.28  4266.6  303.81    4329  300.09
  4392.9  301.12  4415.2  295.99  4428.5   296.7  4442.4  300.83  4456.8  301.57
  4627.7  299.88  4801.3   299.8  4901.3  302.36  4921.3  300.42  4971.3   300.9
  4982.4  295.74  4991.3  291.63  4998.3  291.02  5001.1  290.52  5004.3  291.02
  5031.3  300.91  5106.1  300.38  5191.4  298.61  5221.4  300.06  5391.7  298.77
  5411.5  297.87  5451.5  299.62  5652.1  301.37    5900   312.8  6268.6  338.57
#Mann= 9 ,-1 , 0
  3676.9     .05       0  4266.6     .16       0  4982.4     .12       0
  4998.3     .07       0  5004.3     .12       0  5106.1     .16       0
  5391.7     .05       0  5652.1     .16       0    5900     .05       0
Bank Sta=4971.3,5031.3
XS Rating Curve= 0 ,0
Exp/Cntr=0.3,0.1

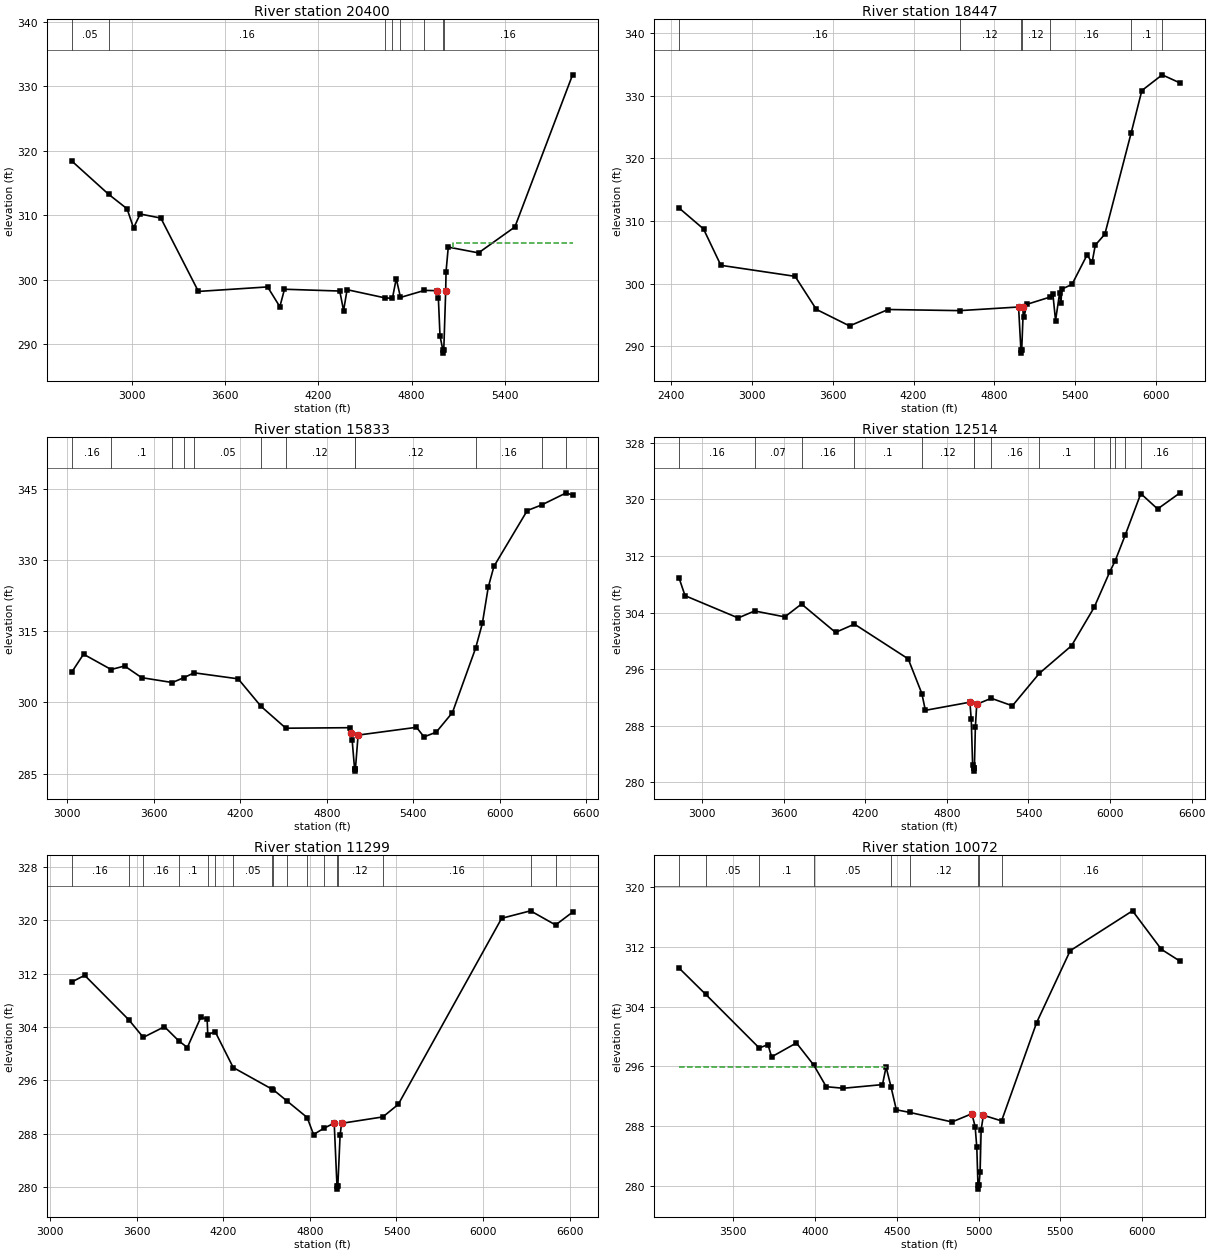
Type RM Length L Ch R = 1 ,20400   ,1953,1953,1953
BEGIN DESCRIPTION:
BEE CREEK 17.0
END DESCRIPTION:
XS GIS Cut Line= 3
      3552565.29     10301822.13      3551836.14     10299955.85
      3551419.47     10298810.02
#Sta/Elev= 30
  2613.2  318.41  2850.2  313.25  2969.4  310.99    3011  308.02  3053.9  310.18
  3186.7  309.55  3428.4  298.17  3873.7  298.87  3952.5   295.8  3982.4  298.51
  4338.1  298.23  4362.6  295.19  4385.2  298.44    4631  297.16    4677  297.11
  4701.5  300.16  4728.8  297.24    4883  298.33  4966.2  298.29  4972.5  297.17
  4983.1  291.27  5001.4   289.1  5004.1   288.6  5007.4   289.1  5019.6  298.17
    5022  301.26  5036.3  305.05  5230.9  304.15  5464.9  308.17  5836.1  331.77
#Mann= 8 ,-1 , 0
  2613.2     .05       0  2850.2     .16       0    4631     .12       0
    4677     .16       0  4728.8     .12       0    4883     .16       0
  5001.4     .07       0  5007.4     .16       0
#XS Ineff= 2 , 0
                         5067.33          305.61
Permanent Ineff=
       F       F
Bank Sta=4966.2,5019.6
XS Rating Curve= 0 ,0
Exp/Cntr=0.3,0.1

Type RM Length L Ch R = 1 ,18447   ,2614,2614,2614
BEGIN DESCRIPTION:
BEE CREEK 16.0
END DESCRIPTION:
XS GIS Cut Line= 3
      3553606.96     10301275.26      3552860.45     10299539.19
      3553181.62     10297742.34
#Sta/Elev= 30
  2461.7  312.06  2641.9  308.74  2770.5  302.94  3321.1  301.18  3478.7  295.91
    3725  293.27  4011.4  295.89  4541.9  295.71  4978.8  296.29  4996.1  289.43
  4998.9  288.93  5002.1  289.43  5014.4  296.23  5019.5  294.75  5039.8  296.71
  5210.4  297.86  5232.8  298.44  5253.1  294.13  5283.6  298.58  5293.6   296.9
  5298.7  299.14    5375  299.89  5486.7  304.59  5524.1   303.4  5547.7  306.15
  5618.8  307.91  5812.9  323.98  5893.1  330.82    6044  333.33  6176.8  332.03
#Mann= 7 ,-1 , 0
  2461.7     .16       0  4541.9     .12       0  4996.1     .07       0
  5002.1     .12       0  5210.4     .16       0  5812.9      .1       0
    6044     .16       0
Bank Sta=4978.8,5014.4
XS Rating Curve= 0 ,0
Exp/Cntr=0.3,0.1

Type RM Length L Ch R = 1 ,15833   ,3319,3319,3319
BEGIN DESCRIPTION:
BEE CREEK 15.0
END DESCRIPTION:
XS GIS Cut Line= 3
      3554223.29     10301092.96      3554014.96     10299461.06
      3553520.18     10297698.95
#Sta/Elev= 30
  3030.1  306.38  3112.1  310.17    3304  306.94  3397.1  307.69  3515.3  305.23
  3728.5   304.2  3810.7  305.26  3879.4  306.25  4185.1  304.98  4343.6  299.19
    4516  294.58  4961.8  294.69  4966.9  293.56  4975.9  292.12  4992.8  286.04
  4995.6  285.54  4998.8  286.04  5017.4  293.13  5422.5  294.77  5474.4  292.76
  5558.9  293.73  5671.8  297.87  5832.7  311.44  5879.5  316.65  5920.4  324.28
  5959.7  328.66  6191.1  340.43  6291.1  341.61    6462  344.16  6505.5  343.64
#Mann= 12 ,-1 , 0
  3030.1     .16       0    3304      .1       0  3728.5     .05       0
  3810.7      .1       0  3879.4     .05       0  4343.6      .1       0
    4516     .12       0  4992.8     .07       0  4998.8     .12       0
  5832.7     .16       0  6291.1      .1       0    6462     .16       0
Bank Sta=4966.9,5017.4
XS Rating Curve= 0 ,0
Exp/Cntr=0.3,0.1

Type RM Length L Ch R = 1 ,12514   ,1215,1215,1215
BEGIN DESCRIPTION:
BEE CREEK 14.0
END DESCRIPTION:
XS GIS Cut Line= 3
       3555021.9      10301101.7      3555377.81     10298384.67
      3554917.76     10297560.06
#Sta/Elev= 30
  2830.8  308.81  2873.5  306.38  3264.5  303.23  3385.6  304.22  3607.4  303.38
  3730.5   305.2  3980.6  301.19  4119.7  302.36  4515.1  297.45  4615.7  292.55
  4641.4  290.18    4969  291.33    4979  288.93  4989.1  282.46  4996.2  282.09
    4999  281.59  5002.2  282.09  5009.3  287.79  5019.4  291.04  5126.3  291.88
  5281.6  290.82  5479.1  295.39  5716.9  299.31  5883.1  304.72  5998.1  309.75
  6037.1  311.27  6113.1  315.01  6226.4   320.8  6349.9  318.63  6515.3  320.91
#Mann= 14 ,-1 , 0
  2830.8     .16       0  3385.6     .07       0  3730.5     .16       0
  4119.7      .1       0  4615.7     .12       0  4996.2     .07       0
  5002.2     .12       0  5126.3     .16       0  5479.1      .1       0
  5883.1     .16       0  5998.1      .1       0  6037.1     .16       0
  6113.1      .1       0  6226.4     .16       0
Bank Sta=4969,5019.4
XS Rating Curve= 0 ,0
Exp/Cntr=0.3,0.1

Type RM Length L Ch R = 1 ,11299   ,1227,1227,1227
BEGIN DESCRIPTION:
BEE CREEK 13.0
END DESCRIPTION:
XS GIS Cut Line= 3
      3555777.12     10300980.15      3556266.06     10298727.41
      3556466.07     10297577.36
#Sta/Elev= 30
  3148.5  310.72  3238.3  311.73    3545  305.04  3644.7  302.42  3791.6  304.02
  3889.1  301.93  3950.1   300.9  4043.3  305.42  4087.3  305.17  4091.9  302.83
  4142.9  303.28  4268.1   297.9  4538.5  294.64  4547.2  294.54  4641.2  292.88
    4781   290.4  4825.2  287.85  4898.8  288.81  4968.4  289.56  4987.6  280.16
  4990.3  279.66  4993.6  280.16  5009.3  287.78  5019.6  289.53  5305.7  290.49
  5412.5  292.37  6129.4  320.28  6329.6   321.4  6503.2  319.28    6621   321.2
#Mann= 17 ,-1 , 0
  3148.5     .16       0    3545     .05       0  3644.7     .16       0
  3889.1      .1       0  4091.9     .05       0  4142.9      .1       0
  4268.1     .05       0  4538.5     .12       0  4547.2     .05       0
  4641.2     .12       0    4781     .07       0  4898.8     .12       0
  4987.6     .07       0  4993.6     .12       0  5305.7     .16       0
  6329.6      .1       0  6503.2     .16       0
Bank Sta=4968.4,5019.6
XS Rating Curve= 0 ,0
Exp/Cntr=0.3,0.1

Type RM Length L Ch R = 1 ,10072   ,1417,1417,1417
BEGIN DESCRIPTION:
BEE CREEK 11.0
END DESCRIPTION:
XS GIS Cut Line= 3
      3556723.29     10300849.97      3557044.47     10298783.98
      3556662.52     10297889.85
#Sta/Elev= 30
    3169  309.17  3330.8  305.67  3658.5  298.47  3711.7  298.93    3734  297.28
  3885.8  299.15    3992  296.17    4068  293.28  4172.3  293.07  4412.1  293.56
    4434  295.93    4465  293.18  4496.9  290.18  4579.1  289.83  4837.1  288.55
  4958.6  289.65  4978.8  287.92  4988.9  285.13  4996.1  280.04  4998.8  279.54
  5002.1  280.04  5009.2  281.86  5015.4  287.52  5029.4  289.45  5140.3  288.69
  5354.9  301.88    5560  311.52  5941.2  316.87  6117.3  311.71  6232.1  310.11
#Mann= 9 ,-1 , 0
    3169     .16       0  3330.8     .05       0  3658.5      .1       0
    3992     .05       0    4465      .1       0  4579.1     .12       0
  4996.1     .07       0  5002.1     .12       0  5140.3     .16       0
#XS Ineff= 2 , 0
          4435.8  295.95
Permanent Ineff=
       F       F
Bank Sta=4958.6,5029.4
XS Rating Curve= 0 ,0
Exp/Cntr=0.3,0.1

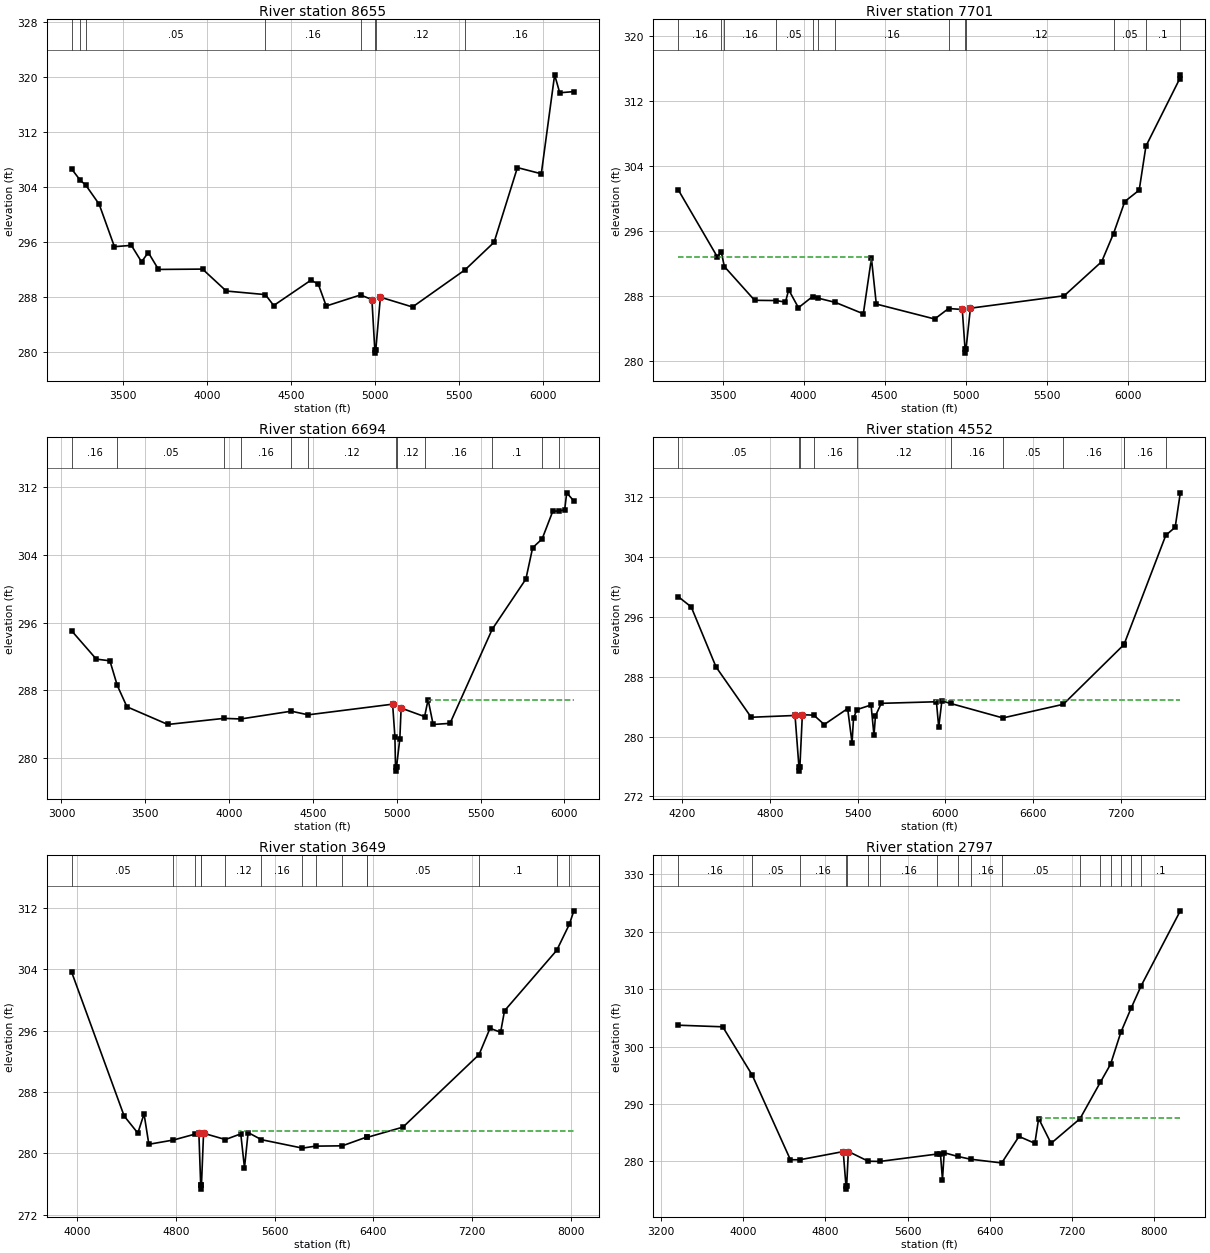
Type RM Length L Ch R = 1 ,8655    ,954,954,954
BEGIN DESCRIPTION:
BEE CREEK 9.0
END DESCRIPTION:
XS GIS Cut Line= 3
      3557921.21     10300643.38      3558108.71     10299094.74
      3557955.94     10297678.11
#Sta/Elev= 30
  3196.5  306.64  3247.7     305  3279.2  304.34  3359.4  301.54  3450.1  295.37
  3550.8  295.56  3611.2  293.17  3651.5  294.52    3712  292.06  3973.9  292.11
  4114.9  288.92  4347.5   288.4  4396.9  286.81  4618.5   290.5  4661.9  289.93
  4709.2  286.74  4913.1  288.35  4980.8  287.68    4998  280.39  5000.7  279.89
    5004  280.39  5031.1  288.03  5222.2   286.6  5534.9  292.01  5707.1  296.01
  5845.8  306.87  5987.8  305.97  6067.1  320.36  6097.3  317.75  6181.3  317.92
#Mann= 8 ,-1 , 0
  3196.5     .05       0  3247.7     .16       0  3279.2     .05       0
  4347.5     .16       0  4913.1     .12       0    4998     .07       0
    5004     .12       0  5534.9     .16       0
Bank Sta=4980.8,5031.1
XS Rating Curve= 0 ,0
Exp/Cntr=0.3,0.1

Type RM Length L Ch R = 1 ,7701    ,1007,1007,1007
BEGIN DESCRIPTION:
BEE CREEK 7.0
END DESCRIPTION:
XS GIS Cut Line= 3
      3558775.38     10300622.49      3558851.77     10298560.02
      3559163.84     10297575.26
#Sta/Elev= 30
  3226.8  301.05  3467.8   292.8  3492.9  293.35  3511.1  291.61    3698  287.45
  3828.8  287.42  3888.1  287.23  3908.1  288.74  3968.2  286.54  4055.3  287.91
  4088.6  287.72  4196.6  287.19  4368.4  285.79  4418.5  292.62  4448.5  286.99
  4808.7  285.15  4894.2  286.44  4978.8  286.32  4995.9  281.45  4998.6  280.95
  5001.9  281.45  5028.9  286.48  5607.6  288.01  5838.8  292.21  5911.8  295.67
  5981.3  299.61  6070.1  301.01  6111.6  306.42  6318.8  314.67  6323.7   315.2
#Mann= 13 ,-1 , 0
  3226.8     .16       0  3492.9     .05       0  3511.1     .16       0
  3828.8     .05       0  4055.3     .16       0  4088.6     .05       0
  4196.6     .16       0  4894.2     .12       0  4995.9     .07       0
  5001.9     .12       0  5911.8     .05       0  6111.6      .1       0
  6318.8     .16       0
#XS Ineff= 2 , 0
         4413.92  292.77
Permanent Ineff=
       F       F
Bank Sta=4978.8,5028.9
XS Rating Curve= 0 ,0
Exp/Cntr=0.3,0.1

Type RM Length L Ch R = 1 ,6694    ,2142,2142,2142
BEGIN DESCRIPTION:
BEE CREEK 6.0
END DESCRIPTION:
XS GIS Cut Line= 3
      3559983.71     10300365.56      3559642.11     10298441.64
      3559532.32     10297407.26
#Sta/Elev= 30
  3061.7     295  3207.9  291.67  3289.1  291.47    3333  288.56  3390.7  286.03
  3634.4  283.94  3969.1  284.66  4069.5  284.59  4370.9  285.51  4471.4  285.08
  4975.1  286.34  4988.7  282.51  4992.4  278.92  4995.1  278.42  4998.4  278.92
  5018.2  282.25  5025.8  285.88  5165.9  284.87  5186.7  286.88  5216.8  283.94
  5317.4  284.07  5569.3  295.21  5769.9  301.14  5810.1  304.84  5866.8  305.89
  5930.8  309.19    5966  309.17  6001.2  309.33  6013.4  311.34  6055.9  310.38
#Mann= 12 ,-1 , 0
  3061.7     .16       0    3333     .05       0  3969.1      .1       0
  4069.5     .16       0  4370.9      .1       0  4471.4     .12       0
  4992.4     .07       0  4998.4     .12       0  5165.9     .16       0
  5569.3      .1       0  5866.8     .16       0    5966     .05       0
#XS Ineff= 2 , 0
                         5189.49          286.86
Permanent Ineff=
       F       F
Bank Sta=4975.1,5025.8
XS Rating Curve= 0 ,0
Exp/Cntr=0.3,0.1

Type RM Length L Ch R = 1 ,4552    ,903,903,903
BEGIN DESCRIPTION:
BEE CREEK 5.0
END DESCRIPTION:
XS GIS Cut Line= 3
      3560797.08     10300340.41      3560829.63     10298821.31
      3559874.78     10297161.17
#Sta/Elev= 30
  4172.9  298.67  4261.7   297.3  4431.7  289.28  4671.8  282.57  4971.9  282.81
  4998.9  275.88  5001.6  275.38  5004.9  275.88  5021.9  282.91  5100.5  282.85
  5171.9   281.6  5331.9  283.73  5361.9  279.14  5371.9  282.45    5395  283.59
    5492  284.21    5512  280.14    5522  282.76    5562  284.43    5939  284.64
  5954.8  281.25  5976.4  284.75  6036.7  284.41  6393.6  282.48  6807.1   284.3
  7219.4  292.22  7222.6  292.29  7508.3  306.87  7572.3  307.93  7607.5  312.53
#Mann= 11 ,-1 , 0
  4172.9     .05       0  4998.9    .035       0  5004.9     .05       0
  5100.5     .16       0    5395     .12       0  6036.7     .16       0
  6393.6     .05       0  6807.1     .16       0  7219.4      .1       0
  7222.6     .16       0  7508.3     .05       0
#XS Ineff= 2 , 0
                         5929.55          284.86
Permanent Ineff=
       F       F
Bank Sta=4971.9,5021.9
XS Rating Curve= 0 ,0
Exp/Cntr=0.3,0.1

Type RM Length L Ch R = 1 ,3649    ,852,852,852
BEGIN DESCRIPTION:
BEE CREEK 4.0
END DESCRIPTION:
XS GIS Cut Line= 3
      3561524.07     10300264.49      3561665.13     10298864.71
      3560829.65     10296336.56
#Sta/Elev= 30
  3956.7  303.61  4381.3  284.88  4492.2  282.65  4542.5  285.16  4581.5  281.19
  4781.2  281.75  4956.1  282.52    4987  282.61  5001.8  275.84  5004.6  275.34
  5007.8  275.84  5024.9  282.63  5201.9  281.81  5326.5  282.55  5356.6  278.12
  5385.9  282.72  5494.4  281.79  5826.6  280.69  5932.6  280.95  6149.5  280.99
    6350  282.15  6352.4   282.1  6641.2  283.43  7258.1   292.9  7346.8  296.32
  7432.6  295.81  7464.3  298.61  7887.6   306.5  7990.3  309.91  8026.2  311.65
#Mann= 15 ,-1 , 0
  3956.7     .05       0  4781.2     .16       0  4956.1     .12       0
  5001.8     .07       0  5007.8     .12       0  5201.9     .12       0
  5494.4     .16       0  5826.6      .1       0  5932.6     .12       0
  6149.5     .05       0    6350     .12       0  6352.4     .05       0
  7258.1      .1       0  7887.6     .05       0  7990.3     .16       0
#XS Ineff= 2 , 0
                         5314.77          282.91
Permanent Ineff=
       F       F
Bank Sta=4987,5024.9
XS Rating Curve= 0 ,0
Exp/Cntr=0.3,0.1

Type RM Length L Ch R = 1 ,2797    ,1483,1483,1483
BEGIN DESCRIPTION:
BEE CREEK 3.0
END DESCRIPTION:
XS GIS Cut Line= 3
      3561686.83     10300568.27      3562478.94     10299797.87
       3562092.1      10296041.6
#Sta/Elev= 30
  3370.7  303.72  3803.4  303.44  4090.5  295.01  4461.1  280.29  4552.1  280.28
  4974.5  281.71  5001.7  275.67  5004.4  275.17  5007.7  275.67  5024.8  281.72
  5217.8  280.03  5328.9  279.99  5888.5  281.28  5919.5  281.37  5939.6  276.83
  5956.2  281.51  6086.8  280.87  6212.7  280.38  6515.4  279.73  6683.5  284.35
  6837.8  283.15  6874.5  287.47  6995.2  283.14  7276.5  287.43  7474.7  293.79
  7573.9  296.93    7673  302.45  7772.2  306.63  7871.3  310.59  8251.8  323.64
#Mann= 17 ,-1 , 0
  3370.7     .16       0  4090.5     .05       0  4552.1     .16       0
  5001.7     .07       0  5007.7     .16       0  5217.8     .12       0
  5328.9     .16       0  5888.5     .07       0  6086.8     .12       0
  6212.7     .16       0  6515.4     .05       0  7276.5      .1       0
  7474.7     .05       0  7573.9      .1       0    7673     .05       0
  7772.2     .16       0  7871.3      .1       0
#XS Ineff= 2 , 0
                         6879.55          287.57
Permanent Ineff=
       F       F
Bank Sta=4974.5,5024.8
XS Rating Curve= 0 ,0
Exp/Cntr=0.3,0.1

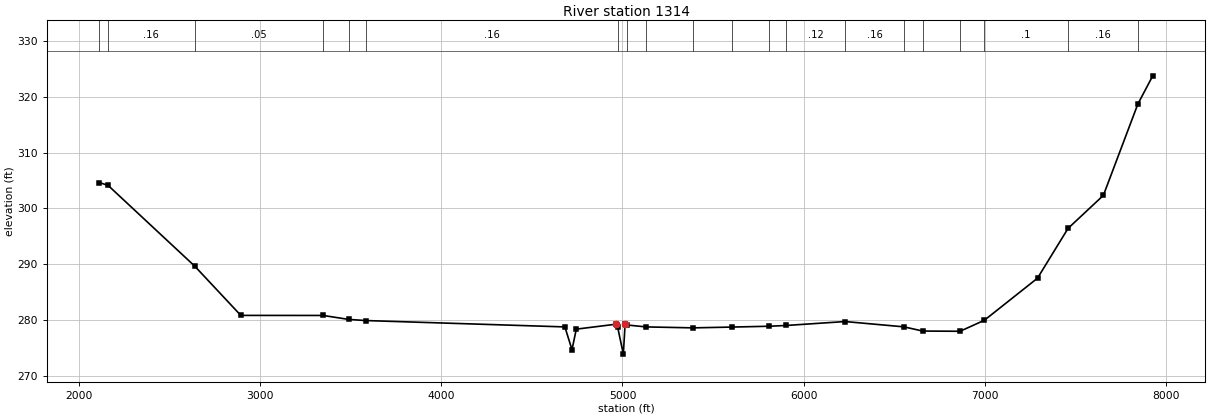
Type RM Length L Ch R = 1 ,1314    ,0,0,0
BEGIN DESCRIPTION:
BEE CREEK 1.0
END DESCRIPTION:
XS GIS Cut Line= 3
      3561827.91     10300958.88      3563661.66     10299396.39
      3562739.35     10296119.46
#Sta/Elev= 30
  2112.9  304.64  2161.2  304.12  2638.5   289.7  2893.7  280.86  3348.4  280.85
  3489.3  280.14  3582.4  279.94  4682.1   278.8  4721.3  274.72  4745.1   278.4
  4963.3  279.28  4973.7   278.7  5004.6  273.93  5014.4  279.29  5025.6  279.14
  5131.1   278.8  5390.8  278.63  5601.7  278.77    5810  278.92  5904.5  279.06
  6228.6  279.76  6553.5  278.81  6656.7  278.06    6863  278.02  6997.1  279.99
  7290.3  287.52  7458.9  296.43  7653.9  302.34  7844.1  318.68  7926.3  323.73
#Mann= 20 ,-1 , 0
  2112.9     .05       0  2161.2     .16       0  2638.5     .05       0
  3348.4     .05       0  3489.3     .05       0  3582.4     .16       0
  4973.7     .07       0  5025.6     .16       0  5131.1     .05       0
  5390.8     .16       0  5601.7     .05       0    5810     .16       0
  5904.5     .12       0  6228.6     .16       0  6553.5     .05       0
  6656.7      .1       0    6863     .05       0  6997.1      .1       0
  7458.9     .16       0  7844.1     .05       0
Bank Sta=4963.3,5014.4
XS Rating Curve= 0 ,0
Exp/Cntr=0.3,0.1

Chan Stop Cuts=-1
Use User Specified Reach Order=0
Composite Channel Slope=5