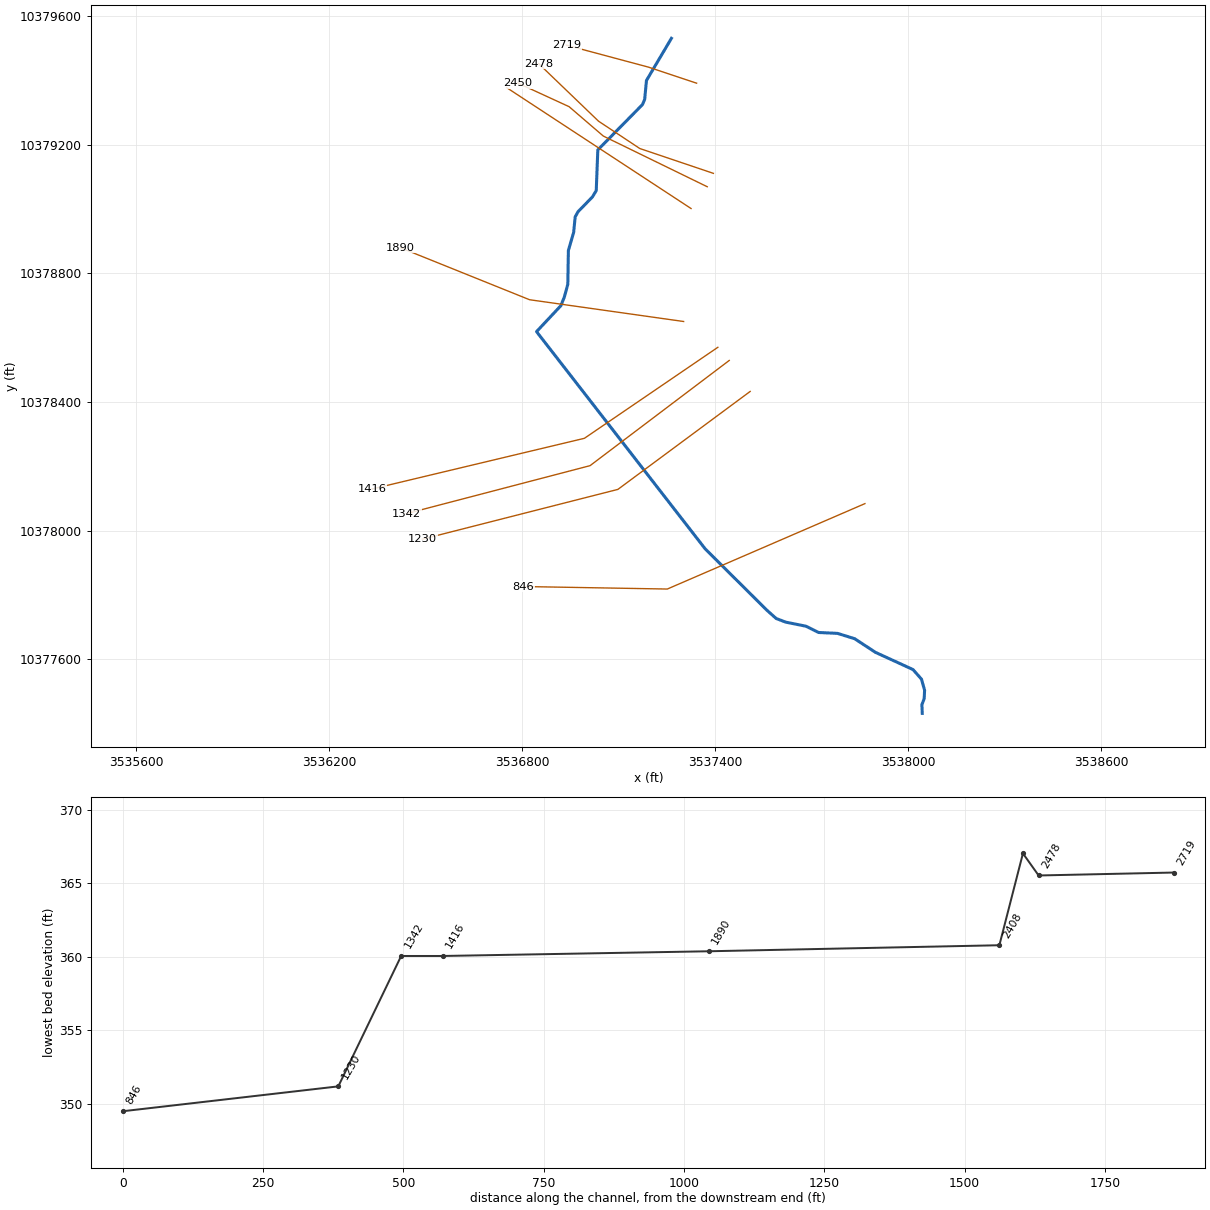
--- BOGGY BRANCH TRIBUTARY 2.prj (project) ---

Proj Title=BOGGY BRANCH TRIBUTARY 2 Base Level Engineering
Current Plan=p01
Default Exp/Contr=0.3,0.1
English Units
Geom File=g01
Flow File=f01
Plan File=p01
BEGIN DESCRIPTION:
BOGGY BRANCH TRIBUTARY 2
END DESCRIPTION:

--- BOGGY BRANCH TRIBUTARY 2.p01 (plan) ---

Plan Title=Multiple Run
Short Identifier=Multiple
Geom File=g01
Flow File=f01
Subcritical Flow
K Sum by GR= 0
Std Step Tol= 0.01
Critical Tol= 0.01
Num of Std Step Trials= 20
Max Error Tol= 0.3
Flow Tol Ratio= 0.001
Split Flow NTrial= 30
Split Flow Tol= 0.02
Split Flow Ratio= 0.02
Log Output Level= 0
Friction Slope Method= 1
Unsteady Friction Slope Method= 2
Unsteady Bridges Friction Slope Method= 1
Parabolic Critical Depth
Global Vel Dist=  1 , 1 , 1
Global Log Level= 0
CheckData=True
Encroach Param= -1, 0, 0, 0
BEGIN DESCRIPTION:
Multiple Run
END DESCRIPTION:

--- BOGGY BRANCH TRIBUTARY 2.f01 (steady flow) ---

Flow Title=Multiple
Number of Profiles=7
Profile Names=10-year,25-year,50-year,1pct_min,100-year,1pct_plu,500-year
River Rch & RM= BOGGY BRANCH TRI,Reach-1,2719
     808    1103    1343    1195    1616    2186    2333
Boundary for River Rch & Prof#=BOGGY BRANCH TRI,Reach-1,1
Up Type=0
Dn Type=3
Dn Slope=0.005
Boundary for River Rch & Prof#=BOGGY BRANCH TRI,Reach-1,2
Up Type=0
Dn Type=3
Dn Slope=0.005
Boundary for River Rch & Prof#=BOGGY BRANCH TRI,Reach-1,3
Up Type=0
Dn Type=3
Dn Slope=0.005
Boundary for River Rch & Prof#=BOGGY BRANCH TRI,Reach-1,4
Up Type=0
Dn Type=3
Dn Slope=0.005
Boundary for River Rch & Prof#=BOGGY BRANCH TRI,Reach-1,5
Up Type=0
Dn Type=3
Dn Slope=0.005
Boundary for River Rch & Prof#=BOGGY BRANCH TRI,Reach-1,6
Up Type=0
Dn Type=3
Dn Slope=0.005
Boundary for River Rch & Prof#=BOGGY BRANCH TRI,Reach-1,7
Up Type=0
Dn Type=3
Dn Slope=0.005

--- BOGGY BRANCH TRIBUTARY 2.g01 (geometry) ---

Geom Title=Existing Conditions

River Reach=BOGGY BRANCH TRI,Reach-1
Reach XY= 30
      3537263.76     10379531.10      3537186.12     10379399.98
      3537180.65     10379341.58      3537173.88     10379325.15
      3537034.87     10379184.11      3537029.97     10379057.53
      3537017.96     10379037.71      3536973.27     10378991.87
      3536964.42     10378975.68      3536959.77     10378927.61
      3536943.32     10378871.51      3536941.57     10378766.29
      3536930.90     10378727.03      3536920.01     10378699.71
      3536844.33     10378618.99      3537368.63     10377943.59
      3537560.59     10377752.64      3537589.40     10377727.00
      3537619.01     10377715.56      3537682.39     10377702.80
      3537721.28     10377683.35      3537780.31     10377680.58
      3537833.78     10377663.91      3537898.36     10377621.55
      3538015.03     10377568.08      3538041.42     10377538.21
      3538051.14     10377503.49      3538049.75     10377477.10
      3538042.81     10377459.05      3538043.85     10377431.79

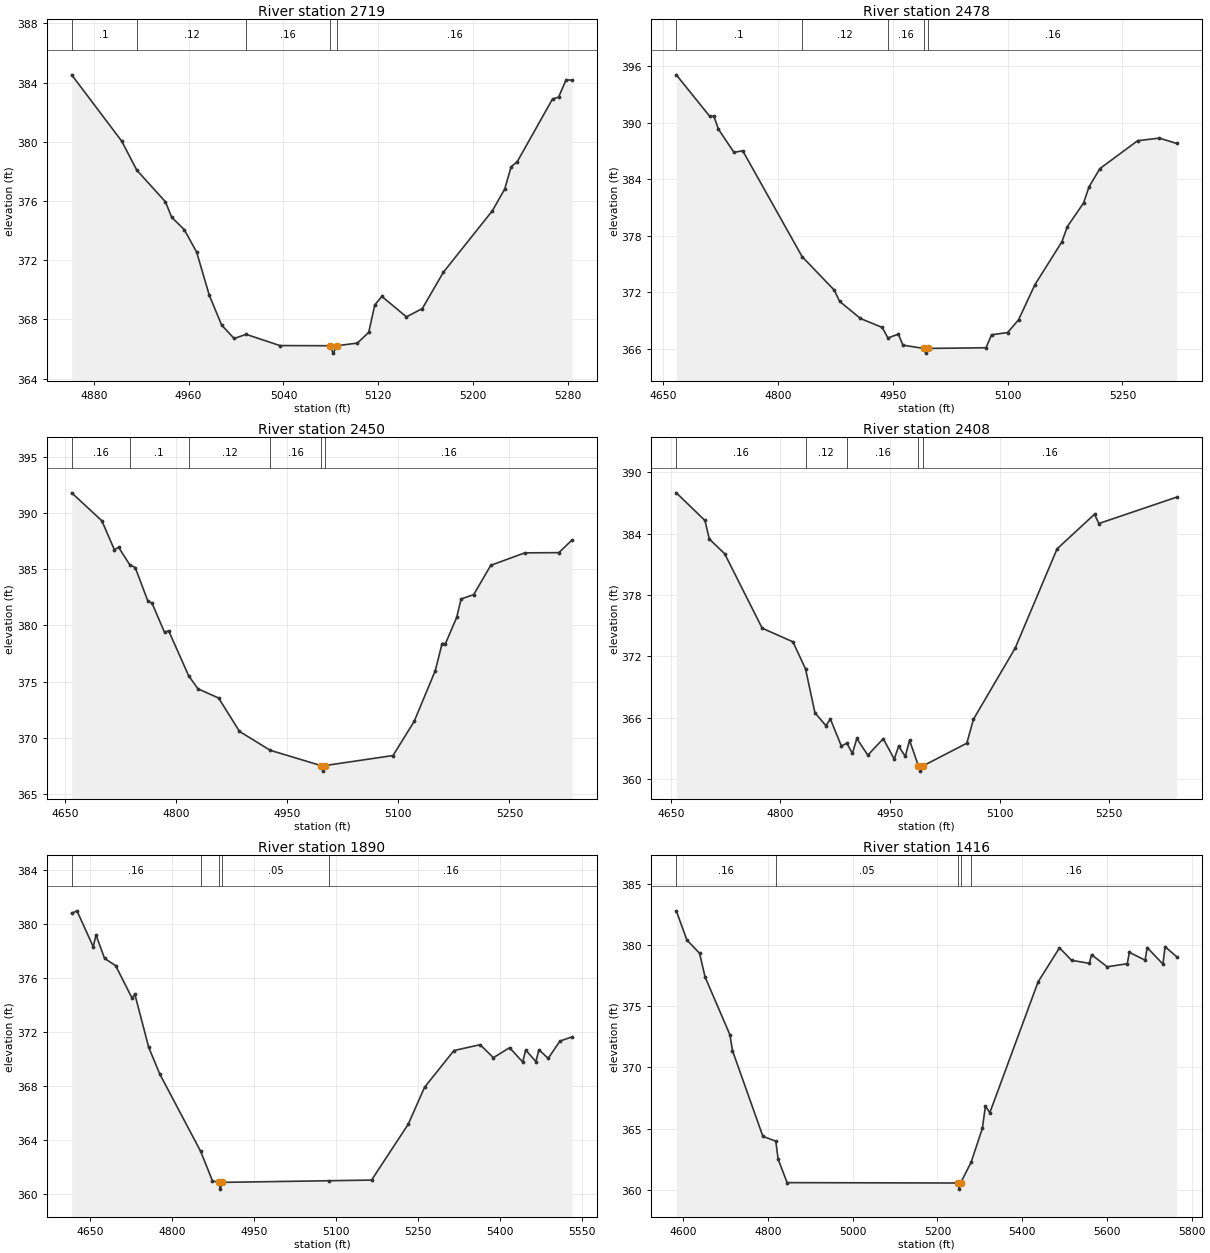
Type RM Length L Ch R = 1,2719,241,241,241
BEGIN DESCRIPTION:
BOGGY BRANCH TRIBUTARY 2 5.0
END DESCRIPTION:
XS GIS Cut Line= 3
      3537342.11     10379391.64      3537192.11     10379441.64
      3536937.19     10379509.86
#Sta/Elev= 30
  4861.4  384.52  4903.6  380.04  4916.3  378.08  4940.5  375.94  4945.7  374.90
  4956.3  374.07  4966.8  372.54  4977.4  369.64  4987.9  367.61  4998.4  366.71
  5008.5  366.99  5037.0  366.23  5079.2  366.22  5081.9  365.72  5085.2  366.22
  5102.3  366.40  5111.9  367.12  5117.0  368.98  5123.0  369.55  5143.7  368.17
  5157.1  368.73  5174.8  371.18  5216.2  375.34  5226.6  376.81  5232.0  378.31
  5237.2  378.66  5266.9  382.89  5272.0  383.01  5278.3  384.17  5283.4  384.17
#Mann=5,-1,0
  4861.4     0.1       0  4916.3    0.12       0  5008.5    0.16       0
  5079.2    0.07       0  5085.2    0.16       0
Bank Sta=5079.2,5085.2
Exp/Cntr=0.3,0.1

Type RM Length L Ch R = 1,2478,28,28,28
BEGIN DESCRIPTION:
Mapping XS 5b9caf97
END DESCRIPTION:
XS GIS Cut Line= 4
      3537394.33     10379111.20      3537165.52     10379188.41
      3537037.05     10379273.48      3536850.83     10379452.53
#Sta/Elev= 30
  4667.0  395.08  4710.8  390.66  4716.1  390.68  4722.1  389.30  4742.3  386.85
  4753.8  387.01  4831.4  375.77  4873.4  372.21  4880.4  371.02  4907.6  369.20
  4936.0  368.25  4943.6  367.13  4957.1  367.54  4963.1  366.37  4990.2  366.02
  4992.9  365.52  4996.2  366.02  5071.7  366.09  5079.0  367.47  5100.0  367.71
  5114.2  369.06  5135.6  372.79  5170.8  377.34  5178.0  378.96  5199.1  381.46
  5206.3  383.18  5220.5  385.12  5269.8  388.08  5298.2  388.36  5320.9  387.79
#Mann=5,-1,0
  4667.0     0.1       0  4831.4    0.12       0  4943.6    0.16       0
  4990.2    0.07       0  4996.2    0.16       0
Bank Sta=4990.2,4996.2
Exp/Cntr=0.3,0.1

Type RM Length L Ch R = 1,2450,42,42,42
BEGIN DESCRIPTION:
Mapping XS da5022b3
END DESCRIPTION:
XS GIS Cut Line= 4
      3537375.23     10379069.54      3537052.05     10379227.14
      3536945.47     10379318.62      3536786.04     10379391.95
#Sta/Elev= 30
  4659.1  391.82  4699.8  389.33  4716.8  386.74  4722.4  386.97  4737.5  385.41
  4744.9  385.16  4761.9  382.18  4767.4  382.01  4784.4  379.39  4790.0  379.53
  4817.0  375.52  4829.5  374.36  4857.5  373.53  4885.6  370.56  4927.0  368.88
  4995.3  367.52  4998.1  367.02  5001.3  367.52  5092.9  368.41  5121.4  371.45
  5149.9  375.97  5159.1  378.39  5163.7  378.39  5178.8  380.72  5184.8  382.36
  5201.8  382.75  5224.8  385.36  5270.7  386.47  5316.7  386.49  5334.6  387.62
#Mann=6,-1,0
  4659.1    0.16       0  4737.5     0.1       0  4817.0    0.12       0
  4927.0    0.16       0  4995.3    0.07       0  5001.3    0.16       0
Bank Sta=4995.3,5001.3
Exp/Cntr=0.3,0.1

Type RM Length L Ch R = 1,2408,518,518,518
BEGIN DESCRIPTION:
BOGGY BRANCH TRIBUTARY 2 4.0
END DESCRIPTION:
XS GIS Cut Line= 2
      3537324.90     10379001.81      3536751.70     10379377.59
#Sta/Elev= 30
  4657.3  387.98  4696.5  385.28  4702.5  383.47  4723.6  382.02  4774.9  374.75
  4817.0  373.42  4834.3  370.77  4847.2  366.48  4862.3  365.22  4868.3  365.88
  4883.4  363.23  4890.9  363.51  4898.5  362.51  4904.5  363.97  4919.6  362.34
  4940.7  363.95  4955.8  361.96  4961.8  363.22  4970.9  362.22  4976.8  363.80
  4988.9  361.28  4991.7  360.78  4994.9  361.28  5055.2  363.51  5064.3  365.85
  5121.5  372.81  5178.8  382.50  5230.1  385.89  5236.1  384.98  5342.7  387.56
#Mann=5,-1,0
  4657.3    0.16       0  4834.3    0.12       0  4890.9    0.16       0
  4988.9    0.07       0  4994.9    0.16       0
Bank Sta=4988.9,4994.9
Exp/Cntr=0.3,0.1

Type RM Length L Ch R = 1,1890,474,474,474
BEGIN DESCRIPTION:
BOGGY BRANCH TRIBUTARY 2 3.0
END DESCRIPTION:
XS GIS Cut Line= 3
      3537301.75     10378650.49      3536822.57     10378718.20
      3536421.50     10378879.68
#Sta/Elev= 30
  4615.8  380.77  4625.5  380.95  4655.3  378.29  4660.3  379.17  4676.0  377.43
  4696.2  376.90  4726.4  374.49  4731.4  374.79  4756.8  370.86  4777.0  368.89
  4852.0  363.16  4873.6  360.98  4885.1  360.87  4887.9  360.37  4891.1  360.87
  5086.6  360.99  5164.9  361.04  5232.2  365.18  5261.9  367.90  5315.8  370.62
  5363.8  371.05  5388.0  370.09  5417.6  370.83  5441.7  369.77  5447.1  370.66
  5465.9  369.80  5471.3  370.68  5488.3  370.04  5509.9  371.32  5532.1  371.63
#Mann=5,-1,0
  4615.8    0.16       0  4852.0    0.05       0  4885.1   0.033       0
  4891.1    0.05       0  5086.6    0.16       0
Bank Sta=4885.1,4891.1
Exp/Cntr=0.3,0.1

Type RM Length L Ch R = 1,1416,74,74,74
BEGIN DESCRIPTION:
BOGGY BRANCH TRIBUTARY 2 2.2
END DESCRIPTION:
XS GIS Cut Line= 3
      3537408.26     10378570.30      3536993.15     10378287.21
      3536332.94     10378129.65
#Sta/Elev= 30
  4583.6  382.78  4608.5  380.40  4638.4  379.32  4651.6  377.37  4710.2  372.65
  4716.2  371.36  4788.0  364.36  4818.4  363.97  4824.0  362.49  4845.2  360.58
  5248.6  360.55  5251.4  360.05  5254.6  360.55  5279.5  362.25  5306.0  365.01
  5313.3  366.84  5323.6  366.29  5437.5  376.97  5488.1  379.76  5516.5  378.74
  5558.6  378.49  5563.8  379.20  5600.7  378.21  5648.0  378.46  5653.1  379.39
  5690.1  378.75  5695.2  379.78  5732.2  378.43  5737.3  379.85  5764.8  379.03
#Mann=5,-1,0
  4583.6    0.16       0  4818.4    0.05       0  5248.6   0.033       0
  5254.6    0.05       0  5279.5    0.16       0
Bank Sta=5248.6,5254.6
Exp/Cntr=0.3,0.1

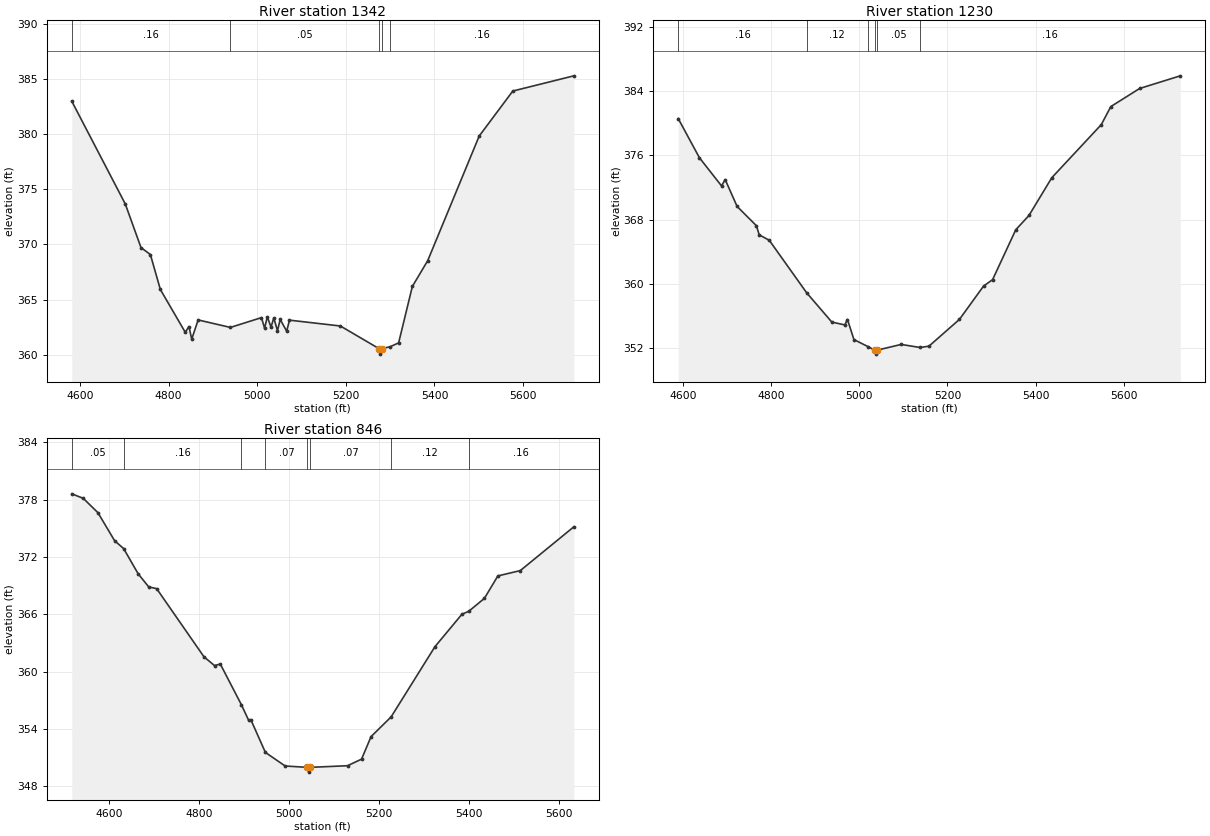
Type RM Length L Ch R = 1,1342,112,112,112
BEGIN DESCRIPTION:
BOGGY BRANCH TRIBUTARY 2 2.1
END DESCRIPTION:
XS GIS Cut Line= 3
      3537443.64     10378529.38      3537010.74     10378202.17
      3536439.58     10378052.87
#Sta/Elev= 30
  4581.5  382.98  4702.3  373.66  4737.7  369.71  4758.9  369.08  4781.4  365.91
  4837.6  362.03  4845.9  362.55  4852.2  361.41  4866.7  363.15  4939.5  362.47
  5009.6  363.36  5016.6  362.40  5022.8  363.43  5031.1  362.50  5037.4  363.33
  5045.7  362.18  5051.9  363.19  5066.5  362.13  5072.8  363.13  5187.7  362.60
  5274.8  360.55  5277.5  360.05  5280.8  360.55  5299.9  360.72  5319.1  361.07
  5350.1  366.19  5384.8  368.53  5500.9  379.82  5576.7  383.90  5714.5  385.28
#Mann=5,-1,0
  4581.5    0.16       0  4939.5    0.05       0  5274.8   0.033       0
  5280.8    0.05       0  5299.9    0.16       0
Bank Sta=5274.8,5280.8
Exp/Cntr=0.3,0.1

Type RM Length L Ch R = 1,1230,384,384,384
BEGIN DESCRIPTION:
BOGGY BRANCH TRIBUTARY 2 2.0
END DESCRIPTION:
XS GIS Cut Line= 3
      3537508.74     10378433.02      3537097.31     10378128.36
      3536489.29     10377973.42
#Sta/Elev= 30
  4589.1  380.60  4637.2  375.71  4687.3  372.20  4695.7  372.98  4722.7  369.63
  4766.6  367.22  4772.8  366.09  4795.8  365.40  4880.5  358.85  4937.7  355.19
  4967.0  354.84  4973.2  355.51  4987.8  353.01  5019.3  352.14  5034.9  351.69
  5037.6  351.19  5040.9  351.69  5095.0  352.40  5137.7  352.02  5158.0  352.18
  5227.3  355.53  5281.9  359.68  5302.5  360.49  5355.1  366.72  5385.0  368.50
  5436.9  373.22  5549.2  379.85  5570.8  382.10  5636.2  384.36  5728.5  385.94
#Mann=6,-1,0
  4589.1    0.16       0  4880.5    0.12       0  5019.3    0.05       0
  5034.9    0.07       0  5040.9    0.05       0  5137.7    0.16       0
Bank Sta=5034.9,5040.9
Exp/Cntr=0.3,0.1

Type RM Length L Ch R = 1,846,0,0,0
BEGIN DESCRIPTION:
BOGGY BRANCH TRIBUTARY 2 1.0
END DESCRIPTION:
XS GIS Cut Line= 3
      3537865.53     10378084.08      3537250.96     10377818.46
      3536803.04     10377826.28
#Sta/Elev= 30
  4516.5  378.62  4542.0  378.15  4574.7  376.65  4611.9  373.71  4632.0  372.89
  4664.3  370.25  4687.8  368.88  4705.4  368.70  4810.7  361.57  4834.2  360.65
  4847.1  360.81  4894.2  356.54  4910.2  354.92  4915.6  354.93  4947.5  351.56
  4991.5  350.14  5041.0  350.00  5043.7  349.50  5047.0  350.00  5130.3  350.17
  5161.5  350.86  5182.7  353.22  5227.3  355.28  5324.9  362.63  5384.9  366.02
  5400.1  366.33  5434.9  367.68  5464.9  370.03  5514.9  370.59  5634.0  375.17
#Mann=8,-1,0
  4516.5    0.05       0  4632.0    0.16       0  4894.2    0.12       0
  4947.5    0.07       0  5041.0    0.07       0  5047.0    0.07       0
  5227.3    0.12       0  5400.1    0.16       0
Bank Sta=5041,5047
Exp/Cntr=0.3,0.1

Chan Stop Cuts=-1