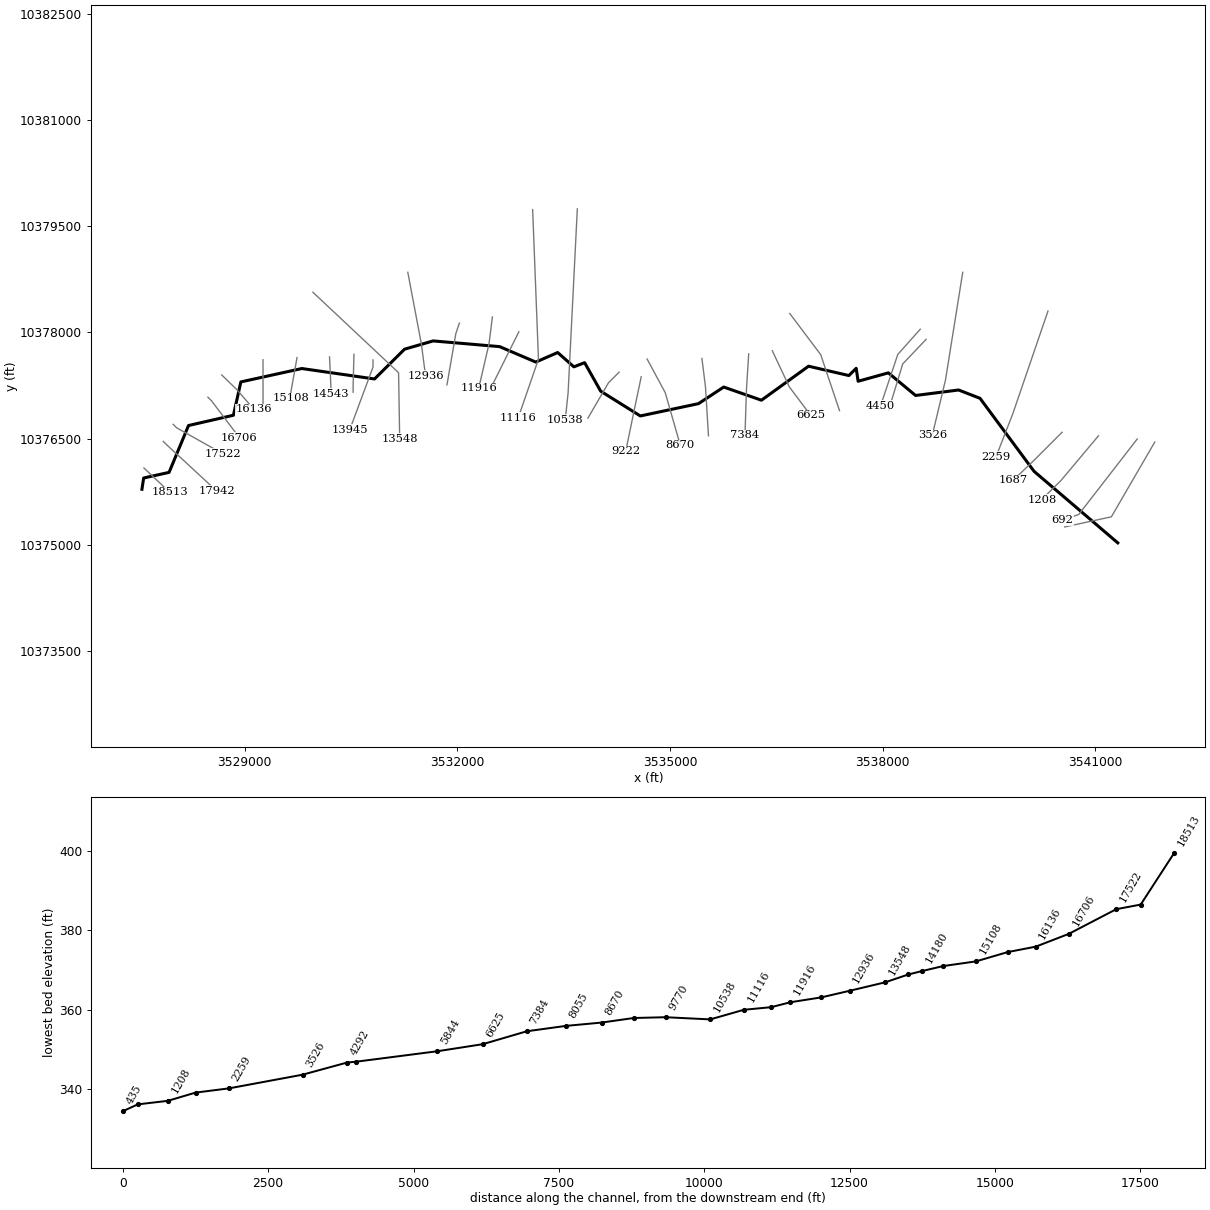
--- BOGGY BRANCH.prj (project) ---

Proj Title=BOGGY BRANCH Base Level Engineering
Current Plan=p01
Default Exp/Contr=0.3,0.1
English Units
Geom File=g01
Flow File=f01
Plan File=p01
BEGIN DESCRIPTION:
BOGGY BRANCH
END DESCRIPTION:

--- BOGGY BRANCH.p01 (plan) ---

Plan Title=Multiple Run
Short Identifier=Multiple
Geom File=g01
Flow File=f01
Subcritical Flow
K Sum by GR= 0
Std Step Tol= 0.01
Critical Tol= 0.01
Num of Std Step Trials= 20
Max Error Tol= 0.3
Flow Tol Ratio= 0.001
Split Flow NTrial= 30
Split Flow Tol= 0.02
Split Flow Ratio= 0.02
Log Output Level= 0
Friction Slope Method= 1
Unsteady Friction Slope Method= 2
Unsteady Bridges Friction Slope Method= 1
Parabolic Critical Depth
Global Vel Dist=  1 , 1 , 1
Global Log Level= 0
CheckData=True
Encroach Param= -1, 0, 0, 0
BEGIN DESCRIPTION:
Multiple Run
END DESCRIPTION:

--- BOGGY BRANCH.f01 (steady flow) ---

Flow Title=Multiple
Number of Profiles=7
Profile Names=10-year,25-year,50-year,1pct_min,100-year,1pct_plu,500-year
River Rch & RM= BOGGY BRANCH,Reach-1,18513
     718     972    1177    1042    1410    1906    2014
River Rch & RM= BOGGY BRANCH,Reach-1,13548
    1315    1843    2286    2066    2795    3779    4170
River Rch & RM= BOGGY BRANCH,Reach-1,10538
    1570    2215    2760    2505    3388    4582    5094
River Rch & RM= BOGGY BRANCH,Reach-1,8055
    1706    2413    3012    2736    3700    5004    5577
River Rch & RM= BOGGY BRANCH,Reach-1,4292
    2127    3039    3817    3488    4717    6380    7195
River Rch & RM= BOGGY BRANCH,Reach-1,2259
    2252    3223    4053    3707    5013    6780    7660
Boundary for River Rch & Prof#=BOGGY BRANCH,Reach-1,1
Up Type=0
Dn Type=3
Dn Slope=0.005
Boundary for River Rch & Prof#=BOGGY BRANCH,Reach-1,2
Up Type=0
Dn Type=3
Dn Slope=0.005
Boundary for River Rch & Prof#=BOGGY BRANCH,Reach-1,3
Up Type=0
Dn Type=3
Dn Slope=0.005
Boundary for River Rch & Prof#=BOGGY BRANCH,Reach-1,4
Up Type=0
Dn Type=3
Dn Slope=0.005
Boundary for River Rch & Prof#=BOGGY BRANCH,Reach-1,5
Up Type=0
Dn Type=3
Dn Slope=0.005
Boundary for River Rch & Prof#=BOGGY BRANCH,Reach-1,6
Up Type=0
Dn Type=3
Dn Slope=0.005
Boundary for River Rch & Prof#=BOGGY BRANCH,Reach-1,7
Up Type=0
Dn Type=3
Dn Slope=0.005

--- BOGGY BRANCH.g01 (geometry) ---

Geom Title=Existing Conditions

River Reach=BOGGY BRANCH,Reach-1
Reach XY= 30
      3527552.04     10375786.99      3527576.34     10375945.84
      3527934.78     10376025.32      3528209.17     10376686.54
      3528842.44     10376831.62      3528947.09     10377301.99
      3529806.90     10377490.87      3530832.13     10377343.51
      3531255.70     10377763.91      3531659.09     10377880.43
      3532596.39     10377799.95      3533106.69     10377581.99
      3533415.18     10377716.74      3533643.59     10377514.76
      3533795.14     10377573.53      3534021.62     10377171.35
      3534580.80     10376821.62      3535400.62     10376995.13
      3535756.85     10377229.39      3536288.78     10377043.81
      3536953.49     10377523.63      3537522.07     10377391.68
      3537625.37     10377494.11      3537652.25     10377311.35
      3538078.74     10377429.71      3538462.43     10377110.66
      3539069.20     10377187.91      3539371.28     10377070.72
      3540132.92     10376040.86      3541314.12     10375030.67

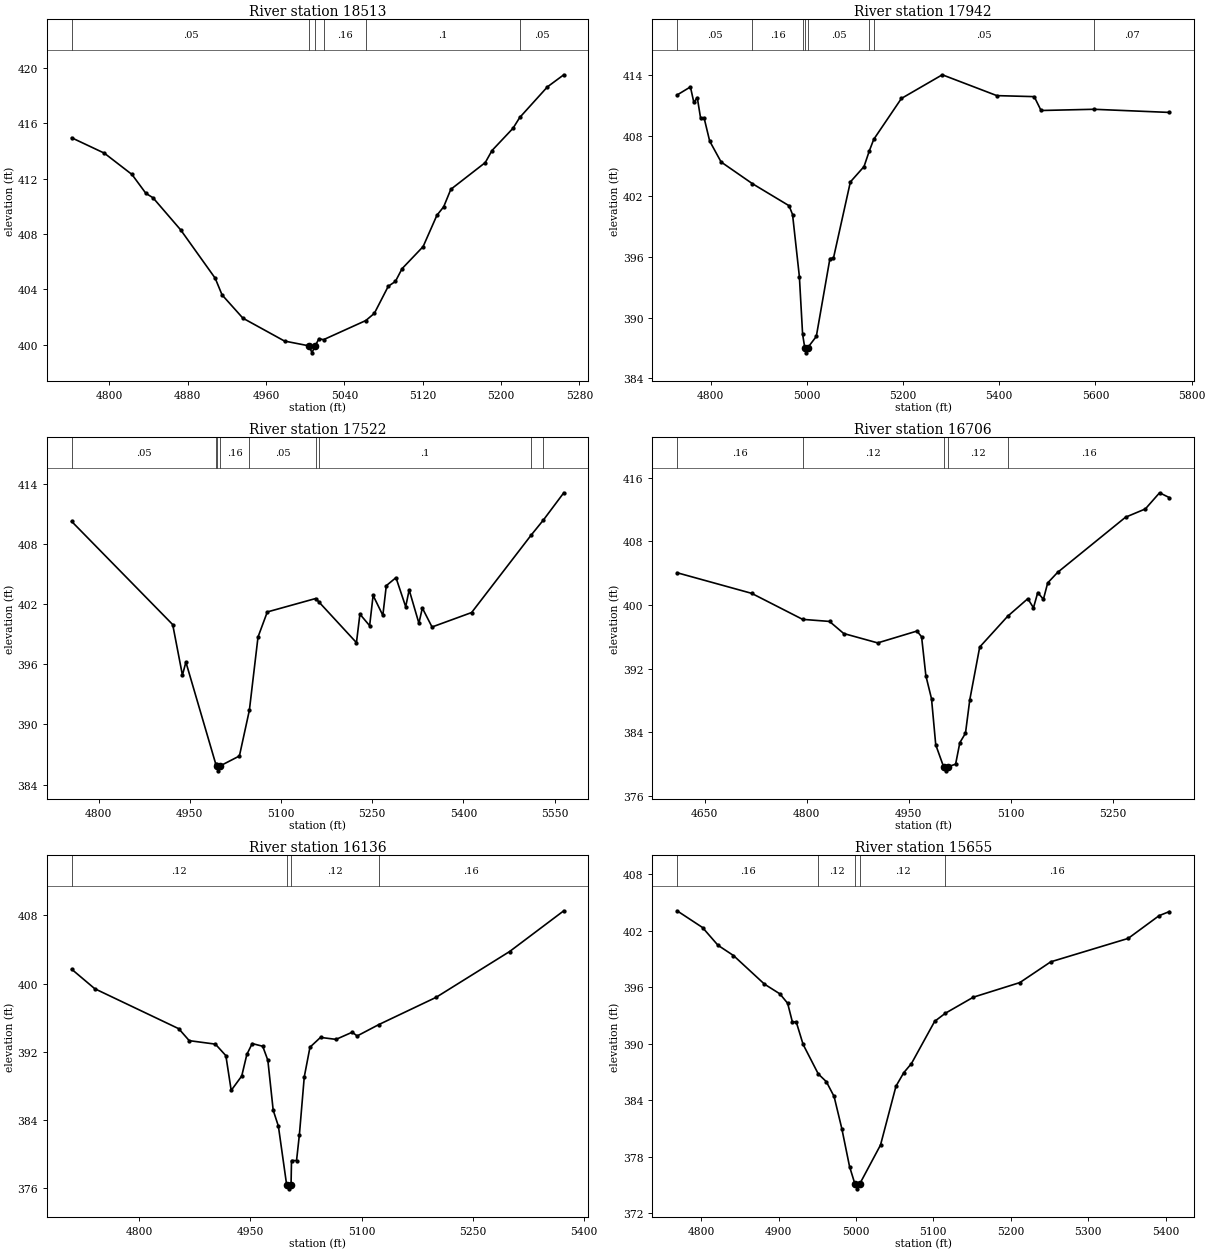
Type RM Length L Ch R = 1,18513,571,571,571
BEGIN DESCRIPTION:
BOGGY BRANCH 37.0
END DESCRIPTION:
XS GIS Cut Line= 2
      3527580.29     10376087.18      3527945.99     10375742.11
#Sta/Elev= 30
  4761.3  414.94  4794.7  413.83  4823.0  412.29  4837.2  410.93  4844.5  410.61
  4872.8  408.29  4908.0  404.81  4915.0  403.61  4936.3  401.93  4978.8  400.28
  5004.1  399.93  5006.8  399.43  5010.1  399.93  5014.0  400.45  5018.7  400.38
  5061.9  401.76  5070.6  402.28  5084.8  404.23  5092.1  404.58  5098.9  405.50
  5120.4  407.09  5134.5  409.35  5141.4  409.96  5148.7  411.22  5183.9  413.15
  5190.8  414.02  5212.2  415.62  5219.1  416.40  5247.4  418.61  5264.1  419.48
#Mann=6,-1,0
  4761.3    0.05       0  5004.1   0.035       0  5010.1    0.05       0
  5018.7    0.16       0  5061.9     0.1       0  5219.1    0.05       0
Bank Sta=5004.1,5010.1
Exp/Cntr=0.3,0.1

Type RM Length L Ch R = 1,17942,420,420,420
BEGIN DESCRIPTION:
BOGGY BRANCH 36.0
END DESCRIPTION:
XS GIS Cut Line= 3
      3527853.57     10376462.47      3527903.56     10376412.48
      3528602.96     10375765.87
#Sta/Elev= 30
  4730.2  412.01  4758.0  412.81  4765.1  411.28  4772.2  411.76  4779.2  409.71
  4786.3  409.77  4798.0  407.46  4821.8  405.39  4886.8  403.25  4963.0  401.07
  4970.3  400.20  4984.5  394.06  4991.2  388.37  4995.7  387.03  4998.4  386.53
  5001.7  387.03  5019.7  388.15  5048.0  395.85  5055.4  395.90  5090.5  403.42
  5118.9  404.94  5129.9  406.49  5139.1  407.63  5196.6  411.67  5281.6  414.01
  5395.0  411.95  5472.7  411.85  5486.9  410.48  5596.7  410.60  5753.4  410.29
#Mann=8,-1,0
  4730.2    0.05       0  4886.8    0.16       0  4991.2    0.05       0
  4995.7    0.07       0  5001.7    0.05       0  5129.9     0.1       0
  5139.1    0.05       0  5596.7    0.07       0
Bank Sta=4995.7,5001.7
Exp/Cntr=0.3,0.1

Type RM Length L Ch R = 1,17522,816,816,816
BEGIN DESCRIPTION:
BOGGY BRANCH 35.0
END DESCRIPTION:
XS GIS Cut Line= 3
      3527993.12     10376703.13      3528043.15     10376653.10
      3528687.14     10376291.13
#Sta/Elev= 30
  4755.6  410.24  4921.9  399.95  4937.9  394.91  4943.6  396.21  4992.8  386.03
  4994.2  385.87  4996.9  385.37  5000.2  385.87  5031.6  386.85  5048.0  391.41
  5062.2  398.71  5077.5  401.21  5157.1  402.55  5162.0  402.23  5224.1  398.15
  5229.8  400.99  5245.8  399.84  5251.5  402.86  5267.5  400.87  5273.2  403.83
  5289.1  404.63  5305.1  401.73  5310.8  403.41  5326.8  400.09  5332.5  401.60
  5348.4  399.71  5413.5  401.15  5511.7  408.89  5531.5  410.37  5565.1  413.09
#Mann=9,-1,0
  4755.6    0.05       0  4992.8    0.16       0  4994.2    0.07       0
  5000.2    0.16       0  5048.0    0.05       0  5157.1    0.16       0
  5162.0     0.1       0  5511.7    0.05       0  5531.5     0.1       0
Bank Sta=4994.2,5000.2
Exp/Cntr=0.3,0.1

Type RM Length L Ch R = 1,16706,570,570,570
BEGIN DESCRIPTION:
BOGGY BRANCH 34.0
END DESCRIPTION:
XS GIS Cut Line= 3
      3528482.74     10377086.42      3528532.73     10377036.43
      3528926.14     10376515.87
#Sta/Elev= 30
  4609.4  404.05  4719.0  401.46  4793.9  398.19  4833.4  397.93  4854.3  396.41
  4904.2  395.23  4961.9  396.72  4968.7  396.00  4975.0  391.10  4983.3  388.21
  4989.5  382.42  5001.1  379.65  5003.9  379.15  5007.1  379.65  5018.7  379.99
  5024.9  382.69  5033.2  383.88  5039.5  388.07  5054.1  394.71  5095.2  398.58
  5124.8  400.79  5133.1  399.64  5139.4  401.56  5147.7  400.71  5154.0  402.77
  5168.5  404.09  5268.4  411.03  5297.5  412.07  5318.4  414.10  5332.6  413.50
#Mann=5,-1,0
  4609.4    0.16       0  4793.9    0.12       0  5001.1    0.07       0
  5007.1    0.12       0  5095.2    0.16       0
Bank Sta=5001.1,5007.1
Exp/Cntr=0.3,0.1

Type RM Length L Ch R = 1,16136,481,481,481
BEGIN DESCRIPTION:
BOGGY BRANCH 32.0
END DESCRIPTION:
XS GIS Cut Line= 3
      3528676.74     10377400.49      3528892.11     10377191.64
      3529129.65     10376916.36
#Sta/Elev= 30
  4708.8  401.70  4740.1  399.40  4853.3  394.71  4867.4  393.31  4902.7  392.90
  4916.8  391.55  4924.0  387.47  4938.2  389.16  4945.1  391.69  4952.3  392.97
  4966.5  392.65  4973.4  391.01  4980.6  385.15  4987.6  383.28  4998.7  376.42
  5001.5  375.92  5004.7  376.42  5005.3  379.24  5012.1  379.24  5015.9  382.24
  5022.5  389.05  5030.2  392.54  5044.4  393.69  5065.3  393.46  5087.2  394.30
  5093.8  393.86  5122.9  395.19  5200.2  398.39  5299.4  403.77  5372.4  408.55
#Mann=4,-1,0
  4708.8    0.12       0  4998.7    0.07       0  5004.7    0.12       0
  5122.9    0.16       0
Bank Sta=4998.7,5004.7
Exp/Cntr=0.3,0.1

Type RM Length L Ch R = 1,15655,547,547,547
BEGIN DESCRIPTION:
BOGGY BRANCH 31.0
END DESCRIPTION:
XS GIS Cut Line= 3
      3529259.81     10377614.59      3529259.81     10377464.56
      3529260.07     10376978.59
#Sta/Elev= 30
  4768.8  404.14  4801.7  402.36  4821.7  400.47  4841.7  399.38  4881.7  396.34
  4901.7  395.30  4911.7  394.30  4917.8  392.32  4922.8  392.32  4931.7  389.92
  4951.3  386.78  4961.7  385.96  4971.7  384.39  4981.7  380.97  4991.7  376.93
  4998.7  375.06  5001.5  374.56  5004.7  375.06  5031.7  379.22  5051.7  385.48
  5061.7  386.91  5071.7  387.89  5101.7  392.38  5115.5  393.24  5151.7  394.95
  5211.7  396.50  5251.7  398.71  5351.7  401.20  5391.7  403.62  5404.8  404.05
#Mann=5,-1,0
  4768.8    0.16       0  4951.3    0.12       0  4998.7    0.07       0
  5004.7    0.12       0  5115.5    0.16       0
Bank Sta=4998.7,5004.7
Exp/Cntr=0.3,0.1

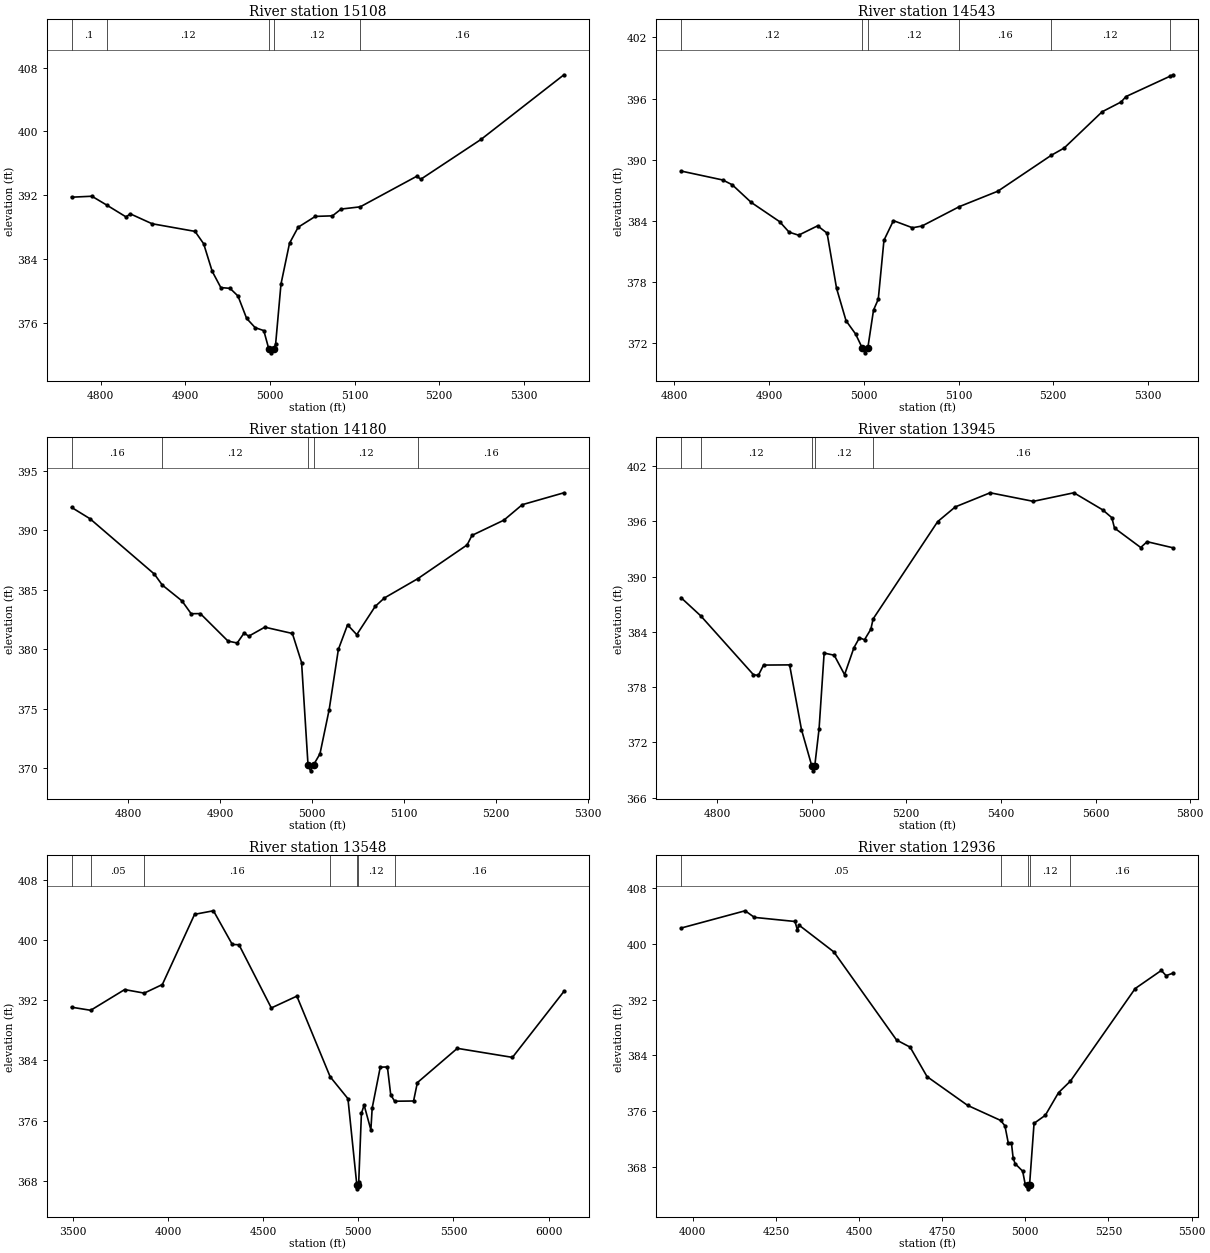
Type RM Length L Ch R = 1,15108,565,565,565
BEGIN DESCRIPTION:
BOGGY BRANCH 30.0
END DESCRIPTION:
XS GIS Cut Line= 3
      3529739.24     10377645.28      3529654.61     10377170.81
      3529654.61     10377070.77
#Sta/Elev= 30
  4765.5  391.74  4789.5  391.86  4806.9  390.76  4829.8  389.27  4834.9  389.65
  4860.6  388.41  4911.4  387.45  4921.6  385.90  4931.7  382.44  4941.9  380.40
  4952.8  380.30  4962.2  379.34  4972.4  376.53  4982.5  375.37  4992.7  375.00
  4998.6  372.71  5001.3  372.21  5004.6  372.71  5006.7  373.32  5013.0  380.83
  5023.1  385.96  5033.3  387.97  5053.6  389.33  5073.9  389.40  5084.1  390.25
  5106.7  390.53  5173.4  394.36  5178.4  394.00  5249.5  398.99  5347.5  407.10
#Mann=5,-1,0
  4765.5     0.1       0  4806.9    0.12       0  4998.6    0.07       0
  5004.6    0.12       0  5106.7    0.16       0
Bank Sta=4998.6,5004.6
Exp/Cntr=0.3,0.1

Type RM Length L Ch R = 1,14543,363,363,363
BEGIN DESCRIPTION:
BOGGY BRANCH 29.0
END DESCRIPTION:
XS GIS Cut Line= 3
      3530197.58     10377655.65      3530219.19     10377186.43
      3530219.19     10377136.55
#Sta/Elev= 30
  4807.1  388.88  4851.2  388.00  4861.2  387.53  4881.2  385.80  4911.2  383.91
  4921.2  382.88  4931.2  382.58  4951.3  383.50  4961.3  382.78  4971.3  377.36
  4981.3  374.18  4991.3  372.89  4998.3  371.53  5001.1  371.03  5004.3  371.53
  5010.3  375.23  5015.3  376.29  5021.3  382.08  5031.3  384.01  5051.4  383.31
  5061.4  383.48  5101.0  385.39  5141.5  386.90  5197.8  390.42  5211.5  391.14
  5251.6  394.70  5271.6  395.66  5276.7  396.19  5322.8  398.17  5326.7  398.33
#Mann=6,-1,0
  4807.1    0.12       0  4998.3    0.07       0  5004.3    0.12       0
  5101.0    0.16       0  5197.8    0.12       0  5322.8    0.16       0
Bank Sta=4998.3,5004.3
Exp/Cntr=0.3,0.1

Type RM Length L Ch R = 1,14180,235,235,235
BEGIN DESCRIPTION:
BOGGY BRANCH 28.0
END DESCRIPTION:
XS GIS Cut Line= 3
      3530542.11     10377691.63      3530530.65     10377256.23
      3530530.65     10377156.39
#Sta/Elev= 30
  4738.3  391.90  4758.3  390.95  4828.3  386.30  4836.9  385.38  4858.3  384.05
  4868.3  382.97  4878.3  382.98  4908.4  380.67  4918.4  380.51  4925.9  381.35
  4930.9  381.08  4948.4  381.84  4978.4  381.31  4988.4  378.87  4995.4  370.27
  4998.1  369.77  5001.4  370.27  5008.4  371.20  5018.4  374.91  5028.4  379.97
  5038.4  382.04  5048.4  381.21  5068.4  383.58  5078.4  384.29  5114.7  385.91
  5168.4  388.75  5173.7  389.55  5208.4  390.83  5228.4  392.13  5273.7  393.13
#Mann=5,-1,0
  4738.3    0.16       0  4836.9    0.12       0  4995.4    0.07       0
  5001.4    0.12       0  5114.7    0.16       0
Bank Sta=4995.4,5001.4
Exp/Cntr=0.3,0.1

Type RM Length L Ch R = 1,13945,397,397,397
BEGIN DESCRIPTION:
BOGGY BRANCH 27.0
END DESCRIPTION:
XS GIS Cut Line= 3
      3530810.86     10377611.48      3530810.86     10377511.43
      3530484.05     10376629.70
#Sta/Elev= 30
  4724.0  387.71  4766.0  385.72  4877.2  379.34  4887.4  379.27  4898.5  380.39
  4953.5  380.41  4978.6  373.39  5000.6  369.41  5003.4  368.91  5006.6  369.41
  5015.8  373.47  5026.5  381.69  5047.8  381.46  5069.7  379.35  5089.5  382.28
  5101.1  383.35  5111.8  383.14  5125.2  384.28  5130.0  385.40  5266.4  395.96
  5303.7  397.56  5377.3  399.09  5468.5  398.16  5554.3  399.09  5615.0  397.24
  5634.4  396.39  5640.1  395.26  5695.5  393.15  5709.0  393.78  5764.4  393.11
#Mann=5,-1,0
  4724.0    0.16       0  4766.0    0.12       0  5000.6    0.07       0
  5006.6    0.12       0  5130.0    0.16       0
Bank Sta=5000.6,5006.6
Exp/Cntr=0.3,0.1

Type RM Length L Ch R = 1,13548,612,612,612
BEGIN DESCRIPTION:
BOGGY BRANCH 26.0
END DESCRIPTION:
XS GIS Cut Line= 3
      3529963.23     10378567.13      3531171.53     10377431.74
      3531187.13     10376501.01
#Sta/Elev= 30
  3492.1  391.05  3592.4  390.64  3771.1  393.39  3874.0  392.92  3969.3  394.06
  4138.9  403.38  4238.0  403.85  4337.1  399.38  4372.3  399.34  4542.3  390.95
  4676.6  392.52  4851.6  381.82  4945.2  378.91  4992.0  367.44  4994.8  366.94
  4998.0  367.44  5001.9  367.87  5016.1  376.95  5030.2  378.06  5065.8  374.77
  5072.7  377.67  5115.2  383.09  5152.7  383.12  5170.2  379.42  5190.8  378.57
  5290.3  378.60  5310.3  381.04  5520.3  385.59  5810.3  384.39  6081.0  393.15
#Mann=7,-1,0
  3492.1    0.07       0  3592.4    0.05       0  3874.0    0.16       0
  4851.6    0.12       0  4992.0    0.07       0  4998.0    0.12       0
  5190.8    0.16       0
Bank Sta=4992,4998
Exp/Cntr=0.3,0.1

Type RM Length L Ch R = 1,12936,487,487,487
BEGIN DESCRIPTION:
BOGGY BRANCH 25.0
END DESCRIPTION:
XS GIS Cut Line= 3
      3531301.73     10378848.46      3531492.11     10377841.64
      3531551.73     10377390.12
#Sta/Elev= 30
  3964.8  402.30  4157.6  404.79  4185.5  403.84  4307.6  403.25  4314.7  402.03
  4319.8  402.72  4424.5  398.87  4612.9  386.20  4653.6  385.18  4704.5  380.94
  4826.6  376.80  4925.7  374.64  4938.6  373.87  4948.7  371.39  4958.2  371.39
  4963.3  369.25  4969.1  368.43  4992.0  367.34  4999.5  365.47  5006.6  365.30
  5009.4  364.80  5012.6  365.30  5026.2  374.22  5060.1  375.38  5099.7  378.63
  5135.6  380.30  5330.3  393.61  5408.8  396.21  5423.2  395.46  5444.9  395.84
#Mann=5,-1,0
  3964.8    0.05       0  4925.7    0.12       0  5006.6    0.07       0
  5012.6    0.12       0  5135.6    0.16       0
Bank Sta=5006.6,5012.6
Exp/Cntr=0.3,0.1

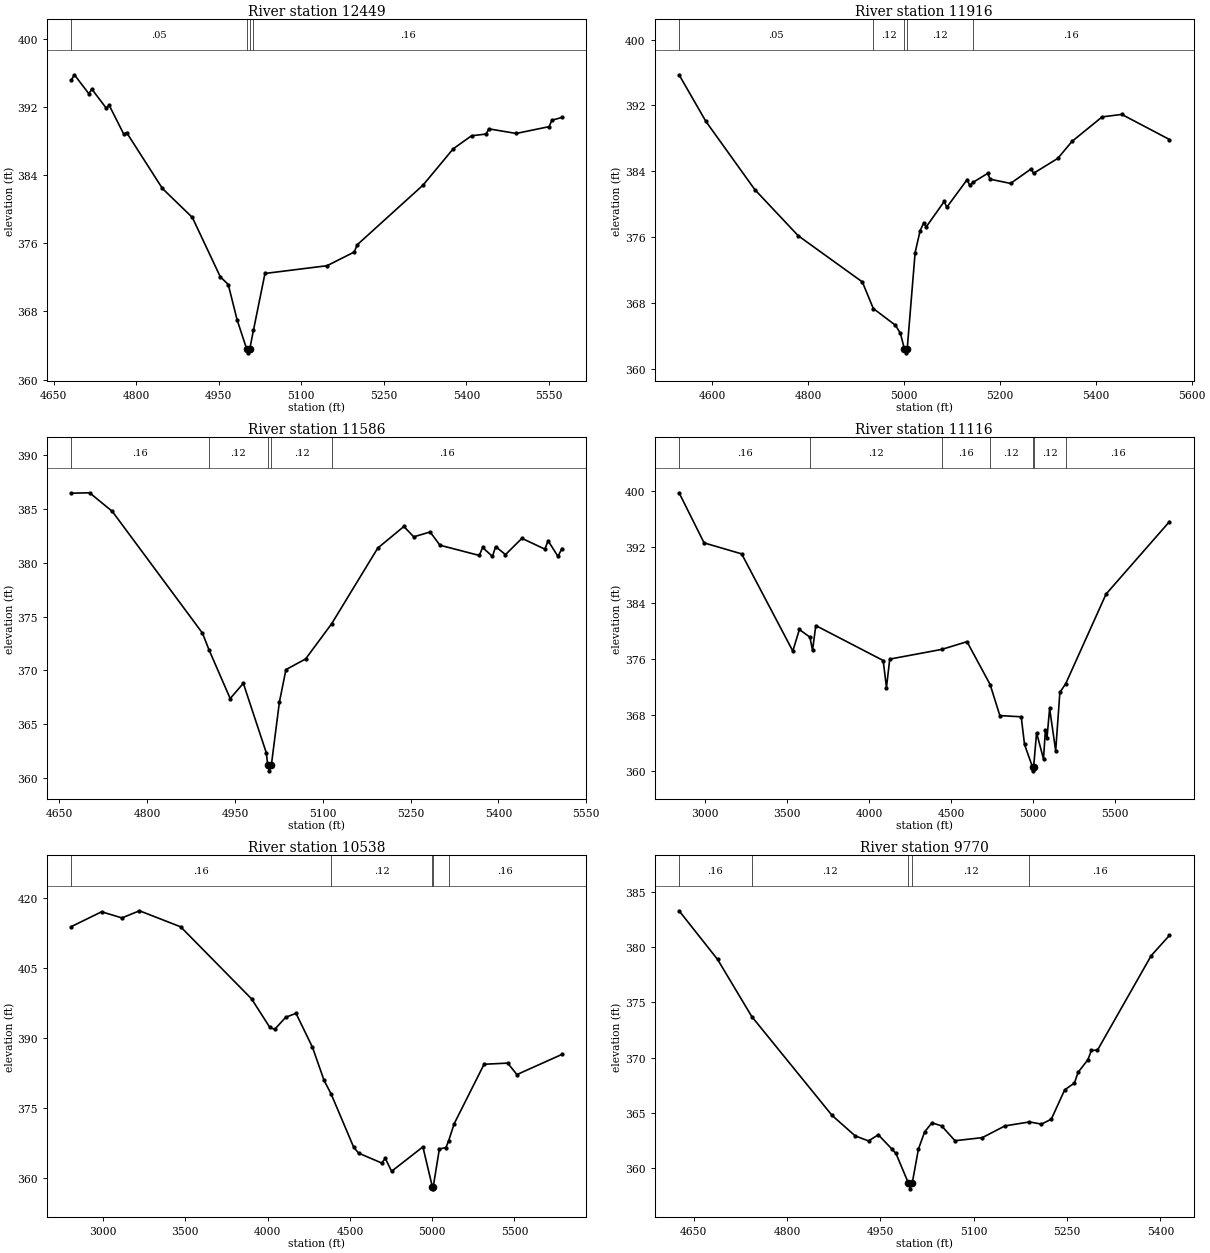
Type RM Length L Ch R = 1,12449,533,533,533
BEGIN DESCRIPTION:
BOGGY BRANCH 24.0
END DESCRIPTION:
XS GIS Cut Line= 3
      3532028.56     10378132.26      3531978.56     10377982.27
      3531853.82     10377259.87
#Sta/Elev= 30
  4682.3  395.21  4687.6  395.79  4713.9  393.56  4719.2  394.11  4745.5  391.87
  4750.8  392.21  4777.2  388.83  4782.4  389.01  4847.5  382.44  4901.9  379.04
  4952.7  372.07  4967.2  371.16  4983.1  367.05  5000.4  363.64  5003.2  363.14
  5006.4  363.64  5012.9  365.77  5033.9  372.46  5146.7  373.37  5196.2  374.98
  5201.4  375.82  5321.1  382.83  5375.9  387.09  5409.3  388.63  5435.7  388.83
  5440.8  389.44  5490.4  388.90  5550.3  389.70  5555.3  390.45  5573.5  390.78
#Mann=4,-1,0
  4682.3    0.05       0  5000.4   0.035       0  5006.4    0.05       0
  5012.9    0.16       0
Bank Sta=5000.4,5006.4
Exp/Cntr=0.3,0.1

Type RM Length L Ch R = 1,11916,330,330,330
BEGIN DESCRIPTION:
BOGGY BRANCH 23.0
END DESCRIPTION:
XS GIS Cut Line= 3
      3532494.45     10378218.19      3532447.57     10377843.20
      3532302.16     10377214.81
#Sta/Elev= 30
  4530.8  395.72  4586.4  390.08  4688.6  381.77  4779.3  376.15  4913.1  370.53
  4935.9  367.30  4982.2  365.26  4992.4  364.29  5000.7  362.41  5003.4  361.91
  5006.7  362.41  5023.2  374.11  5033.5  376.74  5041.2  377.74  5046.4  377.23
  5083.9  380.32  5089.1  379.60  5131.8  382.98  5136.9  382.27  5144.2  382.65
  5174.5  383.73  5179.6  383.02  5222.3  382.51  5265.0  384.27  5270.2  383.74
  5320.9  385.56  5350.4  387.62  5413.3  390.60  5454.3  390.90  5553.7  387.85
#Mann=5,-1,0
  4530.8    0.05       0  4935.9    0.12       0  5000.7    0.07       0
  5006.7    0.12       0  5144.2    0.16       0
Bank Sta=5000.7,5006.7
Exp/Cntr=0.3,0.1

Type RM Length L Ch R = 1,11586,470,470,470
BEGIN DESCRIPTION:
BOGGY BRANCH 22.0
END DESCRIPTION:
XS GIS Cut Line= 3
      3532868.13     10378009.32      3532768.15     10377809.35
      3532494.47     10377259.91
#Sta/Elev= 30
  4670.9  386.45  4701.8  386.49  4740.6  384.76  4894.5  373.46  4905.7  371.91
  4941.9  367.38  4964.3  368.80  5003.5  362.35  5006.1  361.17  5008.8  360.67
  5012.1  361.17  5025.9  367.05  5037.1  370.07  5070.7  371.06  5115.4  374.35
  5193.8  381.35  5238.5  383.36  5255.3  382.40  5283.3  382.85  5300.1  381.62
  5367.3  380.67  5372.9  381.41  5389.7  380.58  5395.2  381.49  5412.0  380.75
  5440.0  382.26  5479.2  381.26  5484.8  382.03  5501.6  380.58  5508.3  381.31
#Mann=5,-1,0
  4670.9    0.16       0  4905.7    0.12       0  5006.1    0.07       0
  5012.1    0.12       0  5115.4    0.16       0
Bank Sta=5006.1,5012.1
Exp/Cntr=0.3,0.1

Type RM Length L Ch R = 1,11116,578,578,578
BEGIN DESCRIPTION:
BOGGY BRANCH 21.0
END DESCRIPTION:
XS GIS Cut Line= 3
      3533062.16     10379733.82      3533144.19     10377622.89
      3532859.10     10376796.51
#Sta/Elev= 30
  2843.4  399.73  2995.7  392.57  3224.6  391.00  3536.1  377.12  3576.1  380.20
  3640.4  379.10  3656.2  377.24  3676.2  380.76  4086.5  375.77  4106.5  371.91
  4126.5  375.97  4443.8  377.36  4596.9  378.46  4737.8  372.34  4797.1  367.90
  4927.2  367.73  4947.2  363.79  4996.6  360.51  4999.3  360.01  5002.6  360.51
  5020.7  365.45  5063.0  361.70  5074.3  365.79  5084.2  364.71  5100.2  368.93
  5137.1  362.88  5162.6  371.21  5198.6  372.48  5443.9  385.26  5830.1  395.61
#Mann=7,-1,0
  2843.4    0.16       0  3640.4    0.12       0  4443.8    0.16       0
  4737.8    0.12       0  4996.6    0.07       0  5002.6    0.12       0
  5198.6    0.16       0
Bank Sta=4996.6,5002.6
Exp/Cntr=0.3,0.1

Type RM Length L Ch R = 1,10538,768,768,768
BEGIN DESCRIPTION:
BOGGY BRANCH 20.0
END DESCRIPTION:
XS GIS Cut Line= 3
      3533692.37     10379744.25      3533562.16     10377145.29
      3533522.31     10376769.72
#Sta/Elev= 30
  2808.3  413.96  2991.1  417.12  3114.8  415.81  3221.4  417.34  3471.7  413.89
  3902.3  398.42  4012.4  392.34  4042.5  391.84  4110.0  394.46  4172.6  395.30
  4272.7  388.00  4342.8  380.92  4386.3  377.94  4523.1  366.52  4553.1  365.26
  4693.3  363.14  4715.2  364.14  4753.3  361.36  4943.6  366.60  5000.7  358.09
  5003.4  357.59  5006.7  358.09  5043.7  366.15  5083.8  366.47  5100.2  367.94
  5133.8  371.59  5315.3  384.36  5458.9  384.61  5514.7  382.14  5788.2  386.47
#Mann=5,-1,0
  2808.3    0.16       0  4386.3    0.12       0  5000.7    0.07       0
  5006.7    0.12       0  5100.2    0.16       0
Bank Sta=5000.7,5006.7
Exp/Cntr=0.3,0.1

Type RM Length L Ch R = 1,9770,548,548,548
BEGIN DESCRIPTION:
BOGGY BRANCH 18.0
END DESCRIPTION:
XS GIS Cut Line= 3
      3534281.71     10377439.58      3534131.69     10377289.56
      3533842.09     10376791.62
#Sta/Elev= 30
  4626.3  383.28  4688.2  378.88  4743.1  373.72  4872.0  364.79  4909.3  362.93
  4930.8  362.47  4946.5  363.03  4968.0  361.76  4974.9  361.34  4995.0  358.64
  4997.8  358.14  5001.0  358.64  5011.0  361.73  5021.0  363.29  5032.7  364.11
  5048.3  363.83  5069.8  362.49  5113.7  362.77  5150.1  363.83  5189.5  364.19
  5208.8  363.99  5224.6  364.44  5246.1  367.09  5261.8  367.71  5267.6  368.67
  5283.3  369.81  5289.1  370.66  5298.8  370.68  5385.1  379.22  5414.5  381.06
#Mann=5,-1,0
  4626.3    0.16       0  4743.1    0.12       0  4995.0    0.07       0
  5001.0    0.12       0  5189.5    0.16       0
Bank Sta=4995,5001
Exp/Cntr=0.3,0.1

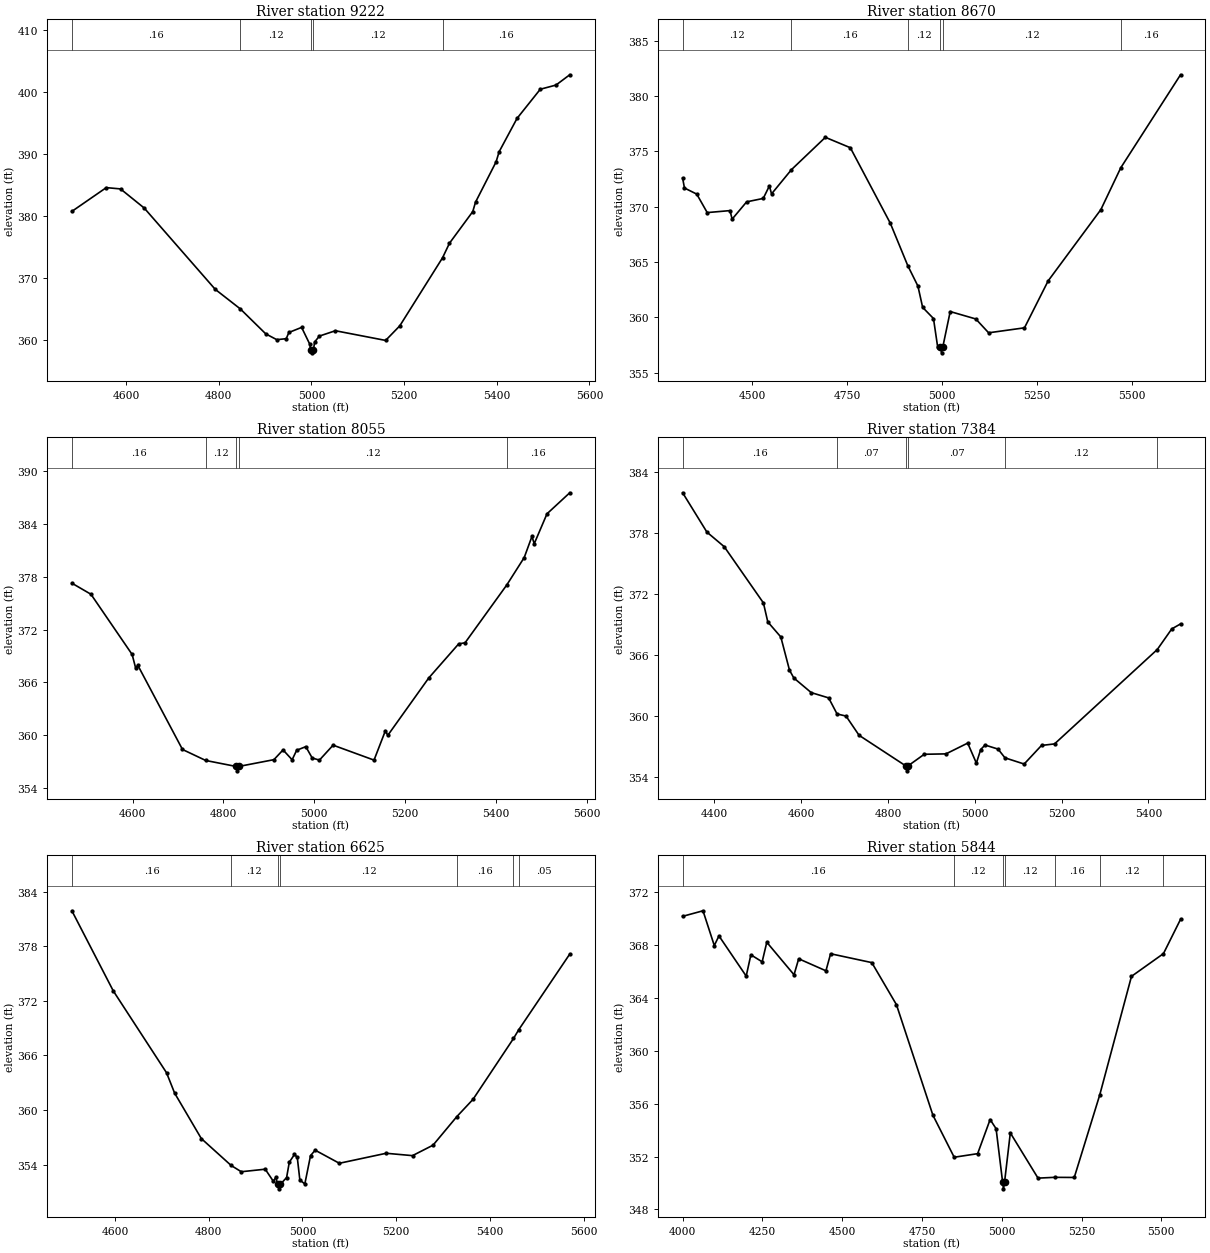
Type RM Length L Ch R = 1,9222,552,552,552
BEGIN DESCRIPTION:
BOGGY BRANCH 17.0
END DESCRIPTION:
XS GIS Cut Line= 3
      3534593.40     10377374.41      3534492.11     10376891.64
      3534374.67     10376322.41
#Sta/Elev= 30
  4482.9  380.73  4557.2  384.56  4587.9  384.35  4639.0  381.27  4792.3  368.17
  4846.4  365.02  4901.3  361.00  4925.1  360.06  4945.5  360.22  4951.2  361.22
  4978.7  362.04  4996.2  359.35  4998.3  358.44  5001.1  357.94  5004.3  358.44
  5006.8  359.68  5017.0  360.64  5051.6  361.50  5160.0  359.94  5190.6  362.29
  5282.9  373.26  5297.8  375.60  5348.1  380.70  5354.0  382.21  5398.4  388.71
  5405.0  390.34  5443.6  395.71  5493.8  400.41  5527.6  401.08  5557.4  402.74
#Mann=5,-1,0
  4482.9    0.16       0  4846.4    0.12       0  4998.3    0.07       0
  5004.3    0.12       0  5282.9    0.16       0
Bank Sta=4998.3,5004.3
Exp/Cntr=0.3,0.1

Type RM Length L Ch R = 1,8670,615,615,615
BEGIN DESCRIPTION:
BOGGY BRANCH 16.0
END DESCRIPTION:
XS GIS Cut Line= 3
      3534676.76     10377624.42      3534931.95     10377150.49
      3535145.36     10376406.15
#Sta/Elev= 30
  4316.3  372.57  4321.1  371.68  4353.5  371.13  4381.1  369.46  4441.2  369.64
  4446.8  368.87  4485.0  370.43  4528.8  370.74  4545.0  371.87  4550.7  371.15
  4603.2  373.34  4692.6  376.26  4758.4  375.32  4863.8  368.50  4909.8  364.67
  4936.6  362.82  4949.0  360.90  4977.6  359.89  4988.6  357.33  4996.0  357.29
  4998.8  356.79  5002.0  357.29  5021.7  360.52  5089.2  359.85  5123.0  358.60
  5217.5  359.05  5279.9  363.29  5418.9  369.73  5471.4  373.51  5628.9  381.91
#Mann=6,-1,0
  4316.3    0.12       0  4603.2    0.16       0  4909.8    0.12       0
  4996.0    0.07       0  5002.0    0.12       0  5471.4    0.16       0
Bank Sta=4996,5002
Exp/Cntr=0.3,0.1

Type RM Length L Ch R = 1,8055,671,671,671
BEGIN DESCRIPTION:
BOGGY BRANCH 14.0
END DESCRIPTION:
XS GIS Cut Line= 3
      3535449.40     10377633.27      3535499.40     10377233.31
      3535542.11     10376541.60
#Sta/Elev= 30
  4466.5  377.29  4508.5  376.03  4599.2  369.18  4606.7  367.68  4611.8  367.94
  4710.0  358.38  4761.1  357.13  4827.9  356.45  4830.7  355.95  4833.9  356.45
  4911.3  357.22  4931.4  358.33  4951.4  357.21  4961.4  358.29  4981.5  358.70
  4995.6  357.41  5011.5  357.17  5041.6  358.87  5131.7  357.17  5156.8  360.52
  5161.9  359.98  5252.0  366.50  5318.1  370.39  5332.1  370.51  5424.0  377.09
  5462.4  380.21  5479.4  382.61  5484.4  381.78  5512.5  385.18  5562.6  387.57
#Mann=5,-1,0
  4466.5    0.16       0  4761.1    0.12       0  4827.9    0.07       0
  4833.9    0.12       0  5424.0    0.16       0
Bank Sta=4827.9,4833.9
Exp/Cntr=0.3,0.1

Type RM Length L Ch R = 1,7384,759,759,759
BEGIN DESCRIPTION:
BOGGY BRANCH 13.0
END DESCRIPTION:
XS GIS Cut Line= 3
      3536109.03     10377697.38      3536077.78     10377197.37
      3536056.95     10376551.50
#Sta/Elev= 30
  4326.9  381.97  4382.8  378.10  4422.8  376.66  4513.0  371.13  4523.1  369.26
  4553.1  367.78  4573.1  364.51  4583.1  363.74  4623.2  362.30  4663.3  361.78
  4682.7  360.20  4703.4  359.99  4733.4  358.10  4840.6  355.10  4843.4  354.60
  4846.6  355.10  4883.6  356.23  4933.7  356.27  4983.7  357.33  5003.7  355.36
  5013.7  356.70  5023.7  357.14  5053.7  356.74  5069.6  355.88  5113.8  355.27
  5153.8  357.10  5183.8  357.25  5420.5  366.54  5453.9  368.57  5474.1  369.06
#Mann=6,-1,0
  4326.9    0.16       0  4682.7    0.07       0  4840.6    0.07       0
  4846.6    0.07       0  5069.6    0.12       0  5420.5    0.16       0
Bank Sta=4840.6,4846.6
Exp/Cntr=0.3,0.1

Type RM Length L Ch R = 1,6625,781,781,781
BEGIN DESCRIPTION:
BOGGY BRANCH 11.0
END DESCRIPTION:
XS GIS Cut Line= 3
      3536442.10     10377741.66      3536681.69     10377232.27
      3536981.67     10376832.29
#Sta/Elev= 30
  4507.7  381.91  4596.1  373.10  4709.8  364.10  4727.1  361.86  4784.0  356.87
  4847.7  353.91  4869.4  353.22  4920.5  353.50  4937.8  352.17  4943.3  352.62
  4946.8  351.84  4949.5  351.34  4952.8  351.84  4966.1  352.58  4971.9  354.27
  4982.9  355.12  4988.9  354.80  4994.4  352.32  5005.0  351.87  5017.2  354.99
  5027.1  355.59  5078.7  354.15  5178.7  355.25  5234.9  354.99  5278.7  356.14
  5329.5  359.28  5364.1  361.18  5450.5  367.87  5461.8  368.84  5570.6  377.15
#Mann=7,-1,0
  4507.7    0.16       0  4847.7    0.12       0  4946.8    0.07       0
  4952.8    0.12       0  5329.5    0.16       0  5450.5    0.12       0
  5461.8    0.05       0
Bank Sta=4946.8,4952.8
Exp/Cntr=0.3,0.1

Type RM Length L Ch R = 1,5844,1394,1394,1394
BEGIN DESCRIPTION:
BOGGY BRANCH 9.0
END DESCRIPTION:
XS GIS Cut Line= 3
      3536688.46     10378267.24      3537124.66     10377686.95
      3537390.06     10376895.94
#Sta/Elev= 30
  3999.9  370.17  4063.7  370.59  4099.1  367.96  4113.7  368.69  4199.1  365.65
  4213.7  367.26  4249.1  366.73  4263.6  368.21  4349.0  365.75  4363.6  366.96
  4449.0  366.05  4463.6  367.34  4592.7  366.67  4669.9  363.49  4784.2  355.13
  4850.9  351.95  4924.4  352.22  4963.5  354.80  4982.2  354.11  5002.7  350.06
  5005.4  349.56  5008.7  350.06  5026.8  353.79  5113.6  350.37  5165.5  350.43
  5227.2  350.42  5306.9  356.65  5406.5  365.63  5506.7  367.35  5560.2  369.94
#Mann=7,-1,0
  3999.9    0.16       0  4850.9    0.12       0  5002.7    0.07       0
  5008.7    0.12       0  5165.5    0.16       0  5306.9    0.12       0
  5506.7    0.16       0
Bank Sta=5002.7,5008.7
Exp/Cntr=0.3,0.1

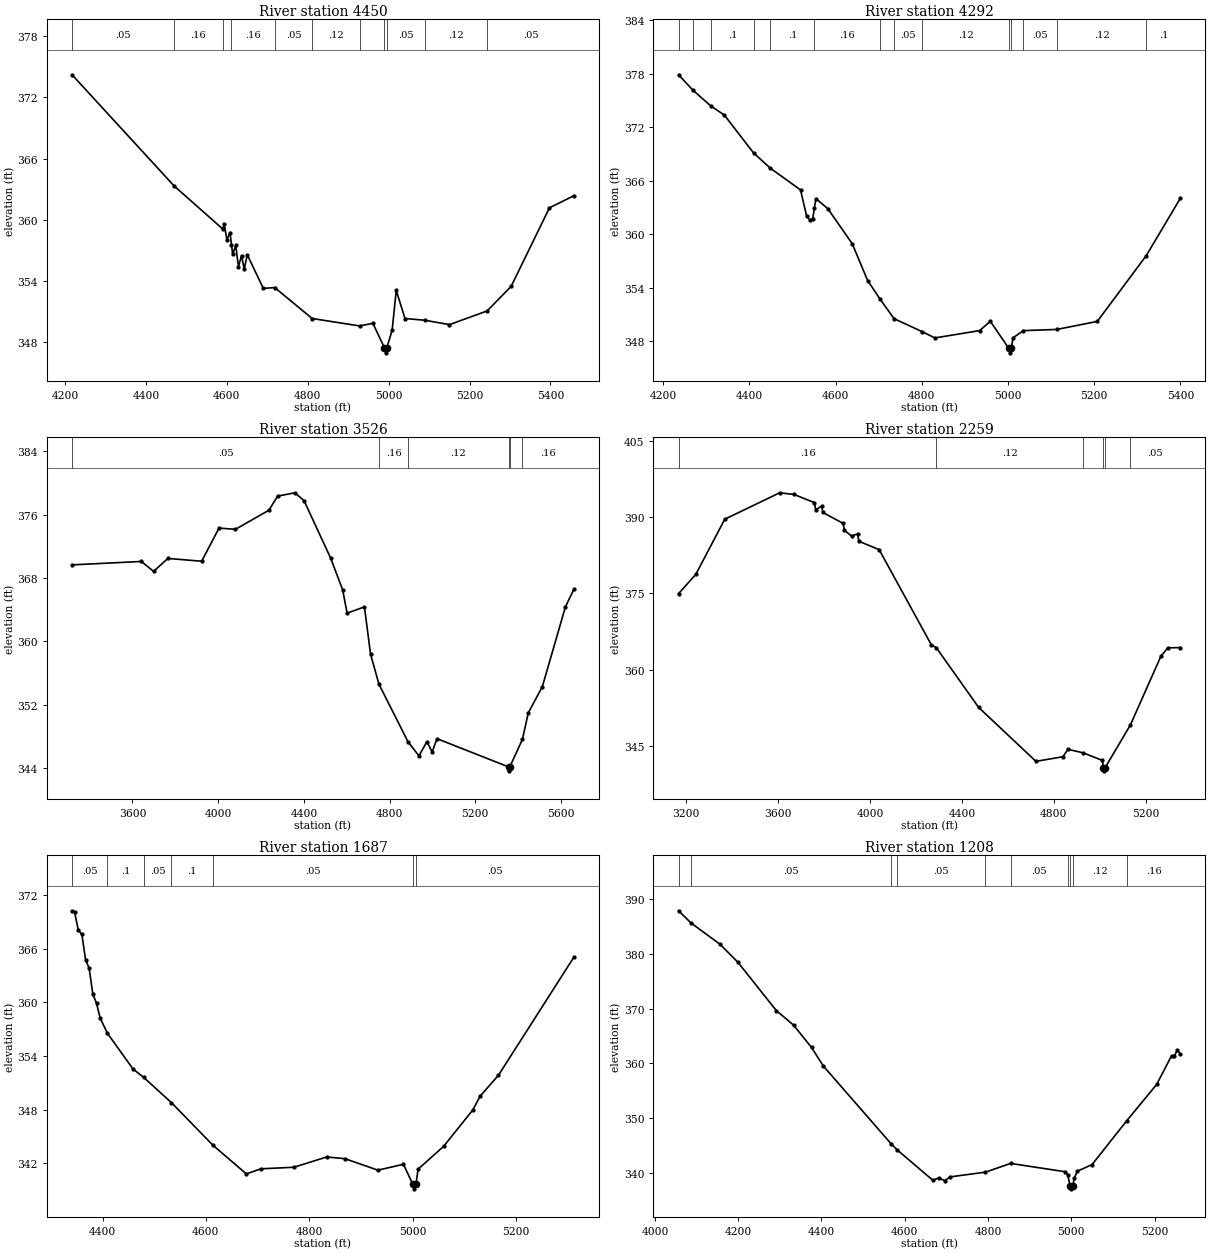
Type RM Length L Ch R = 1,4450,158,158,158
BEGIN DESCRIPTION:
BOGGY BRANCH 8.0
END DESCRIPTION:
XS GIS Cut Line= 3
      3538528.71     10378045.87      3538211.90     10377689.99
      3537969.08     10376965.89
#Sta/Elev= 30
  4217.7  374.22  4469.4  363.33  4589.7  359.10  4593.8  359.53  4600.5  358.01
  4608.0  358.74  4611.7  357.56  4614.7  356.60  4622.2  357.47  4628.9  355.38
  4636.5  356.48  4643.2  355.15  4650.7  356.56  4690.3  353.26  4718.7  353.33
  4811.1  350.30  4928.5  349.57  4961.1  349.83  4989.7  347.43  4992.4  346.93
  4995.7  347.43  5008.8  349.16  5018.9  353.06  5040.5  350.30  5089.0  350.13
  5150.4  349.70  5243.4  351.04  5302.9  353.45  5397.5  361.16  5457.9  362.35
#Mann=11,-1,0
  4217.7    0.05       0  4469.4    0.16       0  4589.7    0.05       0
  4611.7    0.16       0  4718.7    0.05       0  4811.1    0.12       0
  4928.5    0.05       0  4989.7    0.04       0  4995.7    0.05       0
  5089.0    0.12       0  5243.4    0.05       0
Bank Sta=4989.7,4995.7
Exp/Cntr=0.3,0.1

Type RM Length L Ch R = 1,4292,766,766,766
BEGIN DESCRIPTION:
BOGGY BRANCH 7.0
END DESCRIPTION:
XS GIS Cut Line= 3
      3538611.20     10377902.66      3538281.34     10377555.44
      3538081.70     10376900.10
#Sta/Elev= 30
  4235.6  377.86  4269.2  376.12  4310.9  374.35  4341.8  373.35  4409.9  369.09
  4448.7  367.39  4518.6  364.96  4532.7  362.03  4540.0  361.59  4546.9  361.74
  4550.6  362.89  4554.2  364.00  4582.1  362.85  4638.7  358.92  4674.3  354.81
  4702.5  352.77  4735.4  350.54  4801.3  349.07  4830.1  348.38  4933.9  349.20
  4958.9  350.24  5001.8  347.21  5004.5  346.71  5007.8  347.21  5011.2  348.38
  5035.5  349.20  5112.9  349.33  5207.0  350.23  5320.7  357.61  5399.6  364.02
#Mann=14,-1,0
  4235.6     0.1       0  4269.2    0.16       0  4310.9     0.1       0
  4409.9    0.16       0  4448.7     0.1       0  4550.6    0.16       0
  4702.5    0.12       0  4735.4    0.05       0  4801.3    0.12       0
  5001.8    0.07       0  5007.8    0.12       0  5035.5    0.05       0
  5112.9    0.12       0  5320.7     0.1       0
Bank Sta=5001.8,5007.8
Exp/Cntr=0.3,0.1

Type RM Length L Ch R = 1,3526,1267,1267,1267
BEGIN DESCRIPTION:
BOGGY BRANCH 6.0
END DESCRIPTION:
XS GIS Cut Line= 3
      3539127.70     10378848.88      3538884.64     10377329.75
      3538698.00     10376548.48
#Sta/Elev= 30
  3318.4  369.65  3641.7  370.08  3698.6  368.83  3765.7  370.46  3923.2  370.11
  4004.2  374.29  4081.0  374.14  4237.2  376.55  4277.7  378.33  4358.7  378.75
  4401.2  377.74  4525.3  370.49  4581.5  366.47  4601.8  363.55  4682.8  364.35
  4711.4  358.36  4750.6  354.58  4886.7  347.29  4937.3  345.54  4974.2  347.33
  4998.8  346.03  5021.5  347.71  5355.1  344.15  5357.9  343.65  5361.1  344.15
  5420.1  347.62  5447.4  350.97  5512.9  354.27  5620.9  364.36  5660.1  366.57
#Mann=6,-1,0
  3318.4    0.05       0  4750.6    0.16       0  4886.7    0.12       0
  5355.1    0.07       0  5361.1    0.12       0  5420.1    0.16       0
Bank Sta=5355.1,5361.1
Exp/Cntr=0.3,0.1

Type RM Length L Ch R = 1,2259,572,572,572
BEGIN DESCRIPTION:
BOGGY BRANCH 5.0
END DESCRIPTION:
XS GIS Cut Line= 3
      3540329.94     10378301.94      3539835.16     10376856.66
      3539597.41     10376245.93
#Sta/Elev= 30
  3167.3  374.96  3242.3  378.73  3368.4  389.56  3607.3  394.75  3669.9  394.42
  3758.5  392.81  3763.7  391.39  3789.8  392.15  3795.0  390.89  3883.6  388.74
  3888.9  387.37  3920.2  386.27  3946.2  386.68  3951.5  385.25  4040.1  383.59
  4266.9  364.94  4289.1  364.34  4472.9  352.64  4722.1  342.06  4839.8  342.97
  4861.3  344.43  4928.0  343.72  5011.5  342.24  5015.6  340.70  5018.4  340.20
  5021.6  340.70  5132.8  349.18  5266.1  362.71  5295.9  364.33  5350.3  364.38
#Mann=6,-1,0
  3167.3    0.16       0  4289.1    0.12       0  4928.0    0.07       0
  5015.6    0.07       0  5021.6    0.07       0  5132.8    0.05       0
Bank Sta=5015.6,5021.6
Exp/Cntr=0.3,0.1

Type RM Length L Ch R = 1,1687,479,479,479
BEGIN DESCRIPTION:
BOGGY BRANCH 4.0
END DESCRIPTION:
XS GIS Cut Line= 3
      3540528.93     10376591.67      3540128.91     10376191.64
      3539836.13     10375911.41
#Sta/Elev= 30
  4341.1  370.22  4345.9  370.09  4353.0  368.10  4360.1  367.58  4367.2  364.77
  4374.2  363.78  4381.3  360.89  4388.4  359.89  4395.4  358.23  4409.6  356.52
  4459.1  352.53  4479.4  351.61  4533.5  348.77  4613.2  344.04  4678.3  340.81
  4706.6  341.38  4770.2  341.55  4833.8  342.70  4869.2  342.51  4932.8  341.23
  4982.4  341.88  5000.5  339.64  5003.3  339.14  5006.5  339.64  5010.7  341.34
  5060.1  343.89  5116.7  347.97  5130.9  349.51  5166.1  351.83  5312.1  365.03
#Mann=7,-1,0
  4341.1    0.05       0  4409.6     0.1       0  4479.4    0.05       0
  4533.5     0.1       0  4613.2    0.05       0  5000.5    0.03       0
  5006.5    0.05       0
Bank Sta=5000.5,5006.5
Exp/Cntr=0.3,0.1

Type RM Length L Ch R = 1,1208,516,516,516
BEGIN DESCRIPTION:
BOGGY BRANCH 3.0
END DESCRIPTION:
XS GIS Cut Line= 3
      3541042.08     10376541.61      3540516.58     10375914.82
      3540242.09     10375641.63
#Sta/Elev= 30
  4056.7  387.93  4087.0  385.68  4156.2  381.81  4199.1  378.53  4291.5  369.68
  4333.1  367.00  4376.1  362.92  4404.7  359.51  4567.5  345.28  4581.5  344.21
  4667.5  338.63  4681.8  339.07  4696.1  338.55  4709.1  339.25  4793.7  340.11
  4854.2  341.71  4986.1  340.18  4991.8  339.54  4997.2  337.56  5000.0  337.06
  5003.2  337.56  5007.3  339.03  5014.4  340.28  5049.8  341.49  5133.3  349.53
  5205.3  356.18  5240.7  361.40  5247.8  361.40  5254.8  362.45  5261.9  361.72
#Mann=10,-1,0
  4056.7    0.16       0  4087.0    0.05       0  4567.5    0.12       0
  4581.5    0.05       0  4793.7    0.12       0  4854.2    0.05       0
  4991.8    0.12       0  4997.2    0.07       0  5003.2    0.12       0
  5133.3    0.16       0
Bank Sta=4997.2,5003.2
Exp/Cntr=0.3,0.1

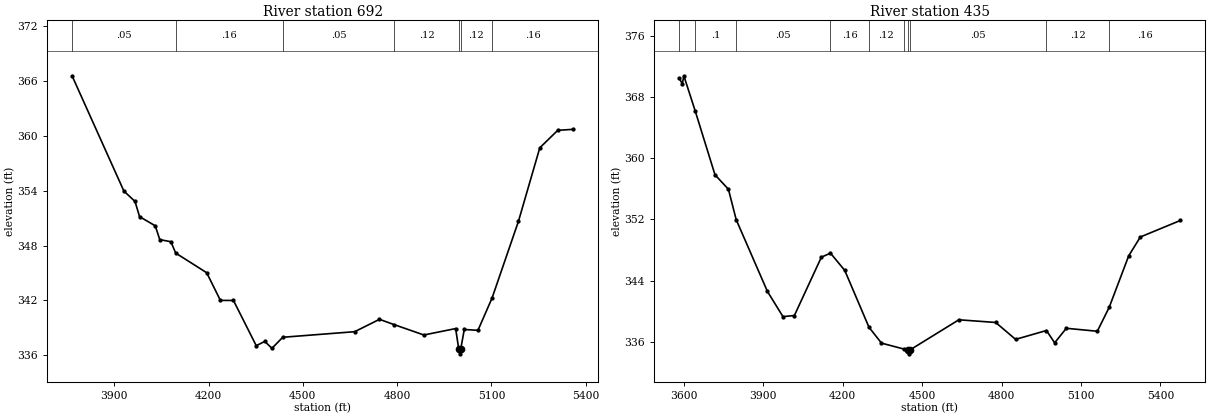
Type RM Length L Ch R = 1,692,257,257,257
BEGIN DESCRIPTION:
BOGGY BRANCH 2.0
END DESCRIPTION:
XS GIS Cut Line= 3
      3541588.64     10376496.43      3540763.63     10375431.23
      3540529.57     10375350.57
#Sta/Elev= 30
  3765.9  366.55  3930.9  353.95  3966.2  352.82  3980.7  351.16  4030.5  350.16
  4045.0  348.65  4080.3  348.42  4095.6  347.18  4194.3  345.03  4237.8  342.01
  4279.4  342.00  4351.9  337.06  4379.1  337.53  4401.7  336.77  4436.2  337.98
  4665.1  338.59  4743.9  339.94  4791.6  339.35  4885.1  338.23  4986.2  338.93
  4996.2  336.67  4999.0  336.17  5002.2  336.67  5013.7  338.83  5057.2  338.74
  5102.0  342.26  5186.1  350.66  5253.9  358.68  5311.0  360.59  5360.8  360.70
#Mann=7,-1,0
  3765.9    0.05       0  4095.6    0.16       0  4436.2    0.05       0
  4791.6    0.12       0  4996.2    0.07       0  5002.2    0.12       0
  5102.0    0.16       0
Bank Sta=4996.2,5002.2
Exp/Cntr=0.3,0.1

Type RM Length L Ch R = 1,435,0,0,0
BEGIN DESCRIPTION:
BOGGY BRANCH 1.0
END DESCRIPTION:
XS GIS Cut Line= 3
      3541836.02     10376453.00      3541224.05     10375398.32
      3540565.75     10375255.40
#Sta/Elev= 30
  3582.2  370.49  3594.8  369.74  3600.5  370.78  3643.4  366.18  3718.1  357.84
  3768.8  355.95  3798.2  351.97  3916.0  342.60  3974.8  339.30  4017.9  339.45
  4119.7  347.07  4154.2  347.60  4208.1  345.34  4299.6  337.91  4346.8  335.84
  4430.9  335.07  4447.9  334.94  4450.6  334.44  4453.9  334.94  4638.9  338.89
  4778.0  338.54  4853.1  336.33  4969.6  337.49  5000.6  335.88  5044.6  337.78
  5161.7  337.39  5206.8  340.54  5280.1  347.24  5324.1  349.71  5475.2  351.87
#Mann=10,-1,0
  3582.2    0.05       0  3643.4     0.1       0  3798.2    0.05       0
  4154.2    0.16       0  4299.6    0.12       0  4430.9    0.05       0
  4447.9    0.07       0  4453.9    0.05       0  4969.6    0.12       0
  5206.8    0.16       0
Bank Sta=4447.9,4453.9
Exp/Cntr=0.3,0.1

Chan Stop Cuts=-1