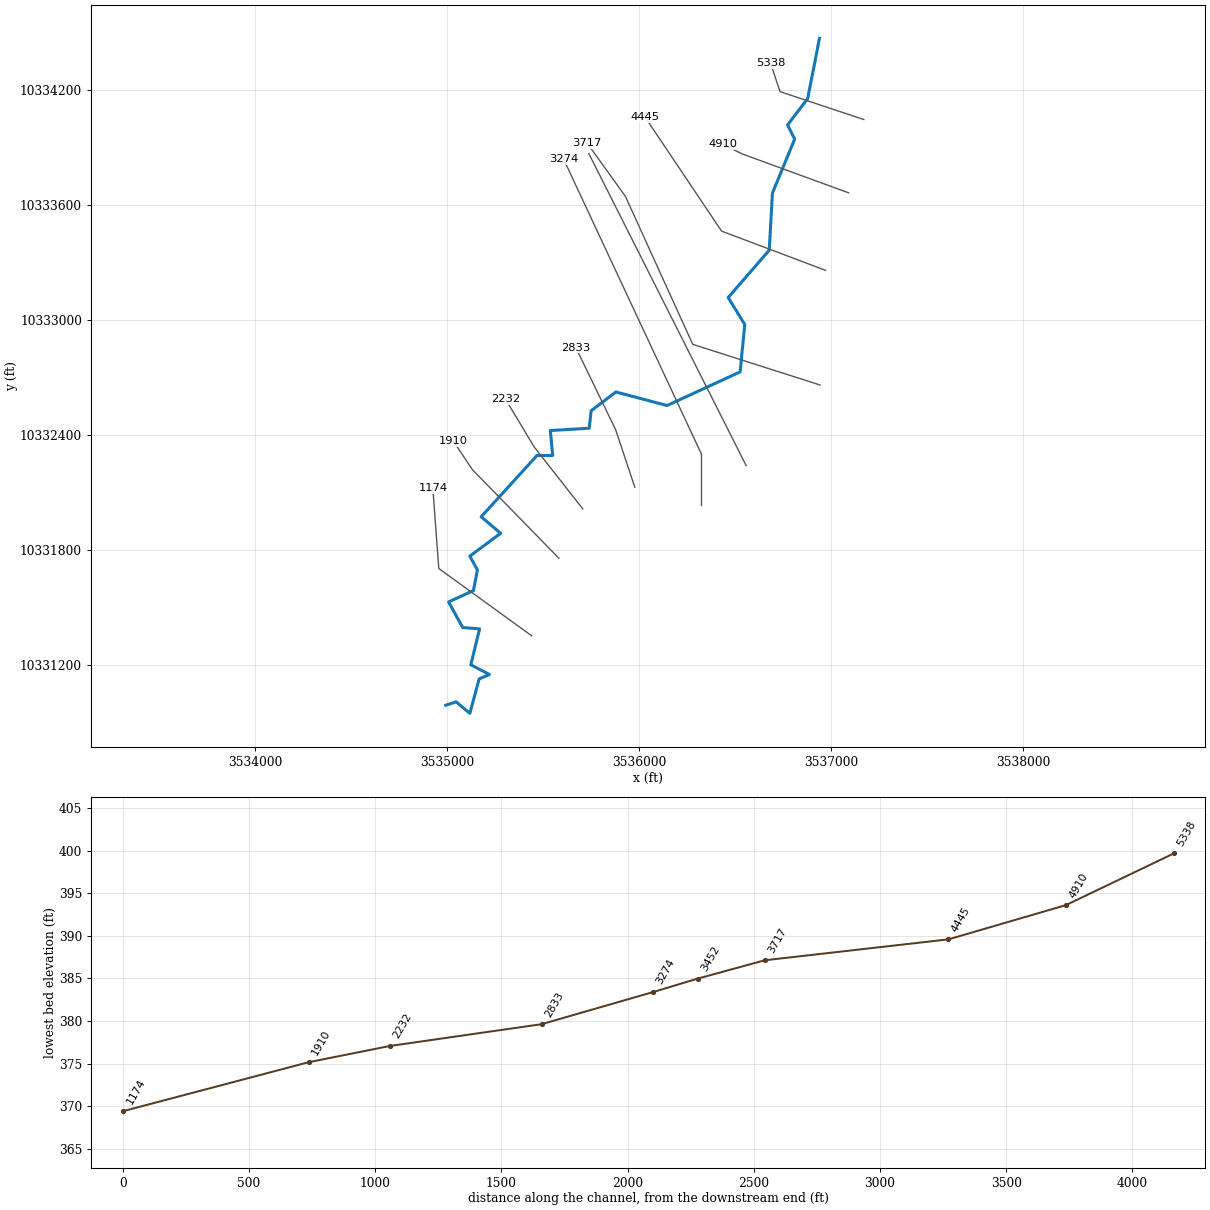
--- BRUSHY CREEK TRIBUTARY 4.prj (project) ---

Proj Title=BRUSHY CREEK TRIBUTARY 4 Base Level Engineering
Current Plan=p01
Default Exp/Contr=0.3,0.1
English Units
Geom File=g01
Flow File=f01
Plan File=p01
BEGIN DESCRIPTION:
BRUSHY CREEK TRIBUTARY 4
END DESCRIPTION:

--- BRUSHY CREEK TRIBUTARY 4.p01 (plan) ---

Plan Title=Multiple Run
Short Identifier=Multiple
Geom File=g01
Flow File=f01
Subcritical Flow
K Sum by GR= 0
Std Step Tol= 0.01
Critical Tol= 0.01
Num of Std Step Trials= 20
Max Error Tol= 0.3
Flow Tol Ratio= 0.001
Split Flow NTrial= 30
Split Flow Tol= 0.02
Split Flow Ratio= 0.02
Log Output Level= 0
Friction Slope Method= 1
Unsteady Friction Slope Method= 2
Unsteady Bridges Friction Slope Method= 1
Parabolic Critical Depth
Global Vel Dist=  1 , 1 , 1
Global Log Level= 0
CheckData=True
Encroach Param= -1, 0, 0, 0
BEGIN DESCRIPTION:
Multiple Run
END DESCRIPTION:

--- BRUSHY CREEK TRIBUTARY 4.f01 (steady flow) ---

Flow Title=Multiple
Number of Profiles=7
Profile Names=10-year,25-year,50-year,1pct_min,100-year,1pct_plu,500-year
River Rch & RM= BRUSHY CREEK TRI,Reach-1,5338
     393     527     636     564     763    1032    1100
Boundary for River Rch & Prof#=BRUSHY CREEK TRI,Reach-1,1
Up Type=0
Dn Type=3
Dn Slope=0.005
Boundary for River Rch & Prof#=BRUSHY CREEK TRI,Reach-1,2
Up Type=0
Dn Type=3
Dn Slope=0.005
Boundary for River Rch & Prof#=BRUSHY CREEK TRI,Reach-1,3
Up Type=0
Dn Type=3
Dn Slope=0.005
Boundary for River Rch & Prof#=BRUSHY CREEK TRI,Reach-1,4
Up Type=0
Dn Type=3
Dn Slope=0.005
Boundary for River Rch & Prof#=BRUSHY CREEK TRI,Reach-1,5
Up Type=0
Dn Type=3
Dn Slope=0.005
Boundary for River Rch & Prof#=BRUSHY CREEK TRI,Reach-1,6
Up Type=0
Dn Type=3
Dn Slope=0.005
Boundary for River Rch & Prof#=BRUSHY CREEK TRI,Reach-1,7
Up Type=0
Dn Type=3
Dn Slope=0.005

--- BRUSHY CREEK TRIBUTARY 4.g01 (geometry) ---

Geom Title=Existing Conditions

River Reach=BRUSHY CREEK TRI,Reach-1
Reach XY= 30
      3536939.84     10334467.13      3536878.43     10334153.08
      3536773.50     10334015.63      3536810.59     10333942.18
      3536694.68     10333660.32      3536678.01     10333362.94
      3536464.05     10333116.34      3536550.47     10332975.87
      3536526.52     10332728.94      3536145.65     10332553.40
      3535878.89     10332624.25      3535749.92     10332526.25
      3535739.94     10332435.21      3535537.14     10332423.14
      3535549.52     10332293.23      3535467.77     10332293.29
      3535176.90     10331973.75      3535278.18     10331887.62
      3535117.74     10331768.51      3535157.09     10331696.72
      3535136.62     10331589.15      3535006.97     10331530.08
      3535080.58     10331396.56      3535168.43     10331389.66
      3535122.90     10331202.16      3535219.82     10331151.93
      3535166.28     10331128.94      3535117.83     10330949.18
      3535046.31     10331009.12      3534992.11     10330991.64

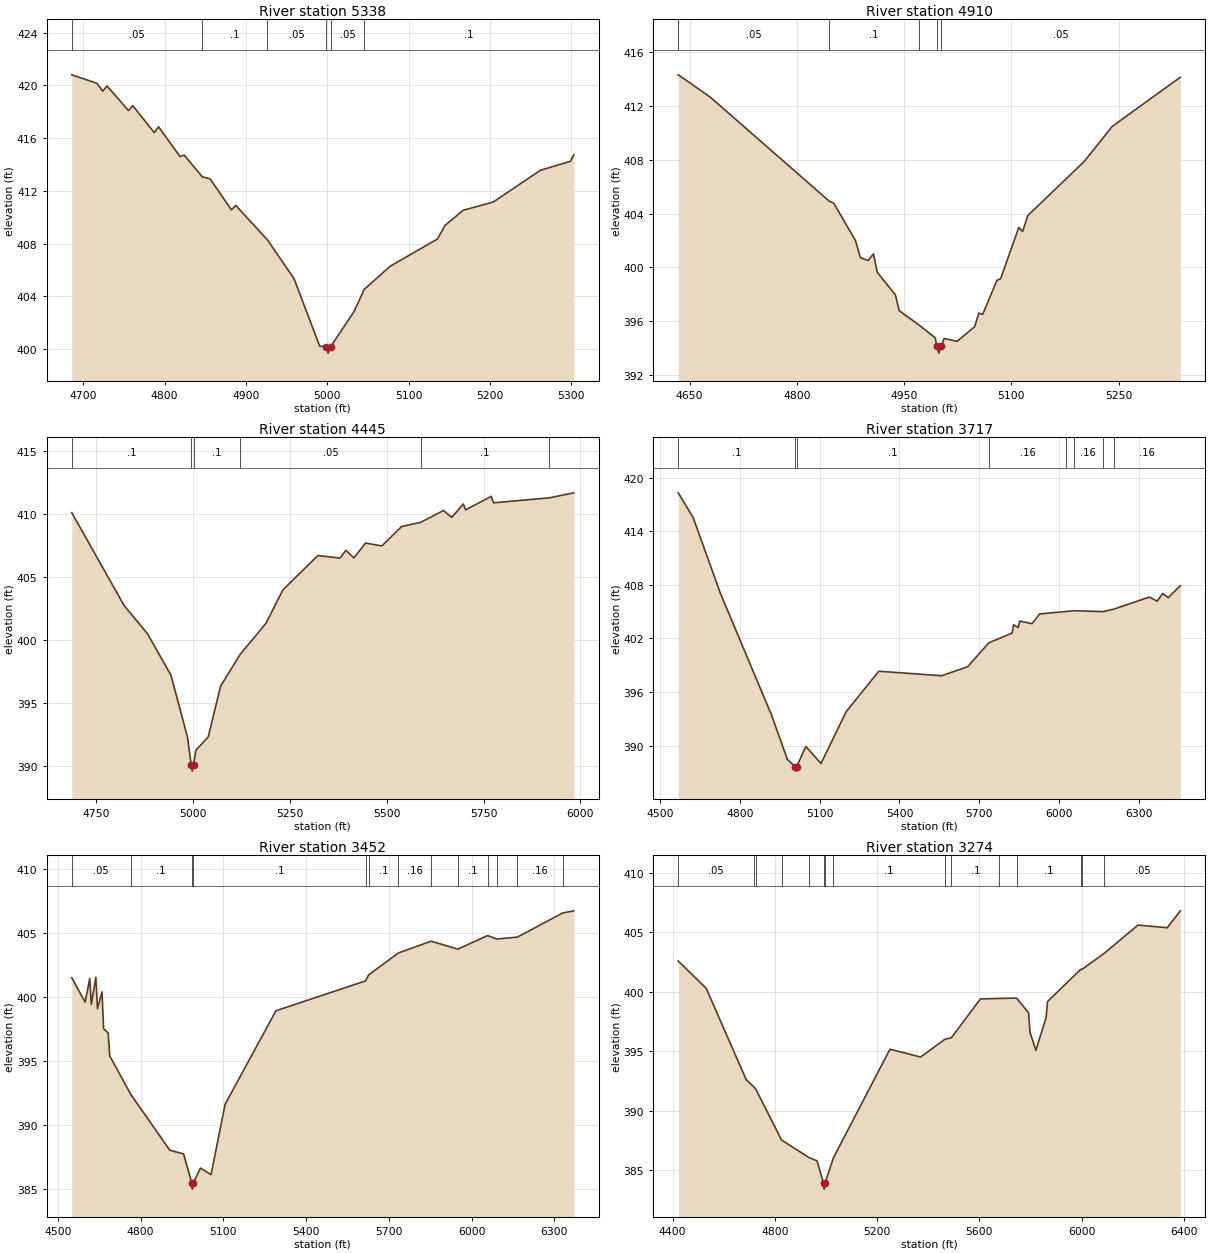
Type RM Length L Ch R = 1,5338,428,428,428
BEGIN DESCRIPTION:
BRUSHY CREEK TRIBUTARY 4 9.0
END DESCRIPTION:
XS GIS Cut Line= 3
      3537171.29     10334043.97      3536734.39     10334189.31
      3536684.82     10334338.02
#Sta/Elev= 30
  4685.8  420.80  4716.6  420.16  4723.9  419.57  4729.2  419.95  4755.5  418.09
  4760.8  418.46  4787.2  416.42  4792.5  416.86  4818.8  414.61  4824.1  414.71
  4846.2  413.07  4855.8  412.92  4882.1  410.56  4887.4  410.90  4926.3  408.29
  4959.0  405.35  4990.6  400.22  4998.1  400.20  5000.9  399.70  5004.1  400.20
  5032.7  402.84  5045.3  404.53  5077.3  406.29  5135.3  408.35  5144.8  409.39
  5166.9  410.53  5203.8  411.15  5261.8  413.56  5298.7  414.24  5303.0  414.73
#Mann=6,-1,0
  4685.8    0.05       0  4846.2     0.1       0  4926.3    0.05       0
  4998.1    0.03       0  5004.1    0.05       0  5045.3     0.1       0
Bank Sta=4998.1,5004.1
Exp/Cntr=0.3,0.1

Type RM Length L Ch R = 1,4910,465,465,465
BEGIN DESCRIPTION:
BRUSHY CREEK TRIBUTARY 4 8.0
END DESCRIPTION:
XS GIS Cut Line= 3
      3537091.47     10333662.13      3536536.72     10333864.79
      3536436.91     10333914.69
#Sta/Elev= 30
  4634.1  414.32  4634.3  414.32  4678.9  412.66  4845.4  404.92  4851.5  404.78
  4882.0  401.99  4888.9  400.72  4899.6  400.51  4907.2  401.00  4912.5  399.62
  4937.8  397.96  4943.1  396.78  4970.4  395.73  4993.5  394.76  4995.8  394.12
  4998.6  393.62  5001.8  394.12  5006.0  394.71  5024.1  394.50  5048.6  395.58
  5054.6  396.60  5059.9  396.50  5079.8  399.03  5085.1  399.16  5110.4  402.97
  5115.7  402.67  5123.2  403.86  5202.0  407.88  5241.0  410.48  5336.3  414.14
#Mann=6,-1,0
  4634.1     0.1       0  4634.3    0.05       0  4845.4     0.1       0
  4970.4    0.05       0  4995.8    0.03       0  5001.8    0.05       0
Bank Sta=4995.8,5001.8
Exp/Cntr=0.3,0.1

Type RM Length L Ch R = 1,4445,728,728,728
BEGIN DESCRIPTION:
BRUSHY CREEK TRIBUTARY 4 7.0111
END DESCRIPTION:
XS GIS Cut Line= 3
      3536971.51     10333258.15      3536429.91     10333462.36
      3536030.55     10334056.97
#Sta/Elev= 30
  4687.8  410.09  4823.0  402.72  4883.4  400.48  4943.8  397.19  4986.4  392.28
  4995.9  390.10  4998.6  389.60  5001.9  390.10  5007.8  391.24  5039.8  392.32
  5071.9  396.35  5122.0  398.85  5188.9  401.32  5232.2  403.96  5322.7  406.69
  5379.7  406.49  5394.7  407.10  5415.7  406.50  5445.7  407.68  5487.7  407.45
  5538.7  408.99  5587.6  409.32  5646.8  410.26  5667.8  409.71  5697.7  410.77
  5703.8  410.31  5769.8  411.38  5775.8  410.87  5919.2  411.26  5982.9  411.66
#Mann=6,-1,0
  4687.8     0.1       0  4995.9    0.07       0  5001.9     0.1       0
  5122.0    0.05       0  5587.6     0.1       0  5919.2    0.16       0
Bank Sta=4995.9,5001.9
Exp/Cntr=0.3,0.1

Type RM Length L Ch R = 1,3717,265,265,265
BEGIN DESCRIPTION:
BRUSHY CREEK TRIBUTARY 4 7.0
END DESCRIPTION:
XS GIS Cut Line= 4
      3536942.89     10332660.50      3536279.38     10332872.45
      3535928.68     10333643.29      3535729.02     10333921.08
#Sta/Elev= 30
  4569.2  418.32  4625.0  415.56  4727.5  407.06  4919.9  393.40  4979.0  388.46
  5007.9  387.64  5010.7  387.14  5013.9  387.64  5048.6  389.90  5105.4  387.99
  5199.9  393.80  5322.4  398.33  5558.5  397.83  5656.2  398.84  5735.8  401.52
  5823.1  402.61  5828.6  403.54  5846.2  403.23  5851.7  403.95  5897.8  403.66
  5926.4  404.75  6025.7  405.03  6053.8  405.11  6164.9  405.01  6207.1  405.31
  6338.2  406.64  6367.7  406.18  6388.6  407.04  6409.4  406.58  6454.7  407.91
#Mann=8,-1,0
  4569.2     0.1       0  5007.9    0.07       0  5013.9     0.1       0
  5735.8    0.16       0  6025.7     0.1       0  6053.8    0.16       0
  6164.9     0.1       0  6207.1    0.16       0
Bank Sta=5007.9,5013.9
Exp/Cntr=0.3,0.1

Type RM Length L Ch R = 1,3452,178,178,178
BEGIN DESCRIPTION:
Mapping XS 73739301
END DESCRIPTION:
XS GIS Cut Line= 2
      3536557.61     10332240.85      3535738.17     10333865.83
#Sta/Elev= 30
  4550.8  401.49  4599.2  399.58  4615.9  401.43  4621.5  399.41  4638.2  401.53
  4643.8  399.07  4660.5  400.38  4666.1  397.51  4682.8  397.17  4688.4  395.39
  4764.3  392.40  4905.9  388.03  4956.1  387.74  4985.5  385.49  4988.2  384.99
  4991.5  385.49  5017.4  386.63  5055.7  386.12  5106.6  391.61  5290.9  398.91
  5615.6  401.24  5626.9  401.71  5734.7  403.42  5853.6  404.34  5950.4  403.72
  6058.2  404.78  6091.7  404.51  6166.1  404.66  6329.8  406.54  6370.7  406.71
#Mann=13,-1,0
  4550.8    0.05       0  4764.3     0.1       0  4985.5    0.07       0
  4991.5     0.1       0  5615.6    0.05       0  5626.9     0.1       0
  5734.7    0.16       0  5853.6    0.05       0  5950.4     0.1       0
  6058.2    0.16       0  6091.7    0.05       0  6166.1    0.16       0
  6329.8    0.05       0
Bank Sta=4985.5,4991.5
Exp/Cntr=0.3,0.1

Type RM Length L Ch R = 1,3274,441,441,441
BEGIN DESCRIPTION:
BRUSHY CREEK TRIBUTARY 4 6.0
END DESCRIPTION:
XS GIS Cut Line= 3
      3536324.96     10332032.58      3536324.96     10332299.89
      3535607.00     10333836.41
#Sta/Elev= 30
  4422.2  402.59  4531.3  400.30  4687.9  392.62  4719.8  391.95  4725.4  391.81
  4826.3  387.53  4932.7  386.06  4964.9  385.78  4990.3  383.90  4993.0  383.40
  4996.3  383.90  5029.0  386.03  5250.1  395.17  5369.9  394.51  5464.8  396.00
  5490.3  396.13  5603.9  399.40  5677.7  399.44  5745.2  399.47  5792.2  398.23
  5797.7  396.60  5820.6  395.07  5860.7  397.83  5866.3  399.18  5996.9  401.90
  6000.1  401.87  6088.9  403.25  6220.0  405.61  6334.3  405.39  6385.5  406.81
#Mann=15,-1,0
  4422.2    0.05       0  4719.8     0.1       0  4725.4    0.05       0
  4826.3     0.1       0  4932.7    0.05       0  4990.3    0.03       0
  4996.3    0.05       0  5029.0     0.1       0  5464.8    0.05       0
  5490.3     0.1       0  5677.7    0.05       0  5745.2     0.1       0
  5996.9    0.05       0  6000.1     0.1       0  6088.9    0.05       0
Bank Sta=4990.3,4996.3
Exp/Cntr=0.3,0.1

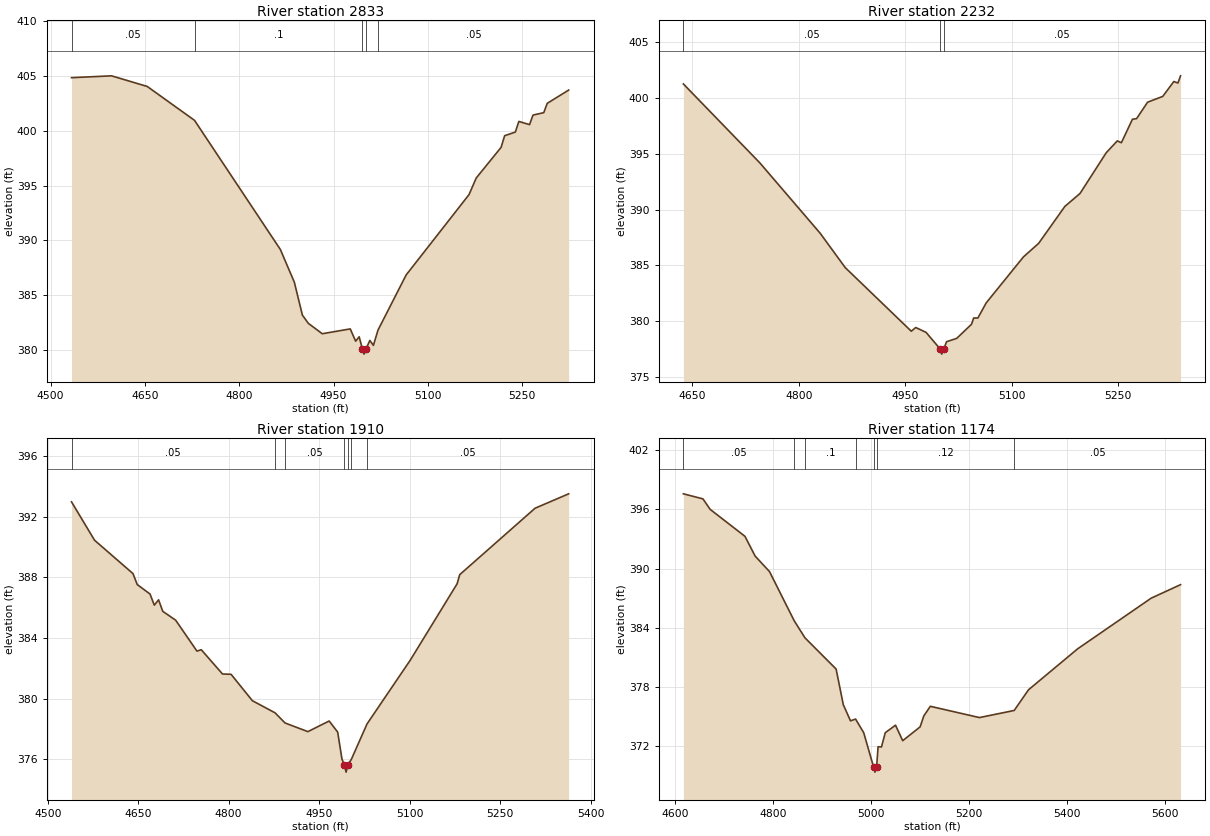
Type RM Length L Ch R = 1,2833,601,601,601
BEGIN DESCRIPTION:
BRUSHY CREEK TRIBUTARY 4 4.0
END DESCRIPTION:
XS GIS Cut Line= 3
      3535977.61     10332127.40      3535877.62     10332427.38
      3535670.72     10332854.17
#Sta/Elev= 30
  4533.3  404.84  4596.9  405.01  4653.7  404.04  4728.9  400.95  4865.4  389.17
  4887.6  386.19  4900.4  383.19  4909.8  382.44  4932.0  381.49  4976.5  381.93
  4985.1  380.81  4990.7  381.21  4995.7  380.13  4998.5  379.63  5001.7  380.13
  5007.7  380.88  5013.3  380.43  5020.7  381.83  5065.4  386.85  5165.4  394.18
  5176.8  395.69  5216.4  398.49  5222.0  399.55  5239.0  399.88  5244.6  400.85
  5261.6  400.56  5267.1  401.43  5284.2  401.65  5289.7  402.50  5323.8  403.71
#Mann=5,-1,0
  4533.3    0.05       0  4728.9     0.1       0  4995.7    0.07       0
  5001.7     0.1       0  5020.7    0.05       0
Bank Sta=4995.7,5001.7
Exp/Cntr=0.3,0.1

Type RM Length L Ch R = 1,2232,322,322,322
BEGIN DESCRIPTION:
BRUSHY CREEK TRIBUTARY 4 3.0
END DESCRIPTION:
XS GIS Cut Line= 3
      3535706.23     10332015.06      3535453.31     10332337.20
      3535303.47     10332586.94
#Sta/Elev= 30
  4637.3  401.23  4745.1  394.17  4830.1  387.88  4865.4  384.81  4958.5  379.12
  4964.8  379.45  4979.3  379.02  4998.7  377.57  5001.4  377.07  5004.7  377.57
  5008.2  378.18  5022.6  378.48  5043.4  379.74  5046.5  380.30  5052.4  380.30
  5064.2  381.66  5116.7  385.77  5138.1  386.98  5175.0  390.28  5196.4  391.44
  5233.3  395.08  5248.9  396.14  5254.7  395.98  5270.3  398.08  5276.1  398.13
  5291.6  399.60  5313.0  400.12  5328.6  401.45  5334.4  401.32  5338.1  401.96
#Mann=3,-1,0
  4637.3    0.05       0  4998.7    0.03       0  5004.7    0.05       0
Bank Sta=4998.7,5004.7
Exp/Cntr=0.3,0.1

Type RM Length L Ch R = 1,1910,736,736,736
BEGIN DESCRIPTION:
BRUSHY CREEK TRIBUTARY 4 2.0
END DESCRIPTION:
XS GIS Cut Line= 3
      3535581.97     10331757.51      3535131.11     10332219.23
      3535031.95     10332367.97
#Sta/Elev= 30
  4539.5  392.98  4577.7  390.45  4641.4  388.25  4648.4  387.53  4669.7  386.90
  4676.7  386.17  4683.8  386.52  4690.8  385.76  4712.1  385.18  4747.4  383.14
  4754.6  383.23  4789.8  381.63  4804.0  381.61  4839.3  379.87  4876.9  379.07
  4893.5  378.40  4931.3  377.83  4966.6  378.53  4980.7  377.80  4987.9  376.00
  4991.9  375.66  4994.6  375.16  4997.9  375.66  5003.2  375.99  5029.4  378.34
  5101.0  382.54  5178.7  387.58  5183.0  388.18  5307.9  392.56  5363.6  393.51
#Mann=7,-1,0
  4539.5    0.05       0  4876.9     0.1       0  4893.5    0.05       0
  4991.9    0.03       0  4997.9    0.05       0  5003.2     0.1       0
  5029.4    0.05       0
Bank Sta=4991.9,4997.9
Exp/Cntr=0.3,0.1

Type RM Length L Ch R = 1,1174,0,0,0
BEGIN DESCRIPTION:
BRUSHY CREEK TRIBUTARY 4 1.0
END DESCRIPTION:
XS GIS Cut Line= 3
      3535439.87     10331353.53      3534955.95     10331704.26
      3534924.88     10332121.55
#Sta/Elev= 30
  4616.4  397.56  4656.3  397.05  4671.0  395.99  4742.2  393.26  4763.0  391.26
  4792.4  389.69  4842.7  384.73  4864.8  382.99  4928.5  379.83  4943.2  376.22
  4957.9  374.59  4968.3  374.77  4984.9  373.39  5005.2  369.90  5007.9  369.40
  5011.2  369.90  5014.3  371.97  5021.2  371.95  5029.0  373.39  5049.9  374.15
  5064.6  372.58  5100.2  373.98  5107.7  375.08  5121.0  376.06  5221.5  374.92
  5292.5  375.64  5321.7  377.73  5422.0  381.87  5572.4  387.00  5632.5  388.37
#Mann=7,-1,0
  4616.4    0.05       0  4842.7    0.12       0  4864.8     0.1       0
  4968.3    0.12       0  5005.2    0.07       0  5011.2    0.12       0
  5292.5    0.05       0
Bank Sta=5005.2,5011.2
Exp/Cntr=0.3,0.1

Chan Stop Cuts=-1