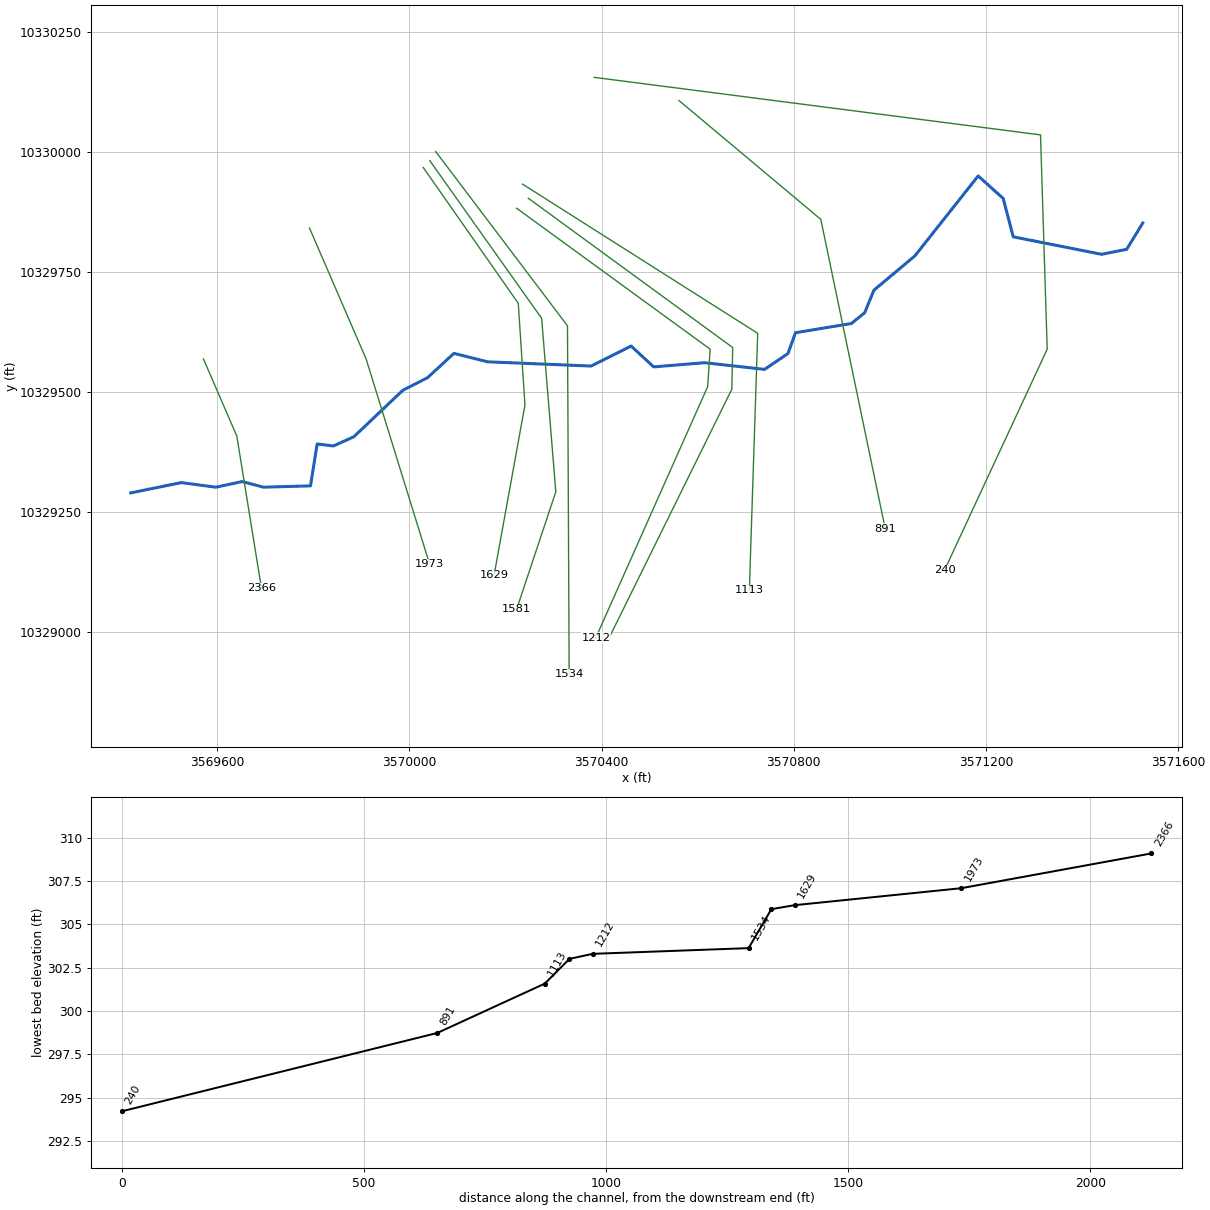
--- BUCKHORN BRANCH.prj (project) ---

Proj Title=BUCKHORN BRANCH Base Level Engineering
Current Plan=p01
Default Exp/Contr=0.3,0.1
English Units
Geom File=g01
Flow File=f01
Plan File=p01
Y Axis Title=Elevation
X Axis Title(PF)=Main Channel Distance
X Axis Title(XS)=Station
BEGIN DESCRIPTION:
BUCKHORN BRANCH
END DESCRIPTION:
DSS Export Rating Curves= 0
DSS Export Rating Curve Sorted= 0
DSS Export Volume Flow Curves= 0
DXF OffsetX= 0
DXF OffsetY= 0
DXF ScaleX= 1
DXF ScaleY= 10

--- BUCKHORN BRANCH.p01 (plan) ---

Plan Title=Multiple Run
Short Identifier=Multiple
Geom File=g01
Flow File=f01
Subcritical Flow
K Sum by GR= 0
Std Step Tol= 0.01
Critical Tol= 0.01
Num of Std Step Trials= 20
Max Error Tol= 0.3
Flow Tol Ratio= 0.001
Split Flow NTrial= 30
Split Flow Tol= 0.02
Split Flow Ratio= 0.02
Log Output Level= 0
Friction Slope Method= 1
Unsteady Friction Slope Method= 2
Unsteady Bridges Friction Slope Method= 1
Parabolic Critical Depth
Global Vel Dist=  1 , 1 , 1
Global Log Level= 0
CheckData=True
Encroach Param= -1, 0, 0, 0
BEGIN DESCRIPTION:
Multiple Run
END DESCRIPTION:

--- BUCKHORN BRANCH.f01 (steady flow) ---

Flow Title=Multiple
Number of Profiles=7
Profile Names=10-year,25-year,50-year,1pct_min,100-year,1pct_plu,500-year
River Rch & RM= BUCKHORN BRANCH,Reach-1,2366
     245     314     368     317     428     579     581
Boundary for River Rch & Prof#=BUCKHORN BRANCH,Reach-1,1
Up Type=0
Dn Type=3
Dn Slope=0.005
Boundary for River Rch & Prof#=BUCKHORN BRANCH,Reach-1,2
Up Type=0
Dn Type=3
Dn Slope=0.005
Boundary for River Rch & Prof#=BUCKHORN BRANCH,Reach-1,3
Up Type=0
Dn Type=3
Dn Slope=0.005
Boundary for River Rch & Prof#=BUCKHORN BRANCH,Reach-1,4
Up Type=0
Dn Type=3
Dn Slope=0.005
Boundary for River Rch & Prof#=BUCKHORN BRANCH,Reach-1,5
Up Type=0
Dn Type=3
Dn Slope=0.005
Boundary for River Rch & Prof#=BUCKHORN BRANCH,Reach-1,6
Up Type=0
Dn Type=3
Dn Slope=0.005
Boundary for River Rch & Prof#=BUCKHORN BRANCH,Reach-1,7
Up Type=0
Dn Type=3
Dn Slope=0.005

--- BUCKHORN BRANCH.g01 (geometry) ---

Geom Title=Existing Conditions
Program Version=4.10

River Reach=BUCKHORN BRANCH ,Reach-1
Reach XY= 30
      3569420.11     10329290.08      3569525.32     10329311.48
      3569597.33     10329301.91      3569652.09     10329313.72
      3569696.23     10329301.96      3569794.21     10329304.71
       3569808.1     10329392.01      3569841.83     10329387.76
      3569884.36      10329406.9      3569986.37     10329503.69
        3570038.     10329530.09      3570092.61     10329580.53
      3570162.58     10329563.02      3570378.15     10329554.18
      3570461.48     10329595.85      3570508.36     10329552.45
      3570614.26     10329561.13      3570739.26     10329547.24
      3570787.87     10329580.23       3570803.5     10329623.63
      3570919.82     10329642.73      3570947.59      10329665.3
      3570966.69     10329712.17      3571051.76     10329783.35
       3571183.7     10329950.02      3571235.79     10329903.14
      3571256.62     10329823.28      3571440.65     10329786.82
      3571492.73     10329797.24      3571526.25     10329852.13

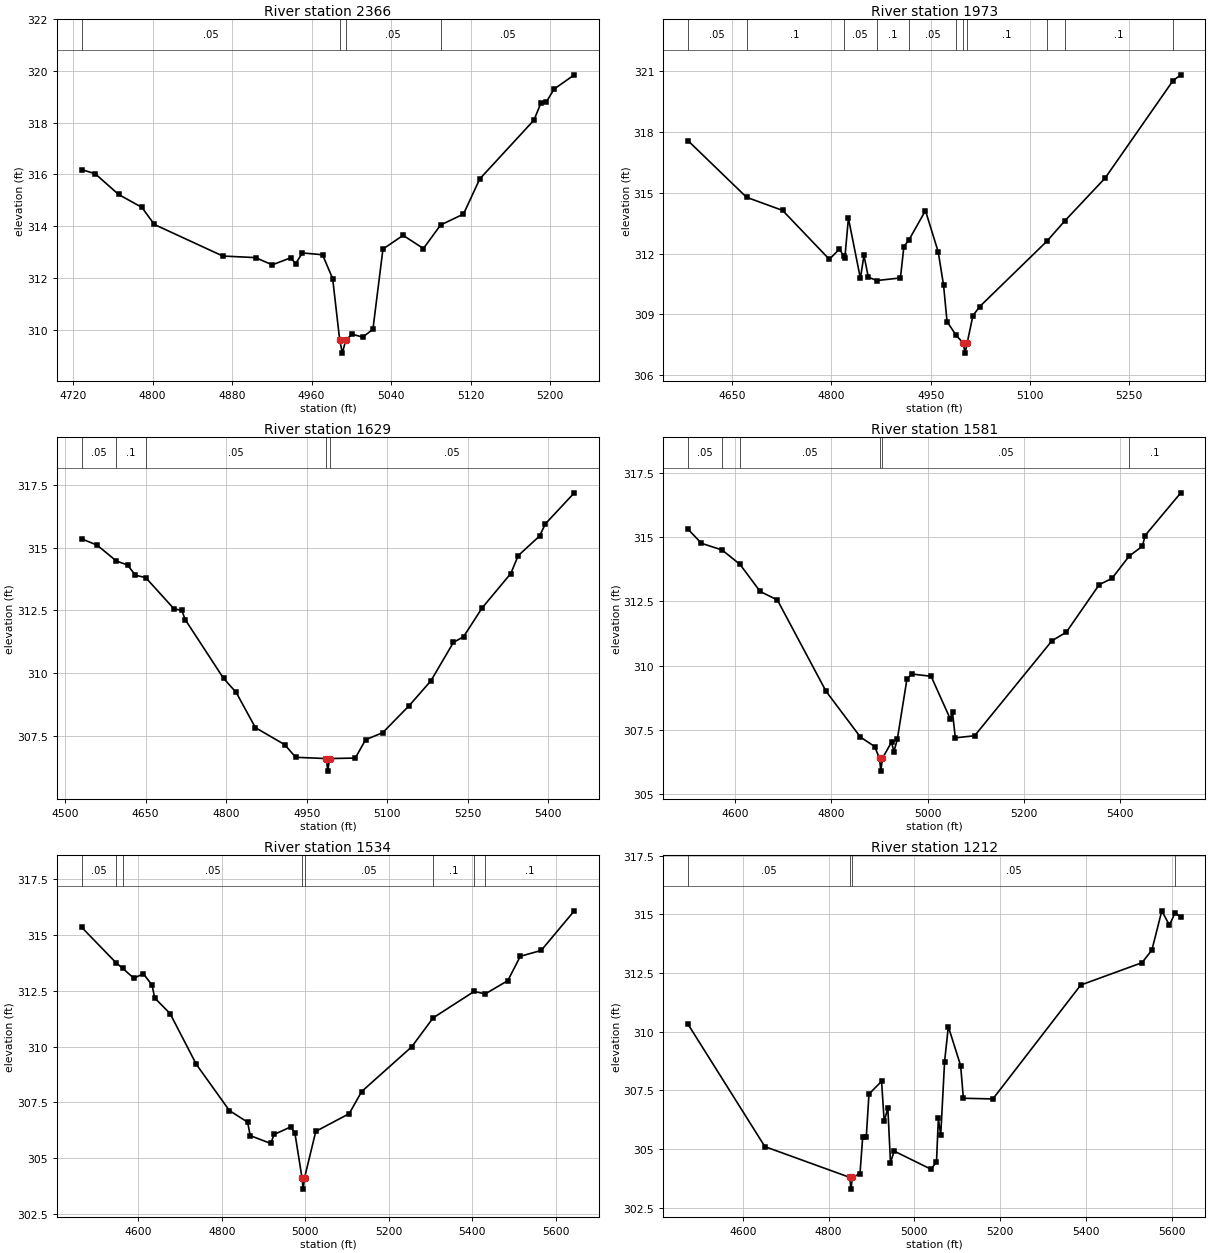
Type RM Length L Ch R = 1 ,2366    ,393,393,393
BEGIN DESCRIPTION:
BUCKHORN BRANCH 4.0
END DESCRIPTION:
XS GIS Cut Line= 3
      3569571.47     10329568.83      3569640.93     10329408.21
      3569692.11     10329091.61
#Sta/Elev= 30
  4728.6  316.19  4742.3  316.03  4765.8  315.23  4789.3  314.73  4801.8  314.07
  4870.7  312.85  4903.6  312.79  4920.4  312.51  4938.9  312.78    4944  312.56
  4950.8  312.97    4971   312.9  4981.2  311.98  4988.3   309.6    4991   309.1
  4994.3   309.6  5000.7  309.83  5011.5  309.72  5021.7  310.02  5031.8  313.12
  5052.1  313.65  5072.5  313.14  5089.8  314.05  5112.8  314.47  5129.2  315.83
  5183.7   318.1  5190.9  318.78  5195.9  318.79    5204   319.3  5224.3  319.85
#Mann= 4 ,-1 , 0
  4728.6     .05       0  4988.3     .07       0  4994.3     .05       0
  5089.8     .05       0
Bank Sta=4988.3,4994.3
XS Rating Curve= 0 ,0
Exp/Cntr=0.3,0.1

Type RM Length L Ch R = 1 ,1973    ,344,344,344
BEGIN DESCRIPTION:
BUCKHORN BRANCH 3.0
END DESCRIPTION:
XS GIS Cut Line= 3
      3569792.09     10329841.68      3569910.02      10329568.8
      3570042.11     10329141.63
#Sta/Elev= 30
  4583.4  317.57  4671.8  314.78  4726.3  314.13  4796.8  311.72  4812.2  312.22
  4818.7  311.87  4820.3  311.78  4825.7  313.75  4843.8  310.78  4849.2  311.91
  4855.8  310.84  4868.5  310.67  4904.3   310.8  4909.5  312.35  4916.9  312.66
  4942.1  314.12  4961.4  312.08  4969.5  310.43  4974.7  308.64  4988.7  307.96
  4999.1  307.59  5001.9  307.09  5005.1  307.59  5013.8  308.94  5024.2  309.39
  5125.5  312.61  5152.5  313.61  5213.6  315.73    5316  320.53  5327.8  320.82
#Mann= 11 ,-1 , 0
  4583.4     .05       0  4671.8      .1       0  4818.7     .05       0
  4868.5      .1       0  4916.9     .05       0  4988.7      .1       0
  4999.1     .07       0  5005.1      .1       0  5125.5     .05       0
  5152.5      .1       0    5316     .05       0
Bank Sta=4999.1,5005.1
XS Rating Curve= 0 ,0
Exp/Cntr=0.3,0.1

Type RM Length L Ch R = 1 ,1629    ,48,48,48
BEGIN DESCRIPTION:
Mapping XS 7b1d1227
END DESCRIPTION:
XS GIS Cut Line= 4
      3570028.72     10329967.77      3570226.61     10329684.82
       3570240.5     10329473.01      3570176.26     10329118.84
#Sta/Elev= 30
  4530.9  315.35  4559.8   315.1  4595.6  314.47  4616.5  314.31  4631.3   313.9
  4650.2  313.81  4702.8  312.57  4717.7   312.5  4723.8  312.14  4795.3   309.8
  4818.8  309.24  4854.6  307.84  4909.4  307.16  4929.5  306.66  4986.6  306.61
  4989.4  306.11  4992.6  306.61  5040.6  306.63  5059.8  307.36  5091.7  307.64
  5140.7  308.71  5181.3   309.7  5223.3  311.23  5242.3  311.46  5276.7   312.6
  5330.1  313.97  5343.9  314.68  5383.6  315.46  5394.7  315.95  5448.4  317.18
#Mann= 5 ,-1 , 0
  4530.9     .05       0  4595.6      .1       0  4650.2     .05       0
  4986.6     .03       0  4992.6     .05       0
Bank Sta=4986.6,4992.6
XS Rating Curve= 0 ,0
Exp/Cntr=0.3,0.1

Type RM Length L Ch R = 1 ,1581    ,47,47,47
BEGIN DESCRIPTION:
Mapping XS b931d290
END DESCRIPTION:
XS GIS Cut Line= 4
      3570042.56     10329981.72      3570275.22     10329653.57
      3570304.74     10329292.45      3570223.14     10329047.67
#Sta/Elev= 30
  4502.8  315.32  4530.7  314.77  4573.4  314.51  4610.6  313.95  4652.5  312.89
  4688.2  312.56  4789.1     309  4860.5  307.21    4890  306.84  4900.2  306.38
  4902.9  305.88  4906.2  306.38  4925.1  307.01  4930.1  306.64  4937.1  307.12
  4957.2  309.48  4967.2  309.67  5007.3  309.58  5046.7  307.93  5051.7  308.17
  5057.5  307.18  5097.6  307.26  5258.2  310.97  5287.8   311.3  5356.3  313.16
  5382.6   313.4  5418.3  314.27  5445.9  314.66  5451.2  315.07  5525.4  316.74
#Mann= 6 ,-1 , 0
  4502.8     .05       0  4573.4      .1       0  4610.6     .05       0
  4900.2    .035       0  4906.2     .05       0  5418.3      .1       0
Bank Sta=4900.2,4906.2
XS Rating Curve= 0 ,0
Exp/Cntr=0.3,0.1

Type RM Length L Ch R = 1 ,1534    ,322,322,322
BEGIN DESCRIPTION:
Mapping XS a0017e0c
END DESCRIPTION:
XS GIS Cut Line= 3
      3570054.73      10330000.8      3570329.04     10329637.94
      3570332.51     10328912.23
#Sta/Elev= 30
  4463.8  315.33  4545.9  313.75  4562.4  313.49  4589.1  313.05  4611.9  313.25
  4632.8  312.74    4639  312.17  4675.9  311.47  4738.9   309.2    4818  307.14
  4861.7  306.62  4867.9  306.02  4917.1  305.67    4925  306.07    4965  306.41
    4975  306.13    4992  304.13  4994.7  303.63    4998  304.13    5025  306.21
    5105     307    5135  307.99    5255  309.99  5306.2  311.28  5404.4  312.46
    5431  312.35    5485  312.94    5515  314.03    5565  314.29  5644.4  316.06
#Mann= 8 ,-1 , 0
  4463.8     .05       0  4545.9      .1       0  4562.4     .05       0
    4992    .035       0    4998     .05       0  5306.2      .1       0
  5404.4     .05       0    5431      .1       0
Bank Sta=4992,4998
XS Rating Curve= 0 ,0
Exp/Cntr=0.3,0.1

Type RM Length L Ch R = 1 ,1212    ,48,48,48
BEGIN DESCRIPTION:
Mapping XS d5f89019
END DESCRIPTION:
XS GIS Cut Line= 4
       3570223.1     10329882.76      3570625.92     10329589.33
      3570620.71      10329511.2      3570388.06     10328988.61
#Sta/Elev= 30
  4472.3  310.32  4651.5  305.11  4849.4   303.8  4852.1   303.3  4855.4   303.8
  4873.2  303.96  4879.4   305.5  4887.9  305.53  4894.1  307.35  4923.5  307.89
  4929.6  306.19  4938.1  306.75  4944.3  304.43  4952.8  304.92  5038.5  304.15
  5051.5  304.45  5055.9  306.31  5061.4  305.59  5070.4  308.73  5079.1  310.22
  5107.8  308.56  5114.2  307.17    5183  307.14  5387.8  311.99  5530.3  312.94
  5553.5  313.47  5576.8  315.15  5594.5  314.54  5607.9  315.07    5621  314.87
#Mann= 4 ,-1 , 0
  4472.3     .05       0  4849.4     .03       0  4855.4     .05       0
  5607.9      .1       0
Bank Sta=4849.4,4855.4
XS Rating Curve= 0 ,0
Exp/Cntr=0.3,0.1

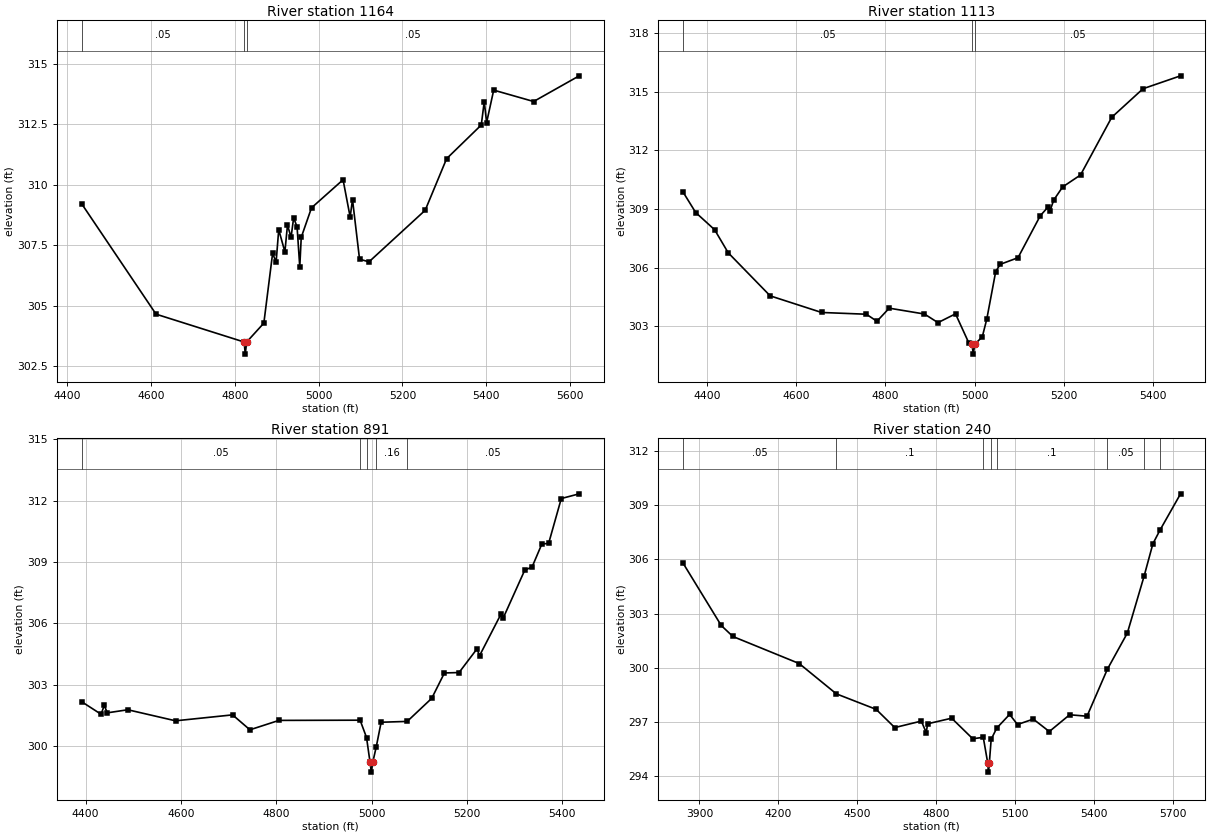
Type RM Length L Ch R = 1 ,1164    ,51,51,51
BEGIN DESCRIPTION:
Mapping XS 8f91c84a
END DESCRIPTION:
XS GIS Cut Line= 4
      3570247.43     10329903.58      3570672.79      10329592.8
      3570671.06       10329506.      3570417.59     10328992.13
#Sta/Elev= 30
  4435.1  309.21  4612.2  304.66  4822.4  303.51  4825.1  303.01  4828.4  303.51
  4869.4  304.29  4890.3  307.17  4898.7  306.81  4904.9  308.15  4919.6  307.23
  4925.8  308.34  4934.3  307.83  4940.5  308.64  4948.7  308.26  4955.1  306.61
  4958.6  307.83  4983.1  309.05  5058.4  310.21  5075.3  308.67  5080.9  309.39
  5097.7  306.93  5120.2  306.82  5254.3  308.95  5305.4  311.08  5388.1  312.47
  5395.2  313.44  5400.8  312.57  5417.7  313.91    5513  313.44  5621.7   314.5
#Mann= 3 ,-1 , 0
  4435.1     .05       0  4822.4     .03       0  4828.4     .05       0
Bank Sta=4822.4,4828.4
XS Rating Curve= 0 ,0
Exp/Cntr=0.3,0.1

Type RM Length L Ch R = 1 ,1113    ,222,222,222
BEGIN DESCRIPTION:
Mapping XS 62951efd
END DESCRIPTION:
XS GIS Cut Line= 3
      3570235.32     10329933.06      3570724.88     10329622.32
      3570707.51     10329087.55
#Sta/Elev= 30
  4346.9  309.86  4375.1  308.82  4417.5  307.94    4448  306.76    4542  304.56
  4657.2  303.71  4757.6  303.62  4781.3  303.26  4808.8  303.93  4887.9  303.63
  4918.1  303.19  4957.4  303.64  4987.5  302.14  4994.5  302.08  4997.2  301.58
  5000.5  302.08  5017.5  302.47  5027.5  303.37  5047.5   305.8  5057.5  306.17
  5097.5  306.51  5147.5  308.66  5164.4  309.09  5169.4  308.92  5177.6  309.46
  5197.6  310.13  5237.6  310.74  5307.6  313.69  5377.7  315.15  5461.8  315.81
#Mann= 3 ,-1 , 0
  4346.9     .05       0  4994.5     .03       0  5000.5     .05       0
Bank Sta=4994.5,5000.5
XS Rating Curve= 0 ,0
Exp/Cntr=0.3,0.1

Type RM Length L Ch R = 1 ,891     ,651,651,651
BEGIN DESCRIPTION:
BUCKHORN BRANCH 1.0
END DESCRIPTION:
XS GIS Cut Line= 3
      3570561.08     10330106.98       3570856.2      10329859.6
      3570990.36      10329214.8
#Sta/Elev= 30
  4391.9  302.17  4432.4  301.56    4439  301.99  4445.5  301.63  4488.5  301.78
  4588.6  301.24  4708.3  301.53  4744.7   300.8  4805.6  301.26  4975.9  301.27
  4989.4  300.42  4996.6  299.23  4999.4  298.73  5002.6  299.23  5009.8  299.97
    5020  301.17  5074.7  301.21  5126.2  302.34  5152.8  303.58  5183.5   303.6
  5221.2  304.76  5226.4  304.42  5271.3  306.45  5276.4  306.28  5321.4  308.61
  5336.7  308.76  5357.1  309.88  5371.5  309.92    5398  312.11  5435.6  312.34
#Mann= 5 ,-1 , 0
  4391.9     .05       0  4975.9     .16       0  4989.4     .05       0
  5009.8     .16       0  5074.7     .05       0
Bank Sta=4996.6,5002.6
XS Rating Curve= 0 ,0
Exp/Cntr=0.3,0.1

Type RM Length L Ch R = 1 ,240     ,0,0,0
BEGIN DESCRIPTION:
BUCKHORN BRANCH 2.0
END DESCRIPTION:
XS GIS Cut Line= 4
      3570384.59      10330155.3      3571313.42     10330035.51
      3571327.31     10329589.33      3571113.78     10329129.29
#Sta/Elev= 30
  3837.8  305.79  3982.6  302.34  4026.9  301.73  4278.9  300.23    4420  298.55
  4571.3  297.69  4641.9  296.68  4742.8  297.04  4761.7   296.4  4766.7  296.89
  4858.2   297.2  4938.3  296.06  4978.3  296.14  4995.3  294.71    4998  294.21
  5001.3  294.71  5008.3  296.03  5029.5  296.65  5078.3  297.41  5108.4  296.85
  5168.4  297.15  5229.2  296.46  5306.4  297.39  5372.5  297.31  5449.7  299.91
  5525.7  301.92  5589.3  305.07  5622.8  306.87  5649.1  307.61  5727.9  309.64
#Mann= 8 ,-1 , 0
  3837.8     .05       0    4420      .1       0  4978.3     .05       0
  5008.3     .16       0  5029.5      .1       0  5449.7     .05       0
  5589.3      .1       0  5649.1     .05       0
Bank Sta=4995.3,5001.3
XS Rating Curve= 0 ,0
Exp/Cntr=0.3,0.1

Chan Stop Cuts=-1
Use User Specified Reach Order=0
Composite Channel Slope=5