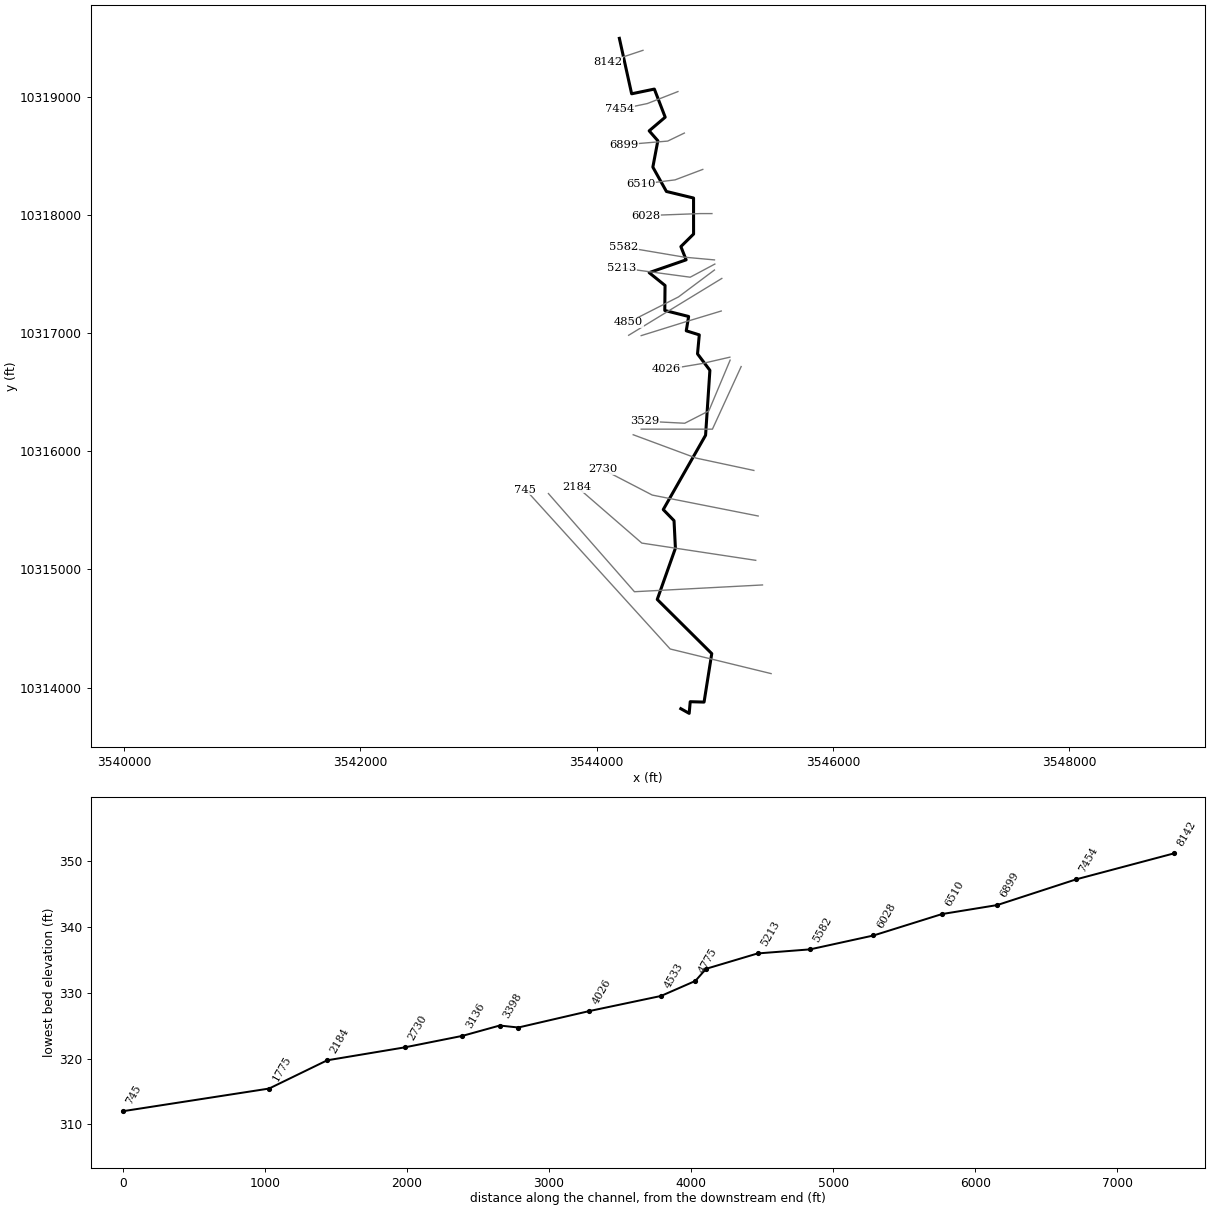
--- CAJKA BRANCH.prj (project) ---

Proj Title=CAJKA BRANCH Base Level Engineering
Current Plan=p01
Default Exp/Contr=0.3,0.1
English Units
Geom File=g01
Flow File=f01
Plan File=p01
BEGIN DESCRIPTION:
CAJKA BRANCH
END DESCRIPTION:

--- CAJKA BRANCH.p01 (plan) ---

Plan Title=Multiple Run
Short Identifier=Multiple
Geom File=g01
Flow File=f01
Subcritical Flow
K Sum by GR= 0
Std Step Tol= 0.01
Critical Tol= 0.01
Num of Std Step Trials= 20
Max Error Tol= 0.3
Flow Tol Ratio= 0.001
Split Flow NTrial= 30
Split Flow Tol= 0.02
Split Flow Ratio= 0.02
Log Output Level= 0
Friction Slope Method= 1
Unsteady Friction Slope Method= 2
Unsteady Bridges Friction Slope Method= 1
Parabolic Critical Depth
Global Vel Dist=  1 , 1 , 1
Global Log Level= 0
CheckData=True
Encroach Param= -1, 0, 0, 0
BEGIN DESCRIPTION:
Multiple Run
END DESCRIPTION:

--- CAJKA BRANCH.f01 (steady flow) ---

Flow Title=Multiple
Number of Profiles=7
Profile Names=10-year,25-year,50-year,1pct_min,100-year,1pct_plu,500-year
River Rch & RM= CAJKA BRANCH,Reach-1,8142
     434     578     693     610     825    1116    1171
Boundary for River Rch & Prof#=CAJKA BRANCH,Reach-1,1
Up Type=0
Dn Type=3
Dn Slope=0.005
Boundary for River Rch & Prof#=CAJKA BRANCH,Reach-1,2
Up Type=0
Dn Type=3
Dn Slope=0.005
Boundary for River Rch & Prof#=CAJKA BRANCH,Reach-1,3
Up Type=0
Dn Type=3
Dn Slope=0.005
Boundary for River Rch & Prof#=CAJKA BRANCH,Reach-1,4
Up Type=0
Dn Type=3
Dn Slope=0.005
Boundary for River Rch & Prof#=CAJKA BRANCH,Reach-1,5
Up Type=0
Dn Type=3
Dn Slope=0.005
Boundary for River Rch & Prof#=CAJKA BRANCH,Reach-1,6
Up Type=0
Dn Type=3
Dn Slope=0.005
Boundary for River Rch & Prof#=CAJKA BRANCH,Reach-1,7
Up Type=0
Dn Type=3
Dn Slope=0.005

--- CAJKA BRANCH.g01 (geometry) ---

Geom Title=Existing Conditions

River Reach=CAJKA BRANCH,Reach-1
Reach XY= 30
      3544192.34     10319493.05      3544296.12     10319023.79
      3544488.33     10319063.74      3544579.98     10318825.83
      3544444.52     10318710.45      3544517.76     10318626.68
      3544475.59     10318403.40      3544590.34     10318197.49
      3544819.90     10318141.98      3544820.18     10317837.25
      3544712.73     10317731.12      3544757.02     10317619.09
      3544444.15     10317510.73      3544578.70     10317402.23
      3544576.53     10317190.64      3544778.33     10317139.85
      3544758.11     10317018.62      3544868.41     10316984.26
      3544853.48     10316823.41      3544958.13     10316684.52
      3544921.67     10316135.04      3544563.59     10315506.13
      3544654.74     10315412.38      3544666.46     10315179.31
      3544512.81     10314745.72      3544973.97     10314287.60
      3544908.86     10313877.44      3544791.68     10313880.70
      3544783.00     10313781.96      3544712.11     10313821.64

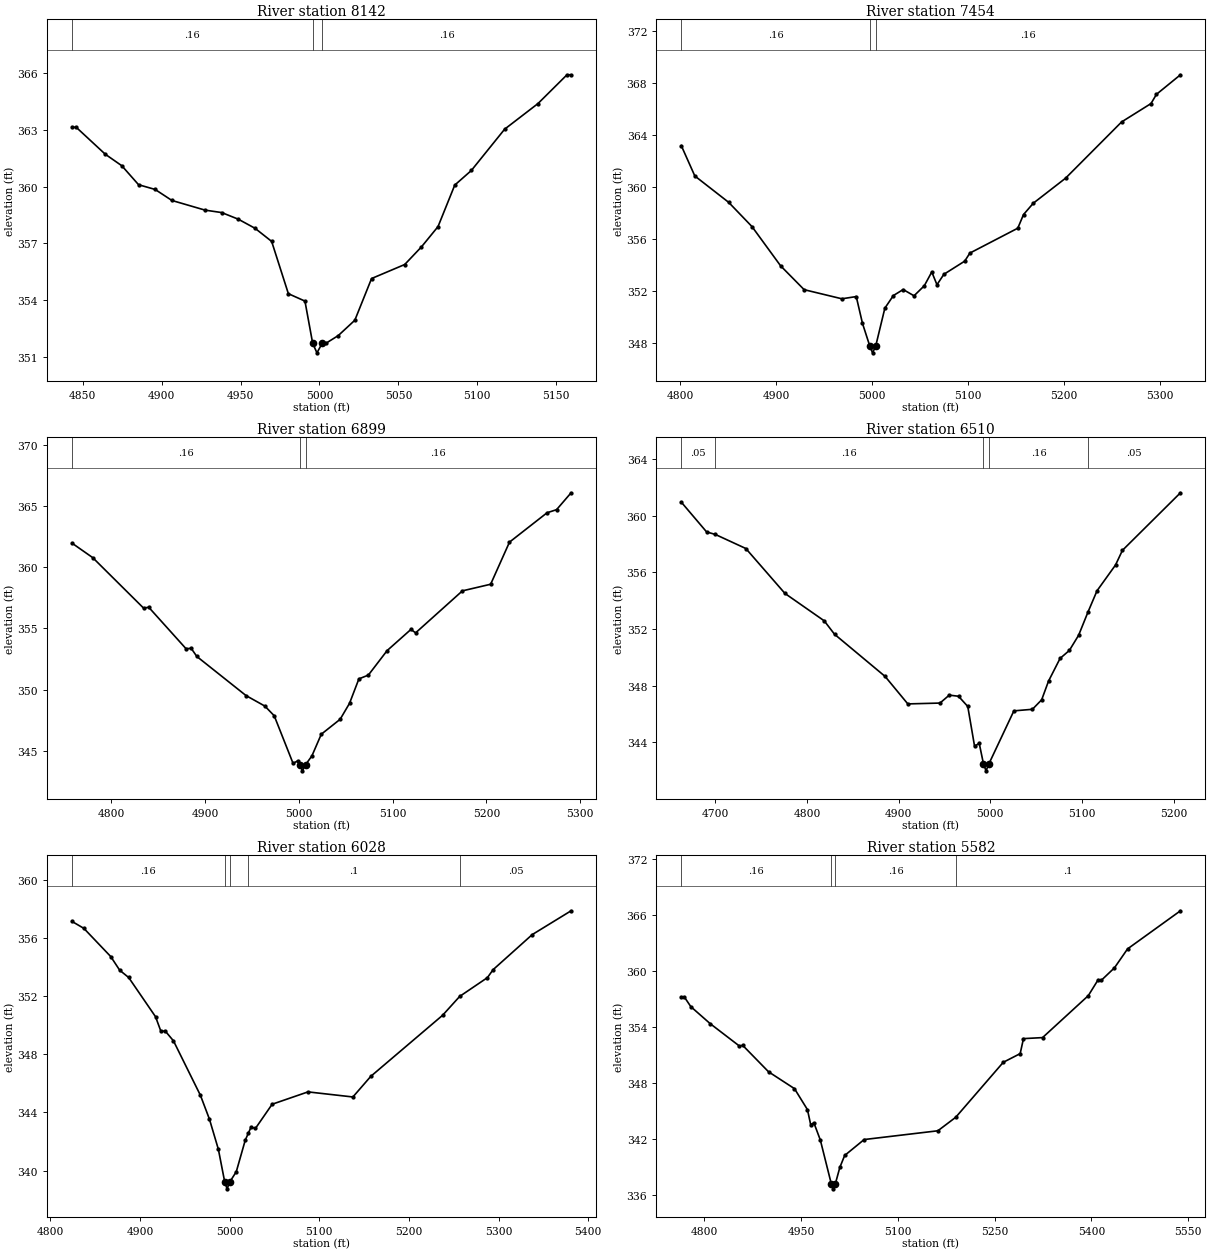
Type RM Length L Ch R = 1,8142,688,688,688
BEGIN DESCRIPTION:
CAJKA BRANCH 15.0
END DESCRIPTION:
XS GIS Cut Line= 3
      3544392.13     10319391.65      3544242.11     10319341.64
      3544092.15     10319291.66
#Sta/Elev= 30
  4843.2  363.13  4845.9  363.13  4864.3  361.71  4874.8  361.10  4885.4  360.10
  4895.9  359.85  4906.5  359.27  4927.5  358.76  4938.1  358.63  4948.6  358.28
  4959.2  357.80  4969.7  357.11  4980.3  354.35  4990.8  353.96  4995.7  351.73
  4998.4  351.23  5001.7  351.73  5004.0  351.73  5011.9  352.14  5022.4  352.95
  5033.0  355.15  5054.0  355.89  5064.6  356.82  5075.1  357.89  5085.7  360.08
  5096.2  360.85  5117.3  363.03  5138.4  364.38  5156.8  365.90  5159.4  365.90
#Mann=3,-1,0
  4843.2    0.16       0  4995.7    0.07       0  5001.7    0.16       0
Bank Sta=4995.7,5001.7
Exp/Cntr=0.3,0.1

Type RM Length L Ch R = 1,7454,555,555,555
BEGIN DESCRIPTION:
CAJKA BRANCH 14.0
END DESCRIPTION:
XS GIS Cut Line= 3
      3544687.90     10319042.67      3544429.19     10318941.39
      3544192.08     10318891.64
#Sta/Elev= 30
  4801.0  363.19  4815.1  360.86  4850.3  358.84  4874.7  356.97  4904.5  353.96
  4929.0  352.13  4968.3  351.43  4983.3  351.60  4989.8  349.54  4997.5  347.78
  5000.3  347.28  5003.5  347.78  5013.1  350.71  5022.0  351.68  5032.2  352.14
  5043.5  351.66  5054.2  352.43  5062.0  353.49  5067.4  352.51  5074.6  353.31
  5096.3  354.32  5101.7  354.94  5151.6  356.85  5157.6  357.90  5167.8  358.77
  5201.4  360.69  5259.8  365.01  5290.4  366.42  5296.1  367.13  5321.1  368.63
#Mann=3,-1,0
  4801.0    0.16       0  4997.5    0.07       0  5003.5    0.16       0
Bank Sta=4997.5,5003.5
Exp/Cntr=0.3,0.1

Type RM Length L Ch R = 1,6899,389,389,389
BEGIN DESCRIPTION:
CAJKA BRANCH 13.0
END DESCRIPTION:
XS GIS Cut Line= 3
      3544742.10     10318691.64      3544601.07     10318623.68
      3544226.62     10318592.48
#Sta/Elev= 30
  4758.1  361.97  4780.3  360.78  4834.5  356.66  4840.0  356.73  4879.7  353.35
  4885.3  353.37  4891.3  352.71  4943.7  349.52  4963.8  348.66  4973.8  347.87
  4993.9  343.98  4999.2  344.20  5001.2  343.87  5003.9  343.37  5007.2  343.87
  5014.0  344.59  5024.0  346.36  5044.1  347.58  5054.1  348.88  5064.1  350.88
  5074.2  351.19  5094.2  353.19  5119.6  354.92  5124.6  354.64  5174.5  358.07
  5204.6  358.61  5224.7  362.05  5264.8  364.45  5274.9  364.70  5290.4  366.08
#Mann=3,-1,0
  4758.1    0.16       0  5001.2    0.07       0  5007.2    0.16       0
Bank Sta=5001.2,5007.2
Exp/Cntr=0.3,0.1

Type RM Length L Ch R = 1,6510,482,482,482
BEGIN DESCRIPTION:
CAJKA BRANCH 12.0
END DESCRIPTION:
XS GIS Cut Line= 3
      3544897.92     10318384.09      3544663.57     10318295.56
      3544371.85     10318259.09
#Sta/Elev= 30
  4663.0  360.95  4690.6  358.85  4700.2  358.67  4733.4  357.68  4776.1  354.51
  4818.9  352.58  4830.2  351.63  4885.3  348.66  4910.1  346.72  4945.2  346.78
  4955.3  347.34  4965.4  347.26  4975.5  346.54  4982.9  343.74  4988.0  343.94
  4992.6  342.50  4995.4  342.00  4998.6  342.50  5025.8  346.23  5046.0  346.34
  5056.1  347.01  5063.6  348.33  5076.2  349.93  5086.3  350.49  5096.4  351.56
  5106.7  353.21  5116.5  354.70  5136.7  356.52  5144.2  357.55  5207.5  361.61
#Mann=5,-1,0
  4663.0    0.05       0  4700.2    0.16       0  4992.6    0.07       0
  4998.6    0.16       0  5106.7    0.05       0
Bank Sta=4992.6,4998.6
Exp/Cntr=0.3,0.1

Type RM Length L Ch R = 1,6028,446,446,446
BEGIN DESCRIPTION:
CAJKA BRANCH 11.0
END DESCRIPTION:
XS GIS Cut Line= 3
      3544975.44     10318010.39      3544875.44     10318010.39
      3544418.76     10317993.47
#Sta/Elev= 30
  4824.0  357.14  4837.3  356.66  4867.3  354.72  4877.3  353.78  4887.3  353.28
  4917.3  350.58  4923.2  349.59  4928.2  349.59  4937.3  348.92  4967.4  345.17
  4977.4  343.54  4987.4  341.46  4994.4  339.24  4997.1  338.74  5000.4  339.24
  5007.4  339.92  5017.4  342.09  5020.8  342.56  5023.8  342.98  5028.8  342.90
  5047.4  344.56  5087.4  345.41  5137.5  345.06  5157.5  346.48  5237.6  350.68
  5256.7  351.98  5287.6  353.27  5294.0  353.82  5337.6  356.23  5381.0  357.87
#Mann=5,-1,0
  4824.0    0.16       0  4994.4    0.07       0  5000.4    0.16       0
  5020.8     0.1       0  5256.7    0.05       0
Bank Sta=4994.4,5000.4
Exp/Cntr=0.3,0.1

Type RM Length L Ch R = 1,5582,369,369,369
BEGIN DESCRIPTION:
CAJKA BRANCH 10.0
END DESCRIPTION:
XS GIS Cut Line= 3
      3544996.87     10317618.48      3544742.11     10317641.64
      3544231.24     10317727.85
#Sta/Elev= 30
  4764.2  357.20  4769.1  357.20  4779.0  356.18  4809.1  354.35  4854.4  351.95
  4859.4  352.03  4899.5  349.19  4939.7  347.38  4959.8  345.13  4964.8  343.52
  4969.8  343.71  4979.8  341.86  4996.9  337.13  4999.7  336.63  5002.9  337.13
  5010.0  338.93  5017.5  340.21  5047.7  341.92  5162.0  342.86  5189.7  344.31
  5263.4  350.21  5289.6  351.14  5294.7  352.75  5324.3  352.86  5395.2  357.36
  5410.5  359.07  5415.6  359.02  5435.8  360.35  5456.1  362.38  5538.1  366.47
#Mann=4,-1,0
  4764.2    0.16       0  4996.9    0.07       0  5002.9    0.16       0
  5189.7     0.1       0
Bank Sta=4996.9,5002.9
Exp/Cntr=0.3,0.1

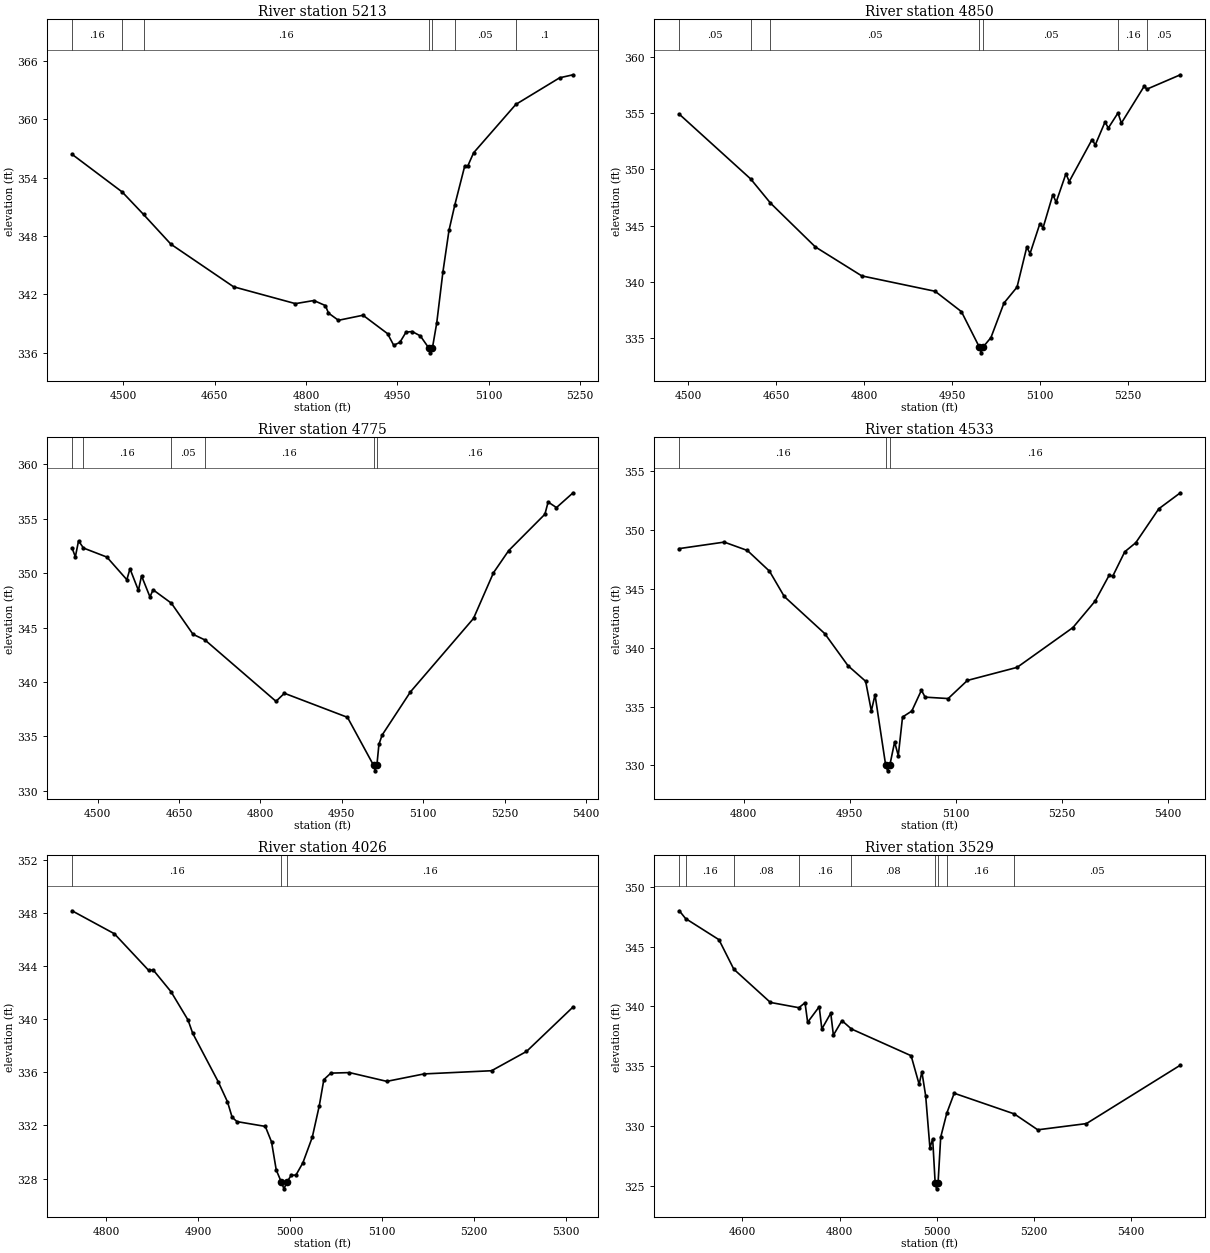
Type RM Length L Ch R = 1,5213,363,363,363
BEGIN DESCRIPTION:
Mapping XS 26306086
END DESCRIPTION:
XS GIS Cut Line= 3
      3545000.06     10317583.28      3544791.72     10317472.17
      3544210.17     10317550.29
#Sta/Elev= 30
  4415.8  356.39  4498.2  352.52  4533.3  350.21  4578.2  347.16  4681.1  342.79
  4782.7  341.06  4813.0  341.38  4831.9  340.86  4837.0  340.09  4853.3  339.35
  4893.7  339.87  4934.0  337.98  4944.1  336.79  4954.2  337.08  4964.3  338.13
  4974.4  338.20  4987.8  337.75  5001.7  336.51  5004.4  336.01  5007.7  336.51
  5014.8  339.09  5024.9  344.30  5034.9  348.58  5044.5  351.20  5060.6  355.15
  5065.7  355.18  5075.3  356.54  5144.7  361.51  5216.6  364.24  5238.7  364.55
#Mann=7,-1,0
  4415.8    0.16       0  4498.2    0.05       0  4533.3    0.16       0
  5001.7    0.07       0  5007.7    0.16       0  5044.5    0.05       0
  5144.7     0.1       0
Bank Sta=5001.7,5007.7
Exp/Cntr=0.3,0.1

Type RM Length L Ch R = 1,4850,75,75,75
BEGIN DESCRIPTION:
CAJKA BRANCH 9.0
END DESCRIPTION:
XS GIS Cut Line= 3
      3544996.56     10317532.91      3544692.77     10317305.50
      3544269.11     10317090.20
#Sta/Elev= 30
  4484.4  354.91  4606.1  349.15  4639.9  347.00  4716.4  343.10  4795.6  340.52
  4920.7  339.15  4965.6  337.34  4996.3  334.17  4999.1  333.67  5002.3  334.17
  5016.0  335.03  5038.2  338.10  5060.5  339.52  5077.1  343.08  5082.7  342.51
  5099.4  345.16  5105.0  344.82  5121.6  347.75  5127.2  347.08  5143.9  349.61
  5149.5  348.92  5188.4  352.65  5194.0  352.18  5210.6  354.22  5216.2  353.68
  5232.7  355.02  5238.5  354.12  5277.4  357.40  5282.0  357.14  5339.1  358.42
#Mann=7,-1,0
  4484.4    0.05       0  4606.1    0.16       0  4639.9    0.05       0
  4996.3    0.04       0  5002.3    0.05       0  5232.7    0.16       0
  5282.0    0.05       0
Bank Sta=4996.3,5002.3
Exp/Cntr=0.3,0.1

Type RM Length L Ch R = 1,4775,242,242,242
BEGIN DESCRIPTION:
Mapping XS eb747450
END DESCRIPTION:
XS GIS Cut Line= 2
      3545059.12     10317461.77      3544270.86     10316980.83
#Sta/Elev= 30
  4452.7  352.32  4458.8  351.50  4464.7  352.97  4473.8  352.31  4516.9  351.48
  4553.7  349.40  4559.5  350.40  4575.0  348.42  4580.8  349.75  4596.3  347.82
  4602.1  348.47  4635.8  347.24  4675.7  344.38  4697.7  343.86  4828.6  338.22
  4844.1  338.96  4960.3  336.75  5008.5  332.33  5011.2  331.83  5014.5  332.33
  5018.3  334.27  5024.2  335.12  5076.4  339.09  5192.6  345.84  5229.4  350.04
  5257.5  352.08  5324.2  355.42  5330.1  356.54  5345.5  356.03  5376.1  357.39
#Mann=6,-1,0
  4452.7    0.05       0  4473.8    0.16       0  4635.8    0.05       0
  4697.7    0.16       0  5008.5    0.07       0  5014.5    0.16       0
Bank Sta=5008.5,5014.5
Exp/Cntr=0.3,0.1

Type RM Length L Ch R = 1,4533,507,507,507
BEGIN DESCRIPTION:
CAJKA BRANCH 8.0
END DESCRIPTION:
XS GIS Cut Line= 3
      3545054.16     10317186.17      3544742.11     10317091.64
      3544377.09     10316977.84
#Sta/Elev= 30
  4708.9  348.42  4772.4  348.97  4805.1  348.26  4836.4  346.50  4857.3  344.35
  4914.5  341.20  4947.4  338.47  4972.3  337.15  4980.4  334.63  4985.6  336.00
  5000.6  330.04  5003.4  329.54  5006.6  330.04  5013.3  331.99  5018.5  330.83
  5024.5  334.11  5037.6  334.62  5051.2  336.39  5056.4  335.80  5089.0  335.68
  5116.2  337.22  5186.5  338.33  5265.4  341.71  5296.8  343.96  5316.5  346.14
  5321.8  346.09  5338.7  348.15  5354.3  348.92  5386.8  351.80  5417.3  353.16
#Mann=3,-1,0
  4708.9    0.16       0  5000.6    0.07       0  5006.6    0.16       0
Bank Sta=5000.6,5006.6
Exp/Cntr=0.3,0.1

Type RM Length L Ch R = 1,4026,497,497,497
BEGIN DESCRIPTION:
CAJKA BRANCH 7.0
END DESCRIPTION:
XS GIS Cut Line= 3
      3545127.08     10316795.55      3544892.11     10316741.64
      3544592.12     10316691.64
#Sta/Elev= 30
  4762.7  348.16  4808.8  346.43  4846.0  343.68  4851.1  343.70  4870.4  342.07
  4888.9  339.94  4894.0  338.94  4921.7  335.30  4931.8  333.79  4936.9  332.62
  4942.2  332.29  4973.0  331.93  4979.8  330.76  4984.9  328.65  4990.5  327.73
  4993.3  327.23  4996.5  327.73  5001.2  328.26  5006.3  328.26  5013.9  329.19
  5024.1  331.11  5031.7  333.47  5036.7  335.45  5044.3  335.94  5064.6  335.98
  5105.2  335.32  5145.7  335.88  5219.2  336.12  5257.2  337.57  5307.9  340.92
#Mann=3,-1,0
  4762.7    0.16       0  4990.5    0.07       0  4996.5    0.16       0
Bank Sta=4990.5,4996.5
Exp/Cntr=0.3,0.1

Type RM Length L Ch R = 1,3529,131,131,131
BEGIN DESCRIPTION:
CAJKA BRANCH 6.0
END DESCRIPTION:
XS GIS Cut Line= 4
      3545129.39     10316770.32      3544949.13     10316340.99
      3544745.28     10316236.49      3544408.94     10316253.85
#Sta/Elev= 30
  4470.0  348.01  4482.9  347.36  4551.6  345.59  4582.2  343.12  4657.5  340.34
  4716.1  339.90  4728.8  340.31  4734.2  338.68  4758.0  339.98  4763.4  338.12
  4781.8  339.44  4787.2  337.60  4804.8  338.82  4824.2  338.12  4947.2  335.88
  4963.7  333.49  4969.4  334.53  4977.2  332.51  4985.9  328.18  4991.6  328.91
  4996.7  325.24  4999.5  324.74  5002.7  325.24  5008.1  329.06  5020.7  331.08
  5035.9  332.74  5159.6  331.01  5207.9  329.68  5308.1  330.20  5501.5  335.09
#Mann=9,-1,0
  4470.0    0.08       0  4482.9    0.16       0  4582.2    0.08       0
  4716.1    0.16       0  4824.2    0.08       0  4996.7    0.07       0
  5002.7    0.08       0  5020.7    0.16       0  5159.6    0.05       0
Bank Sta=4996.7,5002.7
Exp/Cntr=0.3,0.1

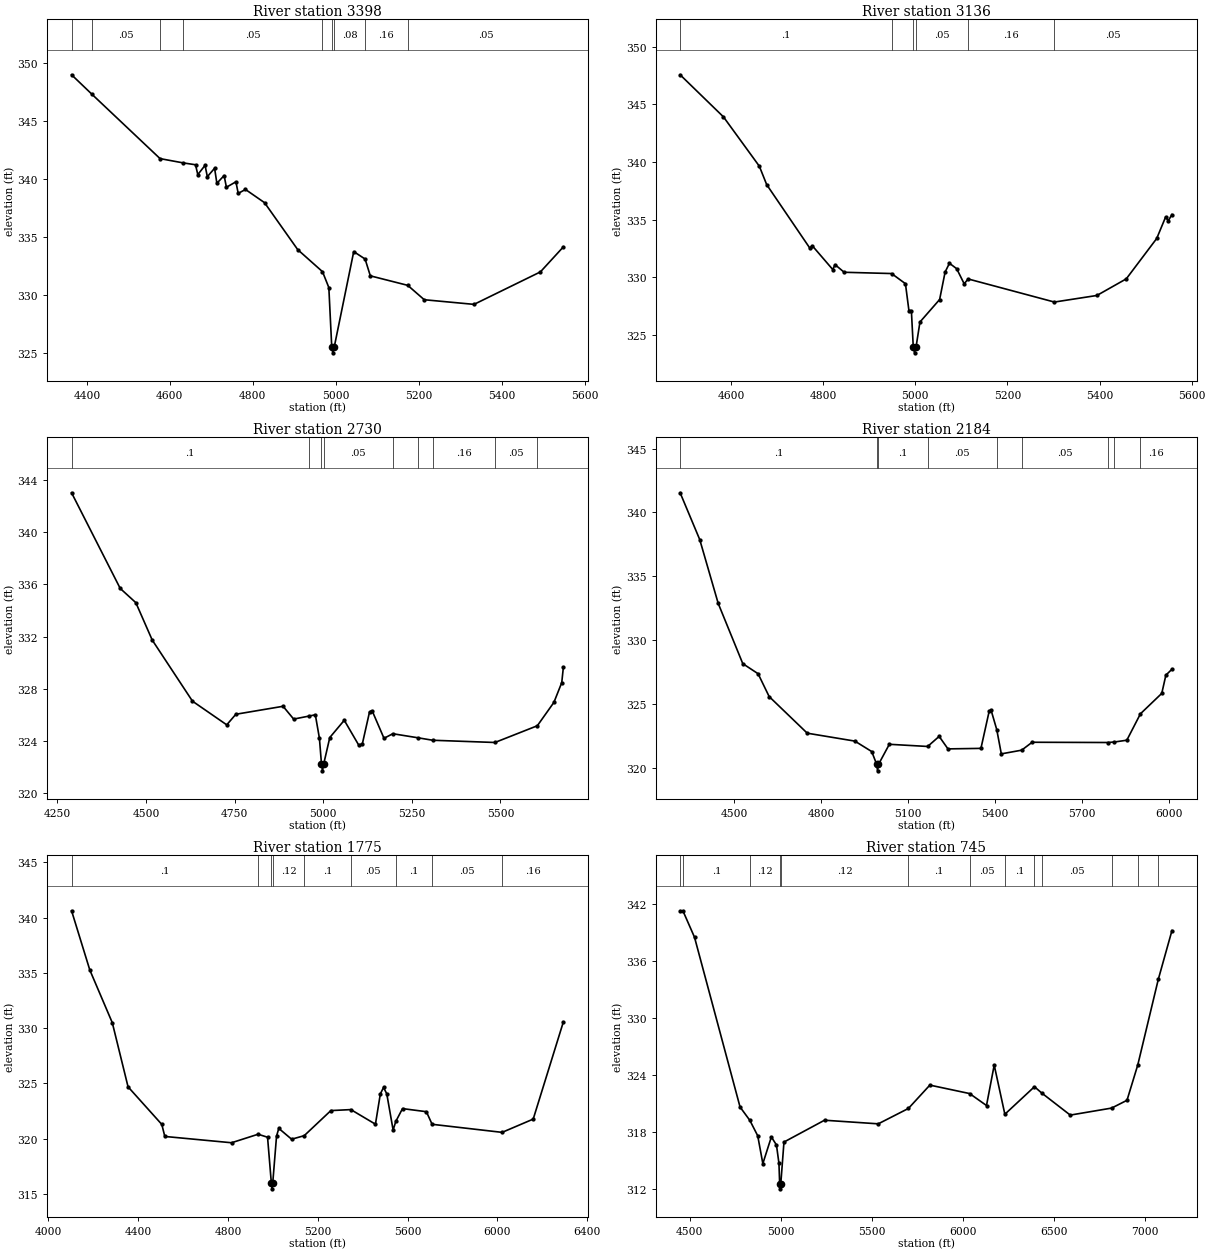
Type RM Length L Ch R = 1,3398,262,262,262
BEGIN DESCRIPTION:
Mapping XS ee87ec84
END DESCRIPTION:
XS GIS Cut Line= 3
      3545222.71     10316716.09      3544979.66     10316186.58
      3544376.68     10316186.58
#Sta/Elev= 30
  4363.2  349.02  4412.3  347.34  4576.5  341.79  4632.4  341.42  4662.0  341.26
  4667.5  340.41  4685.0  341.21  4690.5  340.23  4708.0  340.96  4713.5  339.66
  4730.9  340.33  4736.5  339.32  4759.4  339.79  4764.9  338.79  4782.4  339.13
  4828.4  337.99  4908.4  333.94  4968.1  332.04  4983.4  330.67  4990.4  325.54
  4993.1  325.04  4996.4  325.54  5043.4  333.77  5070.8  333.13  5083.4  331.68
  5173.6  330.86  5213.4  329.62  5333.4  329.22  5493.4  332.02  5548.8  334.18
#Mann=9,-1,0
  4363.2    0.08       0  4412.3    0.05       0  4576.5    0.08       0
  4632.4    0.05       0  4968.1    0.08       0  4990.4    0.07       0
  4996.4    0.08       0  5070.8    0.16       0  5173.6    0.05       0
Bank Sta=4990.4,4996.4
Exp/Cntr=0.3,0.1

Type RM Length L Ch R = 1,3136,406,406,406
BEGIN DESCRIPTION:
CAJKA BRANCH 5.0
END DESCRIPTION:
XS GIS Cut Line= 3
      3545330.25     10315837.22      3544842.11     10315941.64
      3544309.39     10316139.31
#Sta/Elev= 30
  4489.8  347.56  4583.9  343.91  4661.7  339.64  4677.7  338.04  4771.5  332.53
  4776.6  332.75  4821.0  330.69  4826.1  331.11  4845.8  330.45  4948.7  330.34
  4978.8  329.46  4986.4  327.12  4991.7  327.12  4995.8  323.97  4998.6  323.47
  5001.8  323.97  5010.3  326.14  5053.0  328.09  5064.9  330.47  5074.3  331.23
  5090.0  330.76  5106.3  329.45  5114.9  329.87  5302.1  327.87  5394.3  328.44
  5458.1  329.88  5524.2  333.38  5543.6  335.25  5549.2  334.91  5557.2  335.45
#Mann=6,-1,0
  4489.8     0.1       0  4948.7    0.05       0  4995.8    0.04       0
  5001.8    0.05       0  5114.9    0.16       0  5302.1    0.05       0
Bank Sta=4995.8,5001.8
Exp/Cntr=0.3,0.1

Type RM Length L Ch R = 1,2730,546,546,546
BEGIN DESCRIPTION:
CAJKA BRANCH 4.0
END DESCRIPTION:
XS GIS Cut Line= 3
      3545366.69     10315451.81      3544470.86     10315628.89
      3544049.95     10315847.14
#Sta/Elev= 30
  4290.2  343.00  4427.4  335.68  4471.5  334.59  4517.7  331.73  4631.3  327.05
  4727.9  325.24  4753.6  326.05  4886.8  326.66  4916.7  325.68  4959.8  325.91
  4977.8  326.01  4989.3  324.22  4995.2  322.22  4998.0  321.72  5001.2  322.22
  5018.6  324.27  5059.4  325.59  5100.2  323.69  5110.4  323.78  5130.7  326.23
  5138.0  326.32  5171.5  324.21  5196.4  324.56  5267.2  324.25  5309.2  324.06
  5484.4  323.89  5604.0  325.17  5650.8  326.96  5672.9  328.47  5677.5  329.66
#Mann=9,-1,0
  4290.2     0.1       0  4959.8    0.05       0  4995.2    0.04       0
  5001.2    0.05       0  5196.4    0.16       0  5267.2    0.05       0
  5309.2    0.16       0  5484.4    0.05       0  5604.0    0.16       0
Bank Sta=4995.2,5001.2
Exp/Cntr=0.3,0.1

Type RM Length L Ch R = 1,2184,409,409,409
BEGIN DESCRIPTION:
CAJKA BRANCH 3.0
END DESCRIPTION:
XS GIS Cut Line= 3
      3545345.88     10315076.80      3544382.32     10315222.64
      3543836.29     10315695.87
#Sta/Elev= 30
  4312.8  341.54  4380.5  337.87  4444.2  332.87  4529.0  328.15  4581.8  327.36
  4620.0  325.57  4751.5  322.70  4915.8  322.08  4974.0  321.26  4991.2  320.25
  4994.0  319.75  4997.2  320.25  5034.7  321.83  5167.0  321.66  5206.6  322.45
  5237.0  321.47  5350.8  321.51  5379.3  324.43  5386.0  324.49  5405.4  322.98
  5421.1  321.08  5491.4  321.37  5527.5  321.99  5788.0  321.97  5811.5  322.01
  5854.2  322.15  5901.2  324.22  5974.8  325.82  5989.0  327.25  6009.9  327.71
#Mann=9,-1,0
  4312.8     0.1       0  4991.2    0.07       0  4997.2     0.1       0
  5167.0    0.05       0  5405.4     0.1       0  5491.4    0.05       0
  5788.0    0.16       0  5811.5    0.05       0  5901.2    0.16       0
Bank Sta=4991.2,4997.2
Exp/Cntr=0.3,0.1

Type RM Length L Ch R = 1,1775,1030,1030,1030
BEGIN DESCRIPTION:
CAJKA BRANCH 2.0
END DESCRIPTION:
XS GIS Cut Line= 3
      3545403.16     10314868.47      3544319.82     10314811.18
      3543592.13     10315641.61
#Sta/Elev= 30
  4104.3  340.61  4185.5  335.25  4285.6  330.48  4355.7  324.68  4505.9  321.28
  4519.3  320.19  4816.3  319.62  4934.5  320.39  4976.6  320.12  4993.6  315.95
  4996.3  315.45  4999.6  315.95  5016.6  320.22  5026.6  320.92  5083.7  319.94
  5139.7  320.26  5258.4  322.53  5347.3  322.62  5456.8  321.30  5478.6  324.04
  5492.8  324.62  5507.1  324.06  5535.5  320.77  5547.4  321.55  5577.3  322.71
  5683.6  322.43  5709.0  321.29  6020.6  320.56  6159.0  321.76  6293.3  330.56
#Mann=9,-1,0
  4104.3     0.1       0  4934.5    0.12       0  4993.6    0.07       0
  4999.6    0.12       0  5139.7     0.1       0  5347.3    0.05       0
  5547.4     0.1       0  5709.0    0.05       0  6020.6    0.16       0
Bank Sta=4993.6,4999.6
Exp/Cntr=0.3,0.1

Type RM Length L Ch R = 1,745,0,0,0
BEGIN DESCRIPTION:
CAJKA BRANCH 1.0
END DESCRIPTION:
XS GIS Cut Line= 3
      3545476.07     10314118.47      3544621.90     10314326.81
      3543397.93     10315675.78
#Sta/Elev= 30
  4448.2  341.25  4463.4  341.30  4527.2  338.51  4777.3  320.62  4830.9  319.22
  4874.3  317.59  4902.4  314.66  4949.2  317.47  4977.2  316.62  4990.9  314.68
  4994.8  312.50  4997.6  312.00  5000.8  312.50  5018.4  316.93  5241.0  319.23
  5536.3  318.85  5701.7  320.47  5819.5  322.93  6037.8  322.04  6130.6  320.78
  6172.9  325.04  6231.4  319.86  6393.9  322.76  6433.7  322.10  6590.5  319.77
  6817.7  320.51  6902.1  321.33  6961.2  325.05  7073.8  334.06  7148.9  339.21
#Mann=13,-1,0
  4448.2    0.05       0  4463.4     0.1       0  4830.9    0.12       0
  4994.8    0.07       0  5000.8    0.12       0  5701.7     0.1       0
  6037.8    0.05       0  6231.4     0.1       0  6393.9    0.16       0
  6433.7    0.05       0  6817.7    0.16       0  6961.2    0.05       0
  7073.8    0.16       0
Bank Sta=4994.8,5000.8
Exp/Cntr=0.3,0.1

Chan Stop Cuts=-1