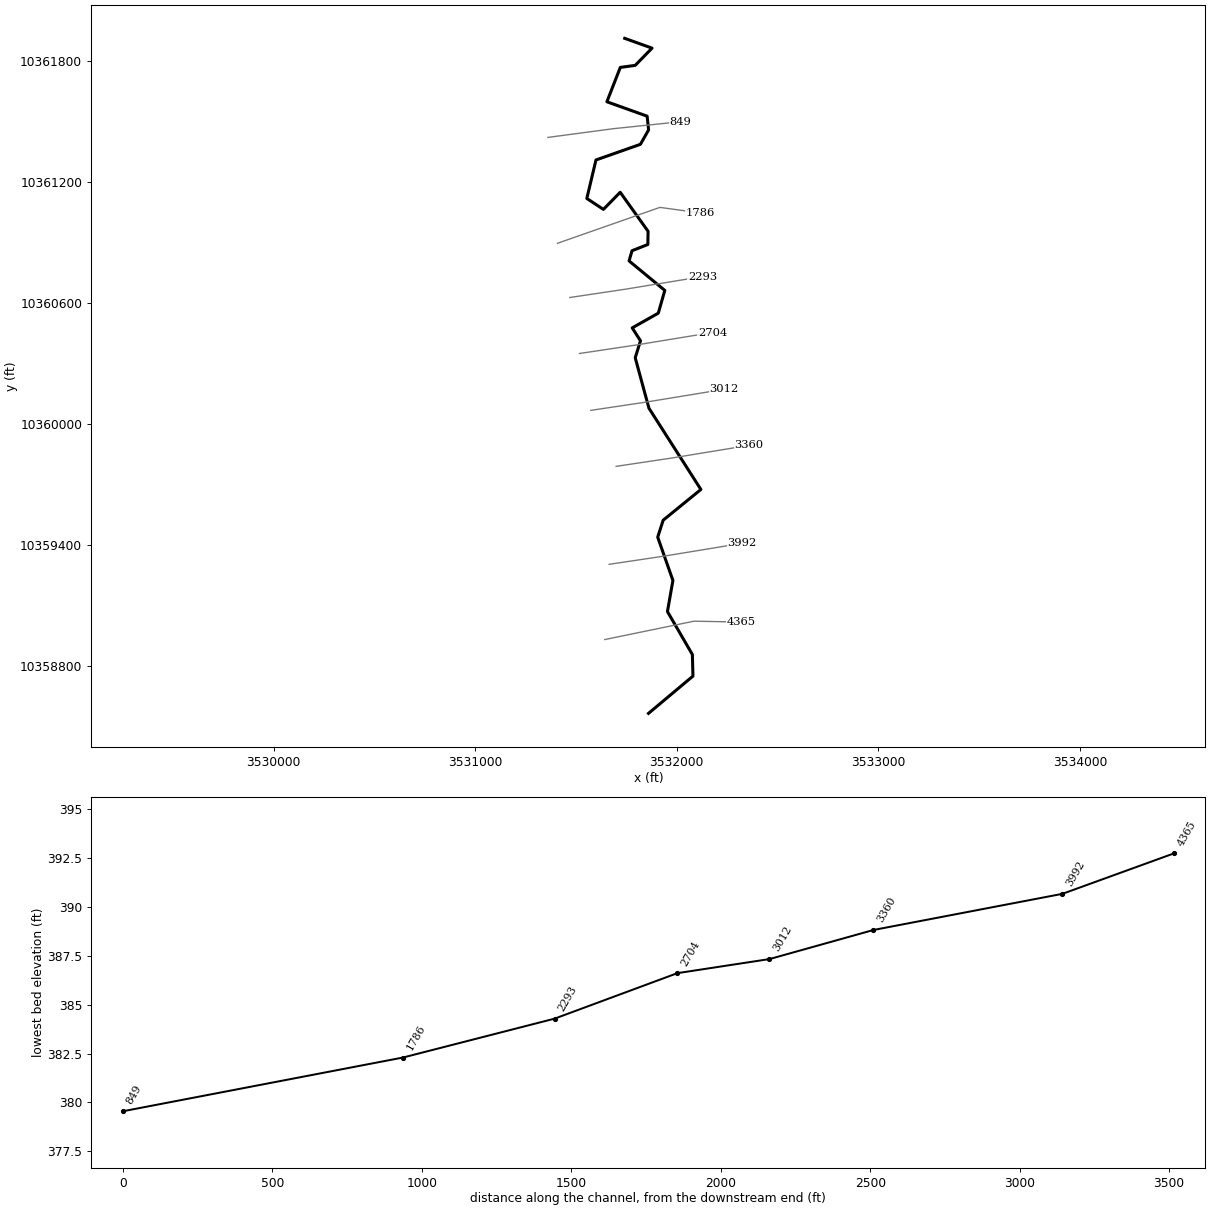
--- CAMP CREEK TRIBUTARY 22 1 1.prj (project) ---

Proj Title=CAMP CREEK TRIBUTARY 22 1 1 Base Level Engineering
Current Plan=p01
Default Exp/Contr=0.3,0.1
English Units
Geom File=g01
Flow File=f01
Plan File=p01
Y Axis Title=Elevation
X Axis Title(PF)=Main Channel Distance
X Axis Title(XS)=Station
BEGIN DESCRIPTION:
CAMP CREEK TRIBUTARY 22 1 1
END DESCRIPTION:
DSS Export Rating Curves= 0
DSS Export Rating Curve Sorted= 0
DSS Export Volume Flow Curves= 0
DXF OffsetX= 0
DXF OffsetY= 0
DXF ScaleX= 1
DXF ScaleY= 10

--- CAMP CREEK TRIBUTARY 22 1 1.p01 (plan) ---

Plan Title=Multiple Run
Short Identifier=Multiple
Geom File=g01
Flow File=f01
Subcritical Flow
K Sum by GR= 0
Std Step Tol= 0.01
Critical Tol= 0.01
Num of Std Step Trials= 20
Max Error Tol= 0.3
Flow Tol Ratio= 0.001
Split Flow NTrial= 30
Split Flow Tol= 0.02
Split Flow Ratio= 0.02
Log Output Level= 0
Friction Slope Method= 1
Unsteady Friction Slope Method= 2
Unsteady Bridges Friction Slope Method= 1
Parabolic Critical Depth
Global Vel Dist=  1 , 1 , 1
Global Log Level= 0
CheckData=True
Encroach Param= -1, 0, 0, 0
BEGIN DESCRIPTION:
Multiple Run
END DESCRIPTION:

--- CAMP CREEK TRIBUTARY 22 1 1.f01 (steady flow) ---

Flow Title=Multiple
Number of Profiles=7
Profile Names=10-year,25-year,50-year,1pct_min,100-year,1pct_plu,500-year
River Rch & RM= CAMP CREEK TRIBU,Reach-1,4365
    1110    1542    1902    1711    2313    3128    3415
Boundary for River Rch & Prof#=CAMP CREEK TRIBU,Reach-1,1
Up Type=0
Dn Type=3
Dn Slope=0.005
Boundary for River Rch & Prof#=CAMP CREEK TRIBU,Reach-1,2
Up Type=0
Dn Type=3
Dn Slope=0.005
Boundary for River Rch & Prof#=CAMP CREEK TRIBU,Reach-1,3
Up Type=0
Dn Type=3
Dn Slope=0.005
Boundary for River Rch & Prof#=CAMP CREEK TRIBU,Reach-1,4
Up Type=0
Dn Type=3
Dn Slope=0.005
Boundary for River Rch & Prof#=CAMP CREEK TRIBU,Reach-1,5
Up Type=0
Dn Type=3
Dn Slope=0.005
Boundary for River Rch & Prof#=CAMP CREEK TRIBU,Reach-1,6
Up Type=0
Dn Type=3
Dn Slope=0.005
Boundary for River Rch & Prof#=CAMP CREEK TRIBU,Reach-1,7
Up Type=0
Dn Type=3
Dn Slope=0.005

--- CAMP CREEK TRIBUTARY 22 1 1.g01 (geometry) ---

Geom Title=Existing Conditions
Program Version=4.10

River Reach=CAMP CREEK TRIBU,Reach-1
Reach XY= 30
      3531860.11     10358562.49      3532080.67     10358747.32
      3532077.81     10358854.47       3531954.1     10359067.63
      3531981.25       10359222.      3531905.81     10359436.75
      3531932.89     10359520.81      3532120.01     10359673.33
      3531862.24     10360076.71      3531794.24     10360326.85
      3531820.36     10360411.02      3531779.28     10360475.06
       3531908.7     10360548.09      3531941.02     10360661.05
      3531763.75     10360807.38      3531778.46     10360857.95
       3531856.9     10360888.81      3531857.98     10360954.33
      3531719.68     10361147.92       3531636.4     10361062.98
      3531554.12     10361117.21      3531599.53     10361308.15
      3531820.01      10361385.8      3531860.66     10361457.26
      3531853.37     10361525.41      3531653.71     10361596.98
      3531720.25      10361767.4      3531794.14     10361777.46
      3531877.68     10361862.96      3531742.11     10361911.64

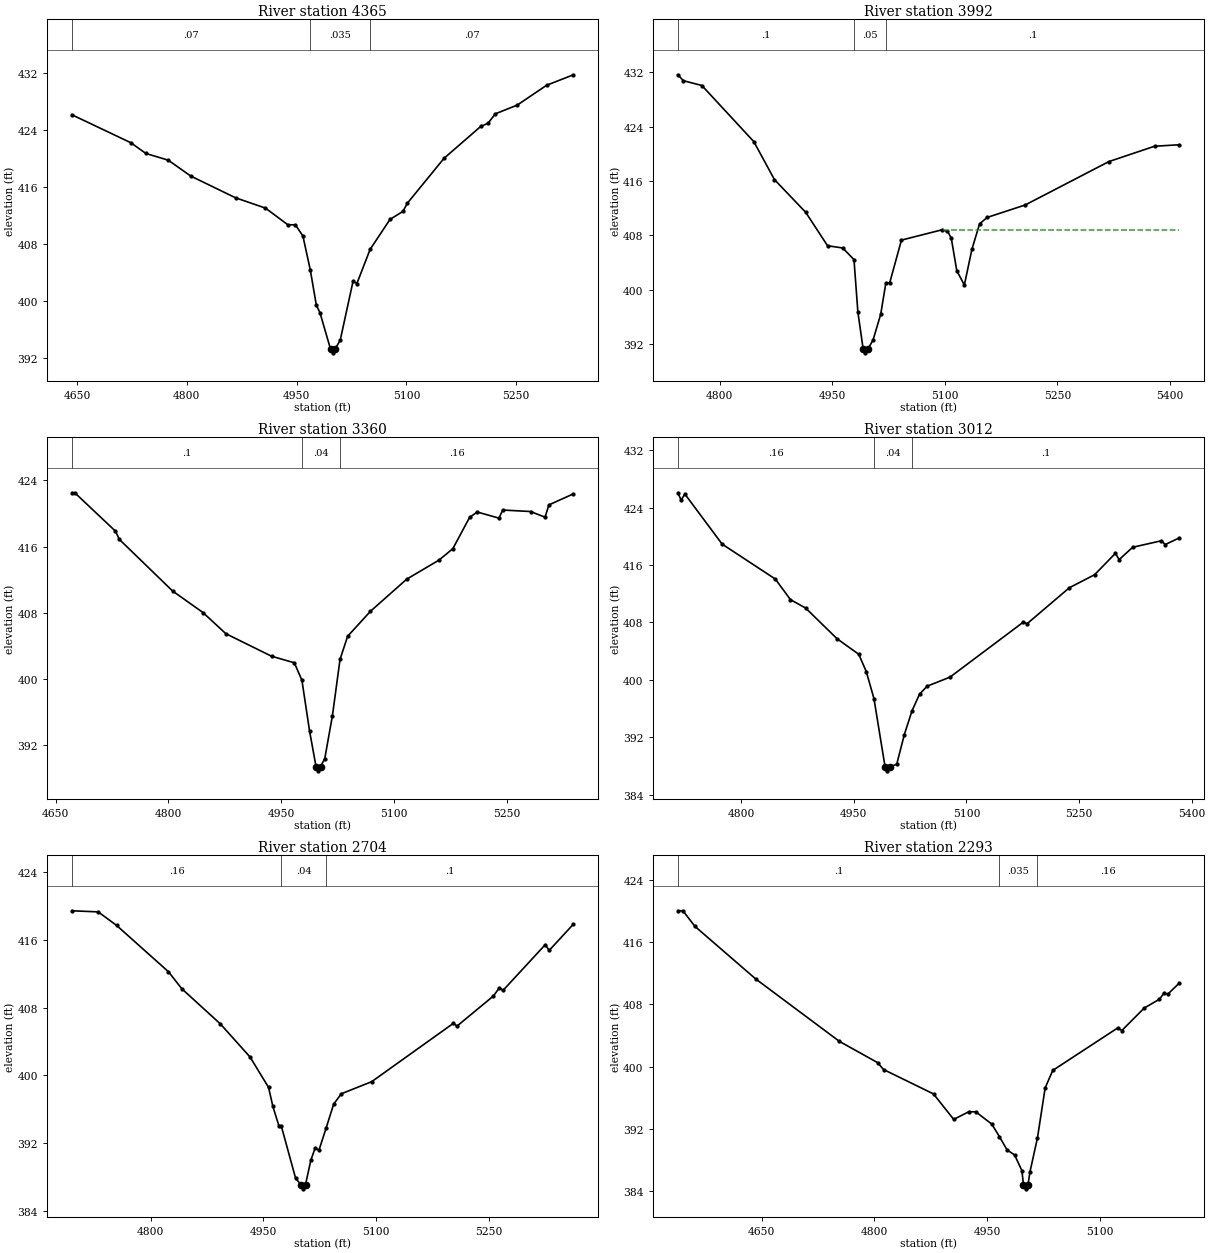
Type RM Length L Ch R = 1 ,4365    ,373,373,373
BEGIN DESCRIPTION:
CAMP CREEK TRIBUTARY 22.1.1 4.0
END DESCRIPTION:
XS GIS Cut Line= 3
      3531643.23     10358928.74      3532085.97      10359019.9
       3532318.7     10359015.59
#Sta/Elev= 30
  4643.2  426.09  4723.7  422.17  4744.2  420.67  4774.8  419.73  4805.4  417.51
  4866.7  414.46  4907.5  413.02  4938.1  410.68  4948.3  410.68  4958.6  409.12
  4968.8  404.31  4976.9  399.46    4982  398.34  4996.4  393.25  4999.1  392.75
  5002.4  393.25  5009.6  394.53  5027.2  402.82  5032.3  402.44  5050.4  407.24
  5077.5  411.43  5095.2  412.56  5101.4  413.72  5151.4     420  5201.4  424.45
  5211.4   424.9  5221.4  426.22  5251.4  427.45  5291.4  430.22    5328  431.69
#Mann= 3 ,-1 , 0
  4643.2     .07       0  4968.8    .035       0  5050.4     .07       0
Bank Sta=4996.4,5002.4
XS Rating Curve= 0 ,0
Exp/Cntr=0.3,0.1

Type RM Length L Ch R = 1 ,3992    ,632,632,632
BEGIN DESCRIPTION:
CAMP CREEK TRIBUTARY 22.1.1 3.4
END DESCRIPTION:
XS GIS Cut Line= 3
      3531665.02       10359302.      3531940.88     10359343.24
      3532324.73     10359406.16
#Sta/Elev= 30
  4744.6  431.65  4751.8  430.78  4776.5  430.07  4845.7   421.8  4873.1  416.22
  4914.9  411.37  4943.9  406.46  4964.1  406.13  4979.1  404.42  4984.3  396.69
  4991.4  391.18  4994.2  390.68  4997.4  391.18  5004.5  392.57  5014.7  396.36
  5021.6     401  5026.7     401  5042.3  407.29  5095.7  408.79  5103.6  408.62
  5108.7  407.58    5116  402.79  5126.1  400.67  5136.2  405.94  5146.4  409.69
  5156.5  410.63  5207.2  412.47  5318.6  418.86  5379.4  421.12  5412.5  421.34
#Mann= 3 ,-1 , 0
  4744.6      .1       0  4979.1     .05       0  5021.6      .1       0
#XS Ineff= 2 , 0
                         5097.27          408.84
Permanent Ineff=
       F       F
Bank Sta=4991.4,4997.4
XS Rating Curve= 0 ,0
Exp/Cntr=0.3,0.1

Type RM Length L Ch R = 1 ,3360    ,348,348,348
BEGIN DESCRIPTION:
CAMP CREEK TRIBUTARY 22.1.1 3.3
END DESCRIPTION:
XS GIS Cut Line= 3
      3531699.69      10359788.1      3531975.61     10359829.35
      3532358.31     10359892.09
#Sta/Elev= 30
  4671.6  422.51  4675.4  422.51  4729.5  417.86  4734.7  416.86  4805.5  410.61
  4845.9     408  4876.3  405.44  4937.1  402.71  4967.3  401.92  4977.4  399.81
  4987.6  393.65  4996.2  389.33    4999  388.83  5002.2  389.33  5007.8  390.31
    5018  395.52  5028.1  402.33  5038.2  405.13  5068.6  408.16  5116.8  412.05
  5159.8  414.36  5178.1  415.74  5200.4  419.53  5210.5  420.18  5239.4  419.44
  5244.5  420.42  5281.4  420.24  5300.7  419.55  5305.8  421.04  5338.4  422.38
#Mann= 3 ,-1 , 0
  4671.6      .1       0  4977.4     .04       0  5028.1     .16       0
Bank Sta=4996.2,5002.2
XS Rating Curve= 0 ,0
Exp/Cntr=0.3,0.1

Type RM Length L Ch R = 1 ,3012    ,308,308,308
BEGIN DESCRIPTION:
CAMP CREEK TRIBUTARY 22.1.1 3.2
END DESCRIPTION:
XS GIS Cut Line= 3
      3531573.84     10360065.88      3531849.74     10360107.13
      3532233.55     10360170.05
#Sta/Elev= 30
  4715.7  426.06  4719.9  425.04    4725  425.88  4774.6  418.91  4845.4  414.05
  4865.6  411.18  4885.8  410.01  4927.5  405.75  4956.6  403.57  4966.7  401.13
  4976.8   397.4  4991.7  387.84  4994.4  387.34  4997.7  387.84  5007.2  388.28
  5017.3   392.4  5027.5   395.7  5037.6  398.03  5047.7  399.13  5078.1  400.39
  5175.8  408.05  5180.8  407.83  5237.1  412.84  5270.7  414.65  5298.4  417.63
  5303.4  416.75  5321.3  418.47  5359.7  419.38  5364.7  418.85  5383.6  419.78
#Mann= 3 ,-1 , 0
  4715.7     .16       0  4976.8     .04       0  5027.5      .1       0
Bank Sta=4991.7,4997.7
XS Rating Curve= 0 ,0
Exp/Cntr=0.3,0.1

Type RM Length L Ch R = 1 ,2704    ,411,411,411
BEGIN DESCRIPTION:
CAMP CREEK TRIBUTARY 22.1.1 3.1
END DESCRIPTION:
XS GIS Cut Line= 3
      3531517.45       10360348.      3531793.31     10360389.24
      3532177.16     10360452.17
#Sta/Elev= 30
  4694.9  419.41  4729.9  419.28  4754.3  417.69  4823.5  412.22  4841.2  410.22
  4892.7  406.06  4932.2  402.16  4956.8  398.58  4962.5  396.35  4970.7  394.01
  4973.8  394.01  4992.9  387.84    5000  387.12  5002.8  386.62    5006  387.12
  5013.1  389.99  5018.9  391.45  5023.9  391.17  5033.4  393.77  5043.5  396.61
  5053.7  397.83  5094.2  399.26  5202.8  406.13  5207.9  405.82  5256.3  409.36
  5264.1  410.32  5269.2  410.03  5325.4  415.42  5330.5  414.73  5362.8  417.83
#Mann= 3 ,-1 , 0
  4694.9     .16       0  4973.8     .04       0  5033.4      .1       0
Bank Sta=5000,5006
XS Rating Curve= 0 ,0
Exp/Cntr=0.3,0.1

Type RM Length L Ch R = 1 ,2293    ,507,507,507
BEGIN DESCRIPTION:
CAMP CREEK TRIBUTARY 22.1.1 3.0
END DESCRIPTION:
XS GIS Cut Line= 3
      3531469.67     10360625.78      3531745.57     10360667.02
      3532128.29     10360729.76
#Sta/Elev= 30
  4538.8  420.01  4545.5  420.01  4561.5     418  4642.4  411.24  4753.6  403.23
  4804.2  400.51  4812.2  399.62  4878.7  396.48  4905.5  393.21  4925.7   394.2
  4934.9  394.18  4956.1  392.61  4966.3     391  4976.4   389.3  4986.5  388.64
  4996.2  386.63  4998.3  384.79    5001  384.29  5004.3  384.79  5006.8  386.42
  5016.9  390.84  5027.1  397.25  5037.2   399.5  5123.9  404.98    5129  404.62
  5158.8  407.51  5179.1  408.65  5185.2  409.44  5190.3  409.31  5205.6  410.73
#Mann= 3 ,-1 , 0
  4538.8      .1       0  4966.3    .035       0  5016.9     .16       0
Bank Sta=4998.3,5004.3
XS Rating Curve= 0 ,0
Exp/Cntr=0.3,0.1

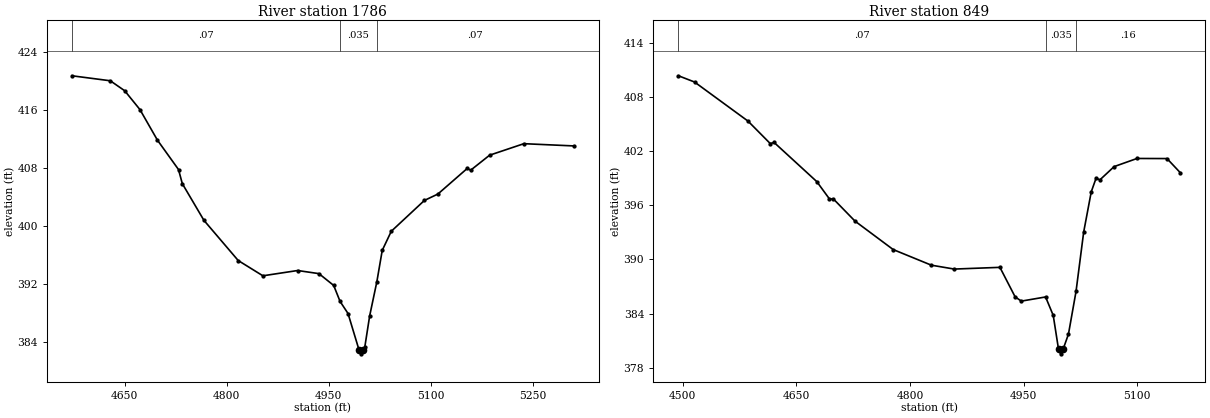
Type RM Length L Ch R = 1 ,1786    ,937,937,937
BEGIN DESCRIPTION:
CAMP CREEK TRIBUTARY 22.1.1 2.0
END DESCRIPTION:
XS GIS Cut Line= 3
      3531408.91      10360894.9       3531916.7     10361072.85
      3532114.78     10361045.73
#Sta/Elev= 30
  4572.3  420.71  4628.7  420.02  4649.9  418.64  4672.3  416.04    4698  411.82
    4729  407.76  4734.6  405.81  4766.4  400.74  4816.8  395.19  4853.1  393.08
  4904.2  393.81  4935.5  393.38  4957.2  391.75  4966.6  389.54  4978.3  387.87
  4994.6   382.8  4997.3   382.3  5000.6   382.8  5002.9   383.2  5010.1  387.54
  5020.7  392.27  5028.6  396.59  5041.9  399.23  5090.6  403.49  5110.4  404.37
  5153.6  407.91  5158.7  407.67  5186.5  409.74  5236.9  411.33  5310.3  411.02
#Mann= 3 ,-1 , 0
  4572.3     .07       0  4966.6    .035       0  5020.7     .07       0
Bank Sta=4994.6,5000.6
XS Rating Curve= 0 ,0
Exp/Cntr=0.3,0.1

Type RM Length L Ch R = 1 ,849     ,0,0,0
BEGIN DESCRIPTION:
CAMP CREEK TRIBUTARY 22.1.1 1.0
END DESCRIPTION:
XS GIS Cut Line= 3
       3531361.1     10361420.06      3531686.67     10361463.47
      3532019.03       10361498.
#Sta/Elev= 30
  4494.3  410.35  4515.5  409.66  4586.1  405.33  4615.5  402.84  4620.6  402.96
  4676.9  398.63  4693.7   396.7  4698.8  396.71  4727.4  394.25  4777.8   391.1
  4828.2  389.37  4858.4  388.94  4918.7  389.13  4938.8  385.86    4947  385.39
    4979  385.85  4989.1  383.81  4996.1  380.05  4998.9  379.55  5002.1  380.05
  5009.2  381.73  5019.2  386.46  5029.3  393.04  5039.3   397.5  5045.7  399.01
  5050.7  398.82  5069.5  400.29  5099.7  401.19  5139.3  401.18  5156.9  399.61
#Mann= 3 ,-1 , 0
  4494.3     .07       0    4979    .035       0  5019.2     .16       0
Bank Sta=4996.1,5002.1
XS Rating Curve= 0 ,0
Exp/Cntr=0.3,0.1

Chan Stop Cuts=-1
Use User Specified Reach Order=0
Composite Channel Slope=5