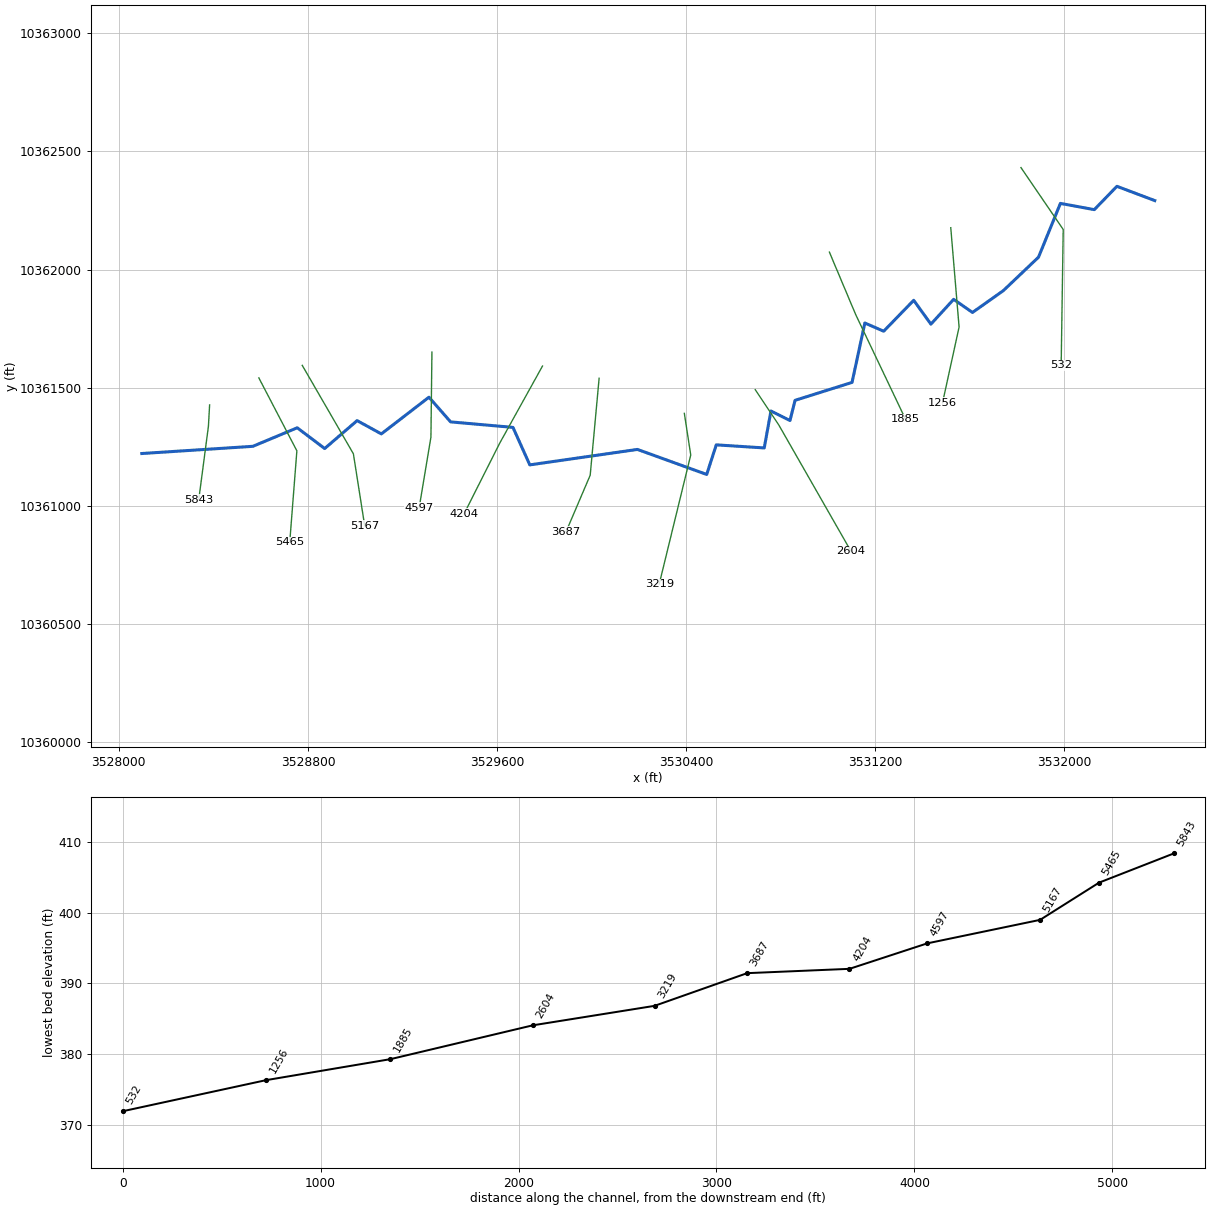
--- CAMP CREEK TRIBUTARY 22 1.prj (project) ---

Proj Title=CAMP CREEK TRIBUTARY 22 1 Base Level Engineering
Current Plan=p01
Default Exp/Contr=0.3,0.1
English Units
Geom File=g01
Flow File=f01
Plan File=p01
Y Axis Title=Elevation
X Axis Title(PF)=Main Channel Distance
X Axis Title(XS)=Station
BEGIN DESCRIPTION:
CAMP CREEK TRIBUTARY 22 1
END DESCRIPTION:
DSS Export Rating Curves= 0
DSS Export Rating Curve Sorted= 0
DSS Export Volume Flow Curves= 0
DXF OffsetX= 0
DXF OffsetY= 0
DXF ScaleX= 1
DXF ScaleY= 10

--- CAMP CREEK TRIBUTARY 22 1.p01 (plan) ---

Plan Title=Multiple Run
Short Identifier=Multiple
Geom File=g01
Flow File=f01
Subcritical Flow
K Sum by GR= 0
Std Step Tol= 0.01
Critical Tol= 0.01
Num of Std Step Trials= 20
Max Error Tol= 0.3
Flow Tol Ratio= 0.001
Split Flow NTrial= 30
Split Flow Tol= 0.02
Split Flow Ratio= 0.02
Log Output Level= 0
Friction Slope Method= 1
Unsteady Friction Slope Method= 2
Unsteady Bridges Friction Slope Method= 1
Parabolic Critical Depth
Global Vel Dist=  1 , 1 , 1
Global Log Level= 0
CheckData=True
Encroach Param= -1, 0, 0, 0
BEGIN DESCRIPTION:
Multiple Run
END DESCRIPTION:

--- CAMP CREEK TRIBUTARY 22 1.f01 (steady flow) ---

Flow Title=Multiple
Program Version=4.10
Number of Profiles= 7
Profile Names=10-year,25-year,50-year,1pct_min,100-year,1pct_plu,500-year
River Rch & RM=CAMP CREEK TRIBU,Reach-1         ,5843
    1025    1427    1762    1589    2149    2907    3189
River Rch & RM=CAMP CREEK TRIBU,Reach-1         ,3687
    1173    1645    2043    1851    2503    3385    3751
River Rch & RM=CAMP CREEK TRIBU,Reach-1         ,532
    1839    2627    3302    3021    4086    5526    6248
Boundary for River Rch & Prof#=CAMP CREEK TRIBU,Reach-1         , 1
Up Type= 0
Dn Type= 3
Dn Slope=0.0059
Boundary for River Rch & Prof#=CAMP CREEK TRIBU,Reach-1         , 2
Up Type= 0
Dn Type= 3
Dn Slope=0.0059
Boundary for River Rch & Prof#=CAMP CREEK TRIBU,Reach-1         , 3
Up Type= 0
Dn Type= 3
Dn Slope=0.0059
Boundary for River Rch & Prof#=CAMP CREEK TRIBU,Reach-1         , 4
Up Type= 0
Dn Type= 3
Dn Slope=0.0059
Boundary for River Rch & Prof#=CAMP CREEK TRIBU,Reach-1         , 5
Up Type= 0
Dn Type= 3
Dn Slope=0.0059
Boundary for River Rch & Prof#=CAMP CREEK TRIBU,Reach-1         , 6
Up Type= 0
Dn Type= 3
Dn Slope=0.0059
Boundary for River Rch & Prof#=CAMP CREEK TRIBU,Reach-1         , 7
Up Type= 0
Dn Type= 3
Dn Slope=0.0059
DSS Import GetInterval= 0
DSS Import GetPeak= 0
DSS Import FillOption= 0

--- CAMP CREEK TRIBUTARY 22 1.g01 (geometry) ---

Geom Title=Existing Conditions
Program Version=4.10

River Reach=CAMP CREEK TRIBU,Reach-1
Reach XY= 30
      3528097.11     10361221.64      3528566.91      10361252.1
      3528754.56     10361330.48       3528870.7     10361242.72
      3529007.84     10361360.81      3529110.35     10361304.65
      3529311.77     10361459.88      3529403.28     10361355.48
      3529667.16     10361332.18      3529738.32     10361173.59
      3530193.59     10361238.95      3530486.72     10361133.07
       3530527.2     10361258.26       3530730.1     10361245.32
      3530758.45     10361401.49        3530839.     10361361.21
      3530860.53     10361446.63      3531101.52     10361522.47
      3531155.72     10361773.69      3531235.36       10361739.
      3531362.37     10361869.79      3531435.17      10361768.9
      3531531.33     10361873.92      3531611.02     10361818.31
      3531741.61     10361910.76      3531890.33     10362052.22
      3531982.98     10362279.72      3532126.33     10362253.31
        3532222.     10362351.98      3532382.11     10362291.64

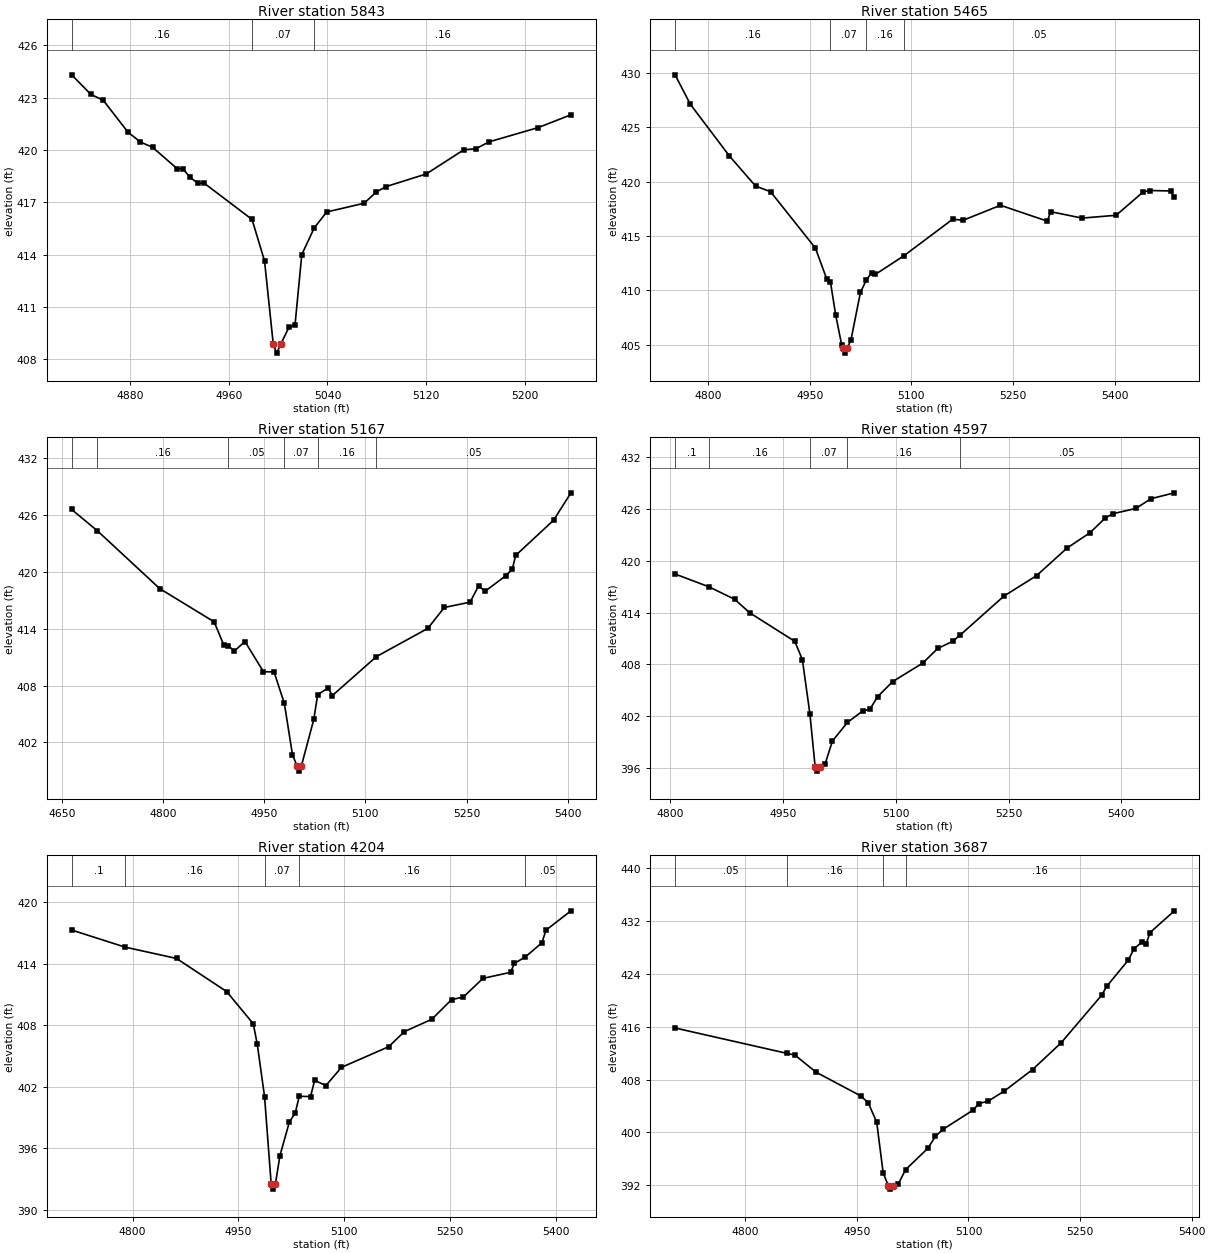
Type RM Length L Ch R = 1 ,5843    ,378,378,378
BEGIN DESCRIPTION:
CAMP CREEK TRIBUTARY 22.1 9.0
END DESCRIPTION:
XS GIS Cut Line= 3
      3528383.88     10361427.21      3528378.88     10361337.12
      3528337.87     10361025.44
#Sta/Elev= 30
  4832.7   424.3  4848.3  423.18  4858.3  422.84  4878.3  421.02  4888.4  420.45
  4898.4  420.14  4918.2  418.92  4922.9  418.92  4928.5  418.43    4935  418.09
  4940.1  418.09  4978.9  416.01    4989  413.64  4996.1  408.85  4998.8  408.35
  5002.1  408.85  5008.7  409.82  5013.7  409.96  5019.2     414  5029.3  415.53
  5039.4  416.44  5069.7  416.94  5079.7  417.59  5087.3  417.89  5120.1  418.62
  5150.4     420  5160.4  420.07    5171  420.46  5210.9  421.28  5237.3  422.01
#Mann= 3 ,-1 , 0
  4832.7     .16       0  4978.9     .07       0  5029.3     .16       0
Bank Sta=4996.1,5002.1
XS Rating Curve= 0 ,0
Exp/Cntr=0.3,0.1

Type RM Length L Ch R = 1 ,5465    ,298,298,298
BEGIN DESCRIPTION:
CAMP CREEK TRIBUTARY 22.1 8.1
END DESCRIPTION:
XS GIS Cut Line= 3
      3528592.12     10361541.62        3528753.     10361233.07
      3528722.84     10360846.01
#Sta/Elev= 30
  4751.6  429.84  4774.1  427.13  4831.7  422.37  4870.3   419.6  4892.4  419.08
  4958.6  413.88  4975.1  411.06  4980.7  410.77  4988.4  407.73  4997.2  404.99
  4999.8  404.72  5002.6  404.22  5005.8  404.72    5011  405.46  5024.9  409.81
  5033.5  410.94  5041.4  411.63    5047  411.47  5088.7  413.17  5161.2  416.56
  5175.8  416.44  5231.4  417.83  5300.4  416.37  5305.4  417.24  5351.8  416.65
  5401.9  416.91    5442  419.07  5452.1  419.19  5482.2  419.15  5487.8  418.55
#Mann= 4 ,-1 , 0
  4751.6     .16       0  4980.7     .07       0  5033.5     .16       0
  5088.7     .05       0
Bank Sta=4999.8,5005.8
XS Rating Curve= 0 ,0
Exp/Cntr=0.3,0.1

Type RM Length L Ch R = 1 ,5167    ,570,570,570
BEGIN DESCRIPTION:
CAMP CREEK TRIBUTARY 22.1 8.0
END DESCRIPTION:
XS GIS Cut Line= 3
      3528775.84      10361594.5      3528992.11     10361220.48
      3529039.88     10360916.25
#Sta/Elev= 30
  4664.7   426.6    4703  424.34  4795.1  418.25  4875.9  414.73  4890.1   412.3
  4897.1  412.18  4905.9  411.65  4921.6  412.65    4949  409.46  4964.7  409.44
  4979.9  406.13    4992  400.69    4999  399.46  5001.8  398.96    5005  399.46
  5023.6  404.42  5029.3  407.04  5045.1  407.75  5050.9  406.93  5116.4  411.06
  5192.6  414.04    5217  416.25  5255.2  416.81  5267.7  418.51  5277.8  417.98
  5308.1   419.6  5317.8  420.31  5322.8  421.75    5379  425.47  5404.7  428.36
#Mann= 6 ,-1 , 0
  4664.7     .05       0    4703     .16       0  4897.1     .05       0
  4979.9     .07       0  5029.3     .16       0  5116.4     .05       0
Bank Sta=4999,5005
XS Rating Curve= 0 ,0
Exp/Cntr=0.3,0.1

Type RM Length L Ch R = 1 ,4597    ,393,393,393
BEGIN DESCRIPTION:
CAMP CREEK TRIBUTARY 22.1 7.0
END DESCRIPTION:
XS GIS Cut Line= 3
      3529324.35     10361650.91      3529320.13     10361290.96
      3529270.13     10360990.97
#Sta/Elev= 30
  4806.4  418.46  4851.4  416.98  4885.7  415.53  4905.7  413.97  4965.7  410.66
  4975.7  408.55  4985.7  402.29  4992.7  396.14  4995.4  395.64  4998.7  396.14
  5005.7  396.41  5015.7  399.13  5035.7  401.28  5055.7  402.59  5065.7  402.82
  5075.7  404.25  5095.7     406  5135.7  408.14  5155.7  409.84  5175.8  410.68
  5185.6  411.39  5243.7   415.9  5287.3  418.28  5327.9  421.48  5358.3  423.24
  5378.6  424.95  5388.7  425.44  5419.1  426.05  5439.4  427.18  5470.5  427.86
#Mann= 5 ,-1 , 0
  4806.4      .1       0  4851.4     .16       0  4985.7     .07       0
  5035.7     .16       0  5185.6     .05       0
Bank Sta=4992.7,4998.7
XS Rating Curve= 0 ,0
Exp/Cntr=0.3,0.1

Type RM Length L Ch R = 1 ,4204    ,517,517,517
BEGIN DESCRIPTION:
CAMP CREEK TRIBUTARY 22.1 6.0
END DESCRIPTION:
XS GIS Cut Line= 3
      3529792.12     10361591.67      3529611.28     10361265.79
      3529460.37     10360966.48
#Sta/Elev= 30
  4713.7  417.28  4789.2  415.62  4862.4  414.51  4933.4  411.29  4971.2  408.15
  4976.9  406.15  4987.2  401.06  4996.6  392.54  4999.4  392.04  5002.6  392.54
    5009   395.3  5022.5   398.6  5030.7  399.45  5036.4  401.09  5052.4  401.05
  5058.2  402.63  5074.2  402.13  5096.2   403.9  5163.1  405.91  5185.4  407.38
  5224.4  408.59  5252.3   410.5    5269  410.75  5296.9  412.57  5335.9  413.16
  5341.5  414.03  5356.9  414.66  5380.5  416.04  5386.1  417.26  5421.6  419.15
#Mann= 5 ,-1 , 0
  4713.7      .1       0  4789.2     .16       0  4987.2     .07       0
  5036.4     .16       0  5356.9     .05       0
Bank Sta=4996.6,5002.6
XS Rating Curve= 0 ,0
Exp/Cntr=0.3,0.1

Type RM Length L Ch R = 1 ,3687    ,468,468,468
BEGIN DESCRIPTION:
CAMP CREEK TRIBUTARY 22.1 5.0
END DESCRIPTION:
XS GIS Cut Line= 3
      3530031.61     10361540.15      3529993.86     10361129.87
      3529892.09     10360891.61
#Sta/Elev= 30
  4705.7  415.79  4855.8  411.96    4867  411.68    4895  409.12  4955.3  405.52
  4965.3  404.48  4976.7  401.55  4985.4  393.88  4992.4  391.93  4995.2  391.43
  4998.4  391.93  5005.5  392.16  5015.5  394.37  5045.6  397.62  5055.7  399.42
  5065.7  400.46  5105.9  403.35  5114.3  404.37  5126.7  404.74  5148.4  406.27
  5186.1   409.5  5224.5  413.54  5278.9  420.72    5286  422.11    5315  426.07
  5322.4  427.75  5333.2  428.79  5338.6  428.43  5344.1  430.22  5376.8   433.5
#Mann= 4 ,-1 , 0
  4705.7     .05       0  4855.8     .16       0  4985.4     .07       0
  5015.5     .16       0
Bank Sta=4992.4,4998.4
XS Rating Curve= 0 ,0
Exp/Cntr=0.3,0.1

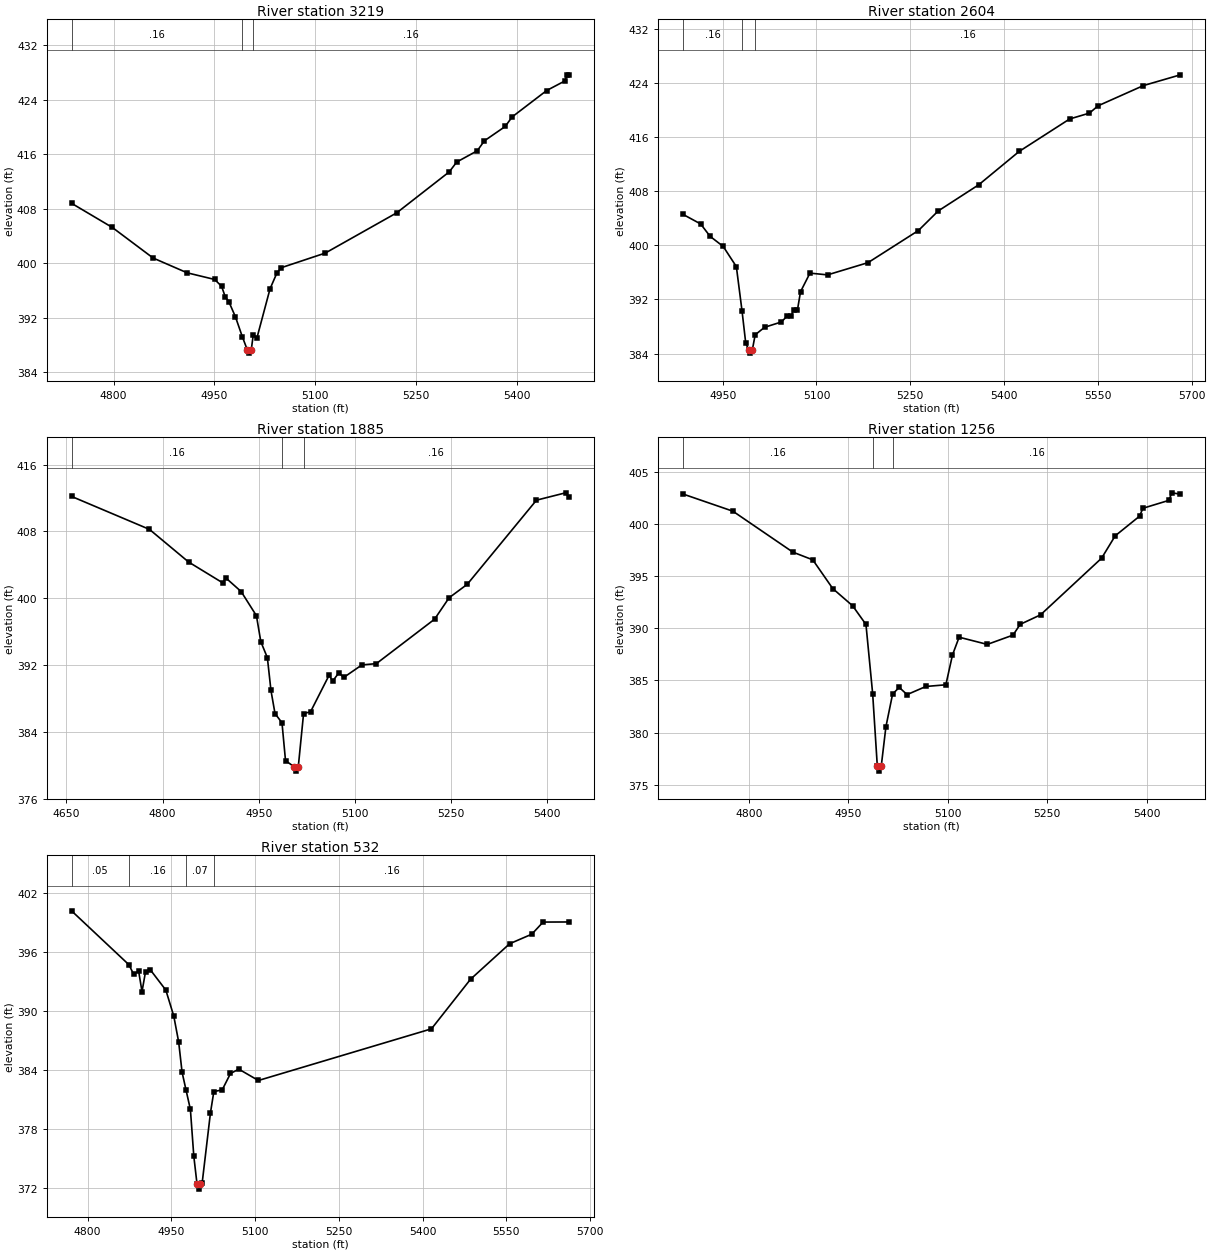
Type RM Length L Ch R = 1 ,3219    ,615,615,615
BEGIN DESCRIPTION:
CAMP CREEK TRIBUTARY 22.1 4.0
END DESCRIPTION:
XS GIS Cut Line= 3
      3530392.11      10361391.6      3530419.22     10361215.45
      3530285.81     10360669.23
#Sta/Elev= 30
  4737.5  408.82  4798.2  405.27  4858.9  400.78  4909.5  398.61  4950.5  397.63
  4960.8  396.63  4966.4  395.05  4971.5  394.39  4981.4  392.15  4991.7  389.22
    4999  387.31  5001.7  386.81    5005  387.31    5008  389.52  5013.2  388.96
  5032.9  396.25  5043.2  398.59  5049.7  399.36  5115.2  401.51  5221.5  407.42
  5299.7  413.44  5310.8  414.88  5341.3  416.53    5352     418  5382.9   420.1
  5393.3  421.51  5444.6  425.38  5471.5  426.78  5475.3  427.69    5478  427.69
#Mann= 3 ,-1 , 0
  4737.5     .16       0  4991.7     .07       0    5008     .16       0
Bank Sta=4999,5005
XS Rating Curve= 0 ,0
Exp/Cntr=0.3,0.1

Type RM Length L Ch R = 1 ,2604    ,719,719,719
BEGIN DESCRIPTION:
CAMP CREEK TRIBUTARY 22.1 3.1
END DESCRIPTION:
XS GIS Cut Line= 3
      3530692.11     10361491.64      3530792.11     10361341.64
      3531097.55     10360807.36
#Sta/Elev= 30
  4886.3  404.59  4914.8  403.16  4929.9  401.33  4950.9  399.83  4971.9  396.85
  4980.9  390.36  4986.9  385.54  4991.5  384.56  4994.2  384.06  4997.5  384.56
    5002  386.77    5017  387.88    5044  388.67  5053.1  389.55  5059.1  389.56
  5063.6  390.38  5069.5  390.38  5074.5  393.13  5089.6  395.89  5117.7  395.63
  5182.5  397.44  5263.1  402.19  5294.7  405.08  5359.5  408.95  5424.3  413.89
  5504.9  418.68  5536.6  419.55  5550.4  420.63  5622.9  423.62    5682  425.21
#Mann= 3 ,-1 , 0
  4886.3     .16       0  4980.9     .07       0    5002     .16       0
Bank Sta=4991.5,4997.5
XS Rating Curve= 0 ,0
Exp/Cntr=0.3,0.1

Type RM Length L Ch R = 1 ,1885    ,629,629,629
BEGIN DESCRIPTION:
CAMP CREEK TRIBUTARY 22.1 3.0
END DESCRIPTION:
XS GIS Cut Line= 3
      3531005.67     10362073.72      3531116.79     10361809.79
      3531327.42     10361367.33
#Sta/Elev= 30
    4658  412.19  4779.6  408.24  4840.7  404.33  4893.6  401.85    4899  402.41
  4922.7  400.79  4946.5   397.9  4953.4  394.78  4963.6  392.87  4969.2  388.94
  4975.5  386.18  4986.4  385.07  4991.9  380.54  5005.8  379.78  5008.5  379.28
  5011.8  379.78  5020.1  386.18  5030.9  386.38    5060  390.78  5065.5  390.06
  5075.2  391.07  5082.7   390.5    5111     392  5133.7  392.16  5224.5  397.48
  5247.2  400.05  5275.5  401.66  5383.5  411.74  5428.9  412.62  5434.4  412.09
#Mann= 3 ,-1 , 0
    4658     .16       0  4986.4     .07       0  5020.1     .16       0
Bank Sta=5005.8,5011.8
XS Rating Curve= 0 ,0
Exp/Cntr=0.3,0.1

Type RM Length L Ch R = 1 ,1256    ,724,724,724
BEGIN DESCRIPTION:
CAMP CREEK TRIBUTARY 22.1 2.0
END DESCRIPTION:
XS GIS Cut Line= 3
      3531519.13     10362176.91      3531554.36     10361756.59
      3531484.14     10361435.58
#Sta/Elev= 30
  4700.2  402.86  4775.7  401.21  4866.1  397.29  4896.2  396.55  4926.3   393.8
  4956.4  392.14  4976.4  390.36  4986.5  383.74  4993.5  376.81  4996.3  376.31
  4999.5  376.81  5006.5  380.56  5016.6   383.7  5026.6  384.33  5038.4  383.64
  5066.8  384.42  5096.9  384.58  5106.9  387.44  5116.9  389.14  5159.4  388.45
  5198.2  389.34    5209  390.37  5239.7  391.28  5331.8  396.71  5352.3  398.85
    5389  400.73  5394.1  401.49  5432.9  402.24    5438  402.97  5450.6  402.84
#Mann= 3 ,-1 , 0
  4700.2     .16       0  4986.5     .07       0  5016.6     .16       0
Bank Sta=4993.5,4999.5
XS Rating Curve= 0 ,0
Exp/Cntr=0.3,0.1

Type RM Length L Ch R = 1 ,532     ,0,0,0
BEGIN DESCRIPTION:
CAMP CREEK TRIBUTARY 22.1 1.0
END DESCRIPTION:
XS GIS Cut Line= 3
      3531816.12     10362431.14      3531994.83     10362169.37
      3531986.17     10361595.19
#Sta/Elev= 30
  4771.3  400.15  4874.1  394.68  4882.6  393.71  4891.5  394.03  4897.5  391.96
  4903.9  393.99  4912.4  394.17  4940.2  392.11  4954.4  389.48  4963.2  386.84
  4969.3  383.78  4976.5  381.94  4984.2     380  4990.3  375.26  4996.1  372.42
  4998.9  371.92  5002.1  372.42  5005.2  372.51  5020.1  379.65  5026.2  381.82
  5041.1  381.98    5056  383.65  5070.9  384.09    5106  382.94    5416  388.18
    5486  393.21    5556  396.81  5595.7  397.78    5616  399.01  5662.5  399.02
#Mann= 4 ,-1 , 0
  4771.3     .05       0  4874.1     .16       0  4976.5     .07       0
  5026.2     .16       0
Bank Sta=4996.1,5002.1
XS Rating Curve= 0 ,0
Exp/Cntr=0.3,0.1

Chan Stop Cuts=-1
Use User Specified Reach Order=0
Composite Channel Slope=5