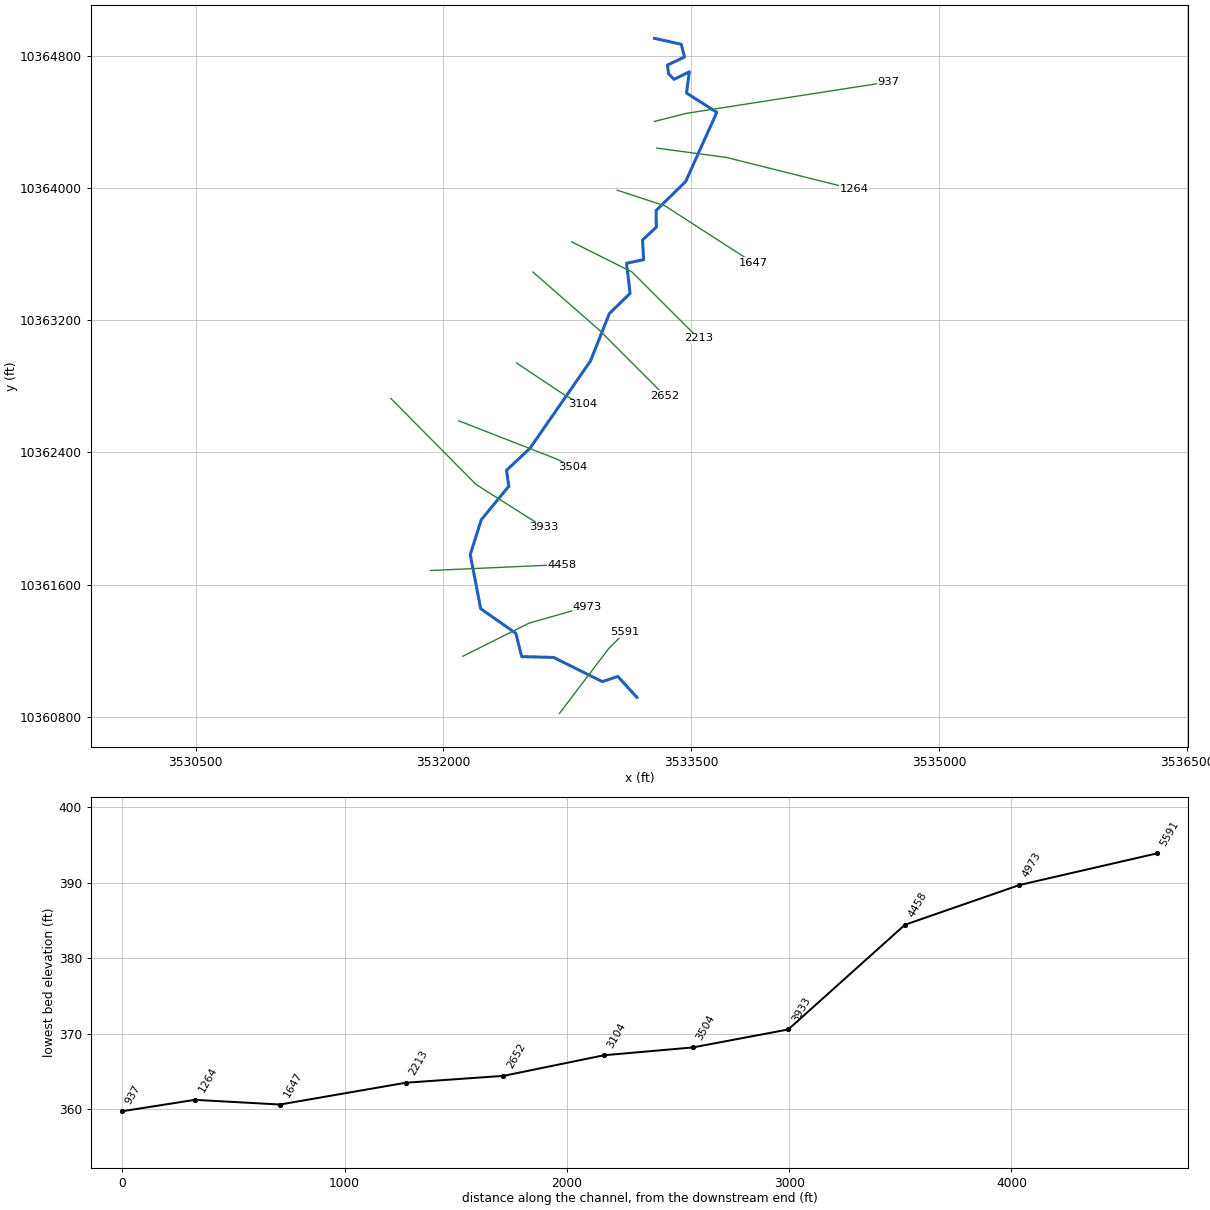
--- CAMP CREEK TRIBUTARY 22.prj (project) ---

Proj Title=CAMP CREEK TRIBUTARY 22 Base Level Engineering
Current Plan=p01
Default Exp/Contr=0.3,0.1
English Units
Geom File=g01
Flow File=f01
Plan File=p01
Y Axis Title=Elevation
X Axis Title(PF)=Main Channel Distance
X Axis Title(XS)=Station
BEGIN DESCRIPTION:
CAMP CREEK TRIBUTARY 22
END DESCRIPTION:
DSS Export Rating Curves= 0
DSS Export Rating Curve Sorted= 0
DSS Export Volume Flow Curves= 0
DXF OffsetX= 0
DXF OffsetY= 0
DXF ScaleX= 1
DXF ScaleY= 10

--- CAMP CREEK TRIBUTARY 22.p01 (plan) ---

Plan Title=Multiple Run
Short Identifier=Multiple
Geom File=g01
Flow File=f01
Subcritical Flow
K Sum by GR= 0
Std Step Tol= 0.01
Critical Tol= 0.01
Num of Std Step Trials= 20
Max Error Tol= 0.3
Flow Tol Ratio= 0.001
Split Flow NTrial= 30
Split Flow Tol= 0.02
Split Flow Ratio= 0.02
Log Output Level= 0
Friction Slope Method= 1
Unsteady Friction Slope Method= 2
Unsteady Bridges Friction Slope Method= 1
Parabolic Critical Depth
Global Vel Dist=  1 , 1 , 1
Global Log Level= 0
CheckData=True
Encroach Param= -1, 0, 0, 0
BEGIN DESCRIPTION:
Multiple Run
END DESCRIPTION:

--- CAMP CREEK TRIBUTARY 22.f01 (steady flow) ---

Flow Title=Multiple
Program Version=4.10
Number of Profiles= 7
Profile Names=10-year,25-year,50-year,1pct_min,100-year,1pct_plu,500-year
River Rch & RM=CAMP CREEK TRIBU,Reach-1         ,5591
     439     582     697     612     828    1119    1161
River Rch & RM=CAMP CREEK TRIBU,Reach-1         ,3933
    1978    2830    3558    3257    4404    5956    6738
River Rch & RM=CAMP CREEK TRIBU,Reach-1         ,3504
    1978    2830    3558    3257    4404    5956    6738
Boundary for River Rch & Prof#=CAMP CREEK TRIBU,Reach-1         , 1
Up Type= 0
Dn Type= 3
Dn Slope=0.005
Boundary for River Rch & Prof#=CAMP CREEK TRIBU,Reach-1         , 2
Up Type= 0
Dn Type= 3
Dn Slope=0.005
Boundary for River Rch & Prof#=CAMP CREEK TRIBU,Reach-1         , 3
Up Type= 0
Dn Type= 3
Dn Slope=0.005
Boundary for River Rch & Prof#=CAMP CREEK TRIBU,Reach-1         , 4
Up Type= 0
Dn Type= 3
Dn Slope=0.005
Boundary for River Rch & Prof#=CAMP CREEK TRIBU,Reach-1         , 5
Up Type= 0
Dn Type= 3
Dn Slope=0.005
Boundary for River Rch & Prof#=CAMP CREEK TRIBU,Reach-1         , 6
Up Type= 0
Dn Type= 3
Dn Slope=0.005
Boundary for River Rch & Prof#=CAMP CREEK TRIBU,Reach-1         , 7
Up Type= 0
Dn Type= 3
Dn Slope=0.005
DSS Import GetInterval= 0
DSS Import GetPeak= 0
DSS Import FillOption= 0

--- CAMP CREEK TRIBUTARY 22.g01 (geometry) ---

Geom Title=Existing Conditions
Program Version=4.10

River Reach=CAMP CREEK TRIBU,Reach-1
Reach XY= 30
      3533170.85     10360917.78      3533055.45     10361044.28
      3532961.97     10361012.71      3532666.88     10361159.21
      3532473.68     10361164.24       3532438.5     10361305.06
      3532225.83     10361453.92      3532162.51     10361781.79
      3532229.22     10361992.61      3532395.92     10362194.99
      3532382.11     10362291.64       3532524.2     10362425.27
      3532889.68     10362952.64      3533004.61     10363240.63
      3533130.02     10363362.54       3533108.4     10363544.66
      3533211.91      10363566.6      3533205.18     10363685.55
      3533288.62     10363763.12       3533287.5     10363864.28
      3533466.17     10364039.39       3533654.8     10364458.36
      3533471.24     10364575.07      3533488.45     10364703.62
      3533395.83     10364657.75      3533363.06      10364691.9
      3533356.04     10364744.08        3533459.     10364793.14
      3533439.76     10364870.07      3533277.37     10364906.06

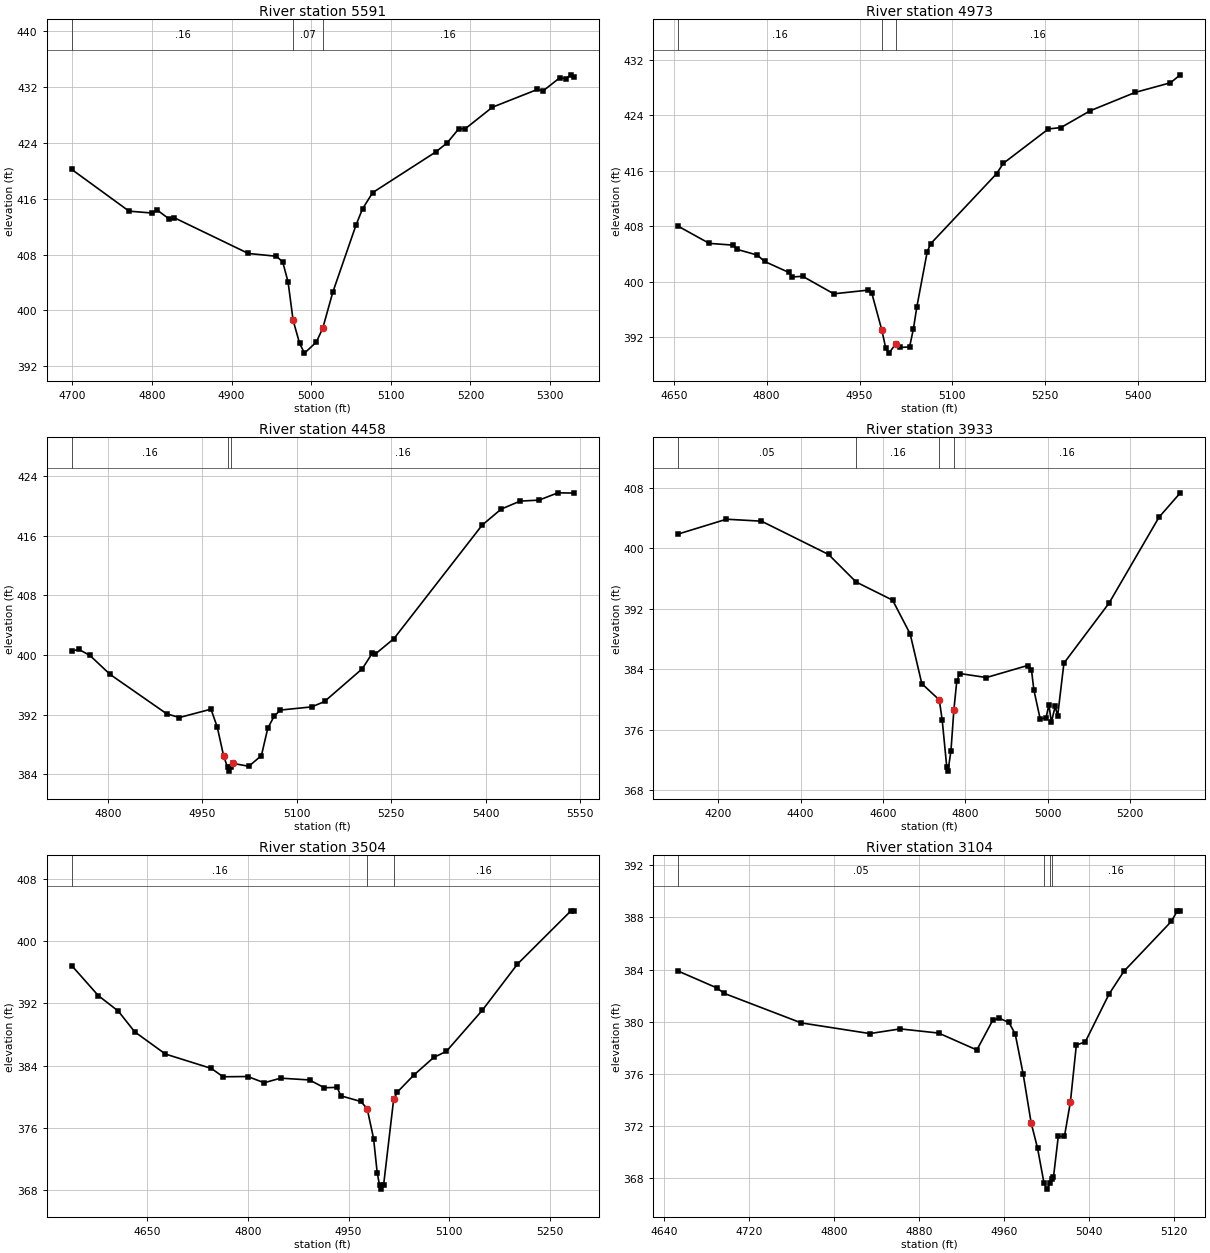
Type RM Length L Ch R = 1 ,5591    ,618,618,618
BEGIN DESCRIPTION:
CAMP CREEK TRIBUTARY 22 16.0
END DESCRIPTION:
XS GIS Cut Line= 3
      3532702.69     10360820.62      3532999.15     10361211.32
      3533098.12     10361310.28
#Sta/Elev= 30
  4699.4  420.19  4771.3  414.22  4800.4  413.95  4806.7  414.37  4821.2  413.14
  4827.5  413.31  4921.1  408.16  4956.4  407.76  4964.3  406.93    4971  404.07
  4977.3  398.59  4985.5  395.27  4991.6  393.89  5006.4  395.46  5014.5  397.45
  5027.2  402.63  5056.3  412.23  5064.5  414.56  5077.3  416.88  5156.1  422.67
  5170.7  423.99  5185.2     426  5193.6  426.03  5227.5   429.1  5284.1  431.65
  5291.2  431.44  5312.4  433.34  5319.4  433.18  5326.5  433.74  5329.8  433.41
#Mann= 3 , 0 , 0
  4699.4     .16       0  4977.3     .07       0  5014.5     .16       0
Bank Sta=4977.3,5014.5
XS Rating Curve= 0 ,0
Exp/Cntr=0.3,0.1

Type RM Length L Ch R = 1 ,4973    ,515,515,515
BEGIN DESCRIPTION:
CAMP CREEK TRIBUTARY 22 15.0
END DESCRIPTION:
XS GIS Cut Line= 3
      3532117.92     10361166.54       3532517.9     10361366.53
      3532867.52     10361466.42
#Sta/Elev= 30
  4657.2  408.01  4707.2  405.54  4746.3  405.28  4751.9  404.68  4784.9  403.85
  4796.6  402.93  4835.7  401.35  4841.3  400.69  4858.1  400.79  4908.4  398.26
  4963.7  398.79  4969.9  398.32  4986.1  392.98  4992.3  390.42  4997.6   389.7
  5008.5  391.05  5014.6  390.52  5030.8  390.59    5037  393.21  5042.6  396.41
  5059.3  404.34  5064.9  405.49  5171.2  415.58  5182.2  417.09    5255  422.05
  5275.2  422.25  5322.6  424.68  5395.4  427.33    5452  428.71    5468  429.86
#Mann= 3 ,-1 , 0
  4657.2     .16       0  4986.1     .07       0  5008.5     .16       0
Bank Sta=4986.1,5008.5
XS Rating Curve= 0 ,0
Exp/Cntr=0.3,0.1

Type RM Length L Ch R = 1 ,4458    ,525,525,525
BEGIN DESCRIPTION:
CAMP CREEK TRIBUTARY 22 14.0
END DESCRIPTION:
XS GIS Cut Line= 3
      3531921.46      10361685.2       3532617.9     10361716.53
      3532717.46     10361716.53
#Sta/Elev= 30
    4743   400.5  4753.7  400.78  4771.8  399.95  4803.7  397.41  4893.8  392.11
  4913.8  391.62  4963.9  392.74  4973.9  390.33  4983.9  386.49  4990.2  384.93
    4993  384.43  4996.2  384.93  4998.2  385.48  5023.9  385.08  5043.9  386.51
    5054  390.17    5064  391.78    5074  392.62    5124  393.05  5144.1  393.77
  5204.1  398.17  5219.6  400.22  5224.6  400.13  5254.2   402.2  5394.3  417.44
  5424.3  419.57  5454.4  420.65  5484.4  420.78  5514.4  421.76  5539.7  421.73
#Mann= 3 ,-1 , 0
    4743     .16       0  4990.2     .07       0  4996.2     .16       0
Bank Sta=4983.9,4998.2
XS Rating Curve= 0 ,0
Exp/Cntr=0.3,0.1

Type RM Length L Ch R = 1 ,3933    ,429,429,429
BEGIN DESCRIPTION:
CAMP CREEK TRIBUTARY 22 13.0
END DESCRIPTION:
XS GIS Cut Line= 3
      3531681.87     10362726.85      3532197.48     10362206.04
      3532607.23      10361946.7
#Sta/Elev= 30
  4103.4  401.91  4220.4  403.87  4305.3  403.61  4467.9  399.21    4535  395.56
  4623.4  393.16  4665.9   388.7  4694.2  382.12  4736.6  379.97  4743.7  377.28
  4754.8  371.05  4757.6  370.55  4764.9  373.24    4772  378.68    4779  382.44
  4786.1  383.46  4850.8  382.93  4950.8  384.52  4960.1  383.97    4966  381.29
  4981.3  377.45  4995.6  377.62  5002.5  379.34  5008.4  377.02  5017.7  379.11
  5023.7  377.86  5038.9  384.83  5148.3  392.77  5269.5  404.13  5321.2  407.36
#Mann= 4 ,-1 , 0
  4103.4     .05       0    4535     .16       0  4736.6     .07       0
    4772     .16       0
Bank Sta=4736.6,4772
XS Rating Curve= 0 ,0
Exp/Cntr=0.3,0.1

Type RM Length L Ch R = 1 ,3504    ,400,400,400
BEGIN DESCRIPTION:
CAMP CREEK TRIBUTARY 22 7.0
END DESCRIPTION:
XS GIS Cut Line= 3
      3532092.07     10362591.66      3532684.81     10362360.39
      3532784.85     10362310.38
#Sta/Elev= 30
  4537.5  396.83    4577  392.99  4606.8     391  4631.3  388.34  4677.1  385.49
  4745.4  383.65    4763  382.58  4799.7  382.61  4824.2  381.81  4848.7   382.4
  4891.8  382.17  4913.8  381.17  4932.9  381.22  4938.3  380.14  4968.1  379.41
  4977.6   378.5  4987.2  374.66  4992.6  370.27  4996.1  368.67  4998.9  368.17
  5002.1  368.67  5017.1  379.67  5022.5  380.61    5047  382.78  5076.8  385.06
  5095.7  385.84  5149.4  391.13  5201.6  397.03  5281.3  403.86  5285.6  403.86
#Mann= 3 , 0 , 0
  4537.5     .16       0  4977.6     .07       0  5017.1     .16       0
Bank Sta=4977.6,5017.1
XS Rating Curve= 0 ,0
Exp/Cntr=0.3,0.1

Type RM Length L Ch R = 1 ,3104    ,452,452,452
BEGIN DESCRIPTION:
CAMP CREEK TRIBUTARY 22 6.0
END DESCRIPTION:
XS GIS Cut Line= 3
      3532442.13     10362941.63      3532742.11     10362741.64
      3532842.07     10362691.66
#Sta/Elev= 30
  4653.4  383.88  4689.4   382.6  4696.9  382.16  4769.1   379.9  4833.7  379.08
  4862.2  379.44  4898.3  379.12  4934.3  377.82  4949.3  380.11  4955.3  380.26
  4964.4  379.94  4970.4  379.05  4977.9  375.96  4985.4  372.21  4991.4  370.28
  4997.4  367.63  5000.2  367.13  5003.4  367.63  5005.2  367.89  5006.4  368.06
  5010.9  371.18  5016.7  371.18  5022.3  373.82  5027.9   378.2  5036.3  378.44
  5058.7  382.12  5072.6  383.86  5117.3   387.7  5122.9  388.51  5125.7  388.51
#Mann= 4 ,-1 , 0
  4653.4     .05       0  4997.4     .03       0  5003.4     .05       0
  5005.2     .16       0
Bank Sta=4985.4,5022.3
XS Rating Curve= 0 ,0
Exp/Cntr=0.3,0.1

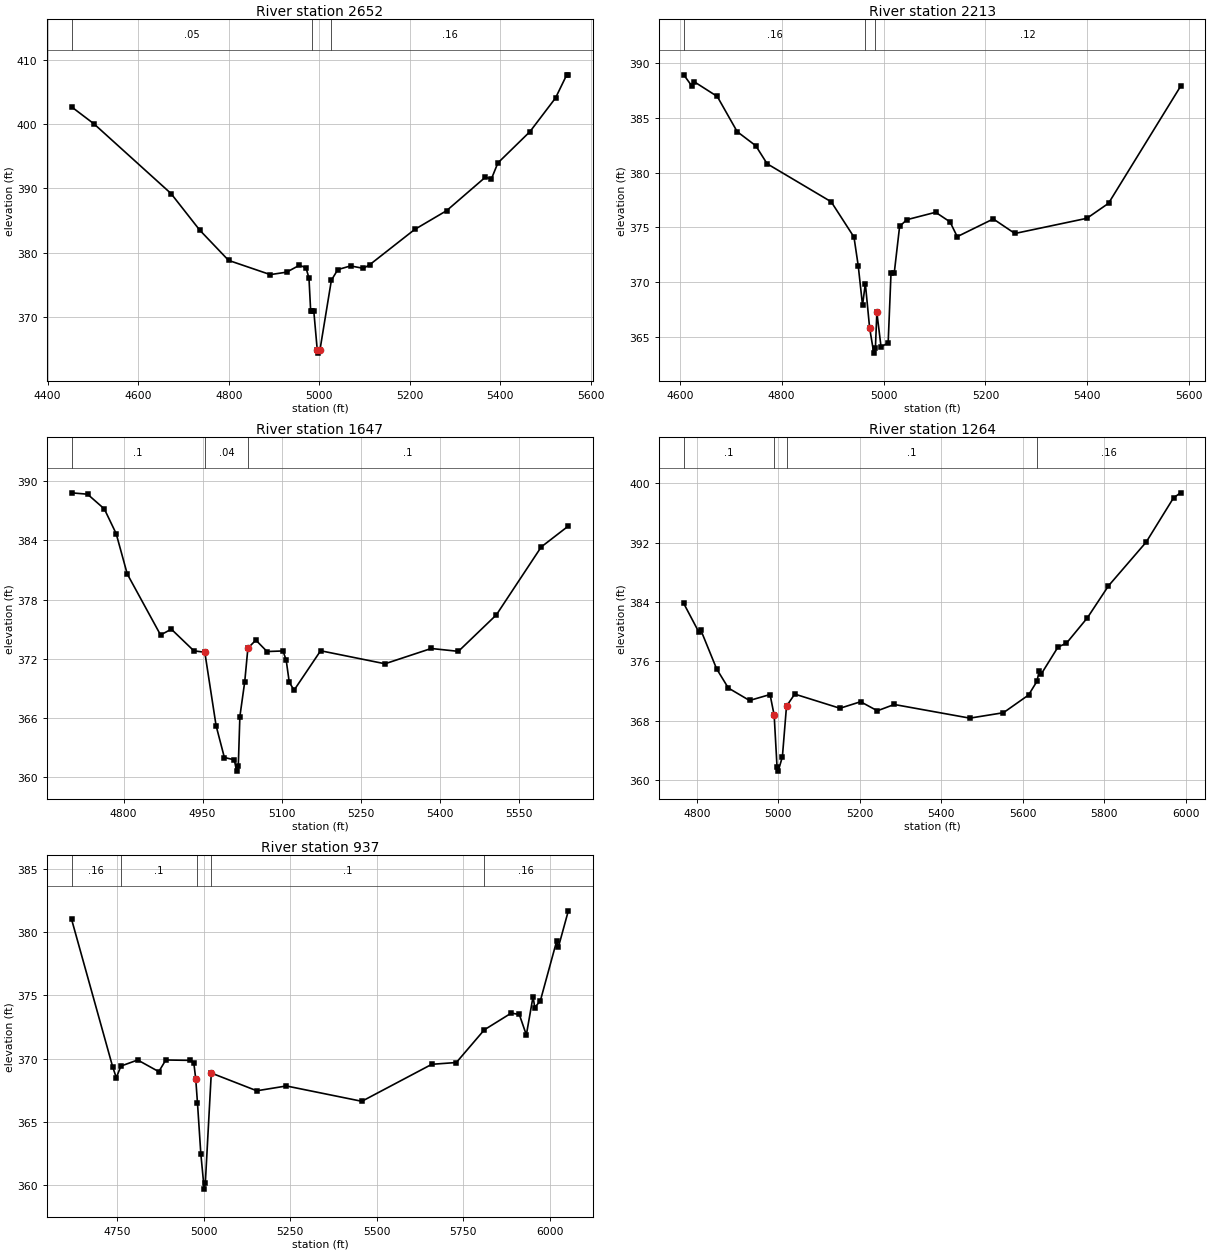
Type RM Length L Ch R = 1 ,2652    ,439,439,439
BEGIN DESCRIPTION:
CAMP CREEK TRIBUTARY 22 5.0
END DESCRIPTION:
XS GIS Cut Line= 3
      3532542.09     10363491.65      3532942.11     10363141.64
       3533342.1     10362741.65
#Sta/Elev= 30
  4452.8  402.67  4502.6  400.01  4672.5   389.2  4736.1   383.5  4799.7  378.81
  4891.8   376.6  4927.9  376.98  4956.3  378.06  4970.6  377.65  4977.2  376.08
    4981  370.92  4984.3  370.92  4987.9  370.92  4995.5   364.9  4998.2   364.4
  5001.5   364.9  5026.7  375.72  5040.9  377.38  5069.2  377.95  5097.5  377.57
  5111.6  378.15  5210.6  383.61  5281.3  386.54  5366.2   391.7  5380.3   391.5
  5394.4  393.95  5465.2  398.81  5521.7  404.04  5546.5  407.64    5550  407.64
#Mann= 3 ,-1 , 0
  4452.8     .05       0  4984.3     .07       0  5026.7     .16       0
Bank Sta=4995.5,5001.5
XS Rating Curve= 0 ,0
Exp/Cntr=0.3,0.1

Type RM Length L Ch R = 1 ,2213    ,566,566,566
BEGIN DESCRIPTION:
CAMP CREEK TRIBUTARY 22 4.0
END DESCRIPTION:
XS GIS Cut Line= 3
      3532775.65     10363674.76      3533142.11     10363491.64
      3533542.14     10363091.61
#Sta/Elev= 30
  4607.8  388.96  4623.3  387.96  4628.9  388.31  4673.6  386.98  4712.7  383.76
  4749.2  382.47  4771.5  380.82  4897.3  377.34    4942  374.11  4950.4  371.47
  4958.8  367.87  4964.3  369.86  4972.7   365.8  4980.9  363.49  4984.1  363.99
 4986.93  367.21  4995.1  364.08  5009.1  364.41  5014.7   370.8    5021   370.8
  5031.6  375.09  5045.7   375.7  5102.3  376.38  5130.6   375.5  5144.7  374.15
  5215.5  375.77  5257.9  374.44  5399.3  375.83  5441.7   377.2  5583.2  387.91
#Mann= 3 ,-1 , 0
  4607.8     .16       0  4964.3     .05       0  4984.1     .12       0
Bank Sta=4972.7,4986.93
XS Rating Curve= 0 ,0
Exp/Cntr=0.3,0.1

Type RM Length L Ch R = 1 ,1647    ,383,383,383
BEGIN DESCRIPTION:
CAMP CREEK TRIBUTARY 22 3.0
END DESCRIPTION:
XS GIS Cut Line= 3
      3533051.69     10363987.27      3533342.11     10363891.64
      3533876.82     10363546.48
#Sta/Elev= 30
  4701.4  388.83  4731.8  388.69  4763.6   387.2  4786.1  384.69  4807.1   380.6
  4870.3  374.41  4890.7     375  4933.5   372.8  4954.2  372.66  4975.6  365.21
  4991.3  361.98  5010.1  361.75  5014.5   360.6  5017.7   361.1  5020.7  366.14
  5029.9  369.66  5035.9  373.07    5051  373.89  5072.2  372.73  5102.4  372.79
  5108.5  371.87  5114.4   369.6  5123.6  368.82  5173.8  372.81  5295.9  371.49
  5383.6  373.04  5435.1  372.75  5507.1  376.45  5592.2  383.34  5643.6  385.46
#Mann= 3 , 0 , 0
  4701.4      .1       0  4954.2     .04       0  5035.9      .1       0
Bank Sta=4954.2,5035.9
XS Rating Curve= 0 ,0
Exp/Cntr=0.3,0.1

Type RM Length L Ch R = 1 ,1264    ,327,327,327
BEGIN DESCRIPTION:
CAMP CREEK TRIBUTARY 22 2.0
END DESCRIPTION:
XS GIS Cut Line= 3
      3533292.13     10364241.64       3533713.1      10364185.2
      3534483.94     10363992.49
#Sta/Elev= 30
  4767.9  383.81  4804.3  380.02  4809.4  380.28  4848.6     375  4877.3  372.42
  4929.3  370.74  4979.7  371.54  4989.8  368.75  4996.9  361.72  4999.7  361.22
    5010  363.16  5020.1  369.98  5040.3   371.6  5151.3  369.69  5201.9  370.57
  5243.1  369.35  5284.4   370.2  5469.9  368.36  5552.4  369.09  5614.2  371.48
  5634.8  373.33  5640.1  374.71  5645.3  374.31  5686.5  377.95    5707  378.45
  5758.5  381.88  5810.2  386.18  5902.8  392.08    5970  398.05  5987.2  398.72
#Mann= 4 ,-1 , 0
  4767.9      .1       0  4989.8    .035       0  5020.1      .1       0
  5634.8     .16       0
Bank Sta=4989.8,5020.1
XS Rating Curve= 0 ,0
Exp/Cntr=0.3,0.1

Type RM Length L Ch R = 1 ,937     ,0,0,0
BEGIN DESCRIPTION:
CAMP CREEK TRIBUTARY 22 1.0
END DESCRIPTION:
XS GIS Cut Line= 3
      3533276.48      10364403.1      3533476.48      10364453.1
      3534692.09     10364641.64
#Sta/Elev= 30
  4617.8  381.02    4737  369.34  4747.3  368.51  4760.7  369.42  4809.1   369.9
  4870.1  368.98  4890.4   369.9  4961.2  369.87  4971.3   369.7    4977  368.38
    4982   366.5  4991.6  362.52  5001.4  359.71  5004.7  360.21  5021.9  368.87
  5153.5  367.47    5239  367.85  5457.1  366.64  5659.4  369.56  5730.3   369.7
  5811.2  372.28  5889.1   373.6  5912.4  373.49  5932.7  371.88  5952.1   374.9
  5957.1  374.04  5973.2  374.57  6020.1  379.26  6025.2  378.79  6054.1  381.67
#Mann= 5 ,-1 , 0
  4617.8     .16       0  4760.7      .1       0    4982    .035       0
  5021.9      .1       0  5811.2     .16       0
Bank Sta=4977,5021.9
XS Rating Curve= 0 ,0
Exp/Cntr=0.3,0.1

Chan Stop Cuts=-1
Use User Specified Reach Order=0
Composite Channel Slope=5