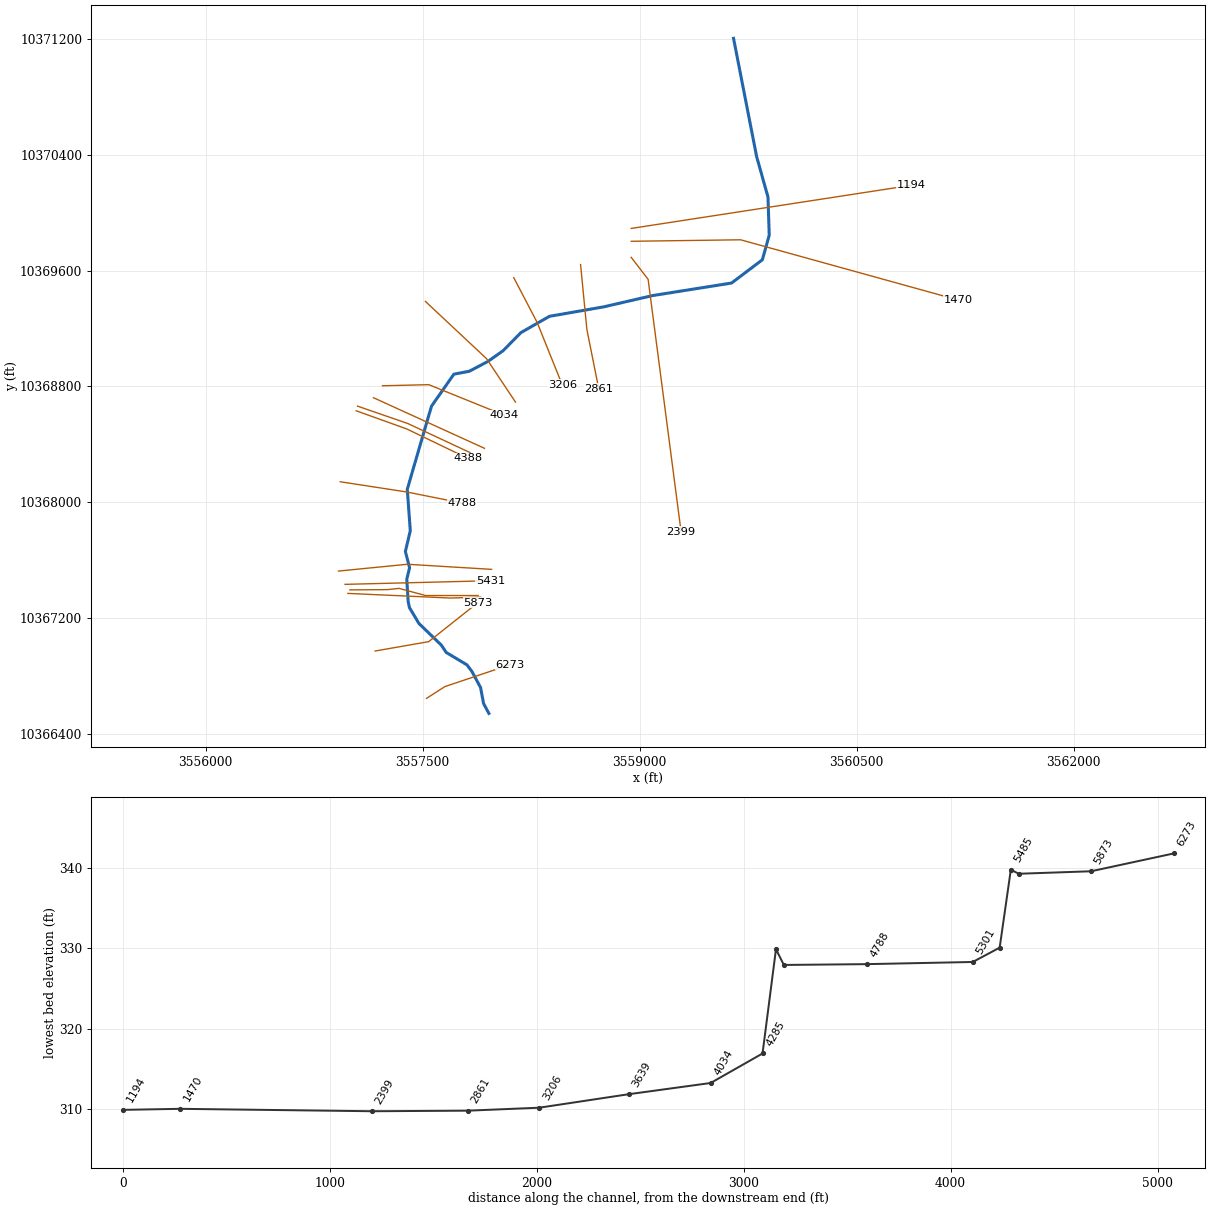
--- CAMP CREEK TRIBUTARY 9.prj (project) ---

Proj Title=CAMP CREEK TRIBUTARY 9 Base Level Engineering
Current Plan=p01
Default Exp/Contr=0.3,0.1
English Units
Geom File=g01
Flow File=f01
Plan File=p01
BEGIN DESCRIPTION:
CAMP CREEK TRIBUTARY 9
END DESCRIPTION:

--- CAMP CREEK TRIBUTARY 9.p01 (plan) ---

Plan Title=Multiple Run
Short Identifier=Multiple
Geom File=g01
Flow File=f01
Subcritical Flow
K Sum by GR= 0
Std Step Tol= 0.01
Critical Tol= 0.01
Num of Std Step Trials= 20
Max Error Tol= 0.3
Flow Tol Ratio= 0.001
Split Flow NTrial= 30
Split Flow Tol= 0.02
Split Flow Ratio= 0.02
Log Output Level= 0
Friction Slope Method= 1
Unsteady Friction Slope Method= 2
Unsteady Bridges Friction Slope Method= 1
Parabolic Critical Depth
Global Vel Dist=  1 , 1 , 1
Global Log Level= 0
CheckData=True
Encroach Param= -1, 0, 0, 0
BEGIN DESCRIPTION:
Multiple Run
END DESCRIPTION:

--- CAMP CREEK TRIBUTARY 9.f01 (steady flow) ---

Flow Title=Multiple
Number of Profiles=7
Profile Names=10-year,25-year,50-year,1pct_min,100-year,1pct_plu,500-year
River Rch & RM= CAMP CREEK TRIBU,Reach-1,6273
     655     879    1060     935    1264    1709    1789
Boundary for River Rch & Prof#=CAMP CREEK TRIBU,Reach-1,1
Up Type=0
Dn Type=3
Dn Slope=0.005
Boundary for River Rch & Prof#=CAMP CREEK TRIBU,Reach-1,2
Up Type=0
Dn Type=3
Dn Slope=0.005
Boundary for River Rch & Prof#=CAMP CREEK TRIBU,Reach-1,3
Up Type=0
Dn Type=3
Dn Slope=0.005
Boundary for River Rch & Prof#=CAMP CREEK TRIBU,Reach-1,4
Up Type=0
Dn Type=3
Dn Slope=0.005
Boundary for River Rch & Prof#=CAMP CREEK TRIBU,Reach-1,5
Up Type=0
Dn Type=3
Dn Slope=0.005
Boundary for River Rch & Prof#=CAMP CREEK TRIBU,Reach-1,6
Up Type=0
Dn Type=3
Dn Slope=0.005
Boundary for River Rch & Prof#=CAMP CREEK TRIBU,Reach-1,7
Up Type=0
Dn Type=3
Dn Slope=0.005

--- CAMP CREEK TRIBUTARY 9.g01 (geometry) ---

Geom Title=Existing Conditions

River Reach=CAMP CREEK TRIBU,Reach-1
Reach XY= 30
      3557958.21     10366539.86      3557921.75     10366607.57
      3557900.92     10366718.68      3557841.89     10366828.05
      3557807.17     10366874.93      3557663.37     10366961.04
      3557629.51     10367011.82      3557474.57     10367161.56
      3557409.46     10367270.93      3557400.35     10367313.90
      3557390.92     10367467.31      3557410.36     10367546.47
      3557381.20     10367658.97      3557415.23     10367802.72
      3557394.26     10368088.79      3557561.60     10368662.87
      3557716.46     10368884.40      3557823.62     10368904.58
      3557952.74     10368972.94      3558056.91     10369046.72
      3558179.52     10369171.51      3558377.01     10369284.17
      3558750.27     10369349.28      3559088.81     10369427.40
      3559635.69     10369514.21      3559848.36     10369674.80
      3559896.10     10369844.07      3559887.42     10370108.83
      3559809.30     10370386.60      3559649.36     10371205.54

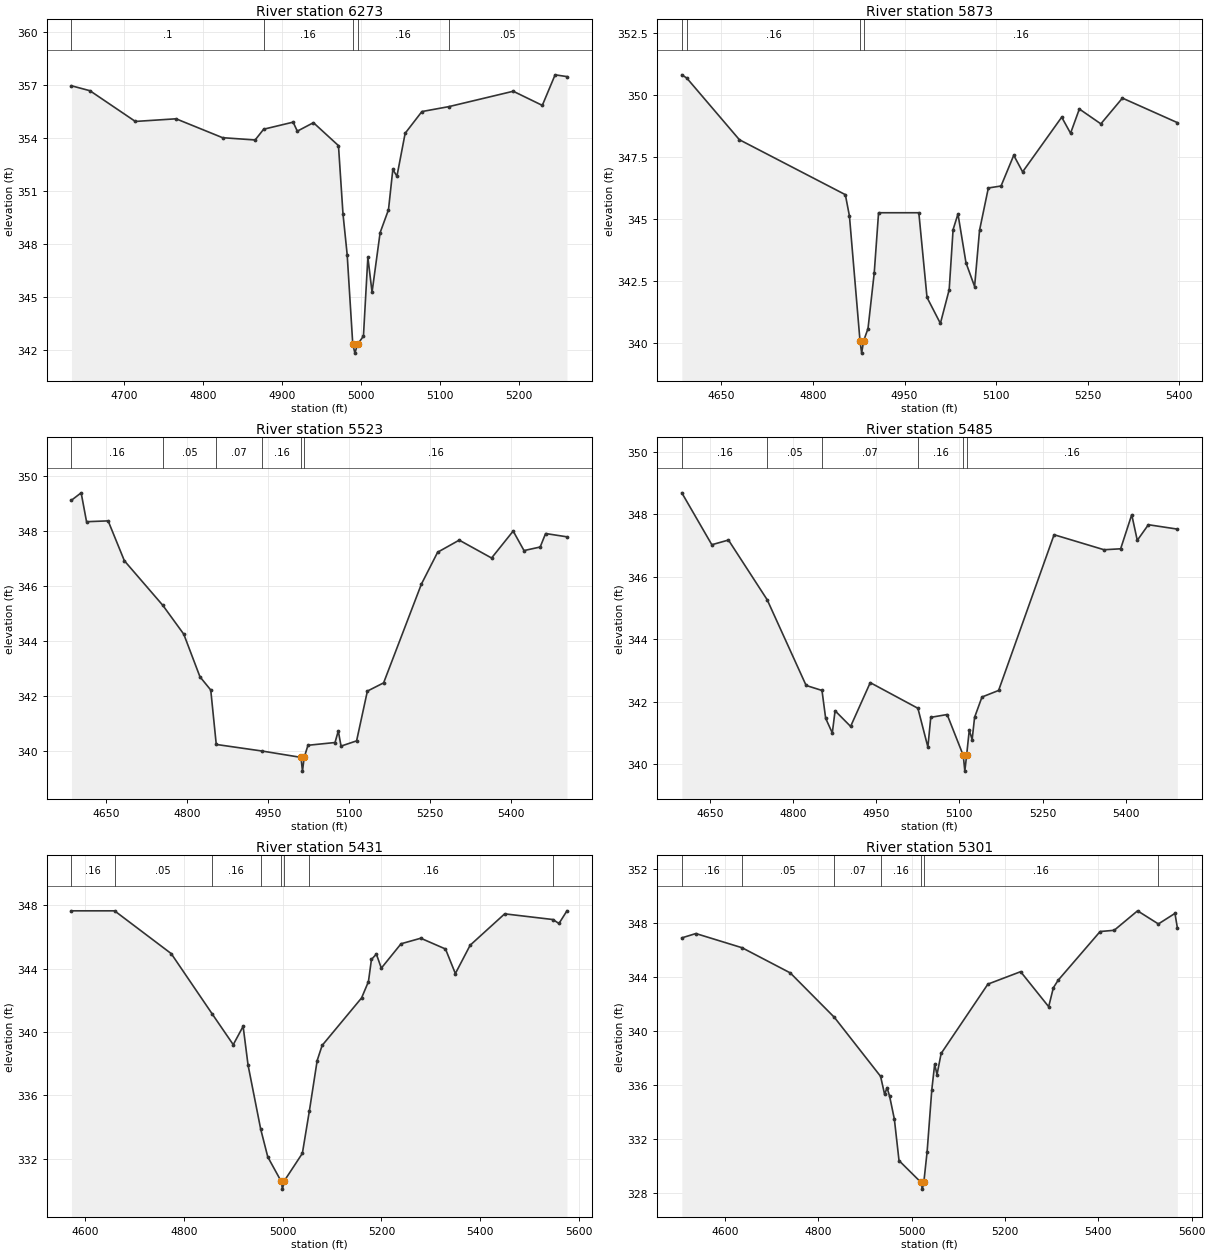
Type RM Length L Ch R = 1,6273,400,400,400
BEGIN DESCRIPTION:
CAMP CREEK TRIBUTARY 9 14.0
END DESCRIPTION:
XS GIS Cut Line= 3
      3557527.73     10366643.74      3557654.01     10366724.89
      3558106.30     10366876.72
#Sta/Elev= 30
  4633.6  356.94  4657.0  356.66  4714.5  354.92  4766.0  355.07  4824.9  354.00
  4866.1  353.87  4876.9  354.48  4914.2  354.88  4919.5  354.37  4939.9  354.85
  4971.6  353.55  4977.3  349.69  4982.6  347.38  4989.7  342.30  4992.4  341.80
  4995.7  342.30  5003.2  342.76  5008.8  347.23  5014.1  345.25  5024.3  348.62
  5034.9  349.92  5040.4  352.20  5045.6  351.82  5056.0  354.25  5077.2  355.48
  5111.4  355.76  5192.8  356.63  5229.6  355.83  5245.8  357.56  5260.8  357.46
#Mann=5,-1,0
  4633.6     0.1       0  4876.9    0.16       0  4989.7    0.07       0
  4995.7    0.16       0  5111.4    0.05       0
Bank Sta=4989.7,4995.7
Exp/Cntr=0.3,0.1

Type RM Length L Ch R = 1,5873,350,350,350
BEGIN DESCRIPTION:
CAMP CREEK TRIBUTARY 9 13.0
END DESCRIPTION:
XS GIS Cut Line= 3
      3557171.83     10366970.88      3557542.24     10367035.56
      3557883.20     10367305.97
#Sta/Elev= 30
  4585.4  350.82  4593.5  350.69  4679.6  348.20  4853.1  345.98  4859.8  345.12
  4877.1  340.08  4879.8  339.58  4883.1  340.08  4890.2  340.57  4900.4  342.82
  4907.5  345.25  4973.4  345.25  4986.8  341.83  5008.7  340.78  5023.1  342.14
  5029.5  344.57  5037.5  345.20  5050.6  343.23  5064.7  342.27  5072.8  344.54
  5087.2  346.25  5108.0  346.33  5128.8  347.57  5143.3  346.90  5207.3  349.11
  5221.8  348.46  5236.2  349.44  5271.4  348.84  5306.7  349.88  5396.6  348.89
#Mann=4,-1,0
  4585.4     0.1       0  4593.5    0.16       0  4877.1    0.07       0
  4883.1    0.16       0
Bank Sta=4877.1,4883.1
Exp/Cntr=0.3,0.1

Type RM Length L Ch R = 1,5523,38,38,38
BEGIN DESCRIPTION:
Mapping XS 77dcbb3e
END DESCRIPTION:
XS GIS Cut Line= 3
      3556984.13     10367369.10      3557692.51     10367336.98
      3557901.72     10367343.06
#Sta/Elev= 30
  4585.6  349.12  4603.6  349.39  4613.6  348.34  4653.6  348.37  4683.7  346.92
  4754.9  345.30  4793.8  344.25  4823.8  342.70  4843.8  342.22  4854.0  340.24
  4939.2  340.00  5011.0  339.77  5013.8  339.27  5017.0  339.77  5024.0  340.21
  5074.1  340.31  5080.2  340.73  5085.3  340.18  5114.1  340.37  5134.1  342.18
  5164.2  342.48  5234.2  346.07  5264.3  347.23  5304.3  347.67  5364.3  347.02
  5404.3  348.00  5424.4  347.29  5454.4  347.42  5464.4  347.91  5504.0  347.79
#Mann=6,-1,0
  4585.6    0.16       0  4754.9    0.05       0  4854.0    0.07       0
  4939.2    0.16       0  5011.0    0.07       0  5017.0    0.16       0
Bank Sta=5011,5017
Exp/Cntr=0.3,0.1

Type RM Length L Ch R = 1,5485,54,54,54
BEGIN DESCRIPTION:
Mapping XS fdcbe32e
END DESCRIPTION:
XS GIS Cut Line= 5
      3556998.06     10367393.40      3557257.61     10367395.14
      3557337.47     10367403.82      3557520.63     10367354.34
      3557884.31     10367354.34
#Sta/Elev= 30
  4599.7  348.68  4653.8  347.02  4683.8  347.17  4753.6  345.26  4823.8  342.52
  4852.4  342.36  4859.0  341.47  4871.0  341.00  4876.0  341.71  4904.0  341.21
  4939.4  342.61  5025.3  341.79  5043.3  340.55  5048.5  341.50  5078.0  341.59
  5107.1  340.28  5109.9  339.78  5113.1  340.28  5117.9  341.09  5123.1  340.79
  5127.5  341.50  5140.8  342.15  5170.8  342.36  5270.8  347.34  5360.8  346.86
  5390.8  346.89  5410.8  347.98  5420.8  347.16  5440.8  347.66  5493.0  347.52
#Mann=6,-1,0
  4599.7    0.16       0  4753.6    0.05       0  4852.4    0.07       0
  5025.3    0.16       0  5107.1    0.07       0  5113.1    0.16       0
Bank Sta=5107.1,5113.1
Exp/Cntr=0.3,0.1

Type RM Length L Ch R = 1,5431,130,130,130
BEGIN DESCRIPTION:
Mapping XS c64ed947
END DESCRIPTION:
XS GIS Cut Line= 2
      3556964.19     10367431.60      3557968.27     10367456.74
#Sta/Elev= 30
  4571.6  347.65  4659.0  347.65  4773.8  344.95  4856.5  341.16  4899.6  339.20
  4919.6  340.36  4929.6  337.91  4955.2  333.87  4969.6  332.11  4996.6  330.58
  4999.4  330.08  5002.6  330.58  5039.7  332.34  5054.0  335.04  5069.7  338.20
  5079.7  339.15  5159.7  342.15  5173.6  343.18  5179.7  344.58  5189.7  344.92
  5199.7  344.03  5239.7  345.57  5279.7  345.92  5329.8  345.24  5349.8  343.69
  5379.8  345.48  5449.8  347.46  5547.6  347.10  5559.8  346.85  5576.0  347.65
#Mann=8,-1,0
  4571.6    0.16       0  4659.0    0.05       0  4856.5    0.16       0
  4955.2    0.07       0  4996.6    0.07       0  5002.6    0.07       0
  5054.0    0.16       0  5547.6    0.05       0
Bank Sta=4996.6,5002.6
Exp/Cntr=0.3,0.1

Type RM Length L Ch R = 1,5301,513,513,513
BEGIN DESCRIPTION:
CAMP CREEK TRIBUTARY 9 12.0
END DESCRIPTION:
XS GIS Cut Line= 3
      3556919.06     10367523.50      3557395.27     10367570.53
      3557977.17     10367535.27
#Sta/Elev= 30
  4507.9  346.88  4538.0  347.20  4637.0  346.15  4740.2  344.29  4834.8  341.00
  4933.7  336.64  4942.4  335.30  4947.5  335.81  4953.1  335.16  4963.2  333.48
  4973.2  330.41  5020.3  328.80  5023.1  328.30  5026.3  328.80  5033.4  331.07
  5043.4  335.64  5049.6  337.54  5054.6  336.77  5063.4  338.33  5163.6  343.46
  5233.7  344.38  5293.8  341.79  5303.8  343.19  5313.9  343.74  5404.0  347.35
  5434.1  347.44  5484.2  348.88  5528.8  347.91  5564.3  348.69  5569.4  347.64
#Mann=7,-1,0
  4507.9    0.16       0  4637.0    0.05       0  4834.8    0.07       0
  4933.7    0.16       0  5020.3    0.07       0  5026.3    0.16       0
  5528.8    0.05       0
Bank Sta=5020.3,5026.3
Exp/Cntr=0.3,0.1

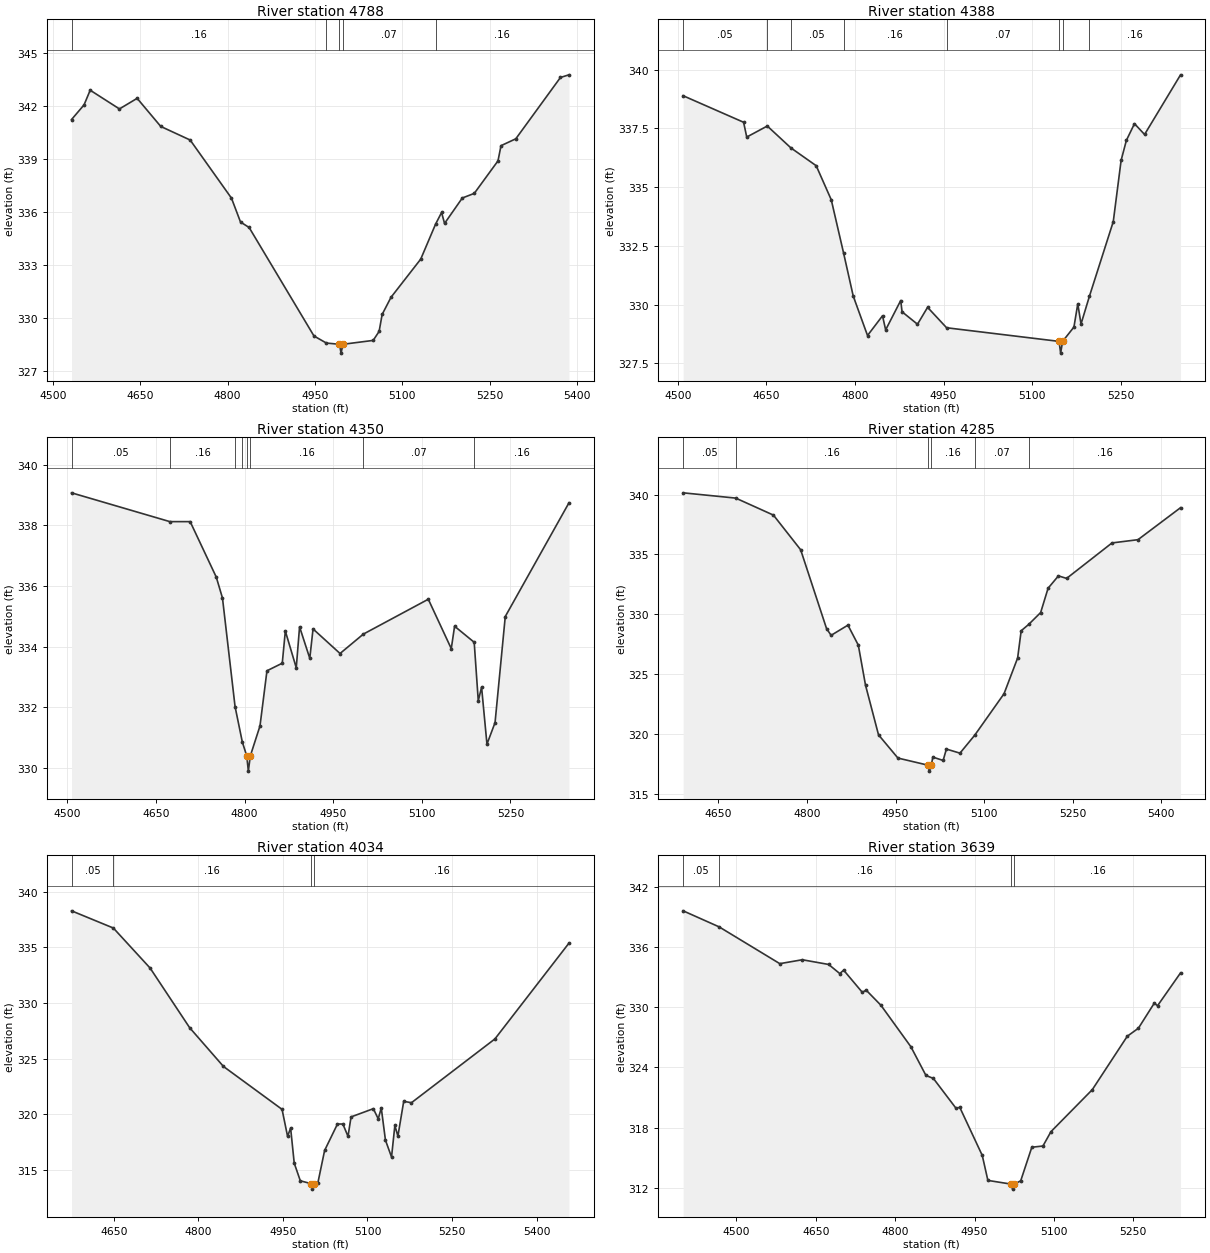
Type RM Length L Ch R = 1,4788,400,400,400
BEGIN DESCRIPTION:
CAMP CREEK TRIBUTARY 9 11.0
END DESCRIPTION:
XS GIS Cut Line= 3
      3556930.82     10368140.78      3557389.39     10368070.24
      3557771.56     10367993.80
#Sta/Elev= 30
  4532.3  341.25  4553.8  342.08  4564.3  342.91  4614.5  341.85  4644.9  342.45
  4685.4  340.86  4735.9  340.09  4806.8  336.80  4822.3  335.45  4837.1  335.14
  4948.4  329.00  4969.7  328.60  4992.1  328.53  4994.9  328.03  4998.1  328.53
  5050.0  328.75  5060.2  329.26  5065.4  330.22  5080.6  331.19  5131.6  333.35
  5157.1  335.33  5167.4  335.99  5172.5  335.37  5203.0  336.81  5223.5  337.07
  5264.2  338.91  5269.4  339.77  5294.8  340.16  5371.4  343.63  5386.0  343.78
#Mann=5,-1,0
  4532.3    0.16       0  4969.7    0.07       0  4992.1    0.07       0
  4998.1    0.07       0  5157.1    0.16       0
Bank Sta=4992.1,4998.1
Exp/Cntr=0.3,0.1

Type RM Length L Ch R = 1,4388,38,38,38
BEGIN DESCRIPTION:
Mapping XS 523904ea
END DESCRIPTION:
XS GIS Cut Line= 3
      3557041.03     10368631.36      3557391.52     10368505.49
      3557814.71     10368301.49
#Sta/Elev= 30
  4509.0  338.89  4611.4  337.76  4616.7  337.13  4651.5  337.60  4691.4  336.67
  4734.3  335.91  4759.8  334.46  4780.6  332.20  4797.0  330.36  4821.2  328.68
  4846.6  329.52  4851.9  328.92  4877.4  330.17  4879.7  329.69  4905.8  329.16
  4922.9  329.88  4955.1  329.01  5145.5  328.43  5148.2  327.93  5151.5  328.43
  5170.7  329.04  5177.2  330.03  5182.7  329.17  5196.9  330.35  5237.3  333.53
  5250.6  336.14  5259.5  336.99  5273.2  337.70  5290.3  337.24  5351.2  339.78
#Mann=8,-1,0
  4509.0    0.05       0  4651.5    0.16       0  4691.4    0.05       0
  4780.6    0.16       0  4955.1    0.07       0  5145.5    0.07       0
  5151.5    0.07       0  5196.9    0.16       0
Bank Sta=5145.5,5151.5
Exp/Cntr=0.3,0.1

Type RM Length L Ch R = 1,4350,65,65,65
BEGIN DESCRIPTION:
CAMP CREEK TRIBUTARY 9 10.0
END DESCRIPTION:
XS GIS Cut Line= 3
      3557050.57     10368663.34      3557398.03     10368543.25
      3557827.82     10368342.47
#Sta/Elev= 30
  4507.1  339.07  4673.5  338.12  4707.9  338.12  4752.1  336.29  4762.6  335.60
  4783.9  332.02  4796.2  330.85  4803.7  330.39  4806.4  329.89  4809.7  330.39
  4826.1  331.38  4837.9  333.20  4863.8  333.45  4869.0  334.51  4887.5  333.30
  4893.1  334.65  4910.4  333.61  4915.9  334.58  4961.6  333.77  5001.1  334.41
  5111.0  335.56  5149.9  333.93  5155.5  334.67  5188.7  334.14  5195.6  332.21
  5201.2  332.66  5210.3  330.78  5224.0  331.49  5241.3  334.99  5349.1  338.74
#Mann=8,-1,0
  4507.1    0.05       0  4673.5    0.16       0  4783.9    0.05       0
  4796.2    0.16       0  4803.7    0.07       0  4809.7    0.16       0
  5001.1    0.07       0  5188.7    0.16       0
Bank Sta=4803.7,4809.7
Exp/Cntr=0.3,0.1

Type RM Length L Ch R = 1,4285,251,251,251
BEGIN DESCRIPTION:
Mapping XS 0d276149
END DESCRIPTION:
XS GIS Cut Line= 2
      3557160.96     10368721.50      3557927.74     10368371.94
#Sta/Elev= 30
  4590.2  340.14  4679.3  339.70  4743.2  338.28  4789.3  335.39  4833.2  328.81
  4840.9  328.25  4869.4  329.10  4887.0  327.43  4899.2  324.09  4921.2  319.95
  4954.1  318.01  5004.7  317.42  5007.4  316.92  5010.7  317.42  5013.2  318.09
  5030.7  317.81  5036.2  318.76  5059.2  318.42  5084.1  319.91  5133.9  323.38
  5156.9  326.36  5162.9  328.63  5175.6  329.16  5195.9  330.15  5208.5  332.18
  5226.0  333.21  5239.9  333.00  5316.8  335.96  5360.8  336.23  5432.9  338.90
#Mann=6,-1,0
  4590.2    0.05       0  4679.3    0.16       0  5004.7    0.07       0
  5010.7    0.16       0  5084.1    0.07       0  5175.6    0.16       0
Bank Sta=5004.7,5010.7
Exp/Cntr=0.3,0.1

Type RM Length L Ch R = 1,4034,395,395,395
BEGIN DESCRIPTION:
CAMP CREEK TRIBUTARY 9 9.0
END DESCRIPTION:
XS GIS Cut Line= 3
      3557222.66     10368804.04      3557542.93     10368811.86
      3558063.77     10368600.92
#Sta/Elev= 30
  4575.1  338.30  4649.3  336.75  4714.6  333.14  4784.6  327.78  4844.6  324.29
  4948.5  320.43  4958.3  318.00  4963.7  318.75  4970.1  315.59  4980.9  314.00
  4999.5  313.75  5002.2  313.25  5005.5  313.75  5011.9  313.78  5024.0  316.73
  5046.8  319.11  5056.4  319.11  5065.5  318.00  5070.9  319.75  5110.4  320.49
  5119.1  319.58  5124.5  320.55  5131.9  317.66  5142.7  316.14  5148.6  318.98
  5154.0  318.02  5164.3  321.15  5178.1  321.03  5326.1  326.77  5457.4  335.39
#Mann=4,-1,0
  4575.1    0.05       0  4649.3    0.16       0  4999.5    0.07       0
  5005.5    0.16       0
Bank Sta=4999.5,5005.5
Exp/Cntr=0.3,0.1

Type RM Length L Ch R = 1,3639,433,433,433
BEGIN DESCRIPTION:
CAMP CREEK TRIBUTARY 9 8.0
END DESCRIPTION:
XS GIS Cut Line= 3
      3557519.48     10369387.38      3557942.11     10368991.64
      3558142.09     10368691.67
#Sta/Elev= 30
  4399.6  339.62  4467.6  338.02  4582.2  334.35  4624.7  334.74  4674.5  334.27
  4695.5  333.36  4702.8  333.70  4738.0  331.49  4745.3  331.71  4773.2  330.20
  4829.8  326.06  4858.2  323.20  4872.3  322.90  4914.8  319.94  4922.2  320.01
  4964.6  315.22  4975.2  312.73  5019.1  312.36  5021.9  311.86  5025.1  312.36
  5037.2  312.69  5058.2  316.04  5079.2  316.16  5094.3  317.59  5172.4  321.78
  5238.5  327.11  5259.5  327.91  5289.6  330.42  5295.6  330.15  5339.1  333.43
#Mann=4,-1,0
  4399.6    0.05       0  4467.6    0.16       0  5019.1    0.07       0
  5025.1    0.16       0
Bank Sta=5019.1,5025.1
Exp/Cntr=0.3,0.1

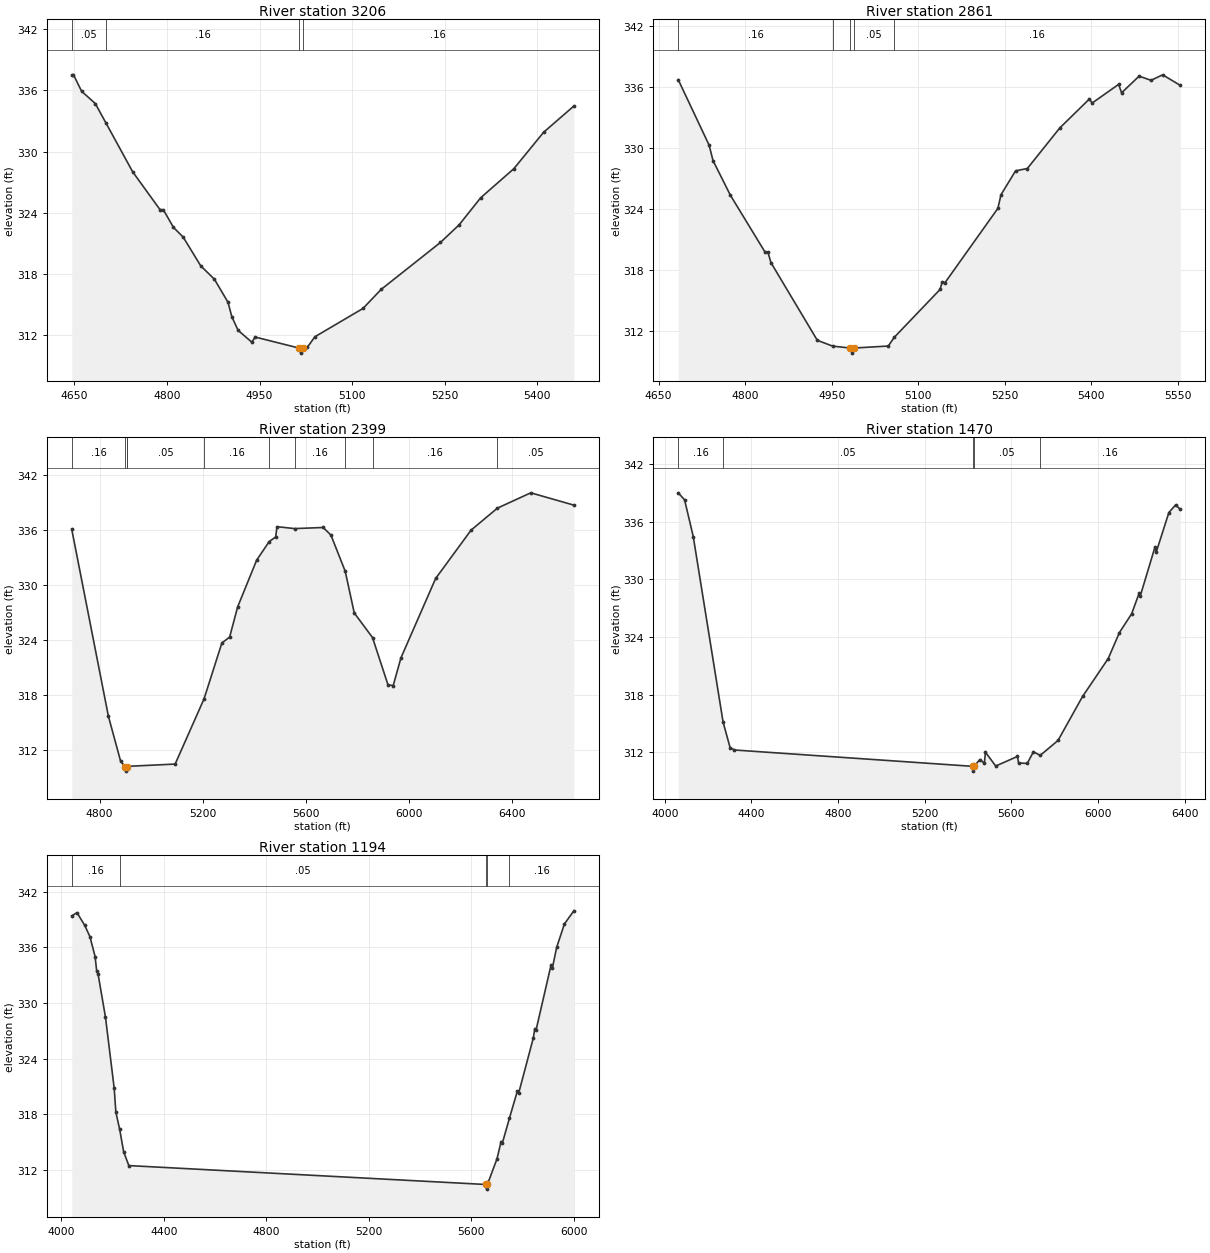
Type RM Length L Ch R = 1,3206,345,345,345
BEGIN DESCRIPTION:
CAMP CREEK TRIBUTARY 9 7.0
END DESCRIPTION:
XS GIS Cut Line= 3
      3558130.14     10369551.69      3558292.11     10369241.64
      3558465.24     10368810.94
#Sta/Elev= 30
  4645.6  337.54  4648.4  337.54  4661.6  335.92  4683.7  334.72  4700.8  332.83
  4744.3  328.01  4788.5  324.30  4794.1  324.27  4810.5  322.54  4826.2  321.59
  4854.7  318.76  4876.8  317.45  4898.9  315.18  4905.1  313.76  4915.3  312.42
  4937.4  311.26  4943.0  311.76  5014.0  310.68  5016.7  310.18  5020.0  310.68
  5027.7  310.77  5039.8  311.79  5117.7  314.57  5147.3  316.45  5243.3  321.06
  5273.6  322.79  5308.5  325.45  5362.3  328.31  5410.7  331.90  5459.6  334.47
#Mann=4,-1,0
  4645.6    0.05       0  4700.8    0.16       0  5014.0    0.07       0
  5020.0    0.16       0
Bank Sta=5014,5020
Exp/Cntr=0.3,0.1

Type RM Length L Ch R = 1,2861,462,462,462
BEGIN DESCRIPTION:
CAMP CREEK TRIBUTARY 9 6.0
END DESCRIPTION:
XS GIS Cut Line= 3
      3558592.11     10369641.64      3558635.71     10369193.10
      3558718.01     10368781.61
#Sta/Elev= 30
  4683.9  336.72  4737.4  330.28  4744.2  328.76  4774.3  325.35  4834.3  319.76
  4839.3  319.74  4844.7  318.71  4925.0  311.07  4951.6  310.50  4982.3  310.31
  4985.1  309.81  4988.3  310.31  5048.1  310.51  5058.1  311.35  5137.8  316.08
  5141.4  316.81  5146.5  316.76  5238.0  324.06  5243.4  325.40  5268.6  327.75
  5289.0  327.98  5345.4  331.98  5396.4  334.81  5401.5  334.43  5447.3  336.26
  5452.4  335.43  5482.8  337.07  5503.4  336.66  5523.6  337.20  5554.2  336.16
#Mann=5,-1,0
  4683.9    0.16       0  4951.6    0.05       0  4982.3   0.033       0
  4988.3    0.05       0  5058.1    0.16       0
Bank Sta=4982.3,4988.3
Exp/Cntr=0.3,0.1

Type RM Length L Ch R = 1,2399,929,929,929
BEGIN DESCRIPTION:
CAMP CREEK TRIBUTARY 9 5.0
END DESCRIPTION:
XS GIS Cut Line= 3
      3558942.12     10369691.63      3559058.99     10369539.95
      3559286.83     10367795.75
#Sta/Elev= 30
  4691.6  336.10  4833.8  315.74  4881.5  310.81  4898.5  310.24  4901.3  309.74
  4904.5  310.24  4906.2  310.26  5093.2  310.51  5205.6  317.63  5274.7  323.71
  5304.9  324.36  5336.0  327.65  5409.9  332.75  5458.5  334.77  5483.8  335.28
  5488.8  336.40  5557.0  336.19  5668.0  336.31  5698.3  335.49  5754.0  331.53
  5789.0  326.99  5859.9  324.31  5920.1  319.15  5940.3  319.07  5970.5  322.10
  6105.2  330.75  6242.8  336.02  6345.1  338.42  6474.8  340.09  6642.1  338.75
#Mann=10,-1,0
  4691.6    0.16       0  4898.5   0.033       0  4904.5    0.16       0
  4906.2    0.05       0  5205.6    0.16       0  5458.5    0.08       0
  5557.0    0.16       0  5754.0    0.05       0  5859.9    0.16       0
  6345.1    0.05       0
Bank Sta=4898.5,4904.5
Exp/Cntr=0.3,0.1

Type RM Length L Ch R = 1,1470,276,276,276
BEGIN DESCRIPTION:
CAMP CREEK TRIBUTARY 9 3.0
END DESCRIPTION:
XS GIS Cut Line= 3
      3558942.86     10369802.77      3559698.05     10369813.19
      3561202.99     10369396.59
#Sta/Elev= 30
  4062.5  339.01  4091.8  338.28  4131.8  334.46  4269.5  315.14  4301.8  312.49
  4321.8  312.24  5420.8  310.54  5423.5  310.04  5426.8  310.54  5454.9  311.25
  5475.0  310.85  5480.2  312.01  5527.5  310.57  5627.8  311.57  5633.0  310.89
  5672.8  310.84  5701.6  312.05  5732.9  311.68  5814.9  313.23  5928.2  317.81
  6046.7  321.76  6098.2  324.46  6154.8  326.42  6189.1  328.55  6194.3  328.26
  6262.9  333.40  6268.1  332.83  6326.5  336.96  6357.6  337.75  6379.3  337.29
#Mann=5,-1,0
  4062.5    0.16       0  4269.5    0.05       0  5420.8   0.033       0
  5426.8    0.05       0  5732.9    0.16       0
Bank Sta=5420.8,5426.8
Exp/Cntr=0.3,0.1

Type RM Length L Ch R = 1,1194,0,0,0
BEGIN DESCRIPTION:
CAMP CREEK TRIBUTARY 9 1.0
END DESCRIPTION:
XS GIS Cut Line= 2
      3558942.12     10369891.64      3560878.41     10370189.71
#Sta/Elev= 30
  4041.2  339.38  4061.4  339.74  4091.8  338.36  4112.0  337.15  4132.2  335.00
  4138.5  333.43  4143.6  333.15  4172.7  328.46  4206.8  320.78  4213.2  318.22
  4228.1  316.36  4243.5  313.96  4263.8  312.45  5657.0  310.41  5659.8  309.91
  5663.0  310.41  5700.5  313.18  5716.4  315.04  5721.5  314.89  5749.1  317.57
  5779.7  320.47  5784.7  320.23  5842.2  326.22  5847.9  327.23  5853.0  327.09
  5911.1  334.05  5916.2  333.72  5933.2  335.98  5963.6  338.52  6000.3  339.93
#Mann=5,-1,0
  4041.2    0.16       0  4228.1    0.05       0  5657.0   0.033       0
  5663.0    0.05       0  5749.1    0.16       0
Bank Sta=5657,5663
Exp/Cntr=0.3,0.1

Chan Stop Cuts=-1