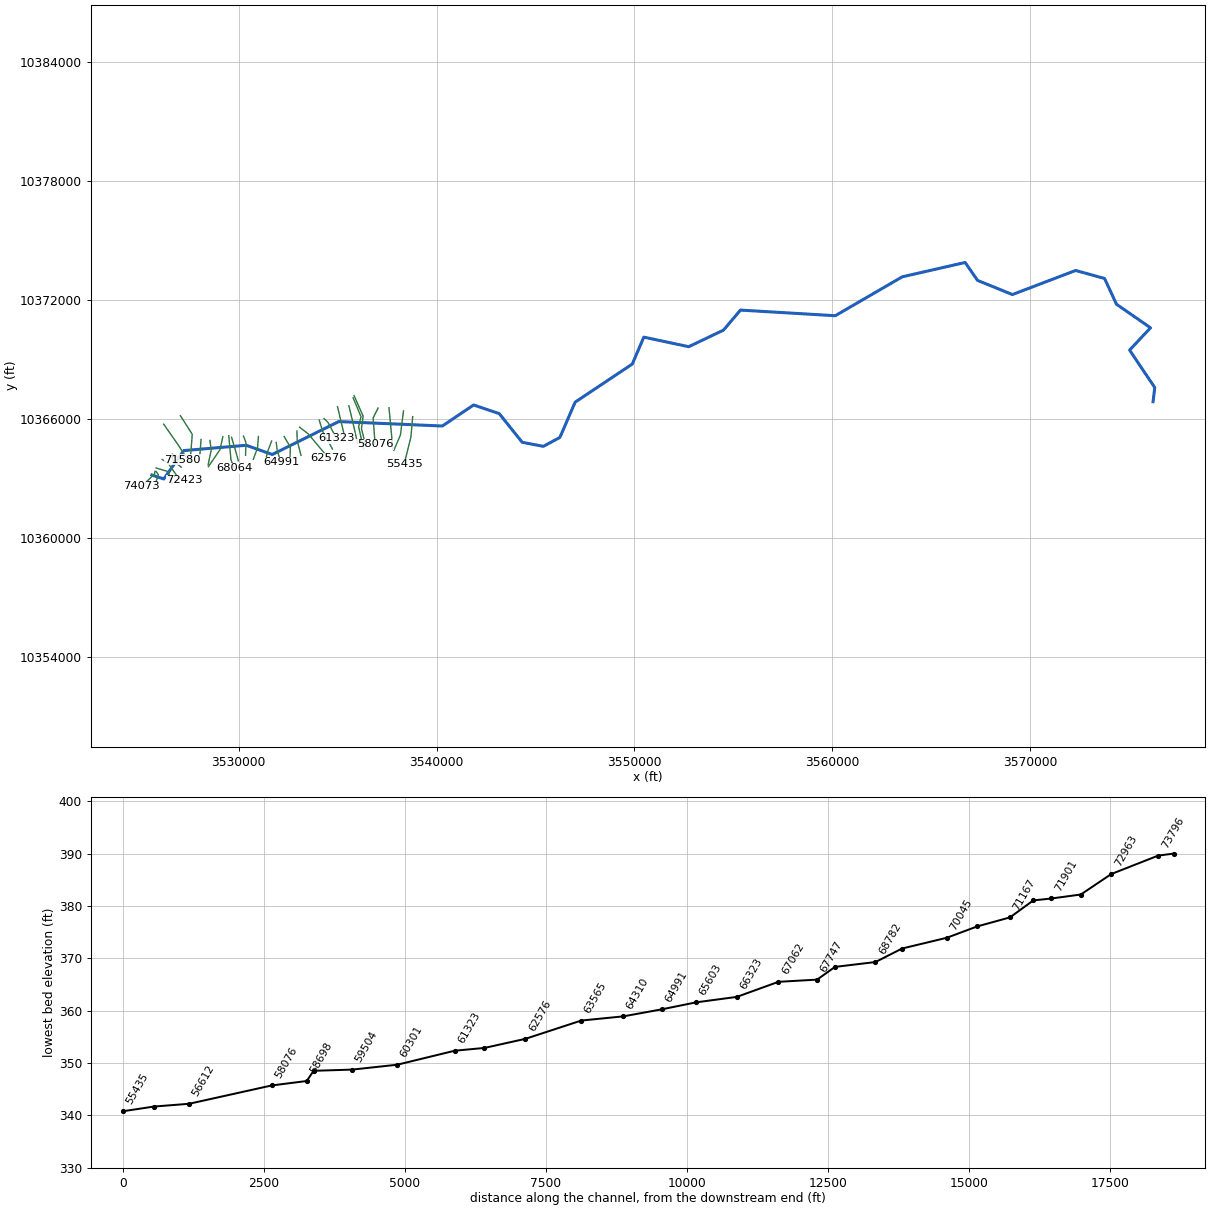
--- CAMP CREEK.prj (project) ---

Proj Title=CAMP CREEK Base Level Engineering
Current Plan=p01
Default Exp/Contr=0.3,0.1
English Units
Geom File=g01
Flow File=f01
Plan File=p01
Y Axis Title=Elevation
X Axis Title(PF)=Main Channel Distance
X Axis Title(XS)=Station
BEGIN DESCRIPTION:
CAMP CREEK
END DESCRIPTION:
DSS Export Rating Curves= 0
DSS Export Rating Curve Sorted= 0
DSS Export Volume Flow Curves= 0
DXF OffsetX= 0
DXF OffsetY= 0
DXF ScaleX= 1
DXF ScaleY= 10

--- CAMP CREEK.p01 (plan) ---

Plan Title=Multiple Run
Short Identifier=Multiple
Geom File=g01
Flow File=f01
Subcritical Flow
K Sum by GR= 0
Std Step Tol= 0.01
Critical Tol= 0.01
Num of Std Step Trials= 20
Max Error Tol= 0.3
Flow Tol Ratio= 0.001
Split Flow NTrial= 30
Split Flow Tol= 0.02
Split Flow Ratio= 0.02
Log Output Level= 0
Friction Slope Method= 1
Unsteady Friction Slope Method= 2
Unsteady Bridges Friction Slope Method= 1
Parabolic Critical Depth
Global Vel Dist=  1 , 1 , 1
Global Log Level= 0
CheckData=True
Encroach Param= -1, 0, 0, 0
BEGIN DESCRIPTION:
Multiple Run
END DESCRIPTION:

--- CAMP CREEK.f01 (steady flow) ---

Flow Title=Multiple
Program Version=4.10
Number of Profiles= 7
Profile Names=10-year,25-year,50-year,1pct_min,100-year,1pct_plu,500-year
River Rch & RM=CAMP CREEK,Reach-1         ,74073
    1532    2186    2745    2513    3399    4597    5203
River Rch & RM=CAMP CREEK,Reach-1         ,71901
    1532    2186    2745    2513    3399    4597    5203
River Rch & RM=CAMP CREEK,Reach-1         ,70045
    1925    2777    3512    3235    4375    5917    6783
River Rch & RM=CAMP CREEK,Reach-1         ,68782
    2192    3163    4002    3684    4982    6737    7713
River Rch & RM=CAMP CREEK,Reach-1         ,62576
    3676    5409    6932    6454    8728   11804   13823
River Rch & RM=CAMP CREEK,Reach-1         ,56612
    3896    5735    7351    6842    9254   12515   14649
River Rch & RM=CAMP CREEK,Reach-1         ,52829
    4246    6262    8035    7486   10124   13692   16054
River Rch & RM=CAMP CREEK,Reach-1         ,50644
    4380    6448    8265    7689   10399   14063   16442
River Rch & RM=CAMP CREEK,Reach-1         ,43926
    6290    9371   12109   11350   15350   20758   24638
River Rch & RM=CAMP CREEK,Reach-1         ,38969
    6324    9411   12152   11379   15389   20812   24655
River Rch & RM=CAMP CREEK,Reach-1         ,35678
    8601   12881   16707   15701   21234   28717   34252
River Rch & RM=CAMP CREEK,Reach-1         ,30845
    8991   13467   17467   16414   22198   30021   35798
River Rch & RM=CAMP CREEK,Reach-1         ,30153
    8991   13467   17467   16414   22198   30021   35798
River Rch & RM=CAMP CREEK,Reach-1         ,28226
    9025   13501   17496   16427   22215   30043   35757
River Rch & RM=CAMP CREEK,Reach-1         ,25548
    9109   13605   17611   16514   22333   30203   35856
River Rch & RM=CAMP CREEK,Reach-1         ,22642
   10769   16212   21105   19901   26913   36397   43683
River Rch & RM=CAMP CREEK,Reach-1         ,19532
   10618   15938   20705   19481   26346   35630   42576
River Rch & RM=CAMP CREEK,Reach-1         ,12318
   10514   15725   20377   19121   25858   34970   41561
Boundary for River Rch & Prof#=CAMP CREEK,Reach-1         , 1
Up Type= 0
Dn Type= 3
Dn Slope=0.001
Boundary for River Rch & Prof#=CAMP CREEK,Reach-1         , 2
Up Type= 0
Dn Type= 3
Dn Slope=0.001
Boundary for River Rch & Prof#=CAMP CREEK,Reach-1         , 3
Up Type= 0
Dn Type= 3
Dn Slope=0.001
Boundary for River Rch & Prof#=CAMP CREEK,Reach-1         , 4
Up Type= 0
Dn Type= 3
Dn Slope=0.001
Boundary for River Rch & Prof#=CAMP CREEK,Reach-1         , 5
Up Type= 0
Dn Type= 3
Dn Slope=0.001
Boundary for River Rch & Prof#=CAMP CREEK,Reach-1         , 6
Up Type= 0
Dn Type= 3
Dn Slope=0.001
Boundary for River Rch & Prof#=CAMP CREEK,Reach-1         , 7
Up Type= 0
Dn Type= 3
Dn Slope=0.001
DSS Import GetInterval= 0
DSS Import GetPeak= 0
DSS Import FillOption= 0

--- CAMP CREEK.g01 (geometry) ---

Geom Title=Existing Conditions
Program Version=4.10

River Reach=CAMP CREEK      ,Reach-1
Reach XY= 30
      3525604.81     10363199.27      3526206.56     10362997.33
      3527217.15     10364429.82       3530375.3     10364697.06
      3531691.85     10364233.02      3535052.95     10365892.82
      3540292.32     10365668.76      3541872.62     10366730.68
      3543171.16      10366291.6      3544329.38     10364847.46
      3545398.17     10364643.79      3546233.36     10365092.23
      3547006.94     10366872.27      3549898.41     10368796.48
      3550480.47     10370150.31      3552747.36     10369667.51
      3554505.17     10370503.02      3555365.15      10371513.7
      3560158.39     10371230.01      3563544.56     10373191.34
      3566726.29     10373914.79      3567349.19      10373012.8
      3569113.82     10372297.37      3572312.11     10373511.64
      3573775.01     10373106.72      3574377.95     10371807.14
      3576098.13       10370620.      3575039.52     10369498.28
      3576312.42      10367606.6       3576225.4     10366893.66

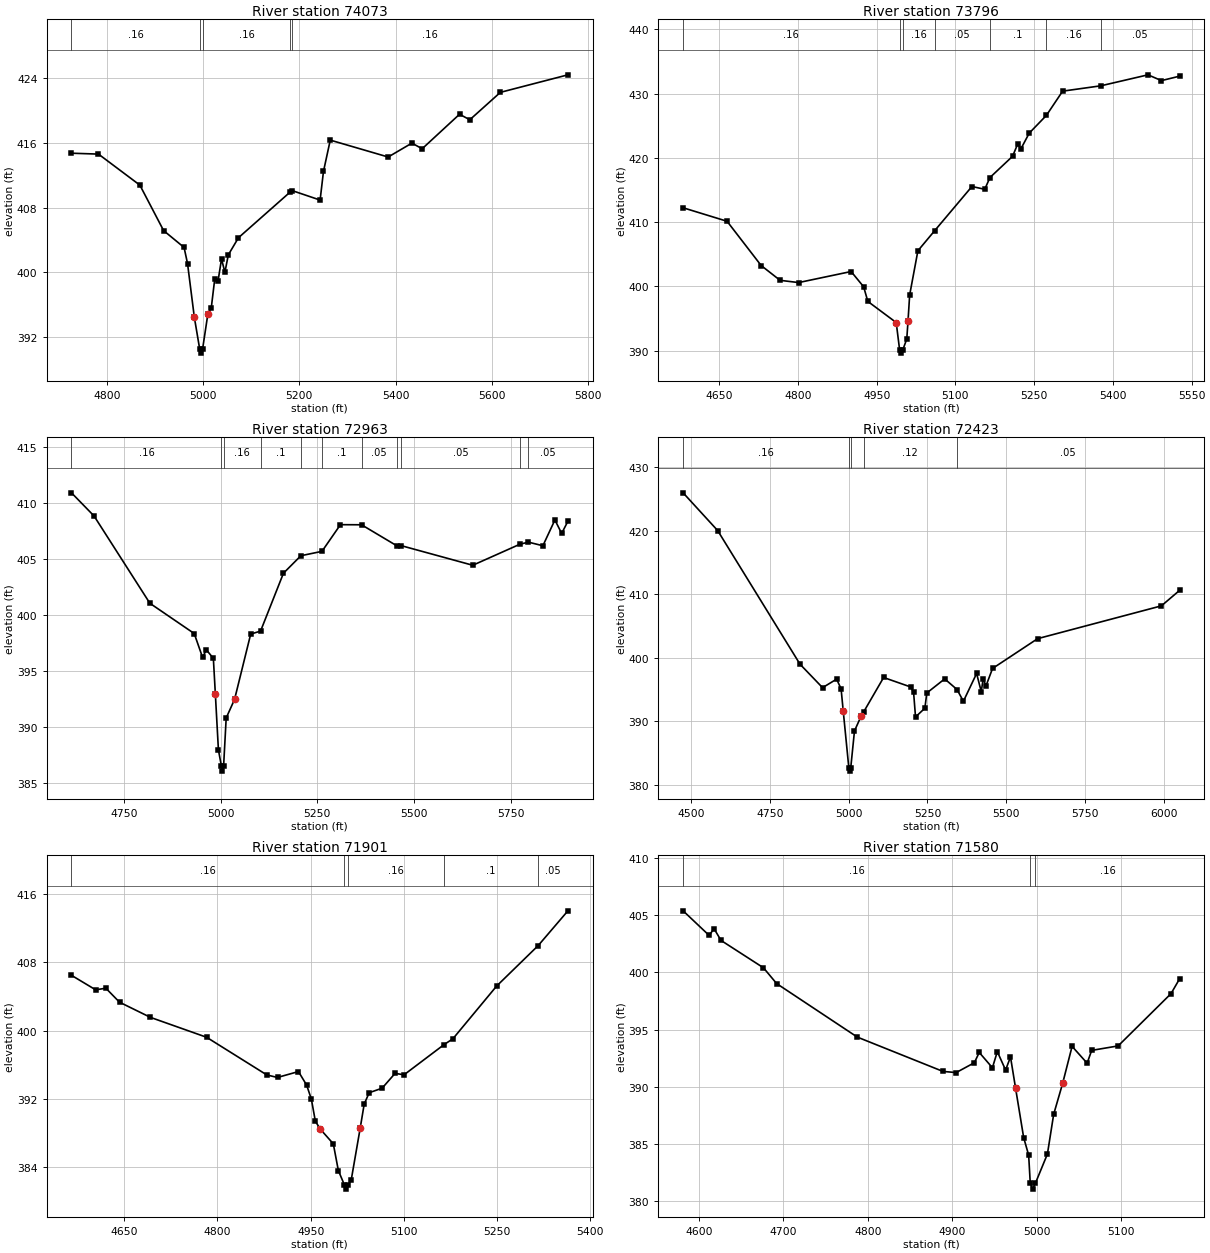
Type RM Length L Ch R = 1 ,74073   ,277,277,277
BEGIN DESCRIPTION:
Mapping XS 18738b2a
END DESCRIPTION:
XS GIS Cut Line= 3
      3525767.86     10363385.29      3525739.41     10363250.17
      3525096.54      10362628.6
#Sta/Elev= 30
  4726.2  414.75  4782.3  414.64  4868.4   410.8  4917.8  405.17  4960.3  403.09
  4967.5   401.1  4981.6  394.47  4992.8  390.51  4995.5  390.01  4998.8  390.51
  5009.9  394.89  5016.9  395.63    5024  399.14    5031  398.96  5038.2  401.66
  5045.2  400.01  5052.3  402.17  5073.4  404.29  5181.4  409.97  5185.7  410.11
  5243.2  408.95  5250.2   412.5  5264.3  416.37  5384.7  414.28  5434.1     416
  5455.4   415.3  5533.1  419.57  5554.5  418.89    5618  422.28  5758.5  424.45
#Mann= 5 ,-1 , 0
  4726.2     .16       0  4992.8     .07       0  4998.8     .16       0
  5181.4     .05       0  5185.7     .16       0
Bank Sta=4981.6,5009.9
XS Rating Curve= 0 ,0
Exp/Cntr=0.3,0.1

Type RM Length L Ch R = 1 ,73796   ,833,833,833
BEGIN DESCRIPTION:
Mapping XS 75959c5b
END DESCRIPTION:
XS GIS Cut Line= 3
      3525824.71     10363371.05      3525934.92     10363207.51
      3525686.58     10362501.52
#Sta/Elev= 30
  4581.4  412.25  4665.1  410.15  4730.1  403.26  4766.1  400.96  4801.4  400.61
  4901.4  402.33  4925.3  399.95  4933.2  397.68  4987.3  394.39  4993.8  390.13
  4996.6  389.63  4999.8  390.13  5007.4  391.82  5009.8  394.64  5012.9  398.67
  5028.6  405.56  5060.3  408.66  5131.5  415.56  5155.9  415.13  5165.9  416.96
  5208.9  420.26  5219.1  422.25  5224.4  421.36  5240.7  423.87  5273.3  426.62
  5304.3   430.4    5377  431.23  5466.9  432.94  5492.5  432.04    5527  432.73
#Mann= 7 ,-1 , 0
  4581.4     .16       0  4993.8     .07       0  4999.8     .16       0
  5060.3     .05       0  5165.9      .1       0  5273.3     .16       0
    5377     .05       0
Bank Sta=4987.3,5009.8
XS Rating Curve= 0 ,0
Exp/Cntr=0.3,0.1

Type RM Length L Ch R = 1 ,72963   ,540,540,540
BEGIN DESCRIPTION:
Mapping XS 4fae18d8
END DESCRIPTION:
XS GIS Cut Line= 3
      3525817.63     10363552.32      3526425.48     10363371.03
      3526638.66     10362756.35
#Sta/Elev= 30
  4613.6  410.92  4672.1  408.85  4816.5  401.07  4931.3  398.37  4952.9  396.24
  4962.6  396.92  4980.8  396.16    4986  392.95  4993.9  387.99  5001.4   386.6
  5004.1   386.1  5007.4   386.6    5014  390.84  5035.7   392.5  5077.4  398.32
    5103  398.59  5162.2  403.75  5207.3  405.31  5261.9   405.7  5309.7  408.08
  5364.4  408.07    5456  406.19  5465.8  406.22  5652.2  404.46  5774.5  406.34
  5796.4  406.52  5833.7   406.2  5864.8   408.5  5882.3   407.3  5898.5  408.39
#Mann= 11 ,-1 , 0
  4613.6     .16       0  5001.4     .07       0  5007.4     .16       0
    5103      .1       0  5207.3     .16       0  5261.9      .1       0
  5364.4     .05       0    5456      .1       0  5465.8     .05       0
  5774.5      .1       0  5796.4     .05       0
Bank Sta=4986,5035.7
XS Rating Curve= 0 ,0
Exp/Cntr=0.3,0.1

Type RM Length L Ch R = 1 ,72423   ,522,522,522
BEGIN DESCRIPTION:
Mapping XS 8db933f6
END DESCRIPTION:
XS GIS Cut Line= 4
      3526130.44     10363982.44      3526425.48      10363797.6
      3526901.82     10363111.53       3527253.7     10362937.37
#Sta/Elev= 30
  4474.3  425.97  4583.9  420.04  4845.4  399.01    4917  395.32  4961.6  396.66
  4975.8  395.14  4982.5   391.7  5000.4  382.69  5003.2  382.19  5006.4  382.69
  5018.3  388.51  5039.2  390.82  5047.3  391.49  5110.8  396.92  5197.3  395.42
    5206  394.56  5212.1  390.71  5241.8  392.09  5247.9  394.48  5304.7   396.7
  5343.8  395.03  5364.1  393.18    5406  397.55  5420.8   394.7  5426.9  396.74
  5435.7  395.58  5456.6  398.34  5599.8  403.03  5992.7  408.19  6050.3  410.62
#Mann= 5 ,-1 , 0
  4474.3     .16       0  5000.4     .07       0  5006.4     .16       0
  5047.3     .12       0  5343.8     .05       0
Bank Sta=4982.5,5039.2
XS Rating Curve= 0 ,0
Exp/Cntr=0.3,0.1

Type RM Length L Ch R = 1 ,71901   ,321,321,321
BEGIN DESCRIPTION:
CAMP CREEK 112.0
END DESCRIPTION:
XS GIS Cut Line= 3
      3526570.75     10364174.27      3526723.51     10363882.63
      3527092.08     10363591.66
#Sta/Elev= 30
  4565.1  406.49    4604  404.79  4620.4  404.98  4642.4  403.34  4692.2  401.56
  4782.5  399.23  4879.5  394.81  4896.6  394.52  4930.3  395.21  4943.5  393.62
  4951.1  391.97  4957.5  389.39  4965.6  388.45  4986.4  386.74  4994.5  383.61
  5004.2  381.93  5006.9  381.43  5010.2  381.93  5015.3  382.54  5029.7   388.6
  5036.1   391.4  5044.1  392.73  5064.9  393.26  5085.8     395  5100.2  394.83
  5164.6  398.37  5178.8  399.05  5249.3  405.24  5316.1  409.98  5363.9  414.05
#Mann= 5 ,-1 , 0
  4565.1     .16       0  5004.2     .07       0  5010.2     .16       0
  5164.6      .1       0  5316.1     .05       0
Bank Sta=4965.6,5029.7
XS Rating Curve= 0 ,0
Exp/Cntr=0.3,0.1

Type RM Length L Ch R = 1 ,71580   ,413,413,413
BEGIN DESCRIPTION:
CAMP CREEK 111.0
END DESCRIPTION:
XS GIS Cut Line= 3
       3526633.5     10364254.01      3526992.11     10364041.64
      3527148.83     10363973.67
#Sta/Elev= 30
  4581.4  405.39  4612.2  403.24    4618  403.83  4626.3   402.8  4676.5  400.41
  4692.1  399.03  4787.6  394.35    4889  391.35  4904.6  391.25  4926.1  392.11
  4931.9  393.01  4947.5  391.67  4953.3  393.08  4963.1  391.47  4968.9  392.62
  4974.9  389.89  4984.5  385.56  4990.4  384.03  4992.3  381.56    4995  381.06
  4998.3  381.56  5012.6  384.13    5020   387.6  5030.6   390.3  5041.8  393.54
  5059.6  392.07    5065  393.19  5096.3  393.58  5158.9  398.15    5169  399.44
#Mann= 3 ,-1 , 0
  4581.4     .16       0  4992.3     .07       0  4998.3     .16       0
Bank Sta=4974.9,5030.6
XS Rating Curve= 0 ,0
Exp/Cntr=0.3,0.1

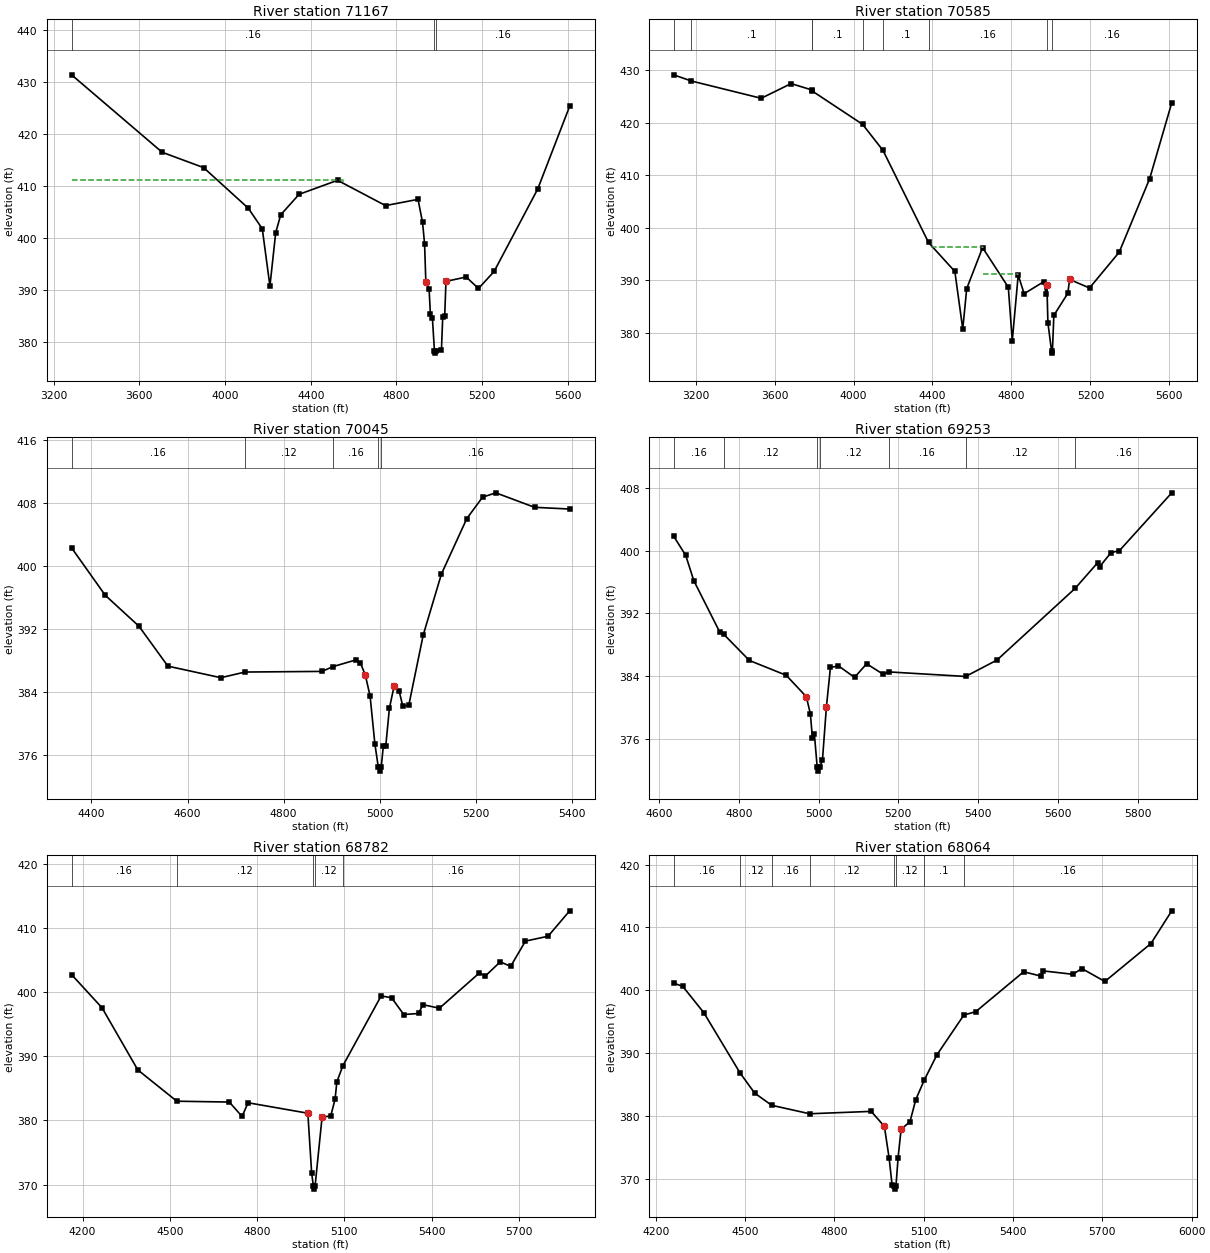
Type RM Length L Ch R = 1 ,71167   ,582,582,582
BEGIN DESCRIPTION:
CAMP CREEK 109.0
END DESCRIPTION:
XS GIS Cut Line= 3
      3526203.36     10365760.96        3526936.     10364715.83
      3527497.79     10363831.53
#Sta/Elev= 30
  3284.2  431.41  3706.8   416.5  3900.3  413.54  4108.6  405.73    4174  401.77
  4209.7  390.74  4236.7  401.04  4260.3  404.47  4345.8   408.4  4525.3   411.1
  4749.1  406.23  4900.7  407.43  4921.9  402.98  4931.2   398.9  4937.1  391.59
  4952.4  390.15  4958.3  385.37  4967.6  384.67  4977.2  378.32  4979.9  377.82
  4983.2  378.32    5010  378.44  5015.9  384.73  5025.2  385.05  5031.1  391.63
  5125.2  392.48  5182.8  390.27  5255.6  393.54  5458.9   409.4  5608.2  425.36
#Mann= 3 ,-1 , 0
  3284.2     .16       0  4977.2     .07       0  4983.2     .16       0
#XS Ineff= 2 , 0
         4551.14  411.18
Permanent Ineff=
       F       F
Bank Sta=4937.1,5031.1
XS Rating Curve= 0 ,0
Exp/Cntr=0.3,0.1

Type RM Length L Ch R = 1 ,70585   ,540,540,540
BEGIN DESCRIPTION:
CAMP CREEK 110.0
END DESCRIPTION:
XS GIS Cut Line= 3
      3527047.99     10366189.77      3527646.93     10365252.29
      3527538.45     10363846.35
#Sta/Elev= 30
  3089.1  429.11  3178.3  427.94  3532.6  424.64    3684  427.44  3789.5  426.22
  3792.2  425.99  4045.9  419.68  4149.5   414.7  4379.9  397.17  4513.2  391.65
  4553.3  380.68  4573.3  388.38  4653.6  396.19    4784  388.64    4804  378.45
  4834.1  390.97  4864.2  387.41  4964.5  389.72  4974.4  387.43  4979.4  389.13
  4984.5  381.87  5004.4  376.09  5007.6  376.59  5014.6  383.28  5084.8  387.45
  5094.9  390.12  5195.2   388.5  5345.6  395.32  5500.1  409.35  5611.7  423.78
#Mann= 9 ,-1 , 0
  3089.1     .05       0  3178.3      .1       0  3789.5     .05       0
  3792.2      .1       0  4045.9     .05       0  4149.5      .1       0
  4379.9     .16       0  4979.4     .07       0  5007.6     .16       0
#XS Ineff= 3 ,-1
  3089.1 4394.32   391.1 4394.32 4653.41  396.28 4653.41 4834.09   391.1
Permanent Ineff=
       F       F       F
Bank Sta=4979.4,5094.9
XS Rating Curve= 0 ,0
Exp/Cntr=0.3,0.1

Type RM Length L Ch R = 1 ,70045   ,792,792,792
BEGIN DESCRIPTION:
CAMP CREEK 108.0
END DESCRIPTION:
XS GIS Cut Line= 3
       3528092.1      10364991.6      3528042.11     10364341.64
      3527994.34     10363958.99
#Sta/Elev= 30
  4358.5  402.29  4428.7  396.26  4498.9  392.33  4559.1  387.26  4669.4  385.79
  4719.9  386.51    4880  386.59    4903   387.2  4950.2  388.04  4960.2  387.66
  4970.3  386.14  4980.3  383.46  4990.3  377.37  4997.4  374.42  5000.1  373.92
  5003.4  374.42  5007.9  377.08  5012.9  377.08  5020.5   381.9  5030.5  384.78
  5040.6  384.15  5048.2  382.23  5060.8  382.26    5091  391.22  5128.9  398.97
  5181.7     406  5214.6  408.73  5242.2  409.28  5322.8  407.44    5396  407.22
#Mann= 5 ,-1 , 0
  4358.5     .16       0  4719.9     .12       0    4903     .16       0
  4997.4     .07       0  5003.4     .16       0
Bank Sta=4970.3,5030.5
XS Rating Curve= 0 ,0
Exp/Cntr=0.3,0.1

Type RM Length L Ch R = 1 ,69253   ,471,471,471
BEGIN DESCRIPTION:
CAMP CREEK 107.0
END DESCRIPTION:
XS GIS Cut Line= 3
       3528542.1     10364941.67      3528605.46     10364455.55
      3528449.22     10363712.53
#Sta/Elev= 30
  4636.3  401.87  4666.6  399.42  4686.8   396.2  4752.3  389.59  4762.4  389.32
  4826.3     386  4918.7  384.11  4969.1  381.37  4979.2  379.21  4984.4  376.12
  4989.4  376.55  4996.4  372.37  4999.1  371.87  5002.4  372.37  5009.5  373.23
  5019.5  380.08  5029.6  385.11  5049.8  385.31  5090.1  383.84  5120.4  385.58
  5161.2  384.26    5176  384.54  5368.7  383.96  5447.3  386.05  5643.3   395.2
  5699.7  398.47  5704.8  397.97  5733.4  399.77  5754.6  400.03  5885.8  407.41
#Mann= 7 ,-1 , 0
  4636.3     .16       0  4762.4     .12       0  4996.4     .07       0
  5002.4     .12       0    5176     .16       0  5368.7     .12       0
  5643.3     .16       0
Bank Sta=4969.1,5019.5
XS Rating Curve= 0 ,0
Exp/Cntr=0.3,0.1

Type RM Length L Ch R = 1 ,68782   ,718,718,718
BEGIN DESCRIPTION:
CAMP CREEK 106.0
END DESCRIPTION:
XS GIS Cut Line= 3
      3529194.68     10365133.84      3529048.84     10364474.08
      3528462.04     10363619.91
#Sta/Elev= 30
  4162.2  402.72  4266.9  397.55  4389.8  387.87    4524  382.99  4704.5  382.86
  4748.2  380.61  4768.7  382.75  4974.3  381.12  4987.4   371.8  4993.2  369.79
  4995.9  369.29  4999.2  369.79  5023.2   380.5    5053   380.7  5067.9  383.31
    5074     386  5094.7  388.52  5226.2   399.4  5262.1  399.11    5304   396.5
  5354.8  396.66  5369.7  398.04  5426.5  397.48  5563.9  402.98  5584.8  402.52
  5635.6  404.71  5671.4  404.01  5722.2  407.94    5800   408.7  5874.2  412.66
#Mann= 5 ,-1 , 0
  4162.2     .16       0    4524     .12       0  4993.2     .07       0
  4999.2     .12       0  5094.7     .16       0
Bank Sta=4974.3,5023.2
XS Rating Curve= 0 ,0
Exp/Cntr=0.3,0.1

Type RM Length L Ch R = 1 ,68064   ,317,317,317
BEGIN DESCRIPTION:
CAMP CREEK 105.0
END DESCRIPTION:
XS GIS Cut Line= 3
      3529493.28     10365182.44       3529604.4     10363956.72
      3529771.07     10363546.97
#Sta/Elev= 30
    4260  401.15  4290.9   400.6  4361.2  396.44  4483.1  386.84  4531.9  383.65
  4589.1   381.7  4716.8  380.35  4923.5  380.73  4967.8  378.35  4983.8  373.29
  4993.8  368.99  5000.8  368.86  5003.6  368.36  5006.8  368.86  5013.9  373.37
  5023.9  377.85    5054  379.12  5073.4  382.62  5101.8  385.71  5144.4  389.73
  5234.7  396.05  5274.9   396.6  5435.6  402.94  5494.4  402.25  5499.8  403.09
  5601.4  402.54  5630.9  403.46  5708.5   401.4  5863.3  407.44  5933.1  412.64
#Mann= 8 ,-1 , 0
    4260     .16       0  4483.1     .12       0  4589.1     .16       0
  4716.8     .12       0  5000.8     .07       0  5006.8     .12       0
  5101.8      .1       0  5234.7     .16       0
Bank Sta=4967.8,5023.9
XS Rating Curve= 0 ,0
Exp/Cntr=0.3,0.1

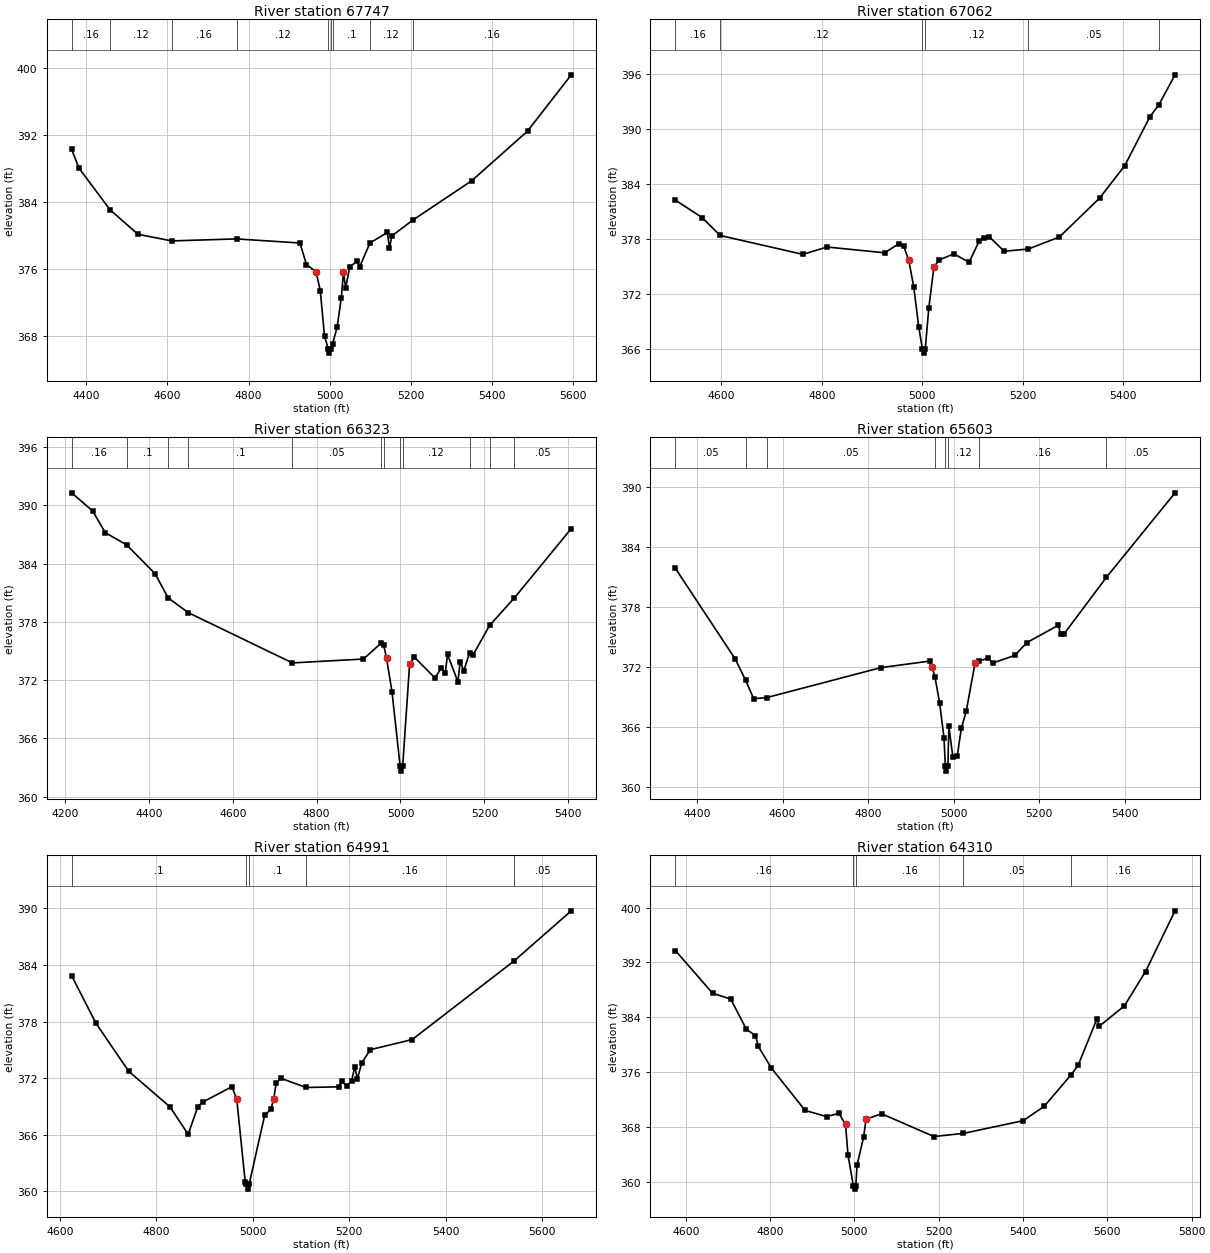
Type RM Length L Ch R = 1 ,67747   ,685,685,685
BEGIN DESCRIPTION:
CAMP CREEK 104.0
END DESCRIPTION:
XS GIS Cut Line= 3
      3529633.23     10365097.94      3529803.37     10364542.35
       3529976.6     10363915.29
#Sta/Elev= 30
  4363.9  390.29  4381.7  388.06  4458.6  383.06  4527.4  380.13  4610.7  379.34
  4770.4  379.58  4926.8  379.09  4942.7  376.51  4966.4  375.66  4976.8  373.39
  4987.2  367.98  4996.6  366.43  4999.4  365.93  5002.6  366.43  5007.2  367.05
  5018.3  369.03  5028.7  372.57    5034  375.65  5039.2  373.68  5049.4  376.24
  5068.3  376.93  5073.5   376.2  5099.3   379.1  5142.2  380.35  5147.4  378.49
  5153.2  379.94  5204.4  381.81  5350.3  386.54  5487.6  392.46  5595.5  399.19
#Mann= 9 ,-1 , 0
  4363.9     .16       0  4458.6     .12       0  4610.7     .16       0
  4770.4     .12       0  4996.6     .07       0  5002.6     .12       0
  5007.2      .1       0  5099.3     .12       0  5204.4     .16       0
Bank Sta=4966.4,5034
XS Rating Curve= 0 ,0
Exp/Cntr=0.3,0.1

Type RM Length L Ch R = 1 ,67062   ,739,739,739
BEGIN DESCRIPTION:
CAMP CREEK 102.0
END DESCRIPTION:
XS GIS Cut Line= 3
       3530237.4     10365163.88      3530358.93      10364842.7
      3530342.11     10364191.62
#Sta/Elev= 30
  4508.5  382.22  4561.6  380.32  4597.8  378.36  4762.1   376.3  4810.3   377.1
  4925.3  376.47    4953  377.45    4963   377.2    4973  375.66    4983  372.75
    4993  368.36    5000  366.01  5002.8  365.51    5006  366.01    5013  370.45
    5023  374.87    5033  375.67    5063  376.36    5093  375.43  5113.1  377.72
  5123.1  378.13  5133.1  378.23  5163.1  376.64    5211  376.88  5273.1   378.2
  5353.1  382.45  5403.1  385.99  5453.2  391.33    5471  392.64  5503.2  395.91
#Mann= 6 ,-1 , 0
  4508.5     .16       0  4597.8     .12       0    5000     .07       0
    5006     .12       0    5211     .05       0    5471     .16       0
Bank Sta=4973,5023
XS Rating Curve= 0 ,0
Exp/Cntr=0.3,0.1

Type RM Length L Ch R = 1 ,66323   ,720,720,720
BEGIN DESCRIPTION:
CAMP CREEK 101.0
END DESCRIPTION:
XS GIS Cut Line= 3
      3530992.11     10365141.64      3530949.21     10364564.92
      3530732.18     10363991.96
#Sta/Elev= 30
  4216.1  391.28  4266.2  389.41  4296.3  387.18  4347.5  385.91    4415  382.95
  4446.2  380.46  4494.4  378.94  4742.4  373.77  4911.7  374.17  4952.9  375.77
  4959.8  375.62  4966.7  374.26  4979.7  370.81  4999.2  363.13    5002  362.63
  5005.2  363.13  5021.7  373.64  5033.2  374.35    5082  372.23  5097.3  373.23
  5106.8  372.75  5112.1  374.64  5136.9  371.82  5142.3  373.91  5150.8  372.96
  5164.7  374.79  5172.4  374.55  5212.3  377.63  5271.3  380.45  5407.1   387.6
#Mann= 12 ,-1 , 0
  4216.1     .16       0  4347.5      .1       0  4446.2     .05       0
  4494.4      .1       0  4742.4     .05       0  4952.9     .16       0
  4959.8     .12       0  4999.2     .07       0  5005.2     .12       0
  5164.7     .05       0  5212.3      .1       0  5271.3     .05       0
Bank Sta=4966.7,5021.7
XS Rating Curve= 0 ,0
Exp/Cntr=0.3,0.1

Type RM Length L Ch R = 1 ,65603   ,612,612,612
BEGIN DESCRIPTION:
CAMP CREEK 99.0
END DESCRIPTION:
XS GIS Cut Line= 3
        3531661.     10364912.11       3531487.4     10364460.76
      3531305.12     10363801.07
#Sta/Elev= 30
  4349.6  381.84  4489.4  372.79  4513.7  370.67  4532.6  368.82  4563.5  368.94
    4830  371.93  4944.1  372.58  4949.3  372.02  4956.4  370.98  4967.1  368.44
  4977.5  364.93  4980.6  362.09  4983.3  361.59  4986.6  362.09  4988.8  366.07
  4998.3  362.97  5008.6  363.14  5017.9  365.86  5029.4  367.56  5050.1  372.38
  5059.3   372.6  5081.3  372.87  5091.6  372.39  5143.5  373.16  5170.8  374.42
  5244.7  376.16  5249.9  375.33  5257.6  375.27    5357  380.94  5517.6  389.39
#Mann= 8 ,-1 , 0
  4349.6     .05       0  4513.7      .1       0  4563.5     .05       0
  4956.4     .12       0  4980.6     .07       0  4986.6     .12       0
  5059.3     .16       0    5357     .05       0
Bank Sta=4949.3,5050.1
XS Rating Curve= 0 ,0
Exp/Cntr=0.3,0.1

Type RM Length L Ch R = 1 ,64991   ,681,681,681
BEGIN DESCRIPTION:
CAMP CREEK 98.0
END DESCRIPTION:
XS GIS Cut Line= 3
      3531892.11     10364841.61      3531942.11     10364441.64
      3532129.63      10363836.2
#Sta/Elev= 30
  4624.1  382.86  4674.5  377.83  4742.5  372.74  4828.1  368.97  4865.9  366.06
  4886.1     369  4896.2  369.48  4956.6   371.1  4966.7  369.81  4984.3  361.01
  4986.4  360.75  4989.1  360.25  4992.4  360.75  5024.7  368.08  5037.6  368.71
  5043.5  369.83  5048.7  371.54  5058.6  371.99  5110.3  371.02  5179.1  371.09
  5184.4   371.7  5194.7  371.17  5205.1  371.71  5211.7  373.23    5217  371.91
  5226.1  373.63  5244.3  375.03  5330.8   376.1  5542.1  384.42    5661  389.74
#Mann= 5 ,-1 , 0
  4624.1      .1       0  4986.4     .07       0  4992.4      .1       0
  5110.3     .16       0  5542.1     .05       0
Bank Sta=4966.7,5043.5
XS Rating Curve= 0 ,0
Exp/Cntr=0.3,0.1

Type RM Length L Ch R = 1 ,64310   ,745,745,745
BEGIN DESCRIPTION:
CAMP CREEK 96.0
END DESCRIPTION:
XS GIS Cut Line= 3
       3532292.1     10365141.65      3532607.19     10364599.64
      3532592.11     10364041.69
#Sta/Elev= 30
  4575.5  393.73  4663.7   387.5  4706.7  386.65  4743.9  382.23  4765.4  381.32
  4772.1  379.75  4802.7  376.62    4883   370.4  4934.1   369.5  4963.3  369.97
    4979  368.35  4984.8   363.9  4997.5  359.41  5000.3  358.91  5003.5  359.41
  5006.3  362.38    5022  366.55  5027.8  369.15    5065   369.9  5188.6  366.59
  5258.2  367.04  5400.5   368.9  5450.5  371.01  5513.1  375.53  5530.6  376.96
  5575.6   383.8  5580.6  382.67  5640.6  385.67  5690.6  390.67  5760.6  399.53
#Mann= 5 ,-1 , 0
  4575.5     .16       0  4997.5     .07       0  5003.5     .16       0
  5258.2     .05       0  5513.1     .16       0
Bank Sta=4979,5027.8
XS Rating Curve= 0 ,0
Exp/Cntr=0.3,0.1

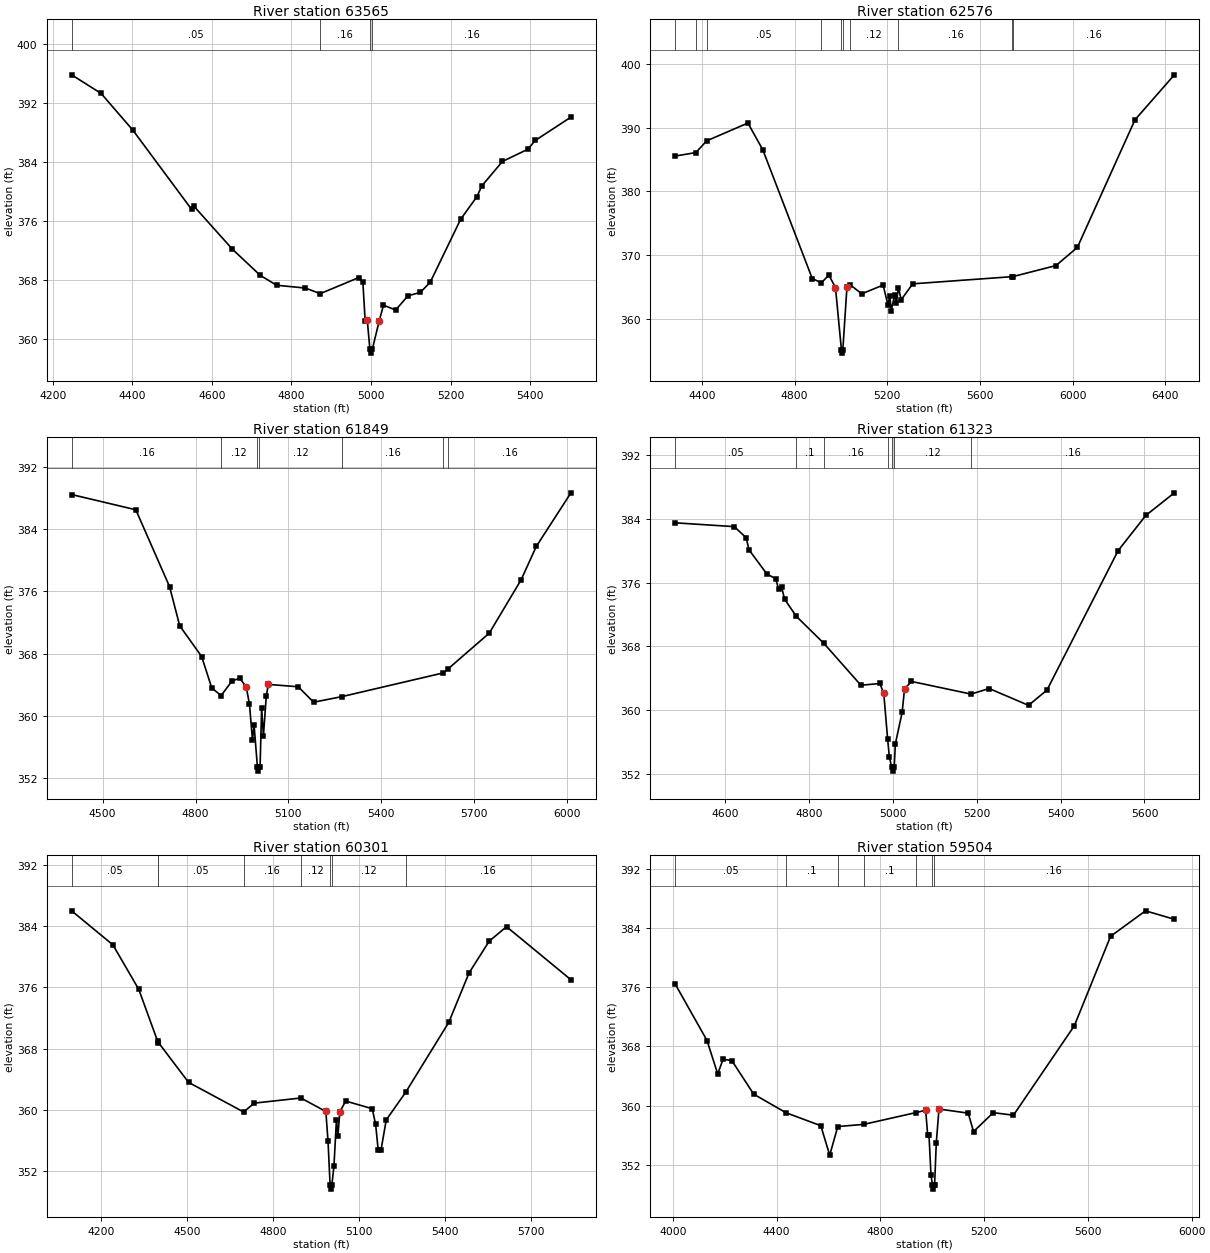
Type RM Length L Ch R = 1 ,63565   ,989,989,989
BEGIN DESCRIPTION:
CAMP CREEK 95.0
END DESCRIPTION:
XS GIS Cut Line= 3
      3532937.05     10365415.62      3532952.87     10364936.78
      3533144.92     10364184.82
#Sta/Elev= 30
  4247.5  395.87  4321.5  393.35  4401.6  388.35  4549.3   377.6  4554.3  378.08
  4651.7  372.21  4721.7  368.66  4762.9  367.32  4835.1  366.94  4872.5  366.18
  4969.3  368.36  4979.6  367.77  4985.5  362.43  4990.6  362.66  4997.3  358.61
    5000  358.11  5003.3  358.61  5020.9  362.52  5031.5  364.62    5062  363.96
  5093.1  365.89  5124.1  366.35  5148.9  367.72  5225.4  376.27  5266.3  379.34
  5278.9  380.81  5330.5  384.12    5394  385.76  5413.1  386.97  5502.7  390.13
#Mann= 4 ,-1 , 0
  4247.5     .05       0  4872.5     .16       0  4997.3     .07       0
  5003.3     .16       0
Bank Sta=4990.6,5020.9
XS Rating Curve= 0 ,0
Exp/Cntr=0.3,0.1

Type RM Length L Ch R = 1 ,62576   ,727,727,727
BEGIN DESCRIPTION:
CAMP CREEK 93.0
END DESCRIPTION:
XS GIS Cut Line= 3
      3533075.98     10365606.56      3533518.65     10365268.05
      3534542.09     10364041.66
#Sta/Elev= 30
  4283.8  385.56  4373.4  386.11  4420.6  387.96  4598.2  390.75  4662.6  386.54
  4875.9  366.33  4915.4  365.66  4947.5  366.88  4976.1  364.91  5001.8  355.12
  5004.5  354.62  5007.8  355.12  5025.6     365  5039.2  365.37  5089.4  363.93
  5181.8  365.31  5202.6  362.18  5210.4  363.63  5216.9  361.29  5231.2  363.79
    5239   362.5  5247.8  364.87  5259.9  363.01  5309.3   365.5  5739.6  366.63
  5741.9  366.64  5927.6  368.37    6020  371.23  6268.6  391.26  6438.4  398.32
#Mann= 10 ,-1 , 0
  4283.8     .05       0  4373.4      .1       0  4420.6     .05       0
  4915.4     .16       0  5001.8     .07       0  5007.8     .16       0
  5039.2     .12       0  5247.8     .16       0  5739.6     .05       0
  5741.9     .16       0
Bank Sta=4976.1,5025.6
XS Rating Curve= 0 ,0
Exp/Cntr=0.3,0.1

Type RM Length L Ch R = 1 ,61849   ,526,526,526
BEGIN DESCRIPTION:
CAMP CREEK 91.0
END DESCRIPTION:
XS GIS Cut Line= 3
      3534065.53     10365971.17      3534242.11     10365391.64
      3534733.93     10364512.84
#Sta/Elev= 30
  4399.7  388.48    4607  386.52    4716  376.63  4748.8  371.59  4819.7  367.63
  4852.5  363.57  4882.6  362.61  4918.2   364.5  4942.8  364.83  4963.7  363.73
  4974.2  361.48  4983.9  356.86  4989.1  358.81  4999.9  353.38  5002.7  352.88
  5005.9  353.38  5008.4  353.38  5013.5  361.01  5019.2  357.37  5028.5  362.55
  5035.2  364.04  5131.6  363.74  5181.4  361.75  5272.8  362.47  5600.1  365.52
  5614.9  366.01  5748.8  370.64  5851.6   377.5  5900.7   381.8  6012.6   388.7
#Mann= 7 ,-1 , 0
  4399.7     .16       0  4882.6     .12       0  4999.9     .07       0
  5005.9     .12       0  5272.8     .16       0  5600.1     .05       0
  5614.9     .16       0
Bank Sta=4963.7,5035.2
XS Rating Curve= 0 ,0
Exp/Cntr=0.3,0.1

Type RM Length L Ch R = 1 ,61323   ,1022,1022,1022
BEGIN DESCRIPTION:
CAMP CREEK 90.0
END DESCRIPTION:
XS GIS Cut Line= 3
      3534313.99     10366043.37      3534513.98     10365843.38
       3534942.1     10365041.65
#Sta/Elev= 30
  4479.6  383.49  4620.9  383.01  4649.2  381.63  4656.3  380.09  4698.7  377.08
  4719.9  376.47    4727  375.14    4734   375.4  4741.1  373.91  4768.9  371.77
  4834.7  368.38  4923.2  363.12  4968.5  363.34  4977.7  362.11  4986.9  356.43
  4991.1  354.14  4996.7  352.85  4999.4  352.35  5002.7  352.85  5005.4  355.76
  5021.6  359.71  5027.3  362.64  5043.6   363.6  5186.2  362.01  5229.2  362.71
  5323.3   360.6  5367.2  362.51  5537.1     380  5603.3  384.42  5671.3  387.25
#Mann= 7 ,-1 , 0
  4479.6     .05       0  4768.9      .1       0  4834.7     .16       0
  4986.9     .12       0  4996.7     .07       0  5002.7     .12       0
  5186.2     .16       0
Bank Sta=4977.7,5027.3
XS Rating Curve= 0 ,0
Exp/Cntr=0.3,0.1

Type RM Length L Ch R = 1 ,60301   ,797,797,797
BEGIN DESCRIPTION:
CAMP CREEK 88.0
END DESCRIPTION:
XS GIS Cut Line= 3
      3534992.11      10366641.6      3535296.62     10365363.86
      3535341.57     10364938.15
#Sta/Elev= 30
  4096.9  386.01  4240.8  381.57  4331.1  375.75  4396.5  369.02  4399.7  368.81
  4504.8  363.61  4696.5  359.75  4734.2   360.9  4896.5  361.57  4983.6  359.81
  4991.2  355.94  4998.5  350.17  5001.3  349.67  5004.5  350.17  5011.8  352.63
  5020.6  358.74  5025.7  356.59  5032.3  359.77  5052.9  361.17  5145.4  360.17
  5157.3  358.12    5166  354.84  5176.3  354.83  5194.3  358.71  5262.3  362.33
  5412.7  371.47    5483  377.89  5553.4  382.05  5613.8  383.94  5838.5  377.01
#Mann= 8 ,-1 , 0
  4096.9     .05       0  4396.5     .16       0  4399.7     .05       0
  4696.5     .16       0  4896.5     .12       0  4998.5     .07       0
  5004.5     .12       0  5262.3     .16       0
Bank Sta=4983.6,5032.3
XS Rating Curve= 0 ,0
Exp/Cntr=0.3,0.1

Type RM Length L Ch R = 1 ,59504   ,684,684,684
BEGIN DESCRIPTION:
CAMP CREEK 87.0
END DESCRIPTION:
XS GIS Cut Line= 3
      3535567.26     10366691.67      3535792.11     10365741.64
      3536001.29     10364816.68
#Sta/Elev= 30
  4008.7  376.46    4132   368.8  4173.2  364.28  4193.7  366.27  4227.4   366.1
  4311.9  361.56    4436  359.06  4570.6   357.3  4604.8  353.32    4636  357.19
  4735.9  357.48  4935.8  359.06  4974.7  359.39  4982.4  356.07  4987.5  356.07
  4995.2  350.66    5001  349.24  5003.7  348.74    5007  349.24  5009.1  349.29
  5015.7     355    5026  359.55  5138.6     359  5159.3  356.51  5235.2  359.06
  5313.1  358.72  5547.7  370.79  5687.5  382.87  5822.1  386.31  5933.3  385.17
#Mann= 7 ,-1 , 0
  4008.7     .05       0    4436      .1       0    4636     .16       0
  4735.9      .1       0  4935.8     .16       0    5001     .07       0
    5007     .16       0
Bank Sta=4974.7,5026
XS Rating Curve= 0 ,0
Exp/Cntr=0.3,0.1

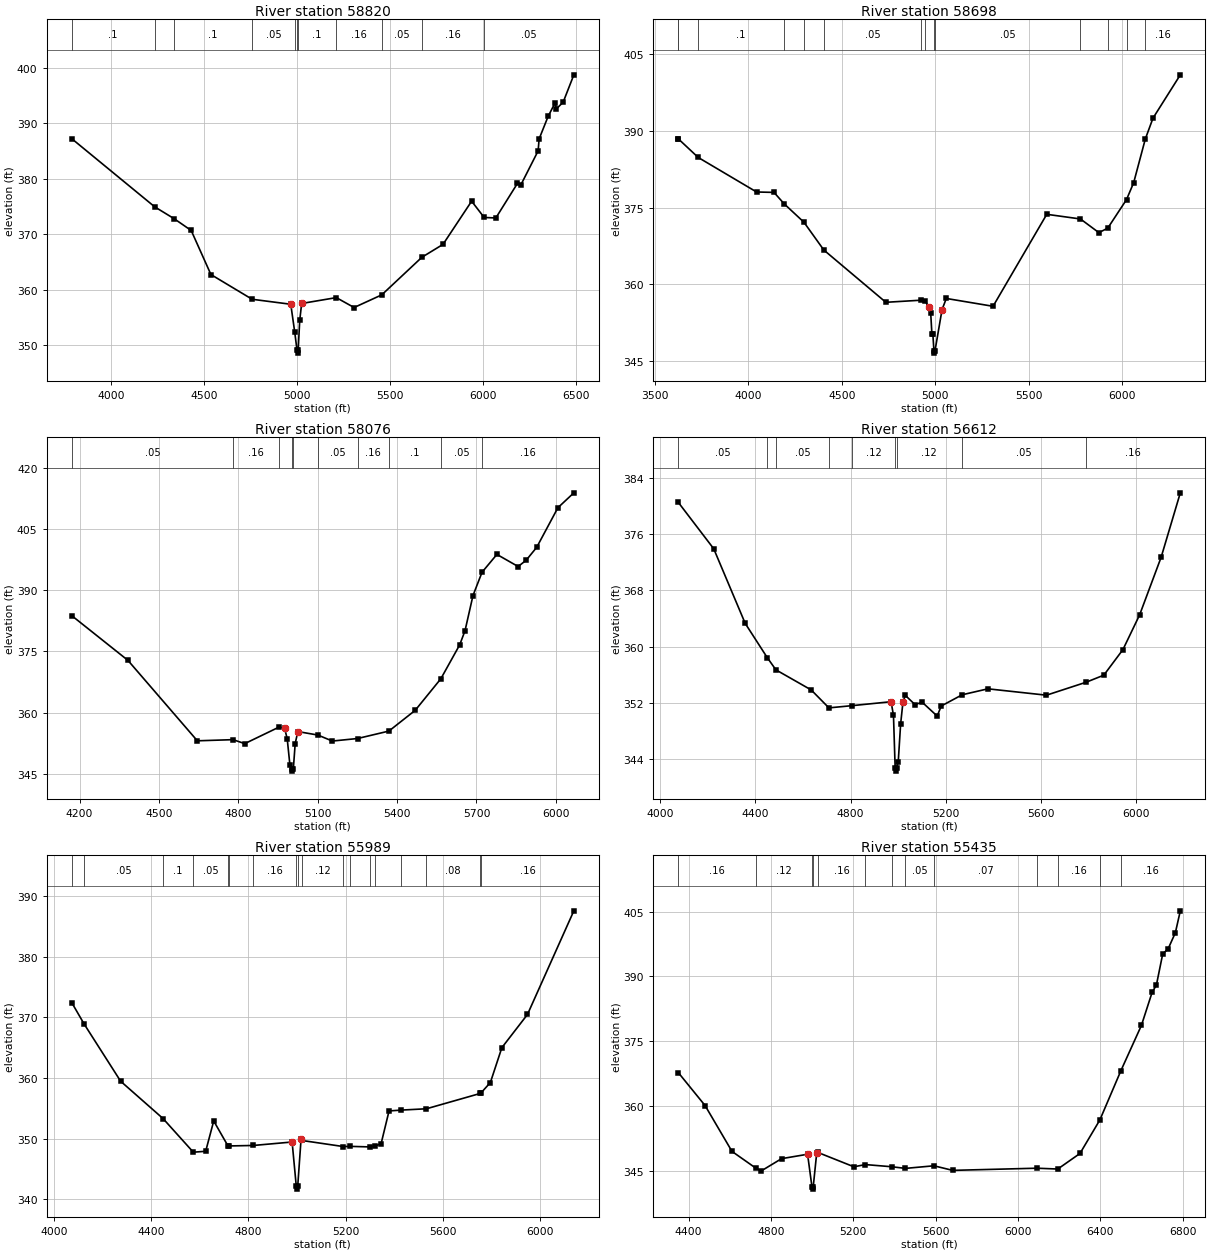
Type RM Length L Ch R = 1 ,58820   ,122,122,122
BEGIN DESCRIPTION:
CAMP CREEK 86.0
END DESCRIPTION:
XS GIS Cut Line= 4
      3535780.57     10367090.98      3536179.87     10366136.12
      3536058.34     10365632.65      3536308.11     10364515.65
#Sta/Elev= 30
  3789.8  387.25  4235.4  374.94  4340.1  372.79  4431.4  370.67  4537.4  362.71
  4758.9  358.24  4966.4  357.34  4987.7   352.3  5000.1  349.01  5002.8  348.51
  5006.1  349.01  5014.6  354.45  5024.9  357.48  5211.1  358.54  5306.6  356.75
  5455.4  359.04  5670.9  365.83  5784.4  368.16  5938.1  375.96  6005.5  373.02
  6068.2  372.93    6184  379.16  6203.6  378.97  6295.5  385.06  6300.6   387.2
  6349.1  391.28  6387.4  393.79  6392.6  392.61  6429.9  393.85  6487.3  398.79
#Mann= 11 ,-1 , 0
  3789.8      .1       0  4235.4     .05       0  4340.1      .1       0
  4758.9     .05       0  4987.7      .1       0  5000.1     .07       0
  5006.1      .1       0  5211.1     .16       0  5455.4     .05       0
  5670.9     .16       0  6005.5     .05       0
Bank Sta=4966.4,5024.9
XS Rating Curve= 0 ,0
Exp/Cntr=0.3,0.1

Type RM Length L Ch R = 1 ,58698   ,622,622,622
BEGIN DESCRIPTION:
Mapping XS c2307ce3
END DESCRIPTION:
XS GIS Cut Line= 4
      3535829.19     10367202.08      3536287.51      10366163.9
      3536200.71     10365535.43       3536426.4     10364650.03
#Sta/Elev= 30
  3626.1  388.41  3626.9  388.41  3732.7  384.79  4044.7  378.04  4137.9  377.96
  4192.4  375.72  4297.9  372.13  4404.2   366.7  4735.6  356.49  4923.3   356.9
  4944.8  356.78  4965.1  355.62  4975.2  354.42  4981.7  350.25  4986.8  350.24
  4992.4  347.06  4995.2  346.56  4998.4  347.06  5035.8  355.05  5058.6  357.24
  5308.4  355.71  5595.4  373.68  5775.5  372.77    5874   370.1  5921.4  370.98
  6021.7  376.56  6059.8  379.85    6122  388.38    6163  392.46  6309.1  400.93
#Mann= 14 ,-1 , 0
  3626.1      .1       0  3626.9     .05       0  3732.7      .1       0
  4192.4     .05       0  4297.9      .1       0  4404.2     .05       0
  4923.3     .16       0  4944.8     .05       0  4992.4     .04       0
  4998.4     .05       0  5775.5      .1       0  5921.4     .16       0
  6021.7      .1       0    6122     .16       0
Bank Sta=4965.1,5035.8
XS Rating Curve= 0 ,0
Exp/Cntr=0.3,0.1

Type RM Length L Ch R = 1 ,58076   ,1464,1464,1464
BEGIN DESCRIPTION:
CAMP CREEK 84.0
END DESCRIPTION:
XS GIS Cut Line= 3
      3537042.12     10366576.05      3536792.11     10366076.02
      3536892.11     10364741.62
#Sta/Elev= 30
  4170.7  383.75  4382.8  372.82  4645.2  353.13    4780  353.41  4824.4  352.44
  4952.8  356.45  4974.8  356.23  4984.8  353.63  4994.9  347.25  5001.9  346.21
  5004.7  345.71  5007.9  346.21  5014.9  352.44    5025  355.39  5100.7  354.54
  5155.3  353.07  5250.6  353.69    5369  355.51  5468.5  360.59  5565.3  368.31
  5636.7  376.63  5656.7  380.08  5686.8  388.68    5721  394.38  5777.1  398.74
  5857.3  395.78  5887.4  397.29  5927.5  400.47  6007.7  410.17  6067.9  413.81
#Mann= 10 ,-1 , 0
  4170.7     .05       0    4780     .16       0  4952.8     .12       0
  5001.9     .07       0  5007.9     .12       0  5100.7     .05       0
  5250.6     .16       0    5369      .1       0  5565.3     .05       0
    5721     .16       0
Bank Sta=4974.8,5025
XS Rating Curve= 0 ,0
Exp/Cntr=0.3,0.1

Type RM Length L Ch R = 1 ,56612   ,623,623,623
BEGIN DESCRIPTION:
CAMP CREEK 82.0
END DESCRIPTION:
XS GIS Cut Line= 3
       3537592.1     10366591.69      3537667.96      10365823.6
      3537792.11      10364491.6
#Sta/Elev= 30
  4075.8  380.59    4225  373.95  4357.2   363.3  4449.9  358.41  4486.2  356.67
  4634.5   353.8  4708.9  351.24  4807.1  351.56  4970.1  352.12  4980.2  350.16
  4987.2  342.71  4989.9  342.21  4993.2  342.71  5000.2  343.55  5010.3  348.96
  5020.3  352.15  5030.4  353.01  5070.5  351.71  5100.7  352.05  5163.8  350.07
    5181  351.51  5268.8  353.11    5377  353.96  5622.9  353.05  5789.6   354.9
    5864  355.91  5944.3  359.56  6014.6  364.53    6105  372.76  6185.4  381.94
#Mann= 9 ,-1 , 0
  4075.8     .05       0  4449.9      .1       0  4486.2     .05       0
  4708.9      .1       0  4807.1     .12       0  4987.2     .07       0
  4993.2     .12       0  5268.8     .05       0  5789.6     .16       0
Bank Sta=4970.1,5020.3
XS Rating Curve= 0 ,0
Exp/Cntr=0.3,0.1

Type RM Length L Ch R = 1 ,55989   ,554,554,554
BEGIN DESCRIPTION:
CAMP CREEK 81.0
END DESCRIPTION:
XS GIS Cut Line= 3
      3538327.67      10366431.2      3538171.43     10365215.96
       3537842.1     10364441.63
#Sta/Elev= 30
  4072.6  372.43  4123.1  368.93  4273.8  359.47  4448.2  353.32    4573  347.77
  4623.8  347.92  4656.9  352.92  4714.9  348.85  4720.4   348.8  4819.9  348.88
  4979.6  349.45  4996.7  342.18  4999.5  341.68  5002.7  342.18  5016.5  349.96
  5018.9  349.71  5190.5   348.7  5217.9  348.73  5301.6  348.64  5319.2  348.73
    5346  349.19  5378.6  354.57  5427.7  354.71  5532.5  354.93  5753.3  357.45
  5758.2  357.59  5795.7  359.26    5843  365.01  5948.4  370.48  6139.3  387.57
#Mann= 18 ,-1 , 0
  4072.6     .16       0  4123.1     .05       0  4448.2      .1       0
    4573     .05       0  4714.9     .16       0  4720.4     .05       0
  4819.9     .16       0  4996.7     .07       0  5002.7     .16       0
  5018.9     .12       0  5190.5     .16       0  5217.9     .12       0
  5301.6     .05       0  5319.2     .08       0  5427.7     .15       0
  5532.5     .08       0  5753.3     .15       0  5758.2     .16       0
Bank Sta=4979.6,5016.5
XS Rating Curve= 0 ,0
Exp/Cntr=0.3,0.1

Type RM Length L Ch R = 1 ,55435   ,787,787,787
BEGIN DESCRIPTION:
CAMP CREEK 80.0
END DESCRIPTION:
XS GIS Cut Line= 3
      3538792.11     10366141.67      3538700.94     10365103.12
       3538362.4     10363748.94
#Sta/Elev= 30
  4349.8  367.76  4480.3  360.11  4610.8  349.51  4727.1  345.62  4753.2     345
  4851.7  347.83    4978  348.85  4999.3  341.28  5002.1  340.78  5005.3  341.28
  5022.4  349.17  5026.8  349.29  5202.8  345.95  5259.2  346.46  5385.8  345.96
  5453.4  345.58  5591.6  346.18  5682.5  345.12  6090.9  345.62  6193.1  345.43
  6300.9  349.03  6397.5  356.79  6499.8   368.2  6599.3  378.66  6651.4  386.33
    6672  387.98    6703  395.26  6728.1  396.28  6764.2  400.11  6788.2  405.17
#Mann= 13 ,-1 , 0
  4349.8     .16       0  4727.1     .12       0  4999.3     .07       0
  5005.3     .12       0  5026.8     .16       0  5259.2     .05       0
  5385.8     .07       0  5453.4     .05       0  5591.6     .07       0
  6090.9     .12       0  6193.1     .16       0  6397.5     .12       0
  6499.8     .16       0
Bank Sta=4978,5022.4
XS Rating Curve= 0 ,0
Exp/Cntr=0.3,0.1