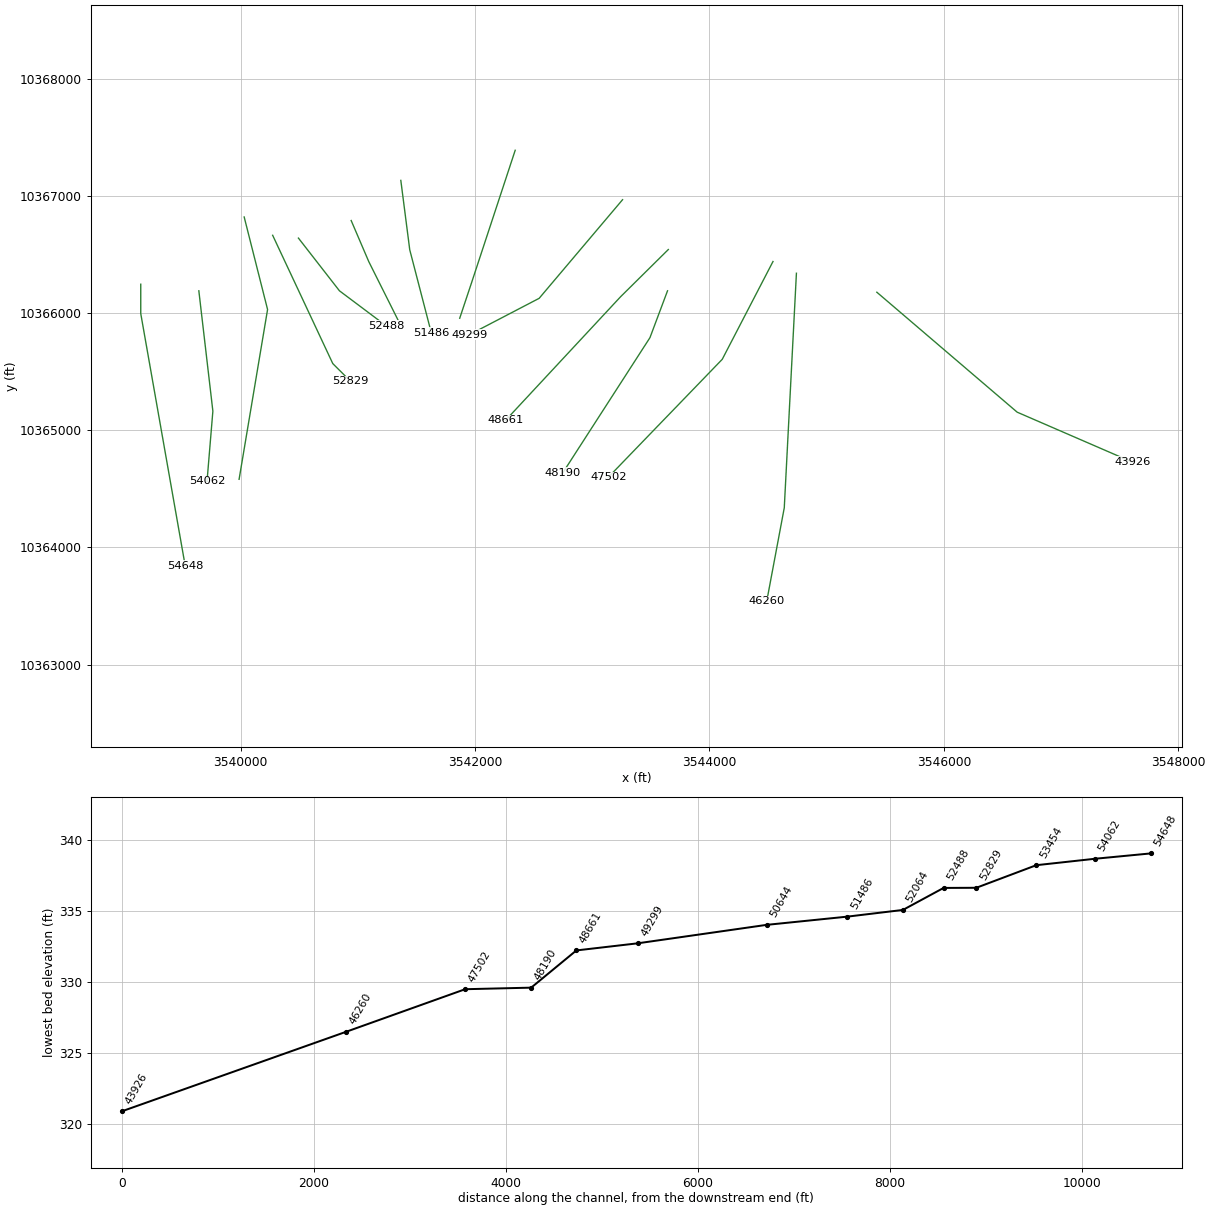
HEC-RAS study CAMP CREEK.prj: CAMP CREEK Base Level Engineering

--- CAMP CREEK.g01 (geometry) --- (continued)

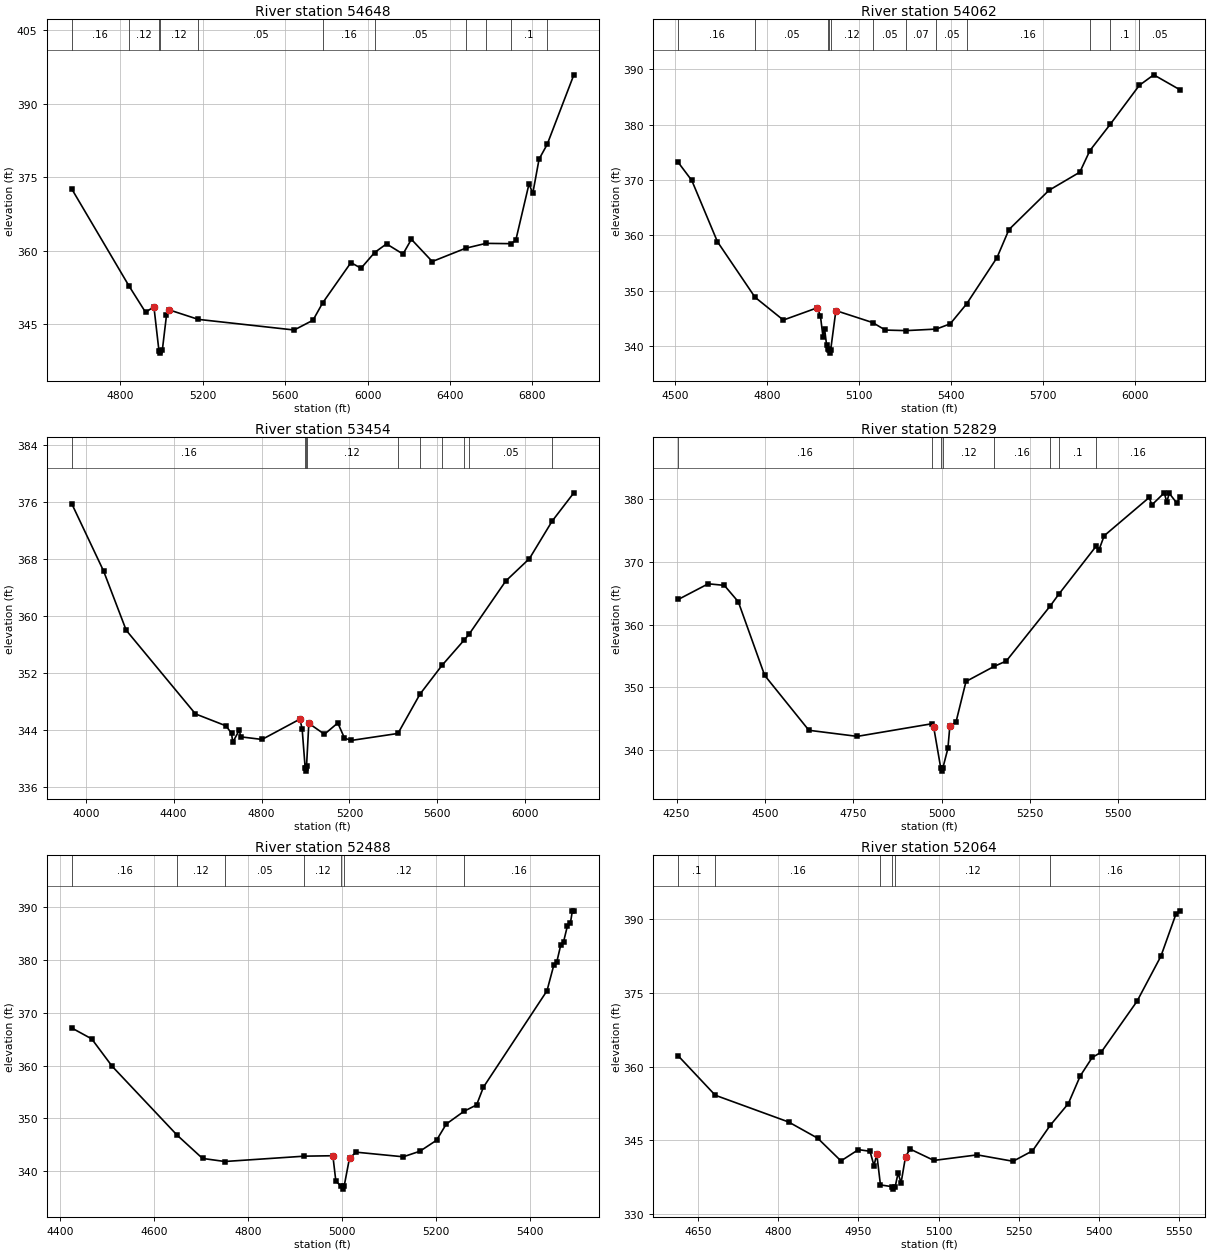
Type RM Length L Ch R = 1 ,54648   ,586,586,586
BEGIN DESCRIPTION:
CAMP CREEK 78.0
END DESCRIPTION:
XS GIS Cut Line= 3
      3539146.27      10366247.9      3539146.27     10365997.89
       3539525.4     10363845.54
#Sta/Elev= 30
  4565.2  372.59  4842.4  352.82  4923.1  347.42  4963.7  348.54    4988  339.58
  4990.8  339.08    4994  339.58  5004.3  339.62  5024.6  346.79  5034.8  347.95
  5178.9  345.97    5644   343.8  5735.4   345.8  5782.3  349.34  5919.3  357.56
  5968.4  356.41  6034.2  359.62    6092  361.38    6172  359.31  6212.6  362.32
  6313.9  357.78  6475.4  360.49  6574.4  361.49  6694.6  361.43  6718.8  362.08
  6783.1  373.61  6801.6  371.72    6832  378.68  6871.4   381.7  7000.7   395.9
#Mann= 11 ,-1 , 0
  4565.2     .16       0  4842.4     .12       0    4988     .07       0
    4994     .12       0  5178.9     .05       0  5782.3     .16       0
  6034.2     .05       0  6475.4      .1       0  6574.4     .15       0
  6694.6      .1       0  6871.4     .16       0
Bank Sta=4963.7,5034.8
XS Rating Curve= 0 ,0
Exp/Cntr=0.3,0.1

Type RM Length L Ch R = 1 ,54062   ,608,608,608
BEGIN DESCRIPTION:
CAMP CREEK 76.0
END DESCRIPTION:
XS GIS Cut Line= 3
      3539642.11      10366191.6       3539761.9     10365164.21
        3539712.     10364565.44
#Sta/Elev= 30
  4511.4  373.18  4555.6  369.92    4639  358.85  4761.5   348.8  4853.7  344.68
  4964.4   346.9  4974.5  345.42  4982.9  341.64  4987.9  343.14  4994.6  340.15
  4999.6  339.48  5001.7   339.2  5004.4   338.7  5007.7   339.2  5024.8  346.39
  5144.4  344.23  5185.9  342.87  5253.5  342.77  5351.9  343.05  5397.3     344
  5450.3  347.58  5549.5  355.96  5588.5  361.04  5718.9  368.14  5819.3  371.42
  5852.2  375.33  5918.5  380.08  6013.3  387.13  6060.1  389.02  6146.6  386.28
#Mann= 12 ,-1 , 0
  4511.4     .16       0  4761.5     .05       0  4999.6     .12       0
  5001.7     .07       0  5007.7     .12       0  5144.4     .05       0
  5253.5     .07       0  5351.9     .05       0  5450.3     .16       0
  5852.2     .05       0  5918.5      .1       0  6013.3     .05       0
Bank Sta=4964.4,5024.8
XS Rating Curve= 0 ,0
Exp/Cntr=0.3,0.1

Type RM Length L Ch R = 1 ,53454   ,625,625,625
BEGIN DESCRIPTION:
CAMP CREEK 75.0
END DESCRIPTION:
XS GIS Cut Line= 3
      3540029.07     10366821.85      3540228.72     10366031.94
      3539985.67     10364582.32
#Sta/Elev= 30
  3936.4  375.73    4081  366.31  4184.2  357.99  4499.2  346.27    4638   344.6
  4663.4  343.55  4668.9  342.29  4699.2  344.03  4704.4  343.06  4802.1  342.69
  4974.5  345.54  4984.7  344.16  4998.3  338.75  5001.1  338.25  5004.3  338.75
  5004.6  338.92  5015.1  344.95  5086.1  343.42  5146.9     345  5177.3  342.88
  5207.7  342.55  5420.6  343.53  5520.8  349.04    5621  353.07  5721.2   356.6
  5743.6  357.41  5911.2   364.9  6018.9  368.04  6122.1  373.29    6221  377.26
#Mann= 10 ,-1 , 0
  3936.4     .16       0  4998.3     .07       0  5004.3     .16       0
  5004.6     .12       0  5420.6     .05       0  5520.8      .1       0
    5621     .05       0  5721.2     .16       0  5743.6     .05       0
  6122.1      .1       0
Bank Sta=4974.5,5015.1
XS Rating Curve= 0 ,0
Exp/Cntr=0.3,0.1

Type RM Length L Ch R = 1 ,52829   ,341,341,341
BEGIN DESCRIPTION:
CAMP CREEK 74.0
END DESCRIPTION:
XS GIS Cut Line= 3
      3540272.11     10366665.64      3540785.16     10365570.46
      3540935.14     10365420.48
#Sta/Elev= 30
  4254.6  364.02  4339.5  366.52  4385.1  366.27  4424.7  363.65  4499.3  351.92
  4624.5  343.17  4761.4   342.2  4973.6  344.22  4977.9  343.66  4997.8  337.16
  5000.5  336.66  5003.8  337.16  5018.1  340.28  5023.6  343.84  5040.9  344.46
  5069.3  350.95  5148.8  353.35  5183.4  354.21    5308     363  5331.5  364.82
    5438  372.53  5445.6   371.9  5460.6  374.18  5588.3  380.29  5595.3  379.08
  5630.7  381.02  5637.8  379.54  5644.8  380.95  5666.1  379.39  5676.1   380.4
#Mann= 8 ,-1 , 0
  4254.6     .16       0  4973.6     .12       0  4997.8     .07       0
  5003.8     .12       0  5148.8     .16       0    5308     .05       0
  5331.5      .1       0    5438     .16       0
Bank Sta=4977.9,5023.6
XS Rating Curve= 0 ,0
Exp/Cntr=0.3,0.1

Type RM Length L Ch R = 1 ,52488   ,424,424,424
BEGIN DESCRIPTION:
CAMP CREEK 73.0
END DESCRIPTION:
XS GIS Cut Line= 3
       3540492.1     10366641.64      3540842.11     10366191.64
      3541242.11     10365891.64
#Sta/Elev= 30
  4424.4   367.1  4466.9  365.04  4510.4  359.87  4648.8  346.86  4703.1  342.45
  4750.7  341.87  4920.2  342.88  4980.9  342.96  4987.2  338.19  4998.8  337.15
  5001.5  336.65  5004.8  337.15  5016.4  342.54  5030.9  343.63  5130.9  342.76
  5166.4  343.81  5201.8  345.88  5222.6  348.95  5260.4  351.36  5287.2  352.56
  5301.8  355.92  5437.2  374.12  5451.8  378.98    5458  379.52  5466.4  382.71
  5472.6   383.4  5480.9  386.43  5487.2  386.96  5491.4  389.24  5494.5  389.24
#Mann= 7 ,-1 , 0
  4424.4     .16       0  4648.8     .12       0  4750.7     .05       0
  4920.2     .12       0  4998.8     .07       0  5004.8     .12       0
  5260.4     .16       0
Bank Sta=4980.9,5016.4
XS Rating Curve= 0 ,0
Exp/Cntr=0.3,0.1

Type RM Length L Ch R = 1 ,52064   ,578,578,578
BEGIN DESCRIPTION:
CAMP CREEK 72.0
END DESCRIPTION:
XS GIS Cut Line= 3
      3540942.11     10366791.63      3541092.11     10366441.64
      3541342.11     10365941.64
#Sta/Elev= 30
  4612.7  362.22    4682  354.21  4819.4  348.76  4873.8  345.46  4917.3  340.84
    4950  343.14  4971.7   342.8    4979   339.9  4984.4  342.16  4991.2  335.96
  5012.8   335.6  5015.6   335.1  5018.8   335.6  5024.2  338.37  5029.8  336.37
  5038.2  341.71  5046.6  343.26  5091.3  340.94  5172.4  342.07  5239.4  340.77
  5275.8  342.89  5308.9  348.07  5342.9  352.51  5365.2  358.14  5387.6  361.89
  5404.4  362.97  5471.4  373.32  5516.2  382.51  5544.1  391.01  5552.5  391.74
#Mann= 6 ,-1 , 0
  4612.7      .1       0    4682     .16       0  4991.2     .12       0
  5012.8     .07       0  5018.8     .12       0  5308.9     .16       0
Bank Sta=4984.4,5038.2
XS Rating Curve= 0 ,0
Exp/Cntr=0.3,0.1

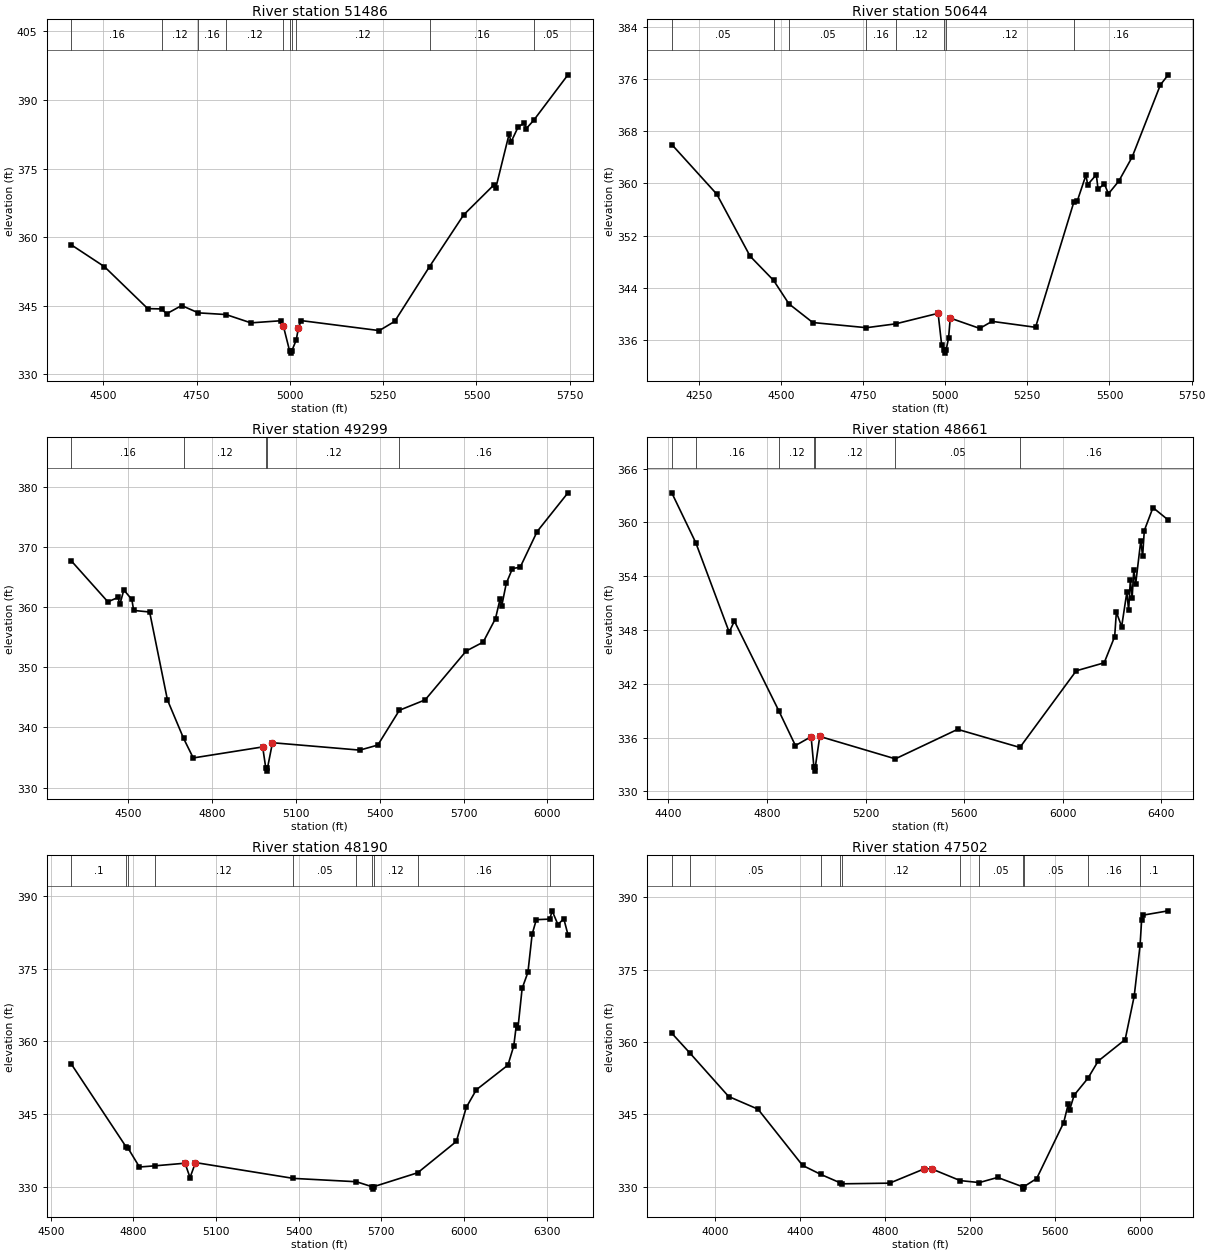
Type RM Length L Ch R = 1 ,51486   ,842,842,842
BEGIN DESCRIPTION:
CAMP CREEK 71.0
END DESCRIPTION:
XS GIS Cut Line= 3
      3541365.87     10367134.39      3541442.11     10366541.64
      3541626.29     10365832.29
#Sta/Elev= 30
  4414.6  358.29  4502.9  353.54    4619  344.36    4656   344.3  4669.4  343.23
  4709.8  345.04  4754.5  343.44  4828.7  343.07  4895.5  341.25    4975  341.71
  4982.6   340.5  4999.1  335.13  5001.9  334.63  5005.1  335.13    5017  337.53
  5022.6  340.07  5029.9  341.75  5239.5  339.56  5280.8  341.58  5374.1  353.55
  5465.7  364.88  5546.9  371.45    5552  370.84  5587.4  382.54  5592.6  380.82
  5611.5  384.08    5628  385.01  5633.1  383.72  5653.1  385.54  5745.1  395.51
#Mann= 10 ,-1 , 0
  4414.6     .16       0    4656     .12       0  4754.5     .16       0
  4828.7     .12       0  4982.6     .16       0  4999.1     .07       0
  5005.1     .16       0    5017     .12       0  5374.1     .16       0
  5653.1     .05       0
Bank Sta=4982.6,5022.6
XS Rating Curve= 0 ,0
Exp/Cntr=0.3,0.1

Type RM Length L Ch R = 1 ,50644   ,1345,1345,1345
BEGIN DESCRIPTION:
CAMP CREEK 69.0
END DESCRIPTION:
XS GIS Cut Line= 3
       3542342.1     10367391.64      3541968.49     10366257.27
      3541868.51      10365957.3
#Sta/Elev= 30
  4168.2  365.96  4305.1  358.37  4406.5  348.88  4478.1  345.17  4524.6  341.59
  4597.2  338.73  4760.6  337.94  4849.5  338.53  4978.5  340.14  4989.4  335.28
  4996.9  334.55  4999.7  334.05  5002.9  334.55  5010.3  336.33  5015.5  339.41
  5105.2  337.83  5142.6  338.91    5275     338  5391.3  357.12  5401.9  357.31
  5428.3  361.27  5433.6  359.82  5459.9  361.34  5465.2  359.12  5484.4  359.94
  5496.8  358.42  5528.4  360.37  5568.7  364.02  5654.9  375.09  5678.7  376.62
#Mann= 8 ,-1 , 0
  4168.2     .05       0  4478.1     .16       0  4524.6     .05       0
  4760.6     .16       0  4849.5     .12       0  4996.9     .07       0
  5002.9     .12       0  5391.3     .16       0
Bank Sta=4978.5,5015.5
XS Rating Curve= 0 ,0
Exp/Cntr=0.3,0.1

Type RM Length L Ch R = 1 ,49299   ,638,638,638
BEGIN DESCRIPTION:
CAMP CREEK 68.0
END DESCRIPTION:
XS GIS Cut Line= 3
      3543258.25     10366969.45      3542546.43     10366127.42
      3541949.13     10365815.79
#Sta/Elev= 30
  4296.9  367.65  4427.1  360.88  4463.4  361.61  4469.9  360.44  4484.2  362.85
  4512.8  361.27  4519.4  359.45  4576.5  359.19  4640.2  344.58  4698.1  338.18
  4732.5  334.94  4980.9  336.77  4992.1  333.25  4994.9  332.75  4998.1  333.25
    5016  337.47  5328.5  336.24  5392.9  337.08    5470  342.86  5562.3  344.59
  5709.2  352.71  5769.8  354.18    5814   358.1  5830.4  361.36  5836.1  360.15
  5852.5  363.94  5874.6  366.41  5902.3  366.62    5963  372.56  6073.2  378.99
#Mann= 5 ,-1 , 0
  4296.9     .16       0  4698.1     .12       0  4992.1     .07       0
  4998.1     .12       0    5470     .16       0
Bank Sta=4980.9,5016
XS Rating Curve= 0 ,0
Exp/Cntr=0.3,0.1

Type RM Length L Ch R = 1 ,48661   ,471,471,471
BEGIN DESCRIPTION:
CAMP CREEK 67.0
END DESCRIPTION:
XS GIS Cut Line= 3
      3543648.85     10366544.08      3543242.11     10366141.64
       3542260.4     10365086.22
#Sta/Elev= 30
  4413.9  363.29  4511.2  357.73  4646.7  347.76  4667.9  348.98  4848.7  338.94
  4915.4   335.1    4979  336.09  4990.2  332.75  4992.9  332.25  4996.2  332.75
  5014.2  336.12  5320.7  333.62  5573.3  336.91  5825.8  334.89  6054.4  343.44
  6167.7  344.33  6210.3  347.26  6217.1  349.98  6238.6  348.37  6259.6  352.19
  6266.9  350.19  6273.8  353.56  6281.1   351.6  6287.9  354.72  6295.3   353.1
  6316.3  357.97  6323.6  356.19  6330.4  359.08  6365.6  361.64  6427.5  360.26
#Mann= 7 ,-1 , 0
  4413.9     .05       0  4511.2     .16       0  4848.7     .12       0
  4990.2     .07       0  4996.2     .12       0  5320.7     .05       0
  5825.8     .16       0
Bank Sta=4979,5014.2
XS Rating Curve= 0 ,0
Exp/Cntr=0.3,0.1

Type RM Length L Ch R = 1 ,48190   ,688,688,688
BEGIN DESCRIPTION:
CAMP CREEK 66.0
END DESCRIPTION:
XS GIS Cut Line= 3
      3543642.12     10366191.69      3543492.11     10365791.64
      3542747.35     10364636.34
#Sta/Elev= 30
  4575.3   355.3  4773.5  338.32  4781.1     338  4821.9  334.18  4879.4  334.43
  4987.4  334.96  5005.5     332  5025.3  335.09  5380.4  331.84  5609.4  331.15
  5665.8  330.13  5668.6  329.63  5671.8  330.13  5831.9     333  5971.9  339.43
  6008.2  346.45  6044.5  350.06  6159.3  355.14  6180.5   359.1  6189.7  363.33
  6195.6  362.74  6210.8   370.9  6231.9  374.24  6247.1  382.04  6262.3  385.05
  6311.4  385.17  6319.7  386.87  6340.8  384.05    6362  385.25  6377.1  381.97
#Mann= 10 ,-1 , 0
  4575.3      .1       0  4773.5     .16       0  4781.1      .1       0
  4879.4     .12       0  5380.4     .05       0  5609.4     .12       0
  5665.8     .07       0  5671.8     .12       0  5831.9     .16       0
  6311.4     .15       0
Bank Sta=4987.4,5025.3
XS Rating Curve= 0 ,0
Exp/Cntr=0.3,0.1

Type RM Length L Ch R = 1 ,47502   ,1242,1242,1242
BEGIN DESCRIPTION:
CAMP CREEK 64.0
END DESCRIPTION:
XS GIS Cut Line= 3
      3544542.12     10366441.68      3544108.93     10365606.59
      3543136.89     10364599.83
#Sta/Elev= 30
  3794.1  361.84  3880.1   357.7  4062.2  348.72  4200.6  346.09  4410.6  334.44
  4496.2  332.58  4589.2   330.8  4597.8  330.62    4821  330.76  4983.6  333.71
  5019.1  333.72  5153.6  331.29  5243.7  330.88  5330.1  331.94  5447.5  330.02
  5450.3  329.52  5453.5  330.02  5514.1  331.71  5641.4   343.3  5662.5  347.07
  5669.7  345.98  5690.8     349  5755.6  352.49    5804  356.06  5931.3  360.53
  5973.8   369.5  6001.5  380.05    6009  385.36  6016.2  386.32  6134.3  387.21
#Mann= 11 ,-1 , 0
  3794.1     .16       0  3880.1     .05       0  4496.2     .12       0
  4589.2     .05       0  4597.8     .12       0  5153.6     .07       0
  5243.7     .05       0  5447.5     .07       0  5453.5     .05       0
  5755.6     .16       0  6001.5      .1       0
Bank Sta=4983.6,5019.1
XS Rating Curve= 0 ,0
Exp/Cntr=0.3,0.1

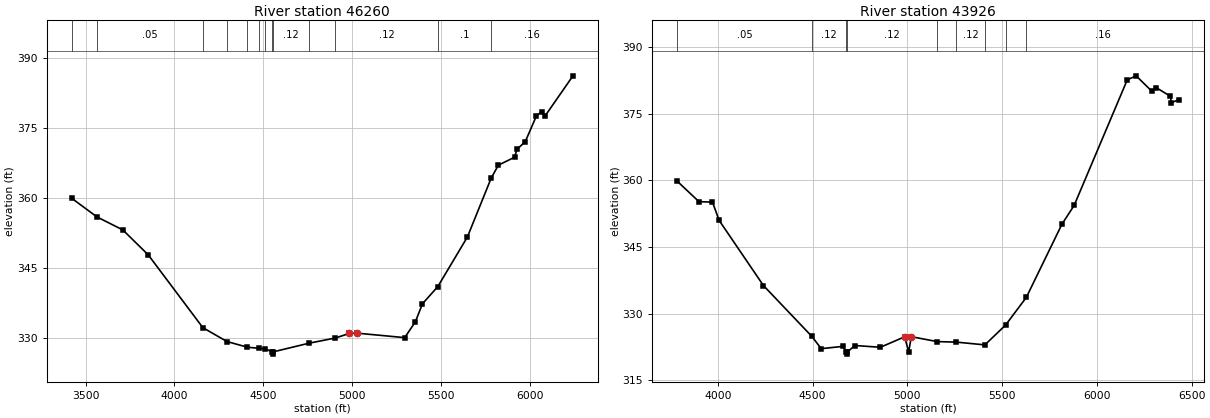
Type RM Length L Ch R = 1 ,46260   ,2334,2334,2334
BEGIN DESCRIPTION:
CAMP CREEK 62.0
END DESCRIPTION:
XS GIS Cut Line= 3
       3544742.1     10366341.62      3544638.44     10364339.23
      3544488.45     10363539.24
#Sta/Elev= 30
  3422.2  359.97    3564  355.97  3709.9  353.17  3852.8  347.81  4159.5  332.21
  4294.8  329.23  4410.4     328  4475.7  327.77  4509.2  327.65  4550.7  327.02
  4553.4  326.52  4556.7  327.02  4754.9  328.85  4904.7  329.98  4984.3  330.97
  5024.3  331.03  5294.7  330.06  5354.8  333.45  5394.8  337.33  5481.2  341.02
  5647.6  351.67  5781.2  364.29  5821.6  367.07  5913.2  368.79  5925.7  370.45
  5973.1  372.13  6035.9  377.67  6065.8  378.57  6083.4  377.58  6241.2  386.25
#Mann= 13 ,-1 , 0
  3422.2     .16       0    3564     .05       0  4159.5     .07       0
  4294.8     .05       0  4410.4     .12       0  4475.7     .05       0
  4509.2     .12       0  4550.7     .07       0  4556.7     .12       0
  4754.9     .07       0  4904.7     .12       0  5481.2      .1       0
  5781.2     .16       0
Bank Sta=4984.3,5024.3
XS Rating Curve= 0 ,0
Exp/Cntr=0.3,0.1

Type RM Length L Ch R = 1 ,43926   ,1132,1132,1132
BEGIN DESCRIPTION:
CAMP CREEK 61.0
END DESCRIPTION:
XS GIS Cut Line= 3
      3545428.36     10366179.52      3546626.29      10365155.2
      3547607.18     10364729.86
#Sta/Elev= 30
  3785.4  359.82  3899.9  355.23  3971.2  355.13  4006.3  351.02  4240.2  336.36
  4494.1  324.99  4545.3  322.16  4658.7  322.67  4677.4  321.43  4680.1  320.93
  4683.4  321.43  4723.2  322.87  4857.1  322.47  4985.6  324.83  5006.4  321.43
  5020.7  324.85  5157.1  323.75  5258.7  323.63  5408.8  323.01  5518.4  327.48
  5627.7  333.71  5815.3  350.14  5880.2  354.41  6160.2  382.63  6207.1  383.54
  6288.4  380.14  6311.9  380.91  6387.8  378.95  6393.2  377.52  6430.7  378.13
#Mann= 9 ,-1 , 0
  3785.4     .05       0  4494.1     .12       0  4677.4     .07       0
  4683.4     .12       0  5157.1     .16       0  5258.7     .12       0
  5408.8     .16       0  5518.4      .1       0  5627.7     .16       0
Bank Sta=4985.6,5020.7
XS Rating Curve= 0 ,0
Exp/Cntr=0.3,0.1