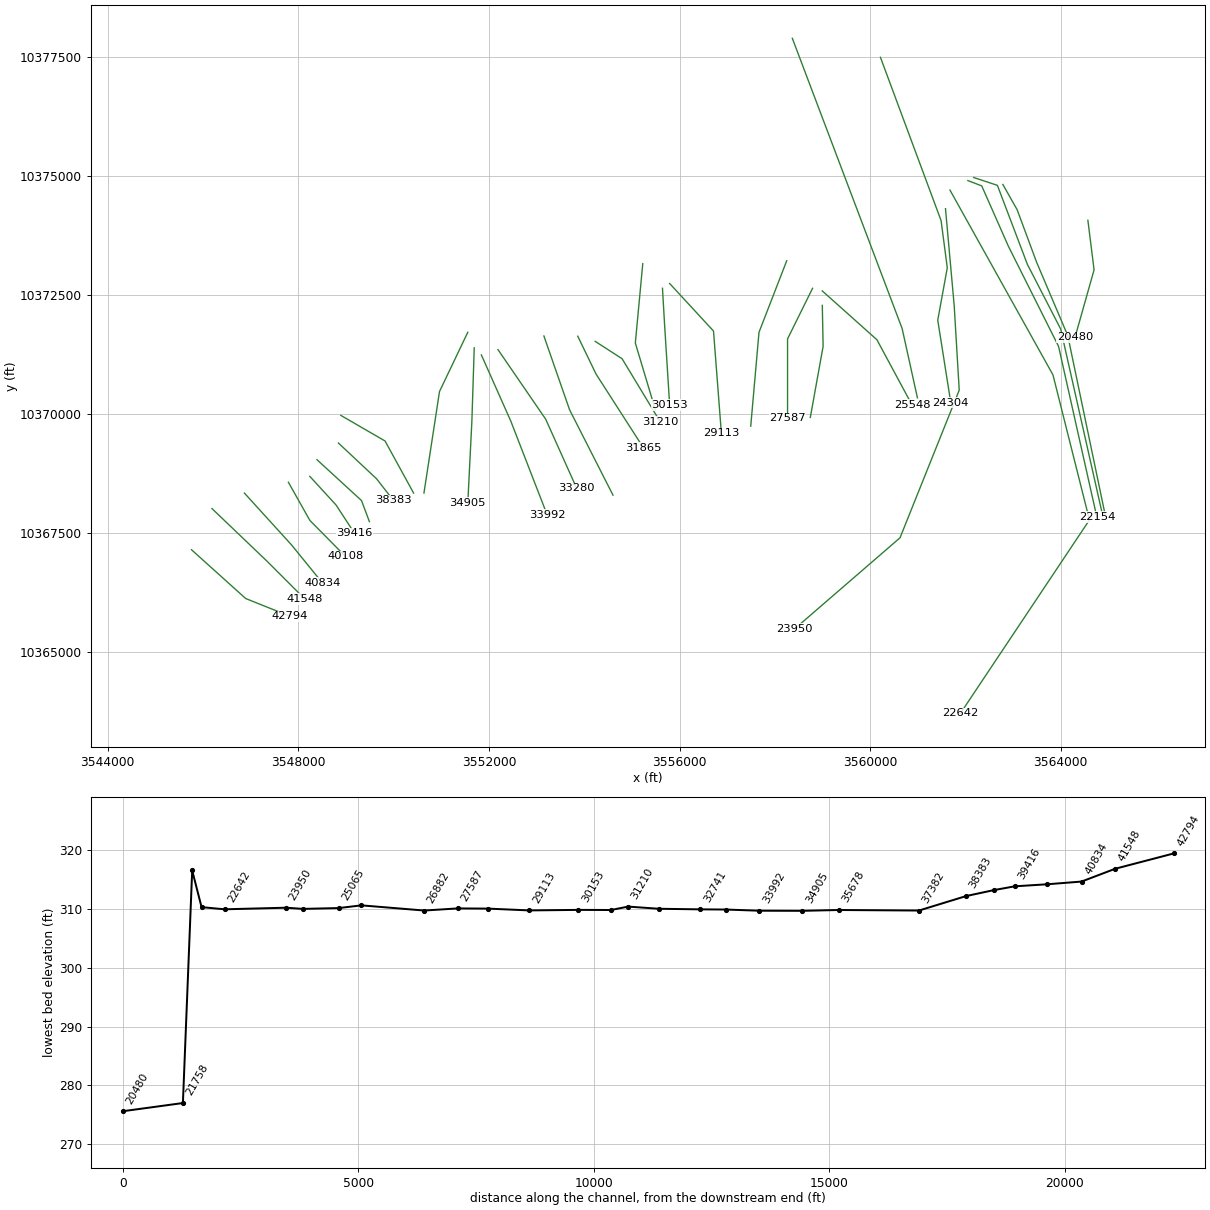
HEC-RAS study CAMP CREEK.prj: CAMP CREEK Base Level Engineering

--- CAMP CREEK.g01 (geometry) --- (continued)

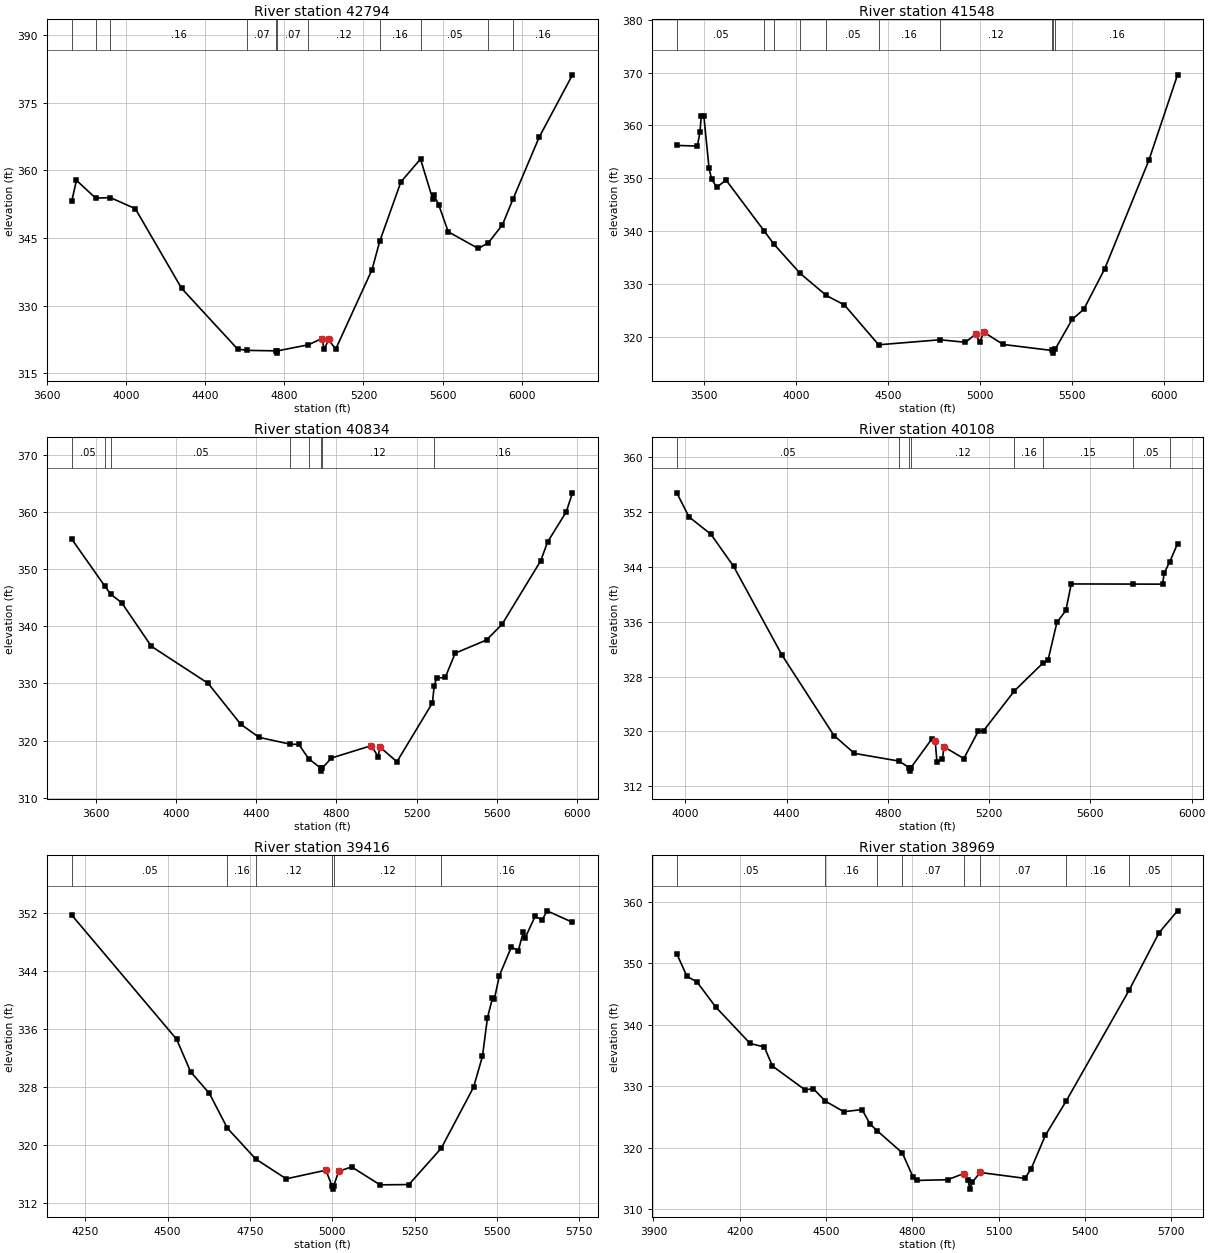
Type RM Length L Ch R = 1 ,42794   ,1246,1246,1246
BEGIN DESCRIPTION:
CAMP CREEK 60.0
END DESCRIPTION:
XS GIS Cut Line= 3
      3545758.22     10367151.75      3546895.39     10366127.42
       3547824.2     10365754.16
#Sta/Elev= 30
  3725.4  353.16  3749.4  357.81  3846.4  353.87  3921.1  353.97  4046.9  351.53
  4280.8  333.86    4564  320.38  4613.7  320.09  4759.1  319.98  4761.9  319.48
  4765.1  319.98  4922.2  321.33  4988.6   322.7  5002.8  320.38  5023.7  322.52
  5059.6  320.34  5243.4  337.99  5282.3  344.26  5389.6  357.47  5488.6  362.54
  5550.9  353.57  5556.2  354.58  5580.4  352.42  5628.8   346.4  5780.4   342.7
  5831.4  343.94    5903  347.97  5956.4  353.68  6088.5  367.39  6256.9  381.22
#Mann= 11 ,-1 , 0
  3725.4     .16       0  3846.4      .1       0  3921.1     .16       0
  4613.7     .07       0  4759.1     .07       0  4765.1     .07       0
  4922.2     .12       0  5282.3     .16       0  5488.6     .05       0
  5831.4      .1       0  5956.4     .16       0
Bank Sta=4988.6,5023.7
XS Rating Curve= 0 ,0
Exp/Cntr=0.3,0.1

Type RM Length L Ch R = 1 ,41548   ,714,714,714
BEGIN DESCRIPTION:
CAMP CREEK 59.0
END DESCRIPTION:
XS GIS Cut Line= 3
      3546188.26     10368015.97      3547338.29     10366915.95
      3548137.37     10366116.86
#Sta/Elev= 30
  3350.5  356.22  3462.4  356.09  3476.6  358.73  3483.5  361.75  3497.7  361.82
    3526   351.9  3540.1  349.81  3568.4  348.29  3618.1  349.67  3826.6  339.96
  3879.2  337.49  4021.3  331.97  4163.4  327.79  4261.6     326  4447.5  318.45
  4781.5   319.4  4919.5  318.92  4975.9  320.51  4997.2  318.89  5018.4  320.86
  5124.4  318.51  5390.1  317.37  5392.9  316.87  5396.1  317.37  5408.1  317.68
  5499.2  323.25  5562.8  325.19    5676  332.82  5916.4  353.42    6072  369.59
#Mann= 10 ,-1 , 0
  3350.5     .05       0  3826.6     .16       0  3879.2     .05       0
  4021.3     .16       0  4163.4     .05       0  4447.5     .16       0
  4781.5     .12       0  5390.1     .07       0  5396.1     .12       0
  5408.1     .16       0
Bank Sta=4975.9,5018.4
XS Rating Curve= 0 ,0
Exp/Cntr=0.3,0.1

Type RM Length L Ch R = 1 ,40834   ,726,726,726
BEGIN DESCRIPTION:
CAMP CREEK 58.0
END DESCRIPTION:
XS GIS Cut Line= 3
      3546869.37     10368340.94      3547857.73     10367252.75
      3548507.41     10366453.15
#Sta/Elev= 30
  3478.2  355.24  3643.6  347.01    3673  345.59  3727.4  344.13  3876.1  336.49
  4159.2  330.03  4322.1  322.88    4414  320.59  4569.9  319.39    4612  319.37
  4660.7  316.87  4722.5  315.19  4725.3  314.69  4728.5  315.19  4774.8  316.98
    4974  319.14  5009.2  317.16  5015.6  318.95  5101.8  316.32  5279.2  326.61
    5288  329.59  5300.1  330.96  5343.2  331.05  5392.7  335.29  5549.3   337.6
  5627.6  340.38  5819.4  351.41  5854.6  354.75  5947.3  359.98  5978.5  363.31
#Mann= 8 ,-1 , 0
  3478.2     .05       0  3643.6      .1       0    3673     .05       0
  4569.9     .16       0  4660.7     .12       0  4722.5     .07       0
  4728.5     .12       0    5288     .16       0
Bank Sta=4974,5015.6
XS Rating Curve= 0 ,0
Exp/Cntr=0.3,0.1

Type RM Length L Ch R = 1 ,40108   ,692,692,692
BEGIN DESCRIPTION:
CAMP CREEK 57.0
END DESCRIPTION:
XS GIS Cut Line= 3
      3547792.48     10368567.64      3548242.45     10367767.68
      3548987.28     10367012.96
#Sta/Elev= 30
  3966.1  354.73  4014.7  351.22  4101.4  348.69    4191  344.01  4381.9  331.11
  4587.1  319.41  4668.1  316.81  4844.1  315.69    4885  314.73  4887.7  314.23
    4891  314.73  4972.8  318.87    4987   318.6    4994  315.53  5015.3  316.02
  5022.3  317.76  5100.1  316.06  5156.7  320.01  5177.9   320.1  5300.2  325.92
  5411.9  329.93  5432.4  330.33  5467.8  335.87  5503.2  337.62  5524.4  341.47
  5767.2  341.45    5885  341.44    5892  343.09  5913.7   344.7  5944.3  347.33
#Mann= 8 ,-1 , 0
  3966.1     .05       0  4844.1     .12       0    4885     .07       0
    4891     .12       0  5300.2     .16       0  5411.9     .15       0
  5767.2     .05       0  5913.7     .16       0
Bank Sta=4987,5022.3
XS Rating Curve= 0 ,0
Exp/Cntr=0.3,0.1

Type RM Length L Ch R = 1 ,39416   ,447,447,447
BEGIN DESCRIPTION:
CAMP CREEK 56.0
END DESCRIPTION:
XS GIS Cut Line= 3
      3548242.08     10368691.68      3548792.11     10368091.64
      3549177.75      10367499.9
#Sta/Elev= 30
  4209.1  351.66  4527.6  334.54  4570.2  330.05  4626.9  327.08  4681.9  322.27
  4767.8  318.03  4860.3   315.3  4980.8  316.49  4998.8  314.38  5001.6  313.88
  5004.8  314.38  5019.7  316.34  5058.9  316.94  5145.3  314.47  5232.8  314.51
    5331  319.52  5428.9  327.91  5456.1  332.19  5471.2  337.48  5486.4   340.2
  5492.3   340.1  5507.5  343.31  5543.7  347.25  5564.8  346.74  5579.9  349.28
  5585.9  348.53  5616.1   351.5  5637.2  350.96  5652.3  352.24  5729.4  350.66
#Mann= 6 ,-1 , 0
  4209.1     .05       0  4681.9     .16       0  4767.8     .12       0
  4998.8     .07       0  5004.8     .12       0    5331     .16       0
Bank Sta=4980.8,5019.7
XS Rating Curve= 0 ,0
Exp/Cntr=0.3,0.1

Type RM Length L Ch R = 1 ,38969   ,586,586,586
BEGIN DESCRIPTION:
CAMP CREEK 55.0
END DESCRIPTION:
XS GIS Cut Line= 3
      3548392.09     10369041.65      3549325.94     10368184.71
      3549492.09     10367741.69
#Sta/Elev= 30
  3980.9  351.57  4016.4   347.9  4051.5  346.97  4115.6  342.94  4235.9  336.96
  4285.2  336.38  4313.6  333.28    4427  329.39  4455.4   329.6  4496.9  327.58
  4561.4  325.84  4624.9  326.19  4653.3  323.81  4677.2  322.75  4764.8  319.14
  4801.9  315.22  4816.1  314.65  4922.1  314.76  4978.9  315.77  4993.1  314.67
  4999.6  313.23  5007.2  314.32  5035.6  315.94    5191  314.99  5212.6  316.54
  5262.3  322.01  5334.4  327.58  5552.9  345.61  5657.5  355.02  5721.5  358.57
#Mann= 8 ,-1 , 0
  3980.9     .05       0  4496.9     .16       0  4677.2     .05       0
  4764.8     .07       0  4978.9    .035       0  5035.6     .07       0
  5334.4     .16       0  5552.9     .05       0
Bank Sta=4978.9,5035.6
XS Rating Curve= 0 ,0
Exp/Cntr=0.3,0.1

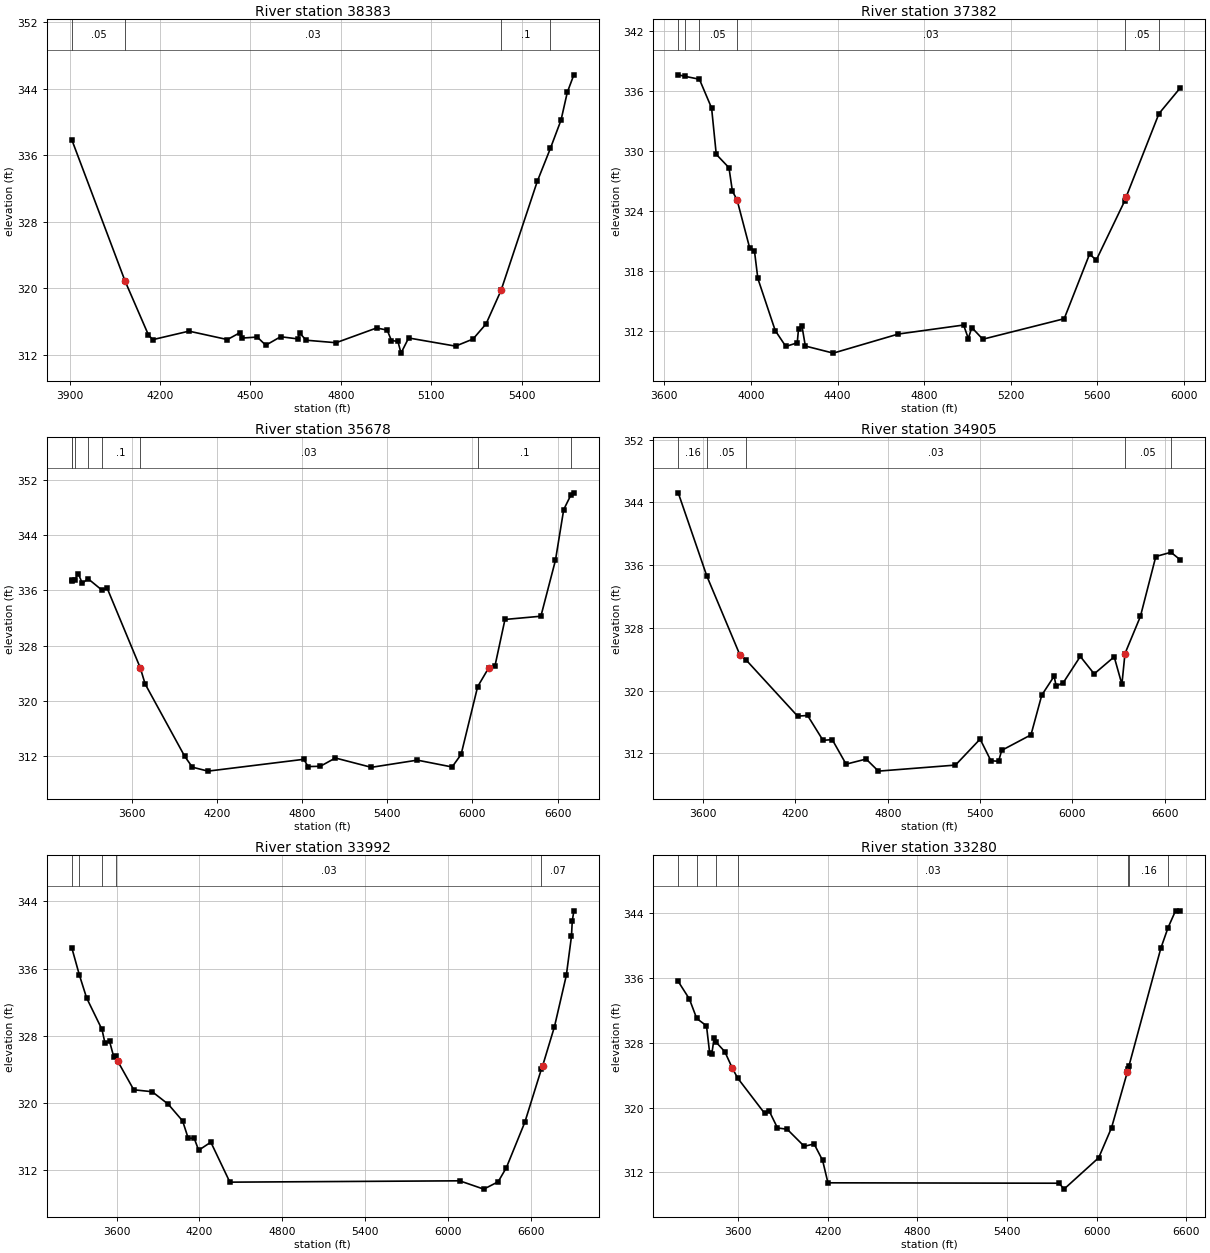
Type RM Length L Ch R = 1 ,38383   ,1001,1001,1001
BEGIN DESCRIPTION:
CAMP CREEK 54.0
END DESCRIPTION:
XS GIS Cut Line= 3
      3548842.09     10369391.65      3549642.11     10368641.64
      3549992.11     10368191.63
#Sta/Elev= 30
  3906.9  337.86    4084  320.86  4161.6  314.39  4175.8  313.84    4296  314.86
  4423.5  313.85  4465.9  314.69  4472.8  314.03  4522.6  314.15  4550.9  313.17
  4600.3  314.19  4656.9  313.93  4663.8  314.61  4685.3  313.77  4784.2  313.47
  4918.7  315.24  4953.9  314.99  4968.1  313.73  4989.6  313.63  4999.8  312.22
  5025.2  314.04  5180.9  313.06  5238.8  313.91  5282.2  315.73    5332  319.76
  5452.3  332.86  5495.8  336.82  5531.1  340.22  5551.9  343.55  5573.6  345.65
#Mann= 4 ,-1 , 0
  3906.9     .05       0    4084     .03       0    5332      .1       0
  5495.8     .16       0
Bank Sta=4084,5332
XS Rating Curve= 0 ,0
Exp/Cntr=0.3,0.1

Type RM Length L Ch R = 1 ,37382   ,1704,1704,1704
BEGIN DESCRIPTION:
CAMP CREEK 52.0
END DESCRIPTION:
XS GIS Cut Line= 3
      3548891.93      10369972.9      3549820.74     10369434.71
       3550419.7     10368340.95
#Sta/Elev= 30
  3663.9  337.59    3695  337.44  3761.7  337.15  3818.1  334.27  3839.6  329.64
  3898.4   328.3  3914.2  325.96  3935.7  325.09  3994.5  320.24    4016  320.01
  4031.8  317.23  4112.1  312.02  4161.1  310.43    4214  310.79  4219.8  312.19
  4235.5   312.5  4251.3  310.47  4380.4  309.76  4681.2  311.67  4982.8  312.57
  5004.6  311.22  5020.7  312.32  5071.5  311.15  5447.7   313.2    5565  319.66
    5596  319.07  5727.1  324.97  5733.8  325.36  5885.7  333.71  5984.4  336.29
#Mann= 6 ,-1 , 0
  3663.9     .05       0    3695     .16       0  3761.7     .05       0
  3935.7     .03       0  5727.1     .05       0  5885.7     .16       0
Bank Sta=3935.7,5733.8
XS Rating Curve= 0 ,0
Exp/Cntr=0.3,0.1

Type RM Length L Ch R = 1 ,35678   ,773,773,773
BEGIN DESCRIPTION:
CAMP CREEK 51.0
END DESCRIPTION:
XS GIS Cut Line= 3
      3551556.85      10371717.7      3550963.29     10370473.59
      3550636.91     10368342.29
#Sta/Elev= 30
    3179  337.33    3183  337.43  3199.6   337.5  3224.7  338.42  3252.9  337.03
  3293.8  337.68  3388.8  336.08  3428.9  336.28  3661.3  324.79  3695.4  322.46
    3973  312.03  4027.8  310.42  4138.3  309.85  4812.3  311.56  4842.7  310.51
  4928.6  310.55  5034.9  311.75  5287.8   310.4  5611.5  311.44  5856.4  310.45
  5919.8  312.26  6036.4  322.07    6115  324.82  6157.8  325.02  6228.7  331.79
  6481.6  332.26    6584  340.34  6642.3  347.69    6694  349.84  6713.6  350.11
#Mann= 8 ,-1 , 0
    3179     .05       0    3183     .08       0  3199.6     .16       0
  3293.8     .05       0  3388.8      .1       0  3661.3     .03       0
  6036.4      .1       0    6694     .05       0
Bank Sta=3661.3,6115
XS Rating Curve= 0 ,0
Exp/Cntr=0.3,0.1

Type RM Length L Ch R = 1 ,34905   ,913,913,913
BEGIN DESCRIPTION:
CAMP CREEK 49.0
END DESCRIPTION:
XS GIS Cut Line= 3
      3551692.11     10371391.68      3551642.11     10369841.64
      3551556.85     10368132.62
#Sta/Elev= 30
    3439  345.23  3624.5  334.62  3839.3  324.56  3879.3  323.91  4214.5  316.73
  4279.5  316.81  4379.5  313.64  4439.6  313.73  4529.6   310.6  4659.7  311.25
  4739.5  309.71  5240.2  310.48  5400.4   313.8  5470.4  311.03  5520.5  310.97
  5540.5  312.36  5730.8  314.34  5800.9  319.41    5881  321.82  5894.5  320.56
    5941  321.01  6051.2  324.35  6141.3  322.12  6271.4   324.3  6321.5  320.79
  6341.5  324.71  6441.7  329.45  6541.8   337.1  6639.9  337.64    6701  336.68
#Mann= 5 ,-1 , 0
    3439     .16       0  3624.5     .05       0  3879.3     .03       0
  6341.5     .05       0  6639.9     .16       0
Bank Sta=3839.3,6341.5
XS Rating Curve= 0 ,0
Exp/Cntr=0.3,0.1

Type RM Length L Ch R = 1 ,33992   ,712,712,712
BEGIN DESCRIPTION:
CAMP CREEK 47.0
END DESCRIPTION:
XS GIS Cut Line= 3
       3551842.1     10371241.66      3552459.62     10369851.38
       3553223.5     10367880.92
#Sta/Elev= 30
  3275.5  338.48  3330.5  335.23  3382.9   332.5  3494.3  328.74  3516.2  327.09
  3549.1  327.33  3579.9  325.44  3592.8  325.64  3608.7  324.95  3724.1  321.56
  3857.7  321.33    3974  319.84    4078  317.85  4118.1   315.8  4161.8  315.78
  4194.2  314.36  4282.2  315.32    4420  310.56  6083.5  310.72    6258  309.73
  6361.9   310.6  6421.7  312.29  6555.2  317.69  6674.9  324.01  6684.1  324.41
  6769.9  329.08  6855.7  335.19  6892.8  339.83  6898.6  341.63  6910.1  342.87
#Mann= 5 ,-1 , 0
  3275.5     .16       0  3330.5     .08       0  3494.3     .07       0
  3592.8     .03       0  6674.9     .07       0
Bank Sta=3608.7,6684.1
XS Rating Curve= 0 ,0
Exp/Cntr=0.3,0.1

Type RM Length L Ch R = 1 ,33280   ,539,539,539
BEGIN DESCRIPTION:
CAMP CREEK 46.0
END DESCRIPTION:
XS GIS Cut Line= 3
      3552190.52     10371353.12      3553192.11     10369891.64
      3553842.12     10368441.62
#Sta/Elev= 30
  3198.8  335.59  3273.3  333.43  3322.5  331.02  3387.9  330.11  3408.9   326.8
  3423.8  326.66  3438.7  328.58  3449.6  328.14  3510.4  326.92  3561.2  324.86
  3597.1  323.64  3776.5  319.31  3806.3  319.64  3863.1  317.49    3928  317.33
  4042.5  315.22  4108.2  315.52    4165  313.49  4200.9  310.71  5748.6  310.66
  5781.2  309.93  6013.3  313.81  6099.3  317.52  6204.3  324.35  6209.7  324.72
  6215.9  325.16  6429.3   339.7  6477.3  342.23  6527.5  344.32  6559.6  344.32
#Mann= 7 ,-1 , 0
  3198.8     .16       0  3322.5     .05       0  3449.6     .07       0
  3597.1     .03       0  6209.7     .05       0  6215.9     .16       0
  6477.3     .05       0
Bank Sta=3561.2,6204.3
XS Rating Curve= 0 ,0
Exp/Cntr=0.3,0.1

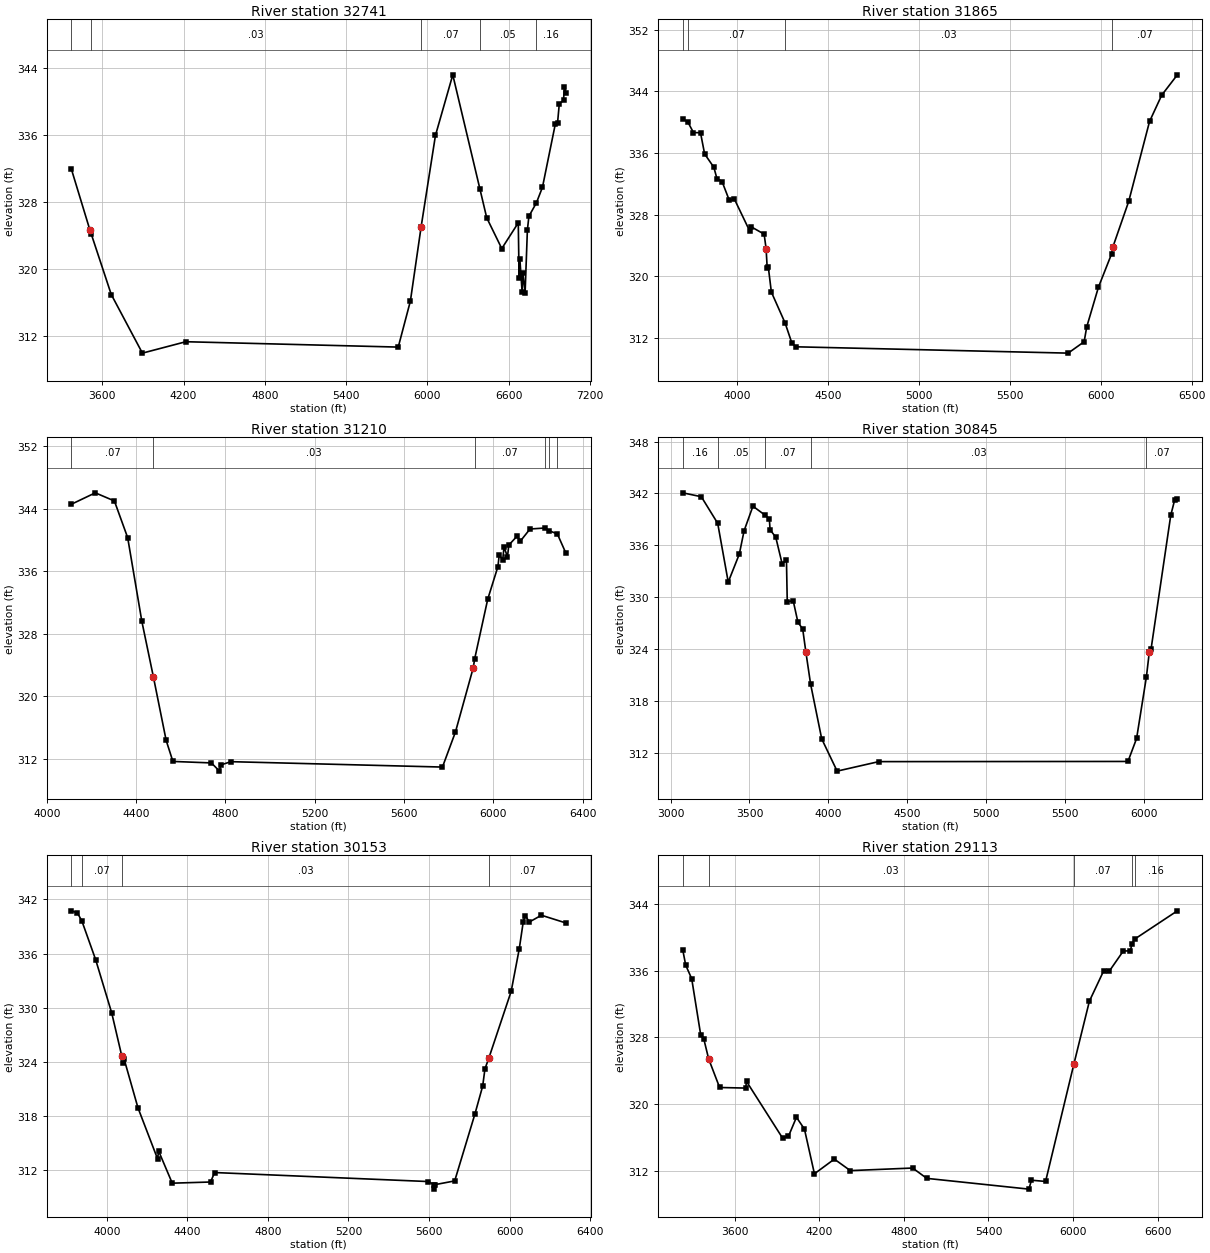
Type RM Length L Ch R = 1 ,32741   ,876,876,876
BEGIN DESCRIPTION:
CAMP CREEK 45.0
END DESCRIPTION:
XS GIS Cut Line= 3
      3553154.06     10371639.61      3553692.11     10370091.64
      3554603.72     10368297.57
#Sta/Elev= 30
  3371.8   331.9  3507.7  324.68  3517.9  324.19  3666.1  316.95    3896  309.96
  4216.6  311.32  5784.6  310.68  5874.3  316.17  5953.6  325.03  6059.3  335.92
  6187.2  343.15  6387.5  329.54  6437.6  326.11  6548.9  322.43  6670.7   325.5
  6676.8  318.91  6682.4   321.2  6699.1  317.23  6704.7  319.53  6721.2  317.18
    6738  324.65  6749.2  326.28  6804.7  327.89  6849.2  329.74  6943.9  337.26
  6960.5  337.39  6973.6  339.71    7005   340.1  7010.6   341.7    7023  341.04
#Mann= 5 ,-1 , 0
  3371.8     .07       0  3517.9     .03       0  5953.6     .07       0
  6387.5     .05       0  6804.7     .16       0
Bank Sta=3507.7,5953.6
XS Rating Curve= 0 ,0
Exp/Cntr=0.3,0.1

Type RM Length L Ch R = 1 ,31865   ,655,655,655
BEGIN DESCRIPTION:
CAMP CREEK 43.0
END DESCRIPTION:
XS GIS Cut Line= 3
      3553864.67      10371634.7      3554247.82     10370840.96
       3555242.1     10369291.64
#Sta/Elev= 30
  3699.1  340.45  3727.3  340.02    3758  338.66  3796.8  338.64  3819.4  335.89
  3870.2  334.16  3887.2  332.69  3915.4  332.31    3955  329.89  3983.2  330.04
  4068.1  325.87  4073.6  326.47    4147  325.49  4157.8  323.61    4164  321.04
  4169.6  321.29  4186.7  317.98  4262.2  313.98  4299.7  311.36  4322.3  310.88
  5820.3  310.06  5908.4  311.54  5922.4  313.45    5987  318.61  6059.7  322.95
  6065.6  323.77  6153.5  329.73  6268.4  340.11  6335.2  343.51  6421.4  346.15
#Mann= 4 ,-1 , 0
  3699.1     .05       0  3727.3     .07       0  4262.2     .03       0
  6059.7     .07       0
Bank Sta=4157.8,6065.6
XS Rating Curve= 0 ,0
Exp/Cntr=0.3,0.1

Type RM Length L Ch R = 1 ,31210   ,365,365,365
BEGIN DESCRIPTION:
CAMP CREEK 42.0
END DESCRIPTION:
XS GIS Cut Line= 3
      3554230.42     10371526.75      3554794.69     10371162.14
       3555592.1     10369841.66
#Sta/Elev= 30
  4110.3  344.58  4217.3  346.04  4302.8     345  4362.3   340.3  4425.8  329.58
  4477.2  322.52  4534.6  314.36  4564.7  311.67  4737.2  311.48  4773.2  310.43
    4778  311.21  4824.5  311.64  5771.6  310.95  5829.8  315.44  5909.4  323.65
  5915.9  324.81  5974.3  332.43    6020  336.61  6025.8   338.1  6041.4  337.45
  6047.2  339.12  6062.7  337.85  6068.6  339.35  6105.4  340.49  6120.9  339.88
  6163.6  341.41  6231.3  341.54    6247  341.21  6285.9  340.79  6324.7  338.29
#Mann= 6 ,-1 , 0
  4110.3     .07       0  4477.2     .03       0  5915.9     .07       0
  6231.3     .05       0    6247     .16       0  6285.9     .05       0
Bank Sta=4477.2,5909.4
XS Rating Curve= 0 ,0
Exp/Cntr=0.3,0.1

Type RM Length L Ch R = 1 ,30845   ,692,692,692
BEGIN DESCRIPTION:
CAMP CREEK 41.0
END DESCRIPTION:
XS GIS Cut Line= 3
      3555228.72     10373158.69      3555072.47     10371492.01
      3555492.11     10370091.62
#Sta/Elev= 30
  3077.2  342.07  3194.8  341.62  3298.7  338.54  3365.5  331.74  3435.8  334.98
  3465.9  337.67  3522.1  340.52  3595.6  339.53  3625.9  339.09  3630.9   337.8
  3666.8  336.93    3707  333.88  3734.7  334.24  3739.7  329.45  3777.3  329.59
  3807.4  327.08  3837.6  326.31  3857.7  323.64  3887.8  319.92  3958.1  313.59
  4055.9  309.85  4319.7  310.95  5899.9  310.97  5954.6  313.63  6016.7  320.75
  6035.6  323.68    6046  323.94  6171.3  339.48  6196.5  341.28  6213.1  341.31
#Mann= 5 ,-1 , 0
  3077.2     .16       0  3298.7     .05       0  3595.6     .07       0
  3887.8     .03       0  6016.7     .07       0
Bank Sta=3857.7,6035.6
XS Rating Curve= 0 ,0
Exp/Cntr=0.3,0.1

Type RM Length L Ch R = 1 ,30153   ,1040,1040,1040
BEGIN DESCRIPTION:
CAMP CREEK 39.0
END DESCRIPTION:
XS GIS Cut Line= 3
       3555642.1     10372641.67      3555688.79     10371839.23
      3555792.96     10370189.91
#Sta/Elev= 30
  3823.9  340.74    3854   340.5    3876  339.61  3944.1  335.34  4024.3   329.4
  4074.4  324.61  4080.8  323.88  4085.8  324.29  4154.5  318.89    4252  313.22
    4257   314.1  4324.8  310.53  4515.1  310.66  4535.1  311.71  5597.2  310.71
  5624.3  310.37    5627  309.87  5630.3  310.37  5727.5  310.78  5827.7  318.18
  5866.5   321.3  5877.8  323.21  5897.8  324.45    6008  331.81  6048.1  336.51
  6068.2  339.55  6078.2  340.21  6098.2   339.5  6158.3  340.25  6280.3  339.39
#Mann= 4 ,-1 , 0
  3823.9     .05       0    3876     .07       0  4074.4     .03       0
  5897.8     .07       0
Bank Sta=4074.4,5897.8
XS Rating Curve= 0 ,0
Exp/Cntr=0.3,0.1

Type RM Length L Ch R = 1 ,29113   ,887,887,887
BEGIN DESCRIPTION:
CAMP CREEK 38.0
END DESCRIPTION:
XS GIS Cut Line= 3
      3555792.97     10372741.99       3556713.1     10371743.74
      3556878.02     10369599.69
#Sta/Elev= 30
  3231.9  338.47  3252.8  336.64  3295.3  335.02  3358.8  328.32  3380.4  327.84
  3415.5   325.4  3493.2  321.97  3677.5   321.9  3684.3  322.69  3939.5  315.91
  3981.5  316.11  4038.2   318.4  4094.9  316.98  4165.8  311.62    4307  313.38
  4420.4     312  4862.4  312.31  4962.7  311.07  5687.1  309.78  5704.9  310.85
  5805.2   310.7  6005.8  324.77  6116.1  332.33  6216.4  335.93  6256.5  335.91
  6356.8  338.35    6407  338.35  6417.1  339.21  6439.1  339.79  6739.9  343.16
#Mann= 5 ,-1 , 0
  3231.9     .07       0  3415.5     .03       0  6005.8     .07       0
  6417.1     .05       0  6439.1     .16       0
Bank Sta=3415.5,6005.8
XS Rating Curve= 0 ,0
Exp/Cntr=0.3,0.1

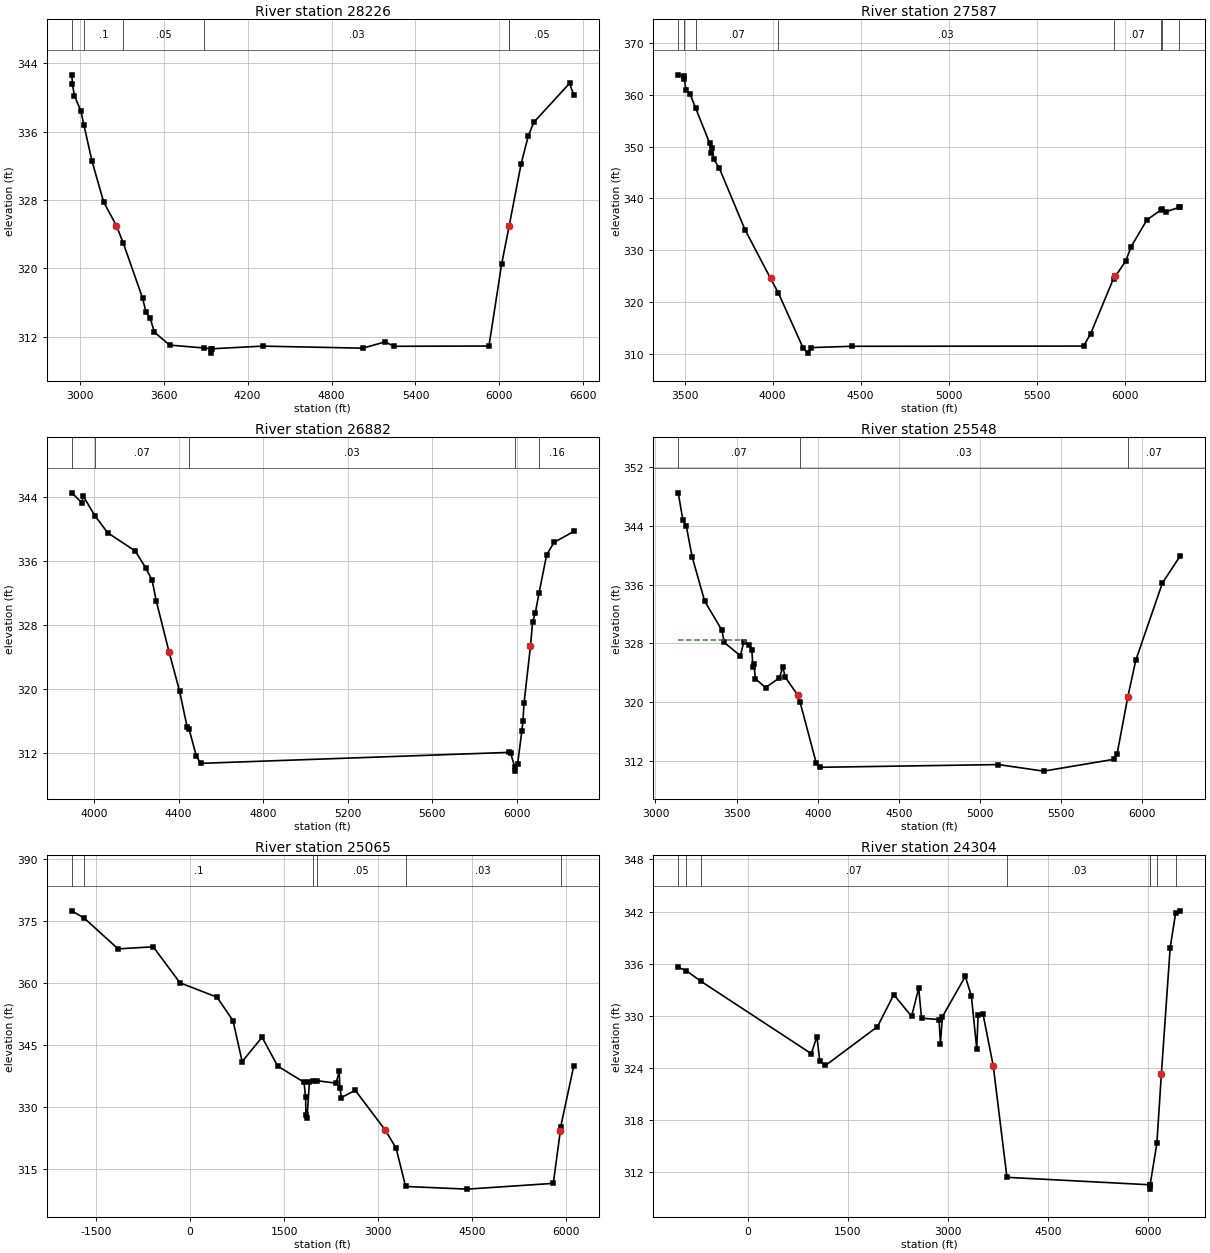
Type RM Length L Ch R = 1 ,28226   ,639,639,639
BEGIN DESCRIPTION:
CAMP CREEK 37.0
END DESCRIPTION:
XS GIS Cut Line= 3
      3558249.56     10373219.45      3557667.96      10371717.7
      3557494.34     10369747.17
#Sta/Elev= 30
  2943.2  342.64  2948.1  341.52  2962.3   340.2    3008  338.43  3030.1  336.77
    3087  332.59  3171.5  327.75  3262.6  324.99  3310.4     323  3449.3  316.53
  3473.9  314.86  3503.8  314.16  3533.7  312.54  3642.7  311.03  3890.7  310.69
  3935.2  310.59  3937.9  310.09  3945.2   310.6  4307.5  310.91  5022.8  310.67
  5182.1   311.4  5247.2  310.89    5925  310.92  6015.3  320.46  6069.5  324.97
  6154.7  332.21  6206.1   335.5  6246.2   337.1  6501.3  341.65  6531.8  340.23
#Mann= 6 ,-1 , 0
  2943.2     .05       0  3030.1      .1       0  3310.4     .05       0
  3890.7     .03       0  6069.5     .16       0  6069.5     .05       0
Bank Sta=3262.6,6069.5
XS Rating Curve= 0 ,0
Exp/Cntr=0.3,0.1

Type RM Length L Ch R = 1 ,27587   ,705,705,705
BEGIN DESCRIPTION:
CAMP CREEK 36.0
END DESCRIPTION:
XS GIS Cut Line= 3
      3558792.12     10372641.67      3558266.92     10371578.81
      3558266.92     10369912.15
#Sta/Elev= 30
  3464.4  363.84  3495.3  363.65  3498.7  362.98    3509  360.85  3531.4  360.15
  3562.6  357.46  3642.9  350.67  3652.4  348.78    3658  349.72  3665.2  347.57
  3697.3  345.86  3843.7  333.95  3988.7  324.55  4033.3  321.73  4174.1  311.09
  4201.9  310.12    4219  311.19    4449  311.44  5767.1  311.48  5807.1  313.87
  5937.1  324.52  5947.1  324.92  6007.1  327.93  6037.1  330.66  6127.1  335.85
  6207.1  337.76  6213.5  337.91  6237.1  337.43  6311.7  338.27  6316.6   338.3
#Mann= 8 ,-1 , 0
  3464.4     .05       0  3498.7     .16       0  3562.6     .07       0
  4033.3     .03       0  5937.1     .07       0  6207.1     .05       0
  6213.5     .16       0  6311.7     .05       0
Bank Sta=3988.7,5947.1
XS Rating Curve= 0 ,0
Exp/Cntr=0.3,0.1

Type RM Length L Ch R = 1 ,26882   ,1334,1334,1334
BEGIN DESCRIPTION:
CAMP CREEK 34.0
END DESCRIPTION:
XS GIS Cut Line= 3
      3558996.08     10372281.96      3559013.44     10371422.56
      3558744.34     10369929.49
#Sta/Elev= 30
  3893.9   344.5  3941.9  343.26  3946.9  344.15  4003.5  341.63  4064.2  339.51
  4194.3  337.24  4244.3  335.12  4274.3  333.58  4294.3  330.95  4354.3  324.65
  4404.3  319.74  4439.5  315.33  4449.3  314.98  4484.3  311.59  4504.3  310.73
  5963.6   312.1  5970.9  312.06  5991.1  310.26  5993.8  309.76  6004.2  310.62
  6024.5  314.77  6029.6  315.98  6034.7  318.23  6065.2  325.32  6075.4  328.38
  6088.2  329.52  6105.8  331.98  6141.8  336.76    6177  338.32  6270.6  339.68
#Mann= 5 ,-1 , 0
  3893.9     .05       0  4003.5     .07       0  4449.3     .03       0
  5991.1     .07       0  6105.8     .16       0
Bank Sta=4354.3,6065.2
XS Rating Curve= 0 ,0
Exp/Cntr=0.3,0.1

Type RM Length L Ch R = 1 ,25548   ,483,483,483
BEGIN DESCRIPTION:
CAMP CREEK 32.0
END DESCRIPTION:
XS GIS Cut Line= 3
      3558996.07     10372585.77      3560141.92     10371561.45
      3560879.74     10370189.96
#Sta/Elev= 30
  3140.4  348.49  3168.9  344.81  3189.8     344  3225.7  339.82  3303.4  333.75
  3409.6  329.81  3423.8  328.14  3523.3  326.33  3544.2  328.19  3579.3  327.84
  3593.5  327.18    3601  324.82  3607.7  325.22  3615.2  323.21  3678.8  322.01
    3764  323.32  3784.9  324.83  3799.2  323.44  3876.9  320.98  3891.1  320.04
  3990.6  311.77  4011.5  311.16  5112.4  311.53  5392.3  310.64  5828.9  312.26
  5845.1  312.98  5910.8   320.7  5960.3  325.72  6124.3  336.22  6234.7  339.93
#Mann= 3 ,-1 , 0
  3140.4     .07       0  3891.1     .03       0  5910.8     .07       0
#XS Ineff= 2 , 0
         3550.85  328.42
Permanent Ineff=
       F       F
Bank Sta=3876.9,5910.8
XS Rating Curve= 0 ,0
Exp/Cntr=0.3,0.1

Type RM Length L Ch R = 1 ,25065   ,761,761,761
BEGIN DESCRIPTION:
CAMP CREEK 31.0
END DESCRIPTION:
XS GIS Cut Line= 3
      3558367.35     10377889.83      3560671.43     10371795.83
      3560992.11      10370341.6
#Sta/Elev= 30
 -1884.1  377.49 -1682.2  375.68 -1146.3  368.29  -585.6  368.79  -159.7  360.09
   431.2   356.6   686.7  350.93   832.3  341.03  1150.2  346.92  1398.3  339.94
  1818.9  336.03  1843.7  332.36    1849  328.05  1866.5  327.37    1904  336.01
  1959.7  336.31  2019.4  336.41  2329.9  335.81  2379.6  338.65  2390.3  334.59
  2415.1  332.34  2635.1  334.08    3116  324.41  3286.4  320.08  3438.2  310.82
  4418.3  310.18  5792.4  311.57    5905  324.27  5910.6  325.29  6120.1  340.08
#Mann= 6 ,-1 , 0
 -1884.1      .1       0 -1682.2      .1       0  1959.7     .05       0
  2019.4     .05       0  3438.2     .03       0  5910.6      .1       0
Bank Sta=3116,5905
XS Rating Curve= 0 ,0
Exp/Cntr=0.3,0.1

Type RM Length L Ch R = 1 ,24304   ,354,354,354
BEGIN DESCRIPTION:
CAMP CREEK 29.0
END DESCRIPTION:
XS GIS Cut Line= 5
      3560216.29     10377490.59      3561488.54     10374063.16
      3561618.84     10373071.85      3561418.84     10371971.85
      3561692.11      10370241.6
#Sta/Elev= 30
 -1041.1  335.58  -917.6  335.17  -700.9  333.97   952.4  325.64  1037.8   327.6
  1080.4  324.79  1165.8  324.28  1944.5  328.74  2189.8  332.43  2456.5  329.93
  2563.1  333.17  2605.6  329.72  2868.5  329.56  2888.7   326.8  2918.9   329.9
  3261.9  334.53  3352.6  332.28  3433.3  326.19  3453.5  330.07  3526.9  330.21
  3680.6  324.23  3885.7   311.4  6025.8  310.54  6028.5  310.04  6031.8  310.54
  6132.8   315.3  6200.9  323.35  6332.5  337.85    6415  341.85  6484.4  342.08
#Mann= 8 ,-1 , 0
 -1041.1     .05       0  -917.6     .16       0  -700.9     .07       0
  3885.7     .03       0  6025.8    .033       0  6031.8     .05       0
  6132.8     .16       0    6415     .05       0
Bank Sta=3680.6,6200.9
XS Rating Curve= 0 ,0
Exp/Cntr=0.3,0.1

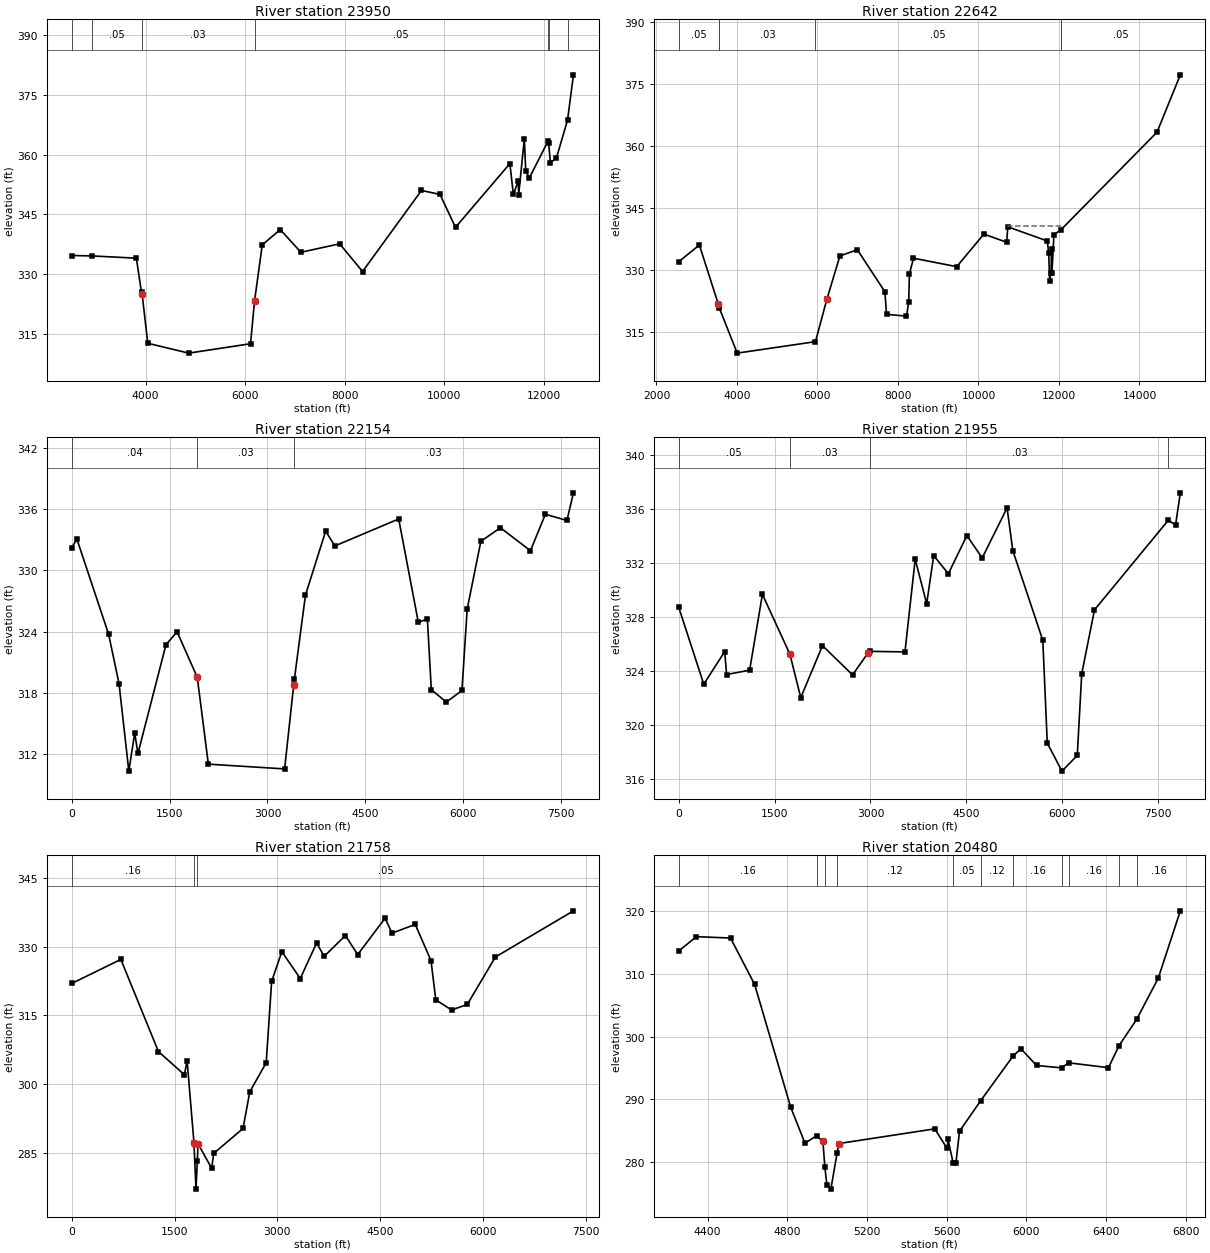
Type RM Length L Ch R = 1 ,23950   ,1308,1308,1308
BEGIN DESCRIPTION:
CAMP CREEK 28.0
END DESCRIPTION:
XS GIS Cut Line= 5
      3561581.26     10374312.94      3561763.55     10372281.72
      3561869.34     10370502.18      3560627.27     10367402.38
      3558418.94     10365492.66
#Sta/Elev= 30
  2517.9   334.7  2933.8  334.59  3816.6  334.03  3922.8  325.11  3927.8  325.53
  4045.3  312.71  4867.7  310.24  6110.1  312.59  6190.2  323.23  6345.9  337.36
  6706.8  341.19  7123.6  335.51  7901.3  337.63  8361.4  330.69  9545.4     351
  9917.5     350   10229  341.76 11321.4  357.72 11391.7  350.02 11491.4  353.35
   11498  349.93 11612.1  363.91 11640.6  355.94 11710.8  354.09   12087  363.32
 12101.8  362.77 12136.4  357.96   12257  359.13 12480.7  368.66 12598.9  379.97
#Mann= 7 ,-1 , 0
  2517.9     .15       0  2933.8     .05       0  3927.8     .03       0
  6190.2     .05       0   12087      .1       0 12101.8     .05       0
 12480.7     .05       0
Bank Sta=3922.8,6190.2
XS Rating Curve= 0 ,0
Exp/Cntr=0.3,0.1

Type RM Length L Ch R = 1 ,22642   ,488,488,488
BEGIN DESCRIPTION:
CAMP CREEK 27.0
END DESCRIPTION:
XS GIS Cut Line= 4
        3561675.     10374703.61      3563836.47     10370823.38
       3564602.1     10367776.51      3561894.62     10363715.29
#Sta/Elev= 30
  2551.1  332.02  3065.9  336.07  3536.9   321.8  3558.6   321.3  3564.4  320.79
  4006.8  309.97  5951.1  312.74  6233.6  322.99  6558.3  333.43  6990.9  334.93
    7675  324.79  7716.3  319.34  8211.2  318.89  8267.6  322.24  8283.4  329.04
  8385.9  332.88  9460.7  330.84 10134.3  338.71 10700.6  336.73 10729.1  340.46
 11710.2  337.04 11746.2  334.02 11767.3  327.49 11803.3  329.33 11818.3  335.15
 11824.3  329.26 11875.4  338.57   12047  339.72 14435.4   363.3 15015.3  377.15
#Mann= 6 ,-1 , 0
  2551.1     .05       0  3558.6    .033       0  3564.4     .03       0
  5951.1     .05       0   12047     .16       0   12047     .05       0
#XS Ineff= 2 ,-1
10734.0912110.23  340.7512110.23 15015.3  334.94
Permanent Ineff=
       F       F
Bank Sta=3536.9,6233.6
XS Rating Curve= 0 ,0
Exp/Cntr=0.3,0.1

Type RM Length L Ch R = 1 ,22154   ,199,199,199
BEGIN DESCRIPTION:
CAMP CREEK 26.0
END DESCRIPTION:
XS GIS Cut Line= 5
     3562051.023    10374903.068     3562341.605    10374791.479
     3562901.069    10373524.119     3563954.244    10371421.034
       3564757.4    10367838.254
#Sta/Elev= 30
       0332.201778.73774333.0486565.0248323.7331724.8815318.8933874.7473310.3366
964.6667314.05391014.622312.06731444.237322.70871614.085323.97631923.807319.5201
2093.655311.01853262.608310.55483402.482318.78833412.473319.34763582.321327.5709
3892.044333.83534031.918332.37275011.252 335.0165311.049324.92785450.954325.1946
5510.914318.30935740.758317.08875980.595318.22846060.541326.19036270.399332.8288
6570.196 334.1597029.884331.90997259.729335.47677589.505334.86727689.437337.5739
#Mann= 3 ,-1 , 0
       0     .04       01923.807     .03       03412.473     .03       0
Bank Sta=1923.807,3402.482
XS Rating Curve= 0 ,0
Exp/Cntr=0.3,0.1

Type RM Length L Ch R = 1 ,21955   ,197,197,197
BEGIN DESCRIPTION:
CAMP CREEK 25.0
END DESCRIPTION:
XS GIS Cut Line= 6
     3562172.516    10374967.684     3562670.253    10374803.107
     3562833.187    10374373.636     3563299.397    10373144.767
     3563998.284    10371785.897     3564878.928    10367872.977
#Sta/Elev= 30
       0328.7356392.8645323.0201720.3122325.4347750.3035323.7367  1110.2324.0565
1310.142329.67241740.018325.24511909.969322.02422249.871325.87442719.781323.7104
2959.736325.31742999.728325.45163539.627325.41083699.598332.27353879.429328.9836
3989.197332.5396 4218.71331.20424508.098334.0334 4747.59332.37025136.766336.0831
5226.576332.91195695.582326.27135765.434318.65615994.948316.5787 6234.44317.7378
6304.292323.7888 6503.87328.52657661.418335.18097771.186334.79237846.475337.1962
#Mann= 4 ,-1 , 0
       0     .05       01740.018     .03       02999.728     .03       0
7661.418      .1       0
Bank Sta=1740.018,2959.736
XS Rating Curve= 0 ,0
Exp/Cntr=0.3,0.1

Type RM Length L Ch R = 1 ,21758   ,1278,1278,1278
BEGIN DESCRIPTION:
CAMP CREEK 24.0
END DESCRIPTION:
XS GIS Cut Line= 5
     3562784.929    10374821.417     3563083.885    10374293.172
     3563492.106    10373191.642     3564147.702    10371644.938
     3564930.897    10367889.036
#Sta/Elev= 30
       0321.9297716.8741 327.1771265.195 307.0551644.035301.98551683.912305.0375
1783.607287.18691813.469277.00521833.362 283.2061843.308286.91622042.234281.5585
2072.073284.80672499.764 290.2532599.227298.29792837.938304.58952917.508322.3668
3066.703328.87473335.253323.0018 3574.31330.78263684.263327.85283994.131332.3891
4174.054 328.2344573.883336.19924673.841332.91065013.696334.82545243.598326.9149
5313.568318.3527 5543.47316.13375773.372317.34026183.197327.70017322.711337.7922
#Mann= 3 ,-1 , 0
       0     .16       01783.607     .05       01833.362     .05       0
Bank Sta=1783.607,1843.308
XS Rating Curve= 0 ,0
Exp/Cntr=0.3,0.1

Type RM Length L Ch R = 1 ,20480   ,948,948,948
BEGIN DESCRIPTION:
CAMP CREEK 23.0
END DESCRIPTION:
XS GIS Cut Line= 3
        3564569.     10374070.13      3564699.21     10373028.46
      3564300.33     10371615.05
#Sta/Elev= 30
    4255  313.66  4344.2  315.96  4515.5  315.74  4636.4  308.33  4817.8  288.67
  4889.1  282.96  4947.6  284.15  4979.1  283.24  4989.2  279.11  4999.2  276.27
  5019.1  275.61  5050.3  281.36  5059.7   282.9  5540.5  285.24  5602.3  282.14
  5607.5  283.55  5633.2  279.74  5646.7  279.75  5665.1  284.87  5771.8  289.77
  5935.1  296.94  5973.5  298.03  6051.8  295.37  6177.8  294.99  6212.5   295.8
  6412.6  295.02  6466.1  298.56    6554  302.73  6662.6  309.33  6773.4  320.09
#Mann= 11 ,-1 , 0
    4255     .16       0  4947.6     .12       0  4989.2     .07       0
  5050.3     .12       0  5633.2     .05       0  5771.8     .12       0
  5935.1     .16       0  6177.8     .05       0  6212.5     .16       0
  6466.1     .05       0    6554     .16       0
Bank Sta=4979.1,5059.7
XS Rating Curve= 0 ,0
Exp/Cntr=0.3,0.1