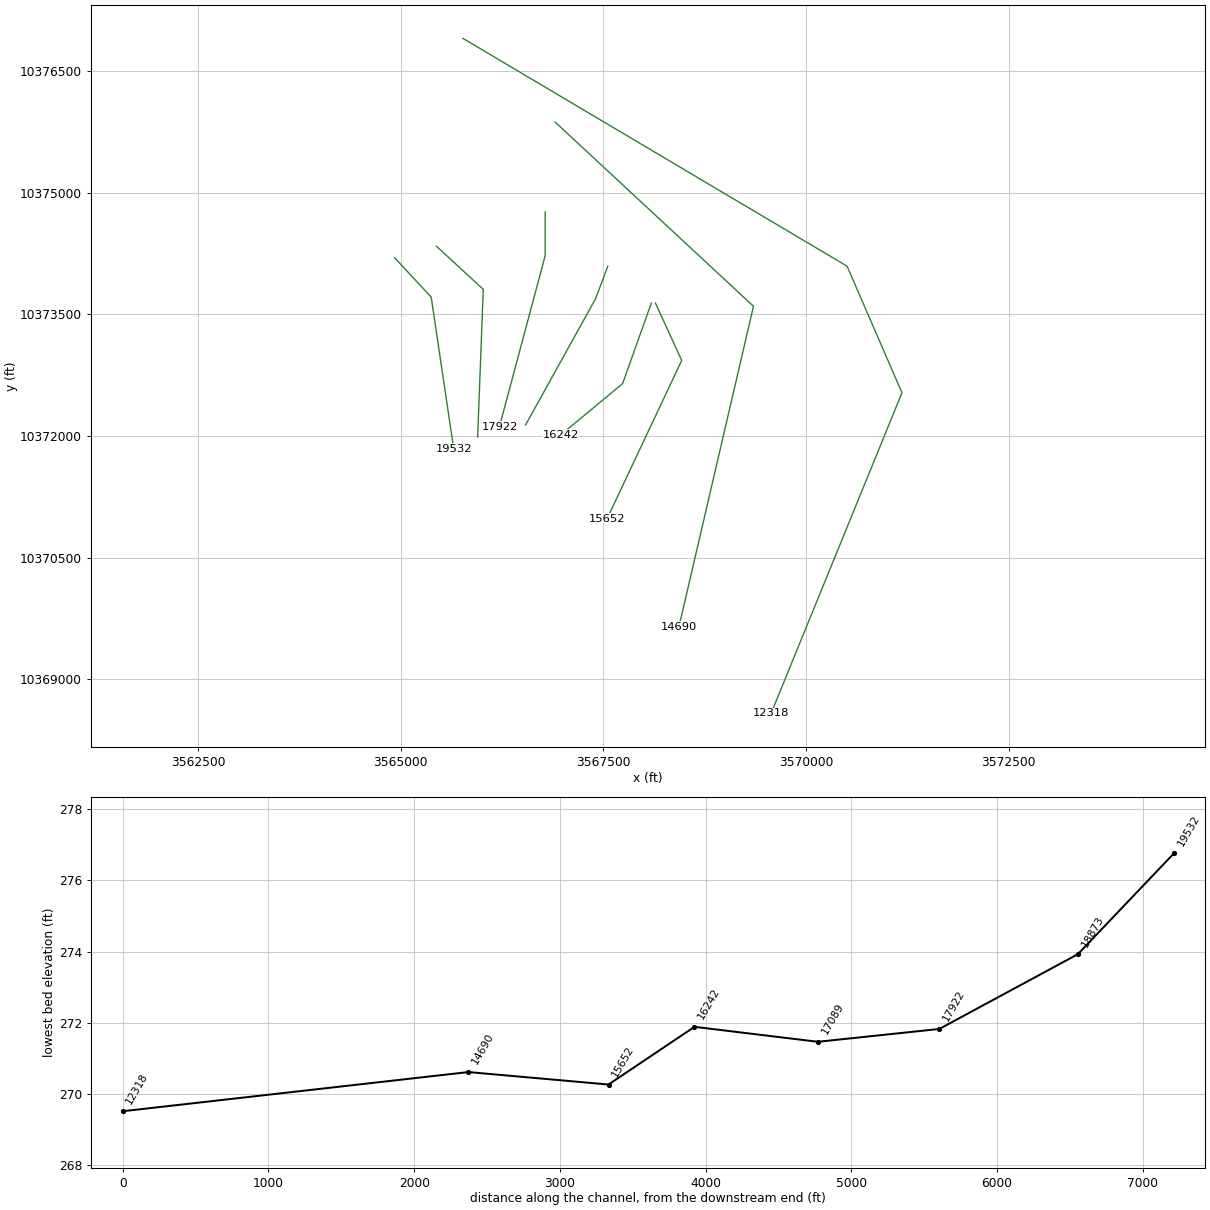
HEC-RAS study CAMP CREEK.prj: CAMP CREEK Base Level Engineering

--- CAMP CREEK.g01 (geometry) --- (continued)

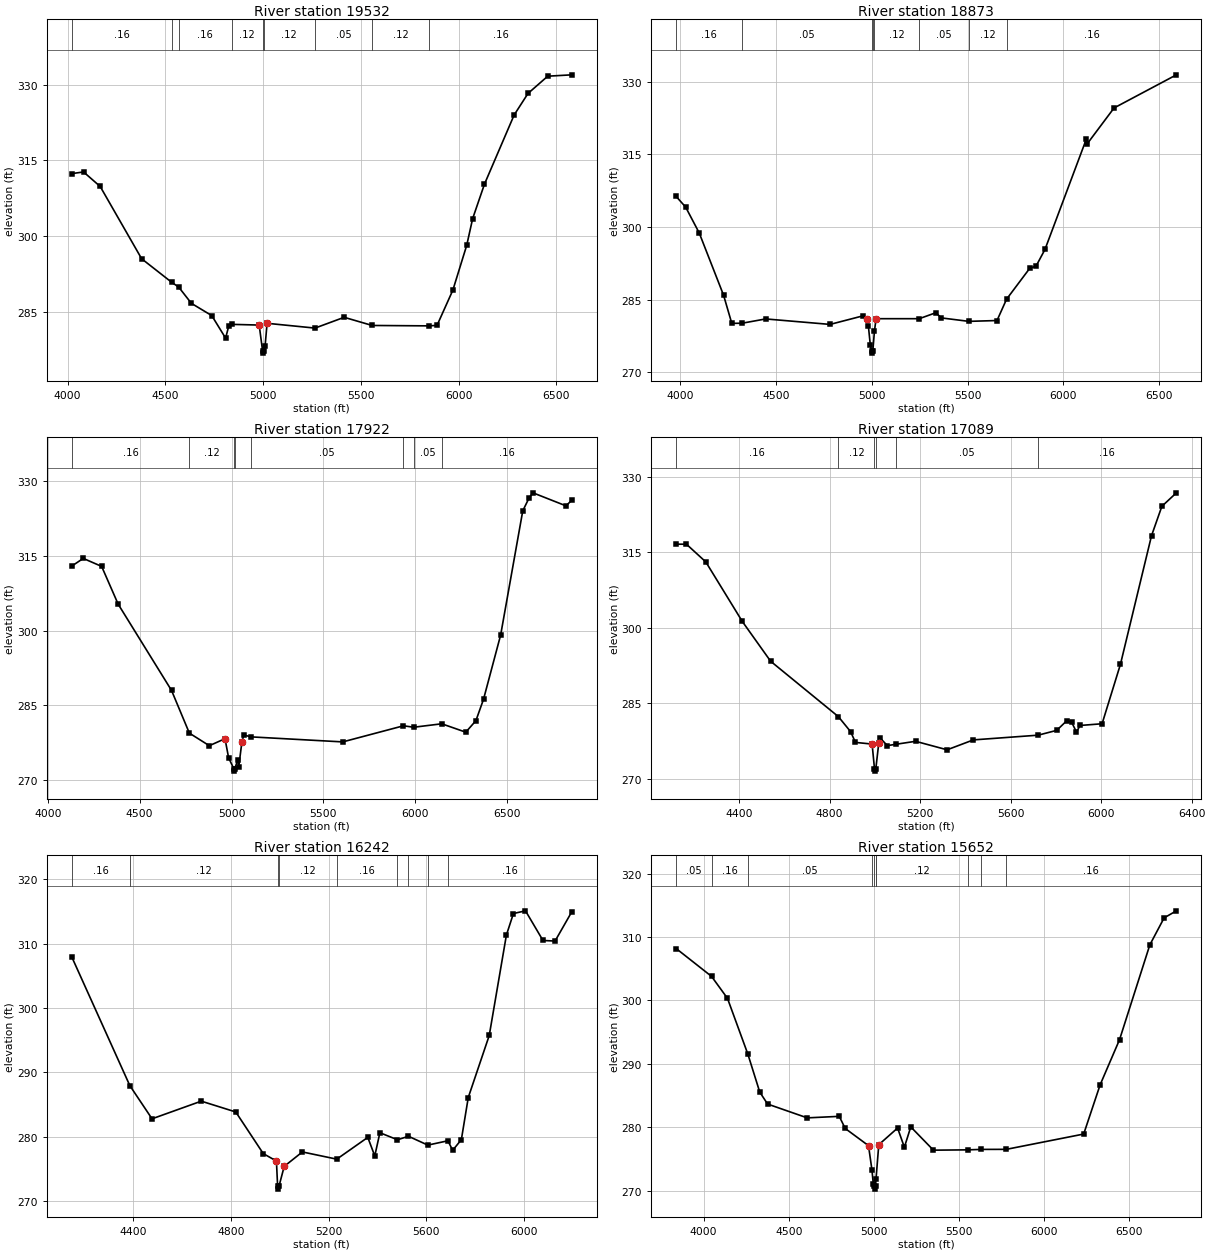
Type RM Length L Ch R = 1 ,19532   ,659,659,659
BEGIN DESCRIPTION:
CAMP CREEK 21.0
END DESCRIPTION:
XS GIS Cut Line= 3
      3564924.93     10374200.31      3565376.29     10373714.23
      3565654.07     10371839.22
#Sta/Elev= 30
  4020.7  312.39  4081.5  312.72  4166.5  309.84  4378.6  295.49  4531.9  290.83
    4568  289.87  4633.1  286.64  4737.2  284.21    4808  279.74  4824.6  282.21
  4839.8  282.47  4979.8  282.33    4997  277.26  4999.8  276.76    5003  277.26
  5010.1  278.22  5020.2  282.68  5265.2  281.73  5414.5  283.87  5557.8  282.25
    5849  282.17  5889.6  282.27  5970.5  289.27  6041.3  298.16  6071.6  303.45
  6132.2  310.31  6283.9  324.03  6354.7   328.3  6455.7  331.73  6579.5     332
#Mann= 9 ,-1 , 0
  4020.7     .16       0  4531.9     .05       0    4568     .16       0
  4839.8     .12       0    4997     .07       0    5003     .12       0
  5265.2     .05       0  5557.8     .12       0    5849     .16       0
Bank Sta=4979.8,5020.2
XS Rating Curve= 0 ,0
Exp/Cntr=0.3,0.1

Type RM Length L Ch R = 1 ,18873   ,951,951,951
BEGIN DESCRIPTION:
CAMP CREEK 20.0
END DESCRIPTION:
XS GIS Cut Line= 3
      3565442.08     10374341.66      3566018.65     10373809.71
      3565949.21     10371986.81
#Sta/Elev= 30
  3980.4  306.28    4030  304.08  4100.9  298.73  4227.9  285.87  4270.5  280.08
  4323.5   280.1  4447.4  280.99    4783  279.86  4953.1  281.61  4973.1  280.94
  4983.1  279.44  4993.1  275.54  5000.1  274.43  5002.9  273.93  5006.1  274.43
  5014.6  278.52  5023.1  281.04  5248.2  281.04  5334.6  282.27  5363.4   281.2
  5506.6  280.49  5653.6  280.66  5703.4  285.06  5823.7  291.41  5857.5  291.91
  5903.8  295.34  6118.9  318.06  6123.9  317.14    6264  324.55  6589.1  331.39
#Mann= 8 ,-1 , 0
  3980.4     .16       0  4323.5     .05       0  5000.1     .03       0
  5006.1     .05       0  5014.6     .12       0  5248.2     .05       0
  5506.6     .12       0  5703.4     .16       0
Bank Sta=4973.1,5023.1
XS Rating Curve= 0 ,0
Exp/Cntr=0.3,0.1

Type RM Length L Ch R = 1 ,17922   ,833,833,833
BEGIN DESCRIPTION:
CAMP CREEK 18.0
END DESCRIPTION:
XS GIS Cut Line= 3
      3566782.54     10374764.61      3566782.54     10374226.38
       3566218.3     10372116.97
#Sta/Elev= 30
  4130.3  312.93  4193.3  314.48  4293.3  312.88  4383.3   305.3  4673.6  288.01
  4770.6  279.45  4879.2  276.93  4964.5  278.33    4984  274.53    5012  272.33
  5014.8  271.83    5018  272.33  5034.2  274.15  5039.4  272.73  5056.4  277.67
  5066.8  279.09  5104.6   278.7  5605.1  277.69  5935.6  280.92  5991.5  280.63
  6143.8  281.32  6274.5  279.64  6329.7  281.95  6371.1  286.24  6464.3  299.13
  6584.6  324.02  6619.4  326.64  6640.2  327.63  6819.7  325.02  6852.1  326.18
#Mann= 8 ,-1 , 0
  4130.3     .16       0  4770.6     .12       0    5012     .07       0
    5018     .12       0  5104.6     .05       0  5935.6     .16       0
  5991.5     .05       0  6143.8     .16       0
Bank Sta=4964.5,5056.4
XS Rating Curve= 0 ,0
Exp/Cntr=0.3,0.1

Type RM Length L Ch R = 1 ,17089   ,847,847,847
BEGIN DESCRIPTION:
CAMP CREEK 17.0
END DESCRIPTION:
XS GIS Cut Line= 3
      3567554.59     10374095.43      3567404.61     10373695.46
      3566540.09     10372135.46
#Sta/Elev= 30
  4121.9   316.6  4167.5  316.59    4253  313.07  4414.3  301.23  4539.5  293.32
  4838.7  282.31  4892.7  279.33  4914.4  277.18  4987.9  276.85  4998.4  271.97
  5001.2  271.47  5004.4  271.97  5017.4  277.08  5023.2  278.07  5055.2  276.54
  5091.6   276.8    5180   277.4  5319.4  275.71  5435.3  277.68  5721.8  278.62
  5803.9  279.58  5847.4  281.46  5869.1  281.24  5891.1  279.24  5906.9  280.55
  6004.2  280.89  6085.4  292.72  6222.6  318.27  6268.4  324.13  6332.6  326.81
#Mann= 6 ,-1 , 0
  4121.9     .16       0  4838.7     .12       0  4998.4     .07       0
  5004.4     .12       0  5091.6     .05       0  5721.8     .16       0
Bank Sta=4987.9,5017.4
XS Rating Curve= 0 ,0
Exp/Cntr=0.3,0.1

Type RM Length L Ch R = 1 ,16242   ,590,590,590
BEGIN DESCRIPTION:
CAMP CREEK 15.0
END DESCRIPTION:
XS GIS Cut Line= 3
      3568092.09      10373641.6       3567737.4     10372646.52
      3566973.53     10372012.85
#Sta/Elev= 30
  4148.1  307.95  4386.3  287.95  4477.2   282.8  4678.9  285.54  4820.2  283.86
  4932.8   277.4  4986.7  276.25  4991.5  272.39  4994.2  271.89  4997.5  272.39
  5018.6  275.42  5092.9  277.66  5233.9  276.54  5360.9  279.92  5389.5  277.04
  5410.4  280.64  5482.5  279.55  5527.5  280.09  5606.8  278.72  5688.9  279.39
  5708.6  277.92  5744.1  279.56  5772.4   286.1  5858.3  295.73  5928.6  311.31
  5957.3  314.65  6006.8  315.07  6078.4  310.47  6127.9  310.38    6197  314.96
#Mann= 9 ,-1 , 0
  4148.1     .16       0  4386.3     .12       0  4991.5     .07       0
  4997.5     .12       0  5233.9     .16       0  5482.5     .12       0
  5527.5     .16       0  5606.8     .12       0  5688.9     .16       0
Bank Sta=4986.7,5018.6
XS Rating Curve= 0 ,0
Exp/Cntr=0.3,0.1

Type RM Length L Ch R = 1 ,15652   ,962,962,962
BEGIN DESCRIPTION:
CAMP CREEK 14.0
END DESCRIPTION:
XS GIS Cut Line= 3
      3568142.11     10373641.64      3568466.57     10372932.98
      3567546.78      10370980.6
#Sta/Elev= 30
  3838.5  308.19  4046.3   303.8  4139.9  300.34    4260  291.52  4329.4  285.57
  4375.4  283.68  4608.4   281.5  4796.3  281.74  4831.4  279.83  4968.1  277.12
  4988.2  273.32  4996.4  271.05  5003.3  270.77    5006  270.27  5009.3  270.77
  5012.5  271.94  5028.4  277.27  5138.9   279.9  5178.7  276.87  5216.3  280.08
  5349.3  276.41  5551.6  276.46    5630  276.53  5777.5  276.54  6231.7  278.95
  6328.4  286.72  6442.3  293.83  6620.2  308.77    6704  313.02  6776.1  314.13
#Mann= 10 ,-1 , 0
  3838.5     .05       0  4046.3     .16       0    4260     .05       0
  4988.2     .16       0  5003.3     .07       0  5009.3     .16       0
  5012.5     .12       0  5551.6     .07       0    5630     .12       0
  5777.5     .16       0
Bank Sta=4968.1,5028.4
XS Rating Curve= 0 ,0
Exp/Cntr=0.3,0.1

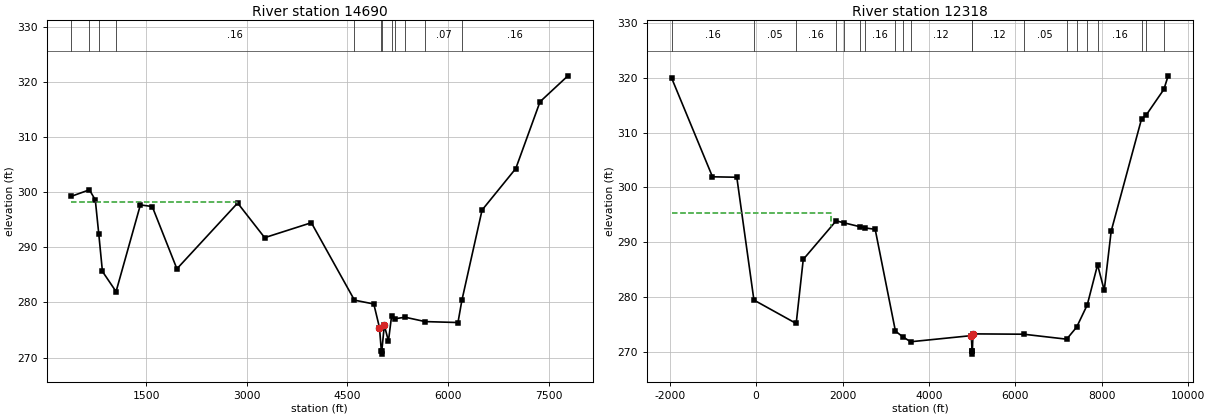
Type RM Length L Ch R = 1 ,14690   ,2372,2372,2372
BEGIN DESCRIPTION:
CAMP CREEK 11.0
END DESCRIPTION:
XS GIS Cut Line= 3
       3566904.1     10375875.66      3569351.99     10373601.38
      3568432.25      10369644.8
#Sta/Elev= 30
   384.7  299.25     652  300.42   739.8  298.58     792  292.38   846.1  285.62
  1049.6  281.96  1412.1  297.68    1589  297.39  1956.9  286.09  2862.8  298.02
  3265.9  291.74  3961.9  294.45  4604.7  280.41  4893.5  279.71  4978.3  275.41
  5006.1  271.12  5008.8  270.62  5012.1  271.12  5050.2  275.86  5111.7  272.98
  5158.2  277.49  5203.2  277.03  5361.7  277.31  5659.6  276.52  6148.7  276.35
  6207.1  280.38    6508  296.75  7010.9  304.28  7372.4  316.39  7788.1  321.09
#Mann= 12 ,-1 , 0
   384.7     .16       0     652      .1       0     792     .15       0
  1049.6     .16       0  4604.7     .12       0  5006.1     .07       0
  5012.1     .12       0  5158.2     .05       0  5203.2     .16       0
  5361.7     .12       0  5659.6     .07       0  6207.1     .16       0
#XS Ineff= 2 , 0
         2854.55  298.16
Permanent Ineff=
       F       F
Bank Sta=4978.3,5050.2
XS Rating Curve= 0 ,0
Exp/Cntr=0.3,0.1

Type RM Length L Ch R = 1 ,12318   ,0,0,0
BEGIN DESCRIPTION:
CAMP CREEK 1.0
END DESCRIPTION:
XS GIS Cut Line= 4
      3565766.91     10376908.67       3570506.5     10374096.17
      3571183.58     10372533.67      3569569.26     10368575.99
#Sta/Elev= 30
 -1953.2  319.92 -1009.9  301.92  -447.1  301.84   -51.1   279.4   927.3  275.12
  1090.8  286.83  1851.3  293.87  2040.9   293.5  2413.4  292.78  2517.9  292.58
  2755.1  292.33  3223.8  273.73  3387.7  272.72  3575.6  271.78  4979.8   272.9
  4998.6  270.02  5001.3  269.52  5004.6  270.02  5018.1  273.22  6188.5  273.16
  7186.4  272.25  7418.4  274.46  7663.5  278.52  7902.1  285.84  8056.5  281.17
    8217  291.99  8918.9  312.47  9031.5  313.25    9437   317.9  9535.2  320.37
#Mann= 20 ,-1 , 0
 -1953.2     .16       0   -51.1     .05       0   927.3     .16       0
  1851.3     .12       0  2040.9     .16       0  2413.4     .05       0
  2517.9     .16       0  3223.8     .07       0  3387.7     .05       0
  3575.6     .12       0  4998.6     .07       0  5004.6     .12       0
  6188.5     .05       0  7186.4     .16       0  7418.4     .12       0
  7663.5     .05       0  7902.1     .16       0  8918.9      .1       0
  9031.5      .1       0    9437     .16       0
#XS Ineff= 2 , 0
         1722.73  295.22
Permanent Ineff=
       F       F
Bank Sta=4979.8,5018.1
XS Rating Curve= 0 ,0
Exp/Cntr=0.3,0.1

Chan Stop Cuts=-1
Use User Specified Reach Order=0
Composite Channel Slope=5