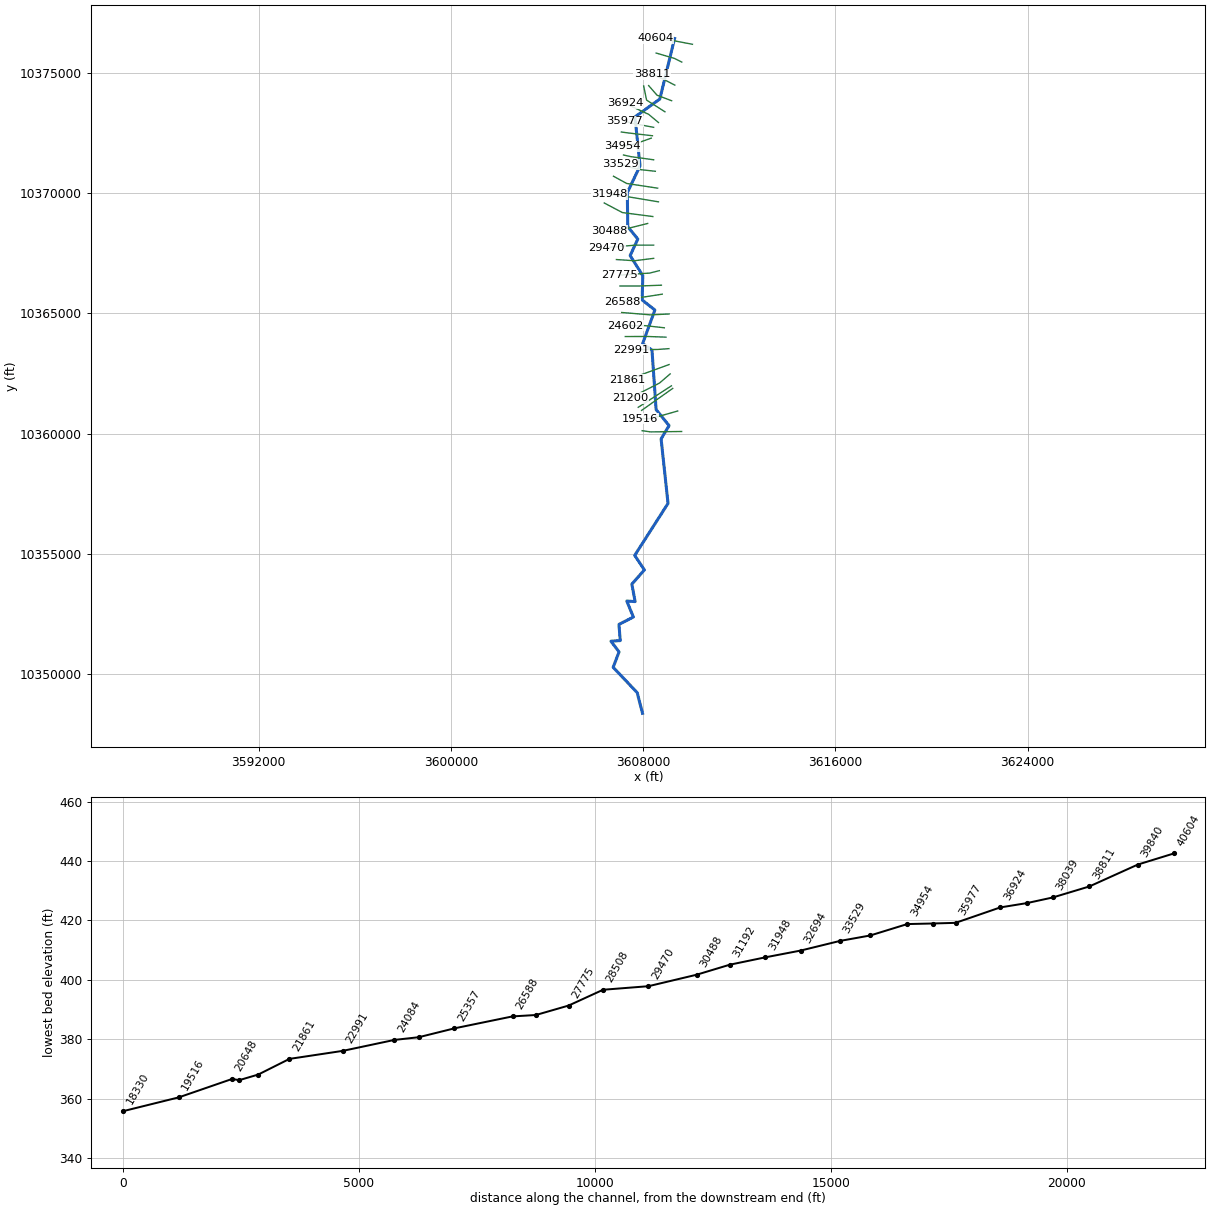
--- CARRYALL CREEK.prj (project) ---

Proj Title=CARRYALL CREEK Base Level Engineering
Current Plan=p01
Default Exp/Contr=0.3,0.1
English Units
Geom File=g01
Flow File=f01
Plan File=p01
Y Axis Title=Elevation
X Axis Title(PF)=Main Channel Distance
X Axis Title(XS)=Station
BEGIN DESCRIPTION:
CARRYALL CREEK
END DESCRIPTION:
DSS Export Rating Curves= 0
DSS Export Rating Curve Sorted= 0
DSS Export Volume Flow Curves= 0
DXF OffsetX= 0
DXF OffsetY= 0
DXF ScaleX= 1
DXF ScaleY= 10

--- CARRYALL CREEK.p01 (plan) ---

Plan Title=Multiple Run
Short Identifier=Multiple
Geom File=g01
Flow File=f01
Subcritical Flow
K Sum by GR= 0
Std Step Tol= 0.01
Critical Tol= 0.01
Num of Std Step Trials= 20
Max Error Tol= 0.3
Flow Tol Ratio= 0.001
Split Flow NTrial= 30
Split Flow Tol= 0.02
Split Flow Ratio= 0.02
Log Output Level= 0
Friction Slope Method= 1
Unsteady Friction Slope Method= 2
Unsteady Bridges Friction Slope Method= 1
Parabolic Critical Depth
Global Vel Dist=  1 , 1 , 1
Global Log Level= 0
CheckData=True
Encroach Param= -1, 0, 0, 0
BEGIN DESCRIPTION:
Multiple Run
END DESCRIPTION:

--- CARRYALL CREEK.f01 (steady flow) ---

Flow Title=Multiple
Program Version=4.10
Number of Profiles= 7
Profile Names=10-year,25-year,50-year,1pct_min,100-year,1pct_plu,500-year
River Rch & RM=CARRYALL CREEK,Reach-1         ,40604
    1276    1776    2195    1979    2677    3620    3967
River Rch & RM=CARRYALL CREEK,Reach-1         ,35977
    2090    2980    3742    3423    4629    6260    7061
River Rch & RM=CARRYALL CREEK,Reach-1         ,31948
    2566    3700    4680    4310    5828    7882    9014
River Rch & RM=CARRYALL CREEK,Reach-1         ,30488
    3032    4389    5567    5134    6944    9391   10778
River Rch & RM=CARRYALL CREEK,Reach-1         ,20648
    3268    4740    6018    5556    7514   10162   11684
River Rch & RM=CARRYALL CREEK,Reach-1         ,12885
    3268    4734    6005    5537    7488   10126   11617
River Rch & RM=CARRYALL CREEK,Reach-1         ,9141
    3834    5580    7102    6567    8881   12011   13860
River Rch & RM=CARRYALL CREEK,Reach-1         ,7436
    3834    5580    7102    6567    8881   12011   13860
Boundary for River Rch & Prof#=CARRYALL CREEK,Reach-1         , 1
Up Type= 0
Dn Type= 3
Dn Slope=0.005
Boundary for River Rch & Prof#=CARRYALL CREEK,Reach-1         , 2
Up Type= 0
Dn Type= 3
Dn Slope=0.005
Boundary for River Rch & Prof#=CARRYALL CREEK,Reach-1         , 3
Up Type= 0
Dn Type= 3
Dn Slope=0.005
Boundary for River Rch & Prof#=CARRYALL CREEK,Reach-1         , 4
Up Type= 0
Dn Type= 3
Dn Slope=0.005
Boundary for River Rch & Prof#=CARRYALL CREEK,Reach-1         , 5
Up Type= 0
Dn Type= 3
Dn Slope=0.005
Boundary for River Rch & Prof#=CARRYALL CREEK,Reach-1         , 6
Up Type= 0
Dn Type= 3
Dn Slope=0.005
Boundary for River Rch & Prof#=CARRYALL CREEK,Reach-1         , 7
Up Type= 0
Dn Type= 3
Dn Slope=0.005
DSS Import GetInterval= 0
DSS Import GetPeak= 0
DSS Import FillOption= 0

--- CARRYALL CREEK.g01 (geometry) ---

Geom Title=Existing Conditions
Program Version=4.10

River Reach=CARRYALL CREEK  ,Reach-1
Reach XY= 30
      3609312.46     10376436.51      3608698.47     10373918.43
      3607663.59     10373175.49      3607875.86     10371138.77
      3607345.87     10370024.89      3607363.76     10368607.09
      3607782.88      10368095.1      3607464.15     10367407.67
      3607989.59     10366570.42      3607963.95     10365559.18
      3608492.59     10365141.82      3607983.67     10363746.73
      3608372.25     10363475.03      3608544.49     10360998.95
      3609083.38     10360334.11      3608751.61     10359781.53
      3609039.77     10357097.44      3607654.13     10354936.17
      3608056.63     10354331.44      3607534.76     10353740.52
      3607670.52     10353012.85      3607324.63     10353036.13
      3607597.78     10352371.63      3606997.56     10352064.44
      3607051.62     10351391.82      3606665.01     10351366.59
      3607001.27     10350921.35      3606757.09     10350279.12
      3607756.39     10349227.39      3607978.18     10348367.27

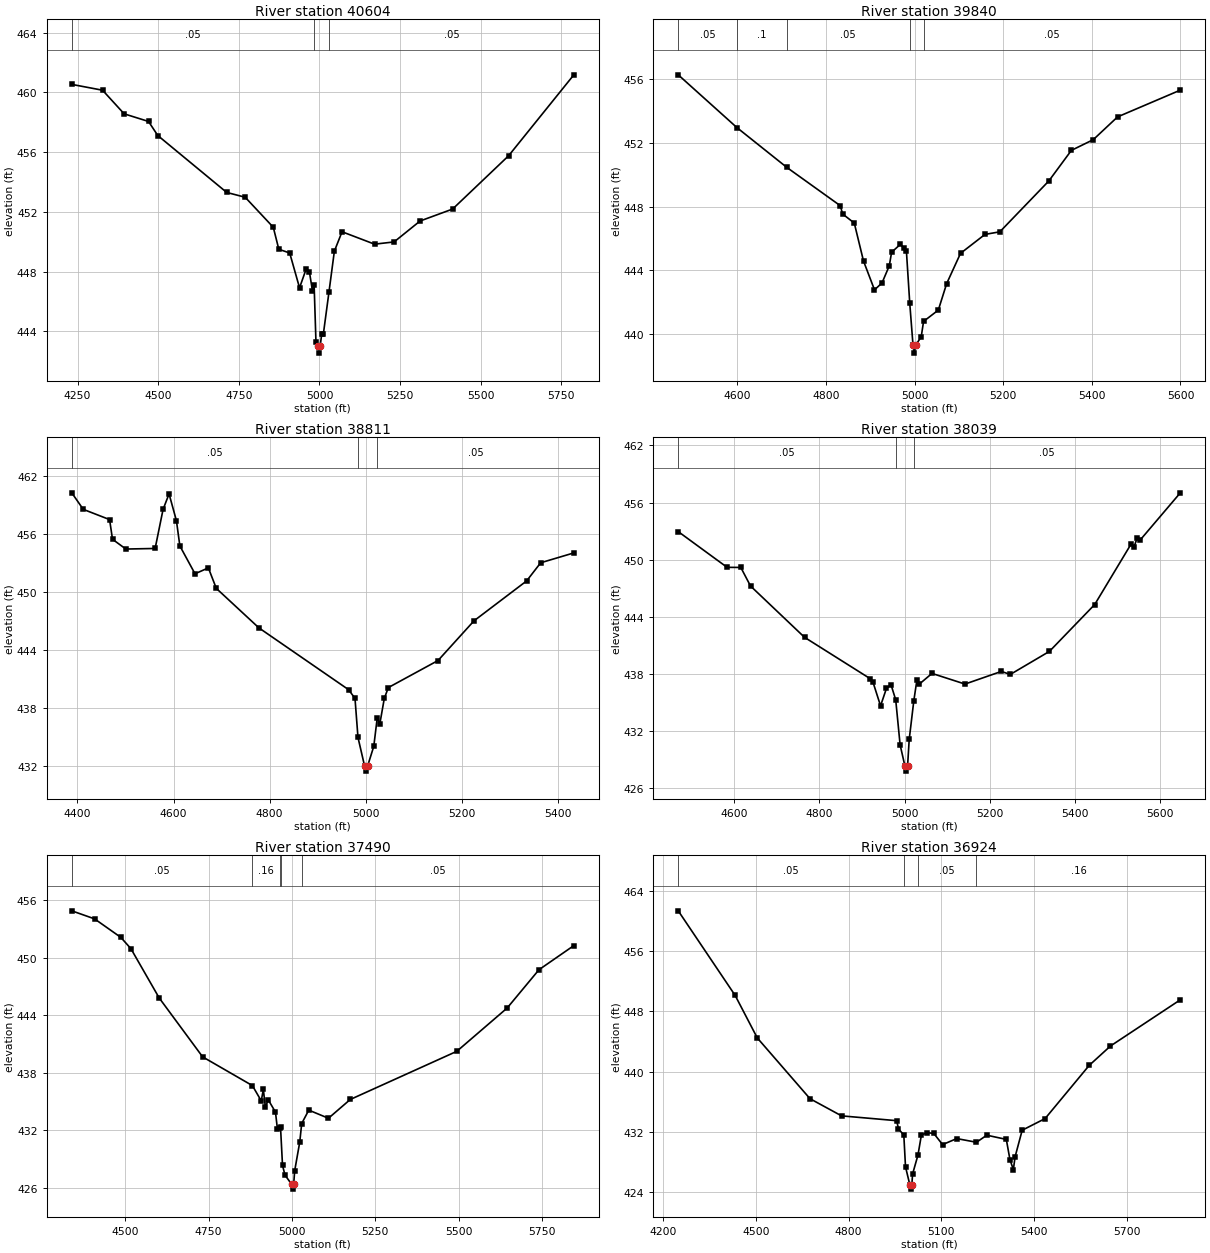
Type RM Length L Ch R = 1 ,40604   ,764,764,764
BEGIN DESCRIPTION:
CARRYALL CREEK 75.0
END DESCRIPTION:
XS GIS Cut Line= 3
      3610055.92     10376196.13      3609292.11     10376341.64
      3608519.45     10376443.53
#Sta/Elev= 30
  4231.9  460.53  4327.4  460.14  4394.3  458.56  4469.9  458.05  4498.6  457.11
  4712.4   453.3  4769.6  452.98  4856.8  450.97  4873.9   449.5  4907.7  449.25
  4938.2  446.92  4958.6  448.17  4968.7     448  4978.3  446.72  4983.4  447.12
  4989.1  443.31  4996.3  443.05    4999  442.55  5002.3  443.05  5006.9  443.82
    5012  443.82  5029.6  446.66  5046.2  449.37    5070  450.67  5170.8  449.84
  5231.4  449.99    5312  451.39  5412.9  452.19  5586.3  455.75  5788.8  461.17
#Mann= 3 ,-1 , 0
  4231.9     .05       0  4983.4     .03       0  5029.6     .05       0
Bank Sta=4996.3,5002.3
XS Rating Curve= 0 ,0
Exp/Cntr=0.3,0.1

Type RM Length L Ch R = 1 ,39840   ,1029,1029,1029
BEGIN DESCRIPTION:
CARRYALL CREEK 73.0
END DESCRIPTION:
XS GIS Cut Line= 3
       3609611.4     10375456.74      3609311.38     10375606.75
      3608546.28     10375831.31
#Sta/Elev= 30
  4466.8  456.27  4599.2  452.96  4711.9  450.46  4832.4  448.06  4837.7  447.54
    4864  446.97  4884.8  444.59  4909.6  442.78  4926.5  443.21    4943  444.29
  4948.2  445.14  4968.2  445.64  4976.4  445.39  4981.6  445.22  4989.1  441.96
  4996.5  439.31  4999.2  438.81  5002.5  439.31    5015  439.83  5020.3   440.8
  5053.6  441.51  5072.4  443.17  5103.7  445.07    5159  446.26  5192.4  446.42
  5302.9  449.61  5353.8  451.53  5403.1   452.2    5458  453.63  5599.6  455.31
#Mann= 5 ,-1 , 0
  4466.8     .05       0  4599.2      .1       0  4711.9     .05       0
  4989.1     .03       0  5020.3     .05       0
Bank Sta=4996.5,5002.5
XS Rating Curve= 0 ,0
Exp/Cntr=0.3,0.1

Type RM Length L Ch R = 1 ,38811   ,772,772,772
BEGIN DESCRIPTION:
CARRYALL CREEK 71.0
END DESCRIPTION:
XS GIS Cut Line= 3
      3609322.06     10374497.57      3608812.49     10374760.25
      3608382.55     10374954.31
#Sta/Elev= 30
  4388.1  460.24    4412  458.53  4466.8  457.47  4472.9  455.43  4500.7  454.42
  4561.6  454.48  4578.1  458.52  4590.6  460.13  4605.9  457.36  4613.1  454.74
  4644.6  451.86  4672.4  452.47  4688.9  450.35  4777.6  446.26  4964.3  439.86
  4977.6  438.96  4983.8  434.92  4997.7  431.93  5000.5  431.43  5003.7  431.93
  5016.7     434  5023.9  436.95  5029.3  436.33  5038.6  438.96    5047  440.08
  5150.4  442.88  5225.3  446.99  5334.8  451.12  5364.1     453  5433.1  454.02
#Mann= 3 ,-1 , 0
  4388.1     .05       0  4983.8     .03       0  5023.9     .05       0
Bank Sta=4997.7,5003.7
XS Rating Curve= 0 ,0
Exp/Cntr=0.3,0.1

Type RM Length L Ch R = 1 ,38039   ,549,549,549
BEGIN DESCRIPTION:
CARRYALL CREEK 69.0
END DESCRIPTION:
XS GIS Cut Line= 3
      3609189.53     10373848.06      3608583.65     10374076.78
      3608233.73     10374476.69
#Sta/Elev= 30
  4468.4  452.94  4583.2  449.18  4615.3  449.17  4638.1  447.22  4764.9  441.82
  4918.7  437.48  4925.3  437.16  4943.5  434.61  4957.3  436.44    4968  436.84
  4979.1  435.24  4989.4  430.51  5000.9  428.24  5003.7  427.74  5006.9  428.24
  5010.8  431.08  5021.5  435.11  5028.7  437.28  5034.1  436.88  5064.3  438.02
  5141.8   436.9  5227.2  438.23  5248.1  437.91  5340.1  440.34  5446.4  445.27
  5531.9  451.64  5538.5  451.31  5546.1  452.26  5552.7  452.03  5647.4  457.02
#Mann= 3 ,-1 , 0
  4468.4     .05       0  4979.1     .03       0  5021.5     .05       0
Bank Sta=5000.9,5006.9
XS Rating Curve= 0 ,0
Exp/Cntr=0.3,0.1

Type RM Length L Ch R = 1 ,37490   ,566,566,566
BEGIN DESCRIPTION:
CARRYALL CREEK 68.0
END DESCRIPTION:
XS GIS Cut Line= 3
      3608911.75       10373388.      3608147.89     10373874.09
      3608026.74     10374462.54
#Sta/Elev= 30
  4339.8   454.9  4408.2  454.06  4486.9  452.13  4517.2  450.95  4602.1   445.8
  4732.4  439.65  4881.7  436.65  4908.3  435.05  4914.5  436.26  4920.4  434.44
  4929.7  435.14  4950.9  433.88  4956.8   432.1  4965.2  432.26  4966.1  432.28
    4972  428.33  4979.4  427.31  4999.5  426.34  5002.3  425.84  5005.5  426.34
  5008.5  427.75  5023.7  430.75  5029.6  432.69  5050.8  434.09  5109.8  433.24
  5175.2   435.2  5494.9  440.23  5645.9  444.75  5741.4  448.75    5846  451.27
#Mann= 5 ,-1 , 0
  4339.8     .05       0  4881.7     .16       0  4965.2     .05       0
  4966.1     .03       0  5029.6     .05       0
Bank Sta=4999.5,5005.5
XS Rating Curve= 0 ,0
Exp/Cntr=0.3,0.1

Type RM Length L Ch R = 1 ,36924   ,947,947,947
BEGIN DESCRIPTION:
CARRYALL CREEK 67.0
END DESCRIPTION:
XS GIS Cut Line= 3
      3608642.14     10372941.61      3608235.09     10373280.82
      3607242.07     10373741.66
#Sta/Elev= 30
  4248.9  461.38  4433.1  450.13  4504.7  444.48  4675.3   436.4  4777.4  434.12
  4955.9  433.48  4961.4  432.39  4978.8  431.58  4984.3  427.35  4998.7  424.88
  5001.5  424.38  5004.7  424.88  5007.2  426.39  5024.6  428.91  5035.6  431.55
    5053   431.9  5075.9  431.78  5104.3   430.3  5150.1   431.1    5214  430.61
  5247.3  431.55  5310.5  430.99  5322.2  428.31  5333.3  426.98  5338.9  428.68
  5361.8  432.21    5436  433.76  5578.9  440.84  5647.6  443.41  5873.5  449.55
#Mann= 4 ,-1 , 0
  4248.9     .05       0  4978.8     .03       0  5024.6     .05       0
    5214     .16       0
Bank Sta=4998.7,5004.7
XS Rating Curve= 0 ,0
Exp/Cntr=0.3,0.1

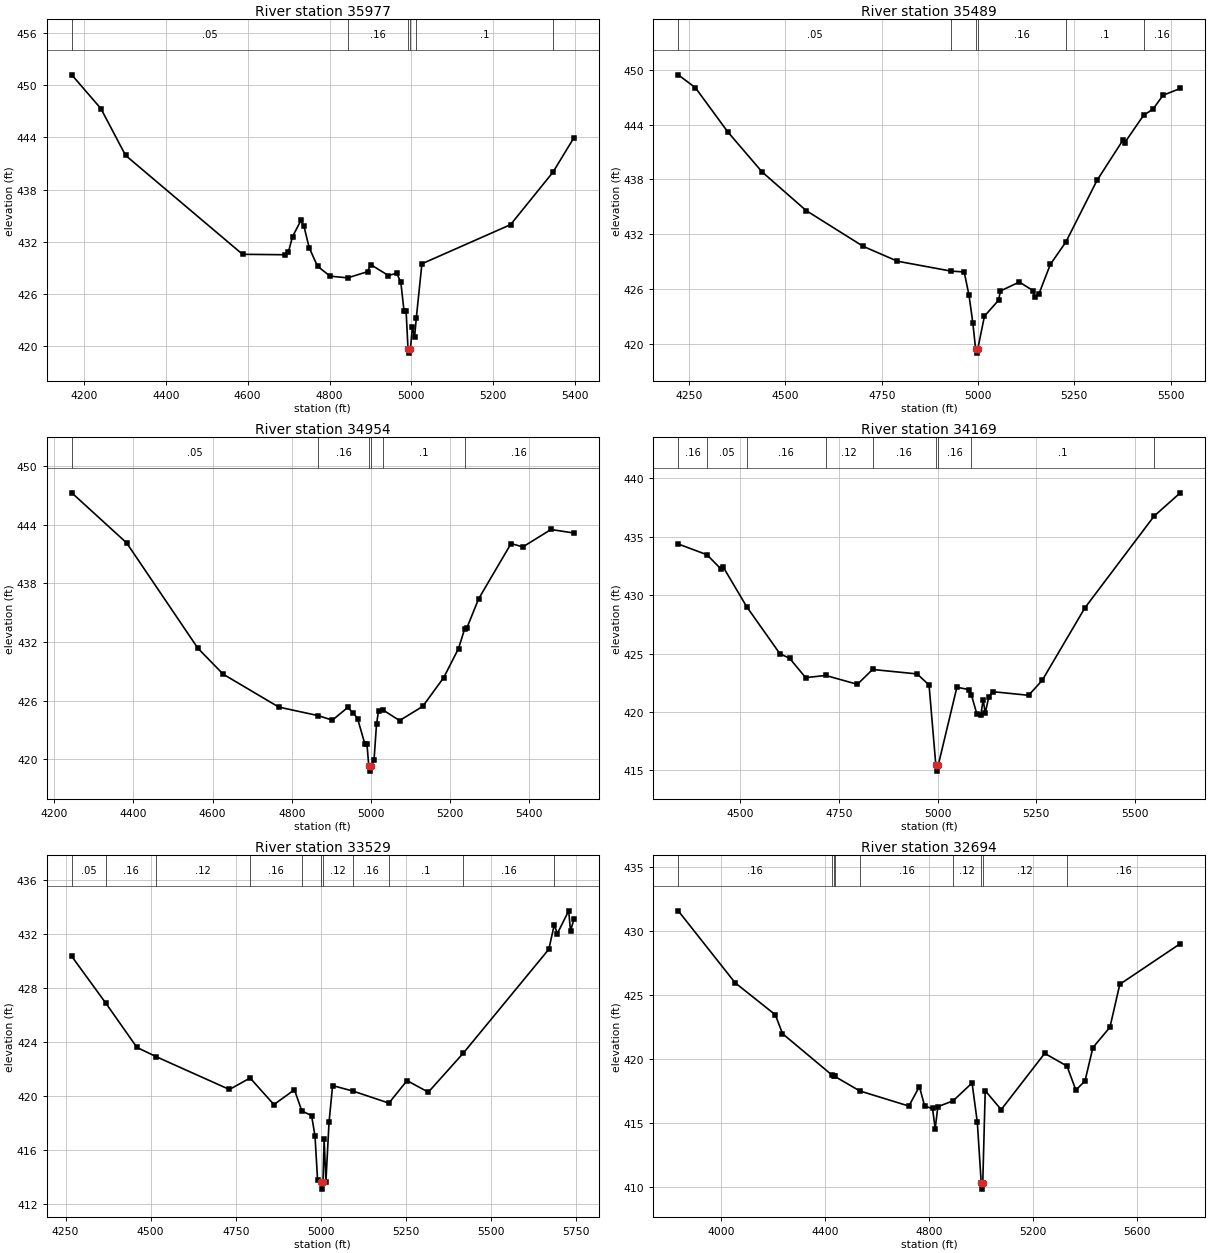
Type RM Length L Ch R = 1 ,35977   ,488,488,488
BEGIN DESCRIPTION:
CARRYALL CREEK 65.0
END DESCRIPTION:
XS GIS Cut Line= 3
      3608442.07     10372741.65      3607642.11     10372891.64
      3607242.12     10372991.64
#Sta/Elev= 30
  4170.5  451.21  4241.7  447.32  4301.9  441.94  4587.6  430.56  4690.2  430.51
  4699.5  430.82  4709.7  432.59  4730.1  434.46  4737.7  433.76  4750.4  431.31
  4770.7  429.19  4801.3  428.05  4844.3  427.85  4892.8  428.56  4900.5  429.38
  4943.7  428.12  4964.1  428.38  4974.2  427.33  4981.9  424.05    4987  424.05
  4991.7  419.69  4994.5  419.19  4997.7  419.69  5002.4  422.25  5007.6  420.99
  5011.9  423.21  5025.6  429.47  5242.1  433.97  5345.6     440  5396.7  443.96
#Mann= 6 ,-1 , 0
  4170.5     .05       0  4844.3     .16       0  4991.7     .07       0
  4997.7     .16       0  5011.9      .1       0  5345.6     .16       0
Bank Sta=4991.7,4997.7
XS Rating Curve= 0 ,0
Exp/Cntr=0.3,0.1

Type RM Length L Ch R = 1 ,35489   ,535,535,535
BEGIN DESCRIPTION:
CARRYALL CREEK 64.0
END DESCRIPTION:
XS GIS Cut Line= 3
      3608392.06     10372391.65      3607427.17     10372502.41
      3607097.56     10372545.96
#Sta/Elev= 30
  4221.7  449.46  4266.2  448.05  4350.3  443.21  4439.5  438.82  4553.8  434.59
  4701.9  430.67    4791  429.04  4929.4  427.96  4964.2  427.86  4976.6  425.34
  4986.6  422.31  4993.7  419.47  4996.5  418.97  4999.7  419.47  5016.8  423.02
  5053.4  424.76  5058.4  425.78  5107.4  426.76  5142.5  425.83  5147.7  425.14
  5157.8  425.41  5187.9  428.69  5228.5  431.16    5309  437.89  5376.2  442.29
  5381.3  442.04  5429.9  445.02  5454.7  445.71  5480.5  447.22  5525.4  447.97
#Mann= 6 ,-1 , 0
  4221.7     .05       0  4929.4     .16       0  4993.7     .07       0
  4999.7     .16       0  5228.5      .1       0  5429.9     .16       0
Bank Sta=4993.7,4999.7
XS Rating Curve= 0 ,0
Exp/Cntr=0.3,0.1

Type RM Length L Ch R = 1 ,34954   ,785,785,785
BEGIN DESCRIPTION:
CARRYALL CREEK 63.0
END DESCRIPTION:
XS GIS Cut Line= 3
      3608342.15     10372291.66      3607642.11     10372041.64
      3607125.39     10371947.34
#Sta/Elev= 30
  4244.2  447.24  4382.8  442.12  4562.8  431.35  4626.5   428.7  4767.2  425.33
  4867.5  424.45  4902.6  423.99  4941.4  425.29  4955.7  424.72  4966.3  424.16
  4984.9  421.54  4990.1  421.54  4994.7  419.28  4997.5  418.78  5000.7  419.28
  5007.9   419.9  5014.2  423.58  5019.3  424.95  5030.4  425.04  5072.5  423.95
  5130.9   425.4  5184.1  428.35  5221.4  431.32  5237.2  433.36  5242.5  433.42
  5272.2   436.4  5354.1  442.05    5384  441.71  5455.1  443.49  5512.8  443.13
#Mann= 6 ,-1 , 0
  4244.2     .05       0  4867.5     .16       0  4994.7     .07       0
  5000.7     .16       0  5030.4      .1       0  5237.2     .16       0
Bank Sta=4994.7,5000.7
XS Rating Curve= 0 ,0
Exp/Cntr=0.3,0.1

Type RM Length L Ch R = 1 ,34169   ,640,640,640
BEGIN DESCRIPTION:
CARRYALL CREEK 61.0
END DESCRIPTION:
XS GIS Cut Line= 3
       3608442.1     10371391.64      3607504.28     10371520.01
      3607185.71      10371590.8
#Sta/Elev= 30
  4342.3  434.38  4415.2  433.46  4450.6  432.24  4455.6  432.45  4515.5  429.03
    4600  424.99  4624.9  424.59  4665.3  422.94    4716  423.13  4796.5  422.37
    4835  423.64  4947.9  423.26  4978.2  422.31  4995.4  415.44  4998.1  414.94
  5001.4  415.44  5048.8  422.12  5079.1  421.92  5085.6  421.46  5099.3  419.84
  5109.4  419.75  5115.5  421.07  5120.5   419.9  5129.6  421.28  5139.7  421.74
  5230.5  421.43  5264.9   422.7    5373   428.9  5548.8  436.77  5615.2  438.76
#Mann= 9 ,-1 , 0
  4342.3     .16       0  4415.2     .05       0  4515.5     .16       0
    4716     .12       0    4835     .16       0  4995.4     .07       0
  5001.4     .16       0  5085.6      .1       0  5548.8     .16       0
Bank Sta=4995.4,5001.4
XS Rating Curve= 0 ,0
Exp/Cntr=0.3,0.1

Type RM Length L Ch R = 1 ,33529   ,835,835,835
BEGIN DESCRIPTION:
CARRYALL CREEK 60.0
END DESCRIPTION:
XS GIS Cut Line= 3
      3608512.45     10370914.03      3607792.11     10370991.64
      3607071.47     10371200.49
#Sta/Elev= 30
  4268.2  430.37  4367.4  426.93  4459.6  423.62  4516.4  422.93  4731.2   420.5
  4792.1  421.35    4862  419.38  4922.3  420.48  4944.1   418.9  4972.6  418.57
  4982.7  417.04  4990.2   413.8  5000.1  413.61  5002.9  413.11  5006.1  413.61
  5009.5  416.82  5014.7  413.67  5023.9  418.07  5034.4  420.79  5095.7  420.37
  5199.7  419.49    5253  421.16  5315.5   420.3  5418.8  423.21  5669.5   430.9
  5685.5  432.71  5694.4  432.06  5727.9  433.75  5733.2  432.26    5743  433.11
#Mann= 11 ,-1 , 0
  4268.2     .05       0  4367.4     .16       0  4516.4     .12       0
  4792.1     .16       0  4944.1     .12       0  5000.1     .07       0
  5006.1     .12       0  5095.7     .16       0  5199.7      .1       0
  5418.8     .16       0  5685.5      .1       0
Bank Sta=5000.1,5006.1
XS Rating Curve= 0 ,0
Exp/Cntr=0.3,0.1

Type RM Length L Ch R = 1 ,32694   ,746,746,746
BEGIN DESCRIPTION:
CARRYALL CREEK 58.0
END DESCRIPTION:
XS GIS Cut Line= 3
      3608607.94      10370210.9      3607320.58     10370406.57
      3606770.62     10370706.55
#Sta/Elev= 30
  3836.1  431.57  4054.4  425.96  4209.1  423.46  4236.5  421.99  4428.3  418.73
    4433   418.7  4437.7  418.65  4533.5  417.52    4722  416.34  4762.5  417.86
  4782.7  416.33    4813  416.15  4823.1  414.56  4833.3  416.29  4891.9  416.75
  4964.8  418.14    4985  415.06  4999.9  410.36  5002.6  409.86  5005.9  410.36
  5015.3  417.54  5076.6  416.06  5243.8  420.45  5329.4  419.46  5363.4  417.59
  5398.5  418.29  5428.9   420.9  5494.4  422.49  5532.3  425.84  5764.7  429.01
#Mann= 9 ,-1 , 0
  3836.1     .16       0  4428.3      .1       0    4433     .16       0
  4437.7      .1       0  4533.5     .16       0  4891.9     .12       0
  4999.9     .07       0  5005.9     .12       0  5329.4     .16       0
Bank Sta=4999.9,5005.9
XS Rating Curve= 0 ,0
Exp/Cntr=0.3,0.1

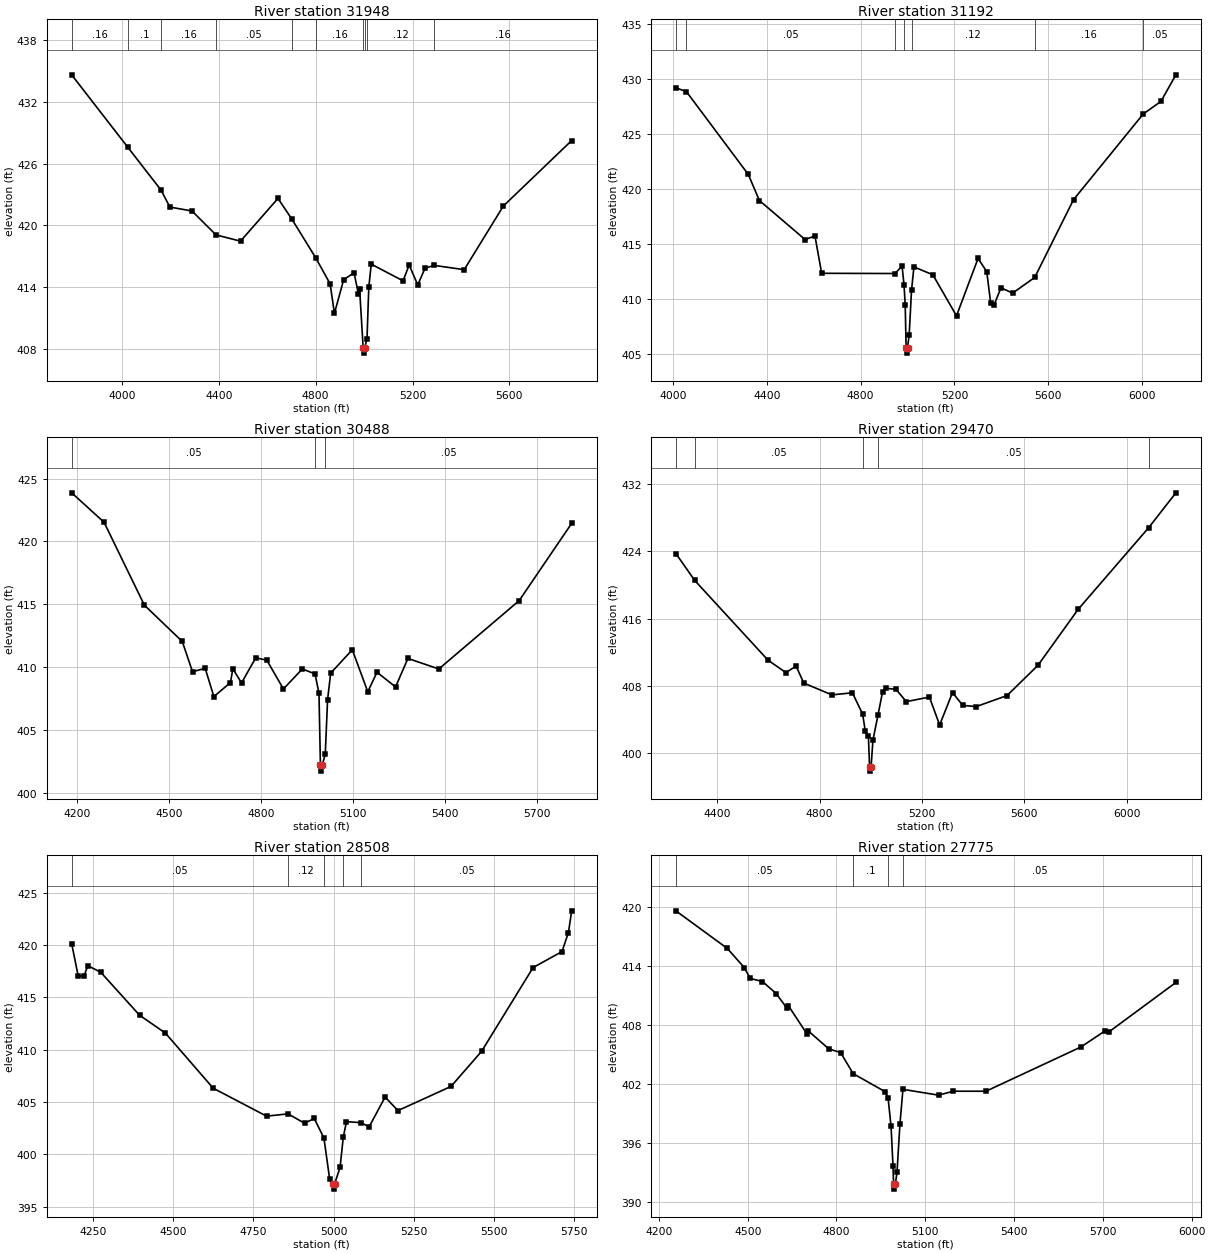
Type RM Length L Ch R = 1 ,31948   ,756,756,756
BEGIN DESCRIPTION:
CARRYALL CREEK 57.0
END DESCRIPTION:
XS GIS Cut Line= 3
      3608642.09     10369641.64      3607442.11     10369841.64
      3606602.73     10369959.16
#Sta/Elev= 30
    3793  434.61  4024.3  427.59  4161.6  423.43  4198.5  421.77  4289.7  421.39
  4388.8  419.07    4490  418.46  4644.6  422.61  4702.3  420.59  4801.3  416.81
    4860  414.31  4877.7  411.45  4915.8  414.72  4958.8  415.39  4976.6  413.35
  4981.7  413.78  4996.4  408.09  4999.1  407.59  5002.4  408.09  5012.2  409.01
  5019.6     414  5029.7  416.23    5161  414.61  5186.2  416.15  5221.6  414.21
  5251.9  415.84  5289.8  416.11  5413.4  415.69    5575  421.87  5857.1  428.23
#Mann= 10 ,-1 , 0
    3793     .16       0  4024.3      .1       0  4161.6     .16       0
  4388.8     .05       0  4702.3     .12       0  4801.3     .16       0
  4996.4     .07       0  5002.4     .16       0  5012.2     .12       0
  5289.8     .16       0
Bank Sta=4996.4,5002.4
XS Rating Curve= 0 ,0
Exp/Cntr=0.3,0.1

Type RM Length L Ch R = 1 ,31192   ,704,704,704
BEGIN DESCRIPTION:
CARRYALL CREEK 55.0
END DESCRIPTION:
XS GIS Cut Line= 3
      3608408.34     10369030.34      3607140.83      10369195.8
      3606386.43     10369594.21
#Sta/Elev= 30
  4012.4  429.23  4057.4  428.88  4321.2  421.35  4368.4  418.98  4563.3  415.43
  4605.3  415.76  4633.9  412.36  4945.9  412.34  4976.7     413    4985  411.31
    4990  409.49  4993.9   405.6  4996.7   405.1  4999.9   405.6    5007  406.78
  5017.1  410.84  5027.2  412.94  5107.8  412.23  5208.7  408.49  5300.5  413.71
  5337.7  412.51  5354.1  409.69  5368.4  409.45  5398.1  411.04  5447.8  410.56
    5542  411.98  5707.6  419.06  6004.7  426.85    6080  427.99  6143.8  430.41
#Mann= 7 ,-1 , 0
  4012.4     .16       0  4057.4     .05       0  4945.9     .12       0
    4985     .03       0  5017.1     .12       0    5542     .16       0
  6004.7     .05       0
Bank Sta=4993.9,4999.9
XS Rating Curve= 0 ,0
Exp/Cntr=0.3,0.1

Type RM Length L Ch R = 1 ,30488   ,1018,1018,1018
BEGIN DESCRIPTION:
CARRYALL CREEK 54.0
END DESCRIPTION:
XS GIS Cut Line= 3
      3608192.08     10368741.64      3607392.11     10368541.64
      3606592.13     10368441.65
#Sta/Elev= 30
  4182.4  423.87    4288  421.53  4419.5  414.93  4543.1  412.04  4576.6  409.63
  4617.9   409.9  4646.2  407.65  4700.3  408.77  4708.1  409.87  4736.4  408.74
  4782.8  410.74  4818.9  410.55    4873  408.26  4934.8  409.85  4976.1  409.46
    4989  407.92  4993.7  402.22  4996.4  401.72  4999.7  402.22  5009.5  403.06
  5017.1  407.42  5027.2  409.52  5097.7  411.38  5148.1  408.04  5178.3  409.59
  5238.8  408.42  5279.1  410.69  5379.9  409.85  5641.9  415.29  5813.2  421.44
#Mann= 3 ,-1 , 0
  4182.4     .05       0  4976.1     .03       0  5009.5     .05       0
Bank Sta=4993.7,4999.7
XS Rating Curve= 0 ,0
Exp/Cntr=0.3,0.1

Type RM Length L Ch R = 1 ,29470   ,962,962,962
BEGIN DESCRIPTION:
CARRYALL CREEK 52.0
END DESCRIPTION:
XS GIS Cut Line= 3
      3608442.14     10367841.64      3607692.11     10367841.64
       3606492.1     10367741.64
#Sta/Elev= 30
  4238.2  423.73  4311.9  420.53  4598.2  411.06  4668.2  409.58  4708.2  410.35
  4738.2  408.33  4848.2  406.93  4928.2  407.18  4968.2  404.64  4978.2  402.69
  4990.7  402.02  4995.3  398.37    4998  397.87  5001.3  398.37  5008.3  401.53
  5028.4  404.57  5045.9  407.27  5058.5  407.71  5098.6  407.59  5138.8  406.13
  5229.1  406.67  5269.2  403.35  5319.4  407.21  5359.5  405.68  5412.2  405.54
  5532.6  406.85    5653  410.43  5811.1  417.12  6086.4  426.81  6192.4  430.94
#Mann= 5 ,-1 , 0
  4238.2     .16       0  4311.9     .05       0  4968.2     .03       0
  5028.4     .05       0  6086.4      .1       0
Bank Sta=4995.3,5001.3
XS Rating Curve= 0 ,0
Exp/Cntr=0.3,0.1

Type RM Length L Ch R = 1 ,28508   ,733,733,733
BEGIN DESCRIPTION:
CARRYALL CREEK 50.0
END DESCRIPTION:
XS GIS Cut Line= 3
      3608442.08     10367291.64      3607642.11     10367191.64
      3606892.07     10367241.64
#Sta/Elev= 30
  4183.8  420.12  4203.9  417.06  4221.6  416.98  4234.2  418.01  4274.5  417.38
  4395.4  413.28    4476  411.57  4624.7  406.31    4791  403.64  4858.2  403.86
  4909.4  402.96  4939.6  403.42  4969.8  401.55  4987.5  397.66    4997  397.17
  4999.8  396.67    5003  397.17  5020.1  398.75  5030.1  401.65  5040.1  403.11
  5085.6  403.02  5110.3  402.61  5160.4  405.46  5200.5  404.17  5365.8  406.48
    5461  409.83  5621.4  417.83  5711.6  419.36  5731.6  421.18  5741.7  423.25
#Mann= 5 ,-1 , 0
  4183.8     .05       0  4858.2     .12       0  4969.8     .03       0
  5030.1     .12       0  5085.6     .05       0
Bank Sta=4997,5003
XS Rating Curve= 0 ,0
Exp/Cntr=0.3,0.1

Type RM Length L Ch R = 1 ,27775   ,692,692,692
BEGIN DESCRIPTION:
CARRYALL CREEK 49.0
END DESCRIPTION:
XS GIS Cut Line= 3
      3608676.17      10366778.8      3608276.13      10366678.8
      3607002.09     10366591.11
#Sta/Elev= 30
  4257.3  419.65  4431.3  415.82  4488.3  413.88  4508.7  412.77  4549.9  412.46
  4596.3  411.23  4632.4  409.75  4637.5     410  4699.9  407.14  4704.9  407.43
  4773.9  405.61    4814  405.23  4856.2  403.09  4964.4  401.25  4974.4  400.59
  4984.4  397.72  4990.9  393.72  4992.9  391.84  4995.6  391.34  4998.9  391.84
  5004.5  393.07  5014.5     398  5024.5  401.49  5144.8   400.9  5194.9   401.3
  5305.2   401.3  5625.9   405.8  5706.1  407.41  5720.8  407.34  5946.7  412.36
#Mann= 4 ,-1 , 0
  4257.3     .05       0  4856.2      .1       0  4974.4     .03       0
  5024.5     .05       0
Bank Sta=4992.9,4998.9
XS Rating Curve= 0 ,0
Exp/Cntr=0.3,0.1

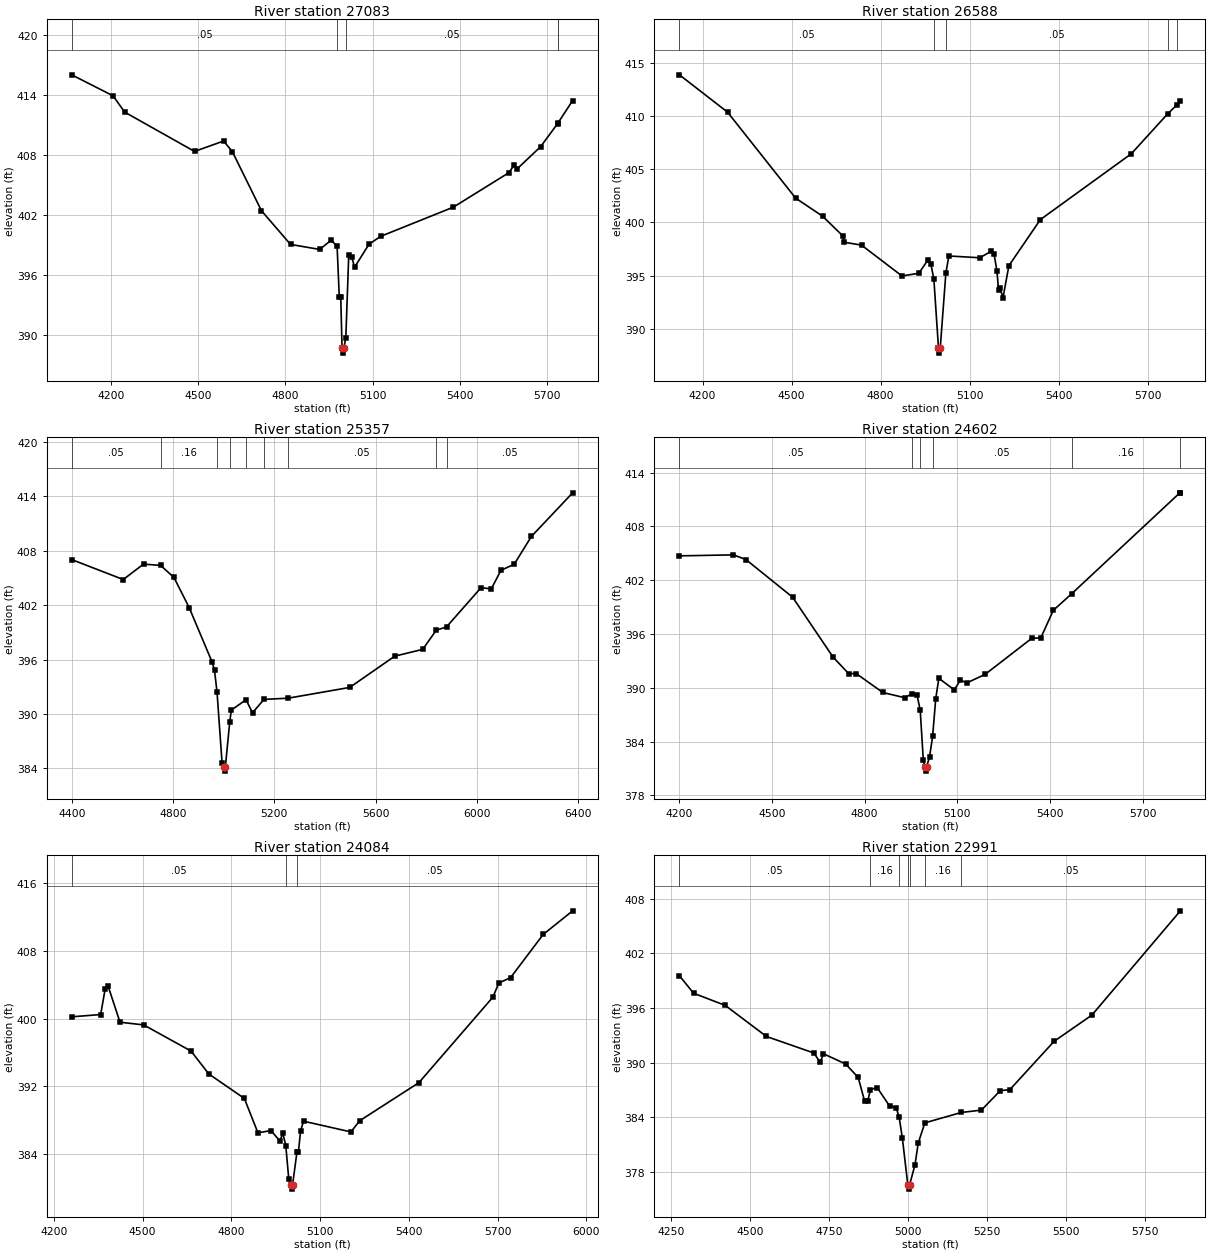
Type RM Length L Ch R = 1 ,27083   ,495,495,495
BEGIN DESCRIPTION:
CARRYALL CREEK 47.0
END DESCRIPTION:
XS GIS Cut Line= 3
       3608764.2     10366174.44      3607842.11     10366141.64
      3607042.08     10366141.64
#Sta/Elev= 30
  4064.8     416    4207   413.9    4247  412.27  4487.2  408.34  4587.2  409.38
  4617.2  408.32  4717.3  402.41  4817.4  399.04  4917.4  398.54  4957.5  399.47
  4977.5  398.84    4985  393.75    4990  393.75  4994.5  388.67  4997.2  388.17
  5000.5  388.67  5007.5  389.72  5017.5     398  5027.5  397.81  5037.5  396.76
  5087.5  399.07  5127.5  399.85  5377.5  402.77  5567.5   406.2  5587.5  407.01
  5597.5  406.62  5677.5  408.82  5735.5  411.11  5736.3  411.15  5787.5  413.43
#Mann= 5 ,-1 , 0
  4064.8     .05       0  4977.5     .03       0  5007.5     .05       0
  5735.5     .16       0  5736.3     .05       0
Bank Sta=4994.5,5000.5
XS Rating Curve= 0 ,0
Exp/Cntr=0.3,0.1

Type RM Length L Ch R = 1 ,26588   ,1231,1231,1231
BEGIN DESCRIPTION:
CARRYALL CREEK 46.0
END DESCRIPTION:
XS GIS Cut Line= 3
      3608798.93     10365801.18      3607697.91     10365630.59
      3607142.07     10365491.63
#Sta/Elev= 30
  4122.3  413.88  4284.3  410.37  4513.7  402.28  4604.4  400.58  4672.5  398.73
  4677.6  398.13  4735.5  397.86  4871.7  394.96  4928.6  395.21    4959  396.46
  4969.1  396.09  4979.2  394.66  4994.7   388.2  4997.5   387.7  5000.7   388.2
  5019.7  395.26  5029.8  396.84  5133.9  396.67  5171.5  397.27  5181.6  397.07
  5191.7  395.42  5196.9  393.64  5201.9  393.84    5212   392.9  5231.8  395.92
  5337.8  400.26  5644.4  406.46  5766.9  410.22    5797  411.03  5809.4   411.4
#Mann= 5 ,-1 , 0
  4122.3     .05       0  4979.2     .03       0  5019.7     .05       0
  5766.9     .16       0    5797     .05       0
Bank Sta=4994.7,5000.7
XS Rating Curve= 0 ,0
Exp/Cntr=0.3,0.1

Type RM Length L Ch R = 1 ,25357   ,755,755,755
BEGIN DESCRIPTION:
CARRYALL CREEK 44.0
END DESCRIPTION:
XS GIS Cut Line= 3
      3609085.43     10364976.53       3608311.9     10364939.91
      3607111.86     10365039.91
#Sta/Elev= 30
  4399.9  407.03  4603.5  404.83  4683.5  406.53    4751  406.39  4803.7  405.06
  4863.7  401.74  4953.8  395.76  4963.9  394.81  4973.9   392.4  4993.9  384.53
  5000.9  384.18  5003.7  383.68  5006.9  384.18  5023.9  389.07  5030.4  390.42
  5088.4  391.56    5114  390.12  5159.4   391.6  5254.5  391.73  5498.2  392.92
  5675.8  396.37  5786.2  397.12  5839.7  399.23  5880.6  399.61    6017  403.94
  6057.1  403.79  6095.3  405.85  6147.5  406.51  6215.7  409.59  6378.5   414.4
#Mann= 9 ,-1 , 0
  4399.9     .05       0    4751     .16       0  4973.9     .03       0
  5023.9     .16       0  5088.4     .05       0  5159.4     .16       0
  5254.5     .05       0  5839.7     .16       0  5880.6     .05       0
Bank Sta=5000.9,5006.9
XS Rating Curve= 0 ,0
Exp/Cntr=0.3,0.1

Type RM Length L Ch R = 1 ,24602   ,518,518,518
BEGIN DESCRIPTION:
CARRYALL CREEK 42.0
END DESCRIPTION:
XS GIS Cut Line= 3
      3608885.72     10364403.61      3608092.11     10364491.64
      3607271.19     10364490.41
#Sta/Elev= 30
  4201.7  404.71  4376.4  404.82  4416.6   404.3  4567.5   400.1  4698.3  393.42
  4748.6  391.58  4773.6  391.57  4859.2  389.47  4929.8  388.89  4954.2  389.34
    4970  389.16  4980.1  387.49  4990.1  381.91  4994.7   381.2  4997.4   380.7
  5000.7   381.2  5010.2  382.28  5020.2  384.58  5030.2  388.76  5040.2  391.05
  5090.2  389.77  5110.2  390.86  5130.2  390.53  5190.2   391.5  5340.2   395.5
  5370.2  395.58  5410.2  398.63  5469.6  400.48  5819.4  411.74  5821.1  411.74
#Mann= 6 ,-1 , 0
  4201.7     .05       0  4954.2     .16       0  4980.1     .03       0
  5020.2     .05       0  5469.6     .16       0  5819.4     .05       0
Bank Sta=4994.7,5000.7
XS Rating Curve= 0 ,0
Exp/Cntr=0.3,0.1

Type RM Length L Ch R = 1 ,24084   ,1093,1093,1093
BEGIN DESCRIPTION:
CARRYALL CREEK 41.0
END DESCRIPTION:
XS GIS Cut Line= 3
      3608955.22     10364012.98      3608192.11     10364041.64
      3607262.46     10364039.02
#Sta/Elev= 30
  4260.1   400.2    4358  400.47  4373.3  403.54  4383.3  403.82  4423.3  399.56
  4503.4  399.24  4663.5  396.14  4723.5  393.43  4843.6  390.53  4889.6  386.45
  4933.7  386.72  4963.7  385.49  4973.7  386.39  4983.7  384.95  4993.7  381.02
  5000.7  380.28  5003.5  379.78  5006.7  380.28  5021.3  384.13  5026.3  384.13
  5033.8   386.7  5043.8  387.83  5203.8  386.56  5233.8  387.89  5433.8   392.4
  5683.8  402.53  5703.8   404.2  5743.8  404.85  5853.8  409.96  5953.4  412.76
#Mann= 3 ,-1 , 0
  4260.1     .05       0  4983.7     .03       0  5021.3     .05       0
Bank Sta=5000.7,5006.7
XS Rating Curve= 0 ,0
Exp/Cntr=0.3,0.1

Type RM Length L Ch R = 1 ,22991   ,1130,1130,1130
BEGIN DESCRIPTION:
CARRYALL CREEK 39.0
END DESCRIPTION:
XS GIS Cut Line= 3
      3609076.74     10363535.55      3608599.28     10363500.83
      3607492.14     10363491.64
#Sta/Elev= 30
  4276.8  399.54  4321.5  397.62  4421.8  396.28  4552.2  392.87  4702.6  391.05
  4722.6  390.01  4732.6  390.97  4802.7  389.85  4842.7  388.37  4862.7  385.81
  4872.7  385.75  4881.5  387.03  4902.7  387.26  4942.7   385.2  4962.7  385.06
  4972.4     384  4982.7  381.67  4999.7   376.6  5002.5   376.1  5005.7   376.6
  5022.7   378.8  5032.7  381.15  5053.8  383.38  5169.1  384.52  5232.7  384.78
  5292.7  386.92  5322.7  387.02  5462.7  392.33  5582.7  395.22  5862.7  406.67
#Mann= 7 ,-1 , 0
  4276.8     .05       0  4881.5     .16       0  4972.4     .05       0
  4999.7     .03       0  5005.7     .05       0  5053.8     .16       0
  5169.1     .05       0
Bank Sta=4999.7,5005.7
XS Rating Curve= 0 ,0
Exp/Cntr=0.3,0.1

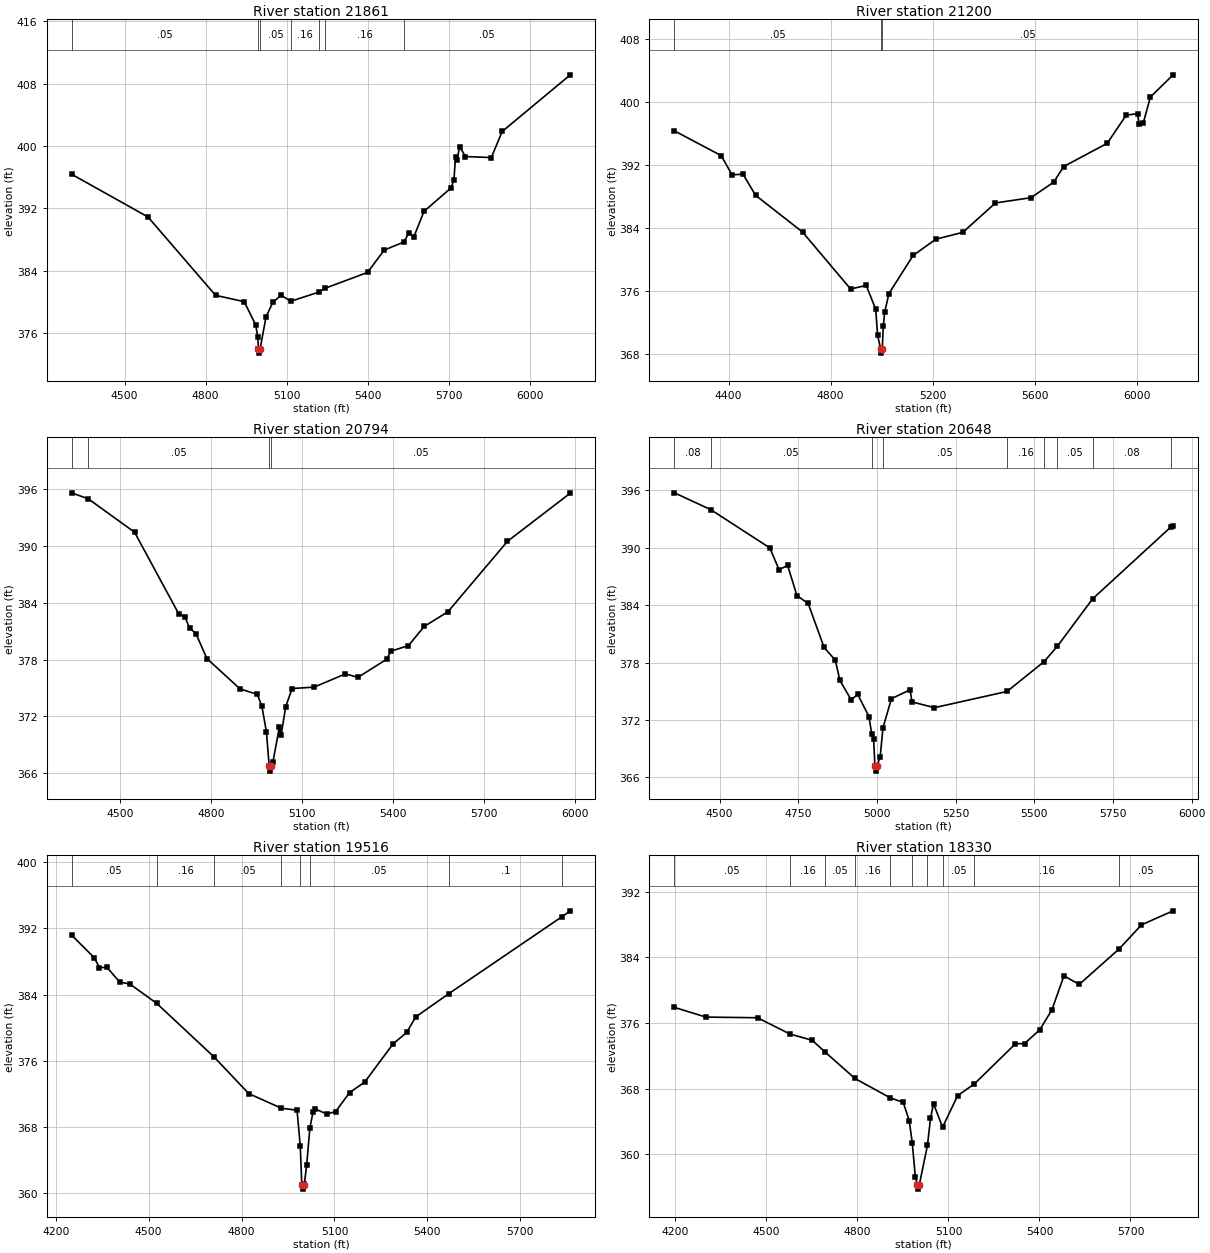
Type RM Length L Ch R = 1 ,21861   ,661,661,661
BEGIN DESCRIPTION:
CARRYALL CREEK 37.0
END DESCRIPTION:
XS GIS Cut Line= 2
      3609083.12      10362873.3      3607347.05     10362241.38
#Sta/Elev= 30
  4303.7  396.36  4586.5  390.88  4836.9  380.82  4943.3     380  4985.9     377
  4993.4  375.44  4995.7   373.9  4998.5   373.4  5001.7   373.9    5024  378.06
  5049.2  379.92  5079.8  380.83  5115.9  380.06  5219.6  381.23  5242.3  381.72
  5400.2  383.76  5461.4  386.62  5534.6  387.66  5553.1  388.83  5571.2  388.29
    5609  391.59  5709.5  394.61  5720.1  395.68    5726   398.6  5731.3  398.21
  5741.4  399.91  5762.7  398.63  5858.5   398.5  5898.8  401.85  6151.2  409.12
#Mann= 7 ,-1 , 0
  4303.7     .05       0  4995.7     .03       0  5001.7     .05       0
  5115.9     .16       0  5219.6     .05       0  5242.3     .16       0
  5534.6     .05       0
Bank Sta=4995.7,5001.7
XS Rating Curve= 0 ,0
Exp/Cntr=0.3,0.1

Type RM Length L Ch R = 1 ,21200   ,406,406,406
BEGIN DESCRIPTION:
CARRYALL CREEK 36.0
END DESCRIPTION:
XS GIS Cut Line= 3
      3609128.21     10362484.38       3608683.8     10362102.47
      3607461.56      10361484.4
#Sta/Elev= 30
  4187.8  396.34  4371.2   393.2  4413.9  390.75  4456.7  390.85  4506.1  388.16
  4690.5  383.49  4878.7  376.27    4940  376.72  4977.4  373.69  4984.5  370.41
  4996.8  368.63  4999.5  368.13  5002.8  368.63  5006.8  371.51  5012.4  373.34
  5029.1  375.69  5123.9  380.53    5213  382.59  5318.8  383.46  5446.9  387.19
  5586.3  387.86  5675.4  389.84  5714.4  391.81  5885.1  394.76  5959.5  398.33
  6004.1  398.52  6009.7  397.27  6026.4  397.34  6054.3  400.63  6143.4  403.45
#Mann= 3 ,-1 , 0
  4187.8     .05       0  4996.8     .03       0  5002.8     .05       0
Bank Sta=4996.8,5002.8
XS Rating Curve= 0 ,0
Exp/Cntr=0.3,0.1

Type RM Length L Ch R = 1 ,20794   ,146,146,146
BEGIN DESCRIPTION:
CARRYALL CREEK 34.0
END DESCRIPTION:
XS GIS Cut Line= 2
      3609181.62     10361989.35      3607800.25     10361095.75
#Sta/Elev= 30
  4340.7  395.61    4396  394.97  4548.4  391.45  4693.5  382.87  4714.6  382.49
  4729.8  381.35  4750.9  380.74  4787.1  378.11    4896  374.92  4953.4  374.33
  4968.5  373.06  4983.3  370.39  4992.6  366.73  4995.3  366.23  4998.6  366.73
  5004.8   367.2  5025.9  370.84  5031.9  370.03    5047  373.04  5068.1  374.95
  5140.7   375.1  5243.6  376.49  5285.8  376.14  5379.5  378.03  5394.6   378.9
    5452  379.48  5503.5   381.5    5582  383.05  5778.5  390.49  5985.9  395.58
#Mann= 4 ,-1 , 0
  4340.7     .08       0    4396     .05       0  4992.6     .04       0
  4998.6     .05       0
Bank Sta=4992.6,4998.6
XS Rating Curve= 0 ,0
Exp/Cntr=0.3,0.1

Type RM Length L Ch R = 1 ,20648   ,1132,1132,1132
BEGIN DESCRIPTION:
CARRYALL CREEK 33.0
END DESCRIPTION:
XS GIS Cut Line= 2
      3609234.99     10361881.26      3607940.72      10360967.2
#Sta/Elev= 30
  4356.6  395.73  4471.8  393.98  4659.7  389.98  4689.3  387.69  4716.3  388.15
  4745.9     385  4781.6  384.17  4832.1  379.59  4867.8  378.25  4882.5  376.13
  4918.2  374.11  4939.1  374.67  4974.8  372.36  4983.5  370.55  4989.6  369.99
  4993.7  367.16  4996.5  366.66  4999.7  367.16  5010.5  368.16  5019.2  371.18
  5046.2  374.23  5105.4  375.15  5111.5  373.89  5182.9  373.29  5413.3  374.98
    5531  378.09  5573.5  379.71  5685.2  384.65  5933.9  392.16  5941.1  392.27
#Mann= 9 ,-1 , 0
  4356.6     .08       0  4471.8     .05       0  4983.5     .03       0
  5019.2     .05       0  5413.3     .16       0    5531     .08       0
  5573.5     .05       0  5685.2     .08       0  5933.9      .1       0
Bank Sta=4993.7,4999.7
XS Rating Curve= 0 ,0
Exp/Cntr=0.3,0.1

Type RM Length L Ch R = 1 ,19516   ,1186,1186,1186
BEGIN DESCRIPTION:
CARRYALL CREEK 31.0
END DESCRIPTION:
XS GIS Cut Line= 3
      3609442.08     10360941.64      3608325.44     10360623.93
       3607876.3     10360623.93
#Sta/Elev= 30
  4251.3  391.19  4324.1  388.47  4341.1  387.27  4365.6  387.28  4407.2  385.48
  4438.4   385.3  4525.8  382.94  4711.9  376.42  4823.1  372.01  4928.7  370.24
  4979.1     370  4989.5  365.69  4994.5  360.95  4997.3  360.45  5000.5  360.95
  5002.7  361.08  5010.2  363.38  5020.6  367.86    5031  369.84  5036.6  370.16
  5075.7  369.54  5103.8  369.84  5148.6  372.13  5197.4   373.4  5289.2  378.03
  5333.5  379.43  5362.2  381.29  5468.1  384.08  5834.5  393.42  5861.4  394.13
#Mann= 8 ,-1 , 0
  4251.3     .05       0  4525.8     .16       0  4711.9     .05       0
  4928.7     .16       0  4989.5     .03       0  5020.6     .05       0
  5468.1      .1       0  5834.5     .05       0
Bank Sta=4994.5,5000.5
XS Rating Curve= 0 ,0
Exp/Cntr=0.3,0.1

Type RM Length L Ch R = 1 ,18330   ,549,549,549
BEGIN DESCRIPTION:
CARRYALL CREEK 29.0
END DESCRIPTION:
XS GIS Cut Line= 3
       3609606.2     10360089.37      3608314.67     10360071.85
      3607965.86     10360121.68
#Sta/Elev= 30
  4196.5  377.91  4300.6  376.73  4470.6  376.65  4577.8  374.66  4650.6  373.91
  4692.8  372.49  4791.5  369.26  4907.8   366.9  4950.7  366.35  4970.7  364.12
  4980.7  361.39  4990.7  357.27  4997.7  356.28  5000.4  355.78  5003.7  356.28
  5030.7  361.11  5040.7  364.39  5050.7  366.19  5080.5  363.32  5130.3  367.17
    5185  368.58  5320.7  373.48  5350.7   373.5  5400.7  375.18  5440.7  377.59
  5480.7  381.75  5531.1  380.71  5663.4  385.06  5736.2  387.96  5840.5  389.67
#Mann= 10 ,-1 , 0
  4196.5     .05       0  4577.8     .16       0  4692.8     .05       0
  4791.5     .16       0  4907.8     .05       0  4980.7     .03       0
  5030.7     .16       0  5080.5     .05       0    5185     .16       0
  5663.4     .05       0
Bank Sta=4997.7,5003.7
XS Rating Curve= 0 ,0
Exp/Cntr=0.3,0.1