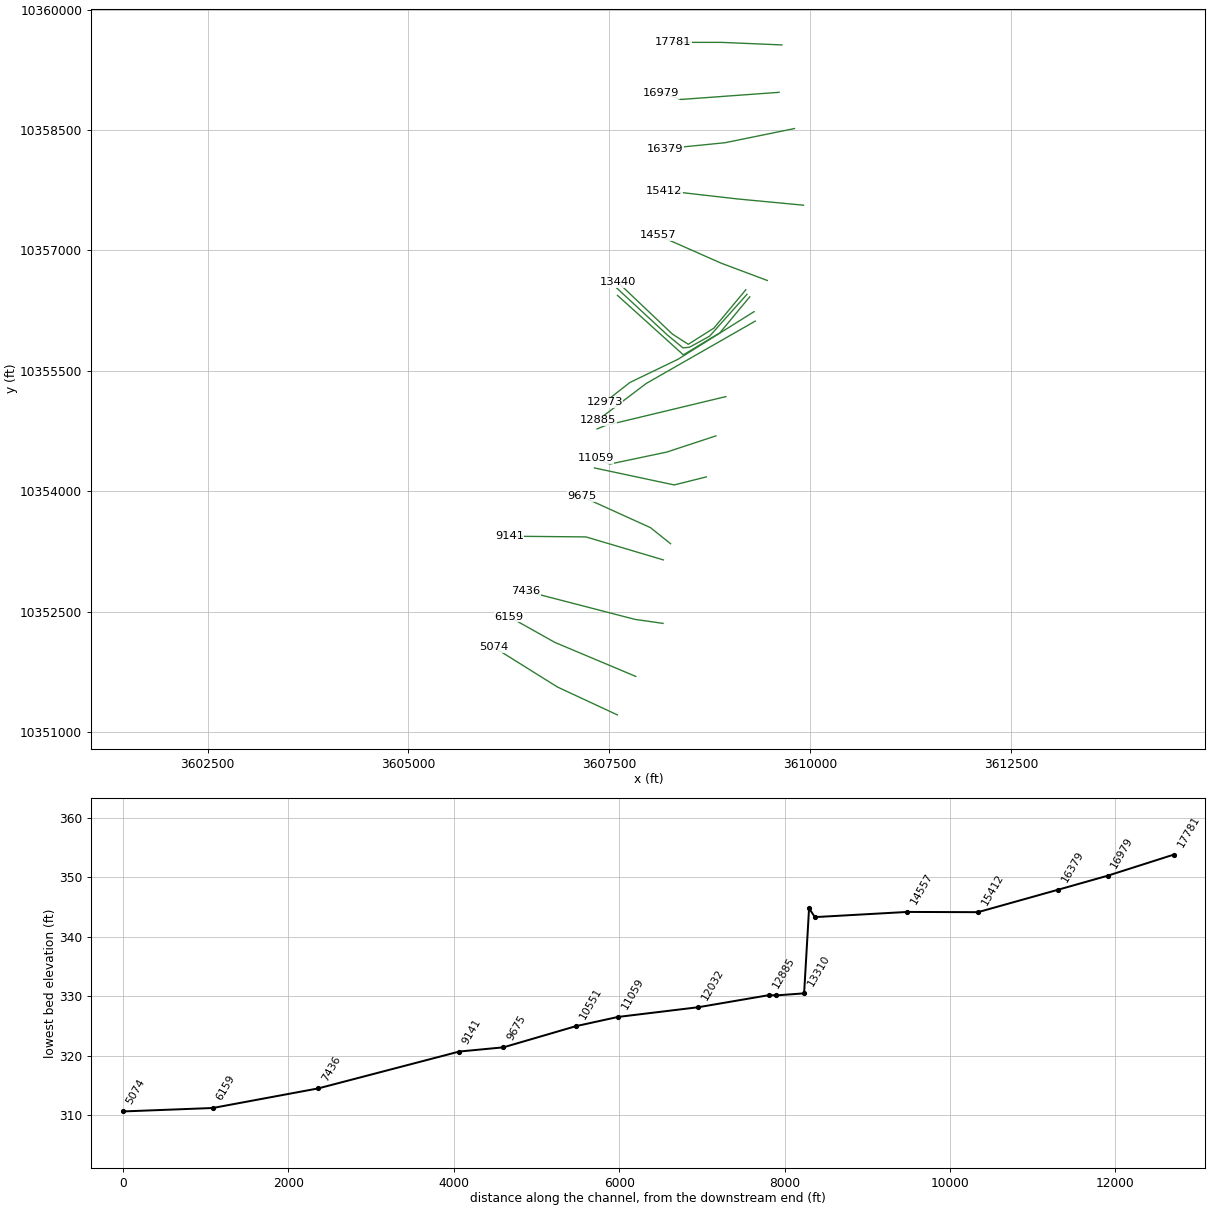
HEC-RAS study CARRYALL CREEK.prj: CARRYALL CREEK Base Level Engineering

--- CARRYALL CREEK.g01 (geometry) --- (continued)

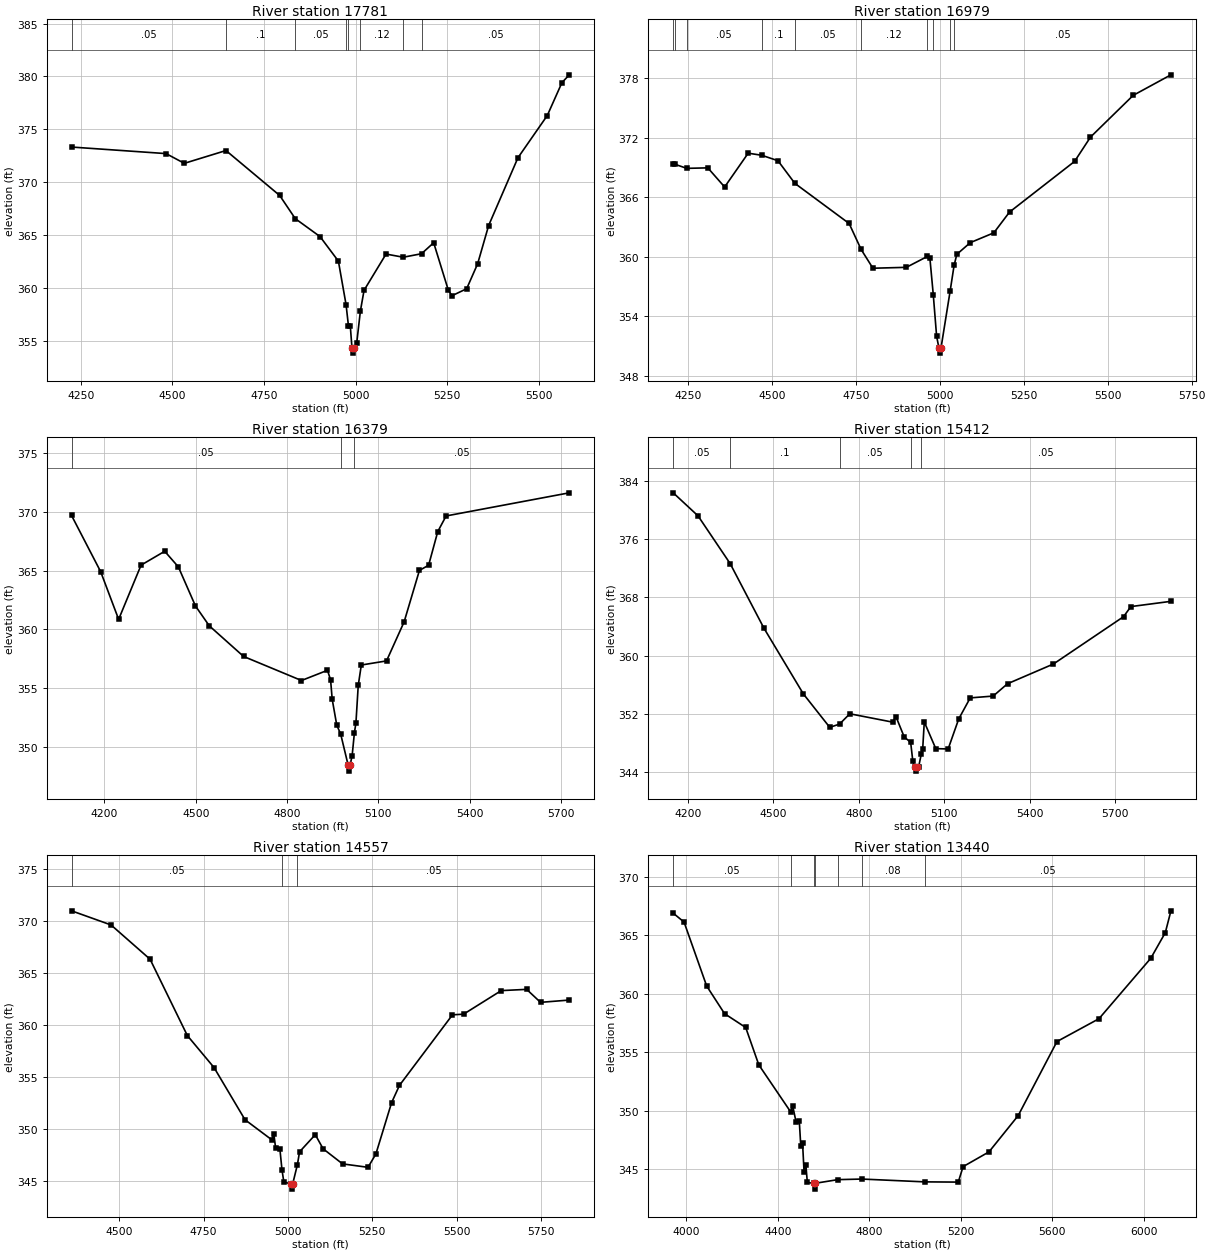
Type RM Length L Ch R = 1 ,17781   ,802,802,802
BEGIN DESCRIPTION:
CARRYALL CREEK 28.0
END DESCRIPTION:
XS GIS Cut Line= 3
      3609649.63     10359559.86      3608892.11     10359591.64
       3608292.1     10359591.64
#Sta/Elev= 30
  4224.6  373.32  4482.4   372.7  4532.4  371.78    4646  372.99  4792.6  368.74
  4835.1  366.55  4902.7  364.85  4952.8  362.53  4973.7  358.42  4980.3  356.39
  4985.3  356.39  4989.8  354.33  4992.5  353.83  4995.8  354.33  5002.8  354.79
  5012.8  357.81  5022.8  359.77  5082.8   363.2  5129.8   362.9  5179.6  363.23
  5212.8  364.27  5252.8  359.78  5262.8  359.26  5302.8  359.92  5332.8  362.28
  5362.8   365.9  5442.8  372.31  5522.8   376.3  5562.8  379.41  5582.8  380.15
#Mann= 8 ,-1 , 0
  4224.6     .05       0    4646      .1       0  4835.1     .05       0
  4973.7     .12       0  4980.3     .03       0  5012.8     .12       0
  5129.8     .16       0  5179.6     .05       0
Bank Sta=4989.8,4995.8
XS Rating Curve= 0 ,0
Exp/Cntr=0.3,0.1

Type RM Length L Ch R = 1 ,16979   ,600,600,600
BEGIN DESCRIPTION:
CARRYALL CREEK 26.0
END DESCRIPTION:
XS GIS Cut Line= 3
      3609614.93     10358969.58       3608392.8     10358880.53
      3608147.92     10358960.89
#Sta/Elev= 30
  4205.1  369.32  4210.3  369.31  4245.4   368.9  4308.2  368.95  4358.3  367.02
  4428.5  370.43  4468.8  370.22  4517.2  369.67  4567.5  367.39  4729.3  363.34
  4765.1  360.72  4800.2  358.83  4899.8  358.92  4962.6  360.02  4969.9  359.87
    4980  356.18    4990  351.97    4997  350.77  4999.8  350.27    5003  350.77
  5030.1  356.49  5042.1  359.12  5050.2  360.23  5090.3  361.41  5160.5   362.4
  5207.2  364.49  5401.1   369.6  5448.5  372.05  5575.8  376.26  5688.2  378.33
#Mann= 10 ,-1 , 0
  4205.1     .05       0  4210.3      .1       0  4245.4     .05       0
  4468.8      .1       0  4567.5     .05       0  4765.1     .12       0
  4962.6     .16       0    4980     .03       0  5030.1     .16       0
  5042.1     .05       0
Bank Sta=4997,5003
XS Rating Curve= 0 ,0
Exp/Cntr=0.3,0.1

Type RM Length L Ch R = 1 ,16379   ,967,967,967
BEGIN DESCRIPTION:
CARRYALL CREEK 25.0
END DESCRIPTION:
XS GIS Cut Line= 3
      3609805.87     10358518.19      3608942.11     10358341.64
      3608192.28     10358266.55
#Sta/Elev= 30
  4091.9  369.69  4187.6   364.9  4246.6  360.84  4320.3  365.46    4398  366.64
  4442.8  365.31    4499  361.98  4544.4  360.29  4657.1  357.68  4847.3  355.63
  4932.7   356.5  4942.9  355.69  4948.3  354.02  4963.3  351.82    4976  351.08
  5000.7  348.41  5003.4  347.91  5006.7  348.41  5013.7  349.21  5021.2  351.18
  5026.2  352.01  5033.8  355.21  5043.9  356.95  5126.7   357.3  5184.6  360.63
  5234.8  365.01    5265  365.45  5295.1  368.32  5322.5  369.65  5727.1  371.62
#Mann= 3 ,-1 , 0
  4091.9     .05       0    4976     .03       0  5021.2     .05       0
Bank Sta=5000.7,5006.7
XS Rating Curve= 0 ,0
Exp/Cntr=0.3,0.1

Type RM Length L Ch R = 1 ,15412   ,855,855,855
BEGIN DESCRIPTION:
CARRYALL CREEK 23.0
END DESCRIPTION:
XS GIS Cut Line= 3
       3609918.7     10357563.33      3609092.11     10357641.64
      3608182.63     10357745.62
#Sta/Elev= 30
  4149.4  382.33  4236.4  379.17  4349.1  372.62  4467.4  363.77  4605.8  354.74
  4698.4  350.15  4732.7  350.59  4768.8  352.01  4919.4  350.86  4930.6  351.63
  4959.6  348.83  4982.2  348.09  4989.8  345.52  4996.8  344.64  4999.6  344.14
  5002.8  344.64  5009.9  344.66  5019.3  346.45  5024.4  347.16    5030  350.89
  5070.3  347.23  5113.7  347.18  5150.8   351.3  5191.1  354.19  5271.6  354.44
  5321.9  356.13    5483  358.84  5728.8  365.33  5754.7  366.72  5895.1  367.44
#Mann= 5 ,-1 , 0
  4149.4     .05       0  4349.1      .1       0  4732.7     .05       0
  4982.2     .03       0  5019.3     .05       0
Bank Sta=4996.8,5002.8
XS Rating Curve= 0 ,0
Exp/Cntr=0.3,0.1

Type RM Length L Ch R = 1 ,14557   ,1117,1117,1117
BEGIN DESCRIPTION:
CARRYALL CREEK 21.0
END DESCRIPTION:
XS GIS Cut Line= 3
      3609467.33     10356625.83      3608892.11     10356841.64
      3608105.78     10357189.49
#Sta/Elev= 30
  4359.1  370.97  4476.1  369.61  4591.7  366.31  4702.1  358.96  4781.2  355.88
  4872.9  350.86  4952.1  348.93  4958.3  349.47  4963.7   348.1  4976.2  348.04
  4982.4  346.03  4987.9  344.87  5008.1  344.68  5010.9  344.18  5014.1  344.68
  5028.1  346.54  5034.4  347.77    5081  349.42  5104.3  348.06  5161.8  346.61
  5237.2  346.28  5260.5  347.56  5307.1  352.51  5330.4  354.17  5487.4  360.96
  5520.2  361.02  5631.8  363.29  5707.1  363.41  5748.2  362.16  5833.3  362.38
#Mann= 3 ,-1 , 0
  4359.1     .05       0  4982.4     .03       0  5028.1     .05       0
Bank Sta=5008.1,5014.1
XS Rating Curve= 0 ,0
Exp/Cntr=0.3,0.1

Type RM Length L Ch R = 1 ,13440   ,70,70,70
BEGIN DESCRIPTION:
CARRYALL CREEK 20.0
END DESCRIPTION:
XS GIS Cut Line= 5
       3609200.1     10356509.87      3608802.97     10356032.44
      3608483.96     10355830.62      3608286.48     10355957.59
      3607602.84     10356606.87
#Sta/Elev= 30
  3943.2  366.87  3990.6  366.11  4089.5  360.65  4167.7  358.29  4260.1  357.11
  4317.4  353.92  4456.5  349.91  4465.8  350.39  4480.1  349.07  4494.4  349.14
  4500.9     347  4508.8  347.22  4515.3  344.79  4523.1  345.39  4529.6  343.88
  4558.5  343.81  4561.2  343.31  4564.5  343.81    4663  344.12  4768.2  344.17
  5042.5  343.93  5189.5  343.91  5210.6  345.23  5323.8  346.49  5451.2  349.58
  5621.1  355.91  5804.8  357.86  6031.3  363.02  6094.8  365.21  6119.3  367.07
#Mann= 7 ,-1 , 0
  3943.2     .05       0  4456.5     .08       0  4558.5     .07       0
  4564.5     .08       0    4663     .05       0  4768.2     .08       0
  5042.5     .05       0
Bank Sta=4558.5,4564.5
XS Rating Curve= 0 ,0
Exp/Cntr=0.3,0.1

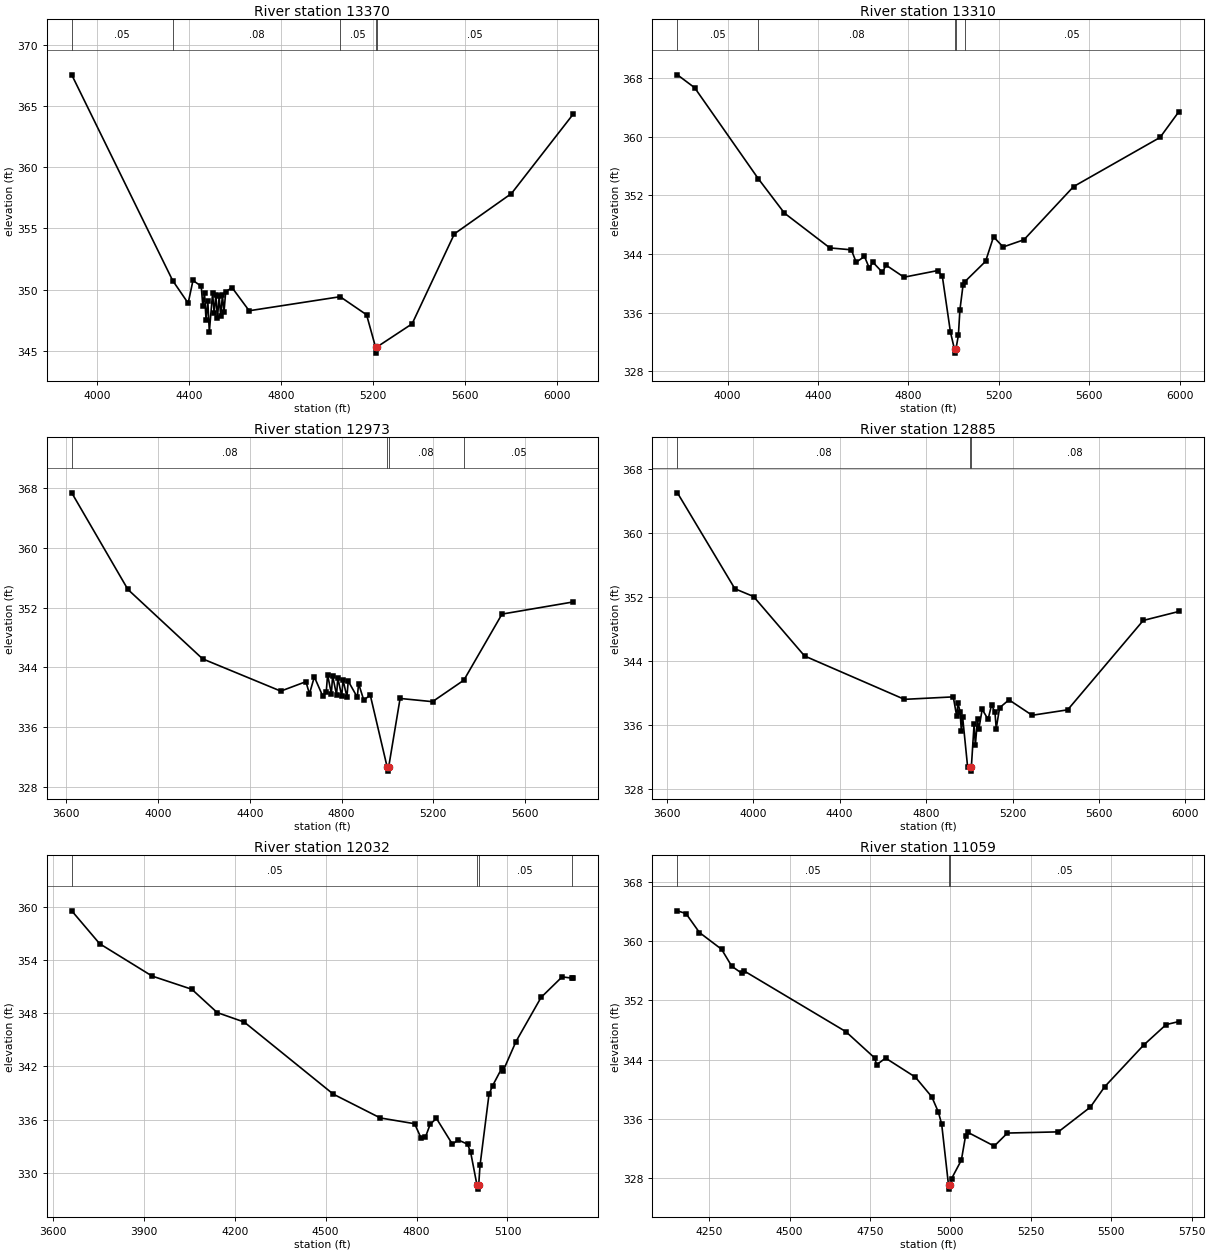
Type RM Length L Ch R = 1 ,13370   ,60,60,60
BEGIN DESCRIPTION:
CARRYALL CREEK 18.0
END DESCRIPTION:
XS GIS Cut Line= 6
      3609214.59      10356452.9      3608748.45     10355930.77
      3608498.45     10355794.05      3608417.73     10355786.24
      3608223.71     10355946.39      3607593.49     10356531.04
#Sta/Elev= 30
  3891.2  367.58  4329.6  350.73  4396.8  348.88  4417.7  350.74  4453.6  350.27
  4460.3  348.68  4467.8   349.7  4474.5  347.49    4482  349.09  4488.7  346.54
  4502.9   349.7  4509.6  348.07  4517.2  349.56  4523.9  347.65  4531.4  349.44
  4538.1   347.8  4545.6  349.55  4552.3  348.14  4559.8  349.81  4587.2  350.16
  4661.7  348.26  5056.8  349.41  5171.6  347.93  5210.4  345.29  5213.2  344.79
  5216.4  345.29  5369.3  347.19    5553  354.56  5800.8  357.86  6068.4  364.35
#Mann= 5 ,-1 , 0
  3891.2     .05       0  4329.6     .08       0  5056.8     .05       0
  5210.4     .07       0  5216.4     .05       0
Bank Sta=5210.4,5216.4
XS Rating Curve= 0 ,0
Exp/Cntr=0.3,0.1

Type RM Length L Ch R = 1 ,13310   ,337,337,337
BEGIN DESCRIPTION:
CARRYALL CREEK 17.0
END DESCRIPTION:
XS GIS Cut Line= 4
      3609248.88     10356421.65      3608877.36     10355973.74
      3608422.65     10355698.99      3607602.85     10356439.44
#Sta/Elev= 30
  3777.9  368.41  3854.2  366.65  4135.5  354.26  4251.4  349.56  4452.3  344.82
  4547.3  344.56  4568.7  342.87  4605.5  343.65  4626.9  342.06  4642.4  342.88
  4685.1  341.48  4700.6  342.48  4780.2  340.83    4929  341.73  4949.9  340.94
  4985.7  333.36  5003.7  330.98  5006.4  330.48  5009.7  330.98  5020.9  332.93
  5027.6  336.37  5041.8  339.83  5048.6  340.19  5141.2  342.99  5176.3  346.33
  5218.9  344.95  5310.8  345.93  5530.5  353.18  5913.1  359.88  5995.8  363.37
#Mann= 5 ,-1 , 0
  3777.9     .05       0  4135.5     .08       0  5003.7     .07       0
  5009.7     .08       0  5048.6     .05       0
Bank Sta=5003.7,5009.7
XS Rating Curve= 0 ,0
Exp/Cntr=0.3,0.1

Type RM Length L Ch R = 1 ,12973   ,88,88,88
BEGIN DESCRIPTION:
Mapping XS d8fcb455
END DESCRIPTION:
XS GIS Cut Line= 4
      3609303.27     10356237.34      3608355.38     10355643.61
      3607756.42     10355354.55      3607441.29     10355107.13
#Sta/Elev= 30
  3624.7  367.32  3869.4  354.41  4194.8  345.14  4535.4  340.83    4645  342.09
  4660.3  340.46  4681.6  342.73  4718.1  340.17  4733.4  340.69  4739.3  343.02
  4755.8  340.49  4761.3  342.87  4778.4  340.31    4784   342.6    4801  340.13
  4806.6  342.35  4823.6  340.03  4829.2  342.17  4868.8  340.01  4874.4  341.84
    4897  339.62  4925.2  340.31  4999.2  330.64    5002  330.14  5005.2  330.64
  5055.2  339.85  5196.4  339.42    5333  342.29  5499.2  351.12  5808.9  352.74
#Mann= 4 ,-1 , 0
  3624.7     .08       0  4999.2     .07       0  5005.2     .08       0
    5333     .05       0
Bank Sta=4999.2,5005.2
XS Rating Curve= 0 ,0
Exp/Cntr=0.3,0.1

Type RM Length L Ch R = 1 ,12885   ,853,853,853
BEGIN DESCRIPTION:
CARRYALL CREEK 16.0
END DESCRIPTION:
XS GIS Cut Line= 3
      3609317.14     10356119.16       3607961.2      10355343.1
      3607357.41     10354886.36
#Sta/Elev= 30
  3649.5  364.96  3915.4  352.97  4001.8     352  4237.8  344.57  4699.7  339.15
  4925.7  339.46  4941.5  337.05  4947.3  338.69  4957.3  337.58  4963.1  335.16
  4968.8  336.99  4991.9  330.75  5003.3  330.68    5006  330.18  5009.3  330.68
  5022.1  336.08  5027.8  333.41  5037.9  336.66  5043.7   335.4  5059.5   337.9
  5086.8  336.65  5102.7  338.44  5118.5  337.57  5124.3   335.5  5140.1   338.1
  5183.3  339.09  5290.5  337.16  5454.9  337.84  5804.5  349.01  5968.9  350.13
#Mann= 3 ,-1 , 0
  3649.5     .08       0  5003.3     .07       0  5009.3     .08       0
Bank Sta=5003.3,5009.3
XS Rating Curve= 0 ,0
Exp/Cntr=0.3,0.1

Type RM Length L Ch R = 1 ,12032   ,973,973,973
BEGIN DESCRIPTION:
CARRYALL CREEK 15.02
END DESCRIPTION:
XS GIS Cut Line= 3
      3608952.48     10355179.17      3607449.05     10354818.07
      3607348.69     10354776.54
#Sta/Elev= 30
  3661.9  359.55    3754  355.84  3927.1  352.19  4058.2   350.7  4142.1  348.07
  4231.2     347  4525.1  338.87  4680.4  336.18  4793.6  335.53  4814.1  333.97
  4829.2  334.01    4845  335.47  4865.6  336.13  4918.3  333.22  4937.5   333.7
  4968.4  333.22  4978.7  332.29  4999.2  328.65    5002  328.15  5005.2  328.65
  5009.5  330.82  5039.1  338.83  5050.7   339.8  5081.1  341.77  5086.2  341.53
  5128.2   344.8    5211  349.78  5280.5   352.1  5311.7  351.96  5316.7  351.92
#Mann= 4 ,-1 , 0
  3661.9     .05       0  4999.2     .03       0  5005.2     .05       0
  5311.7     .08       0
Bank Sta=4999.2,5005.2
XS Rating Curve= 0 ,0
Exp/Cntr=0.3,0.1

Type RM Length L Ch R = 1 ,11059   ,508,508,508
BEGIN DESCRIPTION:
CARRYALL CREEK 15.01
END DESCRIPTION:
XS GIS Cut Line= 4
      3608827.51     10354689.59      3608216.41     10354488.21
      3607508.08      10354338.9      3607331.02      10354411.8
#Sta/Elev= 30
  4151.2  364.08  4177.9  363.71  4219.7  361.15  4288.5  358.89  4320.2   356.6
    4352  355.63  4357.3     356  4674.9  347.77    4765   344.2  4770.3  343.29
  4798.4   344.2    4891  341.63  4942.1  338.97  4962.5  336.92  4972.8   335.3
  4994.2  327.01    4997  326.51  5000.2  327.01  5003.4  327.91  5034.1  330.43
    5047  333.68  5054.5  334.17  5136.3  332.32  5177.2  334.08  5335.6  334.24
  5435.1  337.58  5479.8  340.34  5600.7  345.95  5670.6  348.72    5710  349.13
#Mann= 3 ,-1 , 0
  4151.2     .05       0  4994.2     .03       0  5000.2     .05       0
Bank Sta=4994.2,5000.2
XS Rating Curve= 0 ,0
Exp/Cntr=0.3,0.1

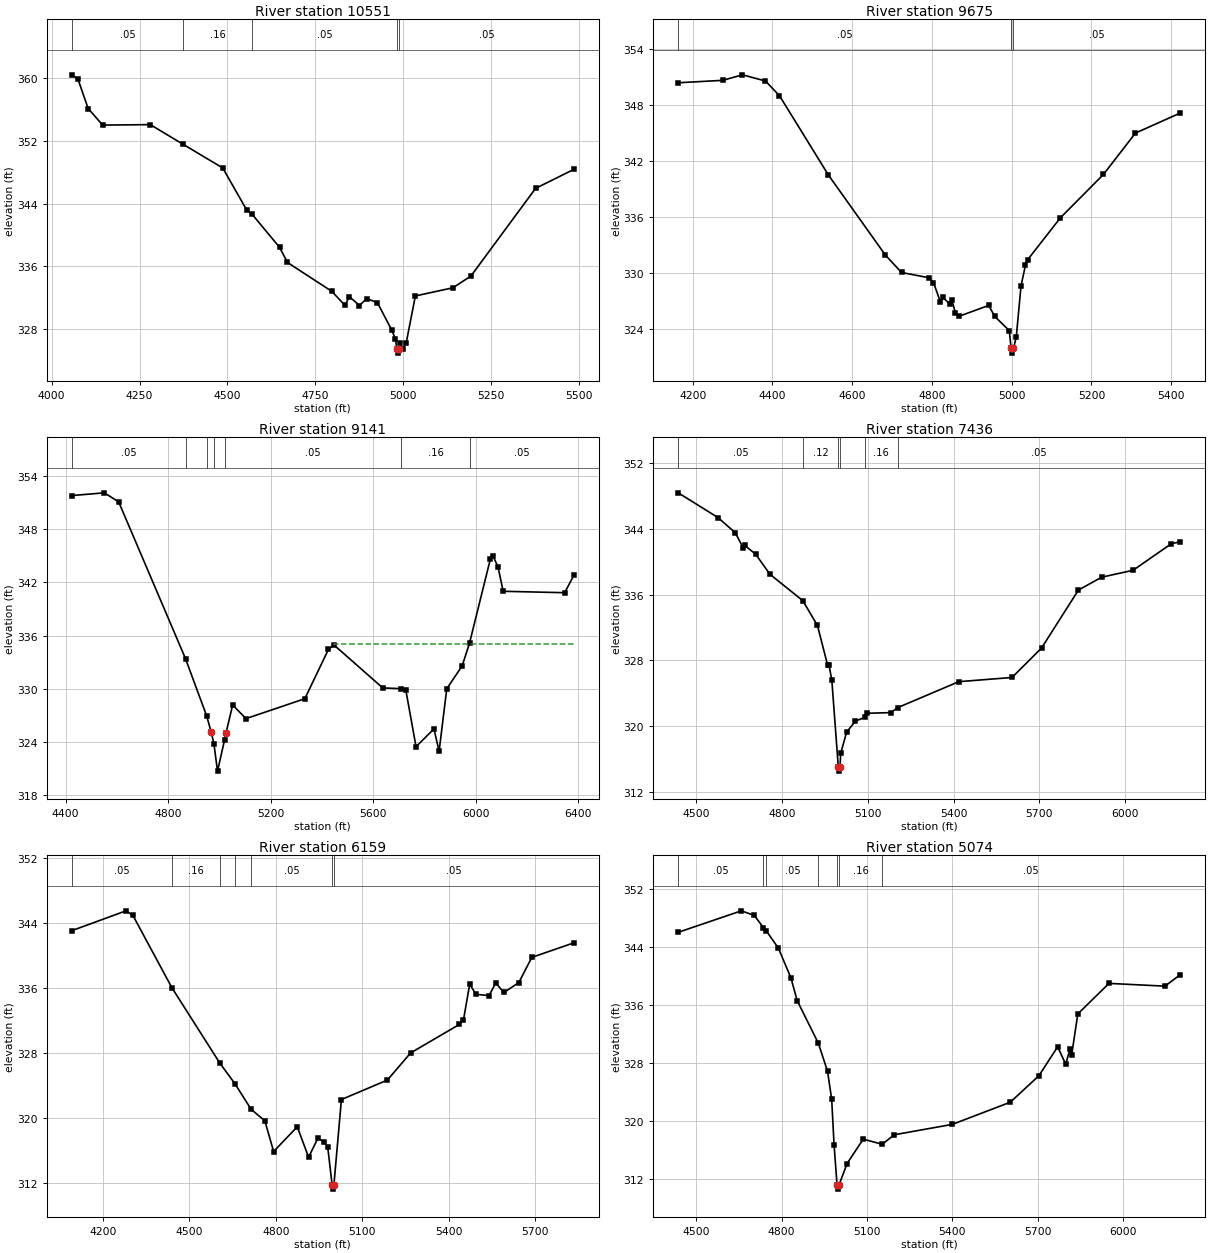
Type RM Length L Ch R = 1 ,10551   ,876,876,876
BEGIN DESCRIPTION:
CARRYALL CREEK 15.0
END DESCRIPTION:
XS GIS Cut Line= 3
       3608708.8      10354178.8      3608308.77      10354078.8
      3607315.83     10354290.49
#Sta/Elev= 30
  4057.2  360.39  4074.4  359.89  4103.8   356.1    4145  353.99  4280.6  354.05
  4373.9  351.54  4486.6  348.53  4554.1  343.21  4570.1  342.63  4648.1  338.42
  4670.6   336.5  4796.7  332.82  4834.2  331.03  4846.2  332.16  4875.1  331.02
  4895.8   331.9  4926.2  331.39  4967.1  327.88  4977.4  326.77  4981.6  325.46
  4984.4  324.96  4987.6  325.46  4989.7  326.26  4997.8  325.48    5008  326.24
  5034.2  332.24    5141  333.28  5192.1  334.77  5376.1  345.94  5484.8  348.35
#Mann= 5 ,-1 , 0
  4057.2     .05       0  4373.9     .16       0  4570.1     .05       0
  4981.6     .03       0  4987.6     .05       0
Bank Sta=4981.6,4987.6
XS Rating Curve= 0 ,0
Exp/Cntr=0.3,0.1

Type RM Length L Ch R = 1 ,9675    ,534,534,534
BEGIN DESCRIPTION:
CARRYALL CREEK 14.0
END DESCRIPTION:
XS GIS Cut Line= 3
      3608263.61     10353346.52      3608013.63      10353546.5
      3607158.29     10353934.86
#Sta/Elev= 30
  4163.6  350.36  4275.1  350.62  4324.7  351.21  4382.4  350.55  4417.6  348.97
  4540.3  340.48  4683.1  331.91  4723.7  330.04  4792.9  329.47  4803.9  328.96
  4821.5  326.86    4827  327.36  4844.6   326.7  4850.1  327.06  4858.8  325.72
  4867.7  325.34  4942.4  326.51  4957.6  325.33  4994.1  323.81  4998.6   321.9
  5001.3   321.4  5004.6   321.9  5011.6  323.13  5023.5  328.59  5034.5   330.8
  5040.2  331.41  5122.4   335.9  5230.3  340.54  5310.5  344.97  5423.1  347.12
#Mann= 3 ,-1 , 0
  4163.6     .05       0  4998.6     .03       0  5004.6     .05       0
Bank Sta=4998.6,5004.6
XS Rating Curve= 0 ,0
Exp/Cntr=0.3,0.1

Type RM Length L Ch R = 1 ,9141    ,1705,1705,1705
BEGIN DESCRIPTION:
CARRYALL CREEK 13.0
END DESCRIPTION:
XS GIS Cut Line= 3
      3608173.95     10353144.92      3607210.39     10353431.38
      3606256.27     10353440.06
#Sta/Elev= 30
  4424.4  351.81  4551.5  352.12  4607.4   351.1  4868.3  333.39  4951.4  326.88
  4968.8  325.06  4979.2  323.77  4993.2  320.69    5021  324.26  5026.6  325.03
  5052.3  328.16  5104.4  326.62    5334  328.87  5426.1  334.44  5447.9  334.93
  5637.9  330.09  5710.6     330  5727.9  329.87  5767.9  323.45  5837.9  325.46
  5857.9  322.93  5887.9     330  5947.9  332.57  5976.6  335.14  6057.9  344.63
  6067.9  345.03    6088  343.73    6108     341    6348  340.84  6383.8   342.8
#Mann= 7 ,-1 , 0
  4424.4     .05       0  4868.3     .16       0  4951.4     .05       0
  4979.2     .03       0    5021     .05       0  5710.6     .16       0
  5976.6     .05       0
#XS Ineff= 2 , 0
                         5448.86          335.07
Permanent Ineff=
       F       F
Bank Sta=4968.8,5026.6
XS Rating Curve= 0 ,0
Exp/Cntr=0.3,0.1

Type RM Length L Ch R = 1 ,7436    ,1277,1277,1277
BEGIN DESCRIPTION:
CARRYALL CREEK 12.0
END DESCRIPTION:
XS GIS Cut Line= 3
       3608169.9     10352354.14      3607819.88     10352404.14
      3606462.11     10352756.04
#Sta/Elev= 30
  4437.1   348.4  4576.3  345.38  4636.9  343.53  4664.5  341.67  4669.6     342
  4707.6  340.93  4758.1  338.47  4872.8  335.26    4924  332.24  4959.4  327.43
  4964.6  327.38  4974.3  325.58    4997  314.99  4999.8  314.49    5003  314.99
  5005.3  316.64    5026  319.24    5057  320.59    5089  321.03  5098.3  321.54
  5180.9  321.62  5205.4  322.24  5418.5  325.39  5604.5   325.9  5707.8  329.48
  5836.9  336.55  5918.1  338.12    6028  338.96  6162.3  342.21  6193.3  342.43
#Mann= 6 ,-1 , 0
  4437.1     .05       0  4872.8     .12       0    4997     .07       0
    5003     .12       0    5089     .16       0  5205.4     .05       0
Bank Sta=4997,5003
XS Rating Curve= 0 ,0
Exp/Cntr=0.3,0.1

Type RM Length L Ch R = 1 ,6159    ,1085,1085,1085
BEGIN DESCRIPTION:
CARRYALL CREEK 10.0
END DESCRIPTION:
XS GIS Cut Line= 3
      3607830.14     10351693.55      3606823.23     10352117.15
      3606255.45     10352435.66
#Sta/Elev= 30
  4091.2  343.06  4279.3  345.51  4303.1  344.97  4438.7  336.04  4605.1  326.74
  4657.4  324.21  4714.1  321.03  4761.7  319.61  4792.1  315.83  4874.2  318.88
  4913.6  315.12  4945.4  317.44  4967.8  317.02    4980  316.35  4995.4  311.69
  4998.1  311.19  5001.4  311.69  5027.5  322.24  5187.1  324.64  5267.6  327.98
  5437.1   331.5  5451.3  332.05    5473  336.47  5494.7  335.21  5540.3  335.06
  5563.3  336.62  5591.6  335.44  5643.5  336.66  5688.6  339.77  5834.6  341.56
#Mann= 7 ,-1 , 0
  4091.2     .05       0  4438.7     .16       0  4605.1     .05       0
  4657.4     .12       0  4714.1     .05       0  4995.4     .03       0
  5001.4     .05       0
Bank Sta=4995.4,5001.4
XS Rating Curve= 0 ,0
Exp/Cntr=0.3,0.1

Type RM Length L Ch R = 1 ,5074    ,1311,1311,1311
BEGIN DESCRIPTION:
CARRYALL CREEK 8.0
END DESCRIPTION:
XS GIS Cut Line= 3
      3607601.02     10351214.37      3606855.99     10351561.09
      3606056.54     10352060.74
#Sta/Elev= 30
  4436.9     346  4658.7  348.96  4704.5  348.32  4736.4  346.63  4746.7  346.18
  4788.7  343.83  4832.8  339.74  4854.8   336.6  4929.3  330.71  4961.7  326.84
  4976.2  322.98  4984.5  316.74  4995.2  311.11    4998  310.61  5001.2  311.11
  5030.3  314.14  5087.1   317.5    5154  316.79    5196   318.1    5400  319.53
    5604  322.59  5704.3  326.23  5770.3  330.22  5798.6  327.83  5813.9  329.91
  5819.8  329.15  5841.1  334.75  5950.7  338.96  6147.7  338.58  6201.4  340.17
#Mann= 7 ,-1 , 0
  4436.9     .05       0  4736.4     .16       0  4746.7     .05       0
  4929.3     .16       0  4995.2     .07       0  5001.2     .16       0
    5154     .05       0
Bank Sta=4995.2,5001.2
XS Rating Curve= 0 ,0
Exp/Cntr=0.3,0.1