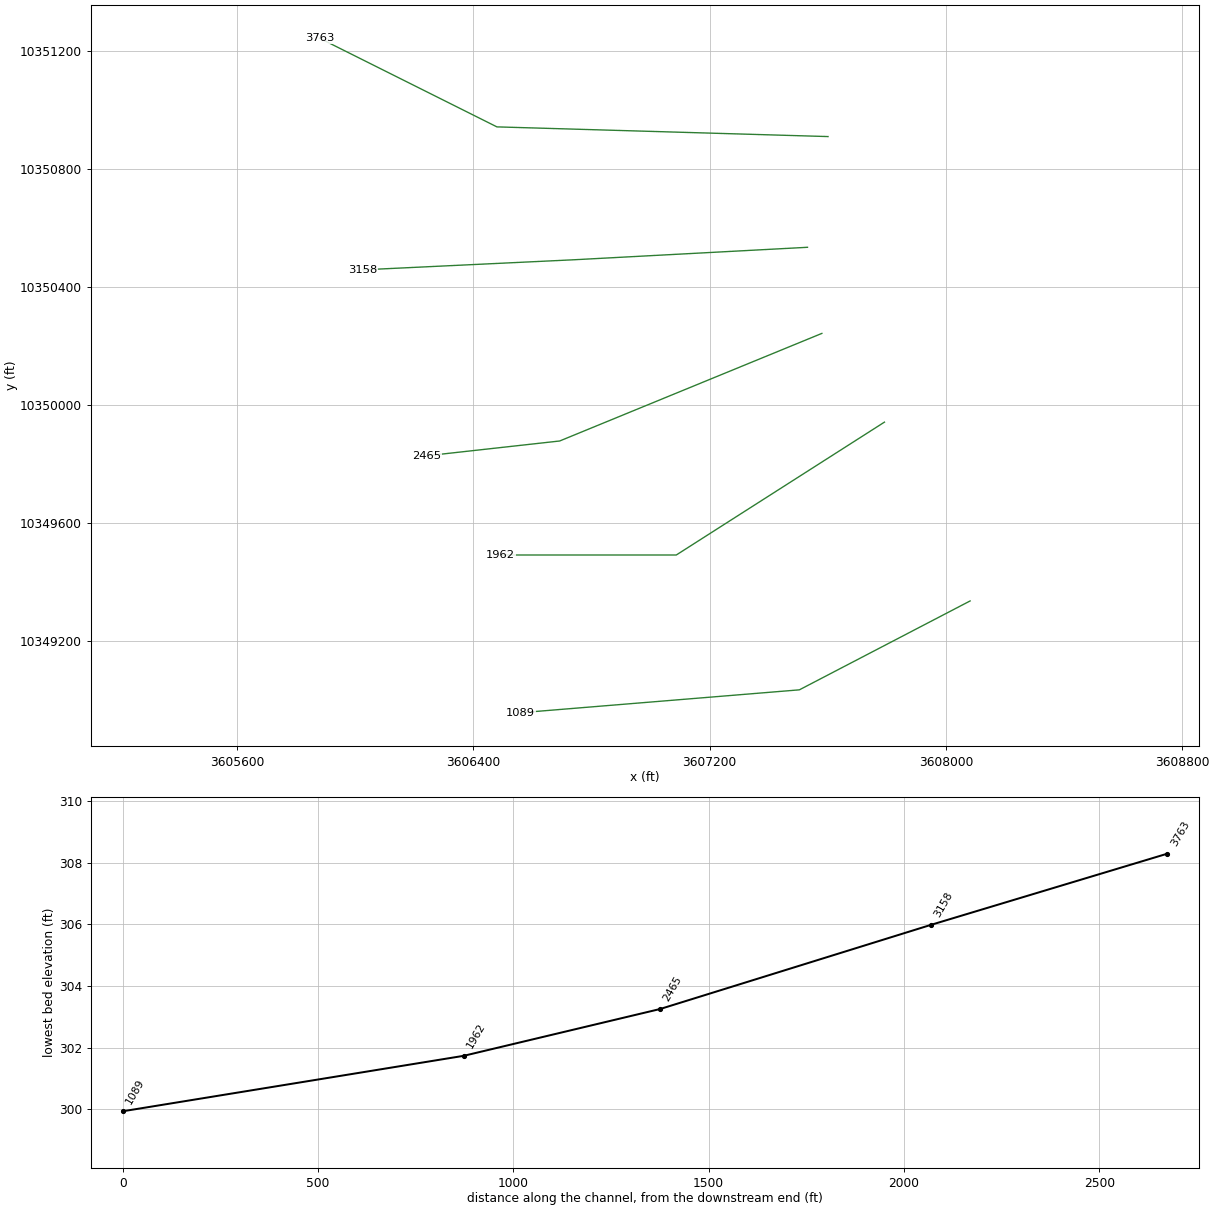
HEC-RAS study CARRYALL CREEK.prj: CARRYALL CREEK Base Level Engineering

--- CARRYALL CREEK.g01 (geometry) --- (continued)

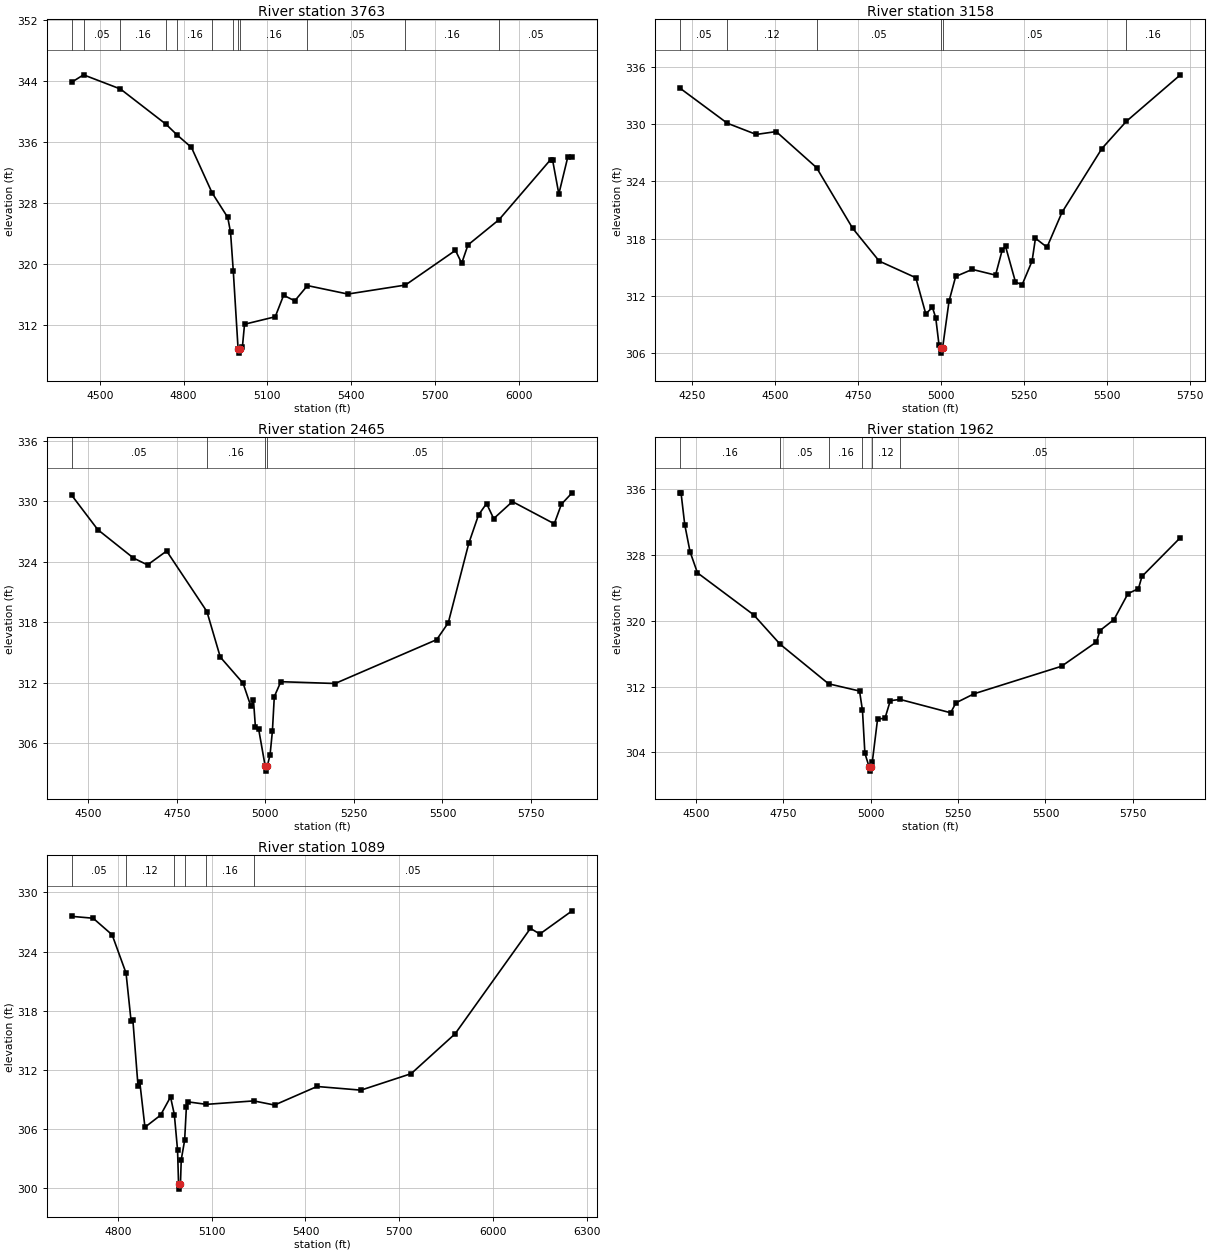
Type RM Length L Ch R = 1 ,3763    ,605,605,605
BEGIN DESCRIPTION:
CARRYALL CREEK 7.0
END DESCRIPTION:
XS GIS Cut Line= 3
      3607601.01     10350908.82      3606479.61     10350941.64
      3605879.61     10351241.64
#Sta/Elev= 30
  4399.2  343.83  4441.6   344.8  4573.9  342.94    4737  338.32  4777.8  336.88
  4828.3  335.27  4902.3  329.31  4958.3  326.09  4968.3  324.14    4978  319.12
  4995.4  308.79  4998.1  308.29  5001.4  308.79  5010.9  309.14  5018.4  312.08
  5128.4  313.06  5158.4  315.88  5198.4  315.15  5243.8  317.15  5388.5  316.04
  5594.7  317.22    5774  321.77  5796.4  320.08  5818.8  322.48  5930.2   325.8
    6115  333.68    6122  333.62  6144.4  329.17  6176.5  334.02  6191.9  333.96
#Mann= 12 ,-1 , 0
  4399.2     .16       0  4441.6     .05       0  4573.9     .16       0
    4737     .05       0  4777.8     .16       0  4902.3     .05       0
    4978     .16       0  4995.4     .07       0  5001.4     .16       0
  5243.8     .05       0  5594.7     .16       0  5930.2     .05       0
Bank Sta=4995.4,5001.4
XS Rating Curve= 0 ,0
Exp/Cntr=0.3,0.1

Type RM Length L Ch R = 1 ,3158    ,693,693,693
BEGIN DESCRIPTION:
CARRYALL CREEK 5.0
END DESCRIPTION:
XS GIS Cut Line= 3
      3607531.52     10350533.81      3606742.11     10350491.64
      3606025.86     10350457.49
#Sta/Elev= 30
    4213   333.8  4355.5  330.12  4442.7  328.94  4502.8  329.24  4624.3  325.46
  4733.2  319.09  4813.3  315.64  4923.4   313.9  4953.5  310.11  4973.5  310.78
  4983.5   309.7  4993.5   306.8    4998  306.48  5000.8  305.98    5004  306.48
  5023.6  311.44  5043.6  314.03  5093.6  314.77  5163.7  314.17  5183.7  316.79
  5193.8  317.19  5223.8  313.44  5243.8  313.16  5273.8  315.65  5283.9  318.04
  5318.7   317.1  5363.9  320.76  5484.1  327.46  5557.6  330.31  5720.6   335.2
#Mann= 6 ,-1 , 0
    4213     .05       0  4355.5     .12       0  4624.3     .05       0
    4998     .03       0    5004     .05       0  5557.6     .16       0
Bank Sta=4998,5004
XS Rating Curve= 0 ,0
Exp/Cntr=0.3,0.1

Type RM Length L Ch R = 1 ,2465    ,503,503,503
BEGIN DESCRIPTION:
CARRYALL CREEK 4.0
END DESCRIPTION:
XS GIS Cut Line= 3
      3607580.18     10350242.15      3606692.11     10349877.75
       3606242.1     10349827.75
#Sta/Elev= 30
  4453.3  330.61  4526.9   327.2  4627.7  324.38  4667.4   323.7  4721.4  325.08
    4835  319.08  4872.8  314.56  4937.1  311.97  4959.2  309.68  4966.5  310.29
  4971.9  307.65  4980.9  307.46  4999.5  303.75  5002.2  303.25  5005.5  303.75
  5013.3  304.86  5019.9   307.2  5025.3  310.64  5043.8  312.12    5197  311.94
  5483.7  316.29  5516.4  317.96  5574.2  325.83  5601.9  328.66  5624.5  329.79
  5644.6  328.29  5697.5  329.98  5815.7  327.78  5835.8  329.72    5866  330.85
#Mann= 4 ,-1 , 0
  4453.3     .05       0    4835     .16       0  4999.5     .07       0
  5005.5     .05       0
Bank Sta=4999.5,5005.5
XS Rating Curve= 0 ,0
Exp/Cntr=0.3,0.1

Type RM Length L Ch R = 1 ,1962    ,873,873,873
BEGIN DESCRIPTION:
CARRYALL CREEK 2.0
END DESCRIPTION:
XS GIS Cut Line= 3
      3607792.14     10349941.66      3607087.12     10349491.64
      3606492.12     10349491.64
#Sta/Elev= 30
  4454.5  335.54  4457.5  335.54  4468.1  331.68  4483.3  328.38  4504.5  325.82
  4665.2  320.72  4741.1  317.14  4879.5  312.34  4968.1  311.46  4976.5  309.11
  4983.4  303.91  4995.6  302.23  4998.3  301.73  5001.6  302.23  5004.5   302.8
  5019.7  308.06  5040.9  308.15  5056.1  310.29    5084  310.44  5228.7  308.82
    5244  310.03  5295.9  311.13  5545.9  314.47  5645.9  317.43  5655.9  318.81
  5695.9  320.14  5735.9  323.29  5765.9   323.9  5775.9  325.38  5885.9   330.1
#Mann= 6 ,-1 , 0
  4454.5     .16       0  4741.1     .05       0  4879.5     .16       0
  4976.5     .03       0  5004.5     .12       0    5084     .05       0
Bank Sta=4995.6,5001.6
XS Rating Curve= 0 ,0
Exp/Cntr=0.3,0.1

Type RM Length L Ch R = 1 ,1089    ,0,0,0
BEGIN DESCRIPTION:
CARRYALL CREEK 1.0
END DESCRIPTION:
XS GIS Cut Line= 3
      3608082.36     10349336.07      3607503.99     10349034.94
      3606559.33     10348957.43
#Sta/Elev= 30
  4652.5  327.57  4721.1  327.38  4781.8   325.7  4826.3  321.82  4842.5  316.92
  4848.1  317.07  4864.6  310.37  4870.2  310.79  4886.7   306.2  4936.5  307.42
  4968.5  309.27  4980.7  307.49    4991  303.88  4994.2  300.43  4996.9  299.93
  5000.2  300.43  5002.8  302.92  5013.6  304.87  5019.3   308.3  5024.9  308.77
  5083.3  308.52  5234.6  308.87    5301  308.45  5436.9  310.33  5577.4  309.96
  5737.9  311.63  5878.4  315.67  6119.2  326.35  6149.3  325.78  6252.4  328.13
#Mann= 6 ,-1 , 0
  4652.5     .05       0  4826.3     .12       0  4980.7     .03       0
  5013.6     .12       0  5083.3     .16       0  5234.6     .05       0
Bank Sta=4994.2,5000.2
XS Rating Curve= 0 ,0
Exp/Cntr=0.3,0.1

Chan Stop Cuts=-1
Use User Specified Reach Order=0
Composite Channel Slope=5