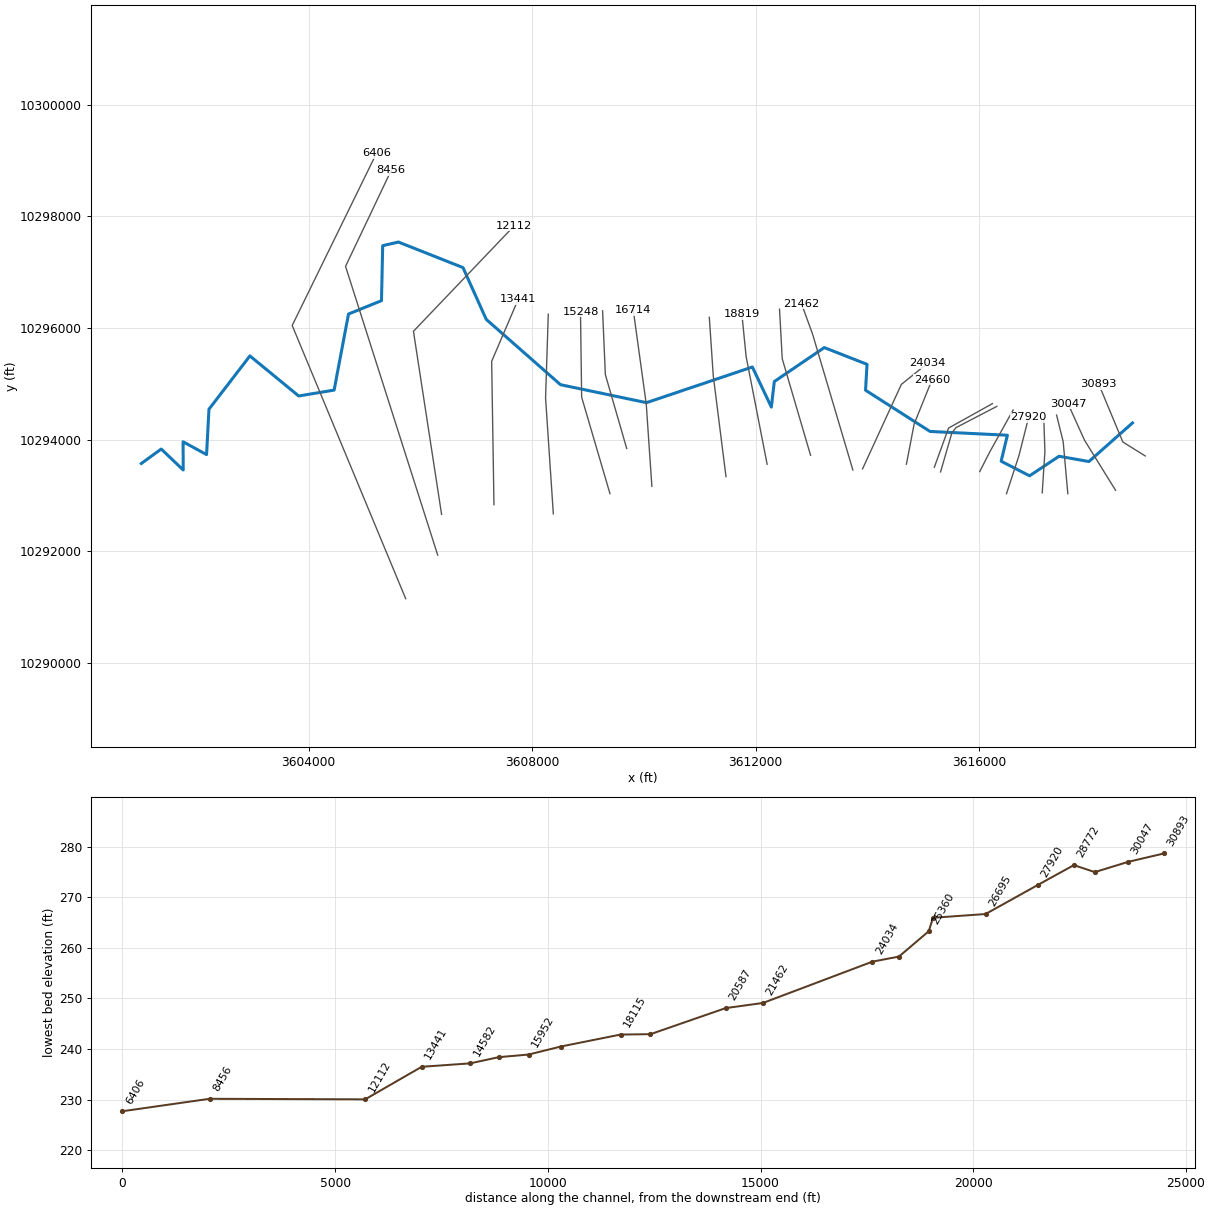
--- CARTER CREEK.prj (project) ---

Proj Title=CARTER CREEK Base Level Engineering
Current Plan=p01
Default Exp/Contr=0.3,0.1
English Units
Geom File=g01
Flow File=f01
Plan File=p01
Y Axis Title=Elevation
X Axis Title(PF)=Main Channel Distance
X Axis Title(XS)=Station
BEGIN DESCRIPTION:
 CARTER CREEK
END DESCRIPTION:
DSS Export Rating Curves= 0
DSS Export Rating Curve Sorted= 0
DSS Export Volume Flow Curves= 0
DXF OffsetX= 0
DXF OffsetY= 0
DXF ScaleX= 1
DXF ScaleY= 10

--- CARTER CREEK.p01 (plan) ---

Plan Title=Multiple Run
Short Identifier=Multiple
Geom File=g01
Flow File=f01
Subcritical Flow
K Sum by GR= 0
Std Step Tol= 0.01
Critical Tol= 0.01
Num of Std Step Trials= 20
Max Error Tol= 0.3
Flow Tol Ratio= 0.001
Split Flow NTrial= 30
Split Flow Tol= 0.02
Split Flow Ratio= 0.02
Log Output Level= 0
Friction Slope Method= 1
Unsteady Friction Slope Method= 2
Unsteady Bridges Friction Slope Method= 1
Parabolic Critical Depth
Global Vel Dist=  1 , 1 , 1
Global Log Level= 0
CheckData=True
Encroach Param= -1, 0, 0, 0
BEGIN DESCRIPTION:
Multiple Run
END DESCRIPTION:

--- CARTER CREEK.f01 (steady flow) ---

Flow Title=Multiple
Program Version=4.10
Number of Profiles= 7
Profile Names=10-year,25-year,50-year,1pct_min,100-year,1pct_plu,500-year
River Rch & RM=CARTER CREEK,Reach-1         ,30893
     731     988    1197    1062    1436    1942    2071
River Rch & RM=CARTER CREEK,Reach-1         ,21462
    2076    2925    3645    3313    4480    6059    6786
River Rch & RM=CARTER CREEK,Reach-1         ,16714
    2221    3127    3894    3535    4781    6466    7226
River Rch & RM=CARTER CREEK,Reach-1         ,8456
    2349    3311    4128    3750    5071    6858    7676
River Rch & RM=CARTER CREEK,Reach-1         ,6406
    2349    3301    4106    3721    5032    6805    7578
Boundary for River Rch & Prof#=CARTER CREEK,Reach-1         , 1
Up Type= 0
Dn Type= 3
Dn Slope=0.0012
Boundary for River Rch & Prof#=CARTER CREEK,Reach-1         , 2
Up Type= 0
Dn Type= 3
Dn Slope=0.0012
Boundary for River Rch & Prof#=CARTER CREEK,Reach-1         , 3
Up Type= 0
Dn Type= 3
Dn Slope=0.0012
Boundary for River Rch & Prof#=CARTER CREEK,Reach-1         , 4
Up Type= 0
Dn Type= 3
Dn Slope=0.0012
Boundary for River Rch & Prof#=CARTER CREEK,Reach-1         , 5
Up Type= 0
Dn Type= 3
Dn Slope=0.0012
Boundary for River Rch & Prof#=CARTER CREEK,Reach-1         , 6
Up Type= 0
Dn Type= 3
Dn Slope=0.0012
Boundary for River Rch & Prof#=CARTER CREEK,Reach-1         , 7
Up Type= 0
Dn Type= 3
Dn Slope=0.0012
DSS Import GetInterval= 0
DSS Import GetPeak= 0
DSS Import FillOption= 0

--- CARTER CREEK.g01 (geometry) ---

Geom Title=Existing Conditions
Program Version=4.10

River Reach=CARTER CREEK    ,Reach-1
Reach XY= 30
       3618744.4     10294298.12      3617965.04     10293606.75
      3617430.86     10293701.78      3616903.25     10293350.74
       3616394.3     10293612.57      3616505.74     10294078.05
      3615121.45     10294146.02       3613967.4     10294884.76
      3613993.97     10295348.82       3613228.9     10295648.87
      3612334.64     10295040.29      3612281.34     10294582.56
      3611941.81      10295300.6      3610046.84     10294661.82
      3608508.08      10294983.7      3607178.83     10296154.02
      3606762.74     10297082.31      3605607.17     10297540.19
      3605325.31     10297474.84      3605303.83     10296489.86
       3604713.7     10296250.58      3604456.07     10294887.19
      3603822.11     10294781.64      3602948.71     10295499.68
      3602216.17     10294544.65      3602172.81     10293731.28
      3601752.61     10293960.92      3601755.45      10293455.1
      3601361.75     10293830.86       3601006.1      10293572.1

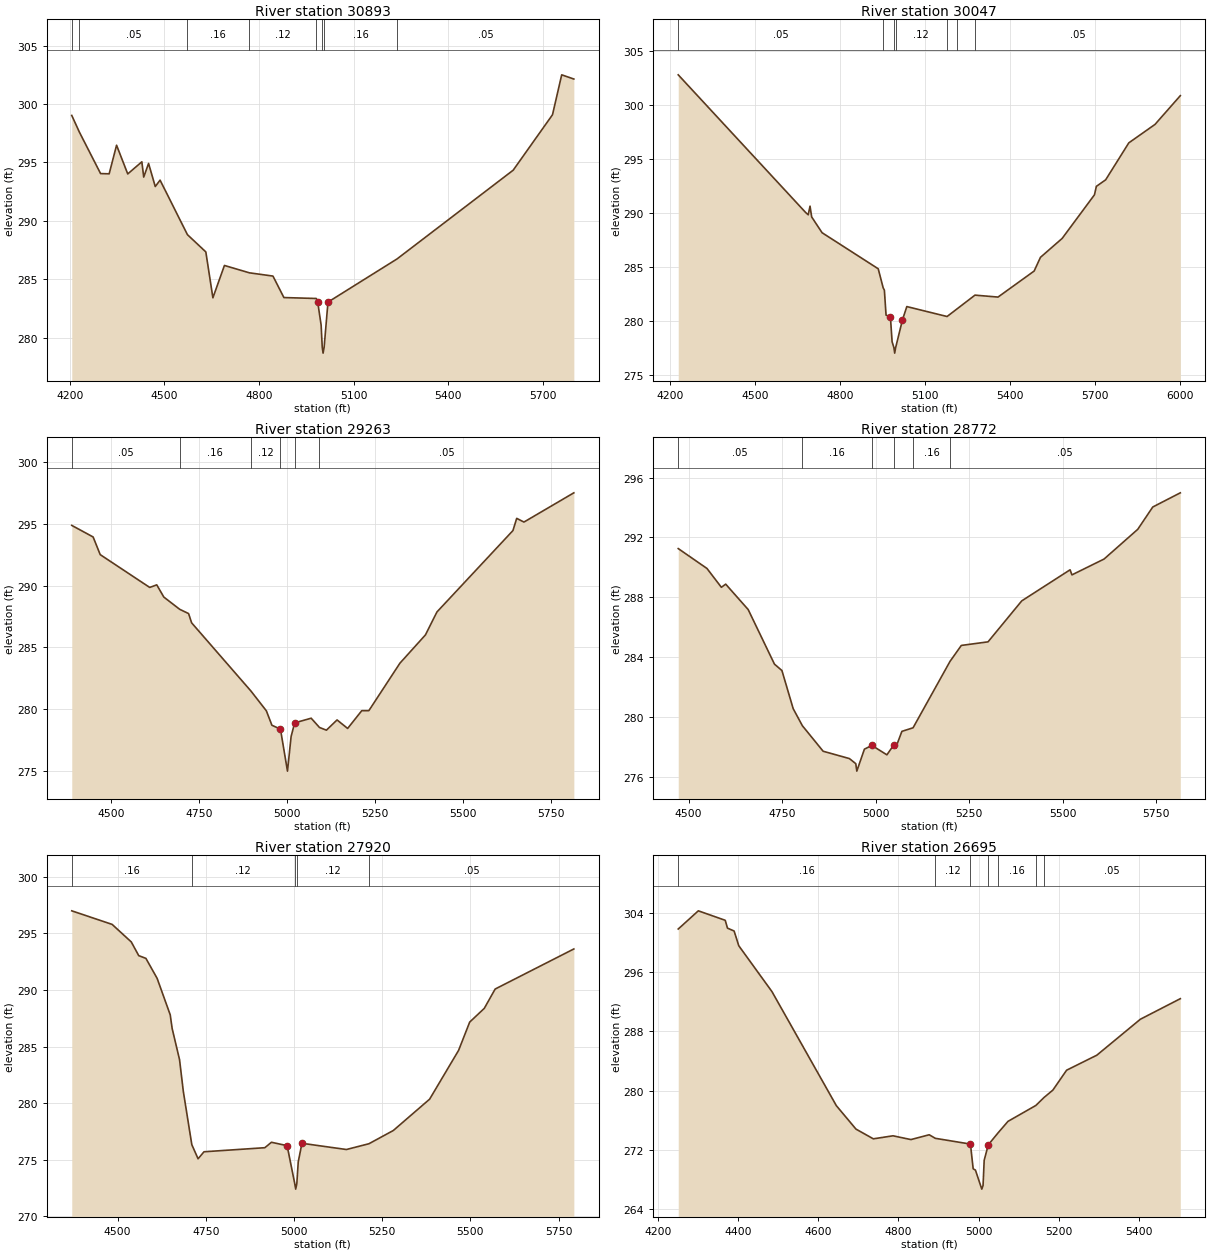
Type RM Length L Ch R = 1 ,30893   ,846,846,846
BEGIN DESCRIPTION:
CARTER CREEK 30.0
END DESCRIPTION:
XS GIS Cut Line= 3
      3618972.64     10293706.94      3618572.66     10293956.92
       3618142.1     10294991.65
#Sta/Elev= 30
  4205.9  299.03  4230.3  297.59  4297.3  294.05  4324.5  294.03    4348  296.48
  4383.4  294.02  4428.2  295.06  4434.1  293.75  4449.5  294.92  4470.7  292.94
    4486  293.49  4572.7  288.82  4631.1  287.34  4653.5  283.41  4690.1  286.18
    4769  285.55    4844  285.27  4878.7  283.43  4981.6  283.35    4986  283.03
  4996.8  281.07  5000.3  279.17    5003  278.67  5006.3  279.17  5018.5  283.04
  5237.6  286.74  5605.9  294.34  5730.6  299.09  5759.8  302.51  5798.3  302.15
#Mann= 8 ,-1 , 0
  4205.9     .16       0  4230.3     .05       0  4572.7     .16       0
    4769     .12       0  4981.6     .16       0  5000.3     .07       0
  5006.3     .16       0  5237.6     .05       0
Bank Sta=4986,5018.5
XS Rating Curve= 0 ,0
Exp/Cntr=0.3,0.1

Type RM Length L Ch R = 1 ,30047   ,784,784,784
BEGIN DESCRIPTION:
CARTER CREEK 28.0
END DESCRIPTION:
XS GIS Cut Line= 3
      3618442.08     10293091.68       3617886.3     10293989.46
      3617592.09     10294641.68
#Sta/Elev= 30
  4230.2  302.77  4679.8  290.02  4688.8  289.81  4695.2  290.61    4701  289.61
  4737.7  288.15  4935.8  284.81  4953.2  283.05  4957.5  282.83  4963.4  280.52
  4978.8  280.36  4984.7  278.06  4991.2   277.5  4993.9     277  4997.2   277.5
  5021.3  280.08  5036.7  281.31  5178.7  280.39  5212.1  281.06  5277.2  282.37
  5358.4  282.19  5485.9   284.6  5508.2  285.87  5584.7  287.62  5698.7  291.66
  5705.4  292.44  5738.3  293.05  5819.9  296.47  5912.4  298.18  6001.6  300.84
#Mann= 7 ,-1 , 0
  4230.2     .05       0  4953.2     .12       0  4991.2     .07       0
  4997.2     .12       0  5178.7     .05       0  5212.1     .12       0
  5277.2     .05       0
Bank Sta=4978.8,5021.3
XS Rating Curve= 0 ,0
Exp/Cntr=0.3,0.1

Type RM Length L Ch R = 1 ,29263   ,491,491,491
BEGIN DESCRIPTION:
CARTER CREEK 26.0
END DESCRIPTION:
XS GIS Cut Line= 3
      3617587.69     10293031.16      3617504.61     10293962.48
      3617386.71     10294439.19
#Sta/Elev= 30
  4388.3  294.89    4449  293.95  4469.1  292.52  4609.7  289.86  4629.7  290.07
  4649.8  289.08  4694.8  288.09  4720.1  287.74  4728.8  286.99    4897  281.47
    4941  279.86  4956.8  278.69  4981.1  278.37    5001  274.97  5011.3  277.77
  5021.3  278.88  5068.3  279.26  5091.9  278.51  5111.6  278.29  5141.8  279.12
  5171.9  278.43    5212  279.87  5232.1  279.87  5320.4  283.72  5392.8  286.01
  5425.5  287.87  5641.4  294.47  5652.1  295.46  5672.7  295.16  5814.4  297.53
#Mann= 6 ,-1 , 0
  4388.3     .05       0  4694.8     .16       0    4897     .12       0
  4981.1     .07       0  5021.3     .12       0  5091.9     .05       0
Bank Sta=4981.1,5021.3
XS Rating Curve= 0 ,0
Exp/Cntr=0.3,0.1

Type RM Length L Ch R = 1 ,28772   ,852,852,852
BEGIN DESCRIPTION:
CARTER CREEK 25.0
END DESCRIPTION:
XS GIS Cut Line= 3
      3617129.36     10293045.04      3617177.74     10293785.51
      3617157.13     10294385.31
#Sta/Elev= 30
  4472.1  291.25  4548.9  289.92  4587.4  288.66    4599  288.87  4659.1  287.17
  4729.3  283.52  4749.3  283.09  4779.4  280.54  4803.9   279.4  4859.5  277.69
  4929.7   277.2  4946.7  276.86  4949.5  276.36  4969.8  277.83  4989.8  278.08
  5029.9  277.45    5048   278.1    5053  277.89    5070  279.02  5099.9  279.26
  5198.6   283.7  5228.9  284.77  5300.3  285.01  5390.4  287.75  5519.6  289.83
  5524.6  289.49  5610.5  290.55  5700.6  292.54  5740.6  294.03  5814.3  294.98
#Mann= 6 ,-1 , 0
  4472.1     .05       0  4803.9     .16       0  4989.8     .07       0
    5048     .12       0  5099.9     .16       0  5198.6     .05       0
Bank Sta=4989.8,5048
XS Rating Curve= 0 ,0
Exp/Cntr=0.3,0.1

Type RM Length L Ch R = 1 ,27920   ,1225,1225,1225
BEGIN DESCRIPTION:
CARTER CREEK 24.0
END DESCRIPTION:
XS GIS Cut Line= 3
      3616490.47     10293031.14      3616712.69     10293711.69
      3616885.98     10294397.93
#Sta/Elev= 30
  4369.8     297  4484.3   295.8  4538.6  294.25  4559.7  293.04    4580   292.8
  4611.9  291.03    4649  287.81  4654.4  286.61  4675.4  283.85  4686.2  281.03
  4710.2  276.34    4728  275.09  4744.7  275.71  4917.3  276.07    4936  276.55
  4980.5  276.25    5002  272.91  5004.8  272.41    5008  272.91    5012  274.82
  5022.5  276.46  5148.6  275.91  5212.4  276.42  5281.6  277.59  5384.6  280.36
  5466.7  284.67  5498.2  287.17  5539.5  288.38  5570.4  290.09  5793.5  293.63
#Mann= 5 ,-1 , 0
  4369.8     .16       0  4710.2     .12       0    5002     .07       0
    5008     .12       0  5212.4     .05       0
Bank Sta=4980.5,5022.5
XS Rating Curve= 0 ,0
Exp/Cntr=0.3,0.1

Type RM Length L Ch R = 1 ,26695   ,1235,1235,1235
BEGIN DESCRIPTION:
CARTER CREEK 23.0
END DESCRIPTION:
XS GIS Cut Line= 3
       3616011.3     10293426.95      3616191.86     10293781.13
      3616607.83     10294529.89
#Sta/Elev= 30
  4249.9  301.85  4300.1  304.31  4367.3  303.03  4372.9  301.97  4389.5  301.58
  4401.1  299.59  4484.1  293.38  4644.9  277.96  4693.8   274.8  4737.2  273.48
  4786.4  273.89  4831.1  273.38  4876.8  274.03    4892  273.55  4979.8  272.77
  4986.6  269.43  4992.3  269.25  5008.1  266.68  5011.3  267.18  5014.1  270.58
  5024.4  272.68  5048.7  274.28  5073.5  275.84  5143.1  277.99  5163.6  279.07
  5185.7  280.07    5220  282.76  5295.5  284.79  5404.2  289.65    5504  292.43
#Mann= 7 ,-1 , 0
  4249.9     .16       0    4892     .12       0  4979.8     .07       0
  5024.4     .12       0  5048.7     .16       0  5143.1     .12       0
  5163.6     .05       0
Bank Sta=4979.8,5024.4
XS Rating Curve= 0 ,0
Exp/Cntr=0.3,0.1

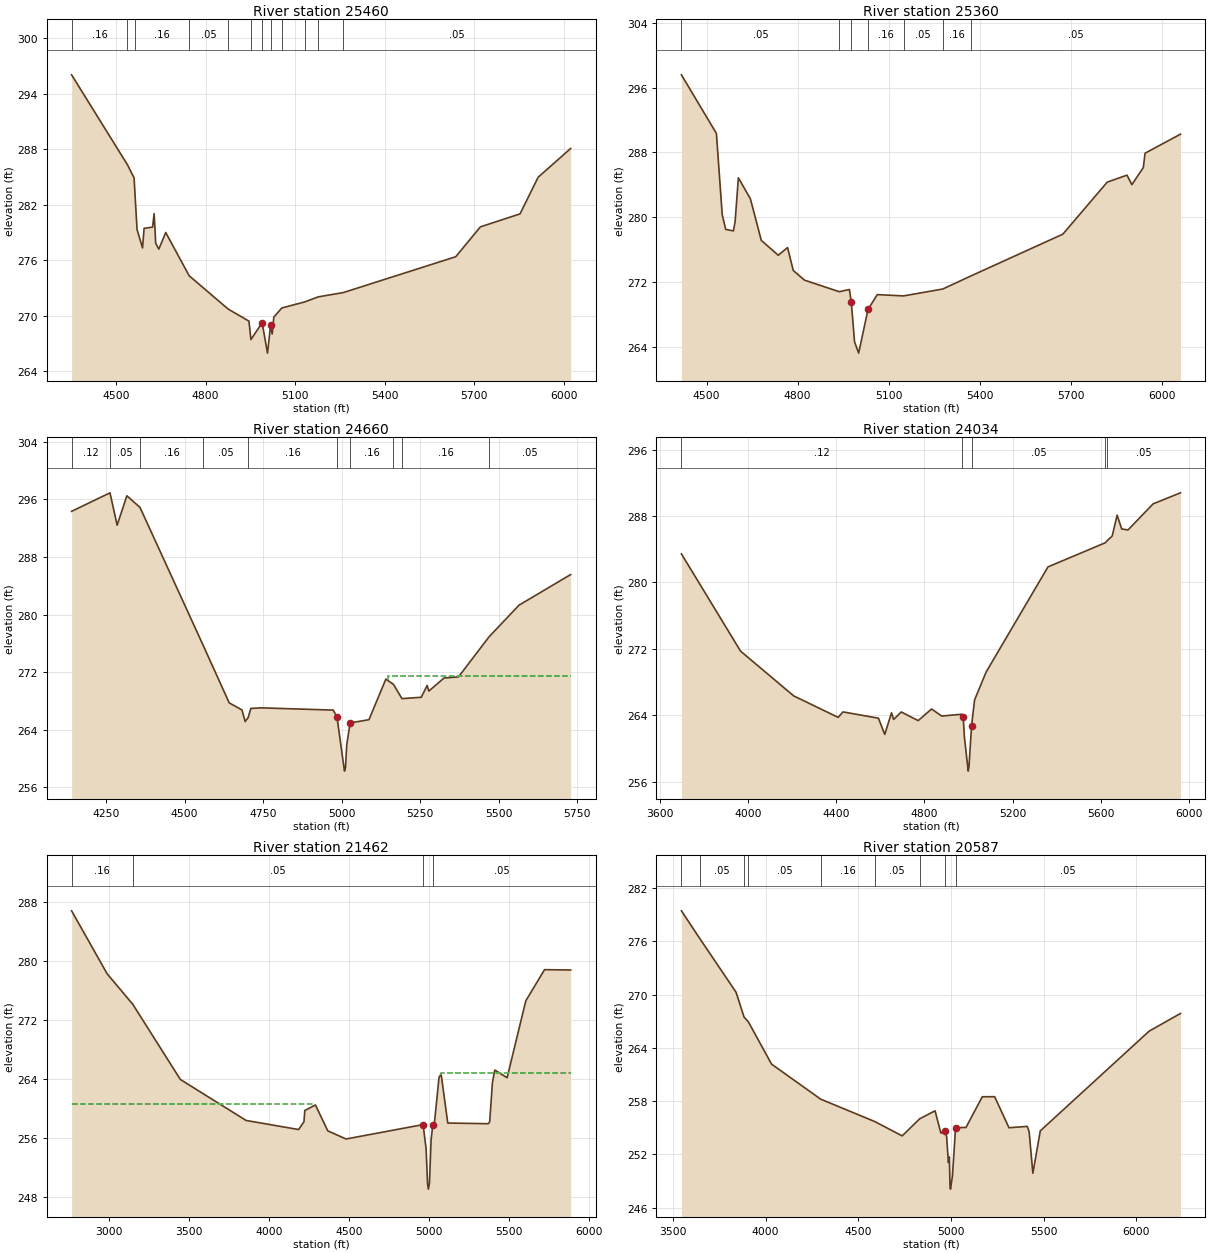
Type RM Length L Ch R = 1 ,25460   ,100,100,100
BEGIN DESCRIPTION:
CARTER CREEK 21.0
END DESCRIPTION:
XS GIS Cut Line= 4
      3615310.22     10293421.11      3615512.04      10294117.7
      3615583.65     10294213.18      3616317.17     10294595.14
#Sta/Elev= 30
  4351.2  296.02  4538.2   286.3  4560.4  284.88  4563.4  283.21  4570.4   279.3
  4588.8  277.31    4594  279.43  4622.4  279.56  4627.6  281.02  4632.9  277.82
  4643.3  277.18  4666.4  278.98    4745   274.3  4876.1  270.69  4945.2   269.4
  4951.9  267.41  4989.4  269.22  5007.4  265.94  5017.8     269    5023  268.01
  5028.5  269.83  5055.3  270.82  5132.6  271.48  5177.1  272.02  5260.8  272.48
  5637.9  276.36  5720.6  279.59  5853.2  280.99  5913.9  284.95  6022.8  288.06
#Mann= 12 ,-1 , 0
  4351.2     .16       0  4538.2     .05       0  4563.4     .16       0
    4745     .05       0  4876.1     .16       0  4951.9     .05       0
  4989.4     .07       0  5017.8     .05       0  5055.3     .16       0
  5132.6     .05       0  5177.1     .16       0  5260.8     .05       0
Bank Sta=4989.4,5017.8
XS Rating Curve= 0 ,0
Exp/Cntr=0.3,0.1

Type RM Length L Ch R = 1 ,25360   ,700,700,700
BEGIN DESCRIPTION:
CARTER CREEK 20.0
END DESCRIPTION:
XS GIS Cut Line= 3
      3615198.88     10293505.28      3615452.79     10294206.24
      3616237.73     10294644.24
#Sta/Elev= 30
  4417.1  297.57  4532.4  290.35  4551.5  280.34  4563.1  278.52  4588.4  278.34
    4594  279.47  4604.7  284.88  4644.3   282.3  4680.3  277.17  4736.2  275.34
  4766.9  276.29  4785.5  273.47  4822.8  272.27    4937  270.85  4970.7  271.12
  4976.9  269.55  4987.6  264.67  5001.1  263.28    5032  268.67  5062.6  270.49
  5148.9  270.33  5278.3  271.18  5371.1  272.79    5674  277.94  5820.2  284.35
  5885.4  285.21  5901.4  284.04  5939.1  286.14  5944.8  287.91  6061.5  290.26
#Mann= 7 ,-1 , 0
  4417.1     .05       0    4937     .16       0  4976.9     .05       0
    5032     .16       0  5148.9     .05       0  5278.3     .16       0
  5371.1     .05       0
Bank Sta=4976.9,5032
XS Rating Curve= 0 ,0
Exp/Cntr=0.3,0.1

Type RM Length L Ch R = 1 ,24660   ,626,626,626
BEGIN DESCRIPTION:
CARTER CREEK 19.0
END DESCRIPTION:
XS GIS Cut Line= 3
      3614698.81     10293558.95      3614837.69     10294281.13
      3615157.13      10295072.8
#Sta/Elev= 30
  4140.3  294.32  4262.5  296.89  4285.3   292.4  4316.2  296.48    4358  294.87
  4559.6  275.69    4642  267.75  4682.8  266.76  4692.9  265.15  4702.4   265.7
    4711  266.97  4743.9  267.05  4973.3  266.74  4985.3   265.8  5009.2  258.27
  5012.4  258.77  5016.4  261.93  5027.2  264.96  5087.2  265.41  5140.9  271.04
    5165  270.32  5192.2  268.33  5253.7  268.52  5272.4  270.16  5277.8  269.38
  5326.1  271.19  5372.3  271.35  5469.2  276.89    5565   281.3  5729.4  285.55
#Mann= 10 ,-1 , 0
  4140.3     .12       0  4262.5     .05       0    4358     .16       0
  4559.6     .05       0  4702.4     .16       0  4985.3    .035       0
  5027.2     .16       0    5165     .05       0  5192.2     .16       0
  5469.2     .05       0
#XS Ineff= 2 , 0
                         5146.48          271.46
Permanent Ineff=
       F       F
Bank Sta=4985.3,5027.2
XS Rating Curve= 0 ,0
Exp/Cntr=0.3,0.1

Type RM Length L Ch R = 1 ,24034   ,2572,2572,2572
BEGIN DESCRIPTION:
CARTER CREEK 18.0
END DESCRIPTION:
XS GIS Cut Line= 3
      3613914.09      10293475.6      3614608.52     10294989.46
      3615073.78     10295364.45
#Sta/Elev= 30
  3698.5  283.45  3966.6  271.73  4207.6  266.33  4409.3  263.74  4431.3   264.4
    4592  263.64  4620.5  261.69  4651.3  264.29    4661  263.49  4695.3  264.39
  4772.3  263.35  4832.9  264.75  4878.9   263.9    4971  264.12  4976.4  263.82
  4981.9  261.34  4999.1  257.26  5002.4  257.76  5014.4  262.76  5027.9  265.84
  5080.4  269.21  5360.8  281.88  5620.7  284.79  5629.8  285.06    5652   285.6
  5674.4  288.12  5695.2  286.45    5724  286.34  5837.5  289.48  5961.6  290.81
#Mann= 5 ,-1 , 0
  3698.5     .12       0    4971    .035       0  5014.4     .05       0
  5620.7     .16       0  5629.8     .05       0
Bank Sta=4976.4,5014.4
XS Rating Curve= 0 ,0
Exp/Cntr=0.3,0.1

Type RM Length L Ch R = 1 ,21462   ,875,875,875
BEGIN DESCRIPTION:
CARTER CREEK 17.0
END DESCRIPTION:
XS GIS Cut Line= 3
      3613740.46     10293454.75      3613019.88     10295888.86
      3612820.28     10296437.77
#Sta/Elev= 30
  2765.6  286.78  2987.7  278.26  3148.4  274.12  3446.1  263.94  3857.4  258.39
  4186.2  257.16  4219.5  258.22  4224.7  259.74  4291.2  260.49  4368.4  256.98
  4483.1  255.88  4964.9  257.83  4983.7  254.56  4992.9   249.8  4997.9  249.09
  5004.6   249.9    5015  255.77  5025.4  257.75  5036.6  258.22  5064.6  264.23
  5077.6  264.68  5119.3  258.04  5373.5  257.95  5381.6  258.23  5398.8  263.54
  5413.5  265.22  5490.6  264.18  5607.6  274.59  5724.7  278.81  5888.2  278.77
#Mann= 4 ,-1 , 0
  2765.6     .16       0  3148.4     .05       0  4964.9    .035       0
  5025.4     .05       0
#XS Ineff= 2 , 0
         4275.85  260.65 5075.28          264.78
Permanent Ineff=
       F       F
Bank Sta=4964.9,5025.4
XS Rating Curve= 0 ,0
Exp/Cntr=0.3,0.1

Type RM Length L Ch R = 1 ,20587   ,1768,1768,1768
BEGIN DESCRIPTION:
CARTER CREEK 15.0
END DESCRIPTION:
XS GIS Cut Line= 3
      3612983.52     10293718.63      3612476.58      10295447.8
      3612427.97     10296336.62
#Sta/Elev= 30
  3545.8  279.45  3648.3  276.22  3840.7  270.27  3883.4  267.49  3907.4  266.92
  4032.1  262.17  4297.2  258.22  4589.5  255.69  4736.7  254.08  4830.7     256
  4914.1  256.91  4945.3   254.4  4966.2  254.64  4976.6  253.98  4986.1  251.07
  4991.3  251.71  4994.4  248.58  4997.2  248.08  5007.9  249.57  5024.7  255.01
  5080.8  255.03  5168.8  258.49  5235.6   258.5  5312.8     255  5411.7  255.15
  5421.7  254.53  5441.7  249.87  5481.8  254.65  6069.1  265.89  6237.9  267.88
#Mann= 9 ,-1 , 0
  3545.8     .16       0  3648.3     .05       0  3883.4     .16       0
  3907.4     .05       0  4297.2     .16       0  4589.5     .05       0
  4830.7     .05       0  4966.2    .035       0  5024.7     .05       0
#XS Ineff= 2 , 0
                         5129.55          256.35
Permanent Ineff=
       F       F
Bank Sta=4966.2,5024.7
XS Rating Curve= 0 ,0
Exp/Cntr=0.3,0.1

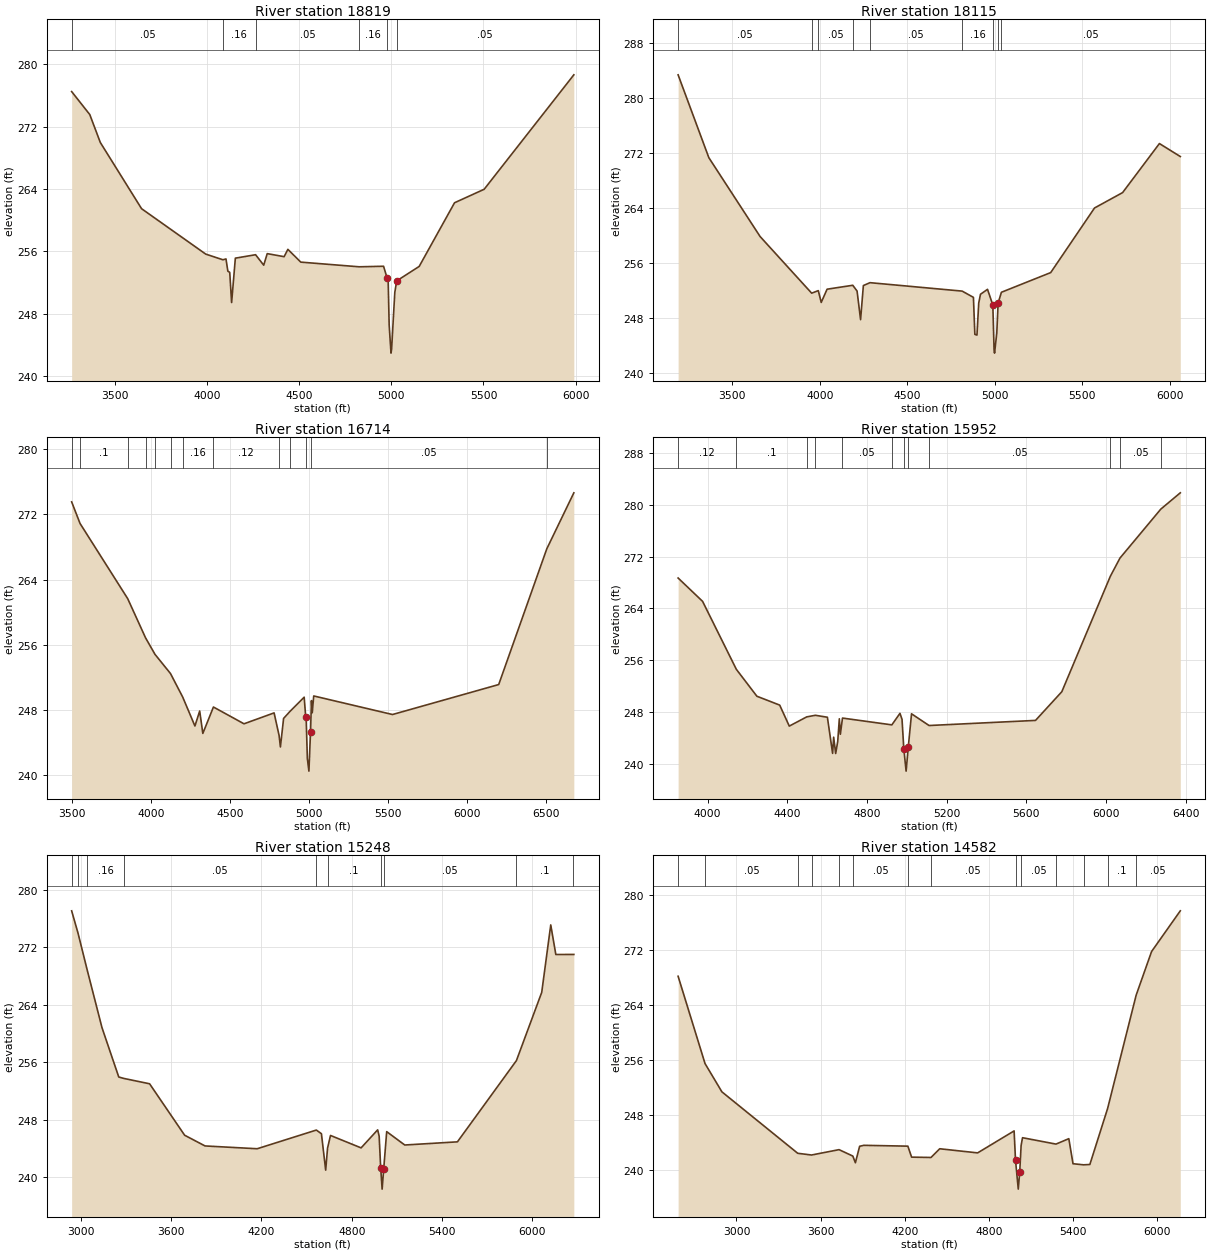
Type RM Length L Ch R = 1 ,18819   ,704,704,704
BEGIN DESCRIPTION:
CARTER CREEK 14.0
END DESCRIPTION:
XS GIS Cut Line= 3
      3612205.75      10293558.9      3611829.61     10295490.25
      3611754.36     10296246.38
#Sta/Elev= 30
  3263.4  276.49  3361.9  273.54    3419  269.96  3643.1  261.46  3991.6  255.63
  4085.3   254.9  4101.6  255.01  4111.8  253.44    4122  253.29  4132.2  249.41
  4152.5  255.11  4262.4  255.55  4306.5  254.21  4325.7  255.69  4417.4   255.3
  4437.8  256.24  4507.9   254.6  4825.1     254  4957.4  254.07  4977.6   252.5
  4982.7  252.01  4987.9  246.54  4997.9  242.92  5001.1  243.42  5018.5   250.7
  5028.7  252.19    5151  254.05    5343  262.22  5503.8  263.95  5990.9  278.64
#Mann= 6 ,-1 , 0
  3263.4     .05       0  4085.3     .16       0  4262.4     .05       0
  4825.1     .16       0  4977.6    .035       0  5028.7     .05       0
Bank Sta=4977.6,5028.7
XS Rating Curve= 0 ,0
Exp/Cntr=0.3,0.1

Type RM Length L Ch R = 1 ,18115   ,1401,1401,1401
BEGIN DESCRIPTION:
CARTER CREEK 13.0
END DESCRIPTION:
XS GIS Cut Line= 3
      3611469.63     10293336.69      3611242.11     10295141.64
      3611171.03      10296190.8
#Sta/Elev= 30
  3190.5  283.41  3366.2  271.33  3659.1  259.84  3953.9  251.58  3991.9  251.95
  4008.6  250.23  4042.1  252.16  4188.9  252.73  4213.5  251.89  4233.6  247.72
  4249.5  252.69  4287.4  253.11  4814.4  251.88  4878.7  250.97  4886.8  245.58
  4898.9  245.47  4908.9  250.13    4919  251.42  4959.3  252.14  4989.6  249.85
  4996.7  243.34  4999.4  242.84  5012.2  245.76  5019.8  250.13  5038.5  251.71
  5320.4  254.58    5571     264  5731.4  266.24  5941.9  273.39  6061.3   271.5
#Mann= 9 ,-1 , 0
  3190.5     .05       0  3953.9     .16       0  3991.9     .05       0
  4188.9     .16       0  4287.4     .05       0  4814.4     .16       0
  4989.6    .035       0  5019.8     .16       0  5038.5     .05       0
Bank Sta=4989.6,5019.8
XS Rating Curve= 0 ,0
Exp/Cntr=0.3,0.1

Type RM Length L Ch R = 1 ,16714   ,762,762,762
BEGIN DESCRIPTION:
CARTER CREEK 11.0
END DESCRIPTION:
XS GIS Cut Line= 3
      3610143.24     10293163.08      3610042.11     10294641.64
      3609809.92     10296322.76
#Sta/Elev= 30
  3497.9  273.54    3551  270.89  3852.7  261.66  3965.7  256.85  4025.5  254.82
  4123.7  252.46    4201  249.57  4278.3  246.02  4308.4  247.86  4328.4  245.11
  4395.5  248.35    4589  246.29  4779.5  247.63    4811  244.87  4819.5  243.45
  4839.6  246.95  4878.5  247.78  4969.9  249.56  4979.9  247.08  4982.4  247.08
    4990  242.04  4999.9  240.48  5010.2  245.33  5015.9  249.14  5020.9  247.64
  5030.4  249.71  5529.1  247.43  6201.4  251.11  6505.7  267.77    6677  274.65
#Mann= 13 ,-1 , 0
  3497.9     .16       0    3551      .1       0  3852.7     .05       0
  3965.7      .1       0  4025.5     .05       0  4123.7      .1       0
    4201     .16       0  4395.5     .12       0    4811      .1       0
  4878.5     .05       0  4982.4    .035       0  5010.2     .05       0
  6505.7      .1       0
Bank Sta=4979.9,5010.2
XS Rating Curve= 0 ,0
Exp/Cntr=0.3,0.1

Type RM Length L Ch R = 1 ,15952   ,704,704,704
BEGIN DESCRIPTION:
CARTER CREEK 9.0
END DESCRIPTION:
XS GIS Cut Line= 3
      3609692.12     10293841.61      3609310.65     10295164.17
      3609261.35     10296307.73
#Sta/Elev= 30
  3851.8   268.7  3974.8  265.09    4144  254.61  4247.3  250.45  4361.8  249.08
  4409.9  245.84  4497.2  247.26  4540.6  247.51  4601.2  247.21  4627.4  241.63
  4632.6  244.13  4642.8  241.61  4653.2   243.5  4661.1  246.97  4666.3  244.58
    4677  247.08  4924.8  246.03  4965.5  247.81  4975.9  246.88  4984.8  242.34
  4996.4  238.89  5007.1  242.55  5023.6  247.74  5111.6  245.93  5646.1  246.72
  5778.1  251.15  6021.7  268.97  6070.1  271.78  6275.2  279.34  6372.9  281.85
#Mann= 12 ,-1 , 0
  3851.8     .12       0    4144      .1       0  4497.2     .05       0
  4540.6      .1       0    4677     .05       0  4924.8      .1       0
  4984.8     .07       0  5007.1      .1       0  5111.6     .05       0
  6021.7     .16       0  6070.1     .05       0  6275.2     .16       0
Bank Sta=4984.8,5007.1
XS Rating Curve= 0 ,0
Exp/Cntr=0.3,0.1

Type RM Length L Ch R = 1 ,15248   ,666,666,666
BEGIN DESCRIPTION:
CARTER CREEK 8.0
END DESCRIPTION:
XS GIS Cut Line= 3
      3609393.23     10293031.18       3608886.3      10294760.3
      3608865.47     10296295.06
#Sta/Elev= 30
  2938.9   277.1  2981.1  274.01  3041.6  268.92  3140.5  260.84    3252  253.97
  3284.7  253.78  3456.8  253.03  3689.7  245.87  3825.2  244.38  4171.7  243.99
  4564.8  246.59  4598.6  246.08  4626.8  241.01  4639.2  244.07  4658.8  245.84
  4862.2  244.11  4972.2  246.62  4982.2  245.73  4992.2  241.36  5001.9  238.37
  5012.2  241.12  5032.2  246.37  5152.2  244.51  5502.2  244.95  5894.3  256.26
  6062.3  265.75  6122.3  275.14  6156.1  271.02  6273.3  271.03  6275.7  271.03
#Mann= 10 ,-1 , 0
  2938.9     .16       0  2981.1     .05       0  3041.6     .16       0
  3284.7     .05       0  4564.8     .16       0  4639.2      .1       0
  4992.2     .05       0  5012.2     .05       0  5894.3      .1       0
  6273.3     .16       0
Bank Sta=4992.2,5012.2
XS Rating Curve= 0 ,0
Exp/Cntr=0.3,0.1

Type RM Length L Ch R = 1 ,14582   ,1141,1141,1141
BEGIN DESCRIPTION:
CARTER CREEK 7.0
END DESCRIPTION:
XS GIS Cut Line= 3
      3608379.36     10292669.97      3608240.47     10294746.41
      3608289.08     10296246.44
#Sta/Elev= 30
  2583.6  268.16  2775.6  255.44    2896  251.32  3436.8  242.37    3535  242.12
  3731.4   242.9  3829.6  241.97  3848.1  240.99  3878.2  243.39  3908.2  243.53
  4222.3  243.41    4249  241.81  4387.4  241.76  4449.4  243.03  4719.9  242.43
  4980.1  245.63  4990.1  241.36  5009.8  237.15  5020.1  239.64  5030.1  243.51
  5040.1  244.64  5278.8  243.71  5370.3   244.5  5400.3  240.85  5475.3  240.69
  5520.4  240.74  5646.8  248.88  5850.7  265.41  5960.6  271.76  6165.5  277.69
#Mann= 14 ,-1 , 0
  2583.6      .1       0  2775.6     .05       0  3436.8      .1       0
    3535     .05       0  3731.4      .1       0  3829.6     .05       0
  4222.3      .1       0  4387.4     .05       0  4990.1    .035       0
  5030.1     .05       0  5278.8      .1       0  5475.3     .05       0
  5646.8      .1       0  5850.7     .05       0
Bank Sta=4990.1,5020.1
XS Rating Curve= 0 ,0
Exp/Cntr=0.3,0.1

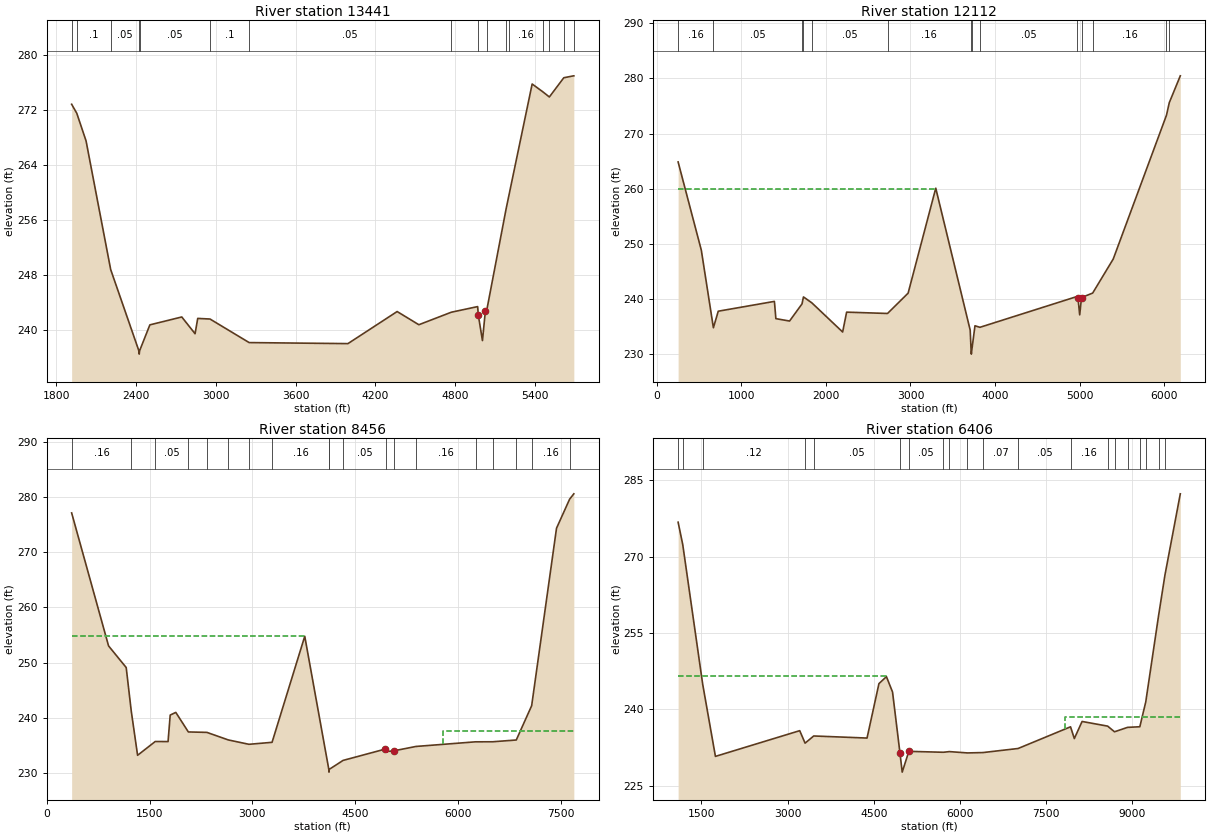
Type RM Length L Ch R = 1 ,13441   ,1329,1329,1329
BEGIN DESCRIPTION:
CARTER CREEK 6.0
END DESCRIPTION:
XS GIS Cut Line= 3
      3607316.86      10292833.2      3607275.72     10295402.28
      3607750.88     10296513.76
#Sta/Elev= 30
  1914.1  272.85  1952.7  271.54  2022.6  267.51  2207.8  248.78  2419.6  236.97
  2422.4  236.47  2425.6  236.97  2502.6  240.73  2742.6  241.88  2842.7  239.44
  2862.7  241.67  2955.1  241.58  3249.6  238.15  3992.8     238  4362.9  242.67
  4526.3  240.75  4770.2  242.57  4968.6  243.39    4974  242.11  5004.8  238.44
  5026.6  242.72  5037.5   242.9  5182.2  257.56  5205.7  259.75  5378.7   275.8
  5460.6  274.64  5508.1  273.91  5616.7  276.71  5690.8  276.99  5692.3  276.99
#Mann= 16 ,-1 , 0
  1914.1     .05       0  1952.7      .1       0  2207.8     .05       0
  2419.6    .035       0  2425.6     .05       0  2955.1      .1       0
  3249.6     .05       0  4770.2      .1       0  4968.6     .05       0
  5037.5     .16       0  5182.2     .12       0  5205.7     .16       0
  5460.6     .05       0  5508.1     .16       0  5616.7     .05       0
  5690.8     .12       0
Bank Sta=4974,5026.6
XS Rating Curve= 0 ,0
Exp/Cntr=0.3,0.1

Type RM Length L Ch R = 1 ,12112   ,3656,3656,3656
BEGIN DESCRIPTION:
CARTER CREEK 5.0
END DESCRIPTION:
XS GIS Cut Line= 3
      3606379.35     10292659.61      3605875.88     10295940.85
      3607681.45     10297833.23
#Sta/Elev= 30
   253.8  264.87   528.2  248.86   670.8  234.81   728.2  237.81  1391.8  239.59
  1409.2  236.46  1571.1  236.03  1718.2  239.14  1735.2   240.4  1833.9  239.33
  2198.3  234.04  2245.3  237.64  2728.8   237.4  2972.1  241.08  3298.8  260.11
  3705.7  234.38  3716.9  230.53  3719.6  230.03  3722.9  230.53  3762.3  235.17
  3820.6  234.89  4971.6  240.49  4978.9  240.29    5000  237.15  5021.4  240.28
  5153.4   241.1  5396.3  247.27  6025.8  273.35  6058.9  275.62    6189  280.48
#Mann= 14 ,-1 , 0
   253.8     .16       0   670.8     .05       0  1718.2     .12       0
  1735.2      .1       0  1833.9     .05       0  2728.8     .16       0
  3716.9     .07       0  3722.9     .16       0  3820.6     .05       0
  4971.6     .05       0  5021.4     .12       0  5153.4     .16       0
  6025.8     .12       0  6058.9     .16       0
#XS Ineff= 2 , 0
         3293.18  260.04
Permanent Ineff=
       F       F
Bank Sta=4978.9,5021.4
XS Rating Curve= 0 ,0
Exp/Cntr=0.3,0.1

Type RM Length L Ch R = 1 ,8456    ,2050,2050,2050
BEGIN DESCRIPTION:
CARTER CREEK 4.0
END DESCRIPTION:
XS GIS Cut Line= 3
       3606309.9     10291930.48      3604660.61     10297104.05
      3605476.58      10298822.8
#Sta/Elev= 30
   361.6   277.1   900.5  253.01  1158.1  249.09  1232.2  241.18  1324.4  233.19
  1582.5  235.69  1769.3  235.67  1800.7  240.48  1882.4  240.96  2065.6  237.42
  2336.2  237.34  2649.6  235.97  2950.8  235.18  3287.9  235.54  3765.3  254.75
  4116.6  230.64  4119.3  230.14  4122.6  230.64  4324.3  232.26    4939  234.31
    4951  233.85  5074.5  234.02  5388.7  234.79  6258.7  235.63  6508.5  235.64
  6853.7  235.96  7078.4  242.17  7441.5  274.33  7632.7  279.59  7694.3  280.56
#Mann= 19 ,-1 , 0
   361.6     .16       0  1232.2     .12       0  1582.5     .05       0
  2065.6     .16       0  2336.2     .05       0  2649.6      .1       0
  2950.8     .05       0  3287.9     .16       0  4116.6    .035       0
  4122.6     .16       0  4324.3     .05       0    4951     .07       0
  5074.5     .05       0  5388.7     .16       0  6258.7     .12       0
  6508.5     .07       0  6853.7     .12       0  7078.4     .16       0
  7632.7     .05       0
#XS Ineff= 2 , 0
         3763.64  254.86 5777.27          237.66
Permanent Ineff=
       F       F
Bank Sta=4939,5074.5
XS Rating Curve= 0 ,0
Exp/Cntr=0.3,0.1

Type RM Length L Ch R = 1 ,6406    ,0,0,0
BEGIN DESCRIPTION:
CARTER CREEK 1.0
END DESCRIPTION:
XS GIS Cut Line= 3
      3605737.01     10291149.15      3603705.74     10296045.02
      3605216.17     10299135.32
#Sta/Elev= 30
  1096.2  276.76  1176.7  272.37  1523.6  244.97  1745.7  230.77  3212.6  235.82
    3306  233.37  3456.5  234.78  4384.3  234.37  4591.5  245.06  4721.7  246.43
  4828.1  243.41  4958.3  231.34  4996.2  227.68  5112.3  231.76  5712.6  231.58
  5817.3  231.71  6131.2  231.45  6399.5  231.52  7013.3  232.32  7925.9  236.58
  7992.1  234.27  8127.2  237.63    8572  236.71  8691.6   235.6    8918  236.47
    9132  236.59  9234.7  241.44  9457.6  258.36    9569  266.37  9836.4  282.33
#Mann= 20 ,-1 , 0
  1096.2     .12       0  1176.7     .16       0  1523.6     .12       0
    3306      .1       0  3456.5     .05       0  4958.3    .035       0
  5112.3     .05       0  5712.6     .16       0  5817.3     .05       0
  6131.2     .16       0  6399.5     .07       0  7013.3     .05       0
  7925.9     .16       0    8572     .12       0  8691.6     .16       0
    8918     .16       0    9132     .12       0  9234.7     .16       0
  9457.6     .05       0    9569      .1       0
#XS Ineff= 2 , 0
         4715.91  246.63 7829.55          238.49
Permanent Ineff=
       F       F
Bank Sta=4958.3,5112.3
XS Rating Curve= 0 ,0
Exp/Cntr=0.3,0.1

Chan Stop Cuts=-1
Use User Specified Reach Order=0
Composite Channel Slope=5