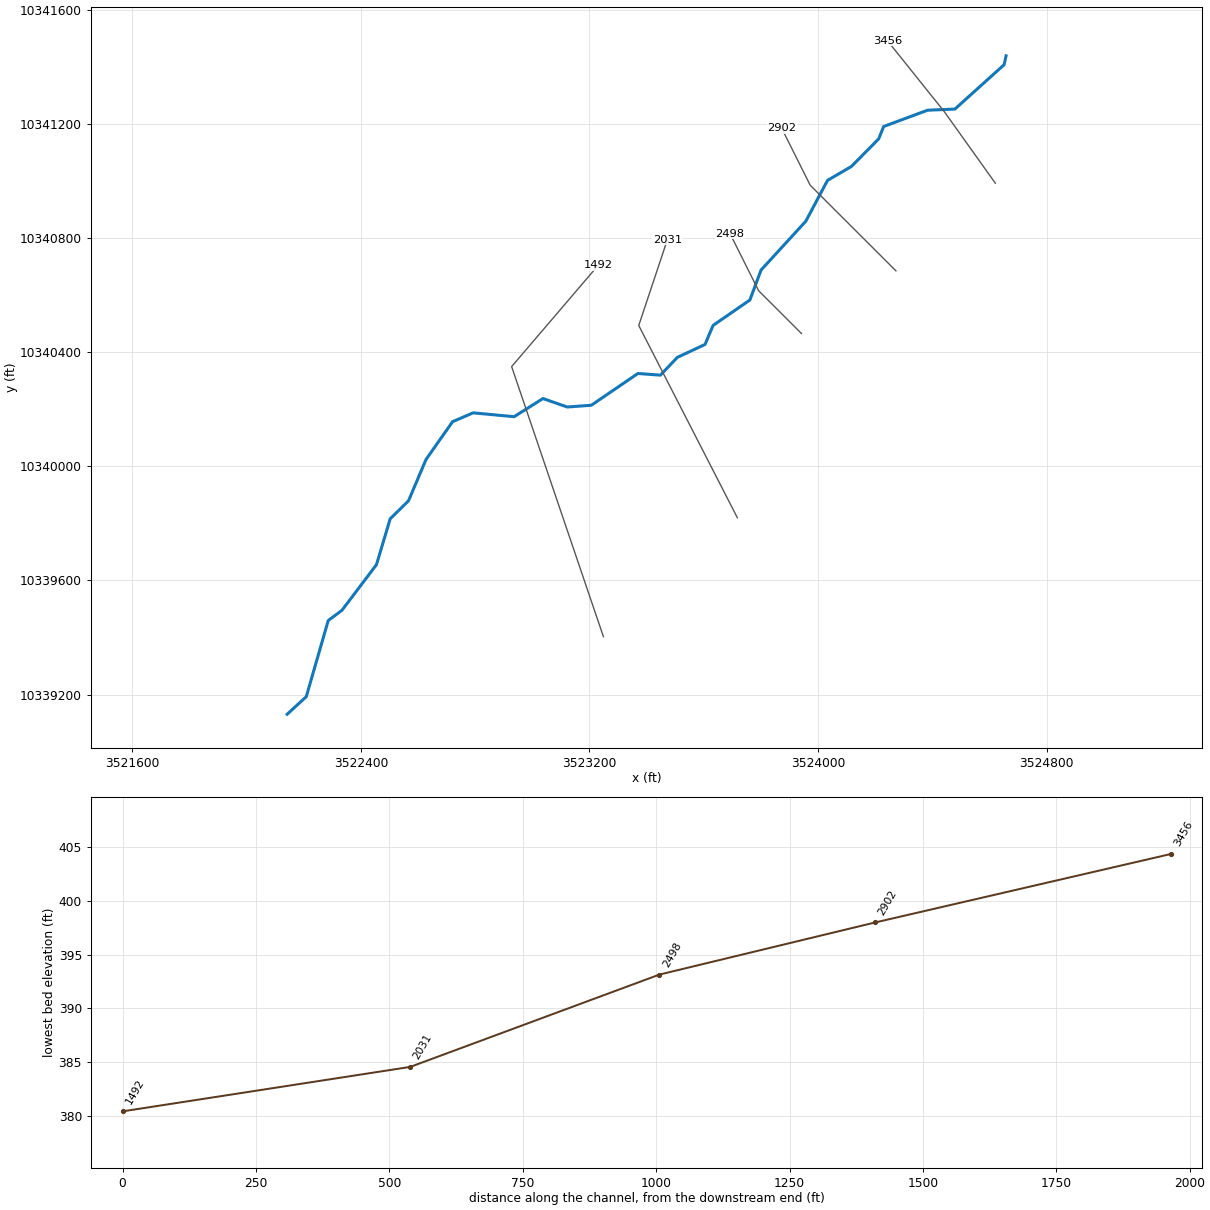
--- CEDAR CREEK TRIBUTARY 11.prj (project) ---

Proj Title=CEDAR CREEK TRIBUTARY 11 Base Level Engineering
Current Plan=p01
Default Exp/Contr=0.3,0.1
English Units
Geom File=g01
Flow File=f01
Plan File=p01
Y Axis Title=Elevation
X Axis Title(PF)=Main Channel Distance
X Axis Title(XS)=Station
BEGIN DESCRIPTION:
CEDAR CREEK TRIBUTARY 11
END DESCRIPTION:
DSS Export Rating Curves= 0
DSS Export Rating Curve Sorted= 0
DSS Export Volume Flow Curves= 0
DXF OffsetX= 0
DXF OffsetY= 0
DXF ScaleX= 1
DXF ScaleY= 10

--- CEDAR CREEK TRIBUTARY 11.p01 (plan) ---

Plan Title=Multiple Run
Short Identifier=Multiple
Geom File=g01
Flow File=f01
Subcritical Flow
K Sum by GR= 0
Std Step Tol= 0.01
Critical Tol= 0.01
Num of Std Step Trials= 20
Max Error Tol= 0.3
Flow Tol Ratio= 0.001
Split Flow NTrial= 30
Split Flow Tol= 0.02
Split Flow Ratio= 0.02
Log Output Level= 0
Friction Slope Method= 1
Unsteady Friction Slope Method= 2
Unsteady Bridges Friction Slope Method= 1
Parabolic Critical Depth
Global Vel Dist=  1 , 1 , 1
Global Log Level= 0
CheckData=True
Encroach Param= -1, 0, 0, 0
BEGIN DESCRIPTION:
Multiple Run
END DESCRIPTION:

--- CEDAR CREEK TRIBUTARY 11.f01 (steady flow) ---

Flow Title=Multiple
Number of Profiles=7
Profile Names=10-year,25-year,50-year,1pct_min,100-year,1pct_plu,500-year
River Rch & RM= CEDAR CREEK TRIB,Reach-1,3456
     506     685     831     739    1000    1352    1452
Boundary for River Rch & Prof#=CEDAR CREEK TRIB,Reach-1,1
Up Type=0
Dn Type=3
Dn Slope=0.005
Boundary for River Rch & Prof#=CEDAR CREEK TRIB,Reach-1,2
Up Type=0
Dn Type=3
Dn Slope=0.005
Boundary for River Rch & Prof#=CEDAR CREEK TRIB,Reach-1,3
Up Type=0
Dn Type=3
Dn Slope=0.005
Boundary for River Rch & Prof#=CEDAR CREEK TRIB,Reach-1,4
Up Type=0
Dn Type=3
Dn Slope=0.005
Boundary for River Rch & Prof#=CEDAR CREEK TRIB,Reach-1,5
Up Type=0
Dn Type=3
Dn Slope=0.005
Boundary for River Rch & Prof#=CEDAR CREEK TRIB,Reach-1,6
Up Type=0
Dn Type=3
Dn Slope=0.005
Boundary for River Rch & Prof#=CEDAR CREEK TRIB,Reach-1,7
Up Type=0
Dn Type=3
Dn Slope=0.005

--- CEDAR CREEK TRIBUTARY 11.g01 (geometry) ---

Geom Title=Existing Conditions
Program Version=4.10

River Reach=CEDAR CREEK TRIB,Reach-1
Reach XY= 30
      3524657.85     10341438.05       3524650.7     10341406.69
      3524478.66     10341251.47      3524382.87     10341247.45
      3524229.35     10341190.45      3524211.88     10341146.96
       3524116.5     10341050.42      3524032.83     10341001.58
      3523957.03     10340858.75      3523800.48     10340687.73
      3523761.14     10340582.54      3523632.54     10340493.67
      3523604.13     10340426.81      3523507.46     10340381.65
      3523448.22      10340319.4      3523369.46     10340325.19
      3523206.39     10340213.92      3523122.13     10340207.77
      3523037.25     10340237.42      3522936.12     10340173.83
      3522792.64     10340187.33      3522720.88     10340156.27
      3522627.95     10340023.93      3522566.67     10339879.15
      3522502.53     10339816.12      3522454.49     10339655.37
      3522334.05     10339495.86      3522285.67     10339459.59
      3522208.94     10339192.99      3522142.11     10339131.64

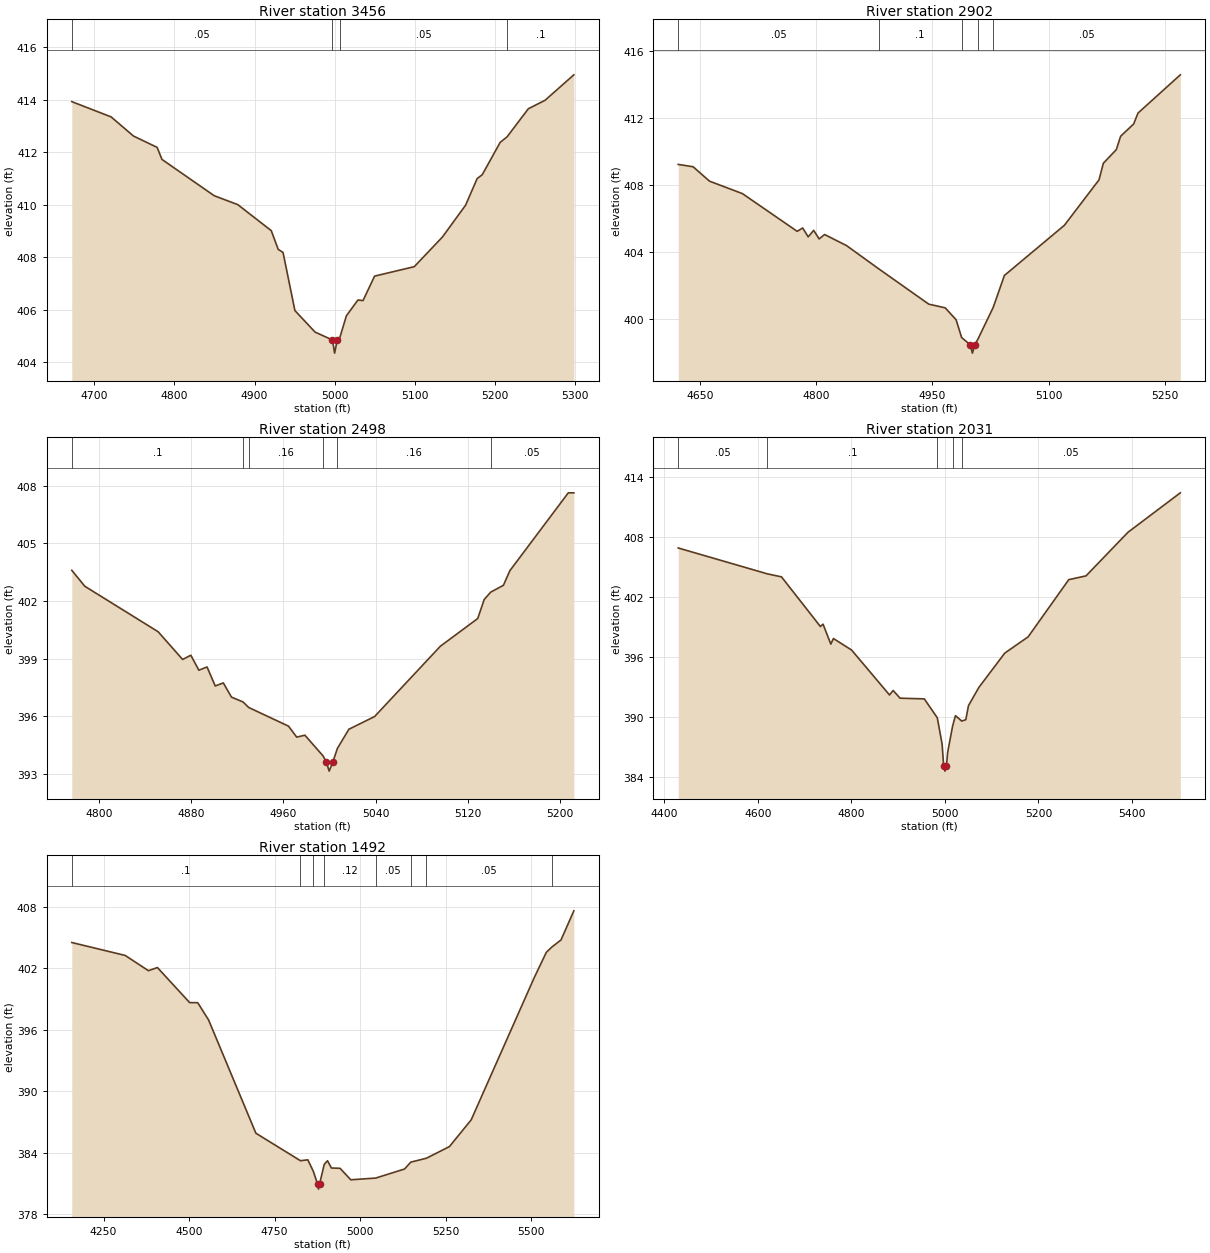
Type RM Length L Ch R = 1 ,3456    ,554,554,554
BEGIN DESCRIPTION:
CEDAR CREEK TRIBUTARY 11 6.0
END DESCRIPTION:
XS GIS Cut Line= 3
      3524620.23     10340991.65      3524442.11     10341241.64
      3524242.12     10341491.63
#Sta/Elev= 30
  4671.7  413.92  4720.8  413.34  4748.8  412.61  4778.3  412.18  4784.4  411.72
  4849.6  410.34  4879.1     410  4920.9  409.01  4929.5   408.3  4935.6  408.18
  4950.4  405.97  4975.6  405.15  4997.3  404.85    5000  404.35  5003.3  404.85
  5006.7  404.96  5014.7  405.77  5029.1  406.37  5035.5  406.35  5049.9  407.28
  5099.5  407.64  5134.7  408.77  5163.6  409.98    5178  410.99  5184.4  411.14
  5206.8  412.37  5215.4  412.58    5242  413.65  5262.8  413.97  5298.8  414.94
#Mann= 4 ,-1 , 0
  4671.7     .05       0  4997.3     .03       0  5006.7     .05       0
  5215.4      .1       0
Bank Sta=4997.3,5003.3
XS Rating Curve= 0 ,0
Exp/Cntr=0.3,0.1

Type RM Length L Ch R = 1 ,2902    ,404,404,404
BEGIN DESCRIPTION:
CEDAR CREEK TRIBUTARY 11 4.0
END DESCRIPTION:
XS GIS Cut Line= 3
      3524272.31      10340684.7      3523972.31      10340984.7
       3523872.3     10341184.73
#Sta/Elev= 30
    4622  409.24  4641.2   409.1  4662.4  408.24  4704.8   407.5  4775.5  405.25
  4782.6  405.45  4789.7  404.92  4796.8  405.31  4803.8   404.8  4810.9  405.06
  4839.2   404.4  4880.6  403.02  4945.3  400.91  4966.5  400.69  4980.6  399.98
  4987.7  398.92  4998.8  398.49  5001.6  397.99  5004.8  398.49  5008.9  398.84
  5028.4  400.71  5042.9  402.62  5120.3  405.61    5165  408.32  5170.6  409.31
  5187.3  410.12  5192.9  410.92  5209.7  411.65  5215.3   412.3  5269.9  414.58
#Mann= 5 ,-1 , 0
    4622     .05       0  4880.6      .1       0  4987.7     .07       0
  5008.9      .1       0  5028.4     .05       0
Bank Sta=4998.8,5004.8
XS Rating Curve= 0 ,0
Exp/Cntr=0.3,0.1

Type RM Length L Ch R = 1 ,2498    ,467,467,467
BEGIN DESCRIPTION:
CEDAR CREEK TRIBUTARY 11 3.0
END DESCRIPTION:
XS GIS Cut Line= 3
      3523941.76     10340465.25      3523791.76     10340615.25
      3523691.77     10340815.22
#Sta/Elev= 30
  4776.4   403.6  4787.7  402.77  4851.4   400.4  4872.6  398.96  4879.7  399.18
  4886.7   398.4  4893.8  398.57  4900.9  397.58  4907.9  397.74    4915     397
    4925  396.75    4930  396.46  4964.5  395.49  4971.6  394.92  4978.7  395.02
  4994.5  393.94  4997.1  393.65  4999.8  393.15  5003.1  393.65  5006.9  394.33
  5016.9  395.33  5039.2  395.99  5096.3  399.65  5128.7  401.09  5134.3  402.08
  5139.9  402.46    5151  402.82  5156.6  403.58  5207.3  407.63  5212.1  407.63
#Mann= 6 ,-1 , 0
  4776.4      .1       0    4925     .05       0    4930     .16       0
  4994.5     .07       0  5006.9     .16       0  5139.9     .05       0
Bank Sta=4997.1,5003.1
XS Rating Curve= 0 ,0
Exp/Cntr=0.3,0.1

Type RM Length L Ch R = 1 ,2031    ,539,539,539
BEGIN DESCRIPTION:
CEDAR CREEK TRIBUTARY 11 2.0
END DESCRIPTION:
XS GIS Cut Line= 3
      3523717.48     10339819.74      3523372.31     10340493.38
       3523472.3     10340793.34
#Sta/Elev= 30
  4430.1   406.9  4620.7  404.31  4650.8  404.01    4734  399.04  4739.6  399.28
  4756.2  397.28  4761.8  397.84  4800.6  396.69  4881.7  392.19  4889.4  392.64
  4904.2  391.87    4956   391.8  4983.8  389.91  4994.1  387.27  4997.4  385.07
  5000.1  384.57  5003.4  385.07    5006  386.47  5016.5  389.07  5022.6  390.12
  5036.1  389.58  5044.8  389.72  5050.4  391.12  5072.7  392.95    5128  396.38
    5178  398.01  5264.8  403.73  5301.7  404.11  5391.3  408.47  5503.2  412.42
#Mann= 5 ,-1 , 0
  4430.1     .05       0  4620.7      .1       0  4983.8     .07       0
  5016.5      .1       0  5036.1     .05       0
Bank Sta=4997.4,5003.4
XS Rating Curve= 0 ,0
Exp/Cntr=0.3,0.1

Type RM Length L Ch R = 1 ,1492    ,0,0,0
BEGIN DESCRIPTION:
CEDAR CREEK TRIBUTARY 11 1.0
END DESCRIPTION:
XS GIS Cut Line= 3
      3523248.72     10339403.08      3522927.54     10340349.27
      3523231.38      10340705.2
#Sta/Elev= 30
  4157.1  404.49  4313.2  403.23  4381.3  401.74  4407.4  402.05  4501.6  398.63
  4525.2  398.62  4556.9  396.94  4695.2  385.89  4825.5  383.21  4846.9   383.3
  4863.1  382.17  4875.3  380.94  4878.1  380.44  4881.3  380.94  4894.8  382.85
  4904.4  383.21  4915.9   382.5  4941.1  382.47  4972.5  381.35  5045.4  381.52
  5129.5   382.4  5147.7  383.07  5193.3  383.45  5260.8  384.59  5324.4   387.2
  5508.9  401.09    5544  403.54  5560.1  404.05  5586.8  404.74  5624.3  407.58
#Mann= 8 ,-1 , 0
  4157.1      .1       0  4825.5     .12       0  4863.1     .07       0
  4894.8     .12       0  5045.4     .05       0  5147.7      .1       0
  5193.3     .05       0  5560.1     .16       0
Bank Sta=4875.3,4881.3
XS Rating Curve= 0 ,0
Exp/Cntr=0.3,0.1

Chan Stop Cuts=-1
Use User Specified Reach Order=0
Composite Channel Slope=5