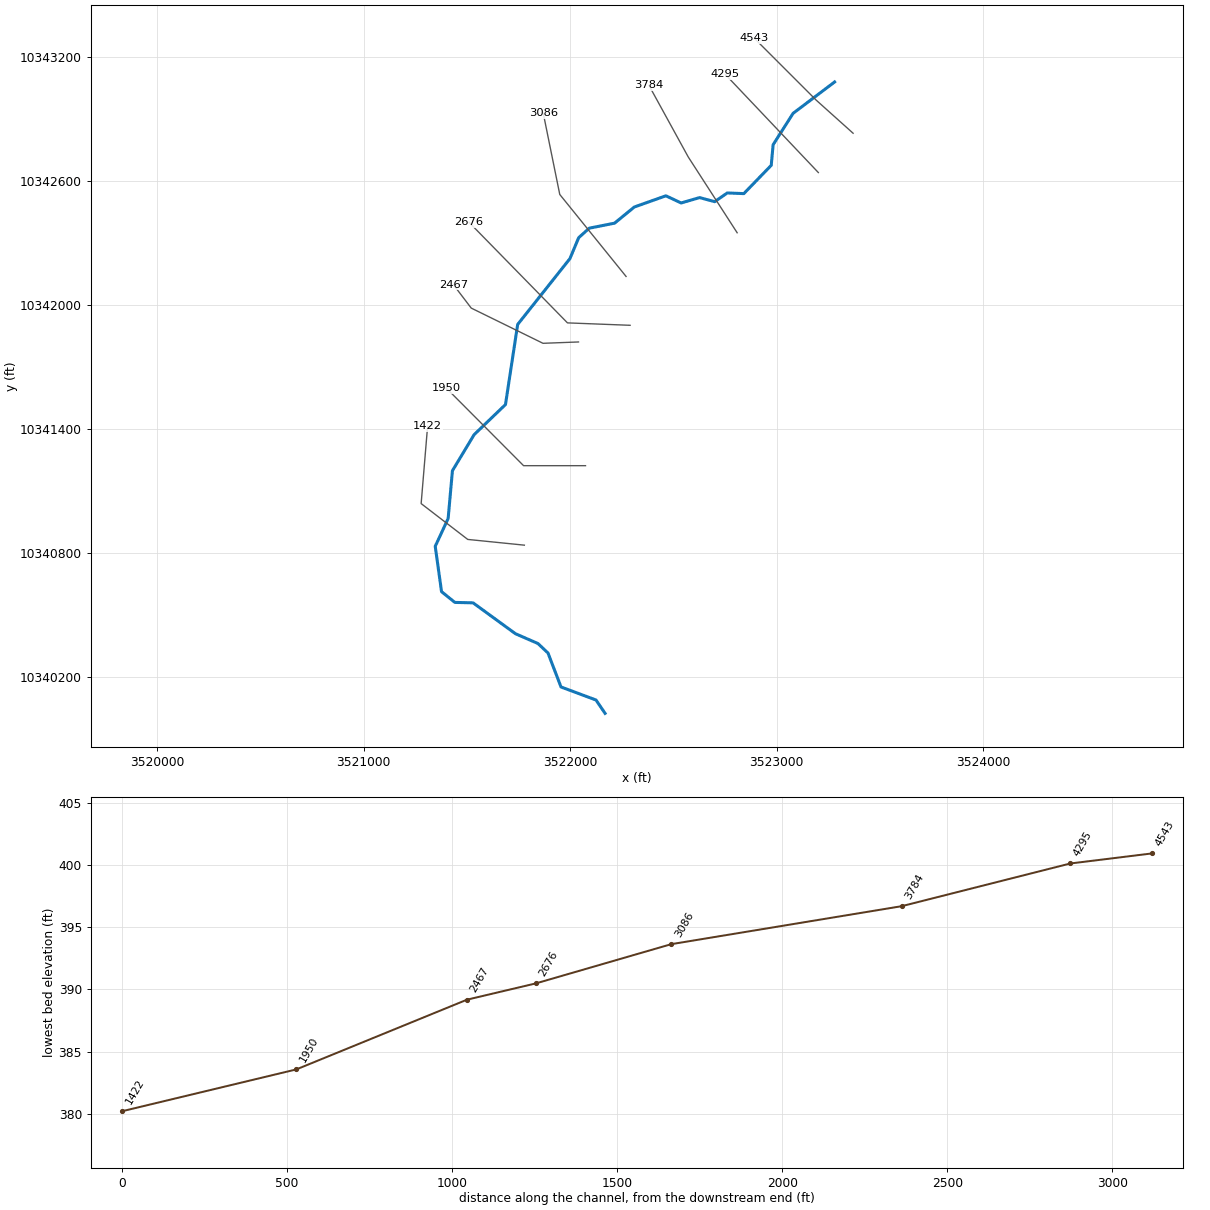
--- CEDAR CREEK TRIBUTARY 12.prj (project) ---

Proj Title=CEDAR CREEK TRIBUTARY 12 Base Level Engineering
Current Plan=p01
Default Exp/Contr=0.3,0.1
English Units
Geom File=g01
Flow File=f01
Plan File=p01
Y Axis Title=Elevation
X Axis Title(PF)=Main Channel Distance
X Axis Title(XS)=Station
BEGIN DESCRIPTION:
CEDAR CREEK TRIBUTARY 12
END DESCRIPTION:
DSS Export Rating Curves= 0
DSS Export Rating Curve Sorted= 0
DSS Export Volume Flow Curves= 0
DXF OffsetX= 0
DXF OffsetY= 0
DXF ScaleX= 1
DXF ScaleY= 10

--- CEDAR CREEK TRIBUTARY 12.p01 (plan) ---

Plan Title=Multiple Run
Short Identifier=Multiple
Geom File=g01
Flow File=f01
Subcritical Flow
K Sum by GR= 0
Std Step Tol= 0.01
Critical Tol= 0.01
Num of Std Step Trials= 20
Max Error Tol= 0.3
Flow Tol Ratio= 0.001
Split Flow NTrial= 30
Split Flow Tol= 0.02
Split Flow Ratio= 0.02
Log Output Level= 0
Friction Slope Method= 1
Unsteady Friction Slope Method= 2
Unsteady Bridges Friction Slope Method= 1
Parabolic Critical Depth
Global Vel Dist=  1 , 1 , 1
Global Log Level= 0
CheckData=True
Encroach Param= -1, 0, 0, 0
BEGIN DESCRIPTION:
Multiple Run
END DESCRIPTION:

--- CEDAR CREEK TRIBUTARY 12.f01 (steady flow) ---

Flow Title=Multiple
Number of Profiles=7
Profile Names=10-year,25-year,50-year,1pct_min,100-year,1pct_plu,500-year
River Rch & RM= CEDAR CREEK TRIB,Reach-1,4543
     391     520     623     548     741    1002    1049
Boundary for River Rch & Prof#=CEDAR CREEK TRIB,Reach-1,1
Up Type=0
Dn Type=3
Dn Slope=0.005
Boundary for River Rch & Prof#=CEDAR CREEK TRIB,Reach-1,2
Up Type=0
Dn Type=3
Dn Slope=0.005
Boundary for River Rch & Prof#=CEDAR CREEK TRIB,Reach-1,3
Up Type=0
Dn Type=3
Dn Slope=0.005
Boundary for River Rch & Prof#=CEDAR CREEK TRIB,Reach-1,4
Up Type=0
Dn Type=3
Dn Slope=0.005
Boundary for River Rch & Prof#=CEDAR CREEK TRIB,Reach-1,5
Up Type=0
Dn Type=3
Dn Slope=0.005
Boundary for River Rch & Prof#=CEDAR CREEK TRIB,Reach-1,6
Up Type=0
Dn Type=3
Dn Slope=0.005
Boundary for River Rch & Prof#=CEDAR CREEK TRIB,Reach-1,7
Up Type=0
Dn Type=3
Dn Slope=0.005

--- CEDAR CREEK TRIBUTARY 12.g01 (geometry) ---

Geom Title=Existing Conditions

River Reach=CEDAR CREEK TRIB,Reach-1
Reach XY= 30
      3523280.63     10343080.17      3523079.55     10342928.24
      3522982.92     10342776.42      3522973.72     10342676.42
      3522840.91     10342539.44      3522760.70     10342542.57
      3522699.76     10342500.38      3522626.85     10342520.17
      3522537.26     10342494.13      3522463.40     10342528.86
      3522310.59     10342474.58      3522214.86     10342396.29
      3522092.09     10342371.96      3522040.98     10342325.96
      3521998.53     10342224.56      3521745.37     10341905.55
      3521686.34     10341517.53      3521534.43     10341371.69
      3521429.39     10341197.22      3521408.56     10340965.44
      3521346.06     10340830.90      3521376.62     10340611.22
      3521441.20     10340559.14      3521529.39     10340557.05
      3521734.41     10340407.63      3521843.79     10340359.88
      3521892.40     10340313.88      3521955.29     10340149.57
      3522124.85     10340086.40      3522168.82     10340021.62

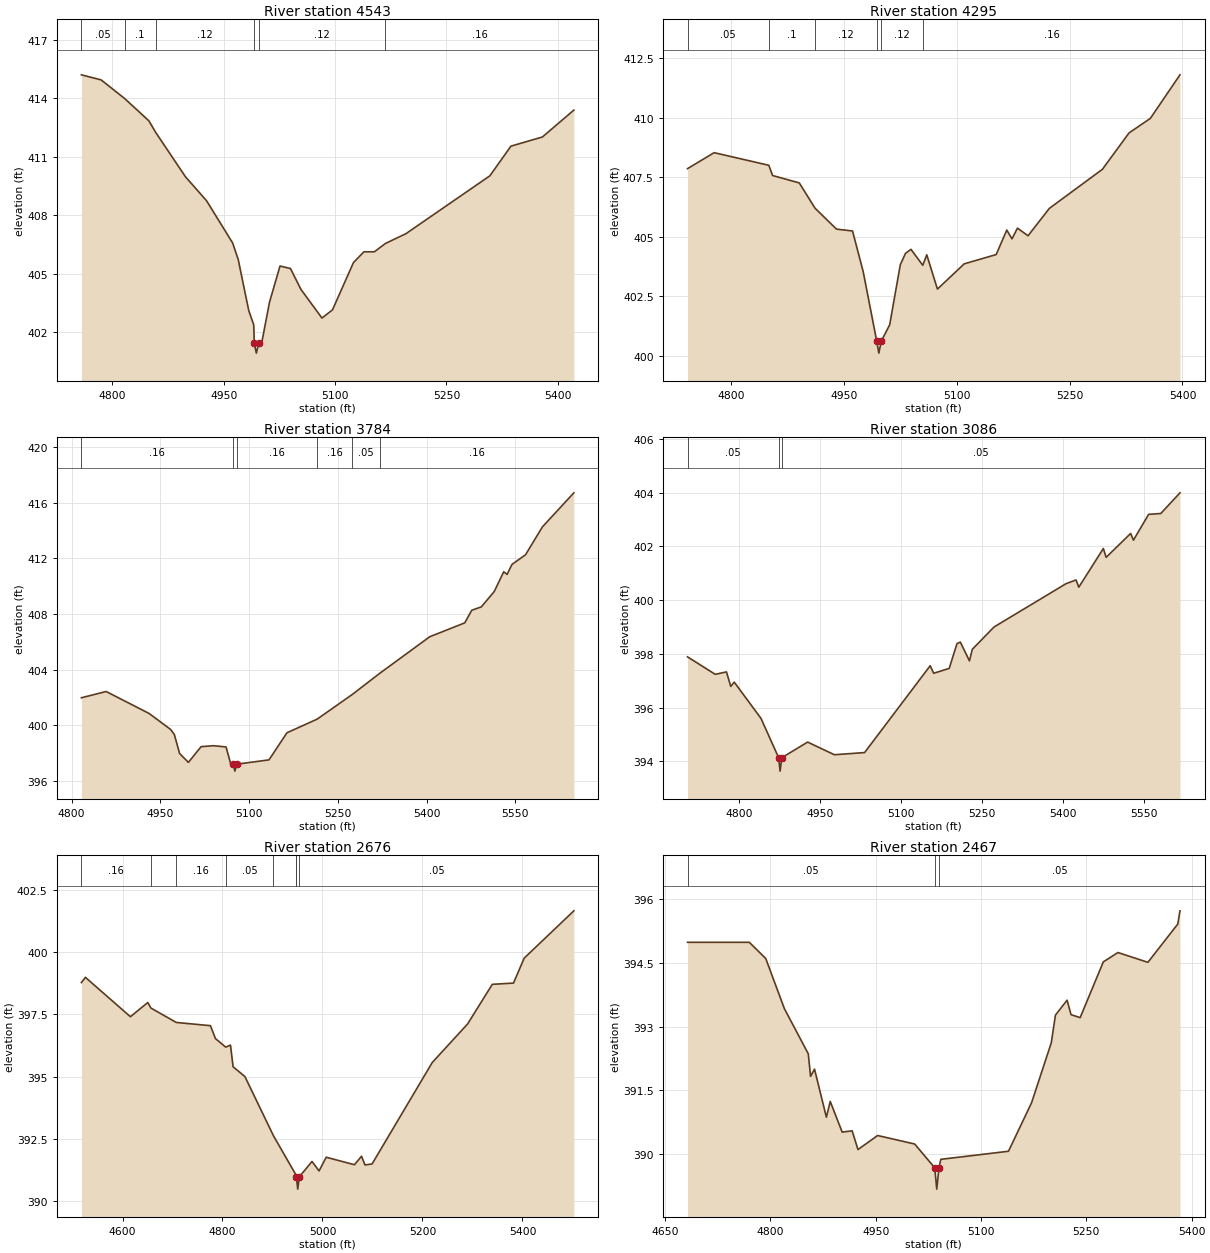
Type RM Length L Ch R = 1,4543,248,248,248
BEGIN DESCRIPTION:
CEDAR CREEK TRIBUTARY 12 5.0
END DESCRIPTION:
XS GIS Cut Line= 3
      3523370.26     10342831.90      3523192.11     10342991.64
      3522892.14     10343291.61
#Sta/Elev= 30
  4758.2  415.21  4784.8  414.95  4816.6  413.99  4849.1  412.85  4858.2  412.26
  4898.4  409.98  4926.8  408.75  4962.0  406.58  4969.5  405.73  4983.7  403.11
  4990.4  402.38  4991.1  401.43  4993.9  400.93  4997.1  401.43  5001.0  401.43
  5011.6  403.54  5025.8  405.40  5039.9  405.27  5054.0  404.20  5082.3  402.73
  5096.5  403.15  5124.8  405.58  5138.9  406.13  5153.0  406.13  5167.5  406.55
  5195.5  407.06  5308.6  410.03  5336.9  411.55  5379.3  412.02  5421.7  413.40
#Mann=6,-1,0
  4758.2    0.05       0  4816.6     0.1       0  4858.2    0.12       0
  4991.1    0.07       0  4997.1    0.12       0  5167.5    0.16       0
Bank Sta=4991.1,4997.1
Exp/Cntr=0.3,0.1

Type RM Length L Ch R = 1,4295,511,511,511
BEGIN DESCRIPTION:
CEDAR CREEK TRIBUTARY 12 4.01
END DESCRIPTION:
XS GIS Cut Line= 2
      3523201.89     10342641.44      3522751.41     10343116.65
#Sta/Elev= 30
  4741.9  407.87  4777.3  408.54  4850.0  408.01  4855.0  407.58  4890.5  407.27
  4911.4  406.21  4939.9  405.33  4961.3  405.25  4975.5  403.54  4993.5  400.62
  4996.3  400.12  4999.5  400.62  5010.7  401.31  5024.8  403.83  5031.7  404.31
  5039.0  404.48  5054.7  403.81  5060.0  404.25  5074.2  402.81  5109.8  403.87
  5152.3  404.26  5166.4  405.29  5173.3  404.92  5180.6  405.37  5194.7  405.05
  5223.0  406.20  5293.5  407.84  5329.0  409.37  5357.3  409.98  5396.7  411.81
#Mann=6,-1,0
  4741.9    0.05       0  4850.0     0.1       0  4911.4    0.12       0
  4993.5    0.07       0  4999.5    0.12       0  5054.7    0.16       0
Bank Sta=4993.5,4999.5
Exp/Cntr=0.3,0.1

Type RM Length L Ch R = 1,3784,698,698,698
BEGIN DESCRIPTION:
CEDAR CREEK TRIBUTARY 12 4.0
END DESCRIPTION:
XS GIS Cut Line= 3
      3522808.66     10342349.76      3522571.66     10342716.98
      3522381.58     10343063.29
#Sta/Elev= 30
  4816.7  401.97  4858.5  402.42  4931.1  400.84  4967.4  399.69  4973.7  399.33
  4982.6  397.96  4997.5  397.32  5018.9  398.45  5040.0  398.52  5061.1  398.43
  5068.9  397.23  5073.3  397.19  5076.0  396.69  5079.3  397.19  5133.7  397.50
  5164.0  399.45  5215.0  400.43  5274.5  402.21  5320.5  403.72  5405.2  406.36
  5464.4  407.36  5476.3  408.27  5492.4  408.51  5514.2  409.61  5530.3  411.04
  5536.0  410.85  5544.3  411.57  5567.1  412.26  5595.7  414.27  5648.8  416.72
#Mann=6,-1,0
  4816.7    0.16       0  5073.3    0.07       0  5079.3    0.16       0
  5215.0    0.16       0  5274.5    0.05       0  5320.5    0.16       0
Bank Sta=5073.3,5079.3
Exp/Cntr=0.3,0.1

Type RM Length L Ch R = 1,3086,410,410,410
BEGIN DESCRIPTION:
CEDAR CREEK TRIBUTARY 12 3.0
END DESCRIPTION:
XS GIS Cut Line= 3
      3522270.52     10342138.17      3521949.33     10342535.31
      3521869.40     10342928.50
#Sta/Elev= 30
  4705.1  397.89  4756.4  397.24  4777.2  397.33  4785.2  396.79  4791.6  396.95
  4841.2  395.60  4873.8  394.14  4876.5  393.64  4879.8  394.14  4927.5  394.72
  4977.0  394.25  5033.0  394.33  5154.5  397.56  5161.0  397.28  5189.7  397.46
  5204.1  398.38  5210.3  398.44  5227.2  397.74  5232.5  398.17  5272.7  399.00
  5406.0  400.61  5424.6  400.75  5429.7  400.48  5475.2  401.92  5480.3  401.59
  5525.8  402.48  5530.9  402.23  5559.1  403.19  5581.5  403.22  5617.1  403.99
#Mann=3,-1,0
  4705.1    0.05       0  4873.8    0.03       0  4879.8    0.05       0
Bank Sta=4873.8,4879.8
Exp/Cntr=0.3,0.1

Type RM Length L Ch R = 1,2676,209,209,209
BEGIN DESCRIPTION:
CEDAR CREEK TRIBUTARY 12 2.01
END DESCRIPTION:
XS GIS Cut Line= 3
      3522290.06     10341901.52      3521986.63     10341913.24
      3521510.08     10342400.21
#Sta/Elev= 30
  4517.8  398.78  4525.8  398.99  4615.8  397.41  4650.6  397.98  4656.7  397.76
  4707.5  397.18  4775.9  397.05  4786.0  396.53  4806.5  396.19  4816.0  396.27
  4821.2  395.40  4844.8  395.01  4902.0  392.63  4946.4  391.08  4947.8  390.99
  4950.5  390.49  4953.8  390.99  4979.1  391.60  4993.2  391.22  5007.4  391.77
  5063.9  391.47  5078.1  391.81  5085.1  391.46  5099.2  391.50  5219.5  395.57
  5290.3  397.12  5339.7  398.71  5382.1  398.76  5403.4  399.76  5502.8  401.66
#Mann=8,-1,0
  4517.8    0.16       0  4656.7    0.05       0  4707.5    0.16       0
  4806.5    0.05       0  4902.0    0.16       0  4946.4    0.05       0
  4947.8   0.035       0  4953.8    0.05       0
Bank Sta=4947.8,4953.8
Exp/Cntr=0.3,0.1

Type RM Length L Ch R = 1,2467,517,517,517
BEGIN DESCRIPTION:
CEDAR CREEK TRIBUTARY 12 2.0
END DESCRIPTION:
XS GIS Cut Line= 4
      3522040.05     10341820.80      3521868.14     10341814.29
      3521520.49     10341984.86      3521434.34     10342098.01
#Sta/Elev= 30
  4681.9  394.98  4769.9  394.98  4793.3  394.60  4819.9  393.42  4853.9  392.36
  4857.2  391.83  4862.8  392.00  4879.7  390.87  4885.2  391.24  4902.2  390.52
  4916.4  390.55  4924.7  390.11  4952.7  390.44  5005.5  390.24  5034.1  389.68
  5036.9  389.18  5040.1  389.68  5042.7  389.88  5139.1  390.07  5172.0  391.21
  5200.1  392.62  5206.0  393.27  5222.6  393.62  5228.2  393.28  5241.2  393.21
  5274.2  394.52  5295.0  394.74  5337.7  394.51  5380.3  395.41  5383.4  395.72
#Mann=3,-1,0
  4681.9    0.05       0  5034.1    0.03       0  5040.1    0.05       0
Bank Sta=5034.1,5040.1
Exp/Cntr=0.3,0.1

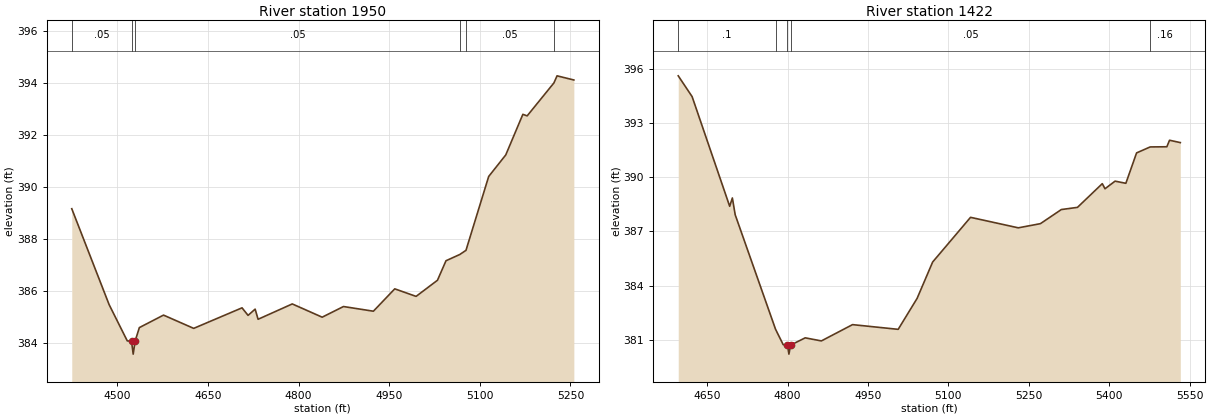
Type RM Length L Ch R = 1,1950,528,528,528
BEGIN DESCRIPTION:
CEDAR CREEK TRIBUTARY 12 1.0
END DESCRIPTION:
XS GIS Cut Line= 3
      3522074.01     10341221.50      3521774.05     10341221.50
      3521399.06     10341597.94
#Sta/Elev= 30
  4424.4  389.17  4486.3  385.48  4516.3  384.09  4523.3  384.08  4526.1  383.58
  4529.3  384.08  4536.3  384.60  4576.3  385.08  4626.3  384.57  4706.3  385.36
  4716.3  385.07  4728.0  385.31  4732.9  384.92  4789.5  385.51  4839.0  385.00
  4874.3  385.41  4923.8  385.23  4959.2  386.09  4994.5  385.80  5029.9  386.42
  5044.0  387.17  5066.8  387.41  5077.1  387.57  5114.7  390.41  5143.0  391.24
  5171.3  392.80  5178.4  392.74  5222.8  394.01  5227.9  394.28  5255.7  394.12
#Mann=6,-1,0
  4424.4    0.05       0  4523.3   0.035       0  4529.3    0.05       0
  5066.8     0.1       0  5077.1    0.05       0  5222.8    0.16       0
Bank Sta=4523.3,4529.3
Exp/Cntr=0.3,0.1

Type RM Length L Ch R = 1,1422,0,0,0
BEGIN DESCRIPTION:
CEDAR CREEK TRIBUTARY 12 1.0111
END DESCRIPTION:
XS GIS Cut Line= 4
      3521777.84     10340836.48      3521503.53     10340864.26
      3521277.84     10341037.87      3521309.09     10341412.92
#Sta/Elev= 30
  4596.0  395.60  4621.9  394.45  4692.0  388.39  4697.0  388.85  4702.3  387.92
  4777.5  381.60  4791.9  380.74  4799.8  380.72  4802.5  380.22  4805.8  380.72
  4832.9  381.12  4863.1  380.95  4921.2  381.85  5006.4  381.59  5041.7  383.30
  5070.7  385.31  5141.4  387.78  5230.5  387.20  5271.8  387.43  5310.8  388.21
  5340.9  388.33  5387.2  389.64  5392.3  389.36  5411.1  389.78  5431.2  389.66
  5451.2  391.34  5476.6  391.67  5507.7  391.68  5512.7  392.04  5532.8  391.91
#Mann=5,-1,0
  4596.0     0.1       0  4777.5    0.05       0  4799.8    0.03       0
  4805.8    0.05       0  5476.6    0.16       0
Bank Sta=4799.8,4805.8
Exp/Cntr=0.3,0.1

Chan Stop Cuts=-1