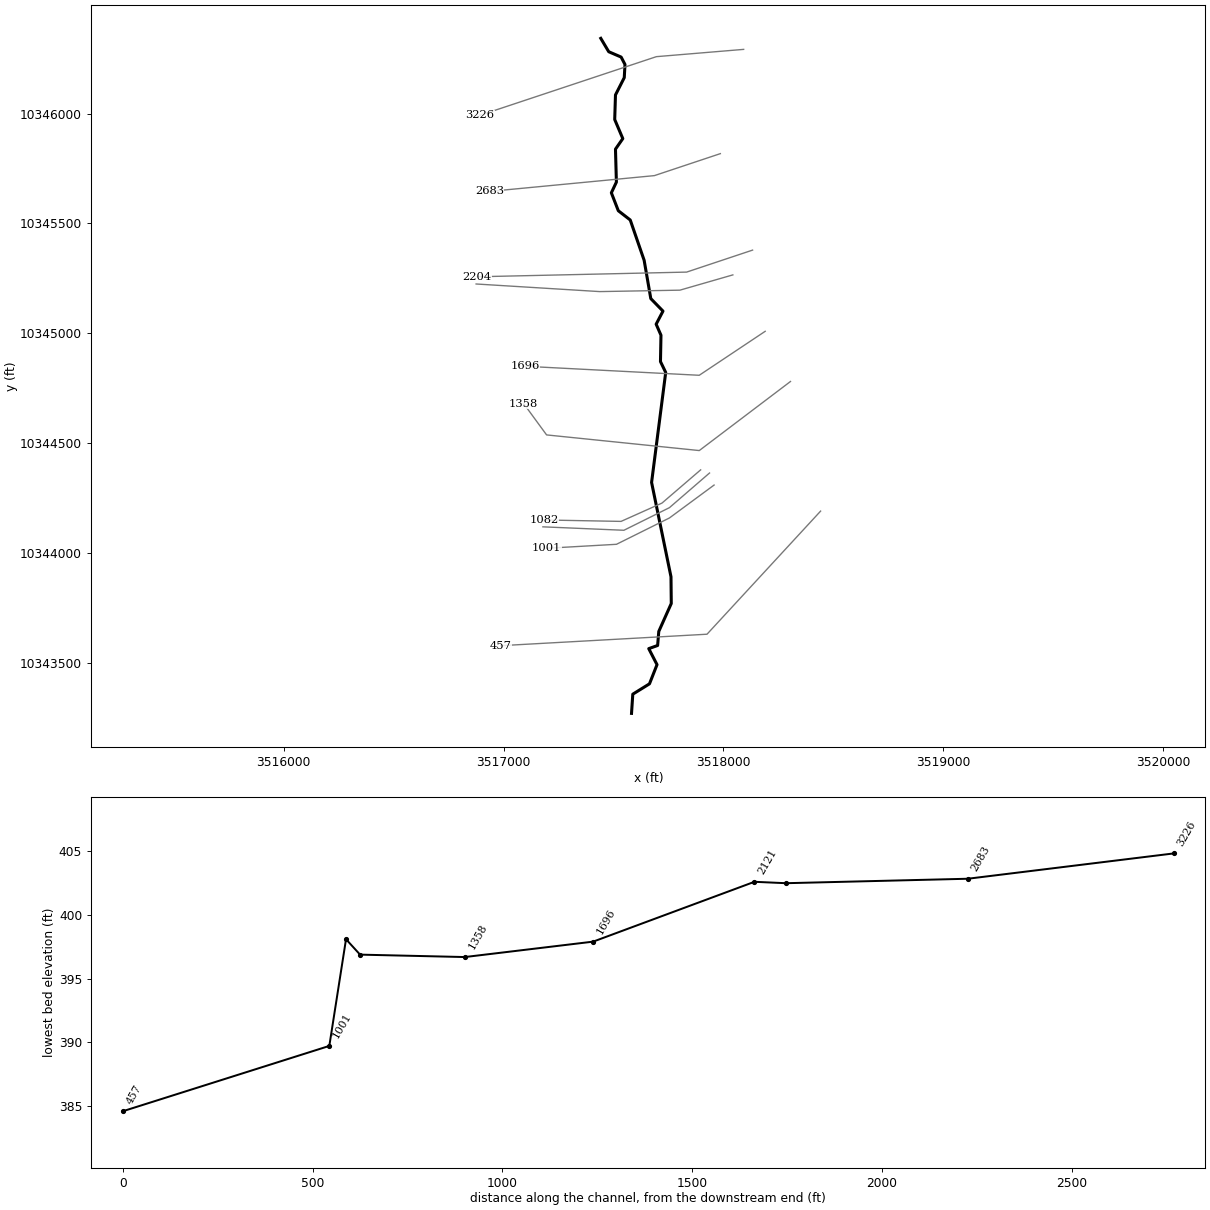
--- CEDAR CREEK TRIBUTARY 13.prj (project) ---

Proj Title=CEDAR CREEK TRIBUTARY 13 Base Level Engineering
Current Plan=p01
Default Exp/Contr=0.3,0.1
English Units
Geom File=g01
Flow File=f01
Plan File=p01
BEGIN DESCRIPTION:
CEDAR CREEK TRIBUTARY 13
END DESCRIPTION:

--- CEDAR CREEK TRIBUTARY 13.p01 (plan) ---

Plan Title=Multiple Run
Short Identifier=Multiple
Geom File=g01
Flow File=f01
Subcritical Flow
K Sum by GR= 0
Std Step Tol= 0.01
Critical Tol= 0.01
Num of Std Step Trials= 20
Max Error Tol= 0.3
Flow Tol Ratio= 0.001
Split Flow NTrial= 30
Split Flow Tol= 0.02
Split Flow Ratio= 0.02
Log Output Level= 0
Friction Slope Method= 1
Unsteady Friction Slope Method= 2
Unsteady Bridges Friction Slope Method= 1
Parabolic Critical Depth
Global Vel Dist=  1 , 1 , 1
Global Log Level= 0
CheckData=True
Encroach Param= -1, 0, 0, 0
BEGIN DESCRIPTION:
Multiple Run
END DESCRIPTION:

--- CEDAR CREEK TRIBUTARY 13.f01 (steady flow) ---

Flow Title=Multiple
Number of Profiles=7
Profile Names=10-year,25-year,50-year,1pct_min,100-year,1pct_plu,500-year
River Rch & RM= CEDAR CREEK TRIB,Reach-1,3226
     242     313     367     317     429     580     586
Boundary for River Rch & Prof#=CEDAR CREEK TRIB,Reach-1,1
Up Type=0
Dn Type=3
Dn Slope=0.005
Boundary for River Rch & Prof#=CEDAR CREEK TRIB,Reach-1,2
Up Type=0
Dn Type=3
Dn Slope=0.005
Boundary for River Rch & Prof#=CEDAR CREEK TRIB,Reach-1,3
Up Type=0
Dn Type=3
Dn Slope=0.005
Boundary for River Rch & Prof#=CEDAR CREEK TRIB,Reach-1,4
Up Type=0
Dn Type=3
Dn Slope=0.005
Boundary for River Rch & Prof#=CEDAR CREEK TRIB,Reach-1,5
Up Type=0
Dn Type=3
Dn Slope=0.005
Boundary for River Rch & Prof#=CEDAR CREEK TRIB,Reach-1,6
Up Type=0
Dn Type=3
Dn Slope=0.005
Boundary for River Rch & Prof#=CEDAR CREEK TRIB,Reach-1,7
Up Type=0
Dn Type=3
Dn Slope=0.005

--- CEDAR CREEK TRIBUTARY 13.g01 (geometry) ---

Geom Title=Existing Conditions

River Reach=CEDAR CREEK TRIB,Reach-1
Reach XY= 30
      3517442.27     10346341.89      3517478.47     10346280.98
      3517534.90     10346256.68      3517552.37     10346222.96
      3517549.09     10346163.08      3517509.13     10346084.44
      3517505.66     10345972.63      3517542.47     10345885.83
      3517509.13     10345837.91      3517513.30     10345687.91
      3517490.39     10345639.30      3517522.08     10345557.75
      3517576.32     10345515.64      3517639.52     10345332.31
      3517669.76     10345158.15      3517725.19     10345101.22
      3517694.14     10345041.76      3517716.04     10344991.73
      3517713.78     10344871.71      3517737.60     10344822.30
      3517673.36     10344322.03      3517761.61     10343892.93
      3517762.91     10343771.41      3517706.05     10343644.24
      3517700.85     10343580.43      3517660.48     10343566.11
      3517698.08     10343493.23      3517663.81     10343406.06
      3517587.89     10343358.95      3517582.11     10343271.64

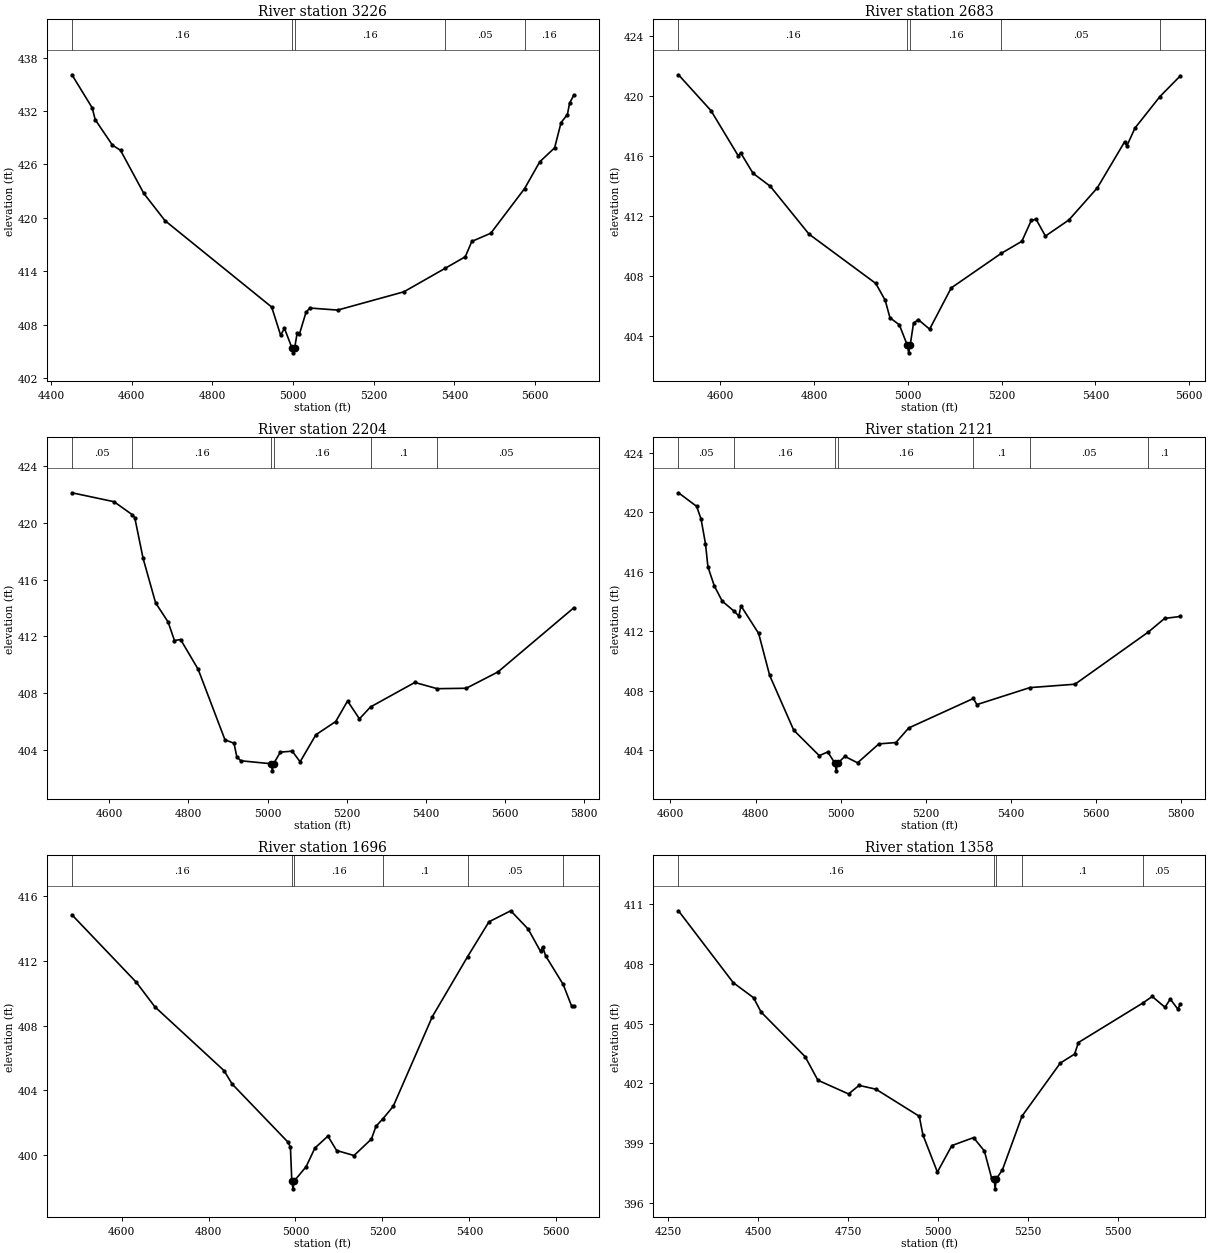
Type RM Length L Ch R = 1,3226,543,543,543
BEGIN DESCRIPTION:
CEDAR CREEK TRIBUTARY 13 7.0
END DESCRIPTION:
XS GIS Cut Line= 3
      3518092.15     10346291.65      3517695.08     10346258.54
      3516892.12     10345991.65
#Sta/Elev= 30
  4451.7  436.07  4501.9  432.36  4509.4  431.03  4552.1  428.17  4572.2  427.59
  4629.8  422.76  4682.5  419.69  4947.1  409.99  4969.2  406.83  4978.7  407.60
  4997.8  405.35  5000.6  404.85  5003.8  405.35  5010.4  407.10  5015.6  406.92
  5032.4  409.43  5042.0  409.88  5110.6  409.65  5274.8  411.70  5376.5  414.32
  5427.2  415.64  5443.4  417.36  5490.5  418.28  5574.4  423.30  5611.9  426.30
  5648.8  427.87  5664.7  430.70  5680.5  431.61  5685.8  432.88  5696.3  433.78
#Mann=5,-1,0
  4451.7    0.16       0  4997.8    0.07       0  5003.8    0.16       0
  5376.5    0.05       0  5574.4    0.16       0
Bank Sta=4997.8,5003.8
Exp/Cntr=0.3,0.1

Type RM Length L Ch R = 1,2683,479,479,479
BEGIN DESCRIPTION:
CEDAR CREEK TRIBUTARY 13 6.0
END DESCRIPTION:
XS GIS Cut Line= 3
      3517986.12     10345817.48      3517686.12     10345717.48
      3516935.79     10345645.58
#Sta/Elev= 30
  4511.1  421.41  4580.4  419.02  4638.4  416.01  4643.7  416.20  4670.0  414.84
  4706.9  413.97  4789.4  410.78  4931.8  407.49  4951.9  406.36  4962.0  405.20
  4982.0  404.73  4999.1  403.36  5001.9  402.86  5005.1  403.36  5012.2  404.83
  5022.2  405.08  5046.6  404.44  5092.6  407.19  5199.5  409.50  5243.2  410.30
  5263.3  411.69  5273.4  411.78  5293.5  410.65  5343.7  411.73  5404.0  413.86
  5462.2  416.93  5467.2  416.67  5484.3  417.85  5537.7  419.96  5581.1  421.34
#Mann=5,-1,0
  4511.1    0.16       0  4999.1    0.07       0  5005.1    0.16       0
  5199.5    0.05       0  5537.7    0.16       0
Bank Sta=4999.1,5005.1
Exp/Cntr=0.3,0.1

Type RM Length L Ch R = 1,2204,83,83,83
BEGIN DESCRIPTION:
CEDAR CREEK TRIBUTARY 13 5.0
END DESCRIPTION:
XS GIS Cut Line= 3
      3518132.72     10345378.69      3517832.68     10345278.67
      3516880.29     10345257.45
#Sta/Elev= 30
  4505.5  422.14  4611.8  421.51  4657.7  420.60  4664.3  420.39  4685.3  417.52
  4717.0  414.37  4748.6  413.02  4764.7  411.71  4780.2  411.78  4824.6  409.68
  4892.4  404.70  4915.2  404.46  4922.4  403.50  4932.4  403.22  5009.4  403.01
  5012.1  402.51  5015.4  403.01  5032.4  403.83  5062.4  403.90  5082.4  403.15
  5122.4  405.06  5172.4  405.99  5202.4  407.44  5232.4  406.18  5260.4  407.02
  5372.5  408.75  5429.0  408.31  5502.5  408.34  5582.5  409.49  5774.4  414.02
#Mann=6,-1,0
  4505.5    0.05       0  4657.7    0.16       0  5009.4    0.07       0
  5015.4    0.16       0  5260.4     0.1       0  5429.0    0.05       0
Bank Sta=5009.4,5015.4
Exp/Cntr=0.3,0.1

Type RM Length L Ch R = 1,2121,425,425,425
BEGIN DESCRIPTION:
Mapping XS 07b8617e
END DESCRIPTION:
XS GIS Cut Line= 4
      3518043.00     10345265.97      3517802.09     10345196.51
      3517437.50     10345190.00      3516875.23     10345224.60
#Sta/Elev= 30
  4618.9  421.30  4661.5  420.39  4671.9  419.54  4682.3  417.88  4688.1  416.32
  4703.1  415.04  4721.7  414.02  4749.8  413.34  4760.6  413.02  4765.8  413.70
  4807.2  411.85  4833.1  409.03  4889.6  405.35  4949.6  403.64  4969.6  403.89
  4986.6  403.12  4989.4  402.62  4992.6  403.12  5009.6  403.59  5039.6  403.16
  5089.6  404.43  5129.6  404.52  5159.7  405.50  5311.4  407.48  5319.8  407.07
  5444.1  408.21  5550.3  408.44  5722.7  411.95  5760.7  412.86  5797.6  412.99
#Mann=7,-1,0
  4618.9    0.05       0  4749.8    0.16       0  4986.6    0.07       0
  4992.6    0.16       0  5311.4     0.1       0  5444.1    0.05       0
  5722.7     0.1       0
Bank Sta=4986.6,4992.6
Exp/Cntr=0.3,0.1

Type RM Length L Ch R = 1,1696,338,338,338
BEGIN DESCRIPTION:
CEDAR CREEK TRIBUTARY 13 4.0
END DESCRIPTION:
XS GIS Cut Line= 3
      3518190.05     10345009.37      3517890.02     10344809.35
      3517097.27     10344850.42
#Sta/Elev= 30
  4485.8  414.86  4634.2  410.68  4676.3  409.18  4835.6  405.23  4854.3  404.40
  4983.4  400.79  4988.4  400.48  4991.5  398.42  4994.3  397.92  4997.5  398.42
  5024.5  399.29  5044.6  400.44  5074.6  401.18  5094.6  400.29  5134.7  399.98
  5174.7  401.00  5185.2  401.79  5201.4  402.26  5224.8  403.02  5314.9  408.57
  5395.8  412.27  5445.1  414.43  5495.2  415.11  5535.2  413.98  5563.7  412.60
  5568.7  412.88  5575.3  412.33  5615.7  410.56  5635.3  409.21  5640.2  409.21
#Mann=6,-1,0
  4485.8    0.16       0  4991.5    0.07       0  4997.5    0.16       0
  5201.4     0.1       0  5395.8    0.05       0  5615.7     0.1       0
Bank Sta=4991.5,4997.5
Exp/Cntr=0.3,0.1

Type RM Length L Ch R = 1,1358,276,276,276
BEGIN DESCRIPTION:
CEDAR CREEK TRIBUTARY 13 3.01
END DESCRIPTION:
XS GIS Cut Line= 4
      3518305.17     10344781.21      3517890.25     10344466.99
      3517195.81     10344538.17      3517091.61     10344680.57
#Sta/Elev= 30
  4278.1  410.66  4430.5  407.05  4486.7  406.30  4507.7  405.58  4630.2  403.34
  4665.6  402.16  4750.9  401.47  4780.0  401.90  4826.9  401.71  4947.5  400.35
  4957.5  399.42  4997.8  397.55  5038.0  398.88  5098.3  399.28  5128.4  398.61
  5148.5  397.25  5155.6  397.21  5158.3  396.71  5161.6  397.21  5178.7  397.67
  5233.1  400.36  5339.5  403.02  5379.2  403.47  5389.8  404.05  5568.6  406.03
  5595.0  406.36  5630.5  405.82  5645.2  406.23  5666.0  405.73  5673.1  405.98
#Mann=5,-1,0
  4278.1    0.16       0  5155.6    0.07       0  5161.6    0.16       0
  5233.1     0.1       0  5568.6    0.05       0
Bank Sta=5155.6,5161.6
Exp/Cntr=0.3,0.1

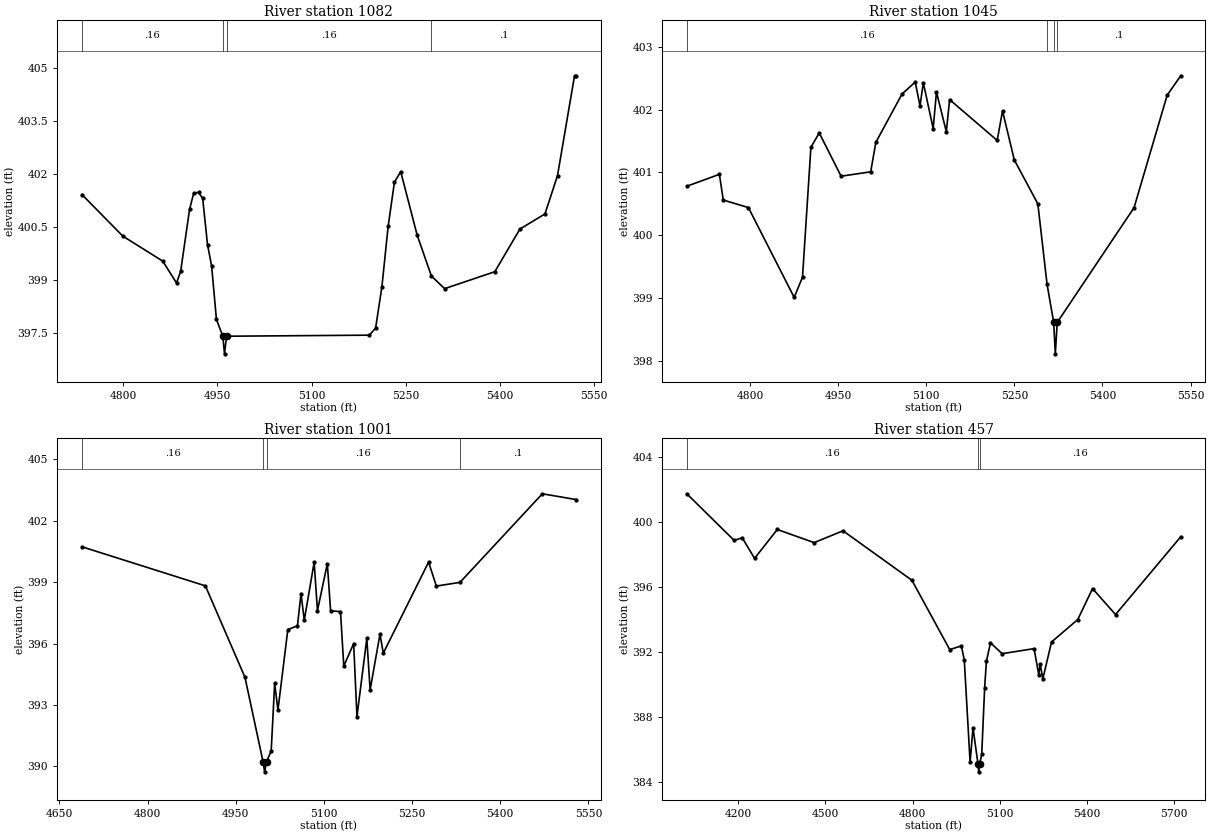
Type RM Length L Ch R = 1,1082,37,37,37
BEGIN DESCRIPTION:
CEDAR CREEK TRIBUTARY 13 3.0
END DESCRIPTION:
XS GIS Cut Line= 4
      3517896.50     10344379.19      3517720.69     10344228.13
      3517534.49     10344144.80      3517182.94     10344151.31
#Sta/Elev= 30
  4733.9  401.42  4799.1  400.24  4862.8  399.53  4884.7  398.91  4891.3  399.24
  4905.5  401.00  4912.1  401.46  4919.8  401.48  4926.4  401.31  4934.1  400.00
  4940.7  399.39  4948.3  397.88  4958.5  397.40  4961.2  396.90  4964.5  397.40
  5192.1  397.43  5202.1  397.63  5212.1  398.80  5222.1  400.52  5232.1  401.77
  5242.1  402.07  5268.3  400.27  5291.0  399.11  5312.1  398.75  5392.1  399.23
  5432.1  400.44  5472.1  400.87  5492.1  401.96  5519.2  404.79  5521.3  404.79
#Mann=4,-1,0
  4733.9    0.16       0  4958.5    0.07       0  4964.5    0.16       0
  5291.0     0.1       0
Bank Sta=4958.5,4964.5
Exp/Cntr=0.3,0.1

Type RM Length L Ch R = 1,1045,44,44,44
BEGIN DESCRIPTION:
CEDAR CREEK TRIBUTARY 13 2.1
END DESCRIPTION:
XS GIS Cut Line= 4
      3517936.87     10344364.87      3517754.54     10344207.30
      3517547.51     10344104.43      3517179.00     10344120.06
#Sta/Elev= 30
  4692.3  400.78  4747.8  400.97  4754.4  400.56  4797.2  400.44  4875.1  399.01
  4889.3  399.33  4903.6  401.40  4917.8  401.63  4955.0  400.94  5005.4  401.01
  5014.2  401.48  5058.8  402.25  5081.2  402.44  5089.4  402.06  5095.0  402.43
  5111.8  401.70  5117.4  402.28  5134.2  401.65  5139.8  402.16  5220.8  401.51
  5229.9  401.98  5249.9  401.20  5290.0  400.50  5305.7  399.22  5317.0  398.61
  5319.8  398.11  5323.0  398.61  5453.9  400.44  5510.2  402.23  5533.3  402.54
#Mann=4,-1,0
  4692.3    0.16       0  5305.7     0.1       0  5317.0    0.07       0
  5323.0     0.1       0
Bank Sta=5317,5323
Exp/Cntr=0.3,0.1

Type RM Length L Ch R = 1,1001,544,544,544
BEGIN DESCRIPTION:
CEDAR CREEK TRIBUTARY 13 2.0
END DESCRIPTION:
XS GIS Cut Line= 4
      3517957.64     10344310.14      3517754.54     10344160.42
      3517513.66     10344040.63      3517195.21     10344022.51
#Sta/Elev= 30
  4688.2  400.73  4898.2  398.82  4965.6  394.35  4996.3  390.23  4999.0  389.73
  5002.3  390.23  5010.2  390.75  5016.1  394.05  5021.7  392.75  5038.5  396.68
  5054.9  396.87  5060.9  398.44  5066.5  397.14  5083.3  399.97  5088.9  397.61
  5105.7  399.90  5111.3  397.60  5128.1  397.56  5133.7  394.90  5150.5  396.00
  5156.1  392.43  5172.9  396.25  5178.5  393.73  5195.3  396.46  5200.9  395.53
  5278.0  399.98  5291.2  398.81  5331.4  398.99  5471.5  403.32  5528.5  403.04
#Mann=4,-1,0
  4688.2    0.16       0  4996.3    0.07       0  5002.3    0.16       0
  5331.4     0.1       0
Bank Sta=4996.3,5002.3
Exp/Cntr=0.3,0.1

Type RM Length L Ch R = 1,457,0,0,0
BEGIN DESCRIPTION:
CEDAR CREEK TRIBUTARY 13 1.0
END DESCRIPTION:
XS GIS Cut Line= 3
      3518442.10     10344191.64      3517925.45     10343631.67
      3516987.90     10343579.58
#Sta/Elev= 30
  4022.6  401.73  4185.6  398.86  4213.4  399.02  4255.9  397.75  4334.2  399.53
  4461.2  398.72  4560.5  399.45  4797.9  396.40  4928.1  392.13  4968.1  392.36
  4978.1  391.50  4998.2  385.19  5008.2  387.31  5025.2  385.10  5028.0  384.60
  5031.2  385.10  5038.2  385.67  5048.3  389.79  5054.3  391.40  5068.3  392.55
  5108.4  391.88  5218.5  392.19  5234.6  390.59  5239.6  391.25  5248.6  390.32
  5278.6  392.60  5368.8  393.98  5419.9  395.89  5499.0  394.29  5723.5  399.08
#Mann=3,-1,0
  4022.6    0.16       0  5025.2    0.07       0  5031.2    0.16       0
Bank Sta=5025.2,5031.2
Exp/Cntr=0.3,0.1

Chan Stop Cuts=-1