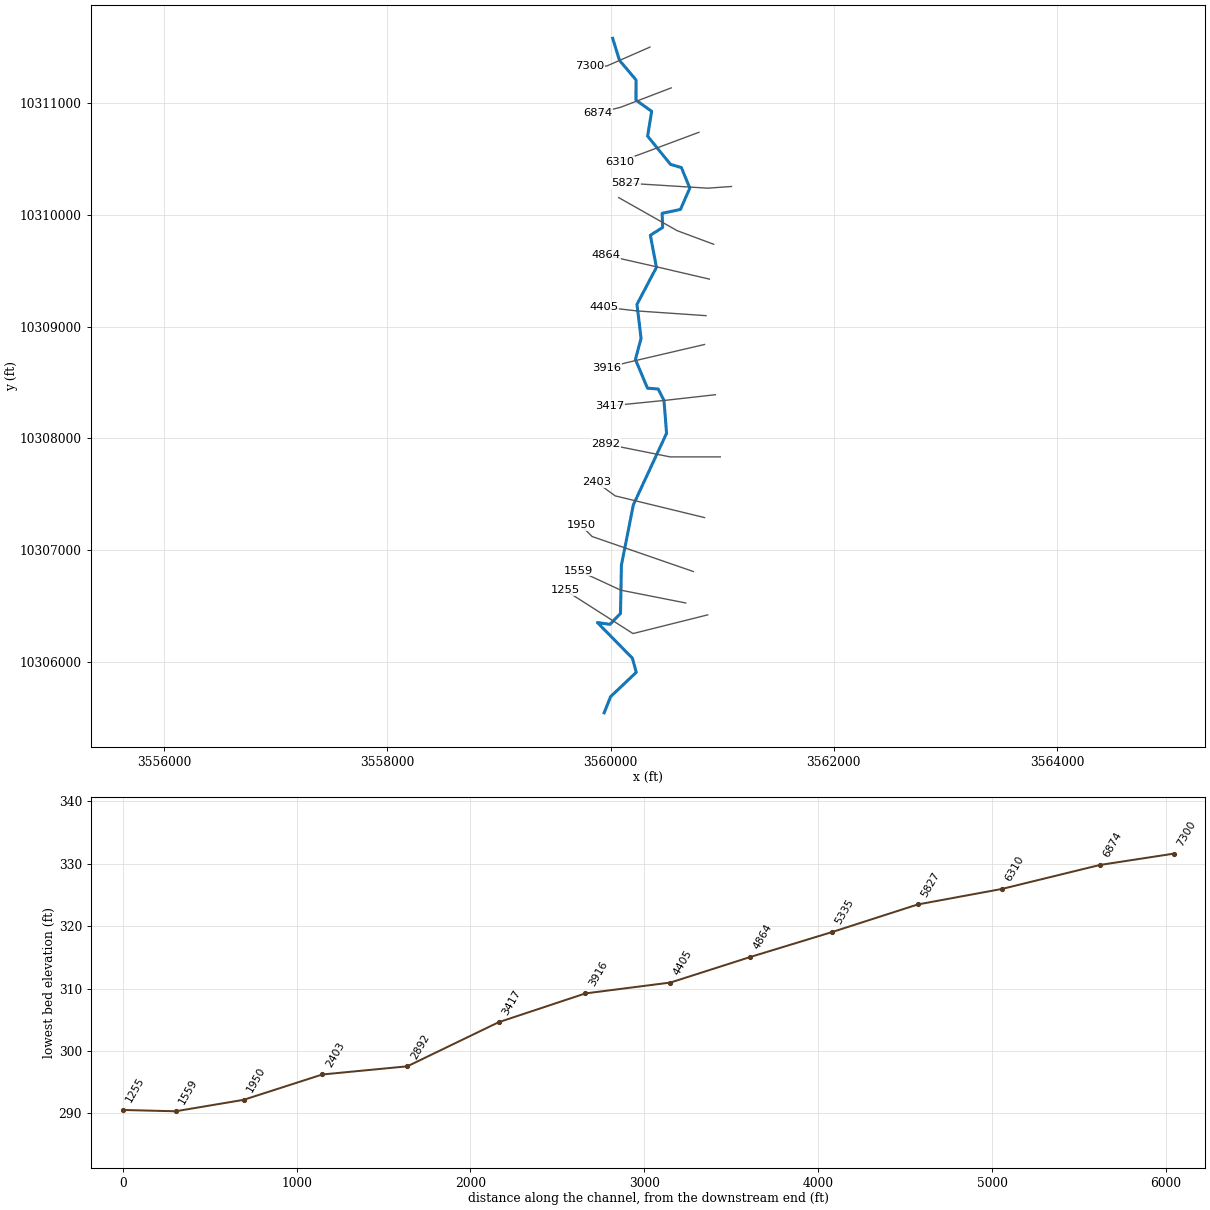
--- CEDAR CREEK TRIBUTARY 14.prj (project) ---

Proj Title=CEDAR CREEK TRIBUTARY 14 Base Level Engineering
Current Plan=p01
Default Exp/Contr=0.3,0.1
English Units
Geom File=g01
Flow File=f01
Plan File=p01
BEGIN DESCRIPTION:
CEDAR CREEK TRIBUTARY 14
END DESCRIPTION:

--- CEDAR CREEK TRIBUTARY 14.p01 (plan) ---

Plan Title=Multiple Run
Short Identifier=Multiple
Geom File=g01
Flow File=f01
Subcritical Flow
K Sum by GR= 0
Std Step Tol= 0.01
Critical Tol= 0.01
Num of Std Step Trials= 20
Max Error Tol= 0.3
Flow Tol Ratio= 0.001
Split Flow NTrial= 30
Split Flow Tol= 0.02
Split Flow Ratio= 0.02
Log Output Level= 0
Friction Slope Method= 1
Unsteady Friction Slope Method= 2
Unsteady Bridges Friction Slope Method= 1
Parabolic Critical Depth
Global Vel Dist=  1 , 1 , 1
Global Log Level= 0
CheckData=True
Encroach Param= -1, 0, 0, 0
BEGIN DESCRIPTION:
Multiple Run
END DESCRIPTION:

--- CEDAR CREEK TRIBUTARY 14.f01 (steady flow) ---

Flow Title=Multiple
Number of Profiles=7
Profile Names=10-year,25-year,50-year,1pct_min,100-year,1pct_plu,500-year
River Rch & RM= CEDAR CREEK TRIB,Reach-1,7300
     496     664     799     706     954    1291    1364
Boundary for River Rch & Prof#=CEDAR CREEK TRIB,Reach-1,1
Up Type=0
Dn Type=3
Dn Slope=0.005
Boundary for River Rch & Prof#=CEDAR CREEK TRIB,Reach-1,2
Up Type=0
Dn Type=3
Dn Slope=0.005
Boundary for River Rch & Prof#=CEDAR CREEK TRIB,Reach-1,3
Up Type=0
Dn Type=3
Dn Slope=0.005
Boundary for River Rch & Prof#=CEDAR CREEK TRIB,Reach-1,4
Up Type=0
Dn Type=3
Dn Slope=0.005
Boundary for River Rch & Prof#=CEDAR CREEK TRIB,Reach-1,5
Up Type=0
Dn Type=3
Dn Slope=0.005
Boundary for River Rch & Prof#=CEDAR CREEK TRIB,Reach-1,6
Up Type=0
Dn Type=3
Dn Slope=0.005
Boundary for River Rch & Prof#=CEDAR CREEK TRIB,Reach-1,7
Up Type=0
Dn Type=3
Dn Slope=0.005

--- CEDAR CREEK TRIBUTARY 14.g01 (geometry) ---

Geom Title=Existing Conditions

River Reach=CEDAR CREEK TRIB,Reach-1
Reach XY= 30
      3560018.52     10311583.04      3560079.83     10311385.41
      3560228.28     10311210.20      3560227.68     10311029.22
      3560367.83     10310929.68      3560331.99     10310706.70
      3560536.76     10310454.59      3560634.68     10310425.43
      3560709.87     10310241.60      3560626.04     10310050.59
      3560462.11     10310016.08      3560466.68     10309889.36
      3560356.38     10309819.49      3560410.90     10309532.21
      3560236.46     10309200.96      3560273.22     10308896.26
      3560222.58     10308707.65      3560330.72     10308450.01
      3560426.17     10308443.18      3560478.59     10308340.13
      3560501.62     10308046.33      3560204.03     10307405.90
      3560097.14     10306866.66      3560088.69     10306433.14
      3559994.63     10306336.00      3559882.11     10306351.64
      3560195.67     10306032.43      3560229.92     10305905.93
      3560000.04     10305688.25      3559942.15     10305543.01

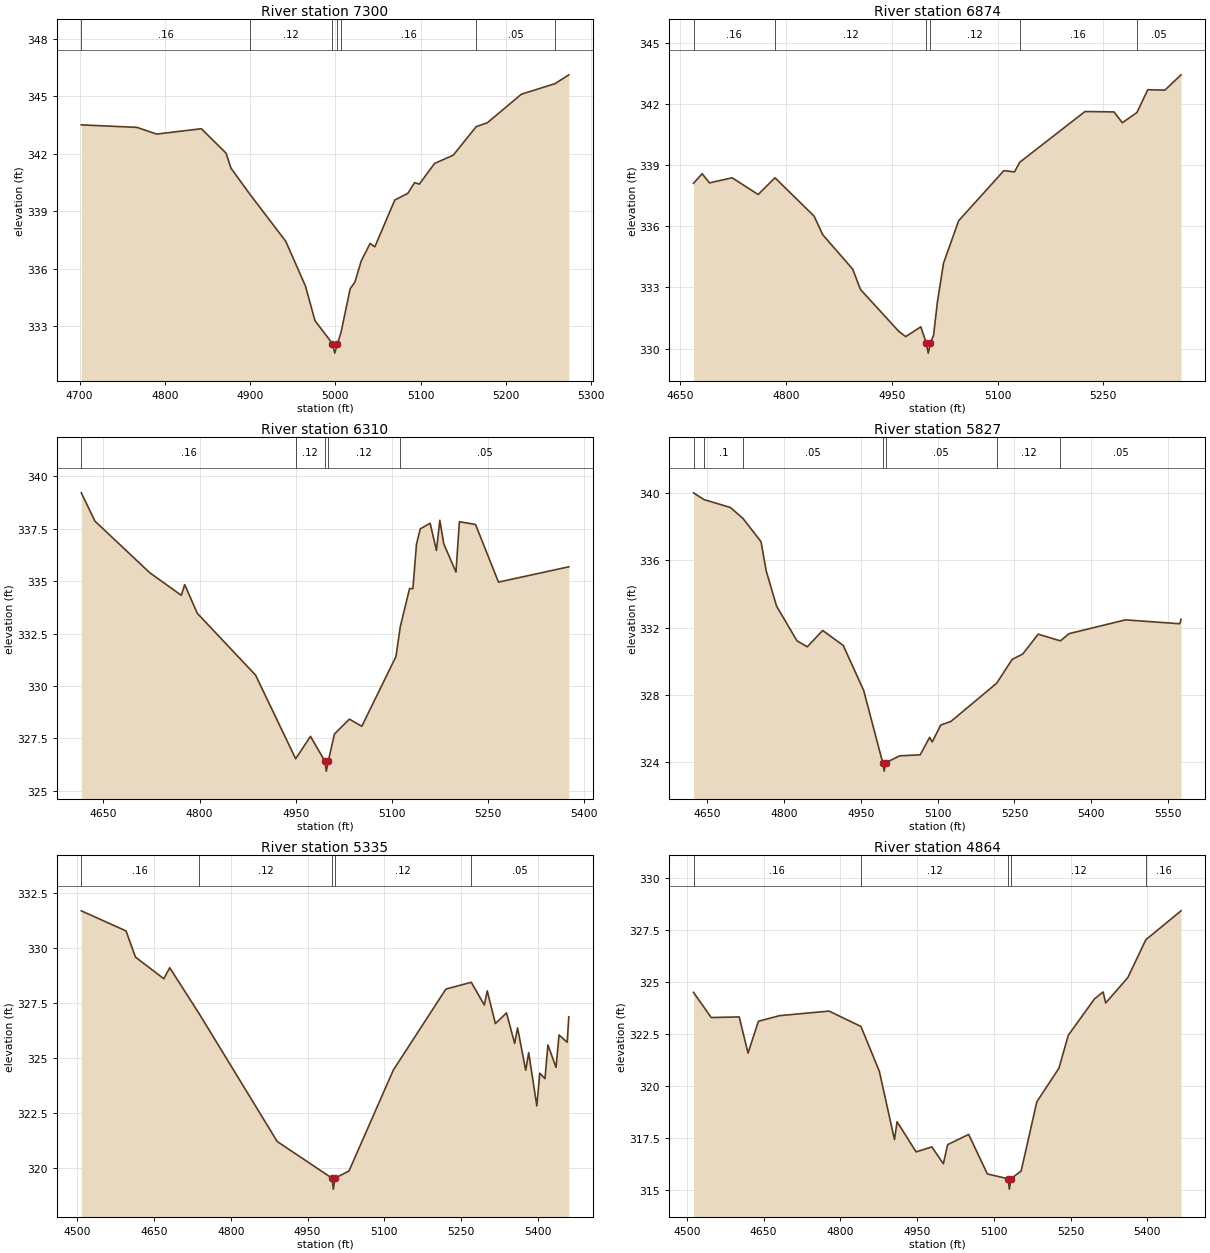
Type RM Length L Ch R = 1,7300,426,426,426
BEGIN DESCRIPTION:
CEDAR CREEK TRIBUTARY 14 14.0
END DESCRIPTION:
XS GIS Cut Line= 3
      3560353.07     10311504.51      3559966.00     10311335.09
      3559816.52     10311335.09
#Sta/Elev= 30
  4702.0  343.50  4767.3  343.37  4790.4  343.02  4842.9  343.30  4871.8  342.03
  4877.7  341.24  4899.4  339.91  4941.9  337.43  4965.0  335.10  4976.2  333.29
  4996.6  332.10  4999.4  331.60  5002.6  332.10  5006.7  332.67  5017.5  334.96
  5023.0  335.30  5030.5  336.41  5040.9  337.32  5046.4  337.14  5069.8  339.58
  5085.1  339.93  5093.1  340.49  5098.6  340.41  5116.5  341.49  5138.4  341.92
  5165.4  343.41  5178.4  343.61  5218.4  345.10  5257.8  345.65  5274.0  346.11
#Mann=7,-1,0
  4702.0    0.16       0  4899.4    0.12       0  4996.6    0.07       0
  5002.6    0.12       0  5006.7    0.16       0  5165.4    0.05       0
  5257.8    0.16       0
Bank Sta=4996.6,5002.6
Exp/Cntr=0.3,0.1

Type RM Length L Ch R = 1,6874,564,564,564
BEGIN DESCRIPTION:
CEDAR CREEK TRIBUTARY 14 13.0
END DESCRIPTION:
XS GIS Cut Line= 3
      3560543.31     10311139.19      3560089.89     10310965.54
      3559889.88     10310915.53
#Sta/Elev= 30
  4668.6  338.11  4680.8  338.58  4691.3  338.13  4723.4  338.38  4760.3  337.56
  4784.2  338.38  4839.7  336.50  4851.9  335.59  4894.4  333.90  4905.5  332.90
  4959.8  330.85  4969.7  330.59  4991.1  331.07  4998.8  330.28  5001.6  329.78
  5004.8  330.28  5009.2  330.66  5014.6  332.28  5023.3  334.19  5044.7  336.27
  5108.9  338.73  5124.0  338.67  5131.4  339.14  5224.0  341.63  5265.2  341.61
  5277.0  341.08  5297.7  341.58  5313.1  342.70  5337.4  342.68  5360.3  343.43
#Mann=6,-1,0
  4668.6    0.16       0  4784.2    0.12       0  4998.8    0.07       0
  5004.8    0.12       0  5131.4    0.16       0  5297.7    0.05       0
Bank Sta=4998.8,5004.8
Exp/Cntr=0.3,0.1

Type RM Length L Ch R = 1,6310,483,483,483
BEGIN DESCRIPTION:
CEDAR CREEK TRIBUTARY 14 12.0
END DESCRIPTION:
XS GIS Cut Line= 3
      3560792.07     10310741.63      3560307.40     10310560.80
      3560079.07     10310477.08
#Sta/Elev= 30
  4615.4  339.22  4636.7  337.87  4722.1  335.41  4771.4  334.33  4776.7  334.84
  4796.4  333.47  4887.3  330.52  4949.8  326.53  4972.9  327.60  4994.9  326.44
  4997.7  325.94  5000.9  326.44  5010.3  327.71  5033.6  328.42  5053.0  328.08
  5106.3  331.41  5113.0  332.83  5127.5  334.65  5132.7  334.65  5138.3  336.77
  5144.2  337.50  5159.6  337.77  5169.4  336.47  5174.7  337.91  5180.9  336.78
  5199.9  335.44  5205.2  337.84  5230.4  337.71  5266.2  334.96  5375.9  335.69
#Mann=5,-1,0
  4615.4    0.16       0  4949.8    0.12       0  4994.9    0.07       0
  5000.9    0.12       0  5113.0    0.05       0
Bank Sta=4994.9,5000.9
Exp/Cntr=0.3,0.1

Type RM Length L Ch R = 1,5827,492,492,492
BEGIN DESCRIPTION:
CEDAR CREEK TRIBUTARY 14 11.0
END DESCRIPTION:
XS GIS Cut Line= 3
      3561083.69     10310256.38      3560870.59     10310241.15
      3560133.74     10310286.73
#Sta/Elev= 30
  4623.5  340.02  4643.8  339.62  4695.3  339.15  4720.0  338.50  4755.3  337.11
  4765.4  335.38  4785.5  333.29  4825.6  331.21  4845.6  330.86  4875.7  331.83
  4915.8  330.94  4955.8  328.26  4992.9  323.96  4995.7  323.46  4998.9  323.96
  5026.0  324.37  5066.1  324.43  5084.5  325.47  5089.6  325.20  5106.1  326.20
  5126.2  326.42  5215.4  328.69  5245.7  330.11  5266.4  330.43  5296.5  331.61
  5339.9  331.21  5356.6  331.64  5466.8  332.46  5573.0  332.23  5575.4  332.49
#Mann=7,-1,0
  4623.5    0.05       0  4643.8     0.1       0  4720.0    0.05       0
  4992.9    0.07       0  4998.9    0.05       0  5215.4    0.12       0
  5339.9    0.05       0
Bank Sta=4992.9,4998.9
Exp/Cntr=0.3,0.1

Type RM Length L Ch R = 1,5335,471,471,471
BEGIN DESCRIPTION:
CEDAR CREEK TRIBUTARY 14 10.0
END DESCRIPTION:
XS GIS Cut Line= 3
      3560923.88     10309738.85      3560596.61     10309860.63
      3560072.18     10310157.04
#Sta/Elev= 30
  4508.3  331.67  4595.6  330.76  4614.1  329.57  4669.5  328.59  4680.9  329.09
  4738.8  326.99  4890.7  321.21  4997.5  319.55  5000.3  319.05  5003.5  319.55
  5030.8  319.87  5117.4  324.45  5219.9  328.12  5269.5  328.43  5295.0  327.40
  5300.7  328.04  5316.6  326.56  5338.3  327.04  5354.2  325.66  5359.9  326.36
  5375.8  324.44  5381.6  325.24  5397.5  322.82  5403.2  324.31  5413.4  324.06
  5419.1  325.59  5435.0  324.57  5440.8  326.04  5456.7  325.71  5459.9  326.86
#Mann=5,-1,0
  4508.3    0.16       0  4738.8    0.12       0  4997.5    0.07       0
  5003.5    0.12       0  5269.5    0.05       0
Bank Sta=4997.5,5003.5
Exp/Cntr=0.3,0.1

Type RM Length L Ch R = 1,4864,459,459,459
BEGIN DESCRIPTION:
CEDAR CREEK TRIBUTARY 14 9.0
END DESCRIPTION:
XS GIS Cut Line= 3
      3560885.82     10309426.82      3560392.11     10309541.64
      3559957.27     10309639.93
#Sta/Elev= 30
  4513.1  324.51  4547.7  323.30  4602.4  323.33  4619.6  321.59  4639.9  323.12
  4681.2  323.39  4778.0  323.61  4840.3  322.87  4876.3  320.71  4905.8  317.43
  4910.9  318.29  4948.1  316.84  4978.9  317.08  5001.3  316.27  5009.7  317.19
  5050.8  317.68  5087.3  315.78  5127.5  315.55  5130.3  315.05  5133.5  315.55
  5153.3  315.92  5184.0  319.25  5227.1  320.86  5245.5  322.45  5296.8  324.20
  5313.5  324.53  5318.6  324.00  5361.8  325.22  5397.0  327.04  5465.8  328.43
#Mann=5,-1,0
  4513.1    0.16       0  4840.3    0.12       0  5127.5    0.07       0
  5133.5    0.12       0  5397.0    0.16       0
Bank Sta=5127.5,5133.5
Exp/Cntr=0.3,0.1

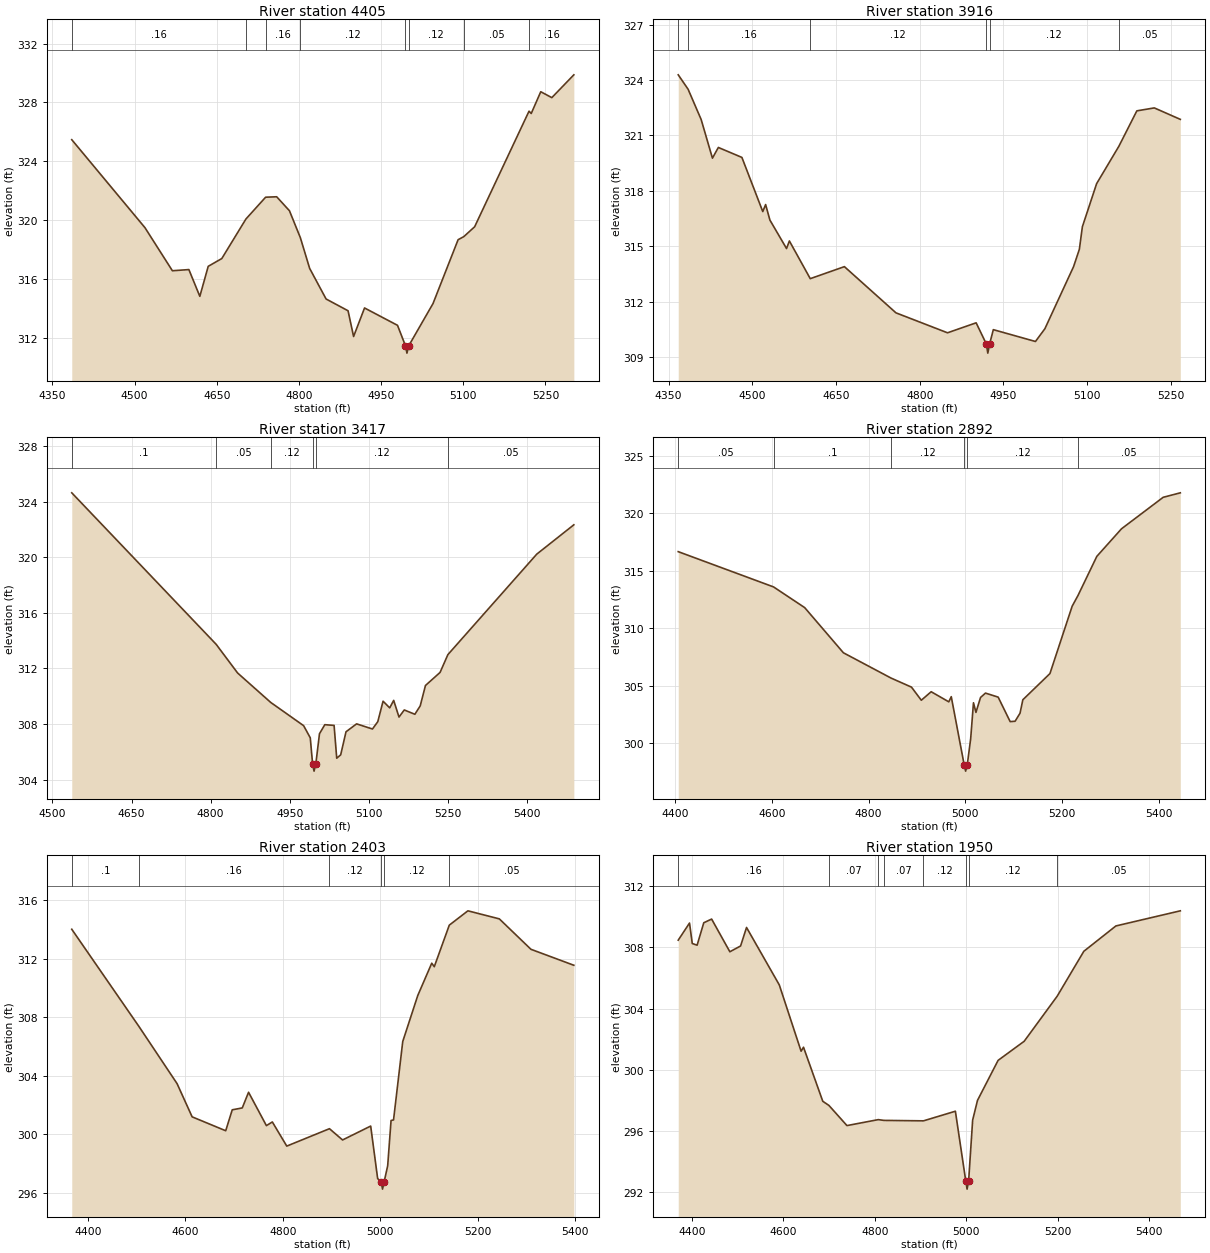
Type RM Length L Ch R = 1,4405,489,489,489
BEGIN DESCRIPTION:
CEDAR CREEK TRIBUTARY 14 8.0
END DESCRIPTION:
XS GIS Cut Line= 3
      3560855.36     10309099.57      3560242.11     10309141.64
      3559942.13     10309175.67
#Sta/Elev= 30
  4385.3  325.47  4518.9  319.49  4569.0  316.56  4599.1  316.64  4619.1  314.82
  4634.4  316.86  4659.2  317.39  4703.3  320.08  4739.2  321.56  4759.4  321.59
  4782.7  320.64  4802.6  318.81  4819.6  316.72  4849.6  314.64  4889.7  313.84
  4899.8  312.09  4919.8  314.03  4980.0  312.85  4994.5  311.46  4997.2  310.96
  5000.5  311.46  5044.8  314.33  5090.6  318.67  5101.0  318.88  5120.8  319.55
  5220.1  327.41  5224.1  327.25  5241.5  328.73  5261.7  328.33  5301.9  329.88
#Mann=8,-1,0
  4385.3    0.16       0  4703.3    0.12       0  4739.2    0.16       0
  4802.6    0.12       0  4994.5    0.07       0  5000.5    0.12       0
  5101.0    0.05       0  5220.1    0.16       0
Bank Sta=4994.5,5000.5
Exp/Cntr=0.3,0.1

Type RM Length L Ch R = 1,3916,499,499,499
BEGIN DESCRIPTION:
CEDAR CREEK TRIBUTARY 14 7.0
END DESCRIPTION:
XS GIS Cut Line= 3
      3560842.09     10308841.64      3560166.00     10308684.03
      3559966.56     10308634.17
#Sta/Elev= 30
  4367.2  324.28  4384.9  323.50  4408.3  321.86  4428.5  319.77  4439.1  320.35
  4481.3  319.81  4518.7  316.88  4523.8  317.26  4531.5  316.42  4561.3  314.88
  4566.4  315.29  4603.8  313.25  4665.0  313.90  4757.4  311.40  4849.8  310.32
  4901.1  310.86  4919.3  309.72  4922.0  309.22  4925.3  309.72  4931.9  310.49
  5007.4  309.85  5024.3  310.54  5075.7  313.90  5086.1  314.84  5091.5  316.06
  5117.0  318.39  5157.0  320.42  5189.1  322.33  5220.4  322.49  5267.0  321.87
#Mann=6,-1,0
  4367.2     0.1       0  4384.9    0.16       0  4603.8    0.12       0
  4919.3    0.07       0  4925.3    0.12       0  5157.0    0.05       0
Bank Sta=4919.3,4925.3
Exp/Cntr=0.3,0.1

Type RM Length L Ch R = 1,3417,525,525,525
BEGIN DESCRIPTION:
CEDAR CREEK TRIBUTARY 14 6.0
END DESCRIPTION:
XS GIS Cut Line= 3
      3560939.04     10308391.78      3560492.11     10308341.64
      3559992.14     10308291.65
#Sta/Elev= 30
  4536.6  324.63  4810.5  313.73  4851.1  311.67  4914.0  309.55  4976.3  307.88
  4988.9  307.01  4993.4  305.11  4996.1  304.61  4999.4  305.11  5006.4  307.30
  5016.5  307.95  5034.1  307.90  5039.1  305.54  5046.6  305.78  5056.7  307.44
  5076.8  308.01  5106.9  307.64  5117.0  308.17  5127.0  309.64  5139.6  309.16
  5147.1  309.70  5157.2  308.50  5167.2  309.01  5187.3  308.70  5197.4  309.30
  5207.4  310.77  5235.1  311.71  5249.9  312.99  5418.5  320.22  5488.8  322.33
#Mann=6,-1,0
  4536.6     0.1       0  4810.5    0.05       0  4914.0    0.12       0
  4993.4    0.07       0  4999.4    0.12       0  5249.9    0.05       0
Bank Sta=4993.4,4999.4
Exp/Cntr=0.3,0.1

Type RM Length L Ch R = 1,2892,489,489,489
BEGIN DESCRIPTION:
CEDAR CREEK TRIBUTARY 14 5.0
END DESCRIPTION:
XS GIS Cut Line= 3
      3560983.44     10307835.09      3560533.43     10307835.09
      3559957.36     10307950.37
#Sta/Elev= 30
  4406.8  316.65  4603.8  313.58  4668.1  311.78  4748.1  307.85  4846.5  305.65
  4888.8  304.86  4909.1  303.72  4929.5  304.46  4965.9  303.58  4971.0  304.03
  4997.9  298.05  5000.7  297.55  5003.9  298.05  5011.1  300.37  5016.9  303.50
  5022.0  302.66  5031.5  303.96  5041.7  304.34  5067.9  303.99  5092.7  301.86
  5102.9  301.89  5113.1  302.59  5118.9  303.76  5174.9  306.04  5220.8  311.90
  5232.8  312.83  5271.8  316.24  5322.8  318.64  5408.9  321.38  5444.3  321.77
#Mann=6,-1,0
  4406.8    0.05       0  4603.8     0.1       0  4846.5    0.12       0
  4997.9    0.07       0  5003.9    0.12       0  5232.8    0.05       0
Bank Sta=4997.9,5003.9
Exp/Cntr=0.3,0.1

Type RM Length L Ch R = 1,2403,453,453,453
BEGIN DESCRIPTION:
CEDAR CREEK TRIBUTARY 14 4.0
END DESCRIPTION:
XS GIS Cut Line= 3
      3560842.09     10307291.65      3560041.03     10307486.13
      3559874.45     10307607.28
#Sta/Elev= 30
  4366.8  314.00  4505.0  307.34  4582.9  303.45  4613.8  301.18  4682.7  300.23
  4696.1  301.66  4716.7  301.79  4729.6  302.86  4766.2  300.58  4778.4  300.83
  4808.0  299.18  4895.6  300.37  4922.5  299.60  4980.2  300.55  4994.5  296.96
  5001.8  296.74  5004.5  296.24  5007.8  296.74  5015.1  297.84  5022.0  300.93
  5027.1  300.97  5046.0  306.33  5076.8  309.47  5105.5  311.68  5110.7  311.44
  5141.5  314.28  5179.7  315.26  5244.2  314.71  5309.1  312.63  5397.1  311.54
#Mann=6,-1,0
  4366.8     0.1       0  4505.0    0.16       0  4895.6    0.12       0
  5001.8    0.07       0  5007.8    0.12       0  5141.5    0.05       0
Bank Sta=5001.8,5007.8
Exp/Cntr=0.3,0.1

Type RM Length L Ch R = 1,1950,391,391,391
BEGIN DESCRIPTION:
CEDAR CREEK TRIBUTARY 14 3.0
END DESCRIPTION:
XS GIS Cut Line= 3
      3560741.17     10306808.80      3559834.41     10307122.08
      3559735.73     10307220.76
#Sta/Elev= 30
  4369.7  308.48  4394.4  309.60  4400.4  308.26  4411.0  308.15  4425.6  309.62
  4442.8  309.86  4482.7  307.72  4506.2  308.10  4519.2  309.31  4590.9  305.55
  4638.6  301.21  4643.9  301.47  4686.1  297.93  4699.5  297.66  4739.0  296.34
  4807.5  296.73  4819.8  296.68  4906.5  296.65  4976.3  297.28  4999.2  292.68
  5001.9  292.18  5005.2  292.68  5014.1  296.70  5024.7  297.99  5069.8  300.61
  5126.9  301.86  5199.1  304.81  5257.4  307.75  5327.6  309.41  5468.6  310.40
#Mann=8,-1,0
  4369.7    0.16       0  4699.5    0.07       0  4807.5    0.12       0
  4819.8    0.07       0  4906.5    0.12       0  4999.2    0.07       0
  5005.2    0.12       0  5199.1    0.05       0
Bank Sta=4999.2,5005.2
Exp/Cntr=0.3,0.1

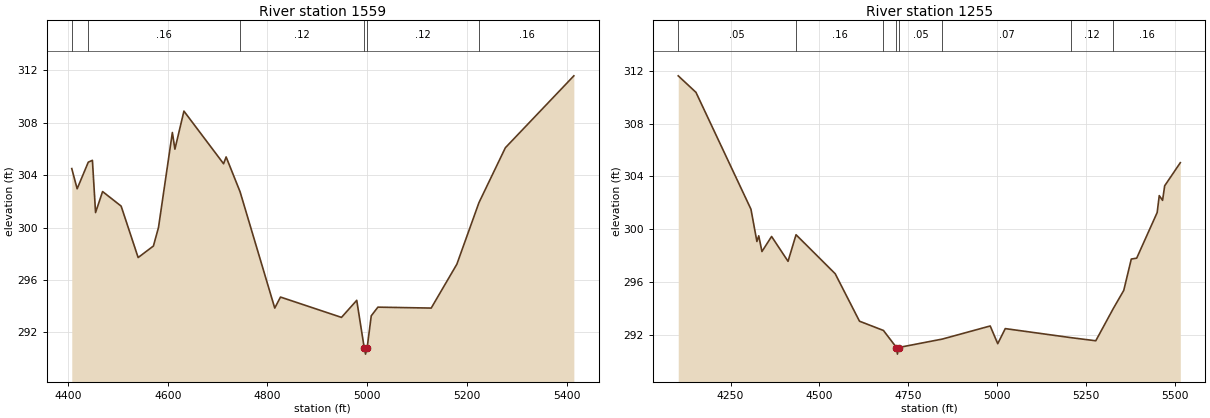
Type RM Length L Ch R = 1,1559,304,304,304
BEGIN DESCRIPTION:
CEDAR CREEK TRIBUTARY 14 2.0
END DESCRIPTION:
XS GIS Cut Line= 3
      3560672.74     10306527.19      3560092.11     10306641.64
      3559715.45     10306815.63
#Sta/Elev= 30
  4407.6  304.49  4418.4  302.95  4440.7  304.98  4449.0  305.12  4455.3  301.14
  4469.4  302.74  4506.6  301.63  4540.7  297.71  4571.3  298.59  4581.5  300.00
  4609.3  307.24  4614.4  305.97  4632.5  308.87  4712.0  304.86  4717.1  305.38
  4745.1  302.72  4814.6  293.86  4826.1  294.70  4948.4  293.15  4979.0  294.45
  4993.9  290.85  4996.6  290.35  4999.9  290.85  5008.1  293.27  5021.4  293.93
  5128.3  293.86  5179.7  297.20  5224.1  301.90  5277.0  306.08  5414.3  311.56
#Mann=6,-1,0
  4407.6    0.05       0  4440.7    0.16       0  4745.1    0.12       0
  4993.9    0.07       0  4999.9    0.12       0  5224.1    0.16       0
Bank Sta=4993.9,4999.9
Exp/Cntr=0.3,0.1

Type RM Length L Ch R = 1,1255,0,0,0
BEGIN DESCRIPTION:
CEDAR CREEK TRIBUTARY 14 1.0
END DESCRIPTION:
XS GIS Cut Line= 3
      3560870.55     10306420.64      3560200.86     10306253.22
      3559592.12     10306641.63
#Sta/Elev= 30
  4102.7  311.61  4152.6  310.36  4307.3  301.52  4324.0  299.08  4329.2  299.51
  4338.2  298.32  4365.3  299.46  4411.6  297.58  4434.1  299.59  4544.3  296.64
  4612.6  293.05  4680.0  292.35  4716.6  291.06  4719.3  290.56  4722.6  291.06
  4845.8  291.70  4980.3  292.69  5001.5  291.35  5022.7  292.49  5206.4  291.81
  5277.3  291.57  5326.6  294.01  5356.0  295.38  5377.2  297.75  5392.4  297.82
  5450.0  301.27  5455.9  302.55  5465.2  302.19  5471.1  303.29  5515.1  305.04
#Mann=8,-1,0
  4102.7    0.05       0  4434.1    0.16       0  4680.0    0.05       0
  4716.6    0.07       0  4722.6    0.05       0  4845.8    0.07       0
  5206.4    0.12       0  5326.6    0.16       0
Bank Sta=4716.6,4722.6
Exp/Cntr=0.3,0.1

Chan Stop Cuts=-1