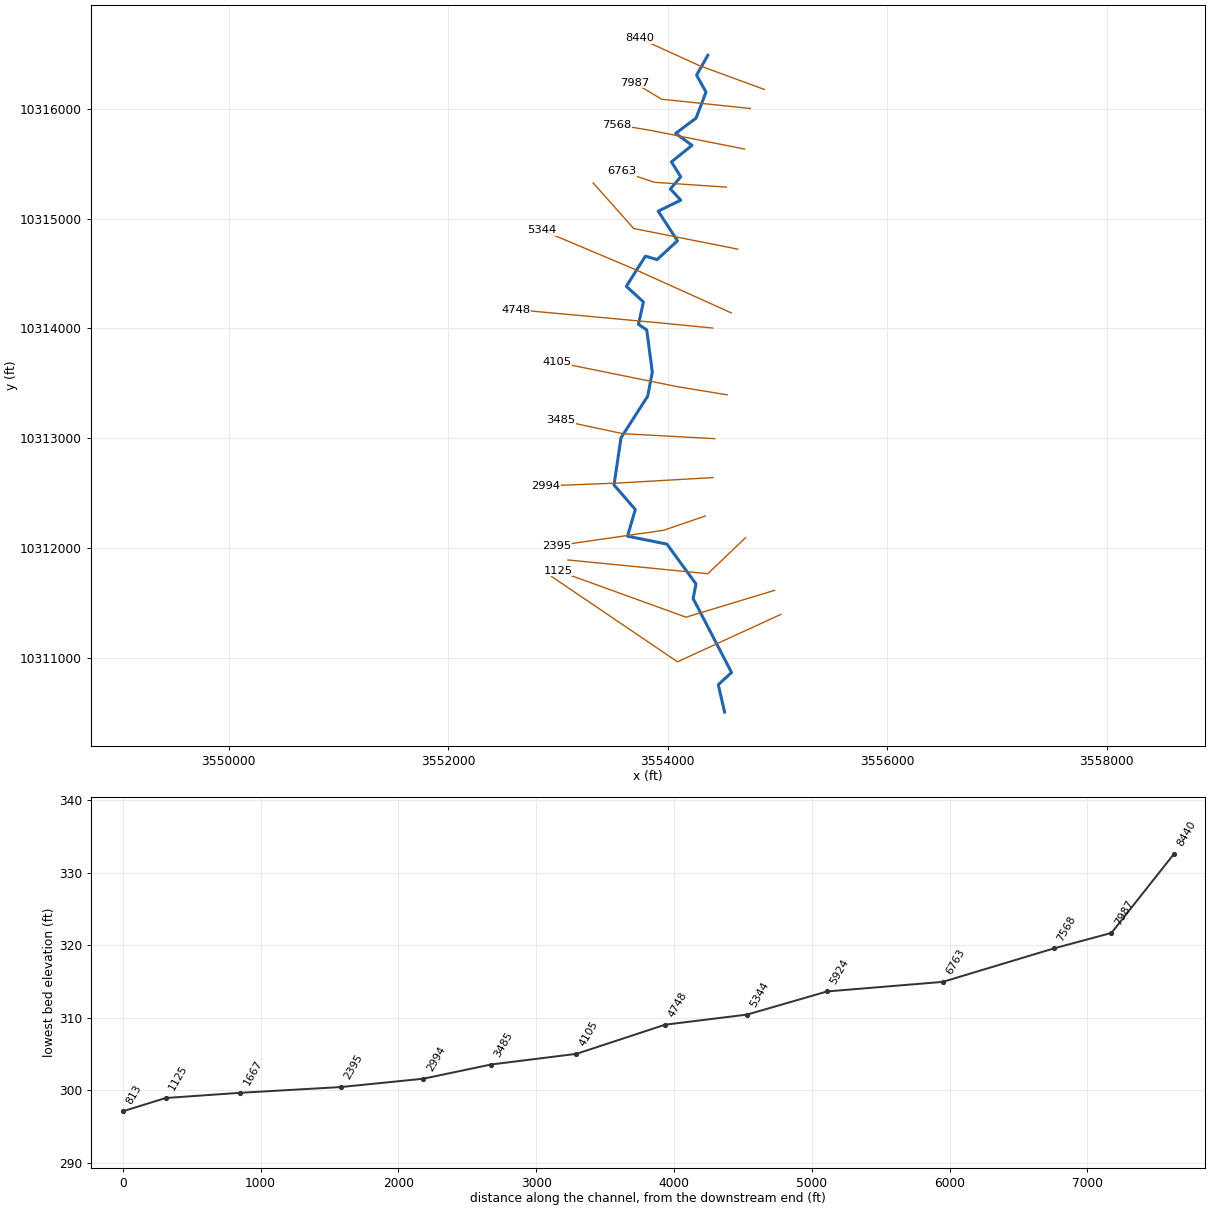
--- CEDAR CREEK TRIBUTARY 16.prj (project) ---

Proj Title=CEDAR CREEK TRIBUTARY 16 Base Level Engineering
Current Plan=p01
Default Exp/Contr=0.3,0.1
English Units
Geom File=g01
Flow File=f01
Plan File=p01
BEGIN DESCRIPTION:
CEDAR CREEK TRIBUTARY 16
END DESCRIPTION:

--- CEDAR CREEK TRIBUTARY 16.p01 (plan) ---

Plan Title=Multiple Run
Short Identifier=Multiple
Geom File=g01
Flow File=f01
Subcritical Flow
K Sum by GR= 0
Std Step Tol= 0.01
Critical Tol= 0.01
Num of Std Step Trials= 20
Max Error Tol= 0.3
Flow Tol Ratio= 0.001
Split Flow NTrial= 30
Split Flow Tol= 0.02
Split Flow Ratio= 0.02
Log Output Level= 0
Friction Slope Method= 1
Unsteady Friction Slope Method= 2
Unsteady Bridges Friction Slope Method= 1
Parabolic Critical Depth
Global Vel Dist=  1 , 1 , 1
Global Log Level= 0
CheckData=True
Encroach Param= -1, 0, 0, 0
BEGIN DESCRIPTION:
Multiple Run
END DESCRIPTION:

--- CEDAR CREEK TRIBUTARY 16.f01 (steady flow) ---

Flow Title=Multiple
Number of Profiles=7
Profile Names=10-year,25-year,50-year,1pct_min,100-year,1pct_plu,500-year
River Rch & RM= CEDAR CREEK TRIB,Reach-1,8440
     492     656     787     693     937    1268    1330
River Rch & RM= CEDAR CREEK TRIB,Reach-1,5344
     714     969    1177    1047    1416    1914    2053
Boundary for River Rch & Prof#=CEDAR CREEK TRIB,Reach-1,1
Up Type=0
Dn Type=3
Dn Slope=0.005
Boundary for River Rch & Prof#=CEDAR CREEK TRIB,Reach-1,2
Up Type=0
Dn Type=3
Dn Slope=0.005
Boundary for River Rch & Prof#=CEDAR CREEK TRIB,Reach-1,3
Up Type=0
Dn Type=3
Dn Slope=0.005
Boundary for River Rch & Prof#=CEDAR CREEK TRIB,Reach-1,4
Up Type=0
Dn Type=3
Dn Slope=0.005
Boundary for River Rch & Prof#=CEDAR CREEK TRIB,Reach-1,5
Up Type=0
Dn Type=3
Dn Slope=0.005
Boundary for River Rch & Prof#=CEDAR CREEK TRIB,Reach-1,6
Up Type=0
Dn Type=3
Dn Slope=0.005
Boundary for River Rch & Prof#=CEDAR CREEK TRIB,Reach-1,7
Up Type=0
Dn Type=3
Dn Slope=0.005

--- CEDAR CREEK TRIBUTARY 16.g01 (geometry) ---

Geom Title=Existing Conditions

River Reach=CEDAR CREEK TRIB,Reach-1
Reach XY= 30
      3554366.83     10316487.02      3554263.78     10316305.80
      3554350.10     10316151.79      3554258.43     10315913.16
      3554073.55     10315775.85      3554222.25     10315666.85
      3554035.18     10315516.15      3554119.92     10315380.21
      3554025.48     10315269.63      3554120.10     10315167.58
      3553914.01     10315067.21      3554090.31     10314797.98
      3553904.22     10314626.38      3553798.04     10314658.13
      3553623.92     10314383.09      3553779.66     10314240.76
      3553734.33     10314036.74      3553809.91     10313985.96
      3553860.84     10313602.08      3553818.80     10313383.08
      3553575.75     10313004.65      3553511.69     10312574.44
      3553705.65     10312351.72      3553635.09     10312108.25
      3553994.37     10312035.68      3554258.26     10311674.13
      3554233.09     10311540.02      3554582.48     10310867.28
      3554461.82     10310756.17      3554519.11     10310507.03

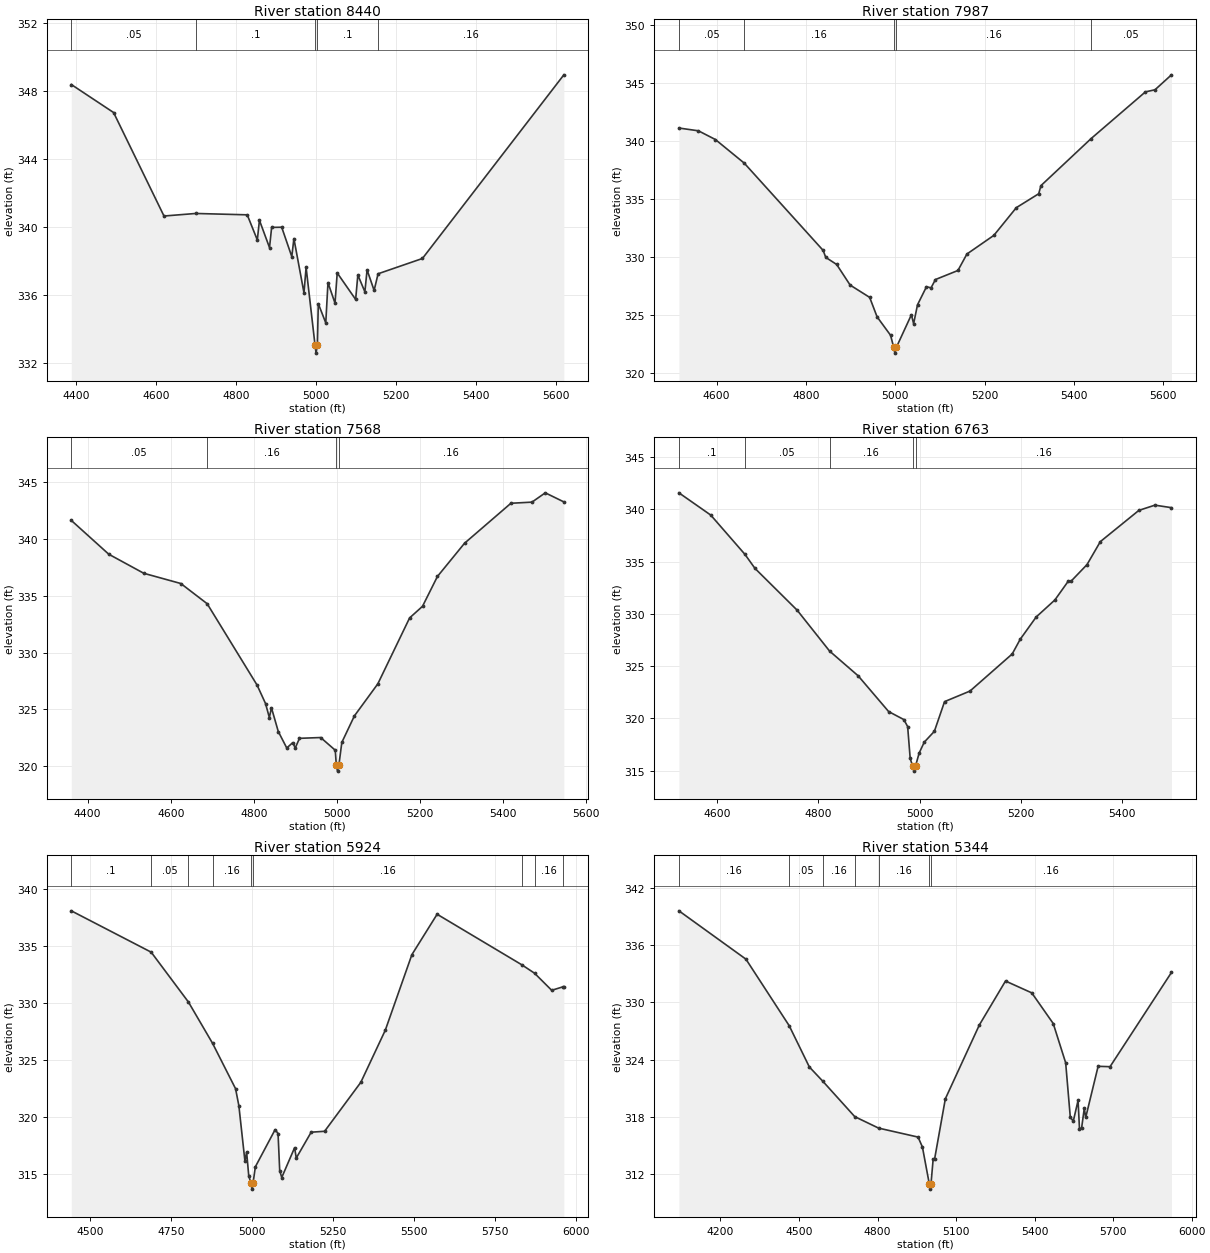
Type RM Length L Ch R = 1,8440,453,453,453
BEGIN DESCRIPTION:
CEDAR CREEK TRIBUTARY 16 17.0
END DESCRIPTION:
XS GIS Cut Line= 3
      3554881.44     10316175.68      3554292.11     10316391.64
      3553742.11     10316641.64
#Sta/Elev= 30
  4388.0  348.40  4493.8  346.75  4619.8  340.66  4699.4  340.81  4828.0  340.73
  4853.2  339.25  4858.5  340.41  4883.7  338.80  4889.0  339.99  4914.2  340.00
  4939.4  338.27  4944.7  339.33  4969.9  336.14  4975.2  337.64  4997.4  333.09
  5000.1  332.59  5003.4  333.09  5005.7  335.50  5024.4  334.37  5029.9  336.74
  5047.5  335.53  5053.0  337.31  5099.1  335.75  5104.6  337.19  5122.2  336.20
  5127.7  337.49  5145.3  336.28  5155.2  337.26  5266.1  338.16  5619.8  348.97
#Mann=5,-1,0
  4388.0    0.05       0  4699.4     0.1       0  4997.4    0.07       0
  5003.4     0.1       0  5155.2    0.16       0
Bank Sta=4997.4,5003.4
Exp/Cntr=0.3,0.1

Type RM Length L Ch R = 1,7987,419,419,419
BEGIN DESCRIPTION:
CEDAR CREEK TRIBUTARY 16 16.0
END DESCRIPTION:
XS GIS Cut Line= 3
      3554753.30     10316002.39      3553945.50     10316086.85
      3553696.49     10316236.26
#Sta/Elev= 30
  4515.8  341.12  4559.5  340.88  4597.4  340.13  4662.1  338.09  4838.7  330.56
  4844.5  329.96  4868.9  329.35  4899.1  327.57  4942.8  326.51  4959.4  324.83
  4989.6  323.24  4996.6  322.20  4999.4  321.70  5002.6  322.20  5036.2  325.01
  5041.2  324.24  5049.9  325.87  5070.0  327.43  5080.1  327.33  5090.1  328.05
  5140.4  328.83  5160.5  330.25  5220.8  331.86  5271.1  334.25  5321.2  335.45
  5326.2  336.15  5438.5  340.21  5560.1  344.24  5581.5  344.42  5618.4  345.71
#Mann=5,-1,0
  4515.8    0.05       0  4662.1    0.16       0  4996.6    0.07       0
  5002.6    0.16       0  5438.5    0.05       0
Bank Sta=4996.6,5002.6
Exp/Cntr=0.3,0.1

Type RM Length L Ch R = 1,7568,805,805,805
BEGIN DESCRIPTION:
CEDAR CREEK TRIBUTARY 16 15.0
END DESCRIPTION:
XS GIS Cut Line= 3
      3554700.59     10315633.17      3553835.92     10315804.67
      3553536.47     10315854.57
#Sta/Elev= 30
  4360.8  341.65  4451.0  338.67  4535.3  336.99  4624.3  336.09  4687.7  334.31
  4807.8  327.14  4828.2  325.51  4837.3  324.28  4842.4  325.14  4858.8  323.05
  4879.2  321.60  4893.6  322.07  4899.6  321.60  4909.8  322.45  4960.8  322.52
  4995.9  321.40  4998.5  320.06  5001.3  319.56  5004.5  320.06  5011.7  322.09
  5042.0  324.43  5098.3  327.25  5174.8  333.06  5205.8  334.08  5241.7  336.71
  5307.0  339.64  5418.5  343.16  5469.2  343.26  5501.2  344.08  5545.9  343.28
#Mann=4,-1,0
  4360.8    0.05       0  4687.7    0.16       0  4998.5    0.07       0
  5004.5    0.16       0
Bank Sta=4998.5,5004.5
Exp/Cntr=0.3,0.1

Type RM Length L Ch R = 1,6763,839,839,839
BEGIN DESCRIPTION:
CEDAR CREEK TRIBUTARY 16 13.0
END DESCRIPTION:
XS GIS Cut Line= 3
      3554534.82     10315286.57      3553881.13     10315330.02
      3553581.09     10315430.03
#Sta/Elev= 30
  4525.4  341.58  4588.2  339.45  4655.5  335.70  4675.4  334.35  4758.6  330.35
  4822.5  326.44  4878.9  324.07  4939.0  320.65  4969.1  319.88  4976.5  319.21
  4981.5  316.17  4986.1  315.45  4988.9  314.95  4992.1  315.45  4999.2  316.68
  5009.2  317.72  5029.2  318.76  5049.3  321.60  5099.4  322.61  5182.7  326.16
  5198.4  327.56  5230.0  329.70  5266.9  331.33  5293.3  333.13  5298.5  333.11
  5330.2  334.71  5356.5  336.91  5432.5  339.90  5464.1  340.40  5496.8  340.16
#Mann=5,-1,0
  4525.4     0.1       0  4655.5    0.05       0  4822.5    0.16       0
  4986.1    0.07       0  4992.1    0.16       0
Bank Sta=4986.1,4992.1
Exp/Cntr=0.3,0.1

Type RM Length L Ch R = 1,5924,580,580,580
BEGIN DESCRIPTION:
CEDAR CREEK TRIBUTARY 16 12.0
END DESCRIPTION:
XS GIS Cut Line= 3
      3554640.33     10314721.45      3553690.91     10314909.82
      3553321.67     10315324.28
#Sta/Elev= 30
  4441.0  338.07  4688.0  334.44  4803.2  330.06  4877.7  326.44  4948.9  322.45
  4959.1  320.96  4978.0  316.06  4983.1  316.89  4989.7  314.79  4996.9  314.13
  4999.7  313.63  5002.9  314.13  5010.1  315.59  5071.3  318.86  5080.3  318.51
  5085.4  315.26  5091.7  314.65  5131.5  317.27  5136.6  316.36  5182.7  318.63
  5224.2  318.71  5336.2  323.01  5411.8  327.58  5494.1  334.22  5572.1  337.77
  5834.6  333.32  5873.4  332.59  5926.4  331.09  5961.6  331.40  5964.0  331.40
#Mann=9,-1,0
  4441.0     0.1       0  4688.0    0.05       0  4803.2     0.1       0
  4877.7    0.16       0  4996.9    0.07       0  5002.9    0.16       0
  5834.6     0.1       0  5873.4    0.16       0  5961.6     0.1       0
Bank Sta=4996.9,5002.9
Exp/Cntr=0.3,0.1

Type RM Length L Ch R = 1,5344,596,596,596
BEGIN DESCRIPTION:
CEDAR CREEK TRIBUTARY 16 11.0
END DESCRIPTION:
XS GIS Cut Line= 3
      3554580.07     10314141.24      3553692.11     10314541.64
      3552855.85     10314894.20
#Sta/Elev= 30
  4041.3  339.58  4297.3  334.52  4462.6  327.55  4539.6  323.23  4589.9  321.77
  4713.0  318.03  4804.0  316.83  4954.8  315.89  4971.5  314.85  4998.1  310.94
  5000.8  310.44  5004.1  310.94  5012.6  313.60  5018.1  313.60  5059.1  319.90
  5189.0  327.63  5288.9  332.23  5389.2  330.99  5471.2  327.78  5518.7  323.67
  5536.3  317.99  5547.8  317.55  5566.1  319.73  5571.5  316.75  5579.7  316.86
  5589.8  318.89  5595.3  317.95  5642.7  323.30  5688.2  323.26  5922.9  333.13
#Mann=7,-1,0
  4041.3    0.16       0  4462.6    0.05       0  4589.9    0.16       0
  4713.0    0.05       0  4804.0    0.16       0  4998.1    0.07       0
  5004.1    0.16       0
Bank Sta=4998.1,5004.1
Exp/Cntr=0.3,0.1

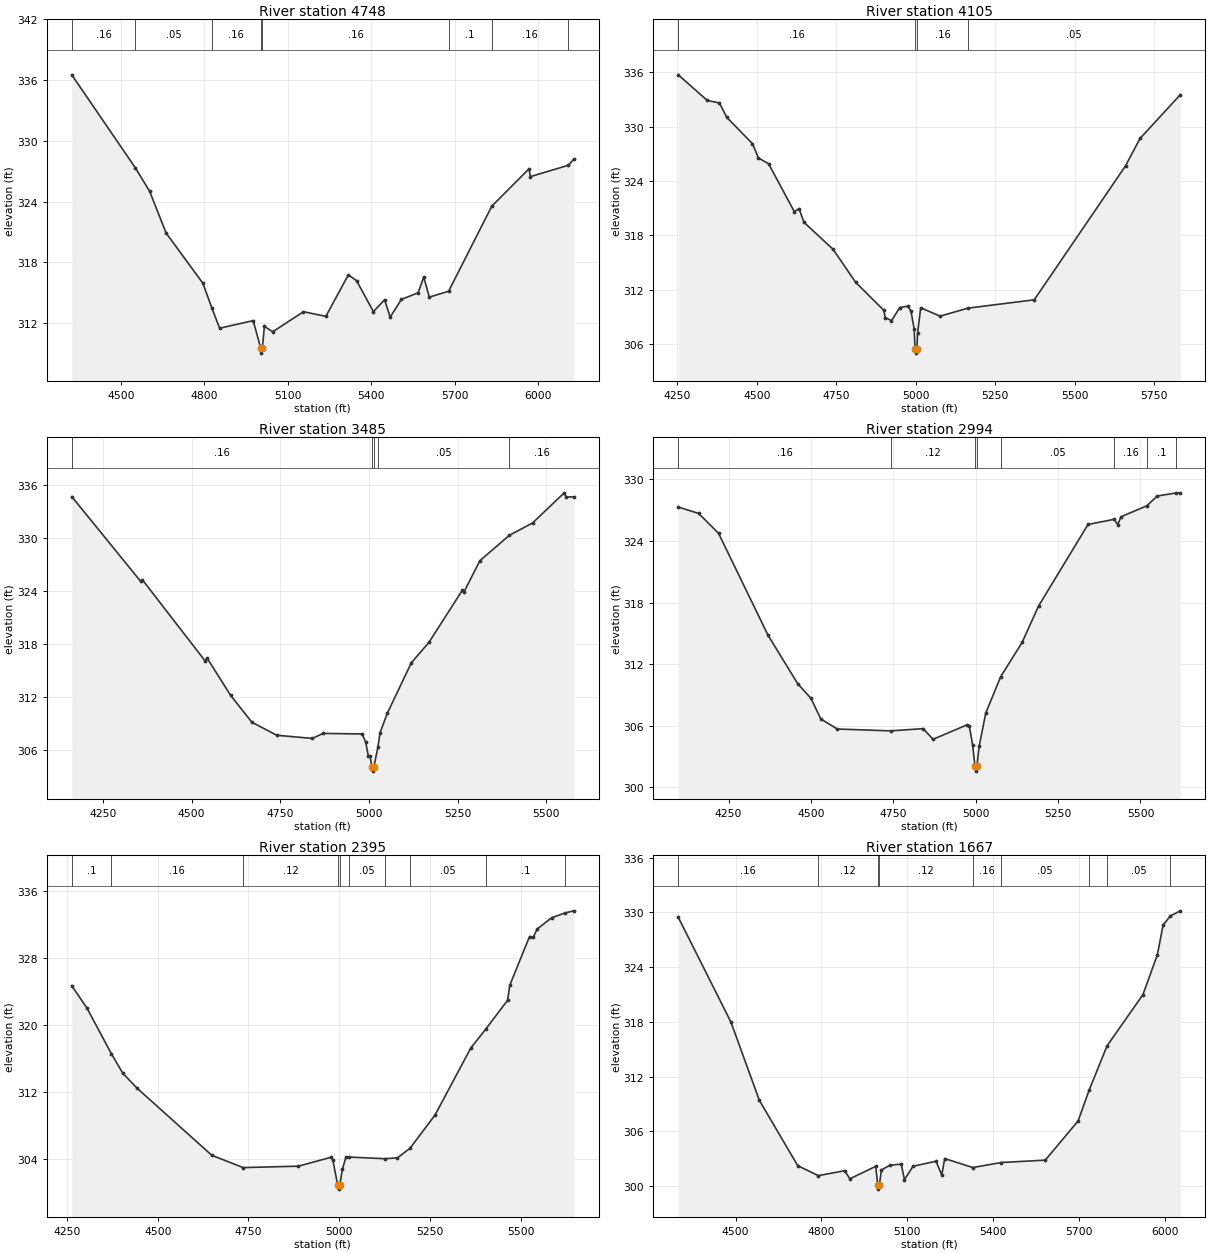
Type RM Length L Ch R = 1,4748,643,643,643
BEGIN DESCRIPTION:
CEDAR CREEK TRIBUTARY 16 10.0
END DESCRIPTION:
XS GIS Cut Line= 3
      3554410.58     10314003.27      3553924.50     10314050.84
      3552615.23     10314171.23
#Sta/Elev= 30
  4323.9  336.52  4552.4  327.33  4603.7  325.01  4662.7  320.90  4794.6  315.95
  4827.0  313.50  4854.9  311.50  4975.4  312.25  5002.5  309.54  5005.3  309.04
  5008.5  309.54  5015.6  311.68  5045.7  311.15  5156.1  313.13  5236.5  312.67
  5317.2  316.77  5346.9  316.19  5407.2  313.14  5447.4  314.31  5467.4  312.59
  5507.6  314.34  5567.9  315.00  5588.0  316.56  5608.0  314.57  5677.3  315.15
  5832.4  323.55  5966.1  327.24  5971.2  326.47  6107.6  327.59  6127.1  328.20
#Mann=8,-1,0
  4323.9    0.16       0  4552.4    0.05       0  4827.0    0.16       0
  5002.5    0.07       0  5008.5    0.16       0  5677.3     0.1       0
  5832.4    0.16       0  6107.6    0.05       0
Bank Sta=5002.5,5008.5
Exp/Cntr=0.3,0.1

Type RM Length L Ch R = 1,4105,620,620,620
BEGIN DESCRIPTION:
CEDAR CREEK TRIBUTARY 16 9.0
END DESCRIPTION:
XS GIS Cut Line= 3
      3554542.39     10313395.30      3554082.73     10313470.65
      3552992.09     10313691.65
#Sta/Elev= 30
  4253.1  335.71  4344.6  332.88  4382.5  332.61  4405.4  331.03  4486.5  328.12
  4505.2  326.54  4537.1  325.91  4618.2  320.61  4632.8  320.96  4648.6  319.44
  4739.9  316.47  4811.4  312.81  4899.1  309.76  4904.2  308.94  4923.6  308.60
  4949.8  310.05  4974.6  310.20  4984.8  309.68  4995.0  307.66  4997.5  305.52
  5000.2  305.02  5003.5  305.52  5005.6  307.21  5015.4  310.02  5076.6  309.10
  5164.0  309.98  5372.5  310.90  5659.4  325.67  5705.0  328.69  5831.7  333.52
#Mann=4,-1,0
  4253.1    0.16       0  4997.5    0.07       0  5003.5    0.16       0
  5164.0    0.05       0
Bank Sta=4997.5,5003.5
Exp/Cntr=0.3,0.1

Type RM Length L Ch R = 1,3485,491,491,491
BEGIN DESCRIPTION:
CEDAR CREEK TRIBUTARY 16 7.0
END DESCRIPTION:
XS GIS Cut Line= 3
      3554429.34     10312995.95      3553592.11     10313041.64
      3553027.82     10313161.73
#Sta/Elev= 30
  4162.1  334.70  4356.4  325.08  4361.4  325.25  4538.3  316.04  4543.3  316.40
  4610.0  312.14  4670.1  309.09  4740.2  307.62  4840.3  307.26  4870.4  307.83
  4980.5  307.77  4990.6  306.88  4998.1  305.27  5003.1  305.27  5007.8  304.05
  5010.6  303.55  5013.8  304.05  5025.2  306.28  5031.2  307.91  5051.7  310.12
  5119.4  315.85  5169.0  318.16  5263.1  324.07  5268.2  323.91  5312.6  327.43
  5395.5  330.30  5461.4  331.72  5550.3  335.13  5555.4  334.67  5577.5  334.66
#Mann=5,-1,0
  4162.1    0.16       0  5007.8    0.07       0  5013.8    0.16       0
  5025.2    0.05       0  5395.5    0.16       0
Bank Sta=5007.8,5013.8
Exp/Cntr=0.3,0.1

Type RM Length L Ch R = 1,2994,599,599,599
BEGIN DESCRIPTION:
CEDAR CREEK TRIBUTARY 16 6.0
END DESCRIPTION:
XS GIS Cut Line= 3
      3554414.22     10312641.81      3553542.11     10312591.64
      3552892.25     10312566.46
#Sta/Elev= 30
  4097.1  327.31  4159.3  326.68  4219.4  324.75  4369.7  314.82  4459.8  310.10
  4499.9  308.68  4529.9  306.67  4580.0  305.69  4742.2  305.51  4840.4  305.73
  4870.5  304.69  4973.2  306.09  4980.7  305.98  4990.7  304.12  4997.7  302.09
  5000.4  301.59  5003.7  302.09  5010.7  304.06  5030.7  307.27  5075.9  310.79
  5140.8  314.12  5190.8  317.67  5340.9  325.61  5420.3  326.11  5431.0  325.59
  5441.0  326.36  5519.0  327.42  5551.1  328.38  5608.7  328.68  5621.0  328.69
#Mann=8,-1,0
  4097.1    0.16       0  4742.2    0.12       0  4997.7    0.07       0
  5003.7    0.12       0  5075.9    0.05       0  5420.3    0.16       0
  5519.0     0.1       0  5608.7    0.16       0
Bank Sta=4997.7,5003.7
Exp/Cntr=0.3,0.1

Type RM Length L Ch R = 1,2395,728,728,728
BEGIN DESCRIPTION:
CEDAR CREEK TRIBUTARY 16 4.0
END DESCRIPTION:
XS GIS Cut Line= 3
      3554342.14     10312291.65      3553965.29     10312162.27
      3552991.33     10312021.65
#Sta/Elev= 30
  4263.4  324.72  4305.0  322.07  4372.4  316.60  4404.1  314.26  4443.2  312.49
  4648.9  304.48  4735.4  303.01  4887.3  303.18  4977.2  304.24  4982.2  303.94
  4995.5  300.94  4998.2  300.44  5001.5  300.94  5008.6  302.83  5018.7  304.29
  5025.9  304.27  5125.1  304.07  5160.1  304.17  5194.6  305.31  5263.6  309.28
  5362.2  317.29  5404.4  319.60  5463.3  322.97  5469.7  324.80  5523.9  330.59
  5534.0  330.51  5545.1  331.49  5584.5  332.83  5621.3  333.40  5645.9  333.66
#Mann=10,-1,0
  4263.4     0.1       0  4372.4    0.16       0  4735.4    0.12       0
  4995.5    0.07       0  5001.5    0.12       0  5025.9    0.05       0
  5125.1    0.16       0  5194.6    0.05       0  5404.4     0.1       0
  5621.3    0.16       0
Bank Sta=4995.5,5001.5
Exp/Cntr=0.3,0.1

Type RM Length L Ch R = 1,1667,542,542,542
BEGIN DESCRIPTION:
CEDAR CREEK TRIBUTARY 16 3.0
END DESCRIPTION:
XS GIS Cut Line= 3
      3554710.05     10312094.54      3554366.33     10311766.44
      3553092.14     10311891.64
#Sta/Elev= 30
  4299.3  329.48  4483.8  317.96  4582.9  309.39  4717.2  302.22  4789.3  301.13
  4881.5  301.67  4899.3  300.78  4989.7  302.15  4996.8  300.15  4999.5  299.65
  5002.8  300.15  5009.8  301.75  5040.0  302.28  5079.2  302.39  5090.2  300.69
  5120.4  302.16  5200.7  302.71  5220.8  301.19  5230.9  303.00  5329.5  302.02
  5429.2  302.57  5582.6  302.83  5697.5  307.13  5736.1  310.52  5798.7  315.37
  5924.2  320.99  5974.5  325.35  5994.6  328.61  6019.7  329.61  6054.8  330.18
#Mann=9,-1,0
  4299.3    0.16       0  4789.3    0.12       0  4996.8    0.07       0
  5002.8    0.12       0  5329.5    0.16       0  5429.2    0.05       0
  5736.1    0.16       0  5798.7    0.05       0  6019.7     0.1       0
Bank Sta=4996.8,5002.8
Exp/Cntr=0.3,0.1

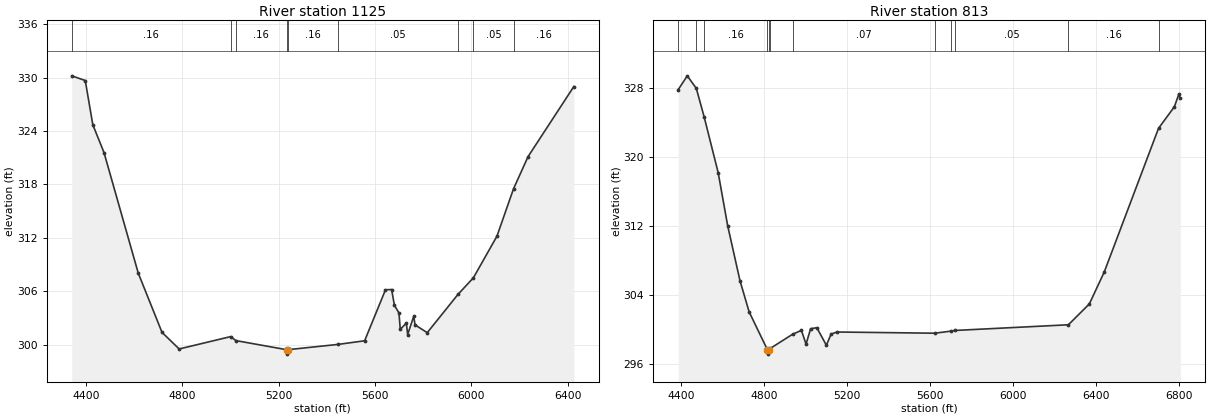
Type RM Length L Ch R = 1,1125,312,312,312
BEGIN DESCRIPTION:
CEDAR CREEK TRIBUTARY 16 2.0
END DESCRIPTION:
XS GIS Cut Line= 3
      3554975.67     10311615.39      3554168.42     10311370.61
      3553001.70     10311792.50
#Sta/Elev= 30
  4340.8  330.20  4396.8  329.67  4428.1  324.71  4474.7  321.57  4616.8  308.03
  4715.5  301.37  4786.6  299.51  5000.6  300.90  5022.1  300.45  5232.2  299.43
  5235.0  298.93  5238.2  299.43  5445.5  300.02  5556.5  300.43  5643.1  306.16
  5668.4  306.19  5680.2  304.42  5699.1  303.55  5704.4  301.72  5729.7  302.41
  5735.1  301.13  5760.4  303.18  5765.7  302.22  5816.4  301.34  5943.7  305.63
  6008.1  307.51  6105.6  312.17  6174.5  317.50  6234.9  321.12  6425.0  329.00
#Mann=9,-1,0
  4340.8    0.16       0  5000.6    0.07       0  5022.1    0.16       0
  5232.2    0.07       0  5238.2    0.16       0  5445.5    0.05       0
  5943.7    0.16       0  6008.1    0.05       0  6174.5    0.16       0
Bank Sta=5232.2,5238.2
Exp/Cntr=0.3,0.1

Type RM Length L Ch R = 1,813,0,0,0
BEGIN DESCRIPTION:
CEDAR CREEK TRIBUTARY 16 1.0
END DESCRIPTION:
XS GIS Cut Line= 3
      3555032.98     10311396.64      3554090.29     10310964.36
      3552942.12     10311741.63
#Sta/Elev= 30
  4385.1  327.82  4428.8  329.42  4472.4  327.96  4510.2  324.65  4577.8  318.18
  4623.8  312.00  4683.1  305.63  4727.1  302.01  4815.8  297.59  4818.5  297.09
  4821.8  297.59  4830.4  297.77  4937.2  299.40  4979.7  299.85  5002.1  298.25
  5024.1  300.04  5054.2  300.16  5100.2  298.12  5123.1  299.42  5151.7  299.66
  5623.1  299.52  5701.0  299.76  5720.8  299.84  6268.6  300.50  6369.8  302.93
  6441.7  306.64  6703.5  323.32  6780.2  325.83  6801.2  327.27  6808.7  326.79
#Mann=12,-1,0
  4385.1    0.05       0  4472.4     0.1       0  4510.2    0.16       0
  4815.8    0.07       0  4821.8    0.16       0  4830.4    0.12       0
  4937.2    0.07       0  5623.1    0.05       0  5701.0    0.16       0
  5720.8    0.05       0  6268.6    0.16       0  6703.5     0.1       0
Bank Sta=4815.8,4821.8
Exp/Cntr=0.3,0.1

Chan Stop Cuts=-1