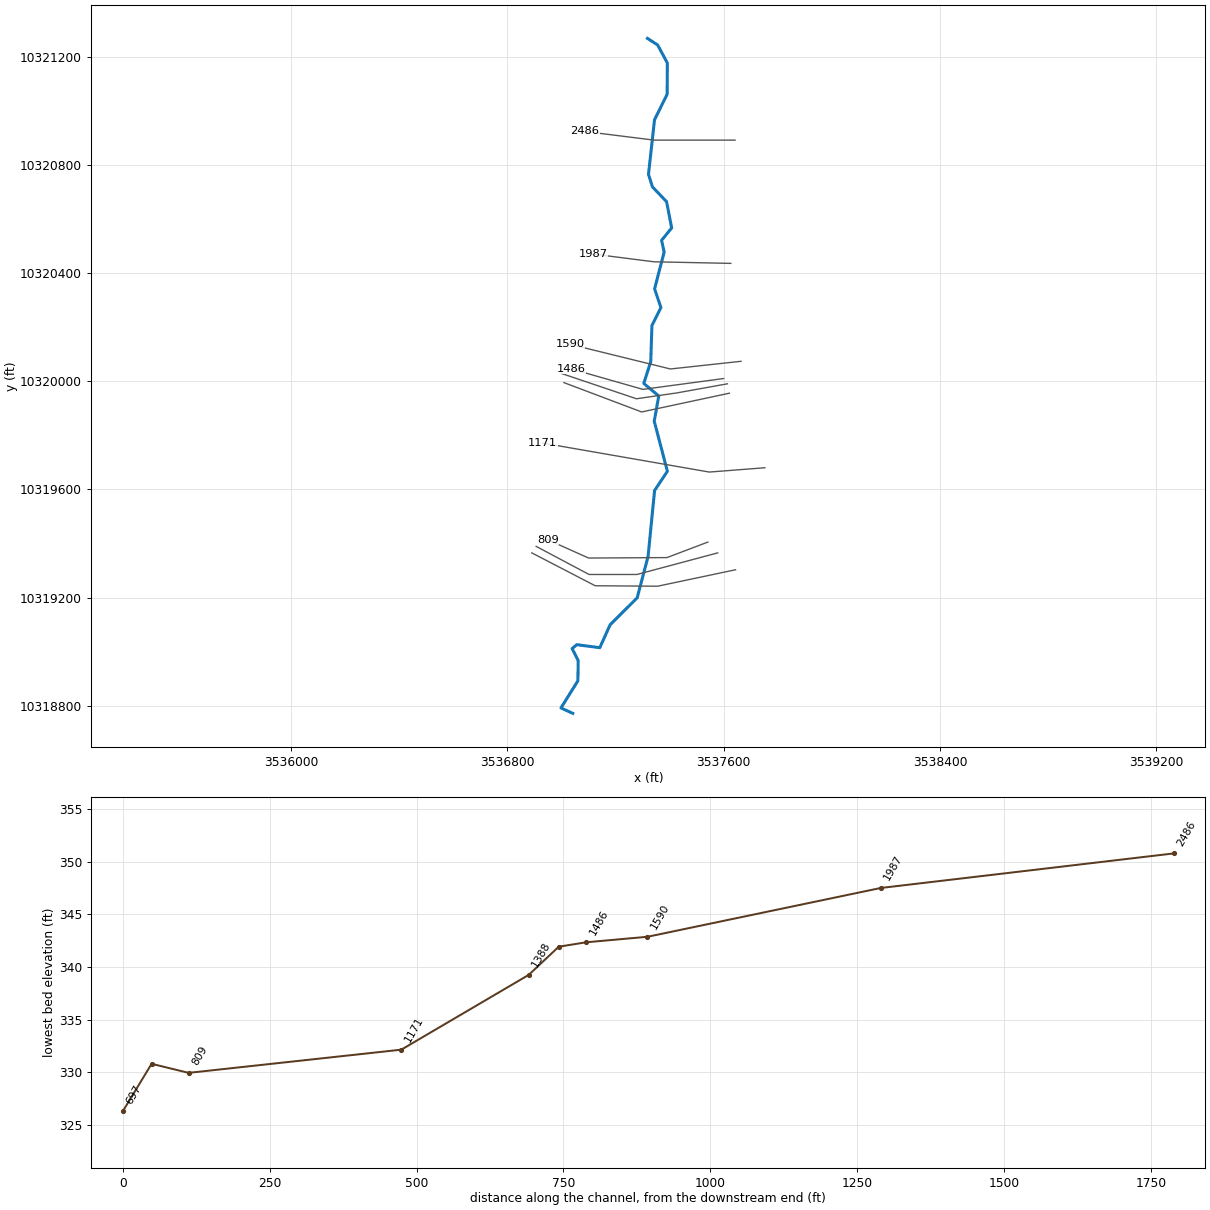
--- CEDAR CREEK TRIBUTARY 2.prj (project) ---

Proj Title=CEDAR CREEK TRIBUTARY 2 Base Level Engineering
Current Plan=p01
Default Exp/Contr=0.3,0.1
English Units
Geom File=g01
Flow File=f01
Plan File=p01
BEGIN DESCRIPTION:
CEDAR CREEK TRIBUTARY 2
END DESCRIPTION:

--- CEDAR CREEK TRIBUTARY 2.p01 (plan) ---

Plan Title=Multiple Run
Short Identifier=Multiple
Geom File=g01
Flow File=f01
Subcritical Flow
K Sum by GR= 0
Std Step Tol= 0.01
Critical Tol= 0.01
Num of Std Step Trials= 20
Max Error Tol= 0.3
Flow Tol Ratio= 0.001
Split Flow NTrial= 30
Split Flow Tol= 0.02
Split Flow Ratio= 0.02
Log Output Level= 0
Friction Slope Method= 1
Unsteady Friction Slope Method= 2
Unsteady Bridges Friction Slope Method= 1
Parabolic Critical Depth
Global Vel Dist=  1 , 1 , 1
Global Log Level= 0
CheckData=True
Encroach Param= -1, 0, 0, 0
BEGIN DESCRIPTION:
Multiple Run
END DESCRIPTION:

--- CEDAR CREEK TRIBUTARY 2.f01 (steady flow) ---

Flow Title=Multiple
Number of Profiles=7
Profile Names=10-year,25-year,50-year,1pct_min,100-year,1pct_plu,500-year
River Rch & RM= CEDAR CREEK TRIB,Reach-1,2486
     305     399     474     414     560     757     782
Boundary for River Rch & Prof#=CEDAR CREEK TRIB,Reach-1,1
Up Type=0
Dn Type=3
Dn Slope=0.005
Boundary for River Rch & Prof#=CEDAR CREEK TRIB,Reach-1,2
Up Type=0
Dn Type=3
Dn Slope=0.005
Boundary for River Rch & Prof#=CEDAR CREEK TRIB,Reach-1,3
Up Type=0
Dn Type=3
Dn Slope=0.005
Boundary for River Rch & Prof#=CEDAR CREEK TRIB,Reach-1,4
Up Type=0
Dn Type=3
Dn Slope=0.005
Boundary for River Rch & Prof#=CEDAR CREEK TRIB,Reach-1,5
Up Type=0
Dn Type=3
Dn Slope=0.005
Boundary for River Rch & Prof#=CEDAR CREEK TRIB,Reach-1,6
Up Type=0
Dn Type=3
Dn Slope=0.005
Boundary for River Rch & Prof#=CEDAR CREEK TRIB,Reach-1,7
Up Type=0
Dn Type=3
Dn Slope=0.005

--- CEDAR CREEK TRIBUTARY 2.g01 (geometry) ---

Geom Title=Existing Conditions

River Reach=CEDAR CREEK TRIB,Reach-1
Reach XY= 30
      3537318.14     10321268.03      3537356.16     10321242.94
      3537391.53     10321176.95      3537391.07     10321061.74
      3537344.12     10320966.36      3537321.89     10320765.02
      3537336.57     10320718.66      3537388.74     10320663.93
      3537407.64     10320567.05      3537370.39     10320521.02
      3537379.81     10320477.59      3537344.50     10320341.61
      3537367.85     10320272.44      3537334.61     10320205.61
      3537330.27     10320072.50      3537304.49     10319991.89
      3537359.85     10319945.40      3537343.19     10319852.18
      3537391.75     10319666.93      3537344.45     10319595.68
      3537320.40     10319352.25      3537280.07     10319198.90
      3537180.08     10319099.54      3537141.89     10319014.47
      3537056.82     10319025.75      3537039.46     10319011.43
      3537061.93     10318966.74      3537060.84     10318892.15
      3536998.21     10318791.75      3537042.11     10318771.64

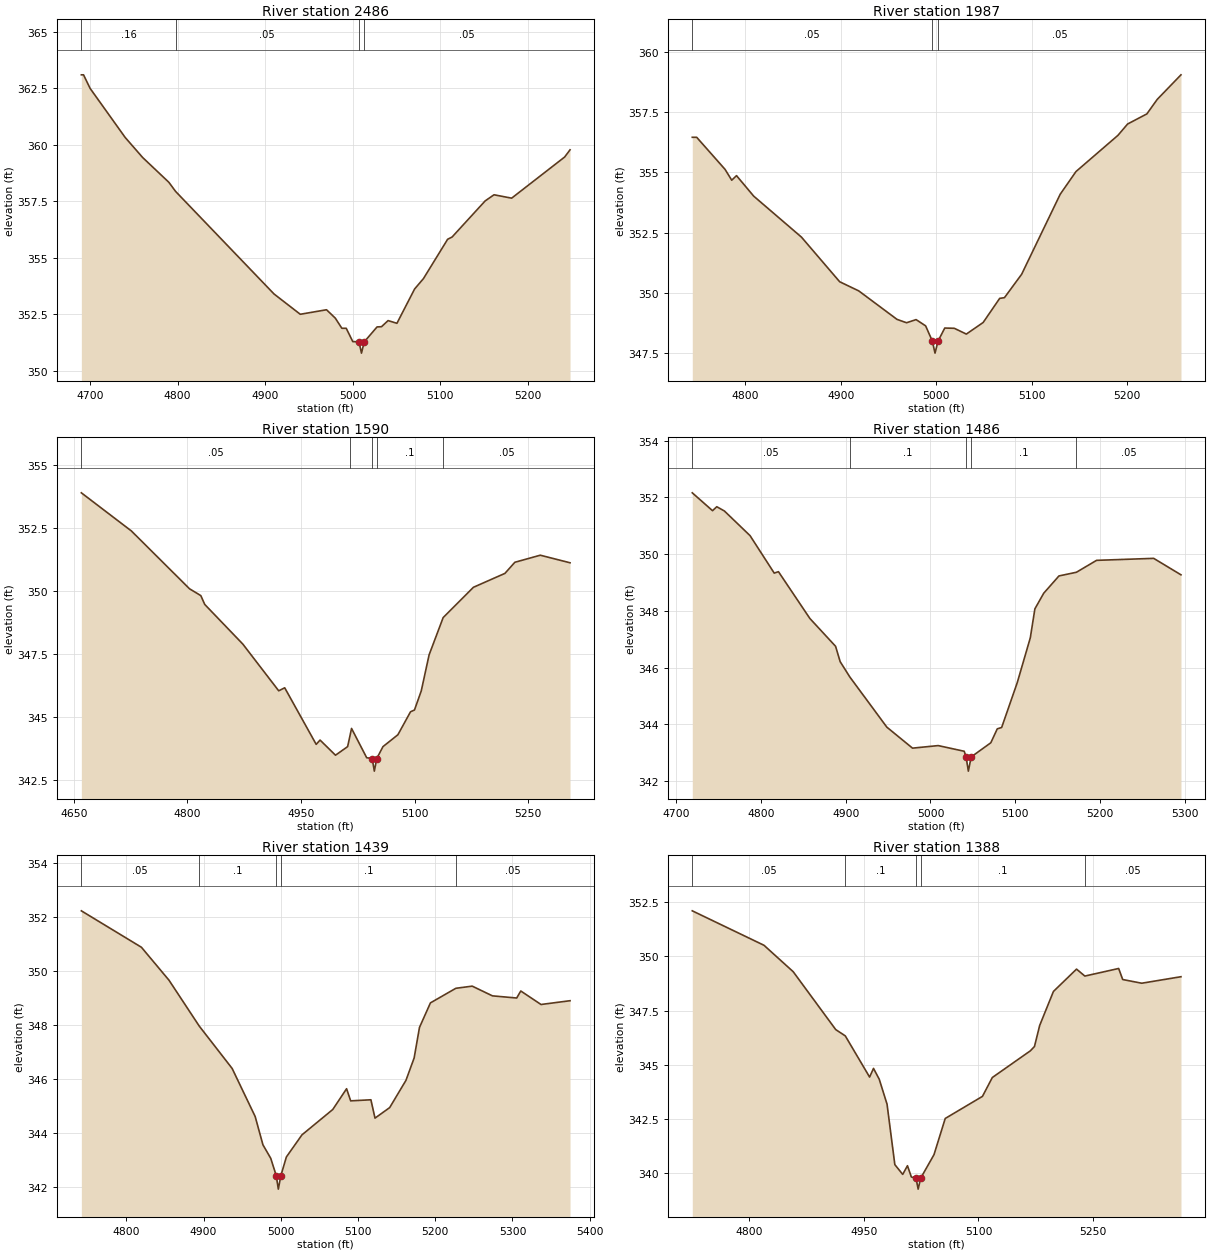
Type RM Length L Ch R = 1,2486,499,499,499
BEGIN DESCRIPTION:
CEDAR CREEK TRIBUTARY 2 5.0
END DESCRIPTION:
XS GIS Cut Line= 3
      3537642.06     10320891.64      3537342.11     10320891.64
      3537085.95     10320923.67
#Sta/Elev= 30
  4690.0  363.10  4692.5  363.10  4700.0  362.50  4740.0  360.33  4760.0  359.44
  4790.0  358.34  4797.6  357.94  4910.0  353.40  4940.0  352.50  4970.0  352.70
  4980.0  352.33  4987.5  351.88  4992.5  351.88  5000.0  351.29  5007.1  351.28
  5009.9  350.78  5013.1  351.28  5027.7  351.94  5032.8  351.95  5040.3  352.22
  5050.4  352.10  5070.6  353.62  5080.7  354.08  5108.3  355.82  5113.4  355.92
  5151.2  357.52  5161.3  357.79  5181.4  357.64  5241.9  359.46  5248.1  359.78
#Mann=4,-1,0
  4690.0    0.16       0  4797.6    0.05       0  5007.1    0.03       0
  5013.1    0.05       0
Bank Sta=5007.1,5013.1
Exp/Cntr=0.3,0.1

Type RM Length L Ch R = 1,1987,397,397,397
BEGIN DESCRIPTION:
CEDAR CREEK TRIBUTARY 2 4.0
END DESCRIPTION:
XS GIS Cut Line= 3
      3537626.39     10320435.75      3537342.11     10320441.64
      3537116.67     10320470.34
#Sta/Elev= 30
  4744.7  356.45  4749.3  356.45  4779.0  355.12  4786.0  354.67  4791.0  354.86
  4809.0  354.01  4859.0  352.31  4899.0  350.46  4919.0  350.08  4959.0  348.90
  4969.0  348.76  4979.0  348.89  4989.0  348.63  4996.0  348.00  4998.8  347.50
  5002.0  348.00  5009.0  348.54  5019.0  348.53  5031.6  348.29  5049.2  348.77
  5066.5  349.77  5071.5  349.80  5089.5  350.77  5129.9  354.09  5146.4  355.03
  5190.3  356.53  5200.4  357.00  5220.6  357.42  5231.4  358.02  5256.3  359.04
#Mann=3,-1,0
  4744.7    0.05       0  4996.0    0.03       0  5002.0    0.05       0
Bank Sta=4996,5002
Exp/Cntr=0.3,0.1

Type RM Length L Ch R = 1,1590,104,104,104
BEGIN DESCRIPTION:
CEDAR CREEK TRIBUTARY 2 3.0
END DESCRIPTION:
XS GIS Cut Line= 3
      3537664.19     10320073.63      3537402.88     10320045.29
      3537031.28     10320136.62
#Sta/Elev= 30
  4659.9  353.89  4726.0  352.38  4802.8  350.09  4817.7  349.82  4822.9  349.47
  4873.2  347.90  4920.6  346.05  4928.5  346.17  4970.1  343.93  4975.2  344.10
  4995.6  343.50  5011.6  343.84  5014.3  344.21  5016.8  344.56  5036.8  343.40
  5044.1  343.37  5046.9  342.87  5050.1  343.37  5058.3  343.84  5078.0  344.31
  5094.7  345.22  5099.9  345.29  5108.9  346.05  5119.2  347.47  5137.8  348.95
  5177.8  350.15  5219.4  350.70  5232.5  351.14  5266.1  351.42  5305.4  351.12
#Mann=5,-1,0
  4659.9    0.05       0  5014.3     0.1       0  5044.1    0.03       0
  5050.1     0.1       0  5137.8    0.05       0
Bank Sta=5044.1,5050.1
Exp/Cntr=0.3,0.1

Type RM Length L Ch R = 1,1486,47,47,47
BEGIN DESCRIPTION:
Mapping XS aeffde97
END DESCRIPTION:
XS GIS Cut Line= 3
      3537599.70     10320009.96      3537301.35     10319969.82
      3537036.30     10320045.55
#Sta/Elev= 30
  4718.9  352.16  4742.8  351.53  4747.8  351.67  4756.8  351.52  4787.1  350.65
  4815.6  349.33  4820.6  349.38  4857.7  347.73  4888.0  346.75  4893.4  346.21
  4904.8  345.67  4948.5  343.90  4978.8  343.16  5009.1  343.25  5039.8  343.05
  5042.0  342.85  5044.7  342.35  5048.0  342.85  5071.2  343.35  5078.8  343.84
  5084.0  343.89  5102.4  345.47  5117.8  347.05  5123.2  348.07  5133.6  348.62
  5151.6  349.23  5172.2  349.36  5196.0  349.78  5263.4  349.85  5295.6  349.27
#Mann=5,-1,0
  4718.9    0.05       0  4904.8     0.1       0  5042.0    0.07       0
  5048.0     0.1       0  5172.2    0.05       0
Bank Sta=5042,5048
Exp/Cntr=0.3,0.1

Type RM Length L Ch R = 1,1439,51,51,51
BEGIN DESCRIPTION:
Mapping XS f9e781dc
END DESCRIPTION:
XS GIS Cut Line= 4
      3537613.81     10319990.43      3537427.21     10319956.80
      3537277.47     10319935.10      3537000.79     10320028.41
#Sta/Elev= 30
  4741.7  352.24  4819.5  350.89  4855.2  349.67  4894.4  347.97  4937.0  346.40
  4966.8  344.62  4976.9  343.57  4987.0  343.07  4994.1  342.43  4996.8  341.93
  5000.1  342.43  5007.2  343.12  5027.4  343.94  5067.3  344.88  5085.2  345.65
  5090.5  345.20  5116.7  345.24  5122.0  344.56  5141.0  344.95  5162.1  345.96
  5172.7  346.79  5179.6  347.92  5193.8  348.83  5226.7  349.37  5247.9  349.45
  5274.1  349.09  5305.5  349.01  5310.8  349.27  5337.0  348.77  5374.6  348.91
#Mann=5,-1,0
  4741.7    0.05       0  4894.4     0.1       0  4994.1    0.07       0
  5000.1     0.1       0  5226.7    0.05       0
Bank Sta=4994.1,5000.1
Exp/Cntr=0.3,0.1

Type RM Length L Ch R = 1,1388,217,217,217
BEGIN DESCRIPTION:
Mapping XS 649f575b
END DESCRIPTION:
XS GIS Cut Line= 3
      3537621.18     10319955.76      3537296.77     10319886.32
      3537009.22     10319994.82
#Sta/Elev= 30
  4725.7  352.10  4819.5  350.51  4857.7  349.29  4913.3  346.62  4925.8  346.33
  4957.6  344.43  4962.7  344.83  4970.2  344.33  4980.4  343.18  4990.6  340.39
  5000.9  339.94  5007.1  340.34  5012.2  339.82  5018.3  339.76  5021.1  339.26
  5024.3  339.76  5041.8  340.85  5056.5  342.52  5105.2  343.54  5118.1  344.41
  5167.8  345.64  5173.2  345.84  5180.0  346.81  5198.0  348.38  5228.2  349.41
  5239.1  349.09  5283.3  349.44  5288.6  348.93  5313.5  348.76  5364.8  349.06
#Mann=5,-1,0
  4725.7    0.05       0  4925.8     0.1       0  5018.3    0.07       0
  5024.3     0.1       0  5239.1    0.05       0
Bank Sta=5018.3,5024.3
Exp/Cntr=0.3,0.1

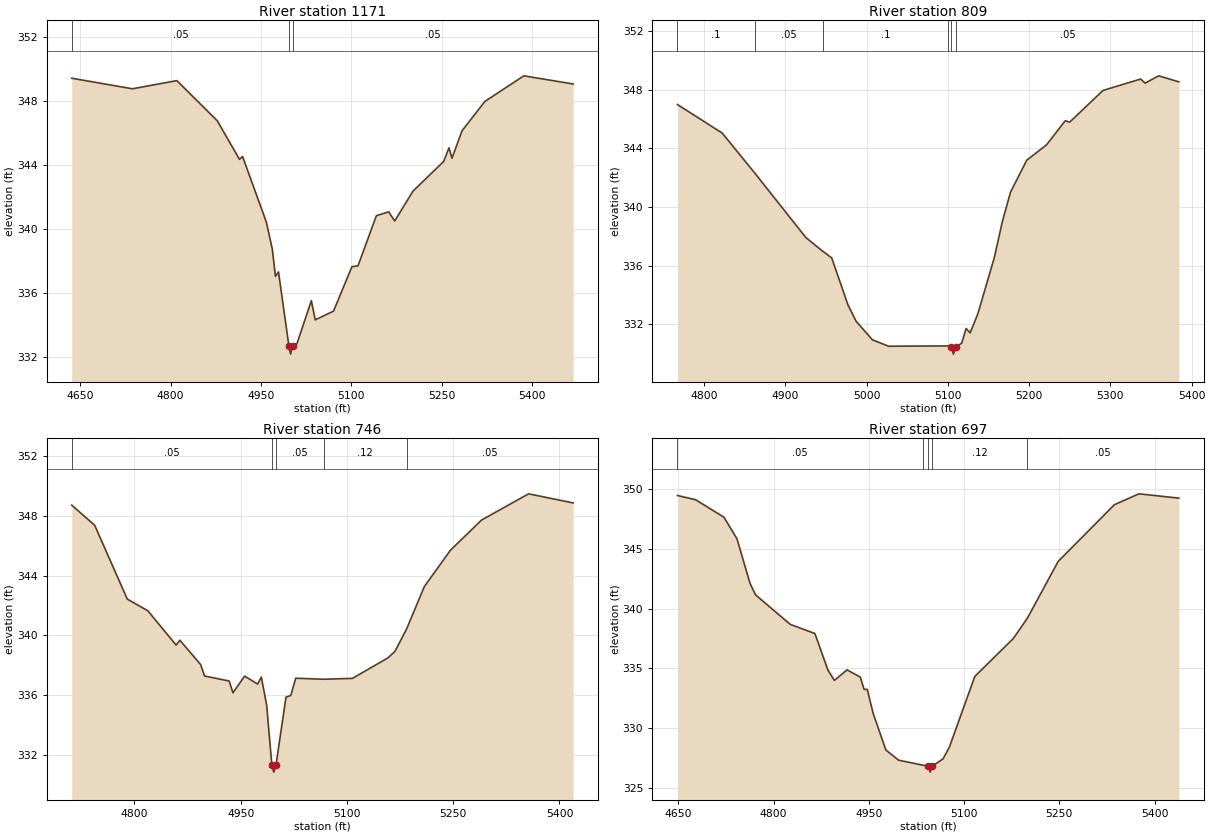
Type RM Length L Ch R = 1,1171,362,362,362
BEGIN DESCRIPTION:
CEDAR CREEK TRIBUTARY 2 2.0
END DESCRIPTION:
XS GIS Cut Line= 3
      3537752.43     10319680.03      3537546.78     10319664.06
      3536930.52     10319771.35
#Sta/Elev= 30
  4636.1  349.40  4736.7  348.74  4810.5  349.25  4877.6  346.74  4914.4  344.33
  4919.5  344.51  4958.8  340.43  4968.9  338.71  4974.0  337.02  4979.1  337.30
  4996.4  332.66  4999.1  332.16  5002.4  332.66  5009.5  332.79  5033.6  335.50
  5040.0  334.30  5070.4  334.85  5100.9  337.62  5111.0  337.68  5141.5  340.81
  5161.8  341.05  5171.9  340.48  5202.3  342.35  5253.1  344.20  5261.9  345.05
  5266.9  344.40  5283.6  346.12  5321.5  347.95  5386.1  349.55  5467.9  349.04
#Mann=3,-1,0
  4636.1    0.05       0  4996.4    0.03       0  5002.4    0.05       0
Bank Sta=4996.4,5002.4
Exp/Cntr=0.3,0.1

Type RM Length L Ch R = 1,809,63,63,63
BEGIN DESCRIPTION:
Mapping XS d6a28f6a
END DESCRIPTION:
XS GIS Cut Line= 4
      3537541.43     10319405.11      3537390.36     10319347.80
      3537100.43     10319346.07      3536949.42     10319413.76
#Sta/Elev= 30
  4767.3  347.00  4822.4  345.05  4862.6  342.31  4925.3  337.92  4946.2  336.98
  4957.1  336.53  4977.1  333.32  4987.1  332.21  5007.1  330.94  5027.1  330.50
  5100.5  330.52  5104.1  330.46  5106.9  329.96  5110.1  330.46  5117.1  330.71
  5122.5  331.71  5127.5  331.41  5137.1  332.74  5157.1  336.53  5167.1  339.01
  5177.1  341.01  5197.1  343.20  5221.3  344.24  5244.5  345.89  5250.0  345.80
  5290.9  347.96  5337.2  348.74  5342.7  348.46  5359.4  348.96  5384.3  348.55
#Mann=6,-1,0
  4767.3     0.1       0  4862.6    0.05       0  4946.2     0.1       0
  5100.5    0.05       0  5104.1    0.07       0  5110.1    0.05       0
Bank Sta=5104.1,5110.1
Exp/Cntr=0.3,0.1

Type RM Length L Ch R = 1,746,49,49,49
BEGIN DESCRIPTION:
Mapping XS df2f6c43
END DESCRIPTION:
XS GIS Cut Line= 4
      3537577.85     10319365.16      3537279.25     10319285.30
      3537102.16     10319285.30      3536906.52     10319389.19
#Sta/Elev= 30
  4711.6  348.73  4744.0  347.38  4790.0  342.43  4818.9  341.65  4859.0  339.34
  4864.2  339.67  4893.5  338.04  4899.1  337.27  4933.9  336.93  4939.1  336.14
  4955.6  337.26  4974.0  336.73  4979.2  337.20  4986.7  335.32  4994.0  331.32
  4996.8  330.82  5000.0  331.32  5014.0  335.85  5020.7  335.96  5027.8  337.12
  5067.1  337.05  5107.8  337.11  5157.8  338.48  5167.8  338.92  5184.1  340.41
  5209.2  343.26  5246.0  345.70  5290.0  347.73  5356.4  349.49  5419.3  348.88
#Mann=5,-1,0
  4711.6    0.05       0  4994.0    0.03       0  5000.0    0.05       0
  5067.1    0.12       0  5184.1    0.05       0
Bank Sta=4994,5000
Exp/Cntr=0.3,0.1

Type RM Length L Ch R = 1,697,0,0,0
BEGIN DESCRIPTION:
CEDAR CREEK TRIBUTARY 2 1.0
END DESCRIPTION:
XS GIS Cut Line= 4
      3537643.81     10319302.75      3537355.63     10319241.90
      3537124.73     10319243.64      3536890.40     10319365.14
#Sta/Elev= 30
  4648.8  349.45  4677.2  349.10  4721.9  347.64  4742.5  345.83  4763.0  342.11
  4771.6  341.15  4826.5  338.67  4865.2  337.91  4885.6  334.86  4895.8  333.99
  4915.8  334.87  4936.7  334.26  4942.6  333.24  4947.6  333.24  4956.9  331.23
  4976.9  328.17  4996.9  327.32  5035.2  326.90  5043.9  326.82  5046.6  326.32
  5049.9  326.82  5066.9  327.43  5076.9  328.41  5116.9  334.32  5177.5  337.49
  5199.7  339.19  5248.2  343.94  5336.7  348.68  5375.3  349.59  5438.2  349.23
#Mann=5,-1,0
  4648.8    0.05       0  5035.2    0.12       0  5043.9    0.03       0
  5049.9    0.12       0  5199.7    0.05       0
Bank Sta=5043.9,5049.9
Exp/Cntr=0.3,0.1

Chan Stop Cuts=-1