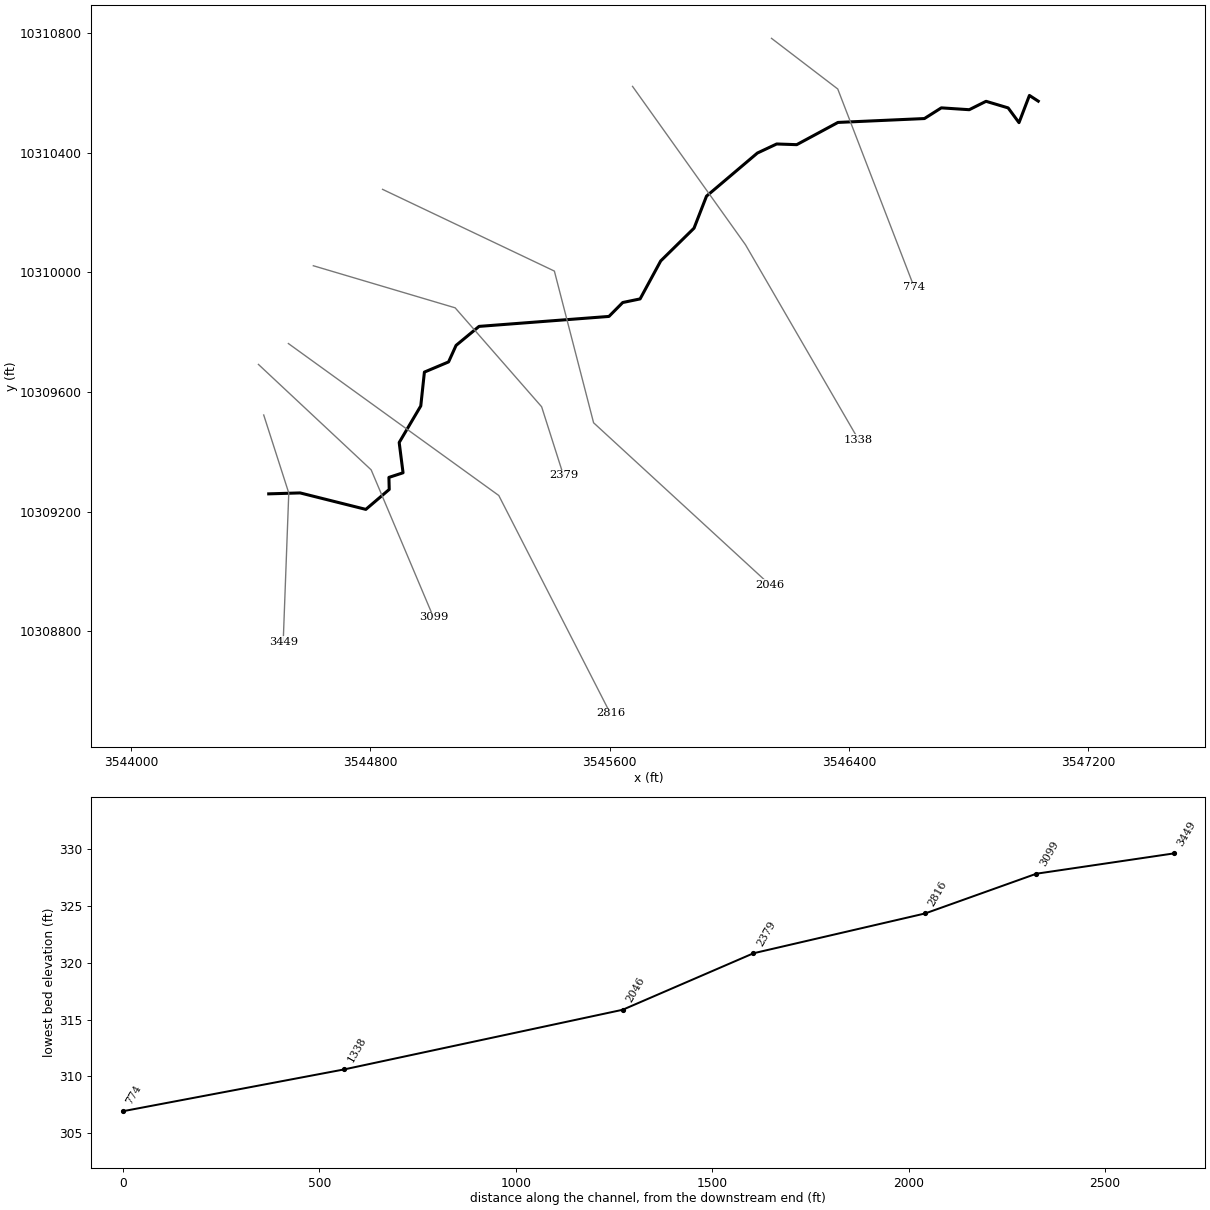
--- CEDAR CREEK TRIBUTARY 21.prj (project) ---

Proj Title=CEDAR CREEK TRIBUTARY 21 Base Level Engineering
Current Plan=p01
Default Exp/Contr=0.3,0.1
English Units
Geom File=g01
Flow File=f01
Plan File=p01
Y Axis Title=Elevation
X Axis Title(PF)=Main Channel Distance
X Axis Title(XS)=Station
BEGIN DESCRIPTION:
CEDAR CREEK TRIBUTARY 21
END DESCRIPTION:
DSS Export Rating Curves= 0
DSS Export Rating Curve Sorted= 0
DSS Export Volume Flow Curves= 0
DXF OffsetX= 0
DXF OffsetY= 0
DXF ScaleX= 1
DXF ScaleY= 10

--- CEDAR CREEK TRIBUTARY 21.p01 (plan) ---

Plan Title=Multiple Run
Short Identifier=Multiple
Geom File=g01
Flow File=f01
Subcritical Flow
K Sum by GR= 0
Std Step Tol= 0.01
Critical Tol= 0.01
Num of Std Step Trials= 20
Max Error Tol= 0.3
Flow Tol Ratio= 0.001
Split Flow NTrial= 30
Split Flow Tol= 0.02
Split Flow Ratio= 0.02
Log Output Level= 0
Friction Slope Method= 1
Unsteady Friction Slope Method= 2
Unsteady Bridges Friction Slope Method= 1
Parabolic Critical Depth
Global Vel Dist=  1 , 1 , 1
Global Log Level= 0
CheckData=True
Encroach Param= -1, 0, 0, 0
BEGIN DESCRIPTION:
Multiple Run
END DESCRIPTION:

--- CEDAR CREEK TRIBUTARY 21.f01 (steady flow) ---

Flow Title=Multiple
Number of Profiles=7
Profile Names=10-year,25-year,50-year,1pct_min,100-year,1pct_plu,500-year
River Rch & RM= CEDAR CREEK TRIB,Reach-1,3449
     149     185     212     179     243     328     317
River Rch & RM= CEDAR CREEK TRIB,Reach-1,1338
     324     425     505     442     597     808     836
Boundary for River Rch & Prof#=CEDAR CREEK TRIB,Reach-1,1
Up Type=0
Dn Type=3
Dn Slope=0.005
Boundary for River Rch & Prof#=CEDAR CREEK TRIB,Reach-1,2
Up Type=0
Dn Type=3
Dn Slope=0.005
Boundary for River Rch & Prof#=CEDAR CREEK TRIB,Reach-1,3
Up Type=0
Dn Type=3
Dn Slope=0.005
Boundary for River Rch & Prof#=CEDAR CREEK TRIB,Reach-1,4
Up Type=0
Dn Type=3
Dn Slope=0.005
Boundary for River Rch & Prof#=CEDAR CREEK TRIB,Reach-1,5
Up Type=0
Dn Type=3
Dn Slope=0.005
Boundary for River Rch & Prof#=CEDAR CREEK TRIB,Reach-1,6
Up Type=0
Dn Type=3
Dn Slope=0.005
Boundary for River Rch & Prof#=CEDAR CREEK TRIB,Reach-1,7
Up Type=0
Dn Type=3
Dn Slope=0.005

--- CEDAR CREEK TRIBUTARY 21.g01 (geometry) ---

Geom Title=Existing Conditions
Program Version=4.10

River Reach=CEDAR CREEK TRIB,Reach-1
Reach XY= 30
      3544460.35     10309259.31      3544565.21     10309262.44
      3544784.93     10309207.42      3544863.06     10309274.04
      3544862.05     10309314.29      3544909.28     10309329.74
      3544896.38      10309430.9      3544968.52     10309553.14
      3544980.64     10309666.24       3545061.4     10309700.25
      3545086.45     10309755.44      3545163.28     10309818.97
      3545597.41     10309852.25      3545643.48     10309898.76
       3545701.5      10309910.8      3545770.34     10310037.68
      3545881.71     10310147.17      3545923.42     10310254.25
      3546093.48     10310398.32      3546157.89     10310428.57
      3546224.91     10310426.29      3546362.69     10310500.58
      3546651.69     10310513.55      3546708.14     10310549.29
      3546801.45     10310543.12      3546857.57     10310571.19
      3546931.47     10310549.14      3546967.77     10310499.83
       3547002.6     10310590.78      3547032.11     10310571.64

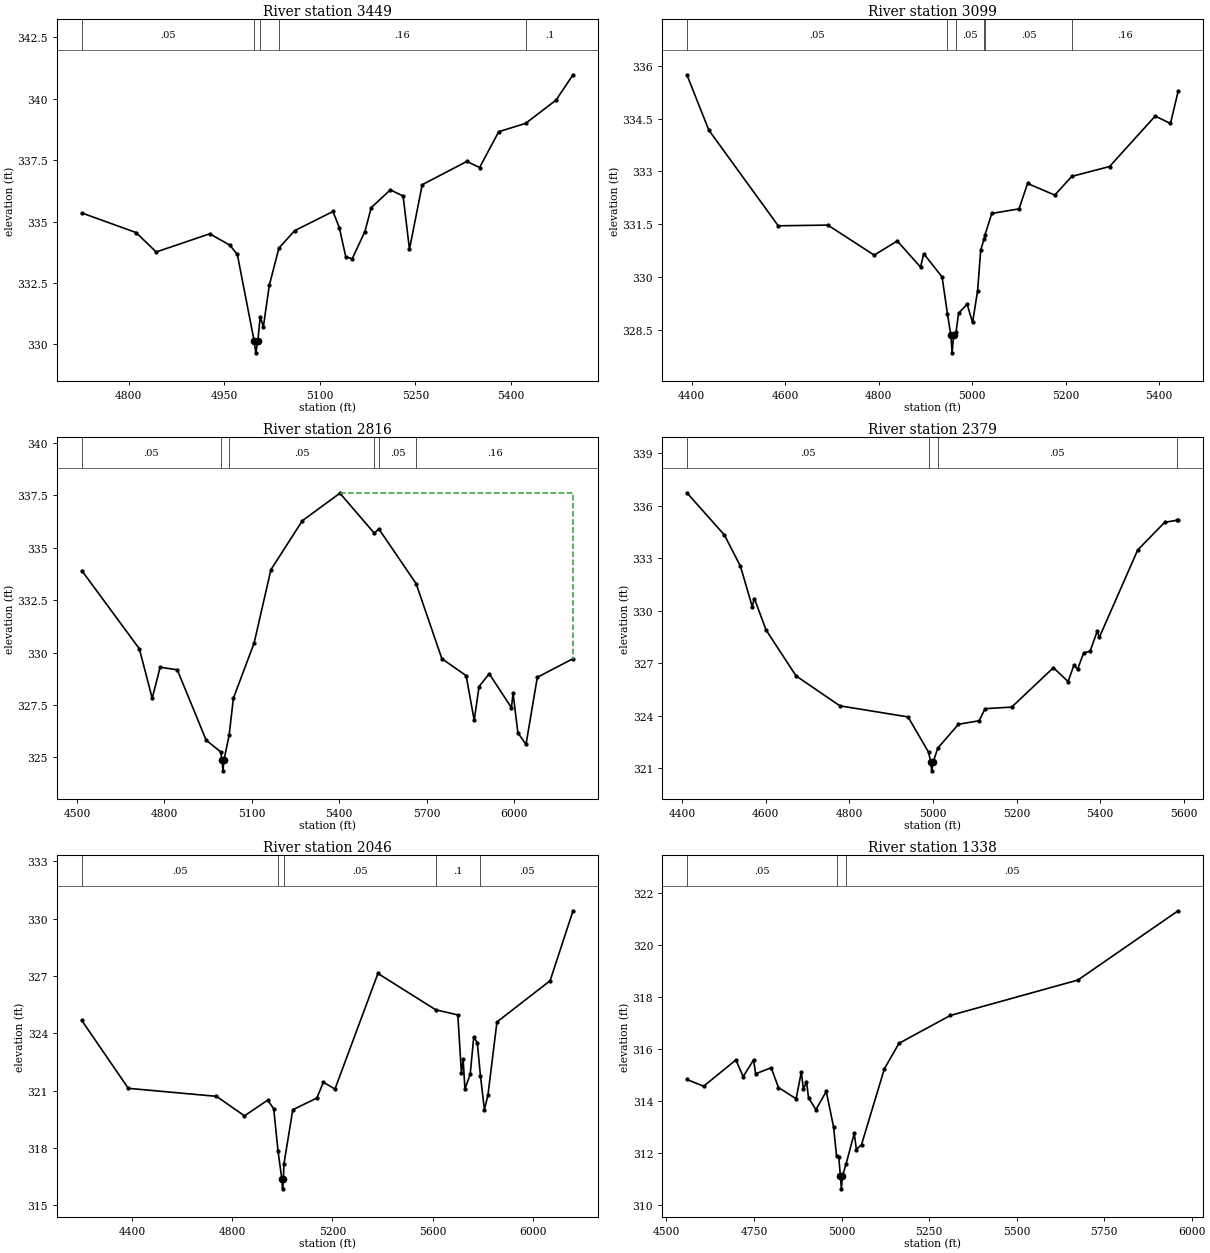
Type RM Length L Ch R = 1 ,3449    ,350,350,350
BEGIN DESCRIPTION:
CEDAR CREEK TRIBUTARY 21 4.0
END DESCRIPTION:
XS GIS Cut Line= 3
      3544443.63     10309522.88      3544527.37     10309262.09
      3544508.78     10308765.04
#Sta/Elev= 30
  4726.1  335.35  4811.4  334.55  4842.9  333.76    4927   334.5  4958.5  334.04
  4970.3  333.66  4996.6  330.15  4999.3  329.65  5002.6  330.15  5006.2  331.13
  5011.2  330.71  5020.5   332.4  5035.6  333.92  5060.5  334.63  5120.5  335.41
  5130.5  334.75  5140.5  333.57  5150.6  333.48  5170.6  334.59  5180.6  335.57
  5210.6  336.29  5230.6  336.04  5240.6  333.87  5260.6   336.5  5330.7  337.45
  5350.7   337.2  5380.7  338.66    5423     339  5470.8  339.95  5497.4  340.98
#Mann= 5 ,-1 , 0
  4726.1     .05       0  4996.6     .03       0  5006.2     .05       0
  5035.6     .16       0    5423      .1       0
Bank Sta=4996.6,5002.6
XS Rating Curve= 0 ,0
Exp/Cntr=0.3,0.1

Type RM Length L Ch R = 1 ,3099    ,283,283,283
BEGIN DESCRIPTION:
Mapping XS bc95cd71
END DESCRIPTION:
XS GIS Cut Line= 3
      3544426.03     10309691.85      3544802.75     10309339.44
      3545011.04     10308846.49
#Sta/Elev= 30
  4389.8  335.74  4436.8  334.17  4585.3  331.46  4691.4  331.48  4790.5  330.63
  4839.9  331.03  4889.7  330.29  4896.5  330.67  4935.8  330.01  4947.3  328.96
  4954.5  328.36  4957.3  327.86  4960.5  328.36  4965.6  328.44    4971  328.98
  4989.3  329.24    5001  328.72  5011.8  329.62  5018.4  330.77  5025.7  331.09
  5027.7  331.21  5042.1  331.81  5100.4  331.94  5118.7  332.66  5176.9  332.33
  5213.2  332.86  5294.1  333.14  5391.8  334.57  5424.4  334.36  5440.8  335.27
#Mann= 6 ,-1 , 0
  4389.8     .05       0  4947.3     .03       0  4965.6     .05       0
  5025.7     .16       0  5027.7     .05       0  5213.2     .16       0
Bank Sta=4954.5,4960.5
XS Rating Curve= 0 ,0
Exp/Cntr=0.3,0.1

Type RM Length L Ch R = 1 ,2816    ,437,437,437
BEGIN DESCRIPTION:
CEDAR CREEK TRIBUTARY 21 3.0
END DESCRIPTION:
XS GIS Cut Line= 3
      3544526.11     10309761.62      3545229.21     10309253.82
      3545601.95     10308525.68
#Sta/Elev= 30
  4516.7  333.91  4714.2  330.18  4758.3  327.82  4785.4   329.3  4844.2  329.18
  4943.5  325.82  4992.8  325.27  4998.2  324.86    5001  324.36  5004.2  324.86
  5022.1  326.05  5036.8  327.82    5108  330.46  5165.5  333.95  5273.5  336.29
  5402.3   337.6  5520.3  335.69  5535.6   335.9  5663.6  333.29    5752  329.71
  5835.2   328.9    5863  326.77  5879.6  328.38  5914.5  328.99  5990.7  327.37
  5996.3  328.06  6012.9  326.17  6040.7  325.62  6079.5  328.82    6202  329.71
#Mann= 6 ,-1 , 0
  4516.7     .05       0  4992.8     .03       0  5022.1     .05       0
  5520.3     .16       0  5535.6     .05       0  5663.6     .16       0
#XS Ineff= 2 , 0
                         5404.36          337.62
Permanent Ineff=
       F       F
Bank Sta=4998.2,5004.2
XS Rating Curve= 0 ,0
Exp/Cntr=0.3,0.1

Type RM Length L Ch R = 1 ,2379    ,333,333,333
BEGIN DESCRIPTION:
Mapping XS ecb7549f
END DESCRIPTION:
XS GIS Cut Line= 4
      3544609.46     10310021.64      3545083.39     10309881.02
      3545372.45     10309550.29      3545445.37     10309321.11
#Sta/Elev= 30
  4411.9  336.73  4501.5  334.32    4540  332.53    4568  330.23  4573.2  330.69
  4601.2  328.89  4672.9  326.27  4777.8  324.56  4940.5  323.93  4989.8   321.9
  4994.4  321.35  4997.2  320.85  5000.4  321.35  5011.7  322.15    5061  323.51
  5110.4  323.71  5124.6   324.4  5188.2  324.49  5287.9  326.74    5323  325.95
  5337.2   326.9  5345.5  326.64  5360.3  327.59  5375.6  327.68  5392.6  328.82
  5397.8  328.48  5489.3  333.46  5553.7  335.04  5582.5  335.16    5586  335.16
#Mann= 4 ,-1 , 0
  4411.9     .05       0  4989.8     .03       0  5011.7     .05       0
  5582.5      .1       0
Bank Sta=4994.4,5000.4
XS Rating Curve= 0 ,0
Exp/Cntr=0.3,0.1

Type RM Length L Ch R = 1 ,2046    ,708,708,708
BEGIN DESCRIPTION:
CEDAR CREEK TRIBUTARY 21 2.1
END DESCRIPTION:
XS GIS Cut Line= 4
      3544840.84     10310276.94        3545415.     10310003.82
      3545546.05     10309496.88      3546135.11     10308955.46
#Sta/Elev= 30
  4200.2  324.68  4385.7  321.13  4737.5  320.71  4849.1  319.69  4941.6  320.51
  4965.8  320.06  4982.9  317.86  4998.3  316.37  5001.1  315.87  5004.3  316.37
  5006.5  317.17  5041.9  320.01  5137.8  320.62  5163.8  321.45  5210.1  321.09
  5381.5  327.14  5611.8  325.24  5700.2  324.97  5714.4  321.94  5721.2  322.66
  5728.6   321.1  5749.6  321.87  5763.7  323.82  5777.9  323.51  5790.3   321.8
  5806.3  320.01  5820.5  320.79  5856.2   324.6  6068.3  326.76  6159.7  330.42
#Mann= 5 ,-1 , 0
  4200.2     .05       0  4982.9     .03       0  5006.5     .05       0
  5611.8      .1       0  5790.3     .05       0
Bank Sta=4998.3,5004.3
XS Rating Curve= 0 ,0
Exp/Cntr=0.3,0.1

Type RM Length L Ch R = 1 ,1338    ,564,564,564
BEGIN DESCRIPTION:
CEDAR CREEK TRIBUTARY 21 2.0
END DESCRIPTION:
XS GIS Cut Line= 3
      3545676.24     10310621.03      3546053.86      10310091.5
      3546431.46     10309440.46
#Sta/Elev= 30
  4558.4  314.82  4606.1  314.56  4698.3  315.57  4719.2  314.93  4748.7  315.57
  4754.8  315.04  4799.1  315.27    4820  314.51  4870.4  314.08  4885.1   315.1
  4891.3  314.44  4899.9  314.74    4906  314.11  4926.9  313.66  4956.4  314.36
  4977.3     313  4985.9  311.88  4992.1  311.84  4996.8  311.12  4999.6  310.62
  5002.8  311.12    5013  311.57  5036.3  312.75  5042.5  312.13  5057.2  312.32
  5122.4  315.23  5164.2  316.21  5310.9  317.28  5675.2  318.64  5961.4   321.3
#Mann= 3 ,-1 , 0
  4558.4     .05       0  4985.9     .03       0    5013     .05       0
Bank Sta=4996.8,5002.8
XS Rating Curve= 0 ,0
Exp/Cntr=0.3,0.1

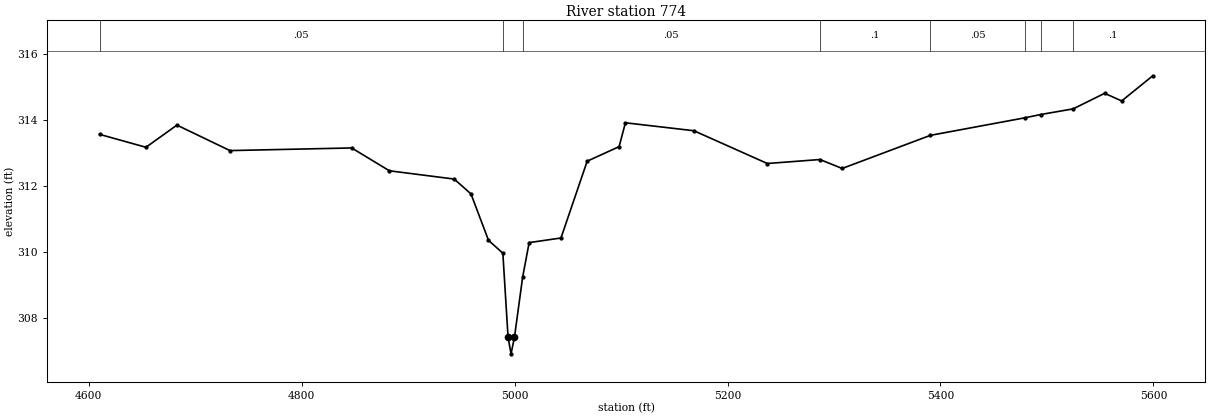
Type RM Length L Ch R = 1 ,774     ,0,0,0
BEGIN DESCRIPTION:
CEDAR CREEK TRIBUTARY 21 1.0
END DESCRIPTION:
XS GIS Cut Line= 3
      3546140.63     10310781.63      3546362.02     10310612.33
      3546617.62     10309949.51
#Sta/Elev= 30
  4610.3  313.56  4653.8  313.17  4682.9  313.84  4732.7  313.07    4847  313.15
  4882.4  312.46  4943.3  312.21  4959.1  311.76  4975.5  310.36    4989  309.97
  4993.9  307.43  4996.7  306.93  4999.9  307.43  5007.6  309.25  5013.7  310.29
  5043.6  310.43  5068.2  312.75  5098.2  313.19  5104.1  313.91  5168.4  313.67
  5237.4  312.68  5286.8   312.8  5307.7  312.53  5390.5  313.53  5479.2  314.06
  5494.2  314.16  5524.6  314.33  5554.2   314.8  5570.2  314.57  5599.4  315.33
#Mann= 8 ,-1 , 0
  4610.3     .05       0    4989     .03       0  5007.6     .05       0
  5286.8      .1       0  5390.5     .05       0  5479.2      .1       0
  5494.2     .05       0  5524.6      .1       0
Bank Sta=4993.9,4999.9
XS Rating Curve= 0 ,0
Exp/Cntr=0.3,0.1

Chan Stop Cuts=-1
Use User Specified Reach Order=0
Composite Channel Slope=5