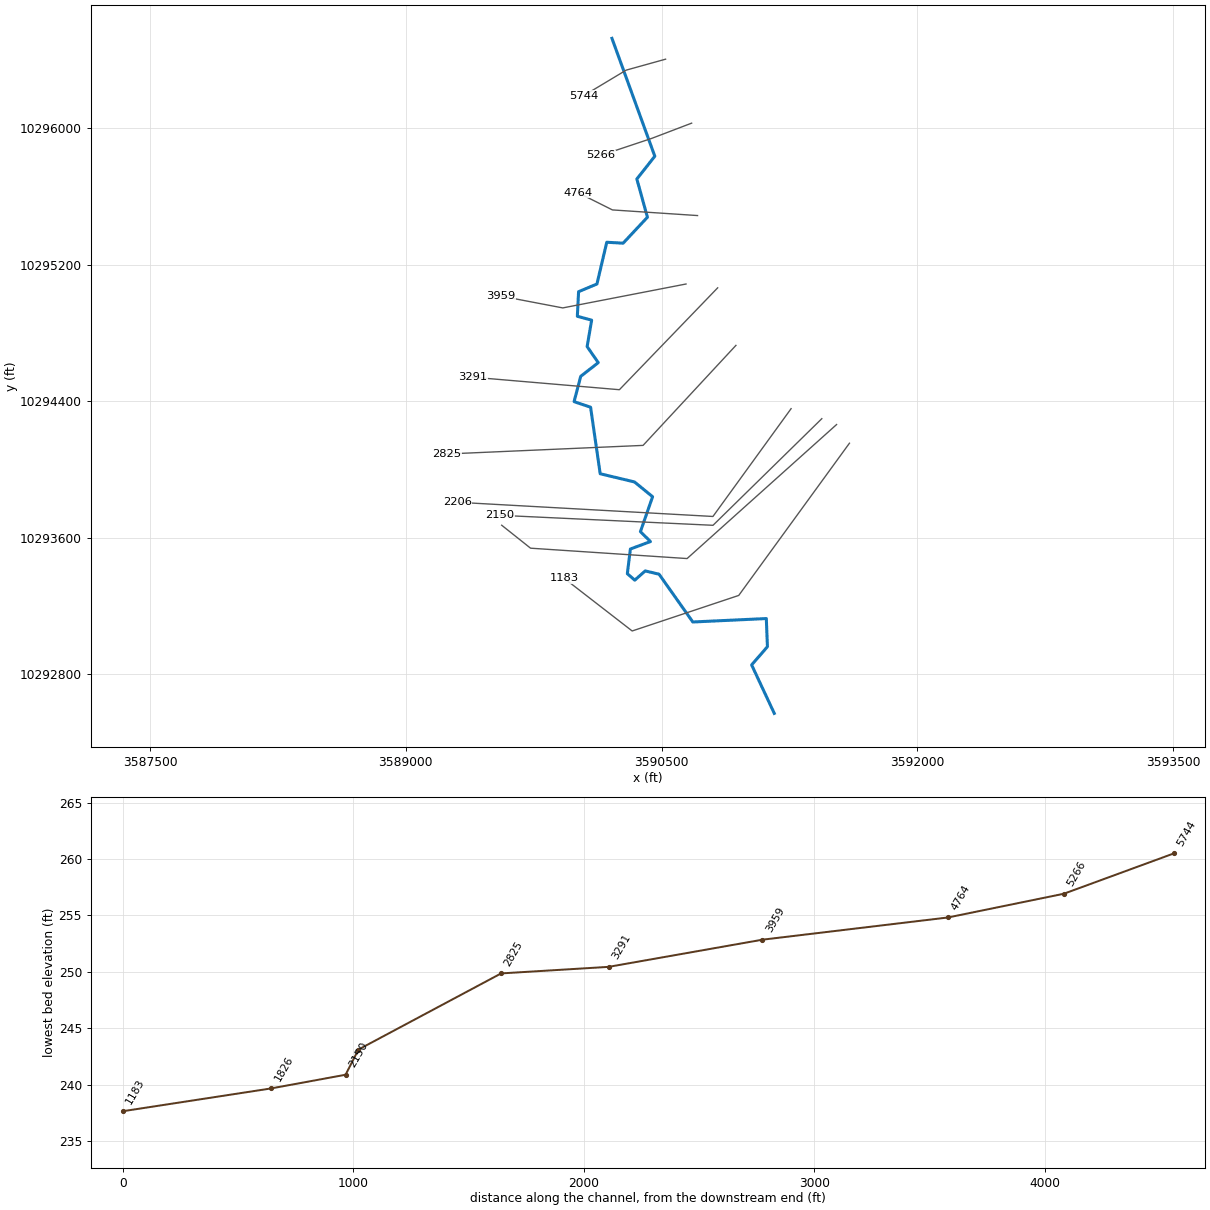
--- CEDAR CREEK TRIBUTARY 4.prj (project) ---

Proj Title=CEDAR CREEK TRIBUTARY 4 Base Level Engineering
Current Plan=p01
Default Exp/Contr=0.3,0.1
English Units
Geom File=g01
Flow File=f01
Plan File=p01
Y Axis Title=Elevation
X Axis Title(PF)=Main Channel Distance
X Axis Title(XS)=Station
BEGIN DESCRIPTION:
CEDAR CREEK TRIBUTARY 4
END DESCRIPTION:
DSS Export Rating Curves= 0
DSS Export Rating Curve Sorted= 0
DSS Export Volume Flow Curves= 0
DXF OffsetX= 0
DXF OffsetY= 0
DXF ScaleX= 1
DXF ScaleY= 10

--- CEDAR CREEK TRIBUTARY 4.p01 (plan) ---

Plan Title=Multiple Run
Short Identifier=Multiple
Geom File=g01
Flow File=f01
Subcritical Flow
K Sum by GR= 0
Std Step Tol= 0.01
Critical Tol= 0.01
Num of Std Step Trials= 20
Max Error Tol= 0.3
Flow Tol Ratio= 0.001
Split Flow NTrial= 30
Split Flow Tol= 0.02
Split Flow Ratio= 0.02
Log Output Level= 0
Friction Slope Method= 1
Unsteady Friction Slope Method= 2
Unsteady Bridges Friction Slope Method= 1
Parabolic Critical Depth
Global Vel Dist=  1 , 1 , 1
Global Log Level= 0
CheckData=True
Encroach Param= -1, 0, 0, 0
BEGIN DESCRIPTION:
Multiple Run
END DESCRIPTION:

--- CEDAR CREEK TRIBUTARY 4.f01 (steady flow) ---

Flow Title=Multiple
Number of Profiles=7
Profile Names=10-year,25-year,50-year,1pct_min,100-year,1pct_plu,500-year
River Rch & RM= CEDAR CREEK TRIB,Reach-1,5744
     649     875    1057     936    1266    1712    1819
Boundary for River Rch & Prof#=CEDAR CREEK TRIB,Reach-1,1
Up Type=0
Dn Type=3
Dn Slope=0.005
Boundary for River Rch & Prof#=CEDAR CREEK TRIB,Reach-1,2
Up Type=0
Dn Type=3
Dn Slope=0.005
Boundary for River Rch & Prof#=CEDAR CREEK TRIB,Reach-1,3
Up Type=0
Dn Type=3
Dn Slope=0.005
Boundary for River Rch & Prof#=CEDAR CREEK TRIB,Reach-1,4
Up Type=0
Dn Type=3
Dn Slope=0.005
Boundary for River Rch & Prof#=CEDAR CREEK TRIB,Reach-1,5
Up Type=0
Dn Type=3
Dn Slope=0.005
Boundary for River Rch & Prof#=CEDAR CREEK TRIB,Reach-1,6
Up Type=0
Dn Type=3
Dn Slope=0.005
Boundary for River Rch & Prof#=CEDAR CREEK TRIB,Reach-1,7
Up Type=0
Dn Type=3
Dn Slope=0.005

--- CEDAR CREEK TRIBUTARY 4.g01 (geometry) ---

Geom Title=Existing Conditions
Program Version=4.10

River Reach=CEDAR CREEK TRIB,Reach-1
Reach XY= 30
      3590208.55     10296528.03      3590460.09     10295836.97
      3590354.69     10295703.33      3590416.73      10295479.3
      3590274.13     10295327.11       3590178.3     10295332.85
      3590120.66     10295087.94        3590013.     10295042.89
      3590005.72     10294898.52      3590089.67     10294876.07
      3590063.09     10294721.21      3590128.38      10294626.9
      3590025.58     10294546.75      3589986.52     10294398.31
      3590083.31     10294365.76      3590139.74     10293975.66
       3590340.5     10293927.74      3590447.06     10293841.18
      3590375.61     10293636.27      3590434.48     10293578.25
      3590316.84     10293534.48      3590298.95     10293389.67
      3590342.52     10293351.86      3590403.79     10293406.08
      3590484.94     10293386.87      3590682.92     10293106.78
      3591114.02     10293126.85      3591120.53     10292961.92
      3591027.88     10292855.12      3591160.71     10292571.05

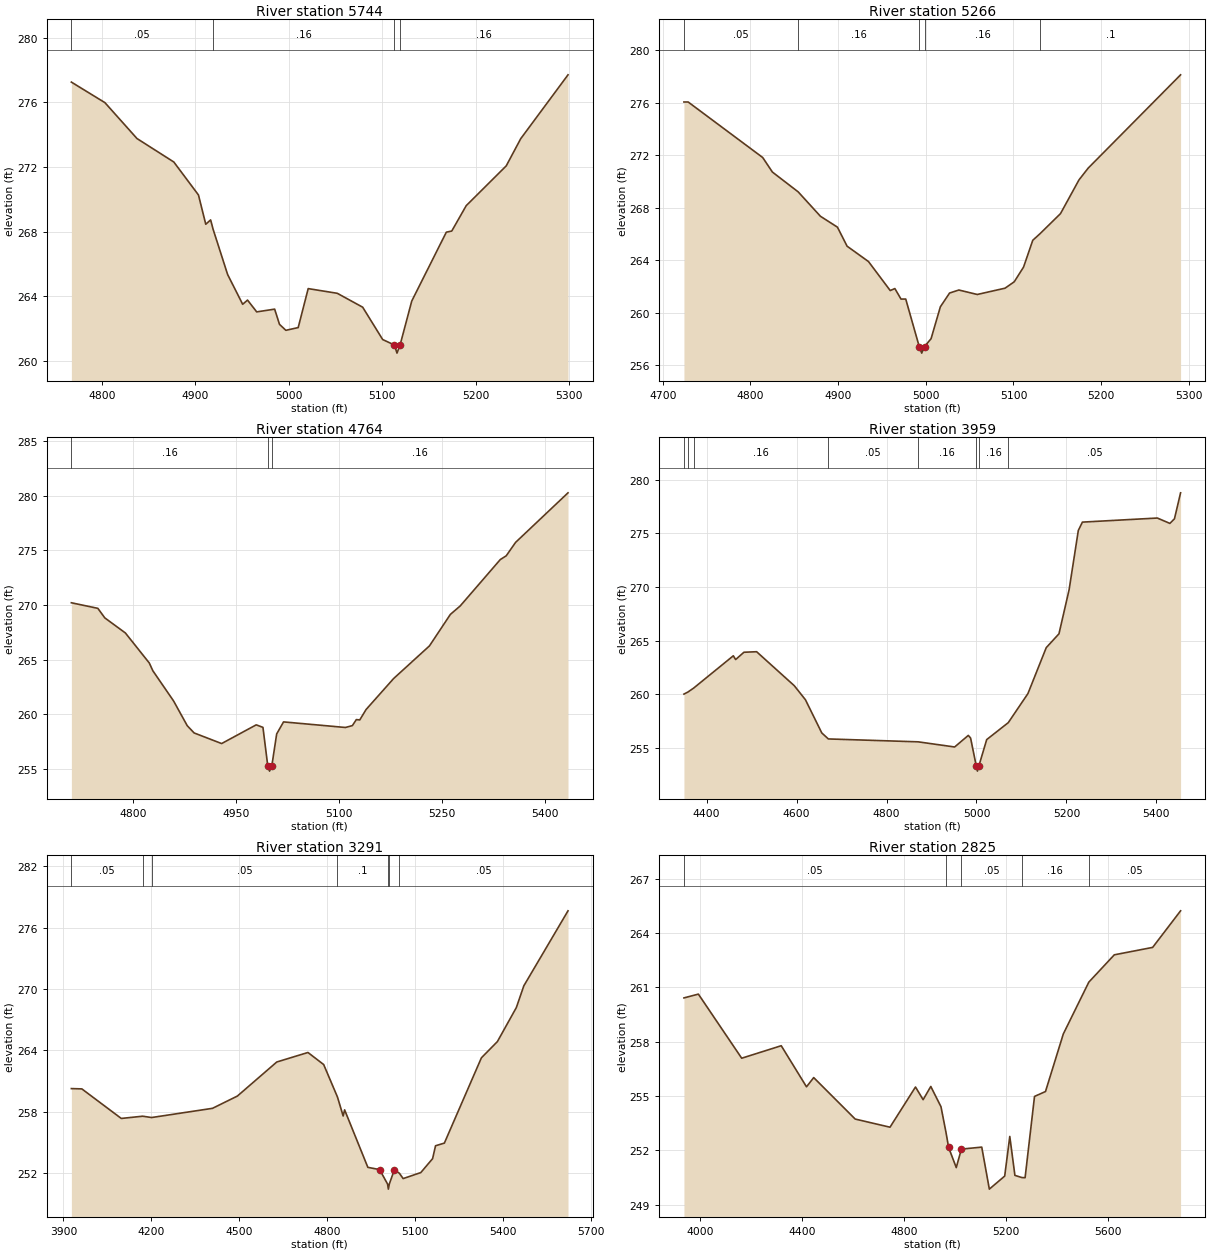
Type RM Length L Ch R = 1 ,5744    ,478,478,478
BEGIN DESCRIPTION:
CEDAR CREEK TRIBUTARY 4 8.0
END DESCRIPTION:
XS GIS Cut Line= 3
      3590523.18     10296405.84      3590292.11     10296341.64
      3590042.09     10296191.63
#Sta/Elev= 30
  4767.3  277.25  4803.2  275.98  4837.5  273.76  4876.9  272.31  4903.3  270.27
  4911.1  268.46  4916.3  268.73  4918.9  268.16  4934.5  265.35  4950.6  263.51
  4955.8  263.77  4965.6  263.04  4984.8  263.21    4990  262.27  4996.8   261.9
    5010  262.07  5020.7  264.48  5051.8  264.19    5079  263.33  5100.4  261.33
    5113  260.99  5115.7  260.49    5119  260.99  5131.5  263.71  5168.5  267.97
  5174.3  268.04  5189.8  269.61  5232.6  272.07  5248.1  273.75  5298.7   277.7
#Mann= 4 ,-1 , 0
  4767.3     .05       0  4918.9     .16       0    5113     .07       0
    5119     .16       0
Bank Sta=5113,5119
XS Rating Curve= 0 ,0
Exp/Cntr=0.3,0.1

Type RM Length L Ch R = 1 ,5266    ,502,502,502
BEGIN DESCRIPTION:
CEDAR CREEK TRIBUTARY 4 7.0
END DESCRIPTION:
XS GIS Cut Line= 3
      3590675.99     10296030.85      3590442.11     10295941.64
      3590142.15     10295841.66
#Sta/Elev= 30
  4724.1  276.05  4728.9  276.05  4813.9  271.82    4825  270.71  4854.4   269.2
  4879.8  267.34  4899.2  266.51  4910.2  265.06  4934.6  263.89  4959.4  261.68
  4964.7  261.83  4971.7  261.03  4977.1  261.03  4992.5  257.41  4995.3  256.91
  4998.5  257.41    5006  258.01  5016.6  260.44  5027.1  261.49  5037.7  261.72
  5058.7  261.38  5090.4  261.86  5100.9  262.35  5111.5  263.47    5122  265.51
  5130.7  266.04  5153.6  267.54  5174.7  270.11  5185.2  271.01  5290.6  278.12
#Mann= 5 ,-1 , 0
  4724.1     .05       0  4854.4     .16       0  4992.5     .07       0
  4998.5     .16       0  5130.7      .1       0
Bank Sta=4992.5,4998.5
XS Rating Curve= 0 ,0
Exp/Cntr=0.3,0.1

Type RM Length L Ch R = 1 ,4764    ,805,805,805
BEGIN DESCRIPTION:
CEDAR CREEK TRIBUTARY 4 6.0
END DESCRIPTION:
XS GIS Cut Line= 3
      3590710.66     10295489.17      3590211.55      10295522.2
      3590011.56     10295622.19
#Sta/Elev= 30
  4710.3   270.2  4748.9  269.69    4759  268.82    4789  267.44  4823.8   264.7
  4829.1  263.98  4859.2  261.23  4879.2  258.96  4889.2   258.3  4929.3  257.33
  4979.7  259.04  4989.5  258.81  4996.5  255.31  4999.2  254.81  5002.5  255.31
  5009.5  258.21  5019.5  259.31  5109.7   258.8  5119.8  258.97  5125.6  259.52
  5130.6  259.49  5139.8  260.44  5179.9  263.27  5232.2  266.26  5262.7  269.14
    5277  269.91  5335.4  274.15    5344  274.49  5357.7  275.72  5434.1  280.25
#Mann= 3 ,-1 , 0
  4710.3     .16       0  4996.5     .07       0  5002.5     .16       0
Bank Sta=4996.5,5002.5
XS Rating Curve= 0 ,0
Exp/Cntr=0.3,0.1

Type RM Length L Ch R = 1 ,3959    ,668,668,668
BEGIN DESCRIPTION:
CEDAR CREEK TRIBUTARY 4 5.0
END DESCRIPTION:
XS GIS Cut Line= 3
      3590643.03     10295087.92      3589920.25      10294947.8
      3589558.71     10295016.79
#Sta/Elev= 30
  4349.6  260.02  4358.4  260.21  4371.2  260.58  4459.4  263.59  4464.5  263.24
    4483  263.92  4511.2  263.97    4595   260.8  4619.8  259.49  4656.1   256.4
  4670.7  255.84  4870.4  255.57  4951.5  255.09  4981.9  256.17    4987  255.92
  4999.5  253.34  5002.2  252.84  5005.5  253.34  5022.8  255.78  5070.8  257.36
  5114.5  260.07  5155.2  264.35  5183.5  265.64  5206.1  269.76  5226.5  275.27
  5235.6  276.05  5402.2  276.43  5430.1  275.93  5440.3  276.36  5453.9  278.78
#Mann= 8 ,-1 , 0
  4349.6     .16       0  4358.4     .05       0  4371.2     .16       0
  4670.7     .05       0  4870.4     .16       0  4999.5     .07       0
  5005.5     .16       0  5070.8     .05       0
Bank Sta=4999.5,5005.5
XS Rating Curve= 0 ,0
Exp/Cntr=0.3,0.1

Type RM Length L Ch R = 1 ,3291    ,466,466,466
BEGIN DESCRIPTION:
CEDAR CREEK TRIBUTARY 4 4.0
END DESCRIPTION:
XS GIS Cut Line= 3
      3590828.73     10295065.56      3590252.34     10294468.34
      3589392.06     10294541.65
#Sta/Elev= 30
  3927.2  260.26  3962.9  260.23  4097.4  257.34  4170.1  257.56  4200.9  257.43
  4408.4  258.33  4493.3  259.53  4627.6  262.86  4733.9  263.79  4787.5  262.61
  4834.6  259.43  4853.9  257.58  4858.9  258.18  4938.1  252.56  4978.2  252.34
  5005.3  250.93  5008.1  250.43  5011.3  250.93  5028.4  252.31  5045.7  251.98
  5058.5  251.46  5118.7  252.05  5158.9  253.41  5168.9  254.67    5199  254.93
  5325.3  263.27  5379.7  264.85  5444.4  268.18    5470  270.31  5620.6  277.64
#Mann= 7 ,-1 , 0
  3927.2     .05       0  4170.1     .16       0  4200.9     .05       0
  4834.6      .1       0  5005.3     .07       0  5011.3      .1       0
  5045.7     .05       0
Bank Sta=4978.2,5028.4
XS Rating Curve= 0 ,0
Exp/Cntr=0.3,0.1

Type RM Length L Ch R = 1 ,2825    ,619,619,619
BEGIN DESCRIPTION:
CEDAR CREEK TRIBUTARY 4 3.0
END DESCRIPTION:
XS GIS Cut Line= 3
      3590935.74     10294728.14      3590391.22     10294141.95
      3589242.09     10294091.64
#Sta/Elev= 30
    3935  260.41  3991.7  260.62  4161.8  257.08  4317.1  257.77  4416.3   255.5
  4444.6  256.01  4607.4  253.72  4744.2  253.27  4844.3  255.49  4874.3  254.79
  4904.4  255.52  4944.4   254.4  4964.4  252.96  4974.4  252.15  5004.4  251.04
  5024.5  252.06  5104.5  252.17  5134.3  249.85  5194.6  250.57  5214.6  252.76
  5234.7  250.61  5261.7  250.49  5274.7  250.48  5311.7  254.97  5354.8  255.24
  5424.8  258.42  5524.9  261.28    5625  262.79  5775.6   263.2  5885.3  265.22
#Mann= 5 ,-1 , 0
    3935     .05       0  4964.4     .03       0  5024.5     .05       0
  5261.7     .16       0  5524.9     .05       0
Bank Sta=4974.4,5024.5
XS Rating Curve= 0 ,0
Exp/Cntr=0.3,0.1

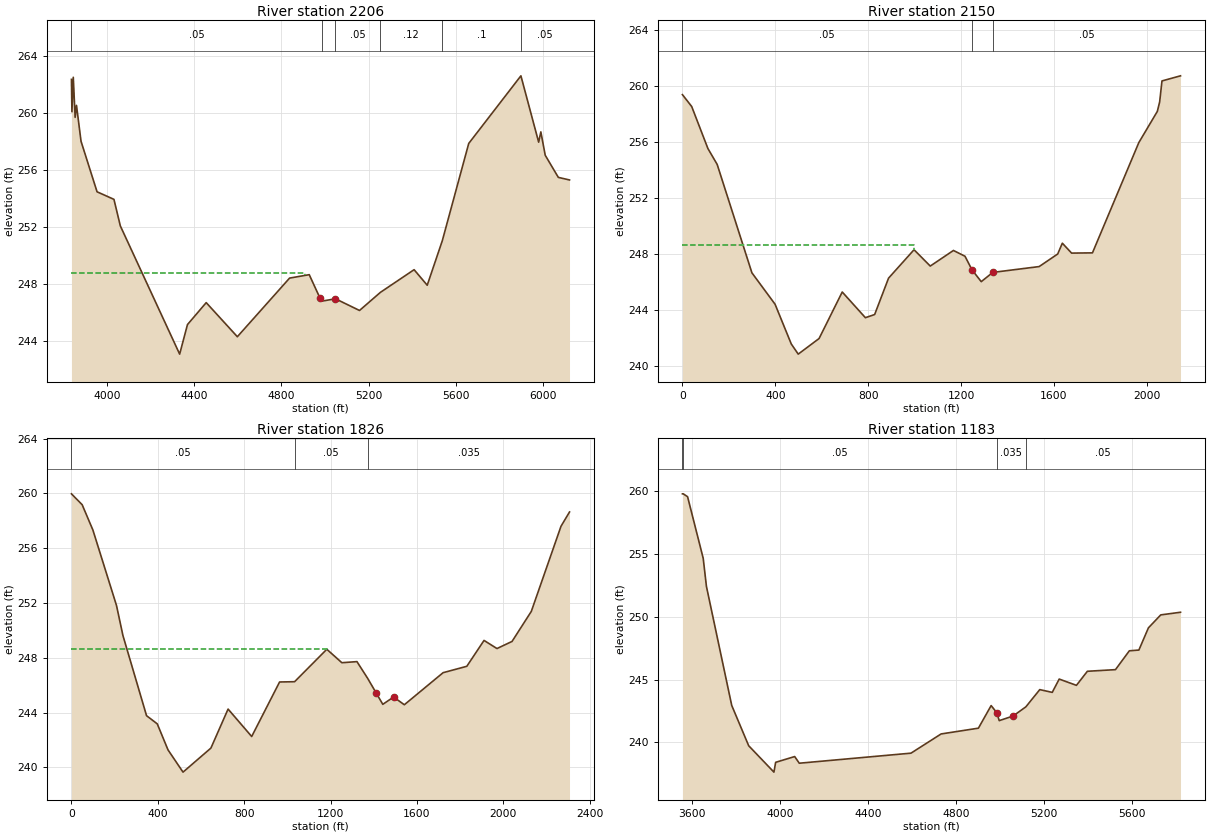
Type RM Length L Ch R = 1 ,2206    ,56,56,56
BEGIN DESCRIPTION:
CEDAR CREEK TRIBUTARY 4 1.0
END DESCRIPTION:
XS GIS Cut Line= 3
       3591259.3     10294357.25      3590800.95     10293725.28
      3589300.95     10293808.61
#Sta/Elev= 30
  3837.7  262.36  3839.9  260.09  3846.1  262.51  3854.6   259.7  3860.8  260.54
  3881.7  258.02  3955.1  254.48  4032.5  253.95  4061.8  252.09  4333.7   243.1
  4369.5  245.17  4455.4  246.71  4598.2  244.32  4837.6  248.43  4927.7  248.67
  4977.8     247  4987.8  246.82  5047.9  246.98  5158.1  246.16  5253.9  247.43
  5408.4  249.02  5468.5  247.93  5537.6  251.05  5658.8  257.87  5897.9  262.61
  5979.3  257.96  5989.3  258.68  6009.4  257.04  6069.5  255.49  6120.7  255.31
#Mann= 6 ,-1 , 0
  3837.7     .05       0  4987.8    .035       0  5047.9     .05       0
  5253.9     .12       0  5537.6      .1       0  5897.9     .05       0
#XS Ineff= 2 , 0
         4906.25  248.82
Permanent Ineff=
       F       F
Bank Sta=4977.8,5047.9
XS Rating Curve= 0 ,0
Exp/Cntr=0.3,0.1

Type RM Length L Ch R = 1 ,2150    ,324,324,324
XS GIS Cut Line= 3
      3591439.44    10294298.533     3590801.419    10293673.533
     3589551.419    10293732.126
#Sta/Elev= 30
       0259.366739.89804258.5191109.7196255.5238149.6177254.3909299.2353246.6617
398.9804244.4214 468.802 241.587498.7255240.8647588.4962241.9768688.2412245.2949
787.9863243.4627827.8844243.6878887.7314246.2815 997.504248.30841067.363247.1429
1167.161248.2563 1217.06247.84281246.999246.87791286.918246.03321336.817246.6917
1536.413247.10751616.252248.00441636.211248.7751 1676.13248.06811765.949248.0848
1965.545255.94462045.383258.17342055.363258.84712065.343260.34432145.181260.7085
#Mann= 3 , 0 , 0
       0     .05       01246.999    .035       01336.817     .05       0
#XS Ineff= 2 , 0
          995.74  248.67
Permanent Ineff=
       F       F
Bank Sta=1246.999,1336.817
XS Rating Curve= 0 ,0
Exp/Cntr=0.3,0.1

Type RM Length L Ch R = 1 ,1826    ,643,643,643
XS GIS Cut Line= 4
     3591526.064    10294264.172     3590649.328    10293478.582
      3589731.36    10293539.346     3589562.089    10293673.894
#Sta/Elev= 30
       0259.967249.67657259.171499.35315257.3247208.6416251.8148238.4476249.6201
 347.736243.7692397.4126243.1715447.0892 241.274516.6364239.6483645.7955 241.404
 725.278244.2521834.5665 242.249963.7256246.22921033.273246.2504 1182.34248.6178
1252.153247.63641321.965247.71671371.831246.48721411.724 245.4091441.644244.5974
 1491.51245.13141541.376244.56791720.894 246.9091830.599247.37511910.385249.2638
1970.224248.67092040.036  249.192129.217251.38272266.819257.60152306.134 258.641
#Mann= 3 ,-1 , 0
       0     .05       01033.273     .05       01371.831    .035       0
#XS Ineff= 2 , 0
         1186.08  248.64 1411.93          245.08
Permanent Ineff=
       F       F
Bank Sta=1411.724,1491.51
XS Rating Curve= 0 ,0
Exp/Cntr=0.3,0.1

Type RM Length L Ch R = 1 ,1183    ,0,0,0
BEGIN DESCRIPTION:
CEDAR CREEK TRIBUTARY 4 1.01
END DESCRIPTION:
XS GIS Cut Line= 4
      3591601.52     10294154.74      3590952.24     10293262.41
      3590327.24     10293054.08      3589927.91     10293363.12
#Sta/Elev= 30
  3555.6  259.79  3559.3  259.79    3579  259.56  3650.1  254.66  3664.8  252.42
    3780  242.94  3857.2  239.73  3972.1  237.63  3979.9  238.41  4066.5  238.87
  4087.5  238.34    4596  239.14  4733.1  240.67  4902.9  241.13  4960.9  242.93
  4986.1  242.37  4997.8  241.73    5061   242.1    5119  242.83  5182.2   244.2
    5239  243.98  5270.7  245.04  5349.1  244.54  5398.9  245.66  5526.8  245.79
    5590  247.29  5633.4  247.35  5676.9  249.12    5733  250.15  5822.9  250.36
#Mann= 4 ,-1 , 0
  3555.6     .05       0  3559.3     .05       0  4986.1    .035       0
    5119     .05       0
Bank Sta=4986.1,5061
XS Rating Curve= 0 ,0
Exp/Cntr=0.3,0.1

Chan Stop Cuts=-1
Use User Specified Reach Order=0
Composite Channel Slope=5