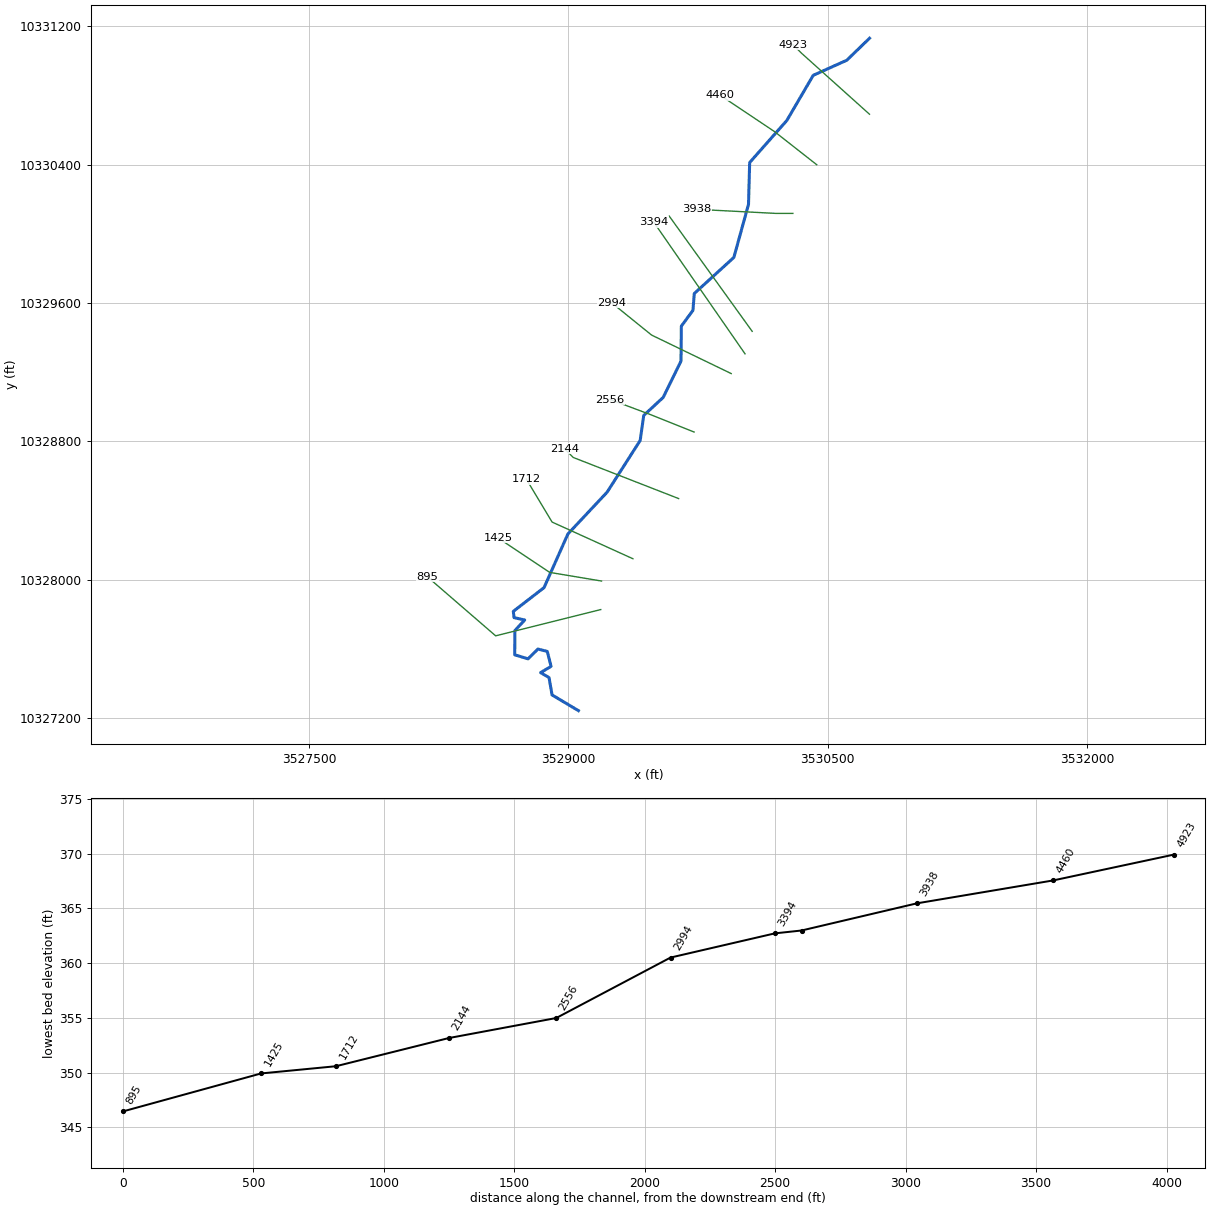
--- CEDAR CREEK TRIBUTARY 7.prj (project) ---

Proj Title=CEDAR CREEK TRIBUTARY 7 Base Level Engineering
Current Plan=p01
Default Exp/Contr=0.3,0.1
English Units
Geom File=g01
Flow File=f01
Plan File=p01
BEGIN DESCRIPTION:
CEDAR CREEK TRIBUTARY 7
END DESCRIPTION:

--- CEDAR CREEK TRIBUTARY 7.p01 (plan) ---

Plan Title=Multiple Run
Short Identifier=Multiple
Geom File=g01
Flow File=f01
Subcritical Flow
K Sum by GR= 0
Std Step Tol= 0.01
Critical Tol= 0.01
Num of Std Step Trials= 20
Max Error Tol= 0.3
Flow Tol Ratio= 0.001
Split Flow NTrial= 30
Split Flow Tol= 0.02
Split Flow Ratio= 0.02
Log Output Level= 0
Friction Slope Method= 1
Unsteady Friction Slope Method= 2
Unsteady Bridges Friction Slope Method= 1
Parabolic Critical Depth
Global Vel Dist=  1 , 1 , 1
Global Log Level= 0
CheckData=True
Encroach Param= -1, 0, 0, 0
BEGIN DESCRIPTION:
Multiple Run
END DESCRIPTION:

--- CEDAR CREEK TRIBUTARY 7.f01 (steady flow) ---

Flow Title=Multiple
Number of Profiles=7
Profile Names=10-year,25-year,50-year,1pct_min,100-year,1pct_plu,500-year
River Rch & RM= CEDAR CREEK TRIB,Reach-1,4923
     511     693     843     753    1018    1377    1488
Boundary for River Rch & Prof#=CEDAR CREEK TRIB,Reach-1,1
Up Type=0
Dn Type=3
Dn Slope=0.005
Boundary for River Rch & Prof#=CEDAR CREEK TRIB,Reach-1,2
Up Type=0
Dn Type=3
Dn Slope=0.005
Boundary for River Rch & Prof#=CEDAR CREEK TRIB,Reach-1,3
Up Type=0
Dn Type=3
Dn Slope=0.005
Boundary for River Rch & Prof#=CEDAR CREEK TRIB,Reach-1,4
Up Type=0
Dn Type=3
Dn Slope=0.005
Boundary for River Rch & Prof#=CEDAR CREEK TRIB,Reach-1,5
Up Type=0
Dn Type=3
Dn Slope=0.005
Boundary for River Rch & Prof#=CEDAR CREEK TRIB,Reach-1,6
Up Type=0
Dn Type=3
Dn Slope=0.005
Boundary for River Rch & Prof#=CEDAR CREEK TRIB,Reach-1,7
Up Type=0
Dn Type=3
Dn Slope=0.005

--- CEDAR CREEK TRIBUTARY 7.g01 (geometry) ---

Geom Title=Existing Conditions

River Reach=CEDAR CREEK TRIB,Reach-1
Reach XY= 30
      3530742.46     10331131.38      3530611.10     10331004.10
      3530416.58     10330916.68      3530263.92     10330655.48
      3530048.94     10330412.31      3530042.25     10330170.58
      3529957.65     10329863.52      3529728.62     10329654.74
      3529720.72     10329557.40      3529653.74     10329465.91
      3529651.71     10329264.01      3529548.68     10329053.68
      3529436.09     10328949.43      3529415.70     10328804.86
      3529224.06     10328505.45      3528997.57     10328263.99
      3528859.35     10327953.47      3528681.59     10327816.19
      3528686.09     10327780.00      3528747.64     10327766.39
      3528690.45     10327704.87      3528690.02     10327564.82
      3528766.80     10327541.67      3528823.99     10327598.28
      3528878.21     10327584.48      3528899.98     10327498.11
      3528839.43     10327461.99      3528888.36     10327433.21
      3528905.72     10327332.94      3529058.42     10327241.86

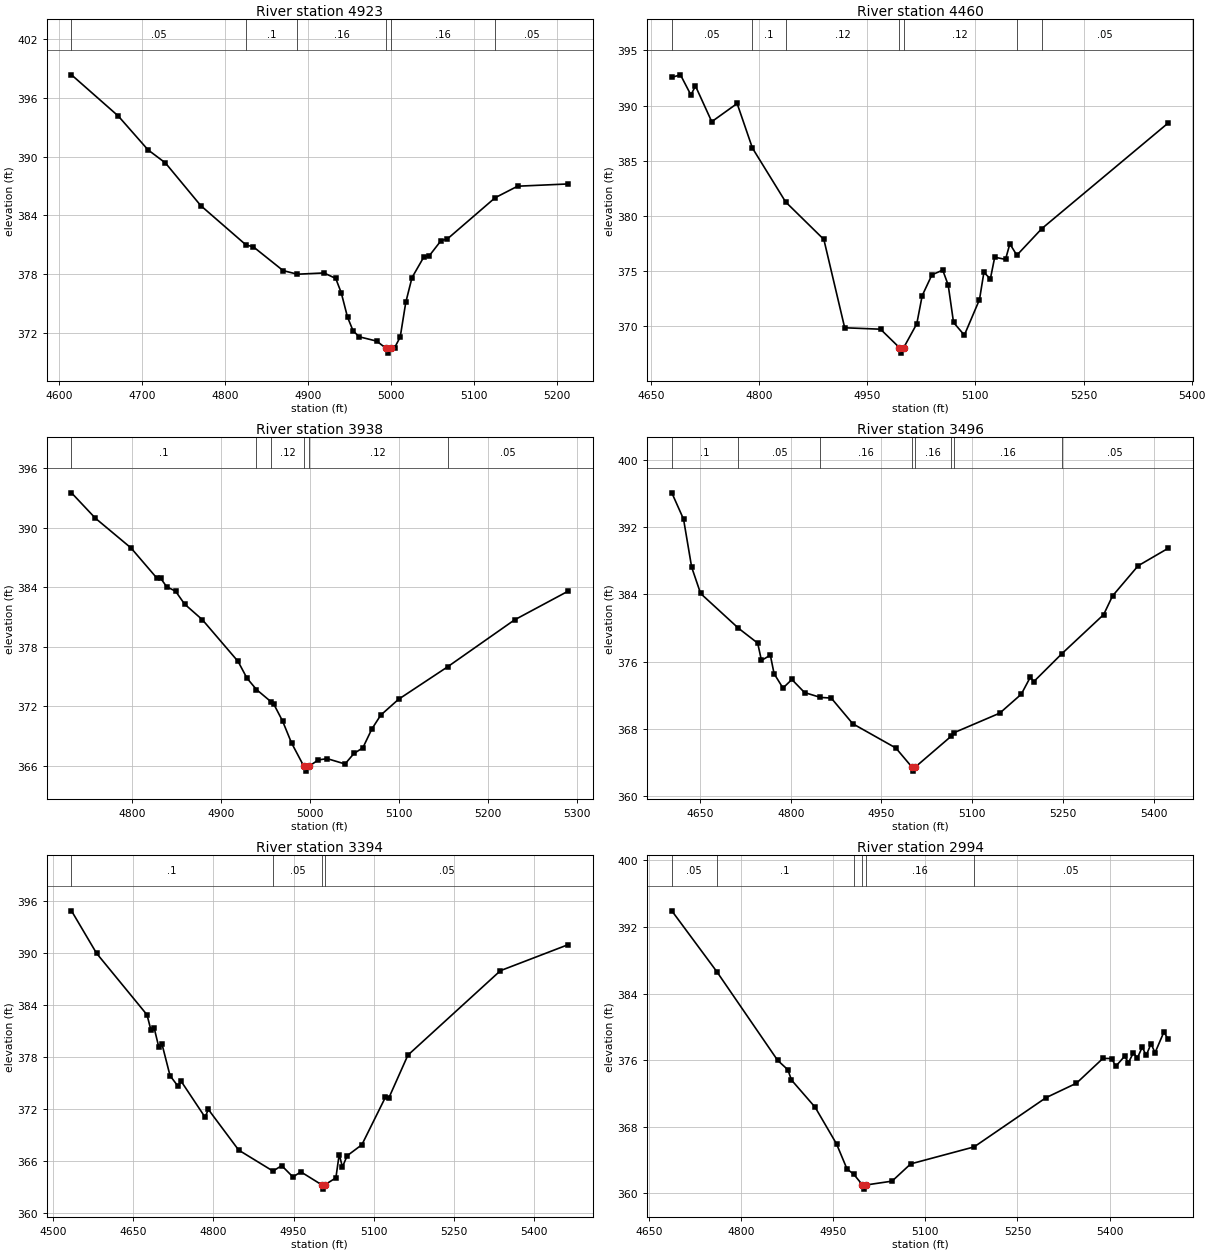
Type RM Length L Ch R = 1,4923,463,463,463
BEGIN DESCRIPTION:
CEDAR CREEK TRIBUTARY 7 10.0
END DESCRIPTION:
XS GIS Cut Line= 3
      3530742.11     10330691.64      3530348.99     10331044.56
      3530298.99     10331094.56
#Sta/Elev= 30
  4614.5  398.37  4670.9  394.16  4706.8  390.70  4727.8  389.36  4770.4  385.00
  4825.1  380.97  4833.9  380.78  4869.8  378.35  4887.0  377.98  4919.1  378.11
  4933.3  377.55  4940.0  376.07  4947.5  373.59  4954.3  372.18  4961.7  371.58
  4982.7  371.14  4993.9  370.41  4996.6  369.91  4999.9  370.41  5004.2  370.44
  5011.1  371.56  5017.8  375.10  5025.3  377.63  5039.5  379.73  5046.2  379.87
  5060.4  381.42  5067.9  381.58  5125.6  385.80  5152.7  386.98  5213.5  387.21
#Mann=6,-1,0
  4614.5    0.05       0  4825.1     0.1       0  4887.0    0.16       0
  4993.9    0.07       0  4999.9    0.16       0  5125.6    0.05       0
Bank Sta=4993.9,4999.9
Exp/Cntr=0.3,0.1

Type RM Length L Ch R = 1,4460,522,522,522
BEGIN DESCRIPTION:
CEDAR CREEK TRIBUTARY 7 9.0
END DESCRIPTION:
XS GIS Cut Line= 3
      3530436.99     10330399.56      3530192.11     10330591.64
      3529878.30     10330801.43
#Sta/Elev= 30
  4678.9  392.56  4690.9  392.79  4705.4  390.96  4711.7  391.78  4734.3  388.54
  4769.5  390.19  4790.7  386.15  4836.8  381.26  4889.8  377.86  4918.7  369.85
  4968.4  369.72  4994.6  368.05  4997.4  367.55  5000.6  368.05  5018.7  370.21
  5026.2  372.76  5039.7  374.65  5054.7  375.08  5062.3  373.72  5069.7  370.33
  5084.7  369.18  5105.7  372.41  5111.8  374.87  5120.8  374.29  5126.8  376.25
  5141.8  376.05  5147.8  377.46  5157.5  376.43  5192.1  378.84  5367.6  388.43
#Mann=7,-1,0
  4678.9    0.05       0  4790.7     0.1       0  4836.8    0.12       0
  4994.6    0.07       0  5000.6    0.12       0  5157.5    0.16       0
  5192.1    0.05       0
Bank Sta=4994.6,5000.6
Exp/Cntr=0.3,0.1

Type RM Length L Ch R = 1,3938,442,442,442
BEGIN DESCRIPTION:
CEDAR CREEK TRIBUTARY 7 8.0
END DESCRIPTION:
XS GIS Cut Line= 3
      3530298.94     10330118.13      3530198.93     10330118.13
      3529742.15     10330141.64
#Sta/Elev= 30
  4732.4  393.54  4759.2  390.98  4799.2  387.98  4828.3  384.93  4832.4  384.93
  4839.2  384.07  4849.3  383.61  4859.3  382.32  4879.3  380.74  4919.4  376.53
  4929.4  374.84  4940.1  373.69  4956.4  372.46  4959.4  372.24  4969.4  370.51
  4979.4  368.31  4993.2  365.96  4996.0  365.46  4999.2  365.96  5009.5  366.59
  5019.5  366.72  5039.5  366.18  5049.5  367.24  5059.5  367.81  5069.6  369.71
  5079.6  371.11  5099.6  372.71  5154.6  375.98  5229.8  380.72  5289.8  383.61
#Mann=6,-1,0
  4732.4     0.1       0  4940.1    0.16       0  4956.4    0.12       0
  4993.2    0.07       0  4999.2    0.12       0  5154.6    0.05       0
Bank Sta=4993.2,4999.2
Exp/Cntr=0.3,0.1

Type RM Length L Ch R = 1,3496,102,102,102
BEGIN DESCRIPTION:
CEDAR CREEK TRIBUTARY 7 7.0
END DESCRIPTION:
XS GIS Cut Line= 2
      3530063.38     10329435.94      3529583.78     10330102.17
#Sta/Elev= 30
  4603.4  396.05  4622.8  392.92  4636.2  387.22  4651.0  384.09  4713.6  379.96
  4745.4  378.19  4751.6  376.13  4766.3  376.76  4772.5  374.56  4787.2  372.85
  4801.9  373.87  4822.8  372.32  4849.1  371.74  4867.0  371.66  4902.6  368.61
  4973.8  365.73  5000.2  363.48  5002.9  362.98  5006.2  363.48  5065.5  367.14
  5069.5  367.53  5145.6  369.87  5181.2  372.12  5195.9  374.11  5202.1  373.63
  5248.4  376.94  5317.4  381.58  5332.1  383.80  5374.4  387.38  5424.3  389.47
#Mann=8,-1,0
  4603.4     0.1       0  4713.6    0.05       0  4849.1    0.16       0
  5000.2    0.07       0  5006.2    0.16       0  5065.5    0.05       0
  5069.5    0.16       0  5248.4    0.05       0
Bank Sta=5000.2,5006.2
Exp/Cntr=0.3,0.1

Type RM Length L Ch R = 1,3394,400,400,400
BEGIN DESCRIPTION:
Mapping XS 4878b031
END DESCRIPTION:
XS GIS Cut Line= 2
      3530022.19     10329305.68      3529493.68     10330068.11
#Sta/Elev= 30
  4535.0  394.81  4581.9  389.91  4676.1  382.82  4683.3  381.09  4689.3  381.35
  4698.1  379.10  4704.2  379.42  4719.1  375.81  4733.9  374.59  4740.0  375.15
  4784.6  371.01  4790.7  371.91  4847.4  367.22  4911.5  364.80  4927.8  365.43
  4948.8  364.12  4963.6  364.71  5002.5  363.22  5005.3  362.72  5008.5  363.22
  5029.0  364.02  5035.2  366.71  5041.3  365.28  5050.1  366.57  5077.6  367.84
  5121.7  373.33  5127.8  373.21  5163.6  378.17  5336.5  387.91  5462.7  390.90
#Mann=4,-1,0
  4535.0     0.1       0  4911.5    0.05       0  5002.5    0.03       0
  5008.5    0.05       0
Bank Sta=5002.5,5008.5
Exp/Cntr=0.3,0.1

Type RM Length L Ch R = 1,2994,438,438,438
BEGIN DESCRIPTION:
CEDAR CREEK TRIBUTARY 7 6.0
END DESCRIPTION:
XS GIS Cut Line= 3
      3529942.10     10329191.65      3529481.29     10329414.51
      3529250.93     10329600.75
#Sta/Elev= 30
  4687.4  393.93  4760.5  386.64  4859.6  375.98  4876.2  374.85  4882.2  373.61
  4920.7  370.34  4955.5  365.94  4972.6  362.92  4983.5  362.30  4997.7  361.01
  5000.5  360.51  5003.7  361.01  5045.9  361.47  5076.2  363.54  5179.4  365.58
  5296.4  371.49  5346.0  373.23  5389.1  376.21  5403.5  376.19  5409.9  375.25
  5424.3  376.46  5430.7  375.71  5438.7  376.89  5445.1  376.25  5453.1  377.57
  5459.5  376.56  5467.4  377.97  5473.9  376.89  5488.3  379.37  5495.5  378.49
#Mann=6,-1,0
  4687.4    0.05       0  4760.5     0.1       0  4983.5    0.16       0
  4997.7    0.07       0  5003.7    0.16       0  5179.4    0.05       0
Bank Sta=4997.7,5003.7
Exp/Cntr=0.3,0.1

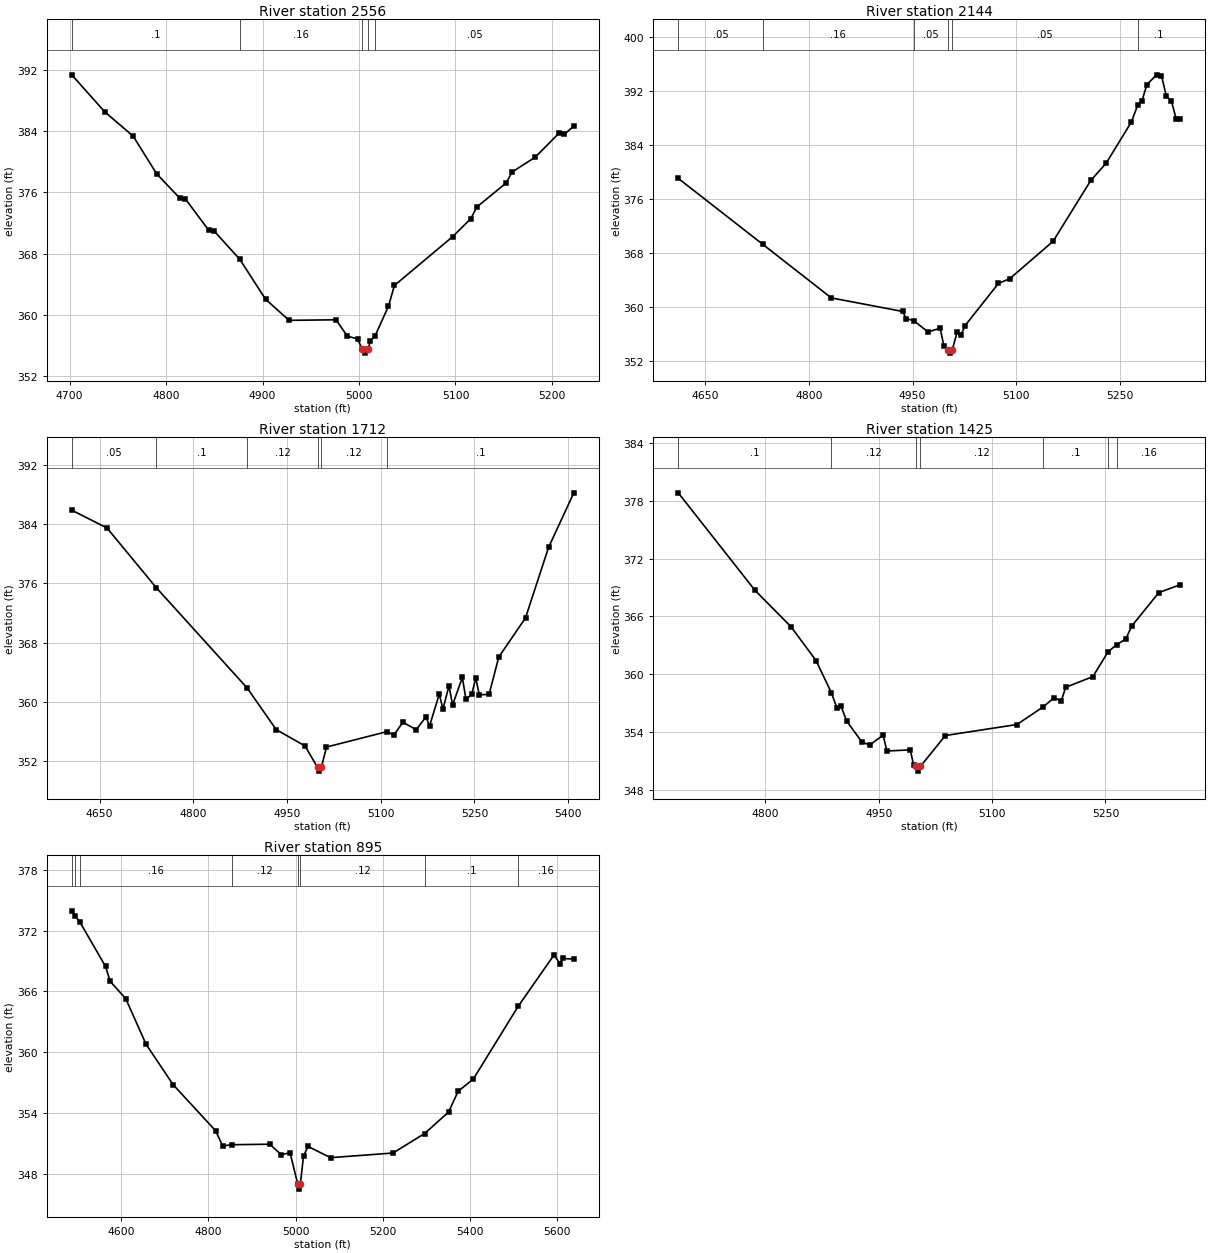
Type RM Length L Ch R = 1,2556,412,412,412
BEGIN DESCRIPTION:
CEDAR CREEK TRIBUTARY 7 5.0
END DESCRIPTION:
XS GIS Cut Line= 3
      3529727.39     10328853.43      3529477.40     10328953.43
      3529242.14     10329041.63
#Sta/Elev= 30
  4702.2  391.39  4736.3  386.56  4765.9  383.36  4790.1  378.46  4814.4  375.23
  4819.8  375.19  4844.0  371.09  4849.4  371.02  4876.5  367.24  4903.2  362.02
  4927.5  359.28  4976.2  359.35  4987.8  357.22  4998.5  356.84  5003.4  355.49
  5006.2  354.99  5009.4  355.49  5011.8  356.59  5016.6  357.24  5030.5  361.12
  5036.7  363.84  5097.2  370.24  5115.9  372.58  5122.2  374.11  5152.4  377.23
  5158.7  378.68  5182.7  380.62  5207.6  383.80  5212.9  383.59  5222.7  384.72
#Mann=5,-1,0
  4702.2     0.1       0  4876.5    0.16       0  5003.4    0.07       0
  5009.4    0.16       0  5016.6    0.05       0
Bank Sta=5003.4,5009.4
Exp/Cntr=0.3,0.1

Type RM Length L Ch R = 1,2144,432,432,432
BEGIN DESCRIPTION:
CEDAR CREEK TRIBUTARY 7 4.0
END DESCRIPTION:
XS GIS Cut Line= 3
      3529638.11     10328468.64      3529028.45     10328706.34
      3528978.43     10328756.36
#Sta/Elev= 30
  4611.6  379.02  4733.3  369.29  4832.7  361.33  4935.6  359.33  4940.9  358.26
  4951.7  357.97  4972.2  356.30  4989.9  356.84  4995.3  354.20  5001.4  353.66
  5004.2  353.16  5007.4  353.66  5014.4  356.28  5019.8  355.82  5025.9  357.24
  5074.1  363.48  5090.3  364.17  5153.0  369.71  5207.4  378.71  5229.8  381.29
  5266.0  387.36  5275.1  389.85  5281.3  390.46  5288.3  392.88  5302.5  394.34
  5309.5  394.23  5316.6  391.16  5323.7  390.53  5330.6  387.86  5336.7  387.86
#Mann=6,-1,0
  4611.6    0.05       0  4733.3    0.16       0  4951.7    0.05       0
  5001.4    0.03       0  5007.4    0.05       0  5275.1     0.1       0
Bank Sta=5001.4,5007.4
Exp/Cntr=0.3,0.1

Type RM Length L Ch R = 1,1712,287,287,287
BEGIN DESCRIPTION:
CEDAR CREEK TRIBUTARY 7 3.0
END DESCRIPTION:
XS GIS Cut Line= 3
      3529373.47     10328120.68      3528905.87     10328332.83
      3528756.50     10328581.78
#Sta/Elev= 30
  4605.4  385.91  4661.8  383.50  4740.6  375.43  4886.4  361.82  4932.7  356.21
  4978.8  354.00  4998.9  351.09  5001.7  350.59  5004.9  351.09  5013.2  353.85
  5110.2  355.94  5121.1  355.48  5135.5  357.21  5156.8  356.20  5172.4  357.92
  5178.2  356.70  5193.8  361.03  5199.6  358.98  5209.3  362.13  5215.1  359.55
  5230.7  363.27  5236.5  360.31  5245.8  360.98  5252.1  363.21  5257.9  360.92
  5273.5  360.98  5289.0  366.03  5331.8  371.33  5368.7  380.87  5409.2  388.26
#Mann=6,-1,0
  4605.4    0.05       0  4740.6     0.1       0  4886.4    0.12       0
  4998.9    0.07       0  5004.9    0.12       0  5110.2     0.1       0
Bank Sta=4998.9,5004.9
Exp/Cntr=0.3,0.1

Type RM Length L Ch R = 1,1425,530,530,530
BEGIN DESCRIPTION:
CEDAR CREEK TRIBUTARY 7 2.0
END DESCRIPTION:
XS GIS Cut Line= 3
      3529192.11     10327991.64      3528892.11     10328041.64
      3528592.11     10328241.64
#Sta/Elev= 30
  4684.5  378.84  4785.9  368.73  4834.0  364.91  4867.0  361.41  4887.1  358.09
  4894.9  356.45  4899.9  356.70  4907.5  355.13  4927.8  352.94  4938.0  352.65
  4955.7  353.66  4960.8  352.02  4991.7  352.14  4996.2  350.53  4999.2  350.43
  5001.9  349.93  5005.2  350.43  5038.2  353.63  5132.9  354.77  5166.8  356.56
  5182.4  357.56  5191.5  357.20  5197.5  358.64  5233.5  359.75  5253.5  362.32
  5265.1  363.08  5277.1  363.65  5284.6  364.97  5320.7  368.47  5349.2  369.30
#Mann=7,-1,0
  4684.5     0.1       0  4887.1    0.12       0  4999.2    0.07       0
  5005.2    0.12       0  5166.8     0.1       0  5253.5    0.12       0
  5265.1    0.16       0
Bank Sta=4999.2,5005.2
Exp/Cntr=0.3,0.1

Type RM Length L Ch R = 1,895,0,0,0
BEGIN DESCRIPTION:
CEDAR CREEK TRIBUTARY 7 1.0
END DESCRIPTION:
XS GIS Cut Line= 3
      3529187.24     10327826.63      3528579.53     10327674.70
      3528183.23     10328017.18
#Sta/Elev= 30
  4487.4  373.97  4495.5  373.43  4505.3  372.91  4564.7  368.48  4575.2  367.01
  4611.1  365.28  4657.6  360.78  4719.5  356.79  4817.3  352.21  4832.9  350.73
  4853.8  350.85  4941.0  350.90  4966.9  349.88  4987.5  350.04  5005.1  346.96
  5007.8  346.46  5011.1  346.96  5018.3  349.74  5028.7  350.68  5080.2  349.57
  5223.3  350.03  5295.5  351.95  5350.6  354.08  5372.5  356.13  5407.6  357.36
  5510.2  364.54  5591.9  369.59  5606.1  368.76  5612.7  369.26  5637.6  369.20
#Mann=8,-1,0
  4487.4    0.05       0  4495.5     0.1       0  4505.3    0.16       0
  4853.8    0.12       0  5005.1    0.07       0  5011.1    0.12       0
  5295.5     0.1       0  5510.2    0.16       0
Bank Sta=5005.1,5011.1
Exp/Cntr=0.3,0.1

Chan Stop Cuts=-1