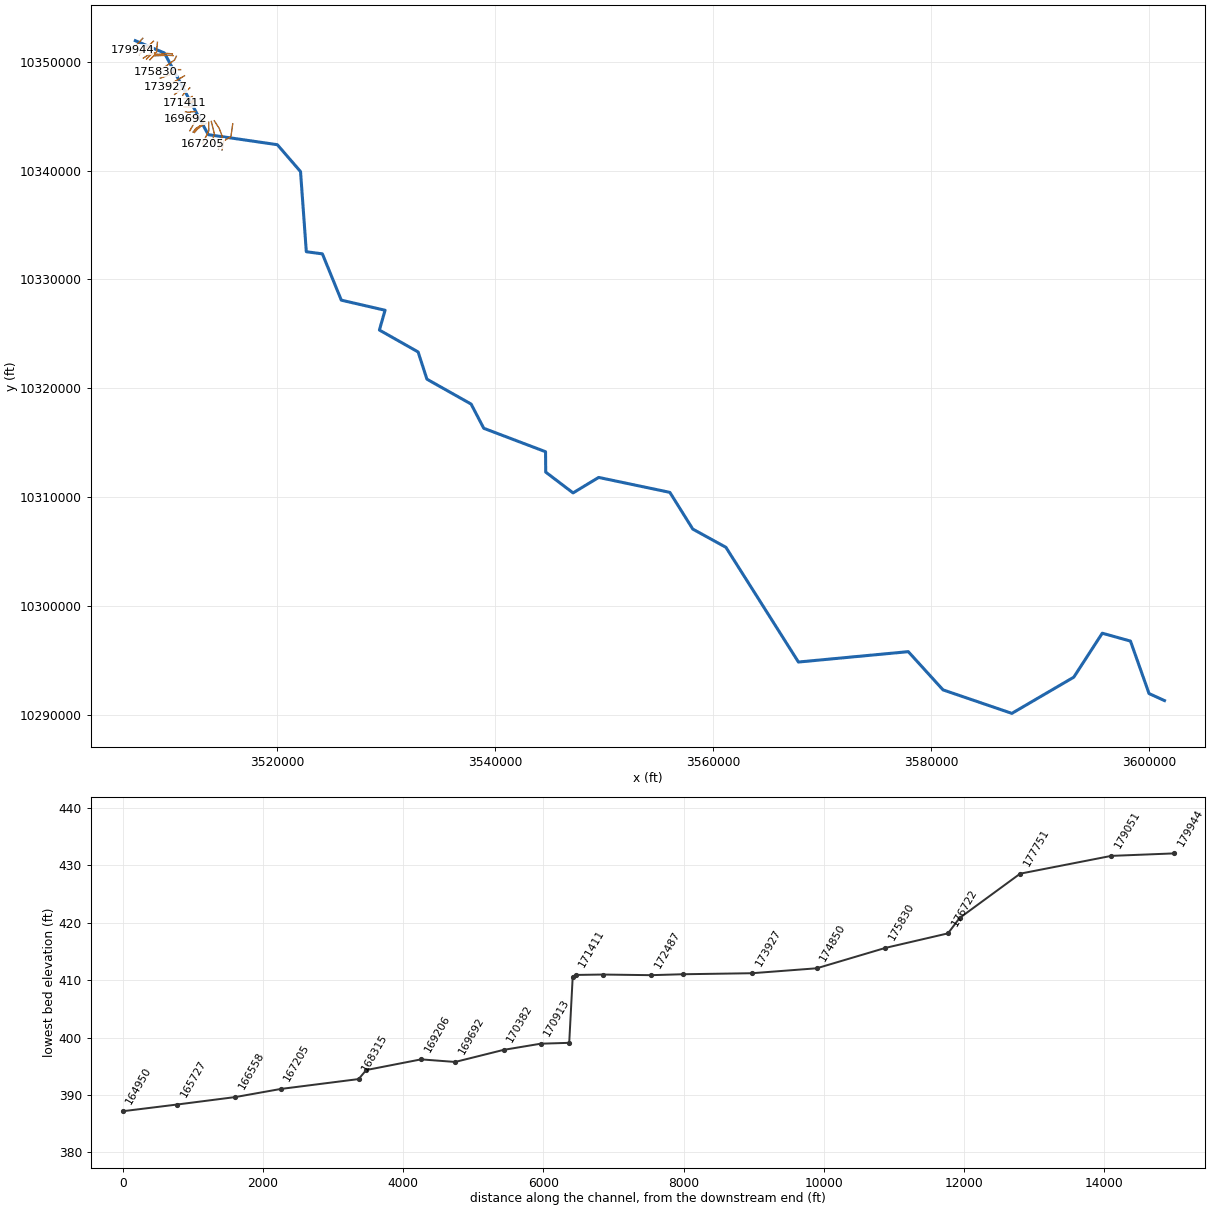
--- CEDAR CREEK.prj (project) ---

Proj Title=CEDAR CREEK Base Level Engineering
Current Plan=p01
Default Exp/Contr=0.3,0.1
English Units
Geom File=g01
Flow File=f01
Plan File=p01
Y Axis Title=Elevation
X Axis Title(PF)=Main Channel Distance
X Axis Title(XS)=Station
BEGIN DESCRIPTION:
CEDAR CREEK
END DESCRIPTION:
DSS Export Rating Curves= 0
DSS Export Rating Curve Sorted= 0
DSS Export Volume Flow Curves= 0
DXF OffsetX= 0
DXF OffsetY= 0
DXF ScaleX= 1
DXF ScaleY= 10

--- CEDAR CREEK.p01 (plan) ---

Plan Title=Multiple Run
Short Identifier=Multiple
Geom File=g01
Flow File=f01
Subcritical Flow
K Sum by GR= 0
Std Step Tol= 0.01
Critical Tol= 0.01
Num of Std Step Trials= 20
Max Error Tol= 0.3
Flow Tol Ratio= 0.001
Split Flow NTrial= 30
Split Flow Tol= 0.02
Split Flow Ratio= 0.02
Log Output Level= 0
Friction Slope Method= 1
Unsteady Friction Slope Method= 2
Unsteady Bridges Friction Slope Method= 1
Parabolic Critical Depth
Global Vel Dist=  1 , 1 , 1
Global Log Level= 0
CheckData=True
Encroach Param= -1, 0, 0, 0
BEGIN DESCRIPTION:
Multiple Run
END DESCRIPTION:

--- CEDAR CREEK.f01 (steady flow) ---

Flow Title=Multiple
Program Version=4.10
Number of Profiles= 7
Profile Names=10-year,25-year,50-year,1pct_min,100-year,1pct_plu,500-year
River Rch & RM=CEDAR CREEK,Reach-1         ,179944
    1437    2015    2500    2259    3055    4131    4560
River Rch & RM=CEDAR CREEK,Reach-1         ,172938
    1437    2015    2500    2259    3055    4131    4560
River Rch & RM=CEDAR CREEK,Reach-1         ,169206
    1892    2694    3377    3084    4171    5640    6376
River Rch & RM=CEDAR CREEK,Reach-1         ,168424
    1892    2694    3377    3084    4171    5640    6376
River Rch & RM=CEDAR CREEK,Reach-1         ,164950
    2585    3723    4703    4322    5845    7905    9047
River Rch & RM=CEDAR CREEK,Reach-1         ,163445
    2585    3723    4703    4322    5845    7905    9047
River Rch & RM=CEDAR CREEK,Reach-1         ,159780
    2642    3806    4809    4420    5978    8084    9257
River Rch & RM=CEDAR CREEK,Reach-1         ,158440
    3502    5092    6472    5981    8088   10939   12651
River Rch & RM=CEDAR CREEK,Reach-1         ,154014
    3981    5804    7392    6843    9254   12515   14526
River Rch & RM=CEDAR CREEK,Reach-1         ,152802
    4201    6134    7822    7249    9803   13257   15428
River Rch & RM=CEDAR CREEK,Reach-1         ,151679
    4201    6134    7822    7249    9803   13257   15428
River Rch & RM=CEDAR CREEK,Reach-1         ,148695
    4173    6078    7737    7158    9680   13091   15180
River Rch & RM=CEDAR CREEK,Reach-1         ,141353
    4747    6920    8815    8160   11035   14924   17336
River Rch & RM=CEDAR CREEK,Reach-1         ,138919
    4747    6920    8815    8160   11035   14924   17336
River Rch & RM=CEDAR CREEK,Reach-1         ,135355
    4977    7258    9249    8565   11583   15664   18209
River Rch & RM=CEDAR CREEK,Reach-1         ,133721
    4977    7258    9249    8565   11583   15664   18209
River Rch & RM=CEDAR CREEK,Reach-1         ,130266
    5149    7517    9585    8882   12011   16244   18907
River Rch & RM=CEDAR CREEK,Reach-1         ,128035
    5149    7517    9585    8882   12011   16244   18907
River Rch & RM=CEDAR CREEK,Reach-1         ,124160
    5055    7352    9352    8643   11689   15808   18305
River Rch & RM=CEDAR CREEK,Reach-1         ,117988
    5560    8108   10333    9568   12940   17500   20343
River Rch & RM=CEDAR CREEK,Reach-1         ,116864
    5560    8108   10333    9568   12940   17500   20343
River Rch & RM=CEDAR CREEK,Reach-1         ,112897
    6382    9328   11911   11048   14941   20206   23569
River Rch & RM=CEDAR CREEK,Reach-1         ,110781
    6430    9395   11993   11122   15041   20341   23713
River Rch & RM=CEDAR CREEK,Reach-1         ,106248
    6592    9632   12295   11400   15417   20850   24302
River Rch & RM=CEDAR CREEK,Reach-1         ,100597
    6622    9665   12327   11421   15445   20888   24306
River Rch & RM=CEDAR CREEK,Reach-1         ,99564
    6622    9665   12327   11421   15445   20888   24306
River Rch & RM=CEDAR CREEK,Reach-1         ,94929
    6645    9692   12357   11444   15477   20930   24336
River Rch & RM=CEDAR CREEK,Reach-1         ,93242
    6645    9692   12357   11444   15477   20930   24336
River Rch & RM=CEDAR CREEK,Reach-1         ,90547
    7055   10287   13113   12142   16421   22207   25809
River Rch & RM=CEDAR CREEK,Reach-1         ,84847
    7195   10484   13360   12365   16722   22614   26256
River Rch & RM=CEDAR CREEK,Reach-1         ,83516
    7195   10484   13360   12365   16722   22614   26256
River Rch & RM=CEDAR CREEK,Reach-1         ,77149
    7239   10549   13444   12443   16827   22757   26423
River Rch & RM=CEDAR CREEK,Reach-1         ,73583
    7209   10480   13332   12317   16658   22528   26063
River Rch & RM=CEDAR CREEK,Reach-1         ,62804
    8937   13058   16677   15466   20916   28286   32967
River Rch & RM=CEDAR CREEK,Reach-1         ,59487
    8937   13058   16677   15466   20916   28286   32967
River Rch & RM=CEDAR CREEK,Reach-1         ,52068
    9184   13395   17086   15825   21402   28944   33642
River Rch & RM=CEDAR CREEK,Reach-1         ,49513
    9467   13837   17676   16397   22174   29988   34962
River Rch & RM=CEDAR CREEK,Reach-1         ,44230
    9912   14492   18518   17182   23237   31425   36655
River Rch & RM=CEDAR CREEK,Reach-1         ,38682
    9984   14580   18617   17259   23341   31567   36757
River Rch & RM=CEDAR CREEK,Reach-1         ,36567
    9984   14580   18617   17259   23341   31567   36757
River Rch & RM=CEDAR CREEK,Reach-1         ,32873
   10055   14650   18676   17287   23378   31616   36692
River Rch & RM=CEDAR CREEK,Reach-1         ,30672
   10055   14650   18676   17287   23378   31616   36692
River Rch & RM=CEDAR CREEK,Reach-1         ,22958
   10055   14650   18676   17287   23378   31616   36692
River Rch & RM=CEDAR CREEK,Reach-1         ,20696
   10091   14692   18722   17321   23424   31678   36728
River Rch & RM=CEDAR CREEK,Reach-1         ,14672
   10104   14704   18731   17323   23427   31682   36706
Boundary for River Rch & Prof#=CEDAR CREEK,Reach-1         , 1
Up Type= 0
Dn Type= 3
Dn Slope=0.001
Boundary for River Rch & Prof#=CEDAR CREEK,Reach-1         , 2
Up Type= 0
Dn Type= 3
Dn Slope=0.001
Boundary for River Rch & Prof#=CEDAR CREEK,Reach-1         , 3
Up Type= 0
Dn Type= 3
Dn Slope=0.001
Boundary for River Rch & Prof#=CEDAR CREEK,Reach-1         , 4
Up Type= 0
Dn Type= 3
Dn Slope=0.001
Boundary for River Rch & Prof#=CEDAR CREEK,Reach-1         , 5
Up Type= 0
Dn Type= 3
Dn Slope=0.001
Boundary for River Rch & Prof#=CEDAR CREEK,Reach-1         , 6
Up Type= 0
Dn Type= 3
Dn Slope=0.001
Boundary for River Rch & Prof#=CEDAR CREEK,Reach-1         , 7
Up Type= 0
Dn Type= 3
Dn Slope=0.001
DSS Import GetInterval= 0
DSS Import GetPeak= 0
DSS Import FillOption= 0

--- CEDAR CREEK.g01 (geometry) ---

Geom Title=Existing Conditions
Program Version=4.10

River Reach=CEDAR CREEK     ,Reach-1
Reach XY= 30
      3506987.28      10351927.2      3509654.14     10350798.26
      3513675.42     10343299.59      3520014.92     10342377.44
      3522142.11     10339911.64      3522673.78      10332547.8
      3524147.59     10332354.56      3525882.69     10328101.01
      3529898.06     10327173.83      3529377.38      10325358.9
      3532928.23     10323346.66      3533737.98     10320845.59
      3537792.25     10318560.87      3538949.49     10316337.37
      3544618.97     10314183.92      3544634.15     10312312.26
      3547143.05     10310404.06      3549491.12     10311824.08
       3556022.7     10310451.16      3558126.04     10307079.42
      3561164.43     10305407.22      3567817.11     10294872.81
       3577894.5      10295825.4      3581079.94     10292315.39
      3587394.17     10290158.27       3593074.7     10293481.69
      3595687.58     10297519.02      3598275.25     10296796.76
      3599977.19     10291979.91      3601396.02     10291331.87

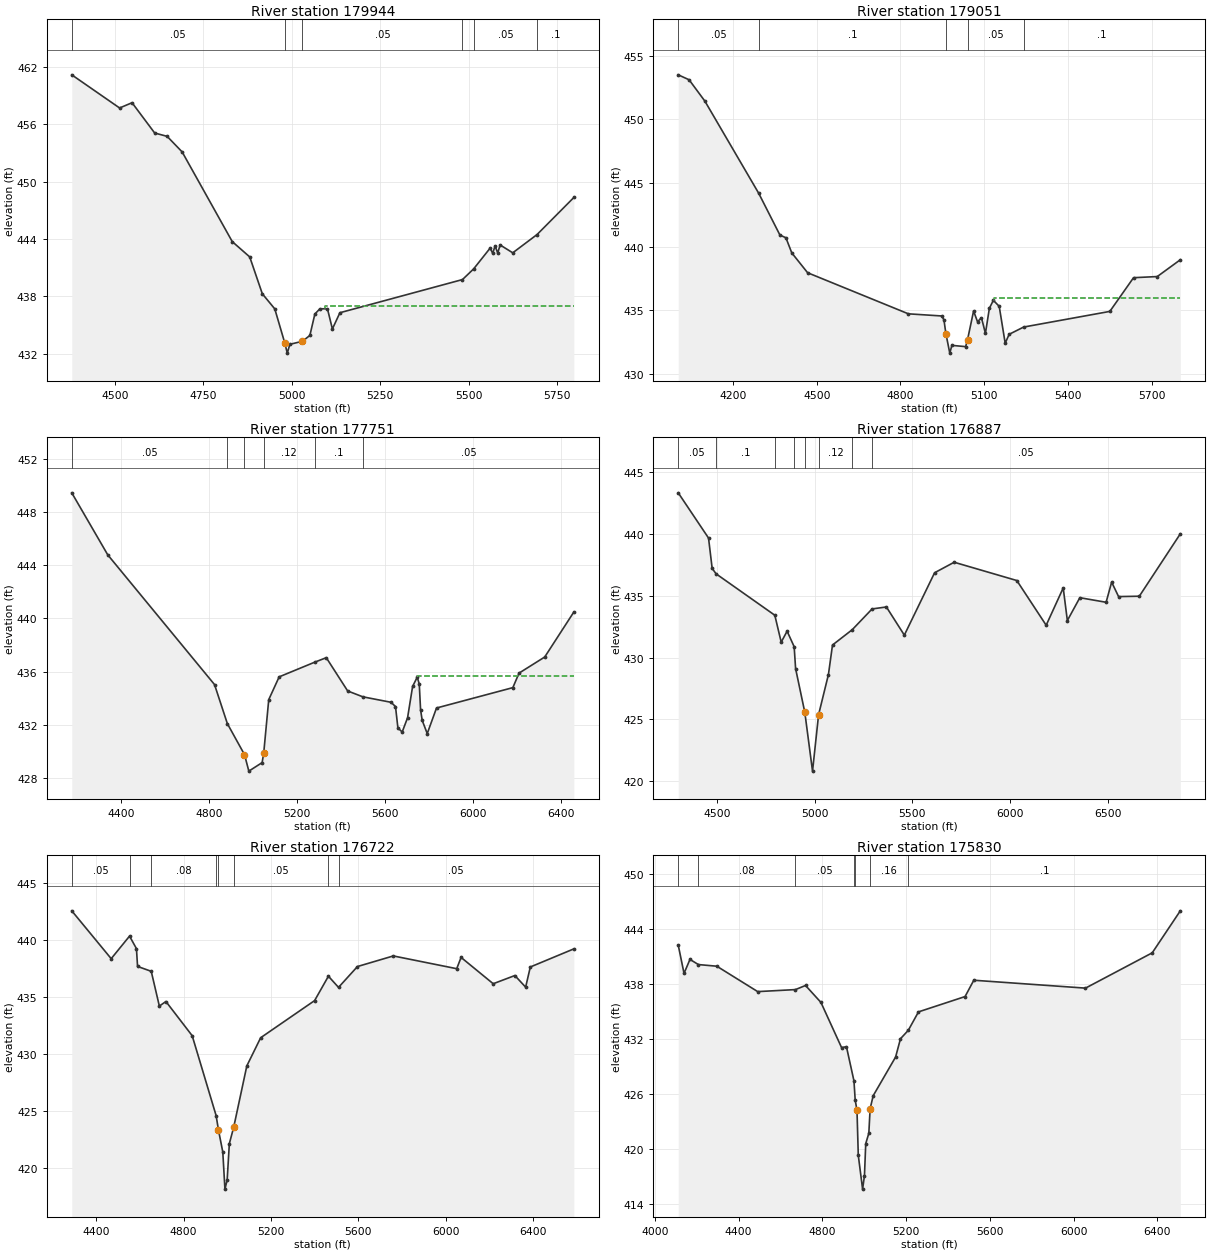
Type RM Length L Ch R = 1 ,179944  ,893,893,893
BEGIN DESCRIPTION:
Mapping XS 093caebd
END DESCRIPTION:
XS GIS Cut Line= 2
      3507670.49     10352144.23      3506691.31     10351118.18
#Sta/Elev= 30
  4378.4  461.19  4513.5  457.72  4548.7  458.27  4612.6   455.1  4647.8  454.75
  4690.2  453.12  4831.8  443.73  4881.1  442.13  4916.7  438.27  4951.9  436.69
  4980.2  433.11  4987.2  432.06  4994.4  432.98  5029.9   433.3    5051  433.91
  5065.1  436.15  5079.3   436.7  5100.7   436.7  5114.6  434.59  5135.9  436.29
  5482.1  439.76  5513.7  440.88  5560.2  443.05  5567.4  442.52  5574.3  443.27
  5581.6  442.54  5588.5  443.38  5624.1  442.56  5692.7  444.47  5796.7  448.35
#Mann= 6 ,-1 , 0
  4378.4     .05       0  4980.2     .07       0  5029.9     .05       0
  5482.1      .1       0  5513.7     .05       0  5692.7      .1       0
#XS Ineff= 2 , 0
                         5092.39          437.01
Permanent Ineff=
       F       F
Bank Sta=4980.2,5029.9
XS Rating Curve= 0 ,0
Exp/Cntr=0.3,0.1

Type RM Length L Ch R = 1 ,179051  ,1300,1300,1300
BEGIN DESCRIPTION:
Mapping XS de94b735
END DESCRIPTION:
XS GIS Cut Line= 2
      3508654.87     10351883.82      3507347.63      10350649.5
#Sta/Elev= 30
  4004.2  453.51  4043.1  453.12  4099.7  451.44  4292.3   444.2  4368.4  440.91
  4389.8   440.7  4410.8  439.51  4467.5  437.95  4828.3  434.72  4948.5  434.55
  4955.8  434.23  4962.6  433.17  4976.6  431.63  4984.1  432.24  5033.4  432.14
  5040.3   432.7  5061.8  434.94  5075.9   434.1  5090.1  434.41  5104.2  433.18
  5118.4  435.16  5132.6  435.78  5153.6  435.31    5175  432.41  5189.2  433.11
  5241.1  433.68  5549.7  434.91  5634.6  437.56  5719.6  437.65  5802.1  438.97
#Mann= 5 ,-1 , 0
  4004.2     .05       0  4292.3      .1       0  4962.6     .07       0
  5040.3     .05       0  5241.1      .1       0
#XS Ineff= 2 , 0
                         5134.65          435.98
Permanent Ineff=
       F       F
Bank Sta=4962.6,5040.3
XS Rating Curve= 0 ,0
Exp/Cntr=0.3,0.1

Type RM Length L Ch R = 1 ,177751  ,864,864,864
BEGIN DESCRIPTION:
Mapping XS 629716d1
END DESCRIPTION:
XS GIS Cut Line= 4
      3509014.26     10351784.89      3508930.92     10350842.17
      3508358.01       10350738.      3507722.68      10350326.6
#Sta/Elev= 30
  4174.8  449.43  4338.7  444.77  4824.7  435.03    4883   432.1  4961.1  429.77
  4980.9  428.53  5041.4  429.17  5048.7   429.9  5071.5   433.9  5118.9  435.61
  5280.5  436.71  5333.4  437.05  5430.8  434.55    5500  434.11  5628.2   433.7
  5648.5  433.38  5659.5  431.77    5679  431.47  5703.5  432.54  5726.4  434.89
  5747.5  435.59  5756.7  435.07  5762.7  433.13  5770.1  432.34    5793  431.35
  5835.2  433.27  6182.7   434.8  6210.9  435.89  6327.8   437.1  6460.4  440.48
#Mann= 6 ,-1 , 0
  4174.8     .05       0    4883     .12       0  4961.1     .07       0
  5048.7     .12       0  5280.5      .1       0    5500     .05       0
#XS Ineff= 2 , 0
                         5747.89          435.64
Permanent Ineff=
       F       F
Bank Sta=4961.1,5048.7
XS Rating Curve= 0 ,0
Exp/Cntr=0.3,0.1

Type RM Length L Ch R = 1 ,176887  ,165,165,165
BEGIN DESCRIPTION:
Mapping XS af8c4741
END DESCRIPTION:
XS GIS Cut Line= 5
      3510384.03     10350706.76      3509951.76     10350764.05
      3509180.92     10350680.71      3508467.38     10350696.34
       3508019.5     10350238.04
#Sta/Elev= 30
  4303.2  443.34    4458  439.68  4476.6  437.22  4496.9  436.78  4796.8  433.43
  4829.4  431.25  4859.6  432.14  4895.7  430.88    4903  429.11  4950.1  425.57
  4989.5  420.81  5020.5  425.38  5070.8  428.63  5091.6  431.02  5192.5  432.26
  5293.9  433.94    5367   434.1  5458.7  431.82  5613.4  436.87  5713.4  437.72
  6033.5  436.24  6183.6  432.62  6270.7  435.64  6291.8     433  6355.6  434.85
  6489.9  434.48  6518.2  436.11  6553.6  434.94  6659.6  434.97  6869.1  440.02
#Mann= 8 ,-1 , 0
  4303.2     .05       0  4496.9      .1       0  4796.8     .08       0
  4895.7     .12       0  4950.1     .07       0  5020.5     .12       0
  5192.5     .16       0  5293.9     .05       0
Bank Sta=4950.1,5020.5
XS Rating Curve= 0 ,0
Exp/Cntr=0.3,0.1

Type RM Length L Ch R = 1 ,176722  ,892,892,892
BEGIN DESCRIPTION:
Mapping XS 89548968
END DESCRIPTION:
XS GIS Cut Line= 4
      3510462.13     10350555.72      3509946.55     10350592.17
      3508670.51     10350534.88      3508321.53     10350170.27
#Sta/Elev= 30
    4288  442.57  4468.5  438.37  4552.5  440.35  4584.2  439.25  4589.2  437.69
  4651.9  437.26    4689  434.21  4719.1  434.61  4839.3  431.61  4948.9   424.6
  4959.5  423.35  4979.5   421.4  4989.3  418.14  4999.5  418.94  5009.5  422.13
  5029.5  423.58  5089.6  428.96  5152.9  431.43  5399.9  434.69  5463.1  436.83
  5509.4  435.85  5596.1  437.68  5760.3  438.61  6050.6  437.49  6070.6  438.48
  6217.7  436.17  6316.8  436.89  6366.2  435.87  6387.6  437.64  6586.9  439.23
#Mann= 8 ,-1 , 0
    4288     .05       0  4552.5      .1       0  4651.9     .08       0
  4948.9     .05       0  4959.5     .07       0  5029.5     .05       0
  5463.1     .08       0  5509.4     .05       0
Bank Sta=4959.5,5029.5
XS Rating Curve= 0 ,0
Exp/Cntr=0.3,0.1

Type RM Length L Ch R = 1 ,175830  ,980,980,980
BEGIN DESCRIPTION:
Mapping XS 93464da5
END DESCRIPTION:
XS GIS Cut Line= 4
      3510750.38     10350498.45      3510590.65     10350158.14
      3509639.26     10349477.59      3508877.27      10349096.6
#Sta/Elev= 30
  4111.8  442.22  4139.5  439.14  4167.8  440.66  4208.1   440.1  4296.1  439.92
  4491.2  437.15  4671.5  437.37  4719.7  437.82  4793.3  435.97  4891.7  431.05
  4915.1  431.14    4951  427.41  4956.8  425.32  4965.4  424.22  4971.6   419.3
  4992.2  415.61  5001.1  417.08  5007.2  420.57    5022  421.71  5028.1  424.37
  5042.8   425.8  5149.9  430.02  5173.1  432.01  5210.4  432.93  5259.1  434.94
  5481.5  436.61  5523.2  438.39  6056.6  437.53  6375.3  441.38  6509.4  445.96
#Mann= 7 ,-1 , 0
  4111.8     .05       0  4208.1     .08       0  4671.5     .05       0
    4951     .16       0  4956.8     .07       0  5028.1     .16       0
  5210.4      .1       0
Bank Sta=4965.4,5028.1
XS Rating Curve= 0 ,0
Exp/Cntr=0.3,0.1

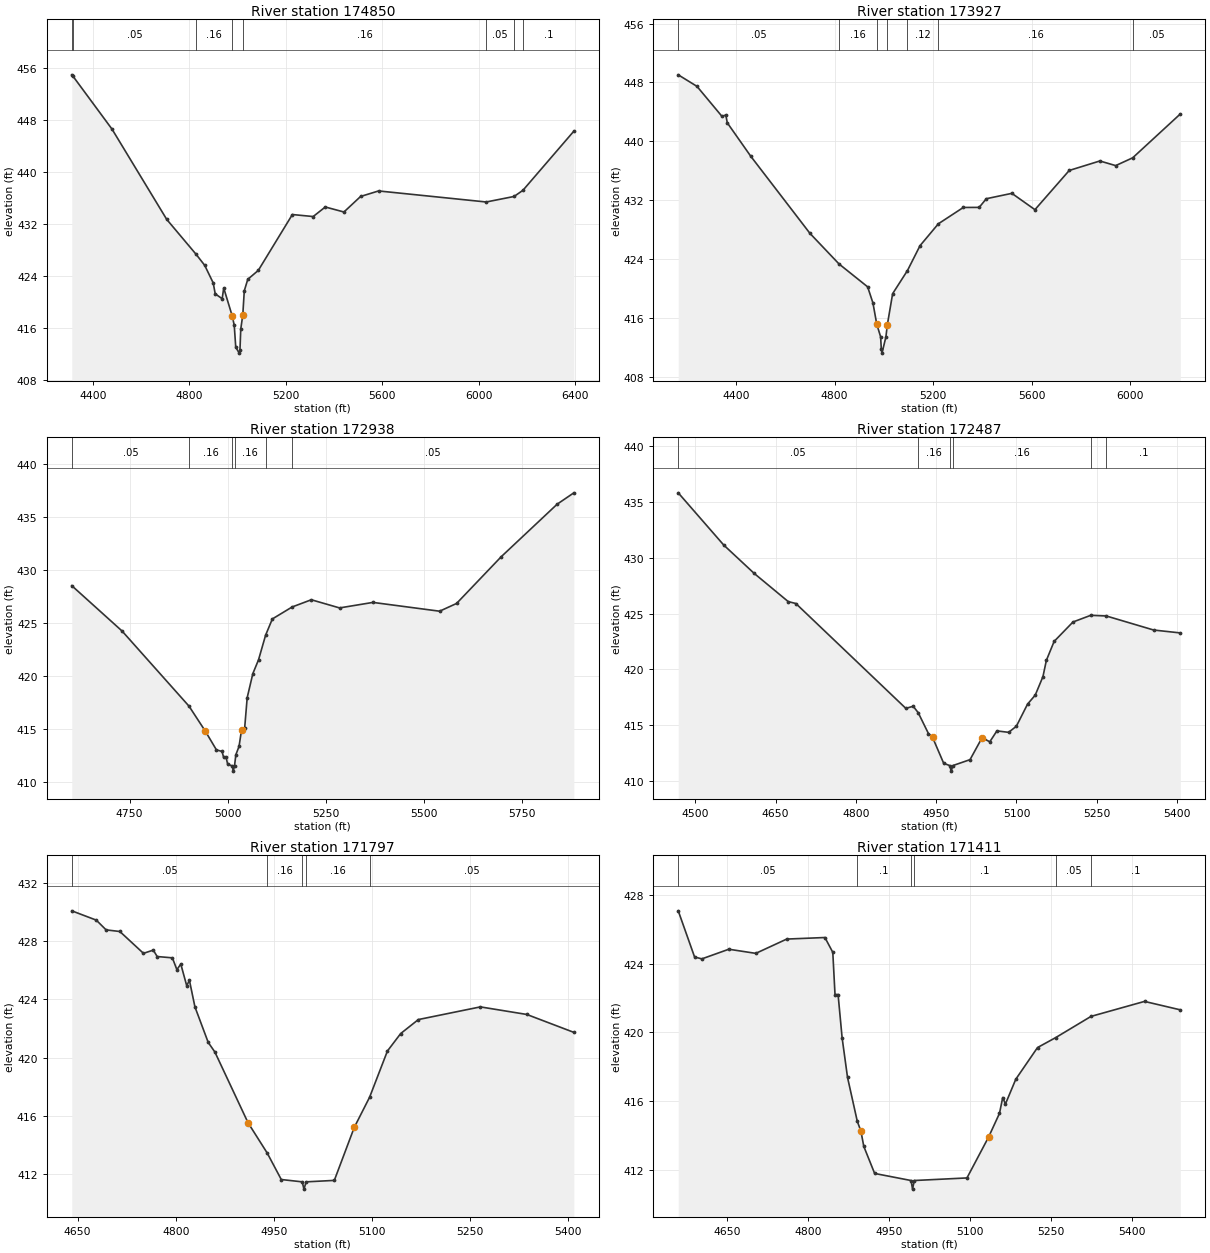
Type RM Length L Ch R = 1 ,174850  ,923,923,923
BEGIN DESCRIPTION:
Mapping XS f3832879
END DESCRIPTION:
XS GIS Cut Line= 4
      3511139.27     10349269.25      3510743.42     10349269.25
      3510125.37     10348797.03      3509271.19     10348484.53
#Sta/Elev= 30
  4311.7  454.89  4314.9  454.77  4478.9  446.52  4705.7  432.64  4827.5  427.27
  4863.3  425.57  4898.6  422.86  4906.9  421.19  4935.7  420.43  4942.2  422.08
  4977.6  417.76  4985.8  416.35  4992.1  412.97  5006.4  412.06  5009.6  412.56
  5012.9  415.77  5021.2   417.9  5027.5  421.65    5042  423.42  5085.6  424.79
    5227  433.39  5313.3  433.08  5363.6  434.55    5441  433.78  5510.1  436.17
  5584.7  437.02  6031.4  435.32  6146.9  436.17  6183.7  437.12  6394.9  446.22
#Mann= 8 ,-1 , 0
  4311.7      .1       0  4314.9     .05       0  4827.5     .16       0
  4977.6     .07       0  5021.2     .16       0  6031.4     .05       0
  6146.9     .16       0  6183.7      .1       0
Bank Sta=4977.6,5021.2
XS Rating Curve= 0 ,0
Exp/Cntr=0.3,0.1

Type RM Length L Ch R = 1 ,173927  ,989,989,989
BEGIN DESCRIPTION:
Mapping XS 223ee9b0
END DESCRIPTION:
XS GIS Cut Line= 2
      3511500.33     10348706.73      3509743.39     10347672.01
#Sta/Elev= 30
  4164.8  449.03    4241  447.46  4342.5  443.38  4358.1  443.57  4363.9  442.51
  4459.6  437.95  4699.7  427.48  4817.8  423.32    4934  420.21  4955.5  418.02
  4971.1  415.13  4986.7  413.42  4989.6   411.7  4992.3   411.2  5008.2  413.41
    5014  415.05  5035.5  419.28  5095.8  422.43  5146.8  425.81  5221.2  428.78
  5322.5     431  5386.9  431.01  5416.1  432.19  5519.7  432.92  5613.4   430.7
  5752.7  436.03    5877  437.32  5941.3  436.69  6010.4  437.75  6203.8  443.71
#Mann= 7 ,-1 , 0
  4164.8     .05       0  4817.8     .16       0  4971.1     .07       0
    5014     .16       0  5095.8     .12       0  5221.2     .16       0
  6010.4     .05       0
Bank Sta=4971.1,5014
XS Rating Curve= 0 ,0
Exp/Cntr=0.3,0.1

Type RM Length L Ch R = 1 ,172938  ,451,451,451
BEGIN DESCRIPTION:
CEDAR CREEK 175.0
END DESCRIPTION:
XS GIS Cut Line= 3
      3511592.14     10347791.67      3511292.11     10347541.64
      3510592.09     10346991.63
#Sta/Elev= 30
  4602.3  428.52  4730.6  424.24  4901.4  417.15  4942.7  414.81  4971.4  413.02
  4985.7  412.88  4989.6  412.32    4996  412.32  5000.1  411.65  5011.5  411.52
  5014.3  411.02  5017.5  411.52  5020.9  412.57    5029  413.35  5035.3  414.88
  5043.4   415.1  5049.8  417.95  5064.2  420.22  5078.7  421.52  5096.8  423.85
    5114  425.38  5164.5  426.51  5213.4  427.19  5285.4  426.42  5370.6  426.94
  5540.6  426.11  5583.9  426.84  5697.8  431.25  5840.6  436.21  5883.1  437.28
#Mann= 6 ,-1 , 0
  4602.3     .05       0  4901.4     .16       0  5011.5     .07       0
  5017.5     .16       0  5096.8     .12       0  5164.5     .05       0
Bank Sta=4942.7,5035.3
XS Rating Curve= 0 ,0
Exp/Cntr=0.3,0.1

Type RM Length L Ch R = 1 ,172487  ,690,690,690
BEGIN DESCRIPTION:
CEDAR CREEK 174.0
END DESCRIPTION:
XS GIS Cut Line= 3
      3511992.09     10347591.62      3511592.11     10347241.64
      3511339.84     10346922.99
#Sta/Elev= 30
  4468.2  435.83  4553.1  431.15  4610.1   428.6  4673.7  426.07  4687.9   425.9
  4893.4  416.49  4907.1  416.68  4916.4  416.11  4935.6  414.23  4943.2   413.9
  4964.1  411.56  4975.3  411.36  4978.1  410.86  4981.3  411.36  5013.3  411.89
  5035.8  413.86  5050.2  413.49  5063.5  414.47  5085.4  414.34  5099.9  414.89
  5120.7  416.87  5135.1  417.68  5149.5  419.34  5155.9   420.8  5170.4   422.5
  5205.6  424.24  5238.8  424.84  5267.9  424.78  5356.3  423.52  5406.1  423.26
#Mann= 6 ,-1 , 0
  4468.2     .05       0  4916.4     .16       0  4975.3     .07       0
  4981.3     .16       0  5238.8     .05       0  5267.9      .1       0
Bank Sta=4943.2,5035.8
XS Rating Curve= 0 ,0
Exp/Cntr=0.3,0.1

Type RM Length L Ch R = 1 ,171797  ,386,386,386
BEGIN DESCRIPTION:
CEDAR CREEK 173.0
END DESCRIPTION:
XS GIS Cut Line= 3
      3512200.06     10346806.26      3512050.08     10346706.27
      3511471.26     10346606.58
#Sta/Elev= 30
  4641.1  430.09  4678.6  429.45  4693.6  428.78  4714.6  428.67  4750.7  427.17
  4765.7  427.39  4771.7  426.95  4794.9  426.86  4801.8  426.05  4807.8  426.43
  4816.8  424.95    4821  425.31  4829.4  423.49  4849.7  421.05  4859.9  420.39
  4910.6  415.53  4939.9  413.45  4961.4  411.63  4993.4  411.47  4996.1  410.97
  4999.4  411.47  5042.5  411.57    5073  415.21  5096.5  417.29  5123.7  420.46
    5144  421.66    5171  422.62  5265.8  423.49  5336.8  422.97  5408.7  421.74
#Mann= 5 ,-1 , 0
  4641.1     .05       0  4939.9     .16       0  4993.4     .07       0
  4999.4     .16       0  5096.5     .05       0
Bank Sta=4910.6,5073
XS Rating Curve= 0 ,0
Exp/Cntr=0.3,0.1

Type RM Length L Ch R = 1 ,171411  ,42,42,42
BEGIN DESCRIPTION:
CEDAR CREEK 172.0
END DESCRIPTION:
XS GIS Cut Line= 3
      3512357.12     10346498.02      3512122.02     10346321.69
      3511489.02     10346249.35
#Sta/Elev= 30
  4558.7  427.06    4589  424.38  4602.5  424.27  4652.5  424.83  4702.5  424.59
  4759.9  425.42  4830.7  425.51  4845.3  424.65  4849.4   422.2  4855.1   422.2
  4862.6  419.68  4872.6  417.39  4890.7  414.84  4897.4  414.27  4902.8  413.38
  4922.9  411.81  4990.4   411.4  4993.2   410.9  4996.4   411.4  5094.1  411.55
  5134.3  413.93  5154.4   415.3  5160.4  416.22  5165.4  415.84  5184.6  417.28
  5224.9  419.12  5258.7   419.7  5324.1  420.93  5423.3   421.8  5489.7  421.31
#Mann= 6 ,-1 , 0
  4558.7     .05       0  4890.7      .1       0  4990.4     .07       0
  4996.4      .1       0  5258.7     .05       0  5324.1      .1       0
Bank Sta=4897.4,5134.3
XS Rating Curve= 0 ,0
Exp/Cntr=0.3,0.1

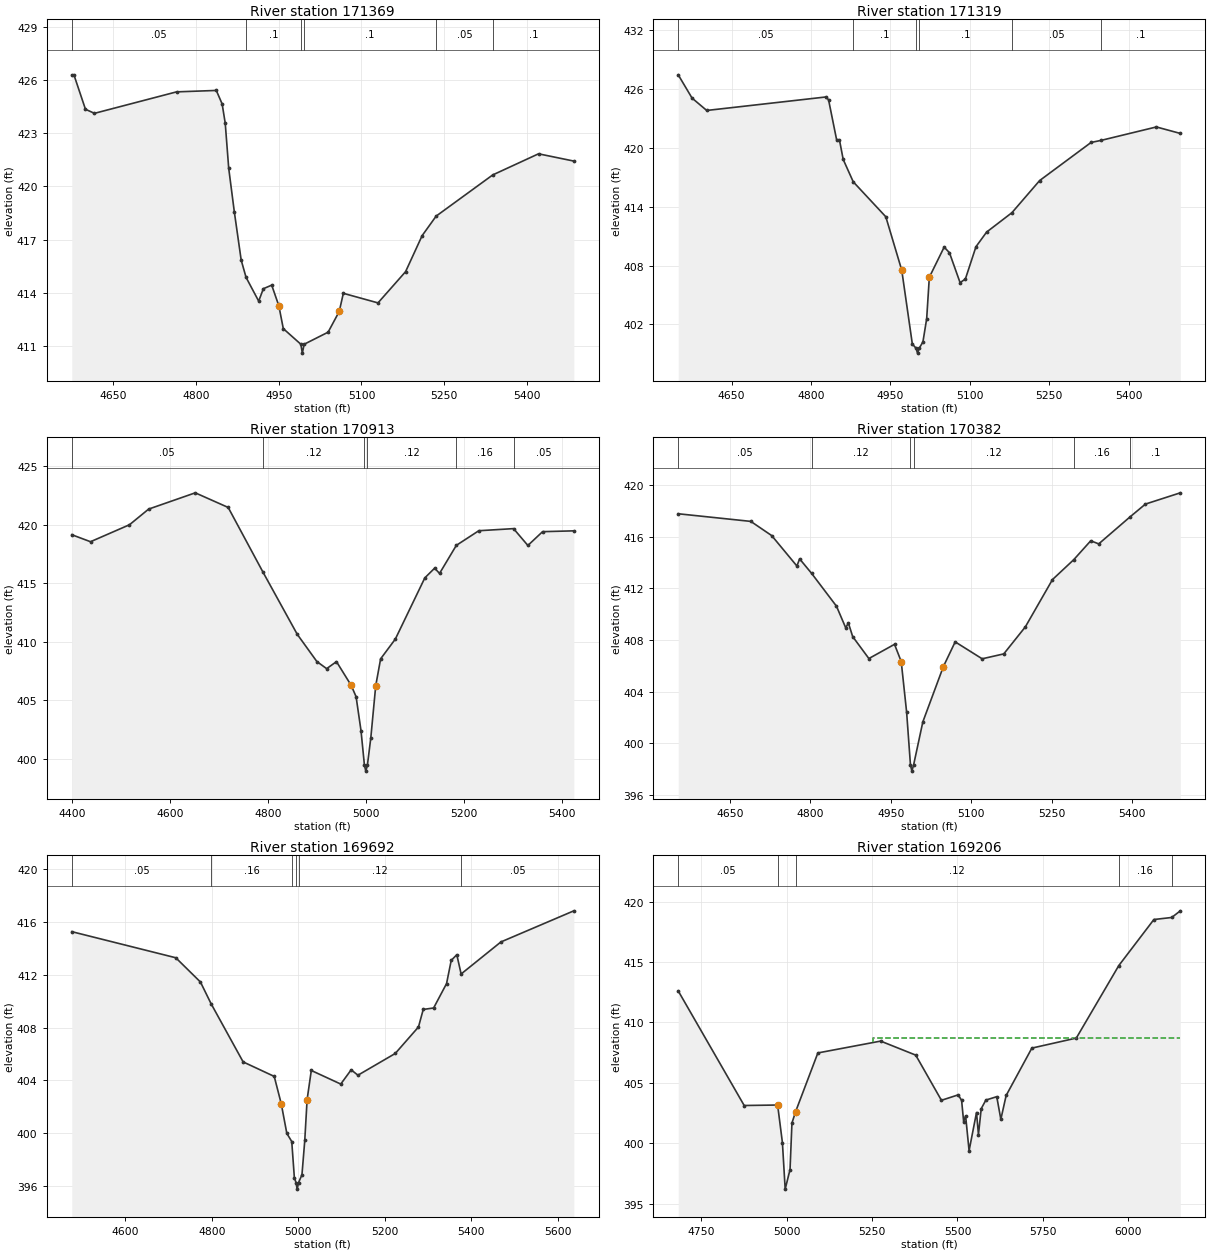
Type RM Length L Ch R = 1 ,171369  ,50,50,50
BEGIN DESCRIPTION:
Mapping XS 8cc0dbef
END DESCRIPTION:
XS GIS Cut Line= 6
      3512374.05     10346445.42      3512065.92     10346283.98
      3512019.04     10346269.22      3511912.27     10346255.33
       3511683.1     10346248.39       3511508.6     10346226.68
#Sta/Elev= 30
  4575.1  426.29    4579  426.29  4599.9  424.35  4616.2  424.12    4765  425.33
    4837  425.41  4847.6  424.65  4853.2  423.56  4859.5  421.02  4869.7  418.56
  4882.1  415.85  4890.9  414.88  4913.8  413.54  4922.3  414.24  4937.4  414.44
  4950.3  413.28  4958.4  411.99  4990.2  411.11  4992.9  410.61  4996.2  411.11
  5039.6  411.79  5059.8  412.96  5067.2  413.98    5130  413.44    5180   415.2
    5210  417.23  5235.4  418.33  5337.9  420.65  5420.9  421.84  5484.9  421.43
#Mann= 6 ,-1 , 0
  4575.1     .05       0  4890.9      .1       0  4990.2     .07       0
  4996.2      .1       0  5235.4     .05       0  5337.9      .1       0
Bank Sta=4950.3,5059.8
XS Rating Curve= 0 ,0
Exp/Cntr=0.3,0.1

Type RM Length L Ch R = 1 ,171319  ,406,406,406
BEGIN DESCRIPTION:
Mapping XS 8296675b
END DESCRIPTION:
XS GIS Cut Line= 3
      3512418.36     10346369.92      3512151.85     10346227.55
      3511506.95     10346185.89
#Sta/Elev= 30
  4549.1  427.43  4575.2  425.06  4602.9   423.8  4827.3  425.17    4833   424.9
  4848.3  420.81  4853.6  420.81  4860.7  418.81  4879.7  416.53  4941.2  412.97
  4971.3  407.53  4991.3  400.01  4998.3  399.58  5001.1  399.08  5004.3  399.58
  5011.3  400.22  5018.4  402.59  5023.4  406.81  5051.4  409.88  5061.4  409.31
  5081.5  406.26  5091.5  406.63  5111.5  409.92  5131.6  411.41  5179.5  413.39
  5231.8  416.66  5328.9  420.54  5347.7  420.75  5452.3  422.12  5497.5  421.46
#Mann= 6 ,-1 , 0
  4549.1     .05       0  4879.7      .1       0  4998.3     .07       0
  5004.3      .1       0  5179.5     .05       0  5347.7      .1       0
Bank Sta=4971.3,5023.4
XS Rating Curve= 0 ,0
Exp/Cntr=0.3,0.1

Type RM Length L Ch R = 1 ,170913  ,531,531,531
BEGIN DESCRIPTION:
CEDAR CREEK 171.0
END DESCRIPTION:
XS GIS Cut Line= 3
      3512436.24     10345997.23      3512136.25     10345847.23
      3511448.36     10345851.49
#Sta/Elev= 30
  4400.1  419.14  4438.3  418.54  4517.7  419.99  4556.8  421.33  4651.8  422.72
  4718.9  421.47  4789.3  415.98  4859.6  410.63  4899.6   408.3  4919.6  407.69
  4939.6  408.29  4969.6  406.26  4979.6  405.29  4989.6  402.39  4996.6  399.43
  4999.4  398.93  5002.6  399.43  5009.6  401.78  5019.6  406.23  5029.6  408.53
  5059.6  410.22  5119.7  415.45  5139.7  416.28  5149.7  415.83  5183.9  418.23
  5229.7  419.48  5300.5  419.66  5329.7  418.22  5359.7   419.4  5423.4  419.47
#Mann= 6 ,-1 , 0
  4400.1     .05       0  4789.3     .12       0  4996.6     .07       0
  5002.6     .12       0  5183.9     .16       0  5300.5     .05       0
Bank Sta=4969.6,5019.6
XS Rating Curve= 0 ,0
Exp/Cntr=0.3,0.1

Type RM Length L Ch R = 1 ,170382  ,690,690,690
BEGIN DESCRIPTION:
CEDAR CREEK 170.0
END DESCRIPTION:
XS GIS Cut Line= 3
      3512515.36     10345431.01      3511838.38     10345356.54
      3511588.39     10345406.54
#Sta/Elev= 30
  4553.8  417.76  4689.1  417.17  4728.1  416.07    4775  413.72  4780.1  414.27
  4802.6  413.14  4848.8  410.61    4866  408.94    4871  409.31    4879  408.26
  4909.2  406.56    4957  407.66  4969.5  406.33  4979.6   402.4  4986.7  398.35
  4989.4  397.85  4992.7  398.35  5009.8  401.66    5048  405.93  5070.1  407.85
  5120.4  406.54  5160.7  406.92  5200.9  409.01  5251.5  412.67  5291.2  414.21
  5322.8  415.67  5337.7  415.43  5396.4  417.53  5424.8  418.51  5489.8  419.38
#Mann= 6 ,-1 , 0
  4553.8     .05       0  4802.6     .12       0  4986.7     .07       0
  4992.7     .12       0  5291.2     .16       0  5396.4      .1       0
Bank Sta=4969.5,5048
XS Rating Curve= 0 ,0
Exp/Cntr=0.3,0.1

Type RM Length L Ch R = 1 ,169692  ,486,486,486
BEGIN DESCRIPTION:
CEDAR CREEK 168.0
END DESCRIPTION:
XS GIS Cut Line= 3
      3512714.31     10345105.49      3512242.11     10344941.64
      3511629.25     10344694.07
#Sta/Elev= 30
  4476.2  415.28  4716.7   413.3  4773.7  411.46  4798.2  409.82  4872.4   405.4
  4944.3   404.3  4960.5  402.23  4973.4  399.98  4984.8  399.36  4990.8  396.63
  4994.6  396.25  4997.3  395.75  5000.6  396.25  5008.4  396.84  5014.9  399.44
  5020.3  402.54    5030  404.75  5098.1  403.72  5122.2   404.8  5137.8  404.39
  5224.1  406.04  5277.8  408.05  5288.8  409.38  5312.8  409.49  5342.7  411.34
  5353.5   413.1  5366.4  413.53  5376.4  412.07  5468.4   414.5    5637  416.86
#Mann= 6 ,-1 , 0
  4476.2     .05       0  4798.2     .16       0  4984.8     .12       0
  4994.6     .07       0  5000.6     .12       0  5376.4     .05       0
Bank Sta=4960.5,5020.3
XS Rating Curve= 0 ,0
Exp/Cntr=0.3,0.1

Type RM Length L Ch R = 1 ,169206  ,782,782,782
BEGIN DESCRIPTION:
CEDAR CREEK 167.0
END DESCRIPTION:
XS GIS Cut Line= 3
      3512692.11     10344941.65      3512542.11     10344641.64
       3511986.4      10343654.2
#Sta/Elev= 30
  4683.2   412.6  4876.1  403.12  4973.9  403.16  4987.9  400.05    4996   396.2
  5010.2  397.82  5015.8  401.67  5026.6  402.62  5091.6  407.47  5275.2  408.45
  5377.8  407.29    5453  403.55    5502     404    5512  403.55    5518  401.78
  5523.7  402.27  5533.9  399.38  5555.6  402.54  5561.3  400.71  5569.4  402.86
    5583  403.57  5614.8  403.85  5626.8  401.98  5642.3  403.95  5717.5  407.87
  5847.5   408.7  5971.8   414.7  6074.4  418.51  6126.6  418.68  6151.7  419.23
#Mann= 5 ,-1 , 0
  4683.2     .05       0  4973.9     .07       0  5026.6     .12       0
  5971.8     .16       0  6126.6     .05       0
#XS Ineff= 2 , 0
                         5253.49          408.72
Permanent Ineff=
       F       F
Bank Sta=4973.9,5026.6
XS Rating Curve= 0 ,0
Exp/Cntr=0.3,0.1

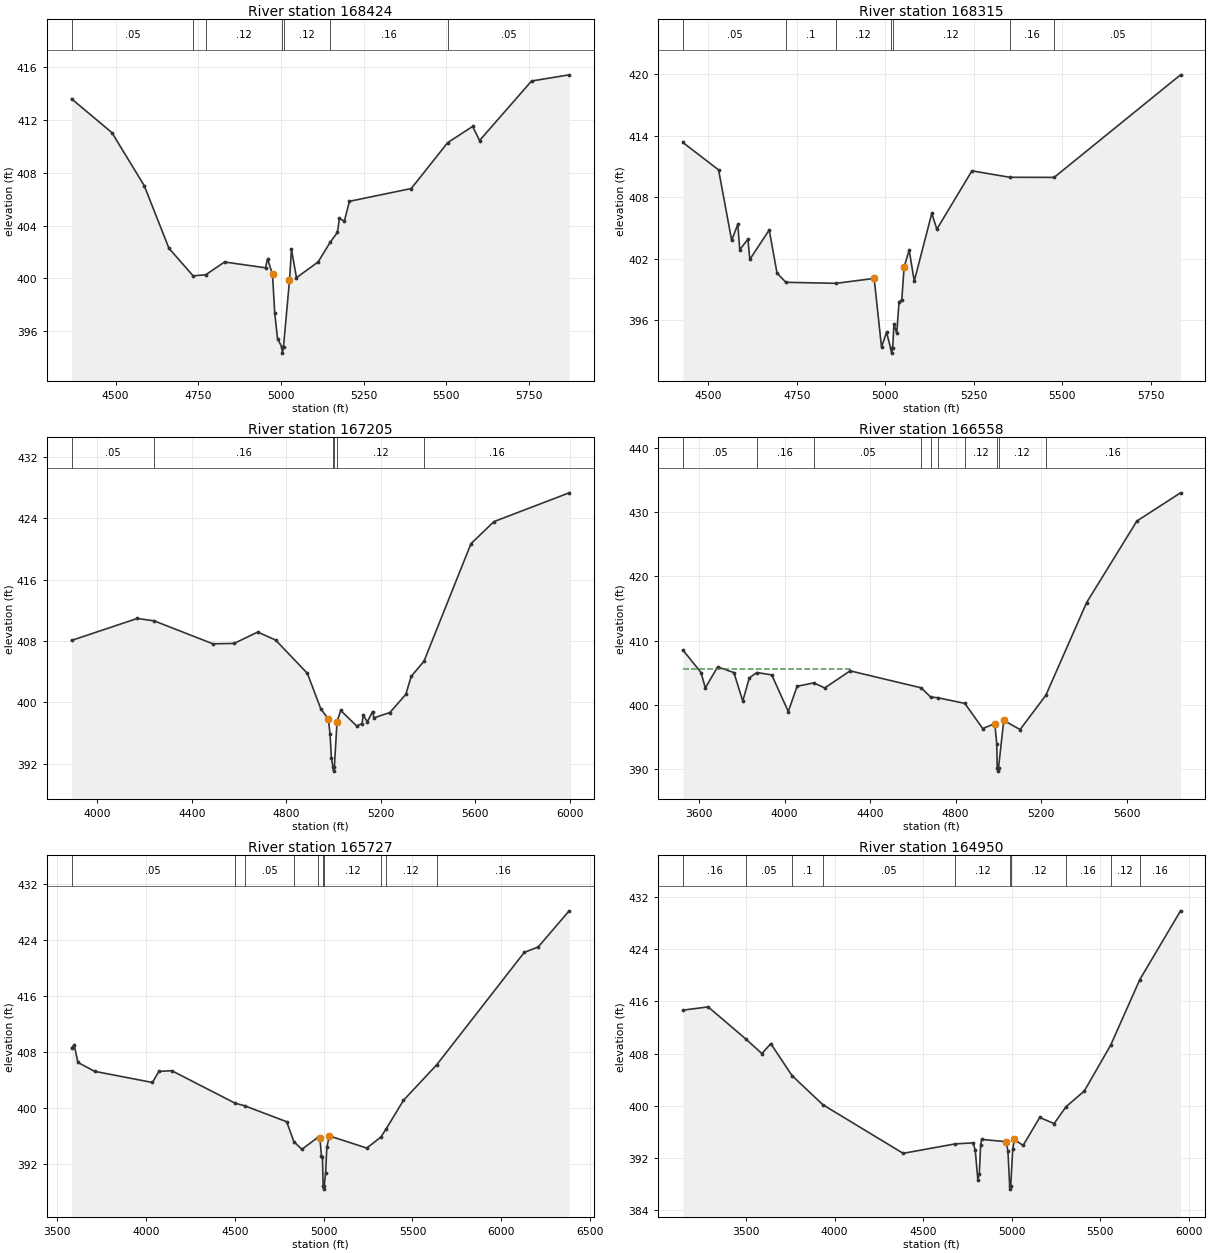
Type RM Length L Ch R = 1 ,168424  ,109,109,109
BEGIN DESCRIPTION:
Mapping XS 16a27d11
END DESCRIPTION:
XS GIS Cut Line= 4
      3513299.61     10344593.38      3513145.95     10344254.81
      3512544.39     10343864.19      3512287.05     10343536.66
#Sta/Elev= 30
  4366.5  413.62  4488.6  411.06  4586.4  407.04  4661.2  402.29  4734.3   400.2
  4772.5  400.28  4829.5  401.25  4953.4  400.81  4959.4  401.49  4974.5  400.31
  4981.4  397.35  4989.7  395.44  5001.8  394.84  5004.6  394.34  5007.8  394.84
  5025.9  399.85  5031.9  402.21    5047  400.06  5112.5  401.25  5149.6  402.77
  5170.9  403.49  5176.9  404.55    5192  404.35  5207.2  405.85  5394.3  406.82
  5504.6   410.3  5580.1  411.53    5601  410.46  5758.2  414.97  5872.1  415.44
#Mann= 7 ,-1 , 0
  4366.5     .05       0  4734.3      .1       0  4772.5     .12       0
  5001.8     .07       0  5007.8     .12       0  5149.6     .16       0
  5504.6     .05       0
Bank Sta=4974.5,5025.9
XS Rating Curve= 0 ,0
Exp/Cntr=0.3,0.1

Type RM Length L Ch R = 1 ,168315  ,1110,1110,1110
BEGIN DESCRIPTION:
CEDAR CREEK 165.0
END DESCRIPTION:
XS GIS Cut Line= 4
      3513513.75     10344333.57      3513101.46      10344143.7
       3512663.1     10343785.63      3512411.59      10343491.8
#Sta/Elev= 30
    4428  413.35  4528.9  410.67  4565.8  403.78  4583.2  405.36  4588.7  402.87
  4611.7   403.9  4617.2  401.93    4672   404.8    4694   400.6  4718.9  399.69
  4860.9  399.59  4968.6  400.07  4989.4  393.36  5003.7  394.81  5015.1  393.27
  5017.8  392.77  5021.1  393.27  5024.5  395.62  5032.5   394.7  5038.9  397.77
  5046.8  397.99  5053.3  401.18  5067.6  402.84    5082  399.81  5131.5  406.42
  5145.9  404.88    5245  410.58  5351.8  409.95  5477.4  409.94  5834.7  419.96
#Mann= 7 ,-1 , 0
    4428     .05       0  4718.9      .1       0  4860.9     .12       0
  5015.1     .07       0  5021.1     .12       0  5351.8     .16       0
  5477.4     .05       0
Bank Sta=4968.6,5053.3
XS Rating Curve= 0 ,0
Exp/Cntr=0.3,0.1

Type RM Length L Ch R = 1 ,167205  ,647,647,647
BEGIN DESCRIPTION:
CEDAR CREEK 164.0
END DESCRIPTION:
XS GIS Cut Line= 3
      3513718.01     10344449.95      3513727.05     10343649.66
      3513153.47      10342475.4
#Sta/Elev= 30
  3890.9  408.07  4169.2  410.93  4240.4  410.62  4489.3  407.63  4579.3  407.68
  4679.3  409.16  4754.9  408.12  4889.4  403.79  4946.2  399.18  4978.4  397.83
  4985.6  395.84  4991.2  392.81  4997.7  391.55  5000.4  391.05  5003.7  391.55
  5015.2   397.5  5030.7  398.95  5098.2  396.93  5120.8  397.24  5126.3  398.34
  5143.3  397.47  5165.8  398.81  5171.4  397.99  5238.9  398.68  5306.5  401.05
    5329  403.38  5383.3  405.36  5582.3  420.67  5679.5  423.54  5998.1  427.29
#Mann= 6 ,-1 , 0
  3890.9     .05       0  4240.4     .16       0  4997.7     .07       0
  5003.7     .16       0  5015.2     .12       0  5383.3     .16       0
Bank Sta=4978.4,5015.2
XS Rating Curve= 0 ,0
Exp/Cntr=0.3,0.1

Type RM Length L Ch R = 1 ,166558  ,831,831,831
BEGIN DESCRIPTION:
CEDAR CREEK 163.0
END DESCRIPTION:
XS GIS Cut Line= 3
      3513957.58     10344513.17      3514242.47     10343369.35
      3513907.91     10342270.73
#Sta/Elev= 30
  3524.7  408.51  3609.7     405  3629.3   402.6  3687.1  405.89  3763.3     405
  3804.5  400.57  3835.4  404.17  3870.1  405.01  3940.1  404.64  4017.5  398.93
  4058.8  402.86  4136.7   403.4  4187.9   402.6  4306.6  405.27  4639.5  402.62
  4683.1  401.19  4716.1  401.08  4843.1   400.2  4926.8  396.28  4983.3  397.04
  4992.5   393.9  4994.7  390.14  4997.5  389.64  5000.7  390.14  5025.1  397.54
  5101.5  396.12  5221.8  401.45  5412.8  415.92  5647.9  428.63  5851.9  433.02
#Mann= 10 ,-1 , 0
  3524.7     .05       0  3870.1     .16       0  4136.7     .05       0
  4639.5      .1       0  4683.1     .16       0  4716.1      .1       0
  4843.1     .12       0  4994.7     .07       0  5000.7     .12       0
  5221.8     .16       0
#XS Ineff= 2 , 0
         4306.69  405.52
Permanent Ineff=
       F       F
Bank Sta=4983.3,5025.1
XS Rating Curve= 0 ,0
Exp/Cntr=0.3,0.1

Type RM Length L Ch R = 1 ,165727  ,777,777,777
BEGIN DESCRIPTION:
CEDAR CREEK 162.0
END DESCRIPTION:
XS GIS Cut Line= 4
       3514228.4     10344578.29      3514686.75     10343875.15
      3514965.86     10343129.73      3514622.81     10342014.81
#Sta/Elev= 30
  3580.4  408.56  3595.3  408.96  3616.4  406.48  3709.9  405.21  4035.9  403.61
  4072.1  405.19  4144.6   405.3  4500.9  400.65  4555.6  400.27  4791.7  397.99
  4832.2  395.14  4877.2  394.04  4968.9  395.78  4978.7  395.67  4987.6   393.1
  4992.9     393  4997.1  388.84  4999.8  388.34  5003.1  388.84  5010.8  390.61
  5017.9  394.39  5032.1  395.96  5242.7  394.22  5321.9  395.79    5350  396.89
  5449.3  401.06  5636.3  406.14  6129.4  422.24  6207.6  423.01  6382.2  428.19
#Mann= 10 ,-1 , 0
  3580.4     .05       0  4500.9      .1       0  4555.6     .05       0
  4832.2     .16       0  4968.9     .12       0  4997.1     .07       0
  5003.1     .12       0  5321.9     .16       0    5350     .12       0
  5636.3     .16       0
Bank Sta=4978.7,5032.1
XS Rating Curve= 0 ,0
Exp/Cntr=0.3,0.1

Type RM Length L Ch R = 1 ,164950  ,1505,1505,1505
BEGIN DESCRIPTION:
CEDAR CREEK 161.0
END DESCRIPTION:
XS GIS Cut Line= 4
      3515926.51     10344302.51       3515752.9      10343108.1
      3515107.07     10342726.15      3514942.11     10341891.69
#Sta/Elev= 30
  3144.1  414.67  3286.5  415.17  3499.7  410.22  3589.6     408  3640.1  409.52
  3759.6  404.62  3933.8  400.14  4386.8  392.67  4680.4  394.12  4781.1  394.28
  4793.5  393.19  4808.3   388.6  4816.7  389.56    4824  393.96  4829.8  394.81
  4968.2  394.46  4978.1  393.01    4988  387.67  4990.7  387.17    4994  387.67
  5005.3  393.36  5014.2   394.8  5063.8  393.88  5157.4  398.18  5238.5  397.24
  5306.2  399.84  5408.6  402.23  5557.4  409.27  5722.1  419.36    5952  429.93
#Mann= 10 ,-1 , 0
  3144.1     .16       0  3499.7     .05       0  3759.6      .1       0
  3933.8     .05       0  4680.4     .12       0    4988     .07       0
    4994     .12       0  5306.2     .16       0  5557.4     .12       0
  5722.1     .16       0
Bank Sta=4968.2,5014.2
XS Rating Curve= 0 ,0
Exp/Cntr=0.3,0.1