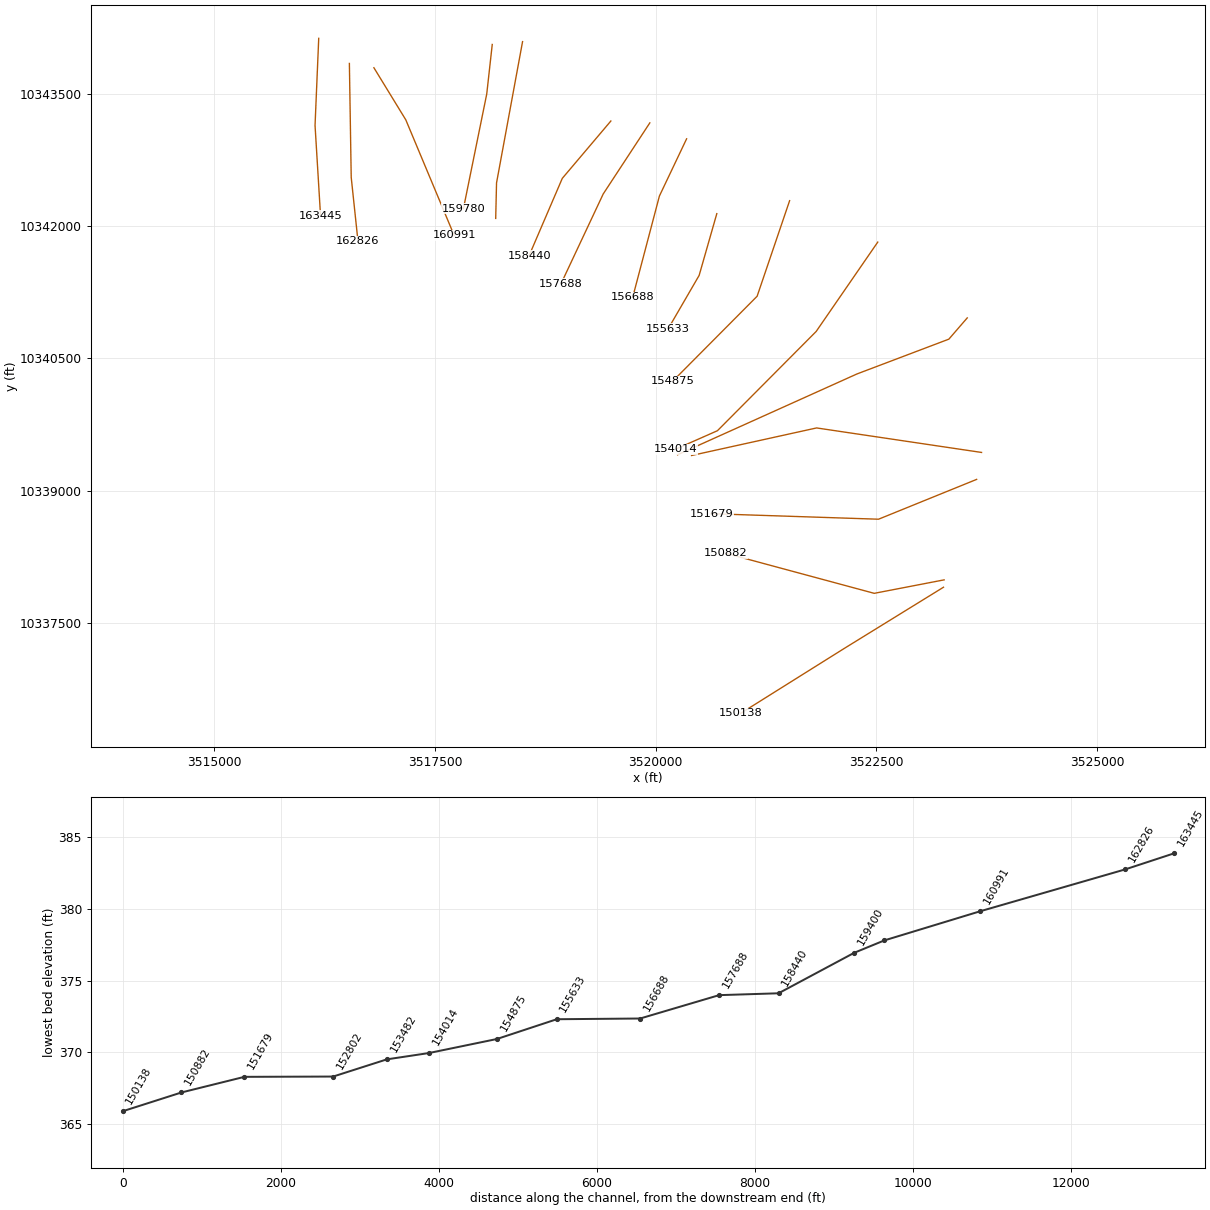
HEC-RAS study CEDAR CREEK.prj: CEDAR CREEK Base Level Engineering

--- CEDAR CREEK.g01 (geometry) --- (continued)

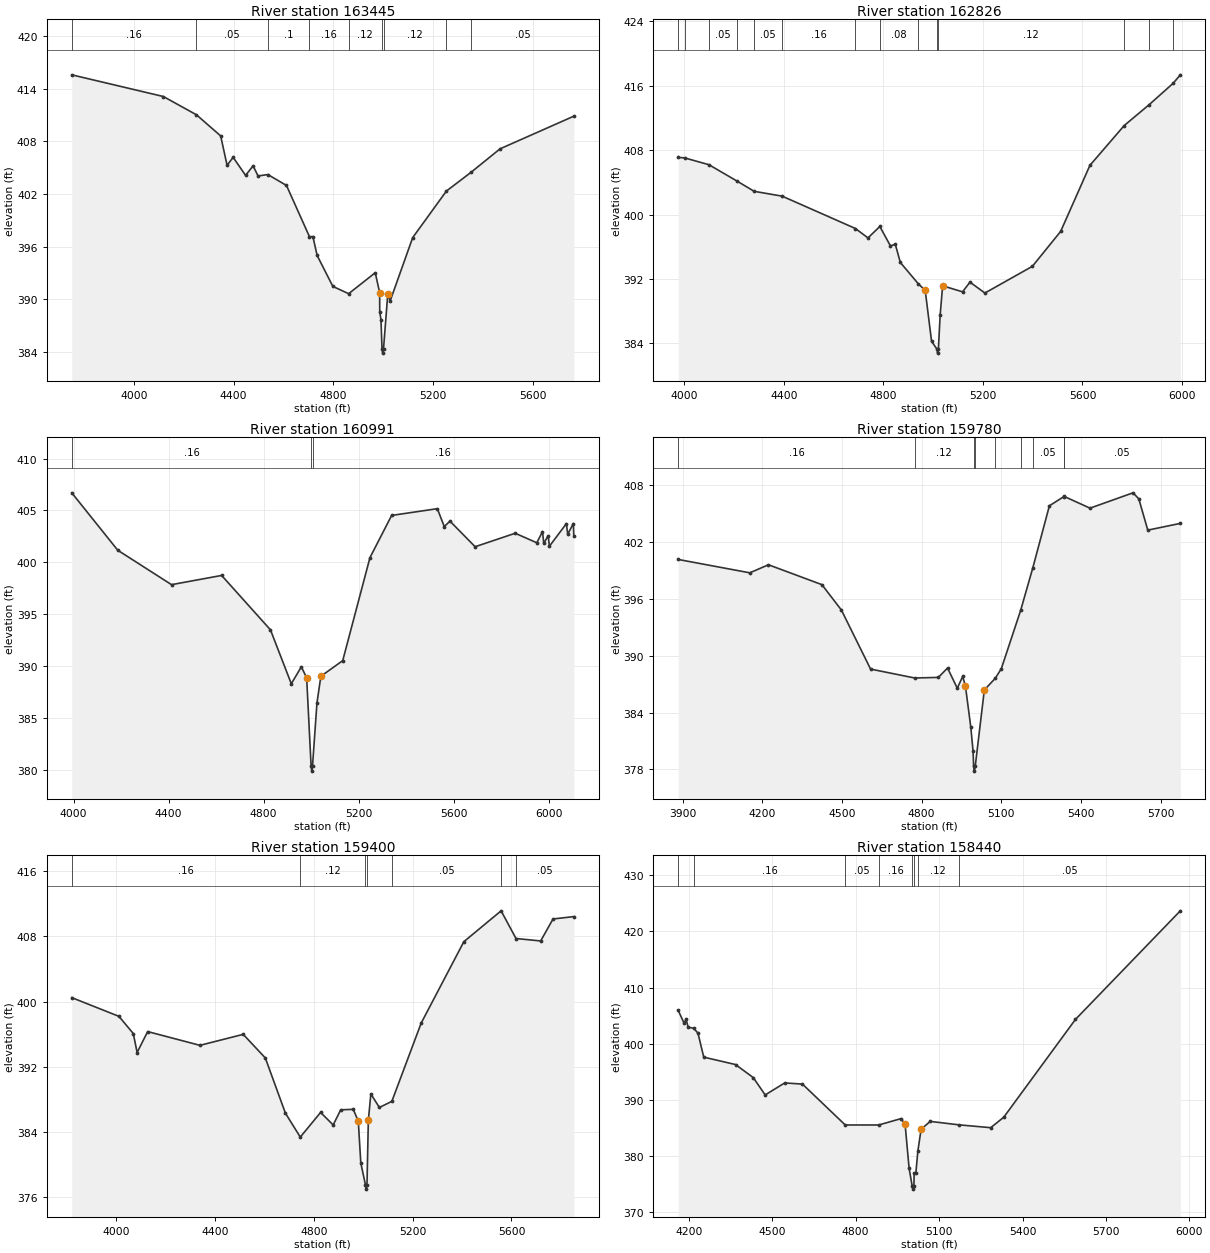
Type RM Length L Ch R = 1 ,163445  ,619,619,619
BEGIN DESCRIPTION:
CEDAR CREEK 159.0
END DESCRIPTION:
XS GIS Cut Line= 3
      3516183.46     10344128.97      3516141.79     10343142.82
      3516204.24     10342115.84
#Sta/Elev= 30
    3750  415.59  4117.7  413.12  4250.5  411.04  4347.9  408.63  4373.5  405.29
  4397.9  406.19  4447.9  404.14    4478  405.22    4498  404.07  4537.3  404.23
  4612.1  402.99  4704.3  397.16  4718.2  397.16  4735.1  395.02  4798.3  391.49
  4861.7  390.66  4968.6  393.05 4986.19  390.77  4986.5  388.63  4991.5  387.69
  4995.7  384.39  4998.4  383.89  5001.7  384.39  5018.7  390.58  5028.7  389.86
  5118.9  397.05  5254.2  402.35  5352.4  404.47  5469.6  407.16  5765.9  410.88
#Mann= 9 ,-1 , 0
    3750     .16       0  4250.5     .05       0  4537.3      .1       0
  4704.3     .16       0  4861.7     .12       0  4995.7     .07       0
  5001.7     .12       0  5254.2     .16       0  5352.4     .05       0
Bank Sta=4986.19,5018.7
XS Rating Curve= 0 ,0
Exp/Cntr=0.3,0.1

Type RM Length L Ch R = 1 ,162826  ,1835,1835,1835
BEGIN DESCRIPTION:
CEDAR CREEK 158.0
END DESCRIPTION:
XS GIS Cut Line= 3
      3516530.68     10343844.22      3516551.51     10342552.54
       3516627.9     10341830.32
#Sta/Elev= 30
  3975.3  407.09  4000.5  407.04  4098.6  406.19  4210.7  404.17  4280.6  402.88
    4393  402.28  4687.5  398.26    4738  397.09  4785.6  398.51    4828  396.11
    4848  396.28    4868  394.04  4940.5  391.38    4968  390.57  4993.5  384.25
    5015  383.27  5017.8  382.77    5021  383.27    5028  387.46    5038  391.14
    5118  390.39    5148  391.59    5208  390.24  5398.8  393.56  5512.5   397.9
  5630.1  406.11    5768  411.06  5866.3   413.6  5964.7  416.31  5993.4  417.36
#Mann= 14 ,-1 , 0
  3975.3     .16       0  4000.5      .1       0  4098.6     .05       0
  4210.7     .16       0  4280.6     .05       0    4393     .16       0
  4687.5     .05       0  4785.6     .08       0  4940.5     .12       0
    5015     .07       0    5021     .12       0    5768      .1       0
  5866.3     .16       0  5964.7      .1       0
Bank Sta=4968,5038
XS Rating Curve= 0 ,0
Exp/Cntr=0.3,0.1

Type RM Length L Ch R = 1 ,160991  ,1211,1211,1211
BEGIN DESCRIPTION:
CEDAR CREEK 157.0
END DESCRIPTION:
XS GIS Cut Line= 3
      3516808.44     10343795.62      3517169.57     10343205.32
      3517717.66     10341894.06
#Sta/Elev= 30
  3992.7   406.7  4186.3  401.16  4412.6  397.84  4623.5  398.73    4829  393.48
  4916.7  388.28  4958.9  389.91  4981.3  388.86    5000  380.35  5002.7  379.85
    5006  380.35  5024.7  386.43  5041.1     389  5133.1  390.51  5247.8  400.45
    5339  404.52  5531.3  405.17  5560.6  403.44  5584.4  403.97  5690.4   401.5
  5859.2   402.8  5950.1  401.88  5973.9  402.96  5979.3  401.82  5997.7  402.56
  6003.1  401.55  6074.6  403.73    6080  402.71  6103.8  403.73  6105.9   402.5
#Mann= 3 ,-1 , 0
  3992.7     .16       0    5000     .07       0    5006     .16       0
Bank Sta=4981.3,5041.1
XS Rating Curve= 0 ,0
Exp/Cntr=0.3,0.1

Type RM Length L Ch R = 1 ,159780  ,380,380,380
BEGIN DESCRIPTION:
CEDAR CREEK 155.0
END DESCRIPTION:
XS GIS Cut Line= 3
      3518148.73     10344059.47      3518086.23     10343496.98
      3517822.34     10342198.37
#Sta/Elev= 30
  3883.4  400.18  4152.9  398.77  4223.3  399.62  4424.5  397.52  4497.9  394.84
  4607.9   388.6  4773.9  387.66    4863  387.72  4897.8  388.71  4934.4  386.58
  4954.8  387.82    4965  386.84  4985.4  382.45  4993.9  379.93    4996  378.32
  4998.8  377.82    5002  378.32  5036.4   386.4  5077.4  387.62  5100.3  388.64
  5173.1   394.8    5219   399.3  5281.4  405.85  5334.7   406.8  5337.1  406.84
  5434.4   405.6  5596.3  407.22  5618.1  406.59    5652  403.28  5774.5  403.99
#Mann= 9 ,-1 , 0
  3883.4     .16       0  4773.9     .12       0    4996     .07       0
    5002     .12       0  5077.4     .05       0  5173.1     .16       0
    5219     .05       0  5334.7      .1       0  5337.1     .05       0
Bank Sta=4965,5036.4
XS Rating Curve= 0 ,0
Exp/Cntr=0.3,0.1

Type RM Length L Ch R = 1 ,159400  ,960,960,960
BEGIN DESCRIPTION:
CEDAR CREEK 154.0
END DESCRIPTION:
XS GIS Cut Line= 3
      3518492.11     10344091.67      3518197.34     10342490.04
      3518187.94     10342087.47
#Sta/Elev= 30
  3821.2  400.48    4012  398.18  4070.1  396.07  4085.6  393.74  4128.2  396.31
  4339.8  394.62  4514.8  395.97  4604.2  393.07  4685.5  386.29  4745.7  383.35
  4827.9  386.38  4878.7  384.84  4909.2   386.7    4960  386.76  4980.4  385.29
  4990.5  380.18  5009.5  377.46  5012.3  376.96  5015.5  377.46    5021   385.4
  5031.2  388.65  5065.6  386.99  5116.1  387.74  5234.9  397.36  5407.4  407.35
  5558.1  411.14  5618.4  407.74  5718.2  407.44  5768.2  410.14  5852.4  410.43
#Mann= 7 ,-1 , 0
  3821.2     .16       0  4745.7     .12       0  5009.5     .07       0
  5015.5     .12       0  5116.1     .05       0  5558.1      .1       0
  5618.4     .05       0
Bank Sta=4980.4,5021
XS Rating Curve= 0 ,0
Exp/Cntr=0.3,0.1

Type RM Length L Ch R = 1 ,158440  ,752,752,752
BEGIN DESCRIPTION:
CEDAR CREEK 152.0
END DESCRIPTION:
XS GIS Cut Line= 3
       3519492.1     10343191.64      3518942.11     10342541.64
      3518566.05     10341665.17
#Sta/Elev= 30
  4162.1  405.94  4183.5  403.64  4190.1  404.41  4197.8  402.95  4217.4  402.78
    4233  401.91  4253.8  397.63  4368.1  396.31  4431.8  393.99  4474.7   390.9
    4545  393.04  4608.7  392.83  4762.6  385.55  4882.9  385.55  4963.5  386.69
  4977.8  385.66  4992.1  377.87  5003.4  374.63  5006.2  374.13  5009.4  374.63
  5010.3  376.93  5016.3  376.93  5023.7   380.9  5035.3  384.78    5068  386.19
  5170.5  385.58  5285.6  385.07  5332.6  386.94  5590.3  404.35  5967.3  423.68
#Mann= 8 ,-1 , 0
  4162.1     .05       0  4217.4     .16       0  4762.6     .05       0
  4882.9     .16       0  5003.4     .07       0  5009.4     .16       0
  5023.7     .12       0  5170.5     .05       0
Bank Sta=4977.8,5035.3
XS Rating Curve= 0 ,0
Exp/Cntr=0.3,0.1

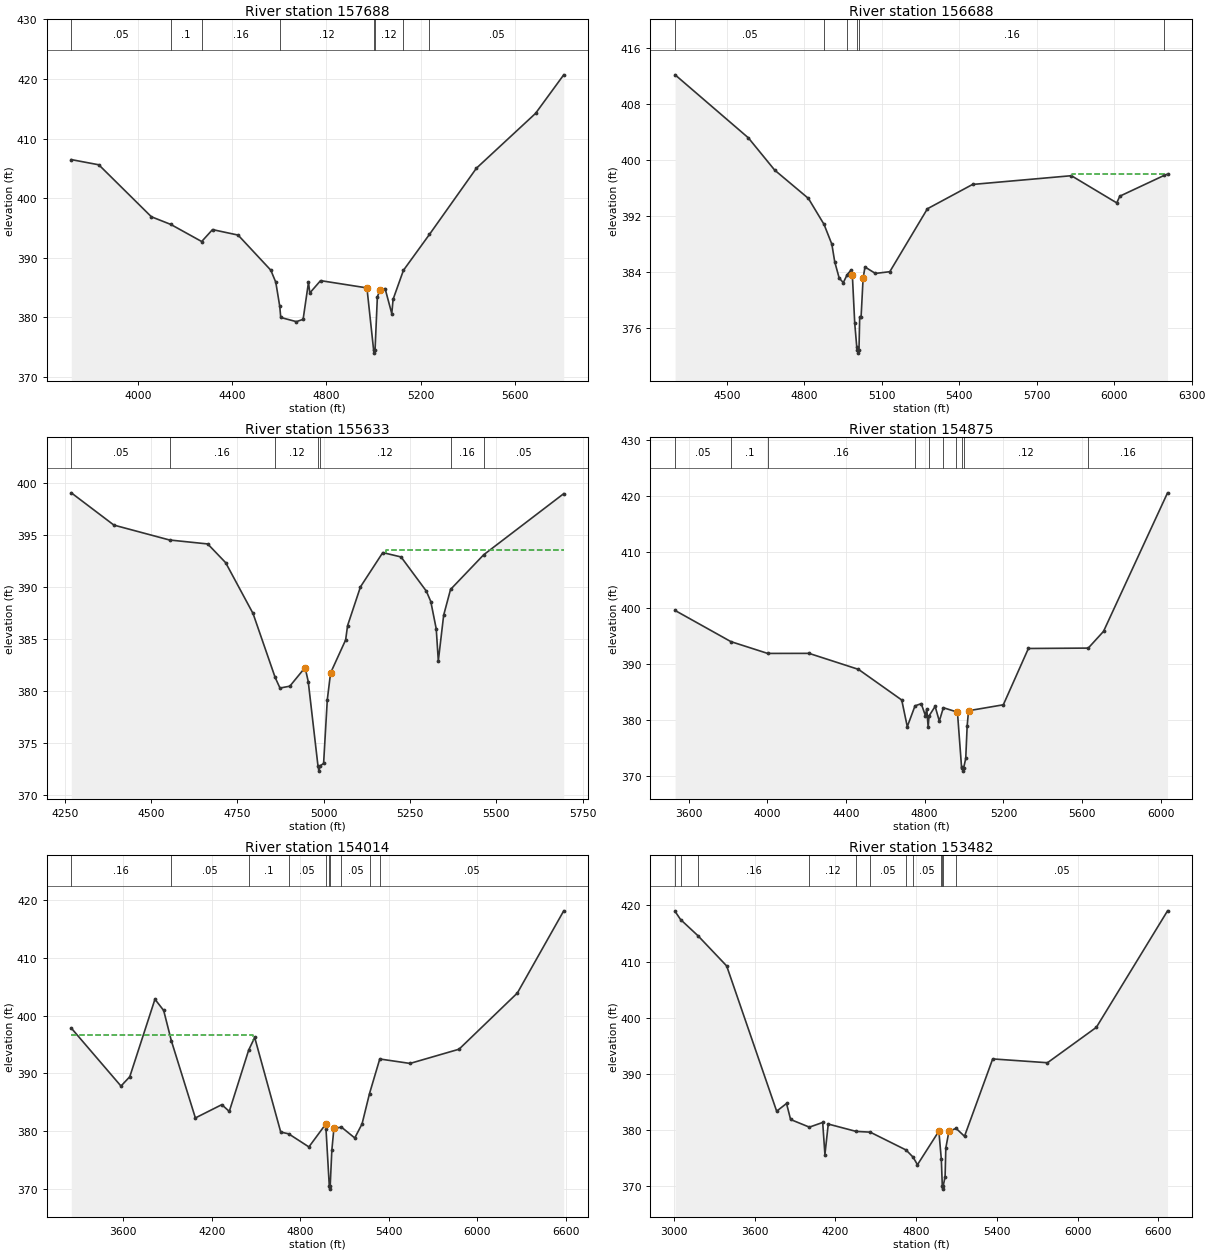
Type RM Length L Ch R = 1 ,157688  ,1000,1000,1000
BEGIN DESCRIPTION:
CEDAR CREEK 150.0
END DESCRIPTION:
XS GIS Cut Line= 3
      3519933.46     10343170.61      3519405.68     10342365.04
      3518927.39     10341346.07
#Sta/Elev= 30
  3717.7  406.46  3834.4  405.59  4057.5  396.87  4139.6  395.59  4270.8  392.72
  4316.7  394.72  4425.2   393.8    4564  387.91  4585.1  385.89  4601.9  381.85
  4606.1  379.98  4672.5  379.28    4701  379.67  4723.8  385.87  4729.4  384.09
    4775  386.16  4971.7  384.94  5000.1   374.5  5002.9     374  5006.1   374.5
  5015.9  383.41  5025.9  384.53  5048.7  384.83  5077.1  380.62  5082.6  383.02
  5126.5  387.89    5237  393.92  5435.9  405.01  5686.8  414.21  5806.4  420.68
#Mann= 8 ,-1 , 0
  3717.7     .05       0  4139.6      .1       0  4270.8     .16       0
  4601.9     .12       0  5000.1     .07       0  5006.1     .12       0
  5126.5     .16       0    5237     .05       0
Bank Sta=4971.7,5025.9
XS Rating Curve= 0 ,0
Exp/Cntr=0.3,0.1

Type RM Length L Ch R = 1 ,156688  ,1055,1055,1055
BEGIN DESCRIPTION:
CEDAR CREEK 149.0
END DESCRIPTION:
XS GIS Cut Line= 3
       3520350.1       10342990.      3520042.11     10342341.64
        3519739.      10341191.4
#Sta/Elev= 30
  4299.3  412.18  4582.9  403.17    4685  398.55  4815.6   394.5  4876.2  390.78
  4906.4  387.95  4917.6  385.42  4934.8  383.11  4950.7  382.45  4965.9   383.6
  4980.2  384.23  4985.8  383.54    4995  376.65    5003   373.2  5005.5  372.87
  5008.3  372.37  5011.5  372.87  5014.3  377.59  5019.7  377.59  5027.4  383.06
  5034.7  384.69    5075  383.77  5130.9  384.02  5276.5  393.02  5451.4   396.5
  5834.1  397.75  6009.9  393.86  6021.6  394.82  6193.3  397.79  6206.6  397.98
#Mann= 6 ,-1 , 0
  4299.3     .05       0  4876.2      .1       0  4965.9     .16       0
  5005.5     .07       0  5011.5     .16       0  6193.3     .05       0
#XS Ineff= 2 , 0
                         5836.85          397.96
Permanent Ineff=
       F       F
Bank Sta=4985.8,5027.4
XS Rating Curve= 0 ,0
Exp/Cntr=0.3,0.1

Type RM Length L Ch R = 1 ,155633  ,758,758,758
BEGIN DESCRIPTION:
CEDAR CREEK 147.0
END DESCRIPTION:
XS GIS Cut Line= 3
      3520692.09      10342141.6      3520492.11     10341441.64
      3520141.81     10340837.29
#Sta/Elev= 30
    4269  399.05  4392.5  395.95  4553.5  394.52  4664.2  394.14  4716.2  392.34
  4795.5  387.46  4859.4  381.33  4873.5   380.3  4902.1  380.48  4946.3  382.27
  4955.4  380.92  4983.6  372.82  4986.3  372.32  4989.6  372.82  4999.9  373.06
  5010.6  379.17  5020.1  381.75  5063.7  384.92  5069.4   386.3  5106.7  390.02
  5171.3  393.31  5224.3  392.89  5297.5  389.61  5310.4  388.61  5326.2  385.98
  5332.2  382.91  5347.7   387.3  5367.6  389.77  5463.6   393.1  5695.5  398.97
#Mann= 7 ,-1 , 0
    4269     .05       0  4553.5     .16       0  4859.4     .12       0
  4983.6     .07       0  4989.6     .12       0  5367.6     .16       0
  5463.6     .05       0
#XS Ineff= 2 , 0
                         5180.23          393.57
Permanent Ineff=
       F       F
Bank Sta=4946.3,5020.1
XS Rating Curve= 0 ,0
Exp/Cntr=0.3,0.1

Type RM Length L Ch R = 1 ,154875  ,861,861,861
BEGIN DESCRIPTION:
CEDAR CREEK 146.0
END DESCRIPTION:
XS GIS Cut Line= 3
       3521516.8     10342288.69      3521148.73     10341205.32
      3520192.08     10340241.61
#Sta/Elev= 30
  3531.9  399.56  3815.5  394.01  4002.2  391.91  4212.4  391.92  4463.5  389.07
  4683.4  383.61  4711.6  378.86  4750.9  382.57  4782.4  382.96  4803.6  380.84
  4810.6  381.99  4817.7  378.76  4822.1  380.77  4853.1  382.48  4874.3  379.85
  4894.9  382.24    4957  381.55  4966.2  381.56  4987.4  371.61  4991.5  371.44
  4994.2  370.94  4997.5  371.44  5008.6  373.19  5015.7  378.93  5022.8   381.7
  5199.6  382.76  5326.9  392.79  5631.1  392.86  5708.7  395.84    6034  420.52
#Mann= 10 ,-1 , 0
  3531.9     .05       0  3815.5      .1       0  4002.2     .16       0
  4750.9     .05       0  4822.1     .12       0  4894.9     .16       0
    4957     .12       0  4991.5     .07       0  4997.5     .12       0
  5631.1     .16       0
Bank Sta=4966.2,5022.8
XS Rating Curve= 0 ,0
Exp/Cntr=0.3,0.1

Type RM Length L Ch R = 1 ,154014  ,532,532,532
BEGIN DESCRIPTION:
CEDAR CREEK 146.01
END DESCRIPTION:
XS GIS Cut Line= 4
      3522515.04     10341819.08      3521817.32     10340805.82
      3520699.26     10339680.82      3520220.12     10339469.03
#Sta/Elev= 30
  3247.2  397.85  3584.3  387.81  3643.9  389.43  3814.7  402.85  3873.9   400.9
  3926.2  395.63  4088.9  382.29  4268.1  384.59  4318.9  383.42  4450.4  394.04
  4491.2  396.23  4667.9  379.84  4721.4  379.54  4858.9  377.27    4972  381.18
  4974.8  380.41  4997.3  370.46    5000  369.96  5003.3  370.46  5014.4  376.66
  5028.6   380.5    5080  380.69    5170  378.82  5219.5  381.26  5270.1  386.52
  5339.6   392.5  5544.7  391.73  5877.1  394.19  6272.7  403.92  6587.4  418.16
#Mann= 10 ,-1 , 0
  3247.2     .16       0  3926.2     .05       0  4450.4      .1       0
  4721.4     .05       0  4974.8     .16       0  4997.3     .07       0
  5003.3     .16       0    5080     .05       0  5270.1     .16       0
  5339.6     .05       0
#XS Ineff= 2 , 0
         4479.65  396.64
Permanent Ineff=
       F       F
Bank Sta=4972,5028.6
XS Rating Curve= 0 ,0
Exp/Cntr=0.3,0.1

Type RM Length L Ch R = 1 ,153482  ,680,680,680
BEGIN DESCRIPTION:
CEDAR CREEK 146.02
END DESCRIPTION:
XS GIS Cut Line= 4
      3523528.48     10340959.69      3523320.14      10340718.8
      3522278.47     10340323.83      3520247.19     10339408.02
#Sta/Elev= 30
  3007.7  418.93  3048.3  417.49  3178.1   414.6  3391.1  409.23  3762.6  383.39
    3836  384.76  3866.2  381.91  4005.8  380.55  4104.8  381.38  4121.4  375.68
  4146.2   381.1  4353.3  379.79  4457.8  379.66  4724.8  376.48  4777.2   375.2
  4809.2  373.86  4968.4  379.83  4986.7  374.83  4994.1  370.02  4996.8  369.52
  5000.1  370.02  5014.7  371.73  5020.2  376.86  5043.3  379.81  5096.6  380.33
    5159  378.92  5368.6  392.69  5775.8  392.01  6139.2  398.31  6668.4  419.04
#Mann= 12 ,-1 , 0
  3007.7     .16       0  3048.3     .05       0  3178.1     .16       0
  4005.8     .12       0  4353.3     .16       0  4457.8     .05       0
  4724.8     .16       0  4777.2     .05       0  4986.7     .16       0
  4994.1     .07       0  5000.1     .16       0  5096.6     .05       0
Bank Sta=4968.4,5043.3
XS Rating Curve= 0 ,0
Exp/Cntr=0.3,0.1

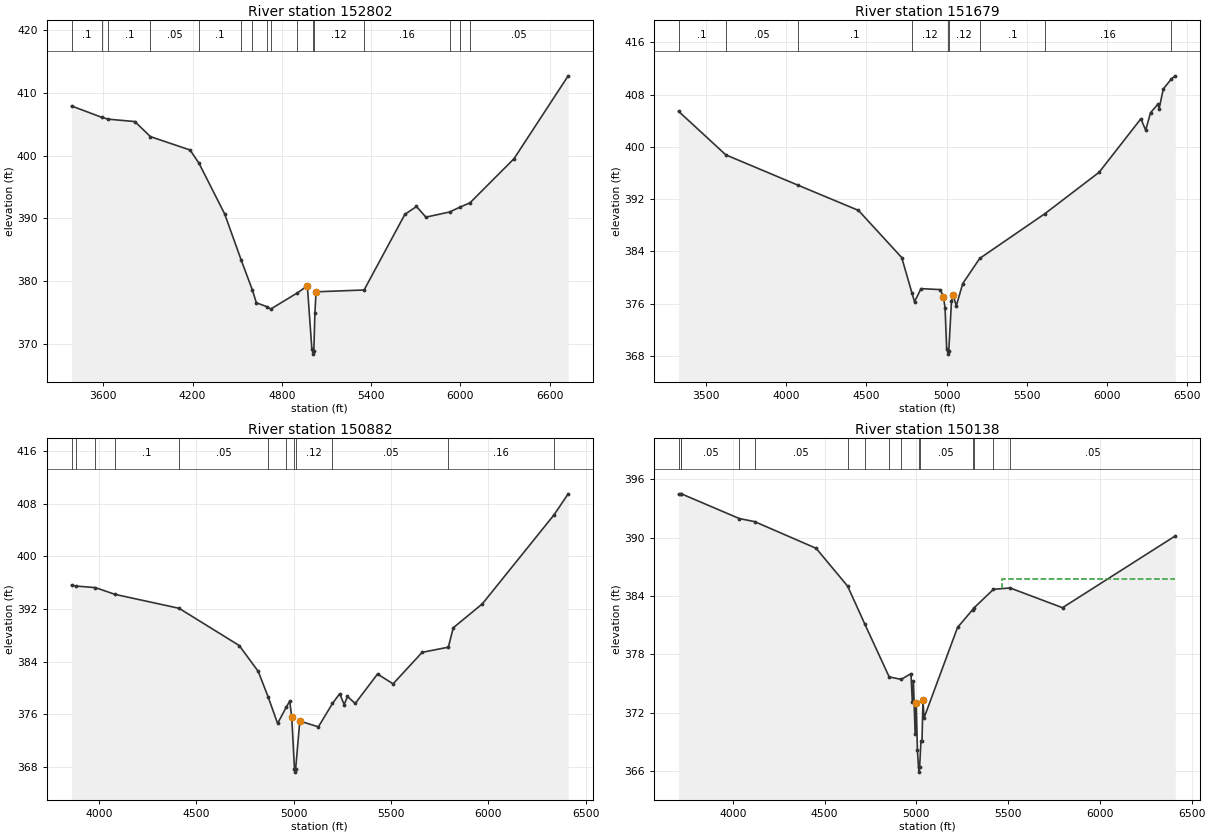
Type RM Length L Ch R = 1 ,152802  ,1123,1123,1123
BEGIN DESCRIPTION:
CEDAR CREEK 144.0
END DESCRIPTION:
XS GIS Cut Line= 3
      3523690.37     10339434.49      3521822.34     10339712.26
      3520406.35     10339399.91
#Sta/Elev= 30
  3386.4  407.94  3590.6  406.12  3633.1  405.83  3811.7  405.45  3917.4  403.04
  4183.3  400.91  4243.2   398.8  4415.8  390.71  4527.6  383.31  4602.1  378.57
    4629  376.52  4702.6  375.87  4725.3  375.51  4903.5  378.08  4971.9  379.21
  5002.2  369.12  5009.4  368.82  5012.1  368.32  5015.4  368.82  5022.5  374.82
  5030.2  378.27  5353.3  378.56  5627.3  390.63  5705.3  391.89  5768.6  390.19
  5927.7  391.01  5995.9  391.77  6064.8  392.47  6360.7  399.51    6725  412.75
#Mann= 16 ,-1 , 0
  3386.4      .1       0  3590.6     .05       0  3633.1      .1       0
  3917.4     .05       0  4243.2      .1       0  4527.6     .16       0
  4602.1      .1       0  4702.6     .12       0  4725.3      .1       0
  4903.5     .12       0  5009.4     .07       0  5015.4     .12       0
  5353.3     .16       0  5927.7      .1       0  5995.9     .16       0
  6064.8     .05       0
Bank Sta=4971.9,5030.2
XS Rating Curve= 0 ,0
Exp/Cntr=0.3,0.1

Type RM Length L Ch R = 1 ,151679  ,797,797,797
BEGIN DESCRIPTION:
CEDAR CREEK 143.0
END DESCRIPTION:
XS GIS Cut Line= 3
      3523634.83     10339128.92      3522523.73     10338677.54
      3520627.95     10338740.04
#Sta/Elev= 30
  3329.8  405.44  3624.3  398.78  4074.3  394.14  4450.8  390.29  4720.8  383.07
  4784.4  377.66  4800.6  376.31  4840.9  378.32  4960.9  378.17    4981  377.07
    4991  375.33    5001  369.04    5008   368.8  5010.7   368.3    5014   368.8
    5031  376.37    5041  377.37    5061  375.68    5101  379.09    5207  382.94
  5614.8  389.81  5951.5  396.12  6211.6   404.3  6241.6  402.56  6271.7  405.23
  6319.8  406.58  6324.8   405.8  6351.7  408.87  6402.1  410.41  6425.9  410.87
#Mann= 9 ,-1 , 0
  3329.8      .1       0  3624.3     .05       0  4074.3      .1       0
  4784.4     .12       0    5008     .07       0    5014     .12       0
    5207      .1       0  5614.8     .16       0  6402.1     .05       0
Bank Sta=4981,5041
XS Rating Curve= 0 ,0
Exp/Cntr=0.3,0.1

Type RM Length L Ch R = 1 ,150882  ,744,744,744
BEGIN DESCRIPTION:
CEDAR CREEK 142.0
END DESCRIPTION:
XS GIS Cut Line= 3
      3523266.76     10337990.03      3522475.12     10337837.26
      3520792.13     10338291.64
#Sta/Elev= 30
    3860   395.6  3883.3  395.48  3983.1  395.24    4083  394.22  4412.2   392.1
  4721.2  386.44  4818.4  382.52    4870  378.59    4918  374.61  4962.7   377.1
  4980.1  377.99  4990.5   375.6  5004.6  367.71  5007.3  367.21  5010.6  367.71
  5031.9  374.97  5127.3  374.09  5199.7  377.65  5236.6  379.12  5259.8  377.47
  5276.5   378.7  5316.4  377.64  5430.9  382.12  5510.7  380.62    5660  385.41
  5794.4  386.19  5819.6  389.14  5968.8  392.77  6337.5  406.32  6409.5  409.49
#Mann= 12 ,-1 , 0
    3860     .05       0  3883.3      .1       0  3983.1     .05       0
    4083      .1       0  4412.2     .05       0    4870      .1       0
  4962.7     .12       0  5004.6     .07       0  5010.6     .12       0
  5199.7     .05       0  5794.4     .16       0  6337.5     .05       0
Bank Sta=4990.5,5031.9
XS Rating Curve= 0 ,0
Exp/Cntr=0.3,0.1

Type RM Length L Ch R = 1 ,150138  ,183,183,183
BEGIN DESCRIPTION:
CEDAR CREEK 141.0
END DESCRIPTION:
XS GIS Cut Line= 3
      3523259.81     10337906.68      3522134.84     10337212.26
      3520961.65     10336476.41
#Sta/Elev= 30
  3703.8  394.48  3718.4  394.51  3718.9  394.52  4034.6  391.98  4118.4  391.66
  4453.2  388.92    4625  385.03  4717.7  381.17  4851.6  375.69  4917.4  375.44
  4970.3  376.03  4977.8  373.12  4983.7  375.24  4993.2   369.8  4999.1  372.99
  5005.5  368.13  5011.5   366.4  5014.2   365.9  5017.5   366.4  5024.5  369.06
  5030.4  369.06  5035.7   373.3  5041.6  371.48  5224.2  380.78    5306   382.6
  5313.3  382.78  5419.8   384.7  5510.5  384.84  5796.3  382.81  6410.7  390.19
#Mann= 15 ,-1 , 0
  3703.8     .05       0  3718.4      .1       0  3718.9     .05       0
  4034.6      .1       0  4118.4     .05       0    4625      .1       0
  4717.7     .05       0  4851.6     .12       0  4917.4     .05       0
  5011.5     .04       0  5017.5     .05       0    5306      .1       0
  5313.3     .05       0  5419.8      .1       0  5510.5     .05       0
#XS Ineff= 2 , 0
                         5466.57          385.79
Permanent Ineff=
       F       F
Bank Sta=4999.1,5035.7
XS Rating Curve= 0 ,0
Exp/Cntr=0.3,0.1