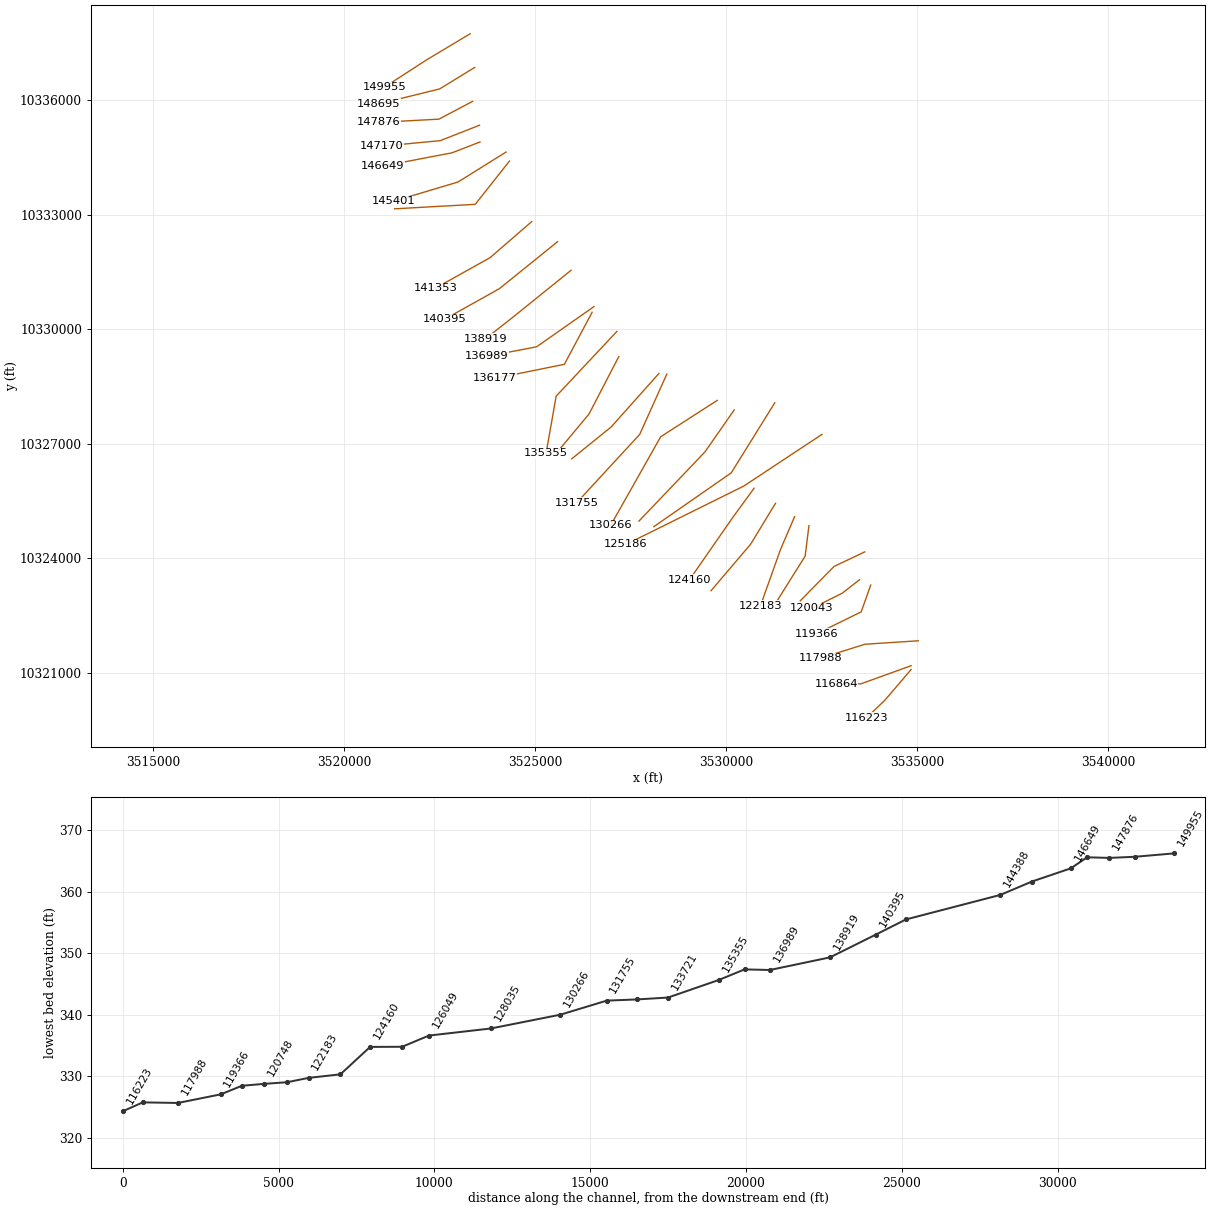
HEC-RAS study CEDAR CREEK.prj: CEDAR CREEK Base Level Engineering

--- CEDAR CREEK.g01 (geometry) --- (continued)

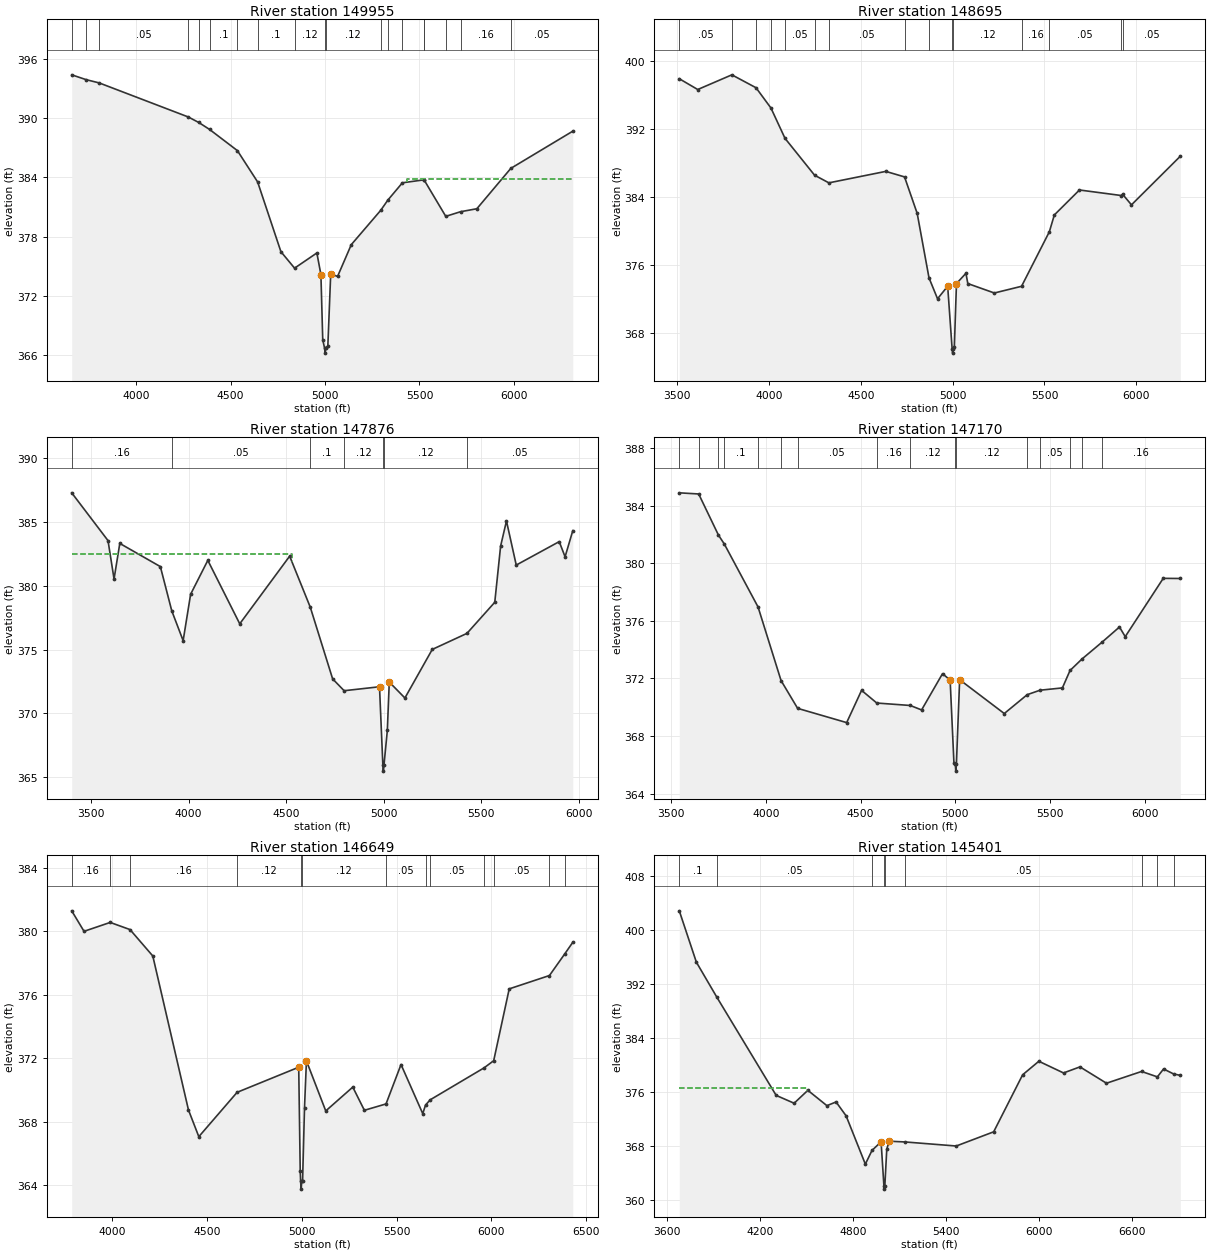
Type RM Length L Ch R = 1 ,149955  ,1260,1260,1260
BEGIN DESCRIPTION:
CEDAR CREEK 140.0
END DESCRIPTION:
XS GIS Cut Line= 3
      3523301.47     10337733.07      3522155.68      10337045.6
      3521051.52     10336330.33
#Sta/Elev= 30
  3659.5  394.39  3735.9   393.9    3805  393.57  4276.3  390.12  4331.9  389.56
  4388.8  388.86  4536.3  386.71  4643.3  383.54  4766.6  376.47  4838.9   374.8
  4956.9  376.34  4978.3  374.15    4988  367.55  4997.8  366.69  5000.6  366.19
  5003.8  366.69    5015  366.94  5030.2  374.23  5066.4  373.96    5139  377.18
  5294.8  380.66  5332.7   381.7  5409.6  383.45  5524.3  383.75    5525  383.72
  5639.1  380.05  5717.4  380.52  5803.6  380.82  5983.3  384.91  6311.3  388.68
#Mann= 19 ,-1 , 0
  3659.5     .05       0  3735.9      .1       0    3805     .05       0
  4276.3      .1       0  4331.9     .05       0  4388.8      .1       0
  4536.3     .16       0  4643.3      .1       0  4838.9     .12       0
  4997.8     .07       0  5003.8     .12       0  5294.8      .1       0
  5332.7     .05       0  5409.6      .1       0  5524.3     .05       0
    5525      .1       0  5639.1     .05       0  5717.4     .16       0
  5983.3     .05       0
#XS Ineff= 2 , 0
                         5433.87          383.83
Permanent Ineff=
       F       F
Bank Sta=4978.3,5030.2
XS Rating Curve= 0 ,0
Exp/Cntr=0.3,0.1

Type RM Length L Ch R = 1 ,148695  ,819,819,819
BEGIN DESCRIPTION:
CEDAR CREEK 139.0
END DESCRIPTION:
XS GIS Cut Line= 3
      3523419.53     10336851.13       3522502.9     10336288.65
      3520898.76     10335892.82
#Sta/Elev= 30
    3512  397.95  3612.4  396.68  3798.2  398.41  3929.7  396.89    4011   394.5
  4087.5  390.93  4248.5  386.59  4326.3  385.69  4636.1  387.04  4738.2  386.39
  4807.1  382.09  4871.4   374.5  4917.9  372.04    4973  373.52  4997.3  366.14
    5000  365.64  5003.3  366.14  5009.3  366.38  5020.9  373.83  5072.4  375.04
  5082.7  373.83    5227  372.72  5375.2  373.51  5526.7  379.94  5553.6  381.91
  5690.4  384.85  5917.7   384.2  5925.1  384.35  5973.5   383.1  6239.7  388.83
#Mann= 15 ,-1 , 0
    3512     .05       0  3798.2      .1       0  3929.7     .05       0
    4011      .1       0  4087.5     .05       0  4248.5      .1       0
  4326.3     .05       0  4738.2     .16       0  4871.4     .12       0
  4997.3     .07       0  5003.3     .12       0  5375.2     .16       0
  5526.7     .05       0  5917.7      .1       0  5925.1     .05       0
Bank Sta=4973,5020.9
XS Rating Curve= 0 ,0
Exp/Cntr=0.3,0.1

Type RM Length L Ch R = 1 ,147876  ,706,706,706
BEGIN DESCRIPTION:
CEDAR CREEK 137.0
END DESCRIPTION:
XS GIS Cut Line= 3
      3523364.02     10335962.26      3522482.07     10335496.98
      3520912.63     10335413.65
#Sta/Elev= 30
  3400.4   387.3  3586.5  383.55  3617.4  380.54  3646.9  383.33  3854.8  381.51
  3913.3  378.04  3971.6   375.7    4010  379.34  4098.1     382  4261.8  377.02
  4517.7  382.33  4623.5  378.32    4738   372.7  4796.9  371.77  4978.3  372.08
  4995.4  365.96  4998.1  365.46  5001.4  365.96  5018.4  368.65  5028.4  372.45
  5108.5   371.2  5248.7  375.01  5426.6  376.27  5569.2  378.71  5599.2  383.12
  5629.2  385.09  5679.3  381.63  5899.6  383.47  5929.7  382.28  5969.2  384.33
#Mann= 7 ,-1 , 0
  3400.4     .16       0  3913.3     .05       0  4623.5      .1       0
  4796.9     .12       0  4995.4     .07       0  5001.4     .12       0
  5426.6     .05       0
#XS Ineff= 2 , 0
         4530.52   382.5
Permanent Ineff=
       F       F
Bank Sta=4978.3,5028.4
XS Rating Curve= 0 ,0
Exp/Cntr=0.3,0.1

Type RM Length L Ch R = 1 ,147170  ,521,521,521
BEGIN DESCRIPTION:
CEDAR CREEK 136.0
END DESCRIPTION:
XS GIS Cut Line= 3
      3523544.55     10335337.26      3522516.79     10334934.48
      3520982.07     10334788.65
#Sta/Elev= 30
  3543.1  384.89  3645.5  384.81    3750  381.95    3781  381.33    3959  376.96
  4080.4  371.85  4167.9  369.92  4426.8  368.93  4505.5  371.17  4585.8  370.29
  4762.5  370.12  4822.4  369.81  4932.9  372.33  4973.1  371.88  4993.2  366.12
  5000.2  366.06    5003  365.56  5006.2  366.06  5023.3  371.91  5258.9  369.56
    5380  370.87  5447.7  371.18  5565.8  371.34  5606.1  372.55  5669.4  373.35
  5775.4  374.52  5867.1  375.57  5897.5   374.9  6098.2  378.95  6188.6  378.94
#Mann= 16 ,-1 , 0
  3543.1     .16       0  3645.5      .1       0    3750     .05       0
    3781      .1       0    3959     .16       0  4080.4      .1       0
  4167.9     .05       0  4585.8     .16       0  4762.5     .12       0
  5000.2     .07       0  5006.2     .12       0    5380      .1       0
  5447.7     .05       0  5606.1     .16       0  5669.4     .05       0
  5775.4     .16       0
Bank Sta=4973.1,5023.3
XS Rating Curve= 0 ,0
Exp/Cntr=0.3,0.1

Type RM Length L Ch R = 1 ,146649  ,1248,1248,1248
BEGIN DESCRIPTION:
CEDAR CREEK 135.0
END DESCRIPTION:
XS GIS Cut Line= 3
      3523558.43     10334899.75      3522822.34     10334615.04
      3521002.91     10334267.82
#Sta/Elev= 30
  3787.4  381.28  3852.3  379.99  3990.3  380.55  4094.7   380.1  4214.8  378.44
  4402.9  368.75  4457.4  367.07  4659.2  369.86  4984.1  371.44    4992  364.92
  4994.1  364.27  4996.9  363.77  5000.1  364.27  5004.5  364.31  5014.6   368.9
  5024.8  371.84  5126.6  368.69  5269.1  370.19  5330.2  368.73  5444.3  369.13
  5523.4  371.61  5637.9  368.52  5652.6  369.06  5677.2  369.39  5961.2   371.4
  6011.9  371.85  6093.8  376.37  6305.9  377.21  6385.9  378.56  6428.9   379.3
#Mann= 13 ,-1 , 0
  3787.4     .16       0  3990.3      .1       0  4094.7     .16       0
  4659.2     .12       0  4994.1     .07       0  5000.1     .12       0
  5444.3     .05       0  5652.6      .1       0  5677.2     .05       0
  5961.2     .16       0  6011.9     .05       0  6305.9      .1       0
  6385.9     .05       0
Bank Sta=4984.1,5024.8
XS Rating Curve= 0 ,0
Exp/Cntr=0.3,0.1

Type RM Length L Ch R = 1 ,145401  ,1013,1013,1013
BEGIN DESCRIPTION:
CEDAR CREEK 134.0
END DESCRIPTION:
XS GIS Cut Line= 3
      3524238.98     10334635.85      3522982.07     10333851.15
      3521308.41     10333351.14
#Sta/Elev= 30
  3679.9  402.81    3790  395.21  3922.1  390.02  4304.2   375.5  4419.8  374.34
  4508.3  376.25  4631.1  373.98  4690.1  374.53  4754.8  372.47  4878.7  365.33
  4921.6  367.36  4980.1  368.63  4998.3  362.13  5001.1  361.63  5004.3  362.13
  5016.7  367.53  5031.9  368.72  5134.9  368.61  5464.3  368.01  5705.5  370.11
  5892.2  378.55  5996.6  380.55  6155.6  378.82  6261.5  379.72  6432.4   377.3
  6658.4  379.04  6760.3  378.24  6800.2  379.41  6864.3  378.68  6908.4  378.46
#Mann= 9 ,-1 , 0
  3679.9      .1       0  3922.1     .05       0  4921.6     .16       0
  4998.3     .07       0  5004.3     .16       0  5134.9     .05       0
  6658.4     .16       0  6760.3     .05       0  6864.3      .1       0
#XS Ineff= 2 , 0
         4499.64  376.55
Permanent Ineff=
       F       F
Bank Sta=4980.1,5031.9
XS Rating Curve= 0 ,0
Exp/Cntr=0.3,0.1

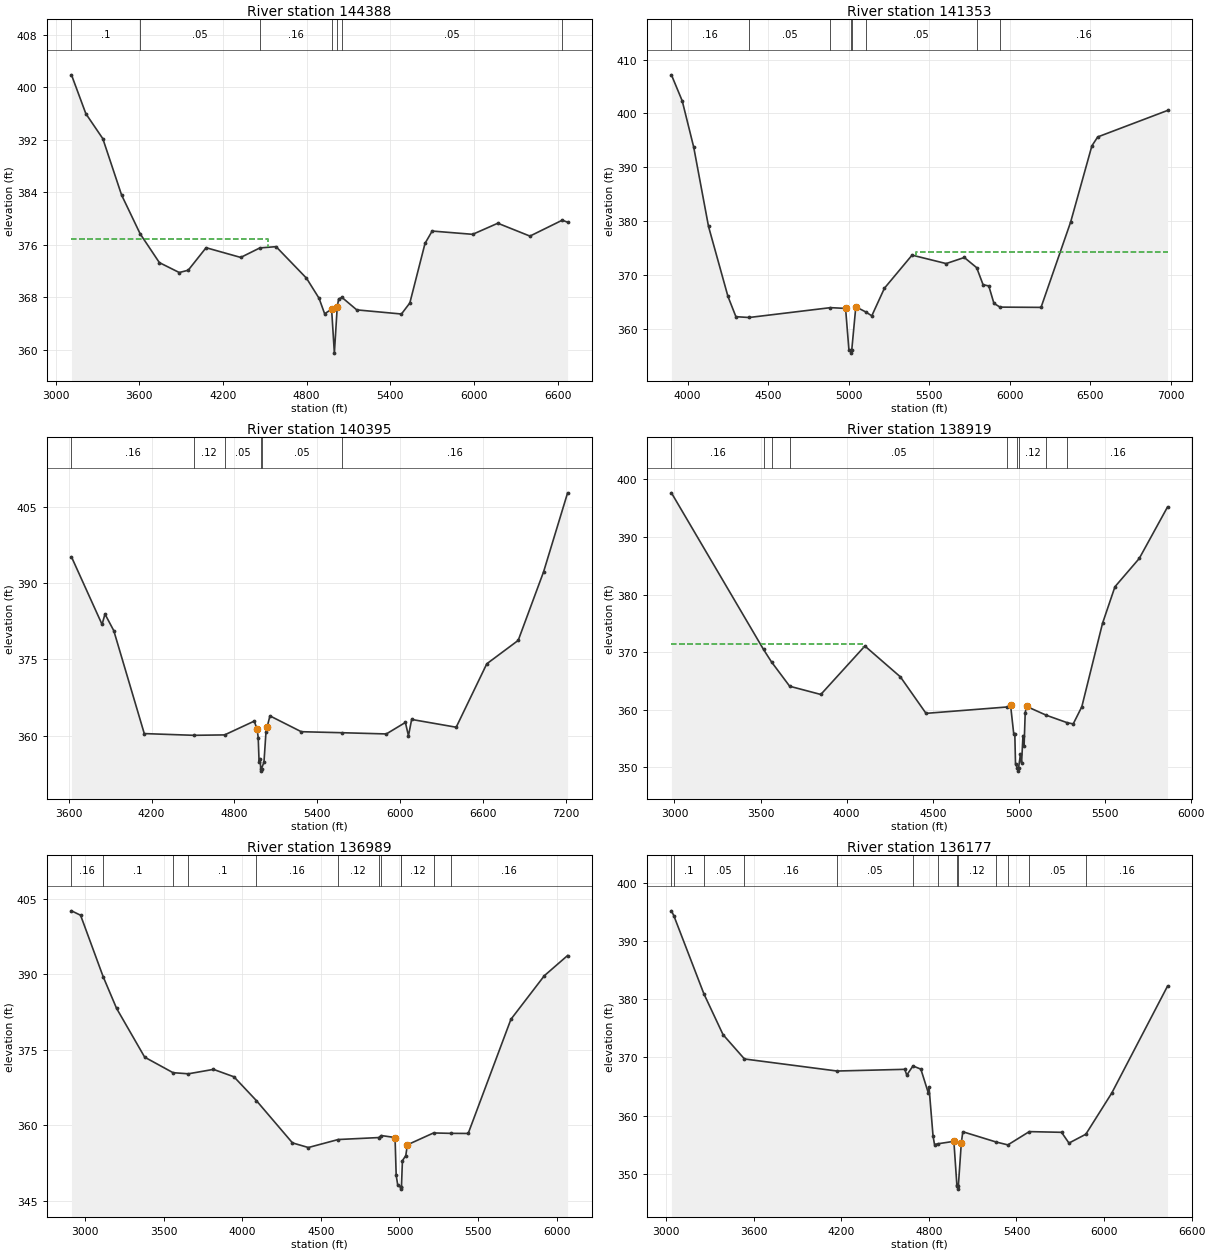
Type RM Length L Ch R = 1 ,144388  ,3035,3035,3035
BEGIN DESCRIPTION:
CEDAR CREEK 133.0
END DESCRIPTION:
XS GIS Cut Line= 3
      3524329.26     10334399.73      3523433.45     10333267.82
      3521322.35     10333149.76
#Sta/Elev= 30
  3113.9  401.86    3217  395.94  3338.8  392.13  3473.4  383.54  3606.4  377.64
  3744.3  373.25  3886.9  371.74    3951  372.09  4079.3  375.52  4327.6  374.04
    4465  375.49  4581.1  375.68  4799.1  370.88  4889.3  367.82  4929.3  365.46
  4979.4  366.15  4999.2  359.46  5019.5  366.43  5029.5  367.71  5053.5  367.95
  5159.7  366.05  5480.2  365.42  5540.3   367.1  5649.3  376.18  5700.5  378.06
    5991  377.56  6171.3  379.25  6401.6  377.29    6633  379.71  6671.8  379.41
#Mann= 7 ,-1 , 0
  3113.9      .1       0  3606.4     .05       0    4465     .16       0
  4979.4     .07       0  5019.5     .16       0  5053.5     .05       0
    6633      .1       0
#XS Ineff= 2 , 0
         4523.26  376.86
Permanent Ineff=
       F       F
Bank Sta=4979.4,5019.5
XS Rating Curve= 0 ,0
Exp/Cntr=0.3,0.1

Type RM Length L Ch R = 1 ,141353  ,958,958,958
BEGIN DESCRIPTION:
CEDAR CREEK 132.1
END DESCRIPTION:
XS GIS Cut Line= 3
      3524912.61     10332816.42      3523822.34     10331871.98
       3522391.8     10331073.38
#Sta/Elev= 30
  3899.2  407.18  3966.3  402.34  4037.6  393.75  4129.7     379  4250.3  366.01
  4299.7  362.24  4381.6  362.09    4887  363.92  4980.7  363.78  5001.6  356.03
  5012.8  355.97  5015.6  355.47  5018.8  355.97  5044.3  364.08  5105.5  363.13
  5143.5   362.4  5221.9  367.53  5393.5  373.68  5605.3  372.11    5718  373.24
  5794.7  371.35  5834.4  368.19    5870  367.95  5901.9  364.72  5939.6  364.02
  6194.4  363.97  6378.4  379.84  6510.1  393.98  6546.3  395.64    6980  400.56
#Mann= 8 ,-1 , 0
  3899.2     .16       0  4381.6     .05       0    4887     .12       0
  5012.8     .07       0  5018.8     .12       0  5105.5     .05       0
  5794.7      .1       0  5939.6     .16       0
#XS Ineff= 2 , 0
                         5417.88          374.19
Permanent Ineff=
       F       F
Bank Sta=4980.7,5044.3
XS Rating Curve= 0 ,0
Exp/Cntr=0.3,0.1

Type RM Length L Ch R = 1 ,140395  ,1476,1476,1476
BEGIN DESCRIPTION:
CEDAR CREEK 132.0
END DESCRIPTION:
XS GIS Cut Line= 3
       3525586.2     10332288.62       3524065.4     10331059.48
      3522635.96      10330261.5
#Sta/Elev= 30
  3619.7  395.15  3841.3  381.86  3862.2  383.91  3926.1  380.64  4146.8  360.41
  4504.8  360.07  4728.5  360.15  4943.1  362.86  4963.9  361.25  4971.8  359.64
  4978.3  354.77  4986.2  355.48  4989.7  353.53  4992.4  353.03  4995.7  353.53
  5013.6   354.8  5027.9  360.63  5035.8  361.62  5056.6  363.89  5283.7  360.78
  5579.9  360.58  5899.6  360.34  6037.5   362.6  6059.9  359.98  6082.8  363.19
  6405.4  361.66    6627  374.13  6854.4  378.73  7038.3  392.22  7212.2  407.74
#Mann= 6 ,-1 , 0
  3619.7     .16       0  4504.8     .12       0  4728.5     .05       0
  4989.7    .035       0  4995.7     .05       0  5579.9     .16       0
Bank Sta=4963.9,5035.8
XS Rating Curve= 0 ,0
Exp/Cntr=0.3,0.1

Type RM Length L Ch R = 1 ,138919  ,1930,1930,1930
BEGIN DESCRIPTION:
CEDAR CREEK 131.0
END DESCRIPTION:
XS GIS Cut Line= 3
      3525942.11     10331541.65      3524392.11     10330291.64
      3523692.08     10329741.62
#Sta/Elev= 30
  2982.3  397.68  3517.3  370.46  3563.8  368.29  3669.2  364.07    3850  362.64
  4105.9  371.06  4312.2   365.7    4461  359.36  4933.5  360.47    4952   360.8
  4970.3  355.84  4976.7  355.84  4980.8  350.56  4992.2  349.82    4995  349.32
  4998.2  349.82  5009.7  352.29    5016  350.72  5024.1   355.5  5030.5   353.6
  5037.1  359.49  5044.9  360.57  5160.6  359.02  5282.5  357.72    5316  357.53
  5365.8   360.5    5486  374.99  5558.3  381.36  5699.3  386.27  5863.8  395.23
#Mann= 9 ,-1 , 0
  2982.3     .16       0  3517.3     .05       0  3563.8      .1       0
  3669.2     .05       0  4933.5     .12       0  4992.2     .07       0
  4998.2     .12       0  5160.6     .05       0  5282.5     .16       0
#XS Ineff= 2 , 0
         4097.38  371.39
Permanent Ineff=
       F       F
Bank Sta=4952,5044.9
XS Rating Curve= 0 ,0
Exp/Cntr=0.3,0.1

Type RM Length L Ch R = 1 ,136989  ,812,812,812
BEGIN DESCRIPTION:
CEDAR CREEK 130.0
END DESCRIPTION:
XS GIS Cut Line= 3
       3526542.1     10330591.64      3525040.72     10329538.86
      3523740.74     10329288.87
#Sta/Elev= 30
  2912.6  402.65  2970.6  401.77  3114.3  389.54  3199.8  383.23  3378.5  373.53
  3559.1  370.44  3656.6  370.22  3816.4   371.1  3946.8  369.62    4089   364.9
    4319  356.47  4420.1  355.55  4610.1  357.14  4866.8  357.53  4884.3  357.93
  4971.9  357.54  4979.1  350.02  4989.3  348.02  5006.7  347.77  5009.4  347.27
  5012.7  347.77  5018.8  352.93  5040.2  353.95  5050.4  356.09  5216.9  358.45
  5325.3  358.37  5437.4  358.35  5709.2  381.06    5922  389.74  6070.1  393.76
#Mann= 12 ,-1 , 0
  2912.6     .16       0  3114.3      .1       0  3559.1     .05       0
  3656.6      .1       0    4089     .16       0  4610.1     .12       0
  4866.8     .16       0  4884.3     .12       0  5006.7     .07       0
  5012.7     .12       0  5216.9     .05       0  5325.3     .16       0
Bank Sta=4971.9,5050.4
XS Rating Curve= 0 ,0
Exp/Cntr=0.3,0.1

Type RM Length L Ch R = 1 ,136177  ,822,822,822
BEGIN DESCRIPTION:
CEDAR CREEK 128.0
END DESCRIPTION:
XS GIS Cut Line= 3
      3526492.12     10330441.66      3525766.79     10329080.32
      3523947.36     10328712.26
#Sta/Elev= 30
    3036  395.18  3052.2  394.37  3258.4  380.93  3389.9   373.9  3536.4  369.73
  4170.6  367.66  4634.3  367.95  4648.5  366.96  4690.7  368.53  4744.9  367.98
  4795.6  363.92  4800.7   364.9  4828.2  356.53  4838.4  355.03  4861.3  355.16
    4971  355.58  4991.4  348.13  4995.5  347.87  4998.3  347.37  5001.5  347.87
    5022   355.3  5032.2  357.23  5259.7  355.47  5340.9  354.97  5487.6  357.25
  5708.7  357.13  5759.4  355.28  5874.9   356.8  6052.5  363.87  6434.8  382.25
#Mann= 13 ,-1 , 0
    3036     .16       0  3052.2      .1       0  3258.4     .05       0
  3536.4     .16       0  4170.6     .05       0  4690.7      .1       0
  4861.3     .12       0  4995.5     .07       0  5001.5     .12       0
  5259.7     .05       0  5340.9     .16       0  5487.6     .05       0
  5874.9     .16       0
Bank Sta=4971,5022
XS Rating Curve= 0 ,0
Exp/Cntr=0.3,0.1

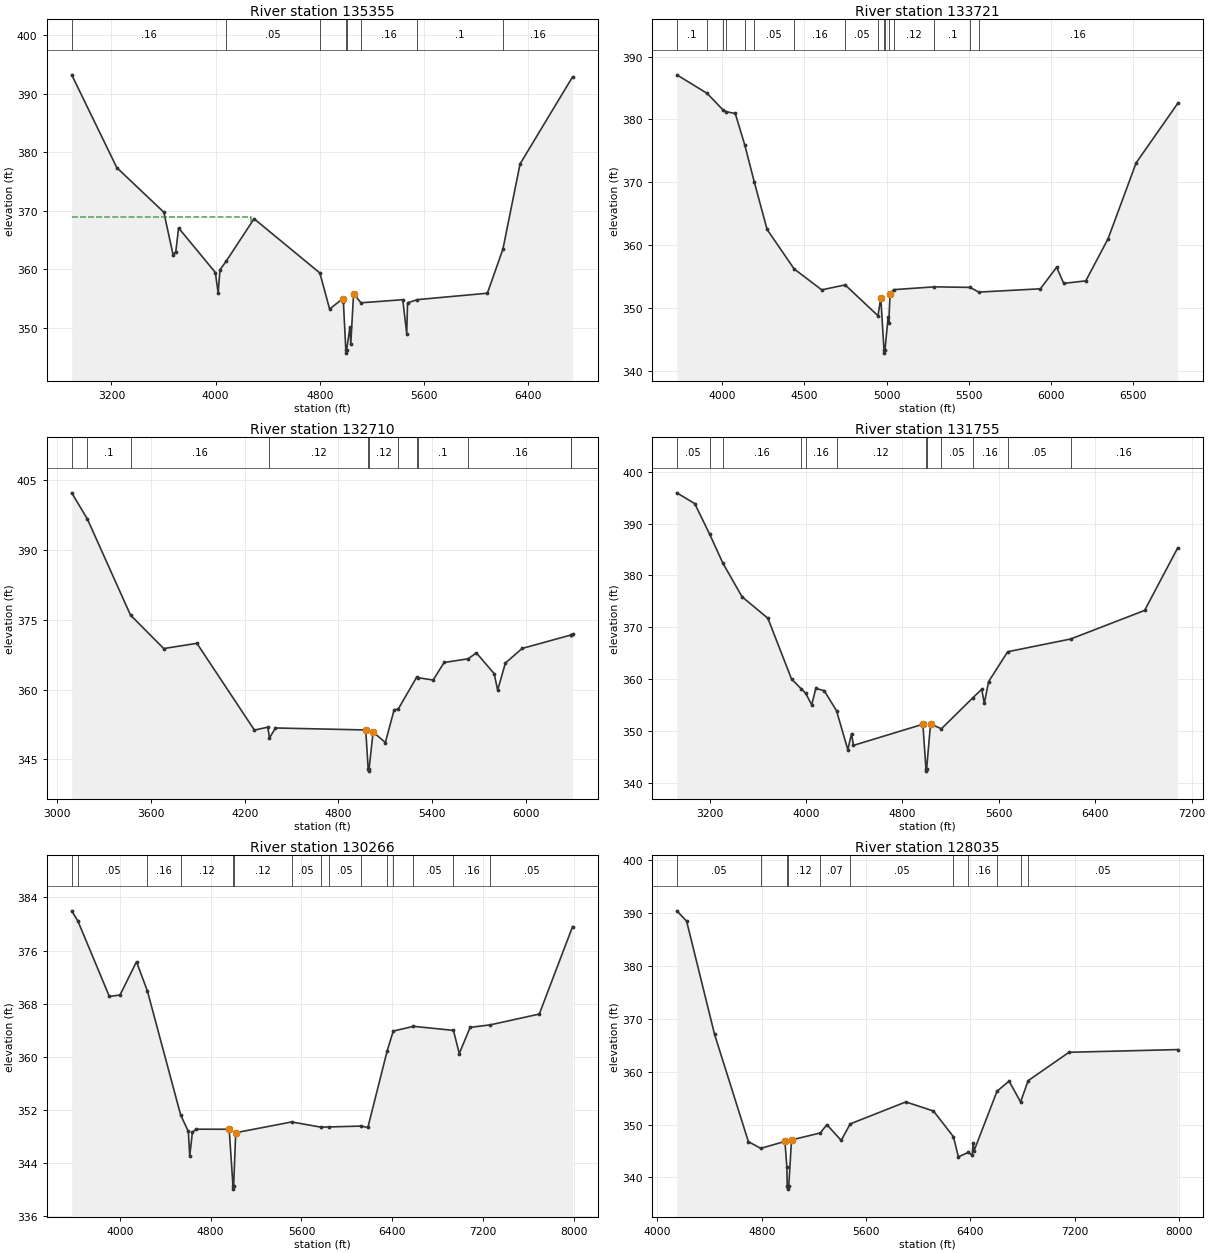
Type RM Length L Ch R = 1 ,135355  ,1634,1634,1634
BEGIN DESCRIPTION:
CEDAR CREEK 127.0
END DESCRIPTION:
XS GIS Cut Line= 3
      3527142.14     10329941.67      3525551.51     10328246.98
      3525287.62     10326746.95
#Sta/Elev= 30
  2894.9  393.27  3241.5  377.38  3602.4  369.77  3673.3  362.52  3694.3  363.01
  3715.8  367.08  3998.6  359.44  4019.6   355.9  4033.8  359.92  4080.4  361.35
  4295.6  368.65    4801  359.37  4875.8  353.21    4975  354.93  4981.8  354.42
  5000.3  346.16    5003  345.66  5006.3  346.16  5031.6  350.09  5038.5  347.24
  5059.9  355.85  5116.6  354.27  5437.8   354.8  5468.2  348.98  5474.4  354.25
  5548.8  354.81  6087.6  355.91  6206.9  363.44  6338.8  378.03  6742.2  392.93
#Mann= 8 ,-1 , 0
  2894.9     .16       0  4080.4     .05       0    4801     .12       0
  5000.3     .07       0  5006.3     .12       0  5116.6     .16       0
  5548.8      .1       0  6206.9     .16       0
#XS Ineff= 2 , 0
         4274.71  368.92
Permanent Ineff=
       F       F
Bank Sta=4975,5059.9
XS Rating Curve= 0 ,0
Exp/Cntr=0.3,0.1

Type RM Length L Ch R = 1 ,133721  ,1011,1011,1011
BEGIN DESCRIPTION:
CEDAR CREEK 125.0
END DESCRIPTION:
XS GIS Cut Line= 3
      3527190.41     10329281.72      3526412.62     10327781.71
      3525545.86     10326741.59
#Sta/Elev= 30
  3725.9  387.09  3910.2  384.13  4007.4  381.47  4026.2  381.22  4080.7  380.94
  4139.2  375.87  4195.9  370.08  4274.2  362.48  4438.6   356.2  4606.1  352.87
  4748.5  353.66  4948.1  348.75  4965.1  351.61  4984.5   343.3  4987.3   342.8
  4990.5   343.3  5009.6  348.57  5013.5  347.65  5021.4   352.2  5042.6   352.9
  5291.2  353.35  5507.8  353.26  5560.4  352.51  5934.7  353.04  6033.7  356.47
  6076.6   353.9  6210.7   354.3  6346.1     361  6516.6  373.08  6769.5  382.55
#Mann= 16 ,-1 , 0
  3725.9      .1       0  3910.2     .05       0  4007.4      .1       0
  4026.2     .05       0  4139.2      .1       0  4195.9     .05       0
  4438.6     .16       0  4748.5     .05       0  4948.1     .12       0
  4984.5     .07       0  4990.5     .12       0  5013.5     .16       0
  5042.6     .12       0  5291.2      .1       0  5507.8     .05       0
  5560.4     .16       0
Bank Sta=4965.1,5021.4
XS Rating Curve= 0 ,0
Exp/Cntr=0.3,0.1

Type RM Length L Ch R = 1 ,132710  ,955,955,955
BEGIN DESCRIPTION:
CEDAR CREEK 123.0
END DESCRIPTION:
XS GIS Cut Line= 3
      3528242.12     10328841.66      3526992.11     10327441.64
       3525961.2     10326608.07
#Sta/Elev= 30
  3094.3  402.33  3194.5   396.7  3470.2  376.04  3682.4  368.85  3894.8  369.97
  4262.6  351.31  4347.9  351.94  4358.9  349.63  4397.2  351.77  4974.4  351.34
  4989.7  342.99  4992.5  342.49  4995.7  342.99  5021.5  350.91  5099.8  348.64
  5155.8  355.68    5182  355.84  5299.8  362.68  5308.3  362.58  5405.2  362.08
  5475.6  365.85  5628.3  366.64  5681.9  367.91  5795.4  363.45  5817.8  359.92
  5867.3  365.73  5974.2  368.87  6285.2  371.75  6289.8  371.82  6296.9  371.87
#Mann= 12 ,-1 , 0
  3094.3     .05       0  3194.5      .1       0  3470.2     .16       0
  4358.9     .12       0  4989.7     .07       0  4995.7     .12       0
    5182      .1       0  5299.8     .05       0  5308.3      .1       0
  5628.3     .16       0  6285.2     .05       0  6289.8      .1       0
Bank Sta=4974.4,5021.5
XS Rating Curve= 0 ,0
Exp/Cntr=0.3,0.1

Type RM Length L Ch R = 1 ,131755  ,1489,1489,1489
BEGIN DESCRIPTION:
CEDAR CREEK 122.0
END DESCRIPTION:
XS GIS Cut Line= 3
      3528447.36     10328823.41      3527739.01     10327246.98
      3526093.18     10325462.27
#Sta/Elev= 30
  2928.2  395.91  3076.7  393.83  3200.7  387.92  3310.3  382.35  3469.2  375.88
  3683.1  371.76  3879.4  360.06  3962.2   358.1  3996.7  357.31    4047  355.08
  4081.3  358.23  4150.6   357.8  4252.9  353.94  4346.9  346.42  4377.3  349.53
  4393.2  347.26  4969.4  351.33  4994.8   342.8  4997.5   342.3  5000.8   342.8
  5032.9   351.4  5123.2  350.46  5383.7  356.42  5457.7  358.07  5479.2  355.35
  5514.4  359.53  5673.3   365.3  6195.3  367.75  6809.5  373.26  7084.2  385.33
#Mann= 12 ,-1 , 0
  2928.2     .05       0  3200.7      .1       0  3310.3     .16       0
  3962.2      .1       0  3996.7     .16       0  4252.9     .12       0
  4994.8     .07       0  5000.8     .12       0  5123.2     .05       0
  5383.7     .16       0  5673.3     .05       0  6195.3     .16       0
Bank Sta=4969.4,5032.9
XS Rating Curve= 0 ,0
Exp/Cntr=0.3,0.1

Type RM Length L Ch R = 1 ,130266  ,2231,2231,2231
BEGIN DESCRIPTION:
CEDAR CREEK 121.0
END DESCRIPTION:
XS GIS Cut Line= 3
      3529766.83      10328135.9      3528287.62     10327184.48
      3526982.09     10324872.02
#Sta/Elev= 30
  3575.2  381.99    3630  380.44  3907.2  369.07    4001   369.3  4146.2  374.31
  4242.8  369.87  4535.4   351.2  4603.2  348.72  4615.2  344.99    4639  348.63
  4674.7  349.06  4963.1  349.05  4996.4  340.52  4999.2  340.02  5002.4  340.52
  5020.6  348.53  5513.7  350.15  5769.9  349.37  5845.6   349.4  6125.3  349.53
  6185.3  349.32    6356  360.91  6408.9  363.85  6586.7  364.57  6939.5  363.96
  6990.9  360.47  7086.4  364.41  7265.3   364.8  7695.8  366.42  7989.5  379.62
#Mann= 15 ,-1 , 0
  3575.2      .1       0    3630     .05       0  4242.8     .16       0
  4535.4     .12       0  4996.4     .07       0  5002.4     .12       0
  5513.7     .05       0  5769.9      .1       0  5845.6     .05       0
  6125.3     .16       0    6356     .05       0  6408.9     .16       0
  6586.7     .05       0  6939.5     .16       0  7265.3     .05       0
Bank Sta=4963.1,5020.6
XS Rating Curve= 0 ,0
Exp/Cntr=0.3,0.1

Type RM Length L Ch R = 1 ,128035  ,1986,1986,1986
BEGIN DESCRIPTION:
CEDAR CREEK 120.0
END DESCRIPTION:
XS GIS Cut Line= 3
      3530211.22     10327885.86      3529447.34     10326788.65
      3527718.42     10324976.41
#Sta/Elev= 30
  4148.9  390.47  4223.6  388.52  4438.3  367.06  4697.5  346.77  4792.2   345.5
  4977.6  346.81  4992.4  342.02  4995.5  338.28  4998.3  337.78  5001.5  338.28
    5007   338.3  5028.2   347.1  5248.4  348.41  5299.6  349.98  5409.1     347
  5478.4  350.13  5904.8  354.29  6117.1  352.57  6270.1  347.71    6308  343.89
  6383.3  344.73    6414   344.2  6421.2  346.55  6428.1  345.03  6604.4  356.32
    6697  358.23  6785.2  354.28    6843  358.31  7156.5  363.69  7990.5   364.2
#Mann= 11 ,-1 , 0
  4148.9     .05       0  4792.2     .12       0  4995.5     .07       0
  5001.5     .12       0  5248.4     .07       0  5478.4     .05       0
  6270.1     .12       0  6383.3     .16       0  6604.4     .05       0
  6785.2     .16       0    6843     .05       0
Bank Sta=4977.6,5028.2
XS Rating Curve= 0 ,0
Exp/Cntr=0.3,0.1

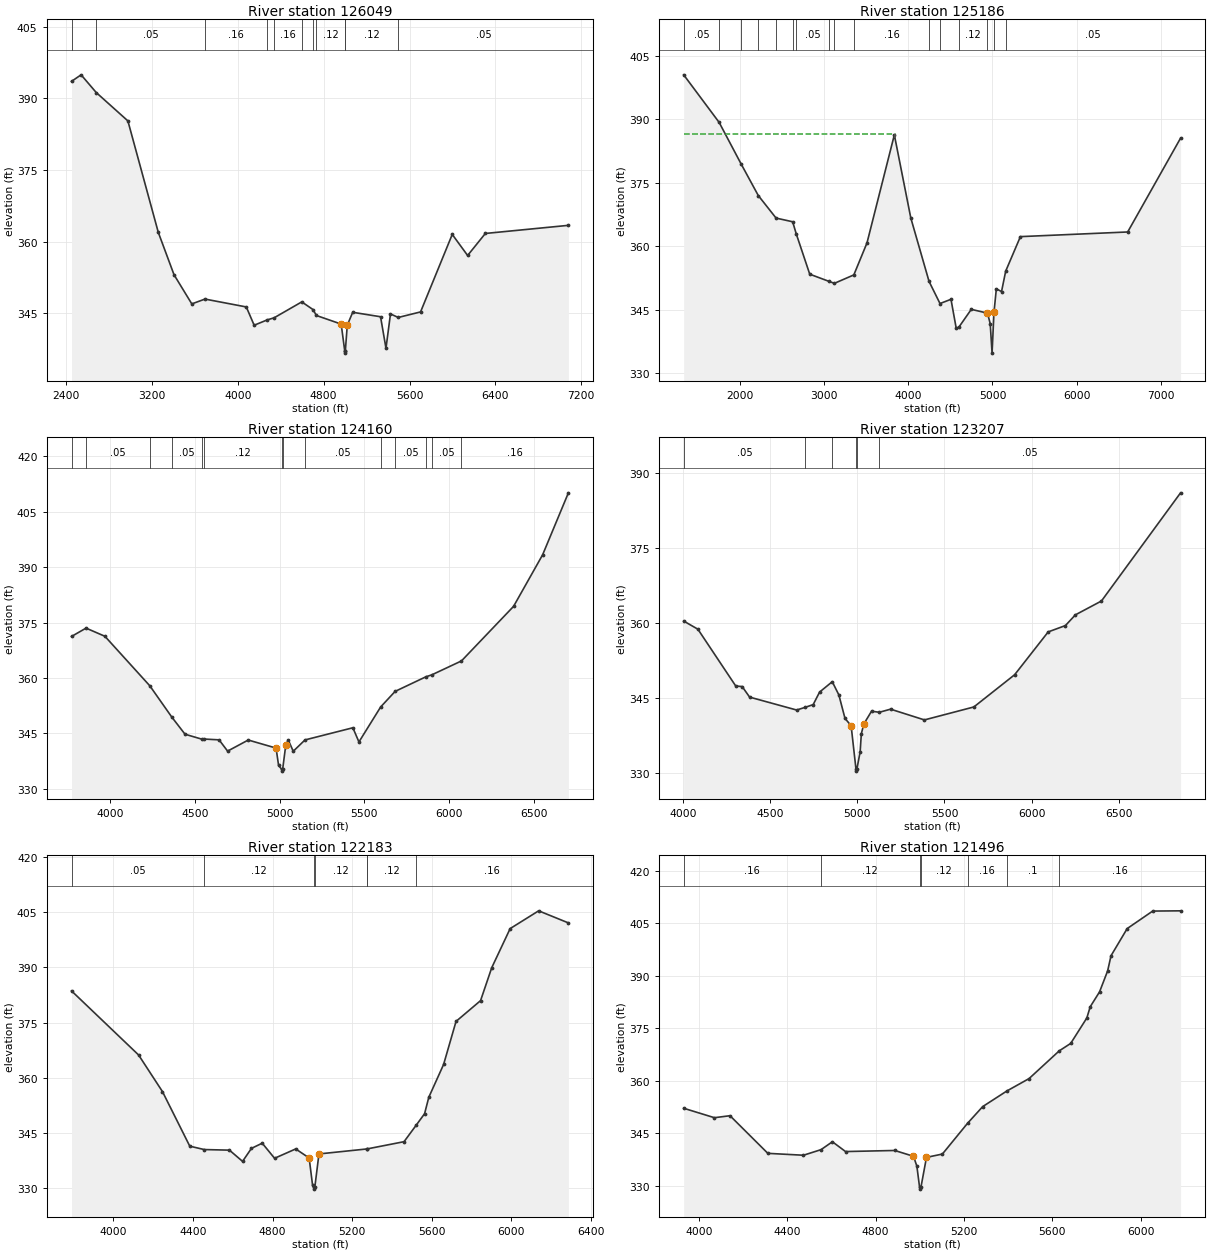
Type RM Length L Ch R = 1 ,126049  ,863,863,863
BEGIN DESCRIPTION:
CEDAR CREEK 119.0
END DESCRIPTION:
XS GIS Cut Line= 3
      3531273.74     10328073.38      3530134.84     10326240.04
      3528107.11     10324830.35
#Sta/Elev= 30
  2451.9  393.54  2541.3  394.91  2682.7  391.19    2977  385.26  3260.4   361.9
  3406.8  353.04  3572.3  346.94    3695  347.95  4079.9   346.3  4153.1  342.47
  4275.8   343.6  4338.2  344.02  4596.6  347.36  4701.2  345.75  4732.8  344.51
  4963.6  342.71  4996.4  337.13  4999.1  336.63  5002.4  337.13  5020.3  342.48
  5070.9  345.18  5330.2  344.25  5380.8  337.65  5422.7  344.84    5495   344.1
  5702.9  345.26    5998  361.49  6141.1  357.08  6306.4  361.69  7079.8  363.39
#Mann= 11 ,-1 , 0
  2451.9     .16       0  2682.7     .05       0    3695     .16       0
  4275.8     .12       0  4338.2     .16       0  4596.6     .12       0
  4701.2     .16       0  4732.8     .12       0  4996.4     .07       0
  5002.4     .12       0    5495     .05       0
Bank Sta=4963.6,5020.3
XS Rating Curve= 0 ,0
Exp/Cntr=0.3,0.1

Type RM Length L Ch R = 1 ,125186  ,1026,1026,1026
BEGIN DESCRIPTION:
CEDAR CREEK 118.0
END DESCRIPTION:
XS GIS Cut Line= 3
      3532509.81     10327246.96      3530461.23     10325892.82
      3527379.48     10324365.82
#Sta/Elev= 30
  1336.4  400.53  1757.3  389.29  2016.8  379.52  2221.6  372.02  2432.6   366.7
  2629.3  365.83  2672.6  362.93  2832.1  353.45  3057.2  351.78  3124.2  351.29
    3355  353.28  3511.2  360.84  3835.7  386.35  4031.1  366.71  4247.5  351.74
  4377.3  346.52  4507.6  347.52  4569.3  340.73  4600.3  340.92  4748.6  345.15
  4940.6  344.25  4972.9  341.79    4995  334.81  5017.7  344.43  5045.7  349.99
  5107.4  349.35  5156.8  354.18  5331.2  362.32    6604  363.42  7231.4  385.58
#Mann= 16 ,-1 , 0
  1336.4     .05       0  1757.3      .1       0  2016.8     .05       0
  2221.6     .16       0  2432.6     .05       0  2629.3     .16       0
  2672.6     .05       0  3057.2      .1       0  3124.2     .05       0
    3355     .16       0  4247.5     .12       0  4377.3     .16       0
  4600.3     .12       0  4940.6     .07       0  5017.7     .12       0
  5156.8     .05       0
#XS Ineff= 2 , 0
         3843.75  386.54
Permanent Ineff=
       F       F
Bank Sta=4940.6,5017.7
XS Rating Curve= 0 ,0
Exp/Cntr=0.3,0.1

Type RM Length L Ch R = 1 ,124160  ,953,953,953
BEGIN DESCRIPTION:
CEDAR CREEK 115.0
END DESCRIPTION:
XS GIS Cut Line= 3
      3530732.05     10325837.23      3530155.68      10325045.6
      3529042.13     10323441.68
#Sta/Elev= 30
  3771.9  371.25  3857.7  373.51  3968.9   371.3  4234.1  357.88  4363.5  349.43
  4441.7  344.78    4542  343.43  4551.8  343.48  4642.6  343.26  4692.9  340.21
  4814.7  343.21  4978.9  341.03  4993.7  336.35  5011.7  335.29  5014.4  334.79
  5017.7  335.29  5035.9  341.77  5050.5  343.25  5080.2  340.17  5149.7  343.24
    5432  346.53  5467.8  342.69  5596.1  352.17  5681.3  356.38  5861.9  360.31
  5897.8  360.86  6072.9  364.63  6380.2   379.4  6551.6  393.36  6703.7  410.14
#Mann= 14 ,-1 , 0
  3771.9      .1       0  3857.7     .05       0  4234.1     .16       0
  4363.5     .05       0    4542     .16       0  4551.8     .12       0
  5011.7     .07       0  5017.7     .12       0  5149.7     .05       0
  5596.1     .12       0  5681.3     .05       0  5861.9     .16       0
  5897.8     .05       0  6072.9     .16       0
Bank Sta=4978.9,5035.9
XS Rating Curve= 0 ,0
Exp/Cntr=0.3,0.1

Type RM Length L Ch R = 1 ,123207  ,1024,1024,1024
BEGIN DESCRIPTION:
CEDAR CREEK 113.0
END DESCRIPTION:
XS GIS Cut Line= 3
      3531292.12     10325441.66      3530641.79     10324371.98
       3529607.1     10323156.75
#Sta/Elev= 30
  4005.4  360.35  4086.8  358.72  4303.8  347.36  4340.6  347.25  4383.3  345.14
  4652.6  342.56  4700.5  343.08  4747.6  343.64  4784.4  346.15    4857  348.22
  4894.8  345.58    4930  340.88  4965.1  339.42  4992.6  330.84  4995.3  330.34
  4998.6  330.84  5016.9  334.22  5023.6  337.82  5038.2  339.79  5082.1  342.32
    5127  342.11  5191.3  342.73  5385.2  340.58  5668.5  343.17  5902.4  349.62
  6094.6  358.18  6193.4  359.45  6250.5  361.59  6399.9  364.36  6853.3  385.99
#Mann= 6 ,-1 , 0
  4005.4     .05       0  4700.5      .1       0    4857     .12       0
  4992.6     .07       0  4998.6     .12       0    5127     .05       0
Bank Sta=4965.1,5038.2
XS Rating Curve= 0 ,0
Exp/Cntr=0.3,0.1

Type RM Length L Ch R = 1 ,122183  ,687,687,687
BEGIN DESCRIPTION:
CEDAR CREEK 112.0
END DESCRIPTION:
XS GIS Cut Line= 3
      3531792.11     10325091.65      3531426.51     10324240.04
      3530898.72     10322760.84
#Sta/Elev= 30
  3789.6  383.62  4126.7  366.21  4246.7  356.26    4384  341.43  4456.8  340.51
  4583.3  340.35  4649.3   337.3  4693.9  340.83  4748.1  342.24  4810.2  338.14
  4916.4  340.68  4983.9  338.22  5001.3  330.76  5006.4  330.26  5009.2  329.76
  5012.4  330.26  5033.2  339.32  5273.4  340.67  5273.9  340.67  5460.9  342.65
  5521.5   347.1  5564.1  350.25  5585.3  354.72  5659.6  363.62  5722.2  375.33
  5845.4  380.97  5901.7  389.93  5994.1  400.54  6137.4  405.37  6286.9  402.09
#Mann= 7 ,-1 , 0
  3789.6     .05       0  4456.8     .12       0  5006.4     .07       0
  5012.4     .12       0  5273.4     .16       0  5273.9     .12       0
  5521.5     .16       0
Bank Sta=4983.9,5033.2
XS Rating Curve= 0 ,0
Exp/Cntr=0.3,0.1

Type RM Length L Ch R = 1 ,121496  ,748,748,748
BEGIN DESCRIPTION:
CEDAR CREEK 110.0
END DESCRIPTION:
XS GIS Cut Line= 3
      3532168.49     10324859.69      3532068.49      10324059.7
      3531301.53      10322837.3
#Sta/Elev= 30
  3931.3  352.16  4070.4  349.46    4141  350.03  4312.3  339.28  4473.5  338.74
  4553.2  340.34  4604.5  342.59    4664  339.79  4886.7   340.1  4971.6  338.44
  4986.9  335.62  4999.2  329.56  5001.9  329.06  5005.2  329.56  5030.4  338.13
  5102.4  339.08  5216.1  347.85    5285  352.64  5394.7  357.11  5494.7  360.63
  5631.3  368.55  5683.2  370.68  5756.3  377.95  5771.6  381.15    5814  385.42
  5850.5  391.41  5865.8  395.73  5938.9  403.48  6054.4  408.48  6180.6  408.55
#Mann= 7 ,-1 , 0
  3931.3     .16       0  4553.2     .12       0  4999.2     .07       0
  5005.2     .12       0  5216.1     .16       0  5394.7      .1       0
  5631.3     .16       0
Bank Sta=4971.6,5030.4
XS Rating Curve= 0 ,0
Exp/Cntr=0.3,0.1

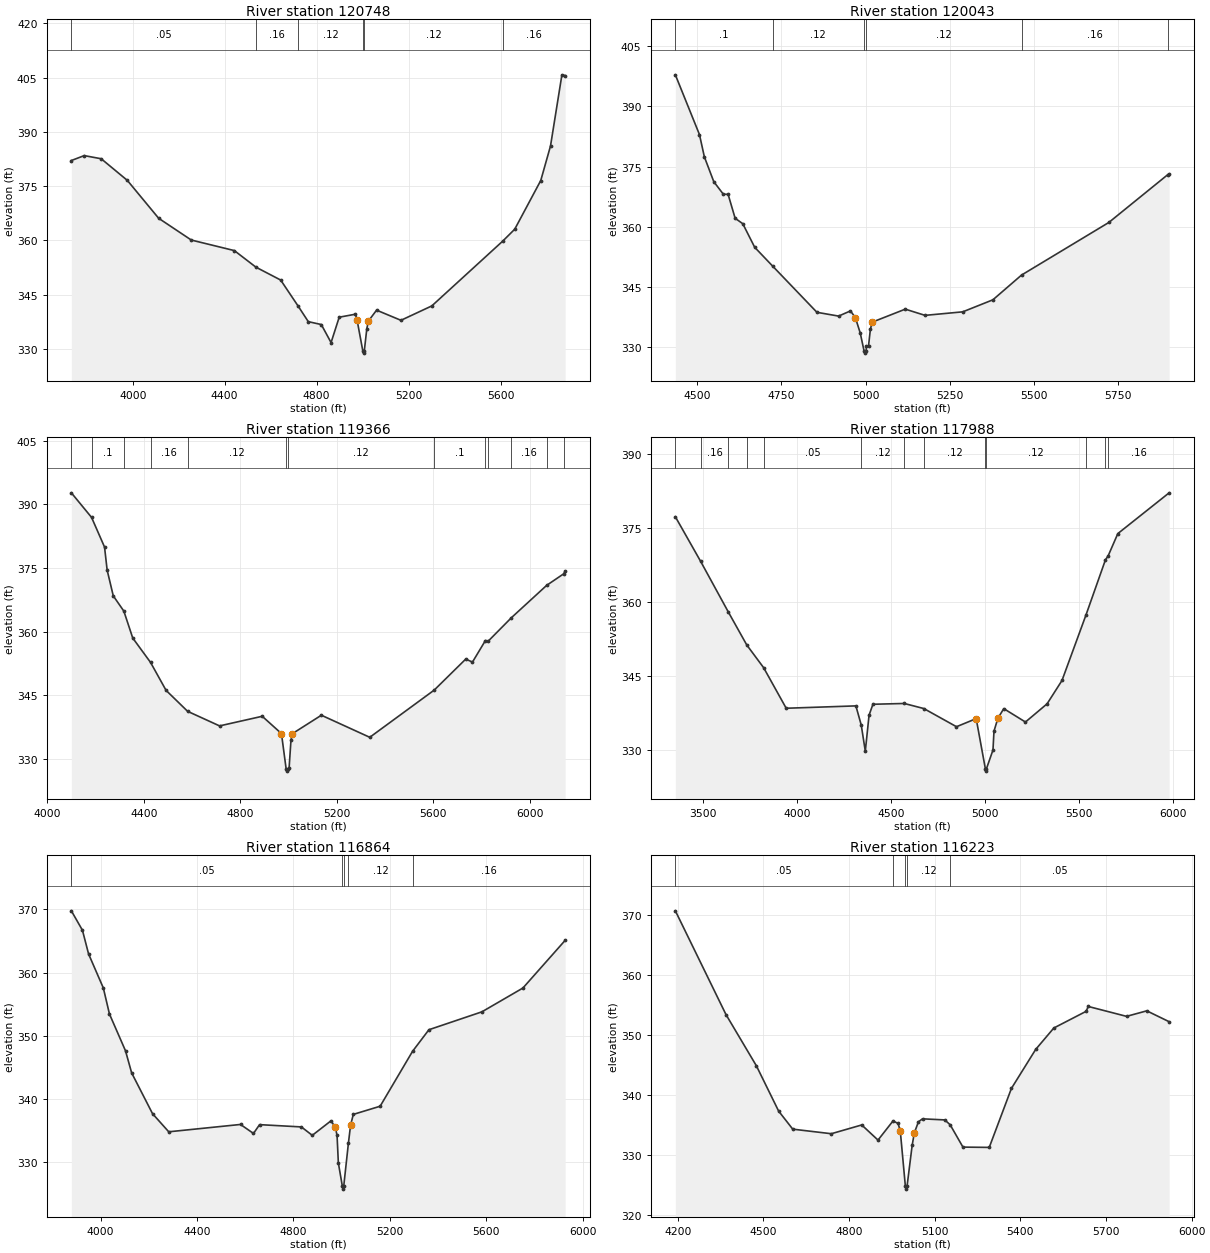
Type RM Length L Ch R = 1 ,120748  ,705,705,705
BEGIN DESCRIPTION:
CEDAR CREEK 108.0
END DESCRIPTION:
XS GIS Cut Line= 3
      3533627.94     10324170.62      3532824.05     10323788.86
      3531942.13     10322891.67
#Sta/Elev= 30
    3733  382.08  3789.1  383.44  3862.8  382.57  3976.4  376.59  4112.8   366.1
  4254.7  360.08    4442  357.16    4536  352.57  4643.6  349.01  4720.2  341.74
  4763.7   337.5  4820.3   336.7  4862.8  331.71  4898.2  338.73  4968.9  339.56
  4975.9  337.96  5001.2  329.29  5003.9  328.79  5007.2  329.29  5018.3  335.54
  5025.5  337.69  5060.8  340.68  5166.8  337.87  5301.2  341.86  5610.2  359.82
  5661.8  363.08    5775  376.55  5817.4   386.1    5867  405.79    5881  405.59
#Mann= 6 ,-1 , 0
    3733     .05       0    4536     .16       0  4720.2     .12       0
  5001.2     .07       0  5007.2     .12       0  5610.2     .16       0
Bank Sta=4975.9,5025.5
XS Rating Curve= 0 ,0
Exp/Cntr=0.3,0.1

Type RM Length L Ch R = 1 ,120043  ,677,677,677
BEGIN DESCRIPTION:
CEDAR CREEK 107.0
END DESCRIPTION:
XS GIS Cut Line= 3
      3533492.09     10323441.63      3533042.11     10323091.64
       3532242.1     10322691.64
#Sta/Elev= 30
  4435.9   397.9  4507.4  382.99  4521.9  377.45  4549.9  371.24    4578  368.14
  4592.4  368.07  4613.2  362.12  4635.9  360.76  4671.2  354.88  4724.3   350.2
  4855.8  338.66    4920  337.72  4955.3  339.01  4969.8  337.34  4984.3  333.48
  4995.7  328.98  4998.5  328.48  5001.7  328.98  5002.8  330.27  5008.8  330.27
  5014.4  334.46  5019.9  336.21  5117.8  339.45  5176.5   337.9  5288.3  338.78
  5377.7  341.78  5462.6  347.95  5721.5  361.07  5895.8  372.96  5900.4   373.2
#Mann= 6 ,-1 , 0
  4435.9      .1       0  4724.3     .12       0  4995.7     .07       0
  5001.7     .12       0  5462.6     .16       0  5895.8     .05       0
Bank Sta=4969.8,5019.9
XS Rating Curve= 0 ,0
Exp/Cntr=0.3,0.1

Type RM Length L Ch R = 1 ,119366  ,1378,1378,1378
BEGIN DESCRIPTION:
CEDAR CREEK 106.0
END DESCRIPTION:
XS GIS Cut Line= 3
      3533785.16     10323301.35      3533535.16     10322601.36
      3532365.53     10322025.51
#Sta/Elev= 30
  4099.7  392.75  4183.5  386.95  4237.3  379.95  4248.1  374.51  4273.5  368.44
  4317.3  364.84  4354.2  358.49  4428.1  352.73  4492.3  346.15  4581.7   341.2
  4714.1  337.76    4891  340.03  4970.7  335.95  4990.2  327.59  4992.9  327.09
  4996.2  327.59  5002.4  327.82  5010.1  334.34  5015.7  335.92  5136.2  340.28
  5336.8  335.07    5604  346.21  5734.6  353.52  5762.6  352.82  5816.2   357.9
  5828.6   357.8  5924.2   363.3  6070.4  370.93  6140.2  373.62  6146.7  374.25
#Mann= 13 ,-1 , 0
  4099.7     .05       0  4183.5      .1       0  4317.3     .05       0
  4428.1     .16       0  4581.7     .12       0  4990.2     .07       0
  4996.2     .12       0    5604      .1       0  5816.2     .16       0
  5828.6      .1       0  5924.2     .16       0  6070.4     .05       0
  6140.2     .16       0
Bank Sta=4970.7,5015.7
XS Rating Curve= 0 ,0
Exp/Cntr=0.3,0.1

Type RM Length L Ch R = 1 ,117988  ,1124,1124,1124
BEGIN DESCRIPTION:
CEDAR CREEK 105.0
END DESCRIPTION:
XS GIS Cut Line= 3
      3535030.67     10321844.21      3533634.84     10321753.93
      3532462.49     10321386.27
#Sta/Elev= 30
  3353.4  377.35  3487.5  368.32  3634.6  358.05  3733.4  351.31  3823.2  346.69
  3943.2  338.46    4314  338.94  4342.5  335.05  4364.1  329.74  4384.1  337.05
  4404.7  339.27  4571.5  339.43  4675.5   338.4  4849.3  334.71  4954.1  336.35
  5002.9  326.19  5005.6  325.69  5008.9  326.19  5043.5  329.99  5048.8   333.8
  5069.4  336.41  5100.9  338.38  5216.2  335.66  5331.4  339.36  5410.7   344.1
  5537.6  357.32  5641.8  368.59  5656.3  369.41  5707.8  373.93  5980.8  382.21
#Mann= 13 ,-1 , 0
  3353.4     .05       0  3487.5     .16       0  3634.6     .05       0
  3733.4     .16       0  3823.2     .05       0  4342.5     .12       0
  4571.5     .16       0  4675.5     .12       0  5002.9     .07       0
  5008.9     .12       0  5537.6     .16       0  5641.8      .1       0
  5656.3     .16       0
Bank Sta=4954.1,5069.4
XS Rating Curve= 0 ,0
Exp/Cntr=0.3,0.1

Type RM Length L Ch R = 1 ,116864  ,641,641,641
BEGIN DESCRIPTION:
CEDAR CREEK 104.0
END DESCRIPTION:
XS GIS Cut Line= 3
      3534842.12     10321191.65      3533526.83     10320716.64
      3532876.96     10320716.64
#Sta/Elev= 30
  3878.7  369.77  3924.7   366.7  3950.1  362.96  4011.4  357.57  4036.8  353.46
  4103.4  347.64  4128.8  344.16  4215.5  337.71  4282.7  334.85  4580.4  336.01
  4634.2  334.59  4659.5  335.98  4832.9  335.62  4878.1  334.29  4955.6  336.58
  4973.8  335.56  4980.9  334.27  4986.3  329.92  5002.7  326.29  5005.5  325.79
  5008.7  326.29  5028.1  333.09    5037  335.88  5048.3   337.6  5159.6  338.89
  5294.1  347.57  5361.9  350.98  5581.9  353.81  5751.9  357.57    5927   365.1
#Mann= 5 ,-1 , 0
  3878.7     .05       0  5002.7    .035       0  5008.7     .05       0
  5028.1     .12       0  5294.1     .16       0
Bank Sta=4973.8,5037
XS Rating Curve= 0 ,0
Exp/Cntr=0.3,0.1

Type RM Length L Ch R = 1 ,116223  ,1096,1096,1096
BEGIN DESCRIPTION:
CEDAR CREEK 103.0
END DESCRIPTION:
XS GIS Cut Line= 3
      3534842.11     10321091.65      3534155.68     10320288.65
      3533669.57     10319823.38
#Sta/Elev= 30
  4191.8  370.71  4369.1  353.43  4475.6  344.89  4553.5  337.35  4602.9  334.34
    4738  333.58  4844.5  335.04  4901.5  332.52  4954.1  335.71  4971.8  335.29
  4979.5  334.06  4997.3  324.85  5000.1  324.35  5003.3  324.85  5021.2  331.67
  5028.9  333.75  5043.2  335.57  5057.4  336.06  5135.4  335.88  5154.2  335.07
    5199  331.35  5291.1   331.3  5368.8  341.13  5453.7  347.62  5517.3  351.19
  5630.5  353.97  5637.7  354.78    5772  353.13  5842.8  354.05  5921.1  352.24
#Mann= 5 ,-1 , 0
  4191.8     .05       0  4954.1     .12       0  4997.3     .07       0
  5003.3     .12       0  5154.2     .05       0
Bank Sta=4979.5,5028.9
XS Rating Curve= 0 ,0
Exp/Cntr=0.3,0.1