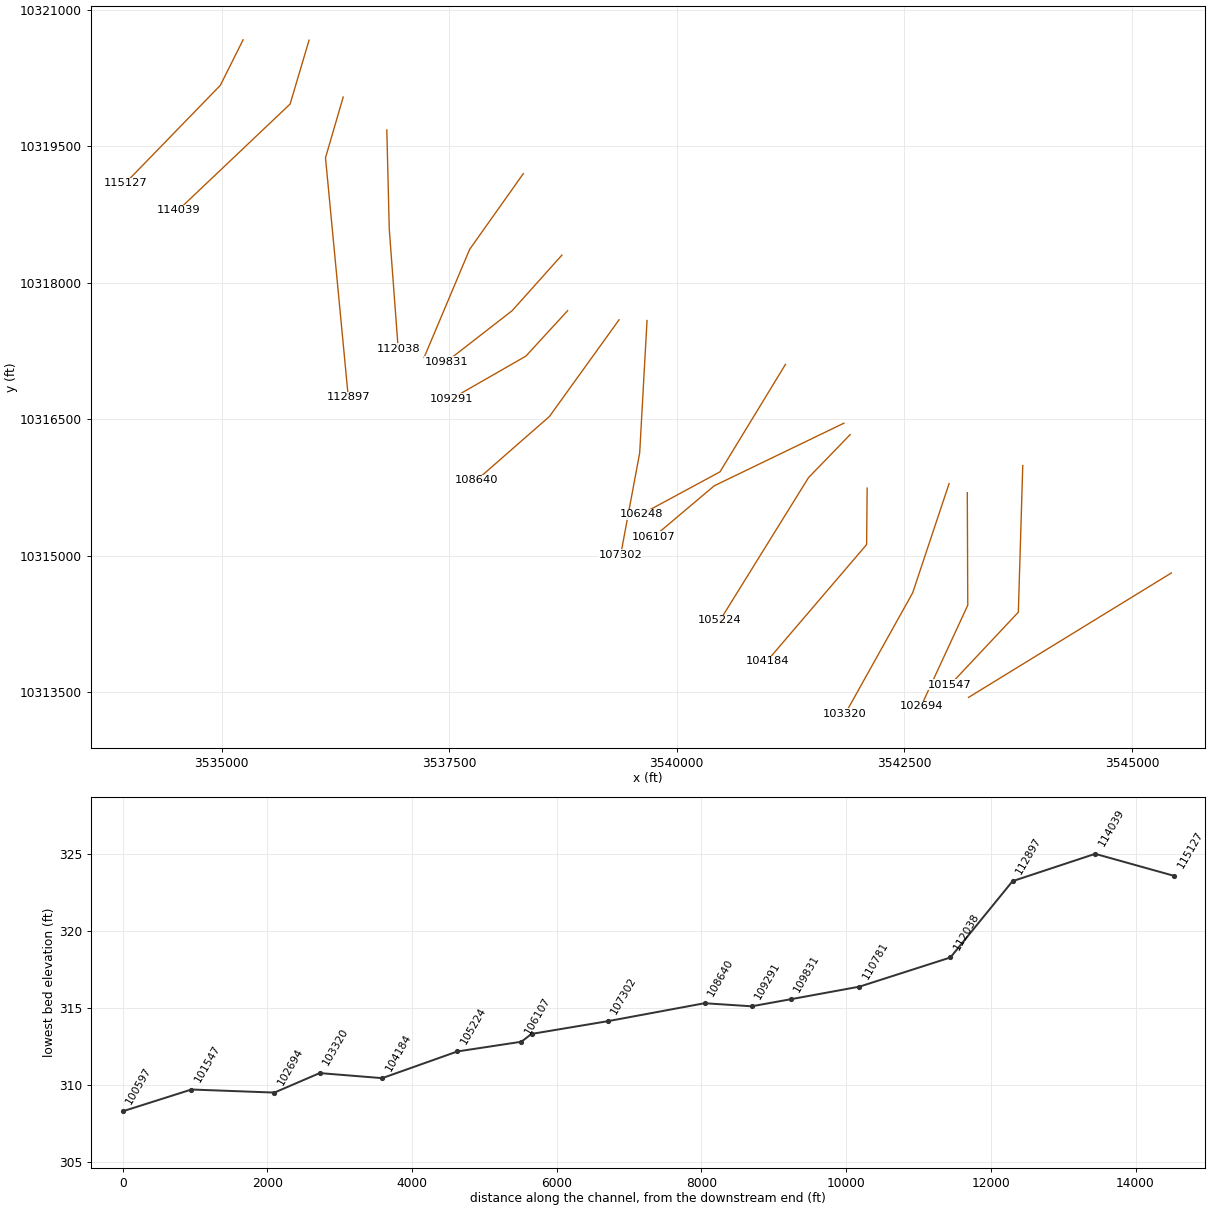
HEC-RAS study CEDAR CREEK.prj: CEDAR CREEK Base Level Engineering

--- CEDAR CREEK.g01 (geometry) --- (continued)

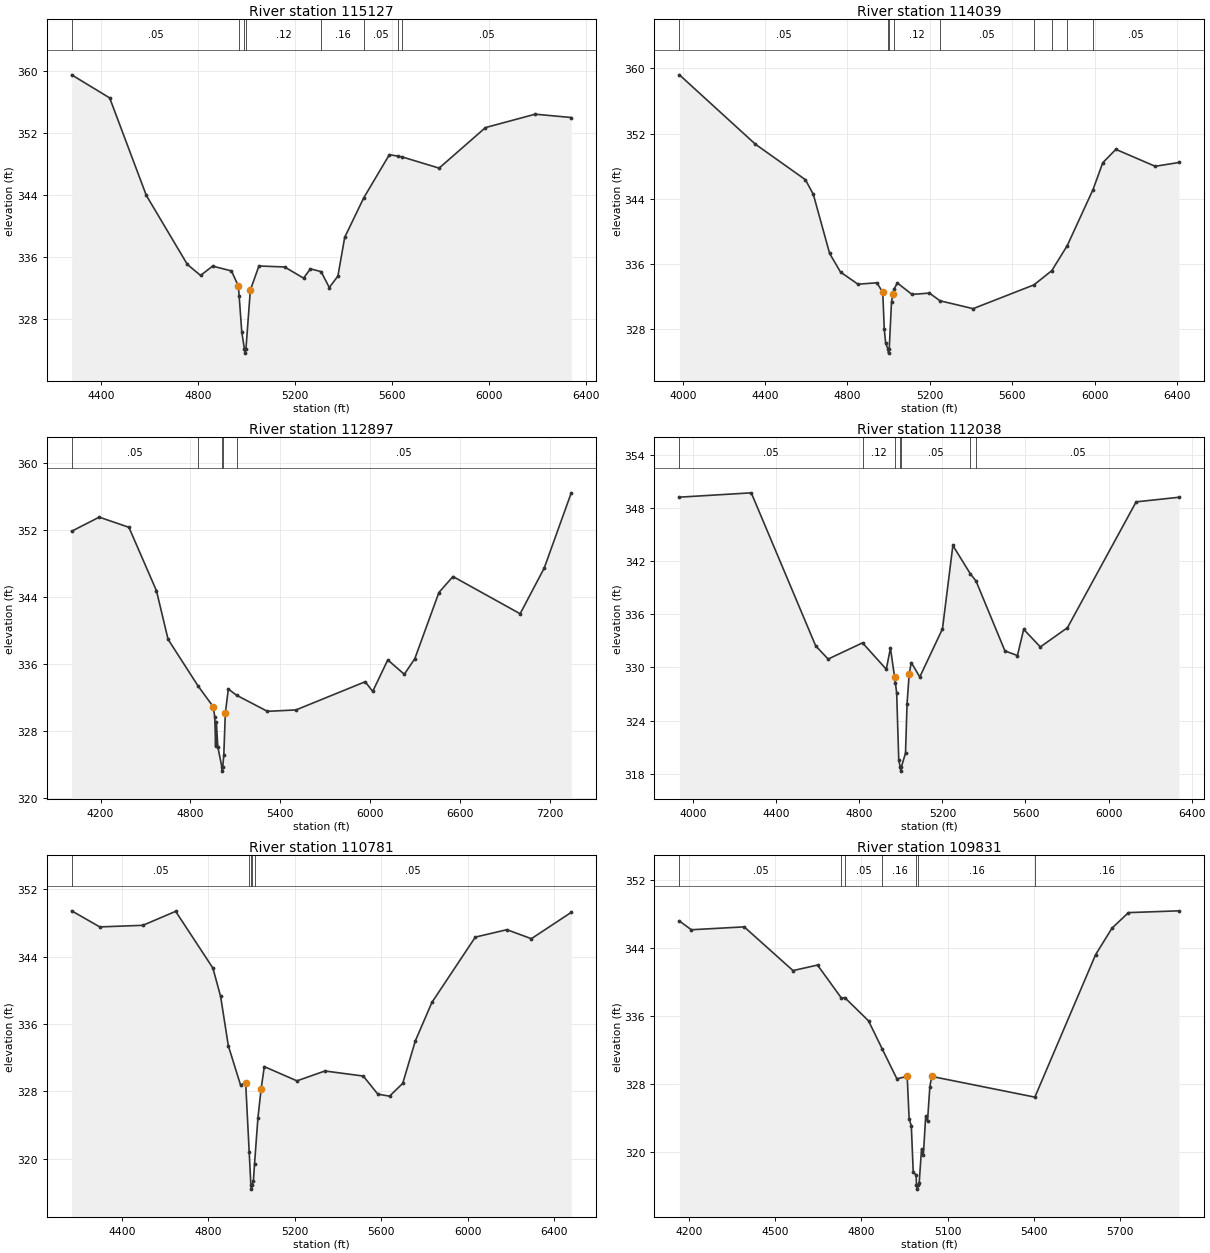
Type RM Length L Ch R = 1 ,115127  ,1088,1088,1088
BEGIN DESCRIPTION:
CEDAR CREEK 101.0
END DESCRIPTION:
XS GIS Cut Line= 3
      3535236.57     10320668.06      3534986.55     10320168.03
      3533942.09     10319091.63
#Sta/Elev= 30
  4278.5  359.53  4435.2  356.55  4586.2  343.97  4755.3  335.06  4809.8  333.64
  4859.4  334.84  4937.1  334.22  4965.4  332.28  4968.7  331.04  4979.6  326.34
  4990.7  324.11  4993.5  323.61  4996.7  324.11  5014.9  331.75  5050.3  334.86
  5156.3  334.73  5234.2  333.29  5262.5  334.49  5306.5  334.13  5340.2  332.08
  5375.7  333.55  5403.8  338.56  5482.2  343.65  5587.7  349.22  5623.1  349.04
  5640.8  348.93  5792.9  347.49  5983.8  352.72  6188.8  354.45  6337.4  354.02
#Mann= 8 ,-1 , 0
  4278.5     .05       0  4968.7     .12       0  4990.7     .07       0
  4996.7     .12       0  5306.5     .16       0  5482.2     .05       0
  5623.1     .16       0  5640.8     .05       0
Bank Sta=4965.4,5014.9
XS Rating Curve= 0 ,0
Exp/Cntr=0.3,0.1

Type RM Length L Ch R = 1 ,114039  ,1142,1142,1142
BEGIN DESCRIPTION:
CEDAR CREEK 100.0
END DESCRIPTION:
XS GIS Cut Line= 3
      3535961.22     10320663.61       3535752.9     10319962.26
      3534524.25     10318796.09
#Sta/Elev= 30
    3984  359.21    4353  350.69  4595.9  346.33  4634.3  344.52  4713.3  337.28
  4766.2  334.99  4851.1   333.5  4942.9  333.68  4971.3  332.49  4978.5  328.01
  4985.4  326.25  4996.6  325.54  4999.3  325.04  5002.6  325.54  5013.7  331.32
  5020.6  332.28  5025.5  332.88    5042  333.66  5112.8  332.25  5197.8  332.41
  5249.1  331.47  5409.7   330.5  5705.3  333.42  5791.9  335.17  5866.7  338.23
    5992  345.12  6039.5  348.42    6103  350.06    6294  347.98  6409.6  348.45
#Mann= 9 ,-1 , 0
    3984     .05       0  4996.6    .035       0  5002.6     .05       0
  5025.5     .12       0  5249.1     .05       0  5705.3     .16       0
  5791.9     .05       0  5866.7     .16       0    5992     .05       0
Bank Sta=4971.3,5020.6
XS Rating Curve= 0 ,0
Exp/Cntr=0.3,0.1

Type RM Length L Ch R = 1 ,112897  ,859,859,859
BEGIN DESCRIPTION:
CEDAR CREEK 98.0
END DESCRIPTION:
XS GIS Cut Line= 3
      3536336.24     10320038.68      3536141.79     10319371.98
      3536392.11     10316741.65
#Sta/Elev= 30
  4006.8  351.87  4191.2  353.55  4389.1  352.34  4573.3  344.77  4650.7  338.98
  4850.6  333.43  4952.8  330.93  4962.8   329.7  4968.2  326.23  4973.2  329.17
  4982.9  326.16    5010  323.76  5012.8  323.26    5016  323.76  5023.1  325.24
  5033.1  330.16  5053.2  333.05  5108.5  332.31  5314.4  330.39  5505.2  330.56
  5967.3  333.92  6017.5  332.77    6118  336.52  6228.5  334.81  6298.8  336.68
  6459.5  344.56  6553.4  346.47    7002  342.03  7162.7  347.47  7343.5  356.45
#Mann= 5 ,-1 , 0
  4006.8     .05       0  4850.6     .12       0    5010     .07       0
    5016     .12       0  5108.5     .05       0
Bank Sta=4952.8,5033.1
XS Rating Curve= 0 ,0
Exp/Cntr=0.3,0.1

Type RM Length L Ch R = 1 ,112038  ,1257,1257,1257
BEGIN DESCRIPTION:
CEDAR CREEK 96.0
END DESCRIPTION:
XS GIS Cut Line= 3
       3536815.4     10319677.52      3536842.11     10318591.64
      3536940.33     10317275.71
#Sta/Elev= 30
  3933.6  349.24  4279.6  349.73  4589.7  332.45  4649.7  330.95  4815.3  332.78
  4929.8   329.8  4949.8  332.18  4969.8  328.91  4973.8   328.2  4979.8  327.13
  4989.8  319.53  4996.8  318.79  4999.5  318.29  5002.8  318.79  5022.3  320.32
  5029.8  325.92  5039.9  329.21  5049.9  330.56    5091  328.93  5200.3  334.36
  5250.4  343.78  5333.8  340.61  5361.7  339.78  5501.1  331.87  5561.3  331.35
  5591.4  334.31  5671.6  332.32    5802  334.49  6132.9  348.71  6339.4  349.23
#Mann= 7 ,-1 , 0
  3933.6     .05       0  4815.3     .12       0  4973.8     .05       0
  4996.8     .03       0  5002.8     .05       0  5333.8     .12       0
  5361.7     .05       0
#XS Ineff= 2 , 0
                         5250.73           343.7
Permanent Ineff=
       F       F
Bank Sta=4969.8,5039.9
XS Rating Curve= 0 ,0
Exp/Cntr=0.3,0.1

Type RM Length L Ch R = 1 ,110781  ,950,950,950
BEGIN DESCRIPTION:
CEDAR CREEK 95.0
END DESCRIPTION:
XS GIS Cut Line= 3
       3538315.4     10319198.38      3537725.12     10318365.04
      3537225.12     10317177.53
#Sta/Elev= 30
  4167.9  349.44    4298  347.53  4497.3  347.72  4648.7  349.38  4820.9  342.64
  4856.6  339.27  4892.3  333.41  4948.9  328.74  4972.3  329.05  4988.6  320.85
  4996.4  316.89  4999.1  316.39  5002.4  316.89    5008  317.32  5013.3  319.36
  5028.9   324.8  5043.7  328.27  5058.5  330.94  5209.4  329.25    5339  330.42
    5516  329.82  5583.4  327.67  5637.7  327.43  5698.4  328.95    5757  334.01
  5833.3  338.56  6034.1  346.32  6180.2   347.2  6293.1  346.13  6477.6  349.26
#Mann= 5 ,-1 , 0
  4167.9     .05       0  4988.6     .16       0  4996.4     .07       0
  5002.4     .16       0  5013.3     .05       0
Bank Sta=4972.3,5043.7
XS Rating Curve= 0 ,0
Exp/Cntr=0.3,0.1

Type RM Length L Ch R = 1 ,109831  ,540,540,540
BEGIN DESCRIPTION:
CEDAR CREEK 93.0
END DESCRIPTION:
XS GIS Cut Line= 3
      3538739.03     10318302.56      3538192.11     10317691.64
      3537468.16     10317128.92
#Sta/Elev= 30
  4167.6  347.17  4208.9  346.13  4392.8  346.47  4562.5  341.32  4647.8  341.97
    4731  338.07  4742.7  338.13    4825   335.4  4872.8  332.08  4923.6  328.57
  4959.5  328.85  4966.3  323.84  4973.8  323.03  4980.5  317.58  4990.7  317.22
  4991.8  316.07  4994.6  315.57  4997.8  316.07  5001.1  316.25  5009.3  320.31
  5015.6  319.55  5023.8  324.16  5030.1  323.58  5038.2  327.61  5044.6  328.85
  5403.3  326.41  5614.7  343.21  5671.5  346.32  5728.7  348.15  5904.5  348.36
#Mann= 7 ,-1 , 0
  4167.6     .05       0    4731     .16       0  4742.7     .05       0
  4872.8     .16       0  4991.8     .07       0  4997.8     .16       0
  5403.3     .16       0
Bank Sta=4959.5,5044.6
XS Rating Curve= 0 ,0
Exp/Cntr=0.3,0.1

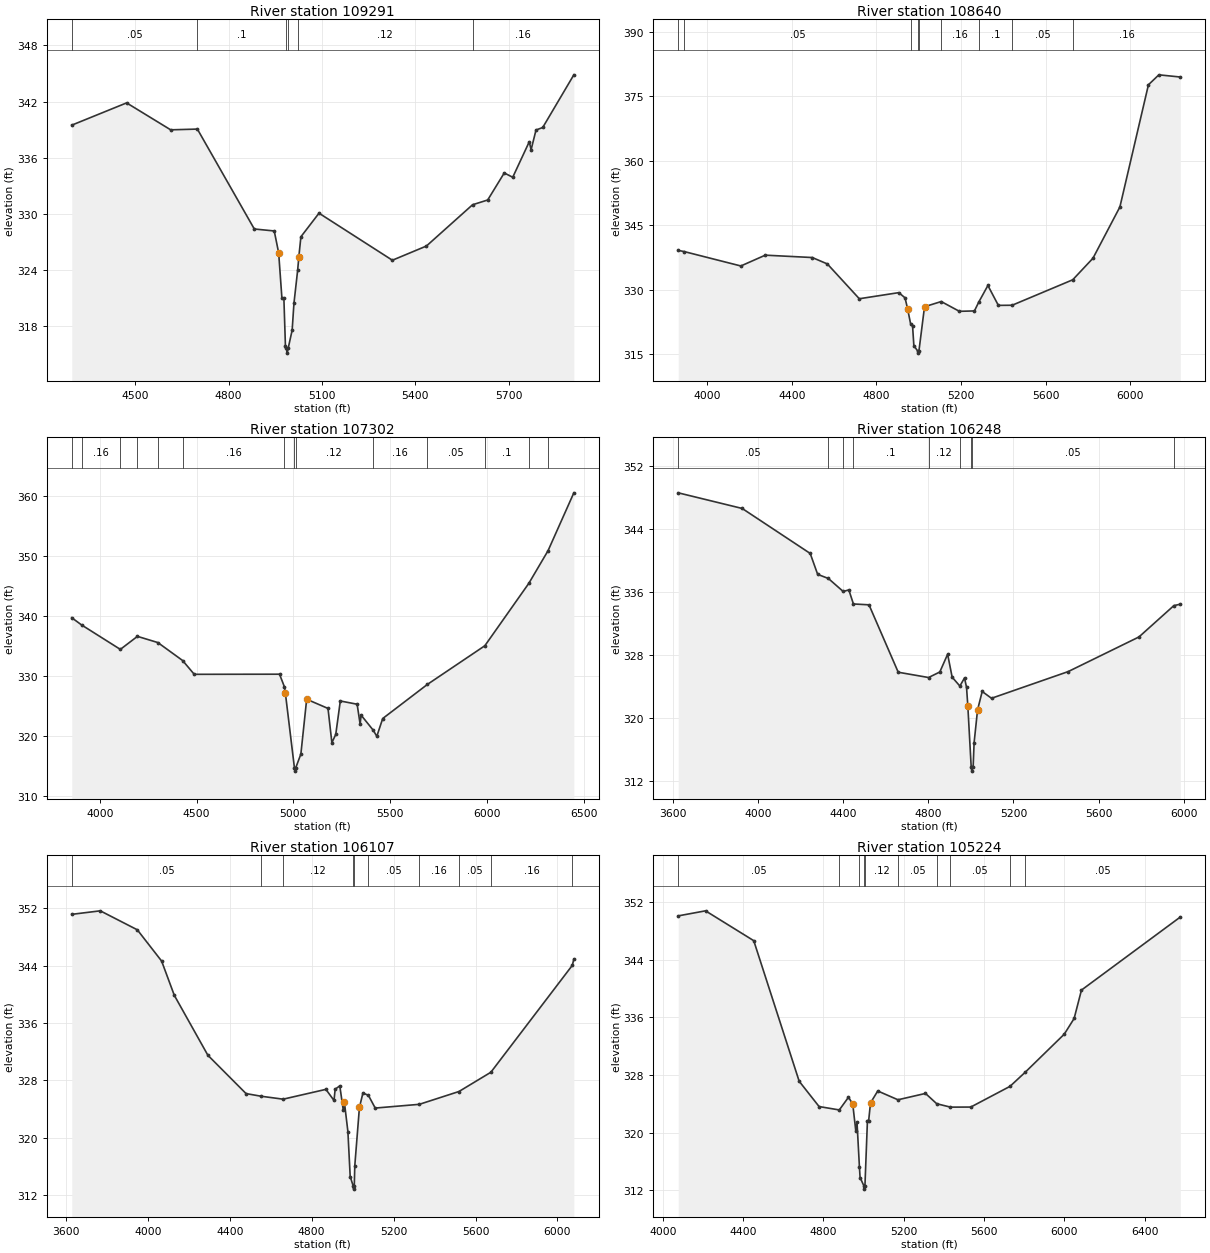
Type RM Length L Ch R = 1 ,109291  ,651,651,651
BEGIN DESCRIPTION:
CEDAR CREEK 92.0
END DESCRIPTION:
XS GIS Cut Line= 3
      3538801.52     10317691.44      3538342.11     10317191.64
      3537531.14     10316726.42
#Sta/Elev= 30
  4295.9  339.48  4472.2  341.86  4613.8  338.98  4699.6  339.06  4882.6  328.38
  4946.7  328.17  4960.9  325.83  4971.4  320.96  4977.7  320.96  4982.7  315.85
  4985.4  315.61  4988.2  315.11  4991.4  315.61  5004.3  317.57    5010  320.42
  5022.1  324.02  5025.8  325.42  5032.4  327.55  5090.6  330.07  5326.4  325.04
  5435.9  326.56  5584.1  330.97  5632.8  331.48    5686  334.37  5713.3  333.91
  5766.5  337.71  5772.3  336.85  5788.1  338.96  5809.7  339.23  5909.7  344.86
#Mann= 6 ,-1 , 0
  4295.9     .05       0  4699.6      .1       0  4985.4     .07       0
  4991.4      .1       0  5022.1     .12       0  5584.1     .16       0
Bank Sta=4960.9,5025.8
XS Rating Curve= 0 ,0
Exp/Cntr=0.3,0.1

Type RM Length L Ch R = 1 ,108640  ,1338,1338,1338
BEGIN DESCRIPTION:
CEDAR CREEK 90.0
END DESCRIPTION:
XS GIS Cut Line= 3
       3539366.6     10317591.35      3538601.83     10316529.14
      3537801.82     10315829.14
#Sta/Elev= 30
  3863.9  339.17  3892.3  338.89  4159.7  335.55  4275.1  338.06  4497.2  337.51
  4568.4  336.02  4719.3  327.94  4905.9  329.36  4935.3  328.15  4947.9  325.51
  4961.3  322.19  4970.9  321.64  4977.1  317.02    4995  315.81  4997.7  315.31
    5001  315.81  5027.4  326.08  5106.3  327.29    5192  325.02  5263.2  325.11
  5283.5  327.15  5326.8  331.02  5376.2   326.4  5441.3  326.43  5727.5  332.34
  5823.2  337.35  5950.4  349.26  6085.2  377.63  6134.5  379.94  6235.8  379.43
#Mann= 9 ,-1 , 0
  3863.9     .16       0  3892.3     .05       0  4961.3     .12       0
    4995     .07       0    5001     .12       0  5106.3     .16       0
  5283.5      .1       0  5441.3     .05       0  5727.5     .16       0
Bank Sta=4947.9,5027.4
XS Rating Curve= 0 ,0
Exp/Cntr=0.3,0.1

Type RM Length L Ch R = 1 ,107302  ,1054,1054,1054
BEGIN DESCRIPTION:
CEDAR CREEK 89.0
END DESCRIPTION:
XS GIS Cut Line= 3
      3539673.89     10317583.52      3539593.18     10316128.93
      3539384.85      10315010.9
#Sta/Elev= 30
  3854.9  339.68  3905.2  338.49  4105.9  334.41  4194.2  336.58  4299.5  335.55
  4427.5  332.56  4487.7  330.26  4928.4  330.28  4953.4  328.19  4958.5  327.14
  5005.5  314.64  5008.3  314.14  5011.5  314.64  5038.6  316.98  5068.6  326.11
  5178.8  324.58  5198.8  318.87  5218.9  320.26  5242.4  325.82  5329.3  325.28
  5344.7  321.98  5349.8  323.46  5411.6  320.99    5431  319.94  5461.5   322.9
  5692.8  328.59  5989.2  335.02  6216.4  345.41  6315.8  350.85    6449  360.48
#Mann= 14 ,-1 , 0
  3854.9     .05       0  3905.2     .16       0  4105.9      .1       0
  4194.2     .16       0  4299.5      .1       0  4427.5     .16       0
  4953.4     .12       0  5005.5     .07       0  5011.5     .12       0
  5411.6     .16       0  5692.8     .05       0  5989.2      .1       0
  6216.4     .16       0  6315.8      .1       0
Bank Sta=4958.5,5068.6
XS Rating Curve= 0 ,0
Exp/Cntr=0.3,0.1

Type RM Length L Ch R = 1 ,106248  ,141,141,141
BEGIN DESCRIPTION:
CEDAR CREEK 88.0
END DESCRIPTION:
XS GIS Cut Line= 3
      3541194.72     10317101.77      3540475.12      10315920.6
      3539613.99     10315455.31
#Sta/Elev= 30
  3622.9  348.57  3923.7  346.59  4243.7  340.89  4278.8  338.24  4329.1  337.72
    4399  336.07  4425.4  336.27    4447  334.49  4520.3  334.38  4657.8  325.84
  4800.5  325.17  4853.4  325.87  4890.2  328.12  4911.5  325.21  4947.8  324.09
  4969.7  325.12  4979.2  323.91  4985.1  321.61  5001.1  313.81  5003.9  313.31
  5007.1  313.81  5010.2  313.81  5014.7   316.9  5030.9  321.05  5052.8   323.4
  5096.6  322.54  5457.2  325.92  5790.3  330.31  5954.5  334.28  5984.8  334.46
#Mann= 9 ,-1 , 0
  3622.9     .05       0  4329.1      .1       0    4399     .05       0
    4447      .1       0  4800.5     .12       0  4947.8     .05       0
  5001.1     .04       0  5007.1     .05       0  5954.5      .1       0
Bank Sta=4985.1,5030.9
XS Rating Curve= 0 ,0
Exp/Cntr=0.3,0.1

Type RM Length L Ch R = 1 ,106107  ,883,883,883
BEGIN DESCRIPTION:
CEDAR CREEK 87.0
END DESCRIPTION:
XS GIS Cut Line= 3
      3541836.26     10316455.33      3540412.62     10315767.82
      3539747.34     10315206.49
#Sta/Elev= 30
  3628.7  351.17  3767.9  351.66  3948.7  349.01  4067.3  344.65  4129.5  339.85
  4293.3  331.49  4479.7  326.14  4553.2  325.77  4660.8  325.36  4869.5  326.73
  4909.1  325.18  4914.7  326.75  4937.3  327.22  4954.3  323.85  4959.9  324.91
  4976.9  320.84  4988.1  314.56  5002.1   313.3  5004.8   312.8  5008.1   313.3
  5010.6  316.08  5033.2  324.21  5050.3  326.22  5076.9   325.9  5110.3  324.12
  5325.5  324.64  5519.1  326.43    5675  329.12  6072.7  344.05  6080.1  344.93
#Mann= 10 ,-1 , 0
  3628.7     .05       0  4553.2     .16       0  4660.8     .12       0
  5002.1     .07       0  5008.1     .12       0  5076.9     .05       0
  5325.5     .16       0  5519.1     .05       0    5675     .16       0
  6072.7     .05       0
Bank Sta=4959.9,5033.2
XS Rating Curve= 0 ,0
Exp/Cntr=0.3,0.1

Type RM Length L Ch R = 1 ,105224  ,1040,1040,1040
BEGIN DESCRIPTION:
CEDAR CREEK 86.0
END DESCRIPTION:
XS GIS Cut Line= 3
      3541905.65     10316330.29      3541447.66     10315856.92
      3540476.12     10314290.27
#Sta/Elev= 30
  4076.3  350.06  4212.3  350.76  4452.6  346.62    4679  327.13  4778.2  323.62
    4879  323.15  4924.7  324.91  4945.9  323.98  4961.3  320.22  4967.2  321.47
  4979.2  315.28  4982.5  313.78  5000.8  312.67  5003.5  312.17  5006.8  312.67
  5019.2  321.68    5025  321.58  5034.5  324.13  5070.6  325.78  5171.3  324.56
  5308.5  325.44  5364.5  324.01    5433  323.54  5534.2  323.55  5729.6  326.42
  5804.8  328.36  6000.2  333.66  6049.2  335.83  6085.8  339.77  6578.4   349.9
#Mann= 10 ,-1 , 0
  4076.3     .05       0    4879     .16       0  4979.2     .12       0
  5000.8     .07       0  5006.8     .12       0  5171.3     .05       0
  5364.5     .12       0    5433     .05       0  5729.6      .1       0
  5804.8     .05       0
Bank Sta=4945.9,5034.5
XS Rating Curve= 0 ,0
Exp/Cntr=0.3,0.1

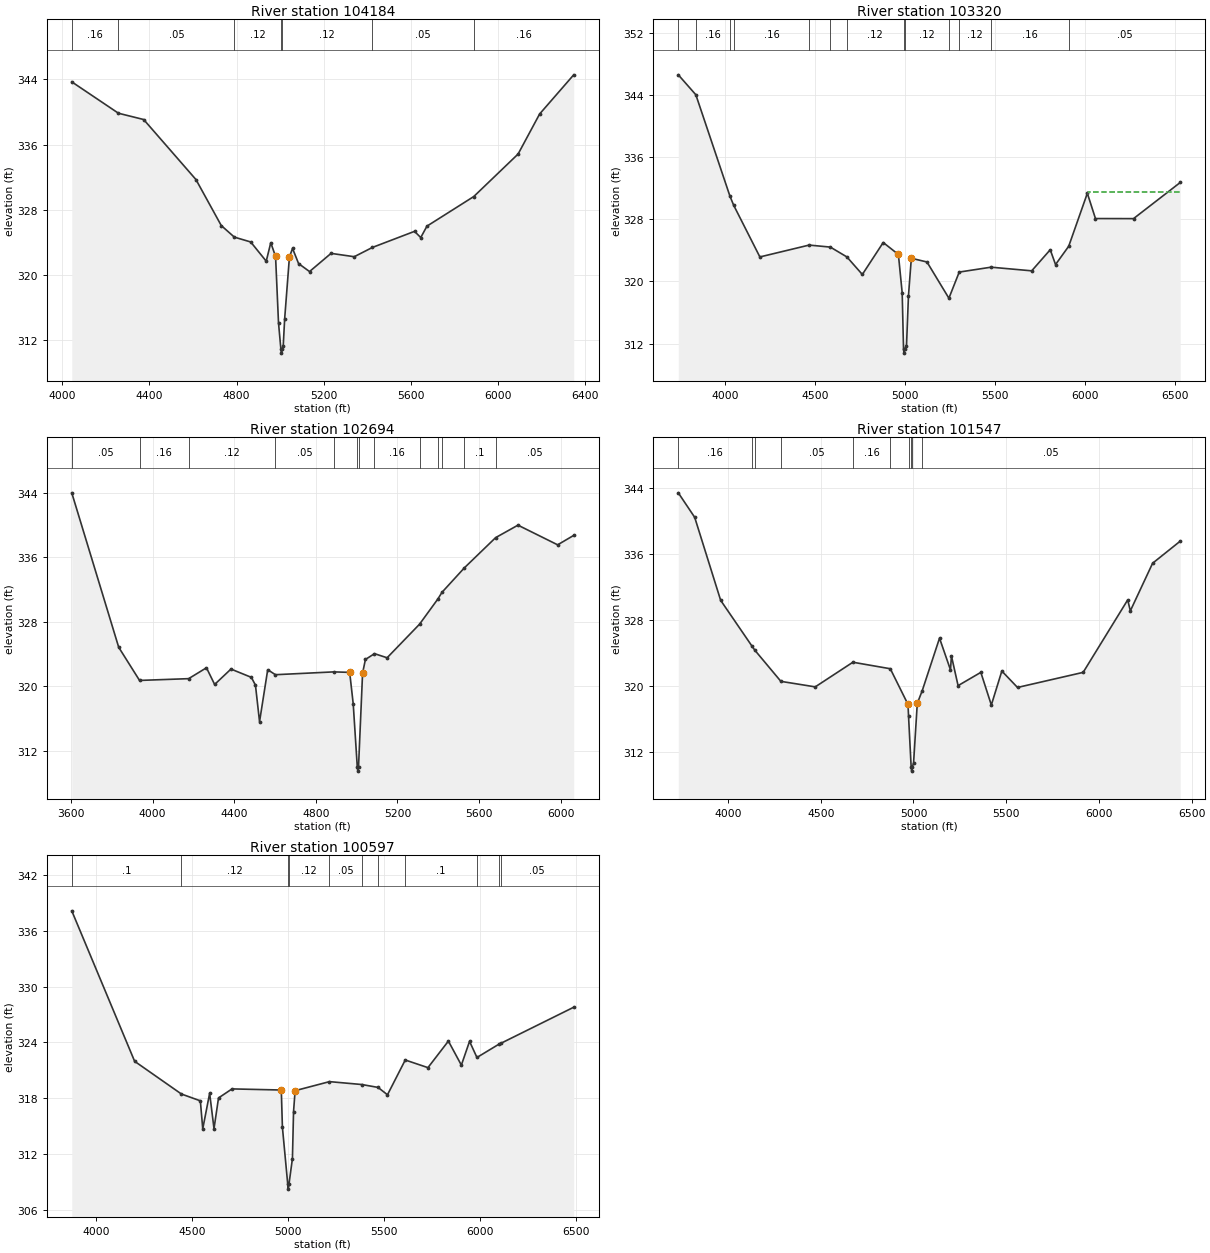
Type RM Length L Ch R = 1 ,104184  ,864,864,864
BEGIN DESCRIPTION:
CEDAR CREEK 84.0
END DESCRIPTION:
XS GIS Cut Line= 3
      3542092.11      10315741.6      3542086.23     10315121.98
       3540992.1     10313841.64
#Sta/Elev= 30
  4043.5  343.69  4257.8  339.84  4373.5  339.07  4613.5  331.71  4729.7  326.07
  4789.8  324.65  4864.7  324.06  4936.1   321.7  4956.9  323.97  4978.9  322.28
  4992.4  314.15  5003.3  310.93  5006.1  310.43  5009.3  310.93    5014  311.28
  5020.6  314.62  5042.5  322.21  5056.8  323.27  5084.5  321.41  5134.8  320.43
  5233.6  322.66    5340  322.25  5423.6  323.39  5616.7  325.36  5645.2   324.6
  5673.8     326  5888.7  329.63  6092.1  334.84  6190.9  339.75  6347.3  344.55
#Mann= 7 ,-1 , 0
  4043.5     .16       0  4257.8     .05       0  4789.8     .12       0
  5003.3     .07       0  5009.3     .12       0  5423.6     .05       0
  5888.7     .16       0
Bank Sta=4978.9,5042.5
XS Rating Curve= 0 ,0
Exp/Cntr=0.3,0.1

Type RM Length L Ch R = 1 ,103320  ,626,626,626
BEGIN DESCRIPTION:
CEDAR CREEK 83.0
END DESCRIPTION:
XS GIS Cut Line= 3
      3542992.09     10315791.61      3542592.11     10314591.64
      3541850.13     10313260.89
#Sta/Elev= 30
  3742.1  346.64  3839.6  344.07  4028.4  331.04  4049.4  329.84  4195.3  323.16
    4469  324.69  4586.9  324.43  4678.8  323.16  4764.5   320.9  4880.5  325.02
  4964.8  323.48  4985.9  318.53  4993.4  311.26  4996.2  310.76  4999.4  311.26
  5009.8  311.66  5020.7  318.14  5036.7  322.99  5123.6  322.51  5245.4  317.84
  5302.8  321.21  5479.6  321.84  5705.4  321.37  5808.4  324.09  5837.8  322.18
    5911  324.54  6014.5  331.37  6059.6  328.11    6271   328.1  6530.6  332.76
#Mann= 13 ,-1 , 0
  3742.1     .05       0  3839.6     .16       0  4028.4     .05       0
  4049.4     .16       0    4469     .12       0  4586.9     .16       0
  4678.8     .12       0  4993.4     .07       0  4999.4     .12       0
  5245.4     .16       0  5302.8     .12       0  5479.6     .16       0
    5911     .05       0
#XS Ineff= 2 , 0
                         6018.17          331.48
Permanent Ineff=
       F       F
Bank Sta=4964.8,5036.7
XS Rating Curve= 0 ,0
Exp/Cntr=0.3,0.1

Type RM Length L Ch R = 1 ,102694  ,1147,1147,1147
BEGIN DESCRIPTION:
CEDAR CREEK 82.0
END DESCRIPTION:
XS GIS Cut Line= 3
      3543192.11     10315691.63      3543197.34     10314455.32
      3542684.01      10313345.4
#Sta/Elev= 30
  3604.2  344.01  3834.2  324.85  3936.3  320.74  4176.8  320.96  4264.2  322.31
  4304.2  320.24  4384.2  322.15  4484.2  321.12  4504.2  320.15  4524.2  315.62
  4564.2  322.07    4602  321.45  4887.8   321.8  4965.8  321.74  4983.2  317.82
  5003.1  309.99  5005.8  309.49  5009.1  309.99    5029  321.64  5042.9  323.34
  5087.4  324.06  5149.2  323.55  5307.9  327.71  5397.3  330.82  5418.1  331.67
  5528.3  334.72  5680.8  338.45  5790.3     340  5984.7  337.56  6063.4  338.73
#Mann= 13 ,-1 , 0
  3604.2     .05       0  3936.3     .16       0  4176.8     .12       0
    4602     .05       0  4887.8     .12       0  5003.1     .07       0
  5009.1     .12       0  5087.4     .16       0  5307.9     .05       0
  5397.3     .16       0  5418.1     .05       0  5528.3      .1       0
  5680.8     .05       0
Bank Sta=4965.8,5029
XS Rating Curve= 0 ,0
Exp/Cntr=0.3,0.1

Type RM Length L Ch R = 1 ,101547  ,950,950,950
BEGIN DESCRIPTION:
CEDAR CREEK 81.0
END DESCRIPTION:
XS GIS Cut Line= 3
      3543801.51     10315990.04       3543752.9     10314378.93
      3543002.91     10313580.33
#Sta/Elev= 30
  3731.4  343.45  3819.8  340.48  3959.9  330.41  4129.9  324.82  4144.2  324.36
  4284.7  320.58  4470.1  319.91  4673.1   322.9  4874.9  322.11  4970.4  317.78
  4973.3  316.37  4987.4  310.19  4990.1  309.69  4993.4  310.19  5000.4  310.67
  5020.4   317.9  5047.3  319.46  5140.4  325.82  5199.6  321.97  5204.6  323.67
  5240.5  320.06  5363.2  321.67  5419.9  317.71  5476.5  321.83    5561  319.84
  5915.1  321.67  6155.4  330.46  6169.6  329.13  6289.8  334.91  6438.8  337.59
#Mann= 10 ,-1 , 0
  3731.4     .16       0  4129.9     .05       0  4144.2     .16       0
  4284.7     .05       0  4673.1     .16       0  4874.9      .1       0
  4973.3     .12       0  4987.4     .07       0  4993.4     .12       0
  5047.3     .05       0
Bank Sta=4970.4,5020.4
XS Rating Curve= 0 ,0
Exp/Cntr=0.3,0.1

Type RM Length L Ch R = 1 ,100597  ,1033,1033,1033
BEGIN DESCRIPTION:
CEDAR CREEK 80.0
END DESCRIPTION:
XS GIS Cut Line= 3
      3545433.46     10314809.49      3544211.23     10314059.48
      3543205.73     10313442.31
#Sta/Elev= 30
  3875.2  338.12  4202.6  321.98  4446.3  318.47  4544.8  317.74  4557.3  314.74
  4593.2  318.55  4615.9  314.76  4639.4  318.05  4709.8  319.02  4966.3   318.9
  4972.1  314.91    5000  308.77  5002.7  308.27    5006  308.77  5024.3  311.55
  5030.1  316.59  5038.3  318.83  5217.3   319.8  5385.5  319.49  5470.1  319.18
  5519.2  318.39  5611.8  322.12    5730   321.3  5836.4  324.15    5904  321.57
  5946.6  324.12  5985.1  322.39  6100.7  323.83  6107.8  323.89    6489  327.78
#Mann= 11 ,-1 , 0
  3875.2      .1       0  4446.3     .12       0    5000     .07       0
    5006     .12       0  5217.3     .05       0  5385.5      .1       0
  5470.1     .12       0  5611.8      .1       0  5985.1     .05       0
  6100.7      .1       0  6107.8     .05       0
Bank Sta=4966.3,5038.3
XS Rating Curve= 0 ,0
Exp/Cntr=0.3,0.1