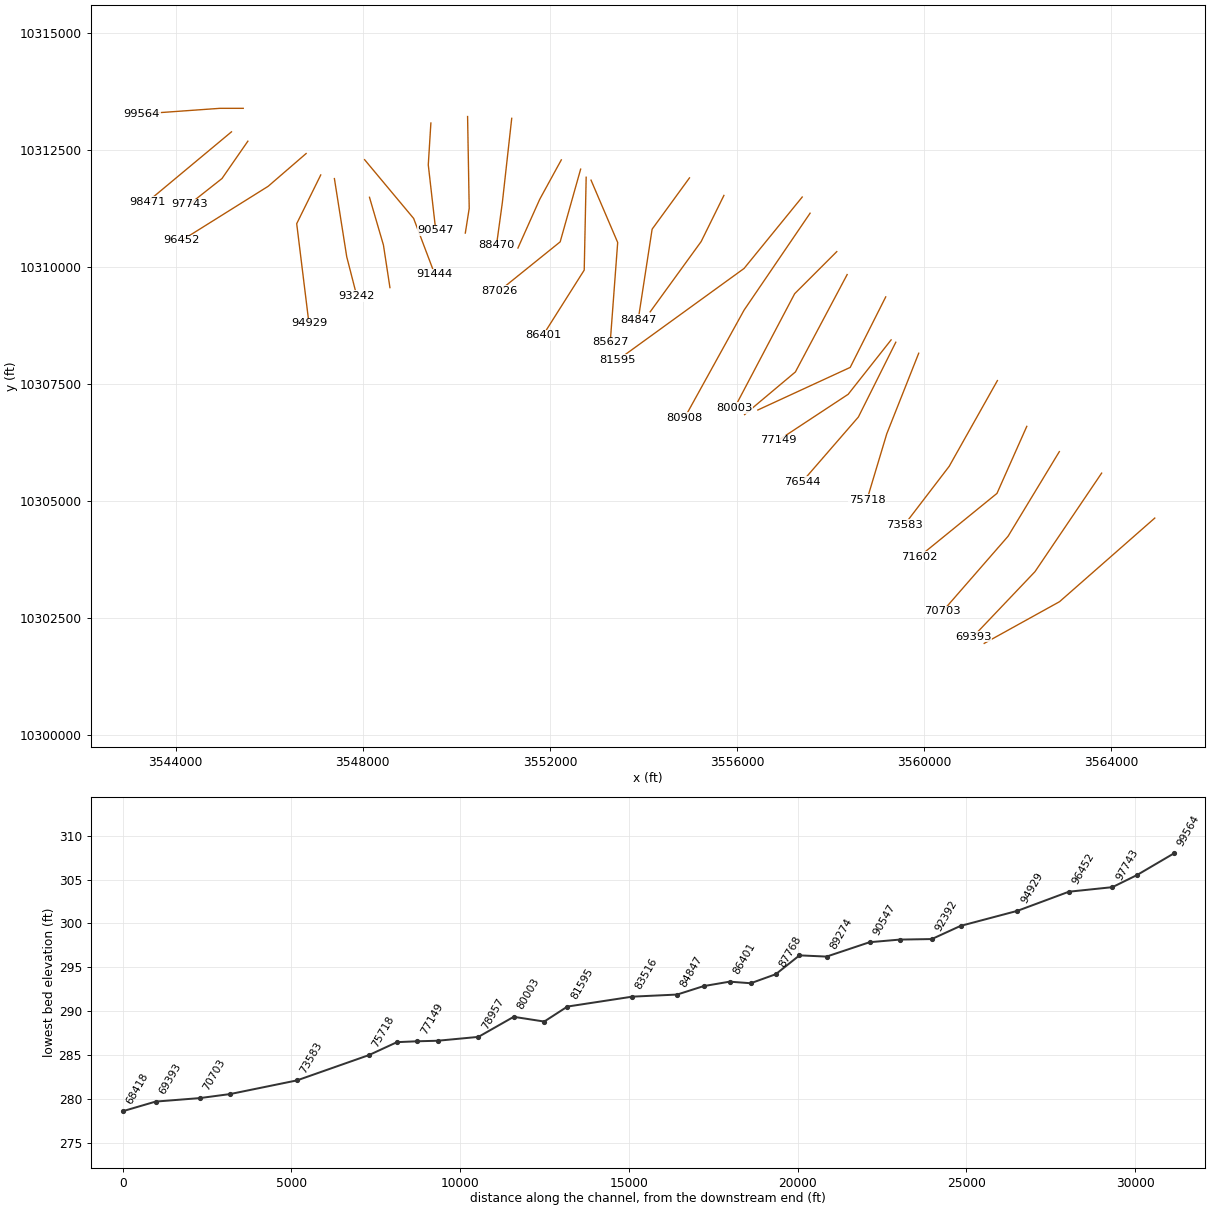
HEC-RAS study CEDAR CREEK.prj: CEDAR CREEK Base Level Engineering

--- CEDAR CREEK.g01 (geometry) --- (continued)

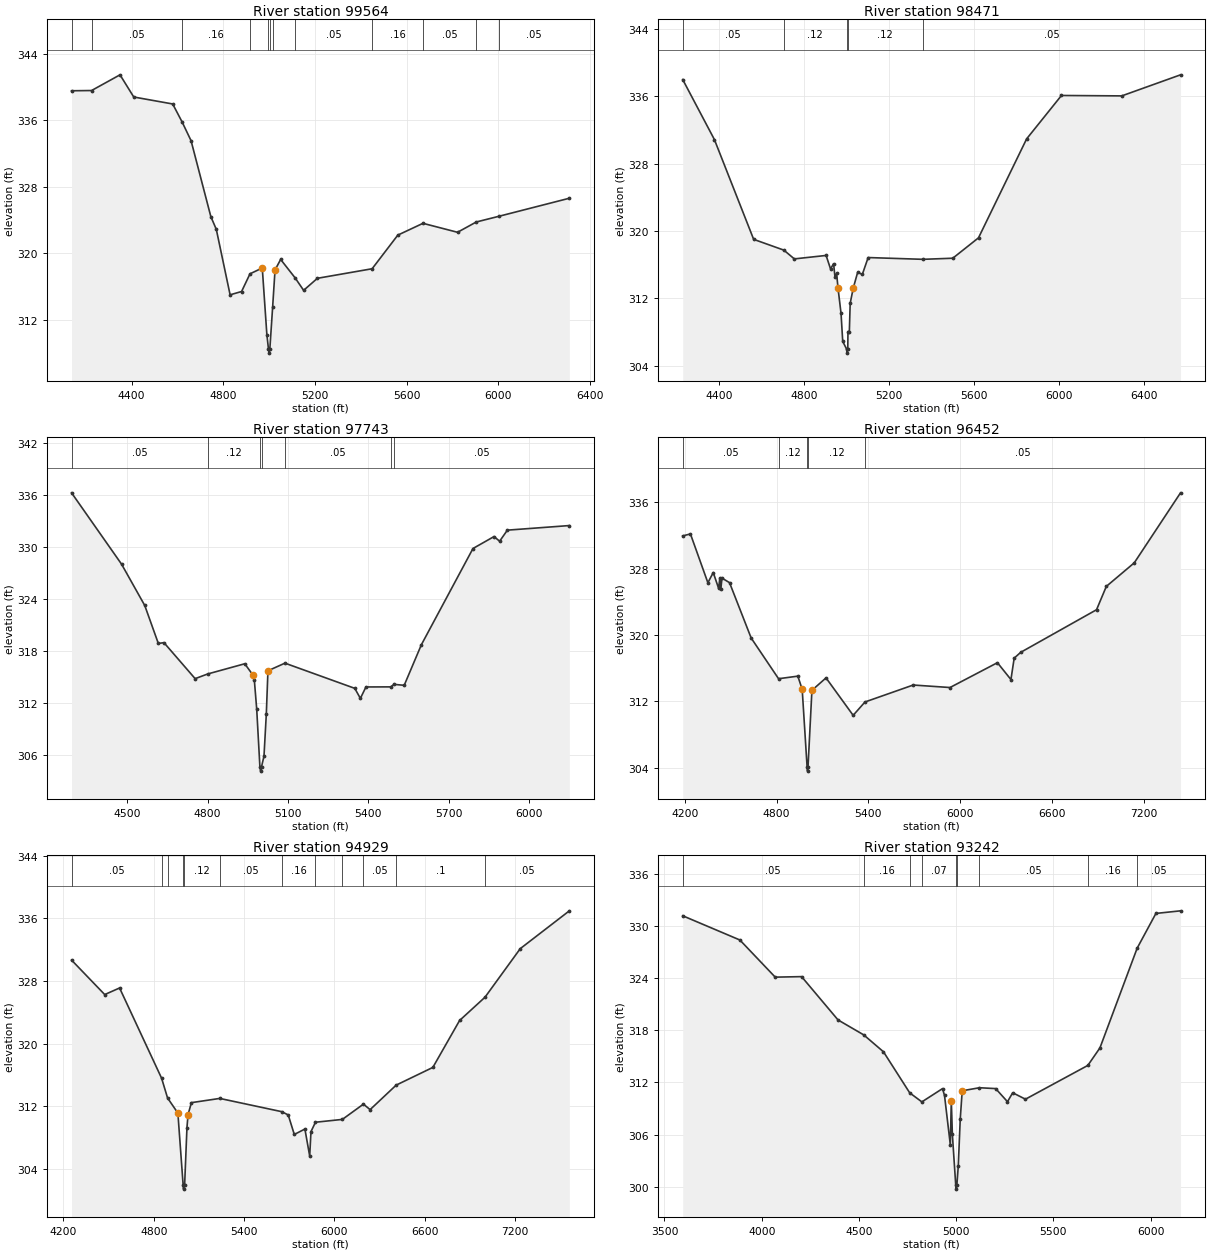
Type RM Length L Ch R = 1 ,99564   ,1093,1093,1093
BEGIN DESCRIPTION:
CEDAR CREEK 79.0
END DESCRIPTION:
XS GIS Cut Line= 3
      3545443.51     10313394.42      3544943.49     10313394.42
      3543275.39     10313274.88
#Sta/Elev= 30
    4138  339.57  4225.4   339.6  4349.4  341.49  4409.4  338.82  4579.4  337.98
  4620.5  335.81  4659.5  333.56  4745.8  324.42  4769.7  322.88  4829.9     315
    4880   315.4  4916.7  317.53  4970.3  318.23  4990.3  310.22  4997.3  308.48
  5000.1  307.98  5003.3  308.48  5015.4  313.48    5026     318  5050.5  319.26
  5114.2  317.02  5150.7  315.54  5210.9  316.99  5449.7  318.14  5561.8  322.19
  5671.6  323.61  5822.4  322.53  5904.2  323.77    6002  324.45  6310.4  326.63
#Mann= 12 ,-1 , 0
    4138     .16       0  4225.4     .05       0  4620.5     .16       0
  4916.7     .12       0  4997.3     .07       0  5003.3     .12       0
  5015.4     .16       0  5114.2     .05       0  5449.7     .16       0
  5671.6     .05       0  5904.2     .16       0    6002     .05       0
Bank Sta=4970.3,5026
XS Rating Curve= 0 ,0
Exp/Cntr=0.3,0.1

Type RM Length L Ch R = 1 ,98471   ,728,728,728
BEGIN DESCRIPTION:
CEDAR CREEK 78.0
END DESCRIPTION:
XS GIS Cut Line= 3
      3545192.12     10312891.65      3544592.11     10312391.64
       3543392.1     10311391.64
#Sta/Elev= 30
  4230.5  337.97  4379.6  330.85  4564.4  319.01  4706.6  317.73  4755.8  316.69
  4905.4   317.1  4926.3   315.5  4940.6  316.12  4947.1  314.55  4954.9  314.96
  4961.4  313.24  4975.7  310.22  4983.6   306.9  5001.4  306.01  5004.1  305.51
  5007.4  306.01  5008.3  308.07  5014.8  308.07  5018.7  311.41    5033  313.21
  5053.8  315.09    5076  314.86  5103.3  316.85  5360.8  316.64  5501.6  316.77
  5622.7  319.19  5849.2  330.93  6013.2  336.08    6297  336.03  6573.6  338.53
#Mann= 5 ,-1 , 0
  4230.5     .05       0  4706.6     .12       0  5001.4     .07       0
  5007.4     .12       0  5360.8     .05       0
Bank Sta=4961.4,5033
XS Rating Curve= 0 ,0
Exp/Cntr=0.3,0.1

Type RM Length L Ch R = 1 ,97743   ,1291,1291,1291
BEGIN DESCRIPTION:
CEDAR CREEK 77.0
END DESCRIPTION:
XS GIS Cut Line= 3
      3545542.13     10312691.67      3544989.01     10311892.82
      3544294.53     10311344.18
#Sta/Elev= 30
  4292.9  336.27  4479.4  328.03  4565.9  323.26  4616.6  318.87  4637.5  318.97
  4753.8  314.81  4800.6  315.35  4938.9  316.53  4968.6  315.26  4974.7  314.63
  4983.5  311.28  4995.4  304.63  4998.1  304.13  5001.4  304.63  5010.6  305.85
  5019.3  310.72  5025.4  315.72  5088.8   316.6  5349.3  313.69  5370.1  312.53
  5390.9  313.85  5483.4  313.86  5495.7  314.15  5533.6  314.04  5597.7  318.73
  5790.1  329.84  5868.7  331.22  5889.5  330.68  5918.4  331.96  6149.6  332.49
#Mann= 7 ,-1 , 0
  4292.9     .05       0  4800.6     .12       0  4995.4     .07       0
  5001.4     .12       0  5088.8     .05       0  5483.4      .1       0
  5495.7     .05       0
Bank Sta=4968.6,5025.4
XS Rating Curve= 0 ,0
Exp/Cntr=0.3,0.1

Type RM Length L Ch R = 1 ,96452   ,1523,1523,1523
BEGIN DESCRIPTION:
CEDAR CREEK 76.0
END DESCRIPTION:
XS GIS Cut Line= 3
      3546787.65     10312427.56      3545975.12     10311726.15
      3544126.75      10310568.8
#Sta/Elev= 30
  4186.6  331.94    4237  332.18  4351.1   326.3  4386.2  327.53  4421.3  325.62
    4429  326.84  4435.6  325.51  4443.2  326.86  4492.6  326.31  4634.1  319.64
  4813.1  314.74  4939.1  315.05  4967.6  313.46  4999.7  304.11  5002.5  303.61
  5005.7  304.11  5031.2  313.34  5123.4  314.84  5300.8  310.33  5378.2  311.94
  5693.3  313.98  5933.8  313.68  6243.8  316.67  6332.2  314.64  6353.4  317.22
  6396.2  317.92  6891.8  323.05  6955.8  325.86  7138.5   328.7  7440.8  337.13
#Mann= 5 ,-1 , 0
  4186.6     .05       0  4813.1     .12       0  4999.7     .07       0
  5005.7     .12       0  5378.2     .05       0
Bank Sta=4967.6,5031.2
XS Rating Curve= 0 ,0
Exp/Cntr=0.3,0.1

Type RM Length L Ch R = 1 ,94929   ,1687,1687,1687
BEGIN DESCRIPTION:
CEDAR CREEK 75.0
END DESCRIPTION:
XS GIS Cut Line= 3
      3547100.11     10311969.18      3546586.23     10310927.54
      3546847.79     10308797.74
#Sta/Elev= 30
  4253.7  330.67    4474  326.27  4572.8  327.11  4851.9  315.59  4891.5  313.07
  4960.1  311.14  4995.1  301.93  4997.8  301.43  5001.1  301.93    5005     302
  5020.4  309.28  5027.5  310.93  5049.9  312.47  5238.3  313.01  5649.8  311.32
  5693.2   310.9  5733.5  308.41    5804   309.1  5835.9  305.65  5844.3  308.77
  5874.2  309.97  6052.7  310.33  6192.8  312.28  6237.2  311.58  6410.5  314.71
  6654.1  316.97  6831.7  322.96  7000.5  325.93  7234.7  332.13    7561  336.96
#Mann= 12 ,-1 , 0
  4253.7     .05       0  4851.9     .16       0  4891.5     .12       0
  4995.1     .07       0  5001.1     .12       0  5238.3     .05       0
  5649.8     .16       0  5874.2     .05       0  6052.7      .1       0
  6192.8     .05       0  6410.5      .1       0  7000.5     .05       0
Bank Sta=4960.1,5027.5
XS Rating Curve= 0 ,0
Exp/Cntr=0.3,0.1

Type RM Length L Ch R = 1 ,93242   ,850,850,850
BEGIN DESCRIPTION:
CEDAR CREEK 74.0
END DESCRIPTION:
XS GIS Cut Line= 3
       3547392.1     10311891.68      3547655.68     10310219.21
      3547870.95     10309378.96
#Sta/Elev= 30
  3593.8   331.2  3887.7  328.41  4069.6  324.13  4205.2  324.19  4392.7   319.2
  4524.8  317.48  4626.4  315.53  4761.4   310.8  4823.9  309.76  4930.1  311.29
  4940.3  310.51  4970.2  304.82  4975.3   309.9  4980.7  306.03    4998  300.21
  5000.7  299.71    5004  300.21  5011.1  302.36  5021.2  307.76  5031.4  311.04
  5120.3  311.39  5203.5  311.29  5264.2  309.78  5291.1  310.81  5356.7  310.07
  5677.5  313.96  5739.8  315.98  5931.3  327.47  6027.7  331.47  6154.3  331.77
#Mann= 9 ,-1 , 0
  3593.8     .05       0  4524.8     .16       0  4761.4     .05       0
  4823.9     .07       0    4998     .07       0    5004     .07       0
  5120.3     .05       0  5677.5     .16       0  5931.3     .05       0
Bank Sta=4975.3,5031.4
XS Rating Curve= 0 ,0
Exp/Cntr=0.3,0.1

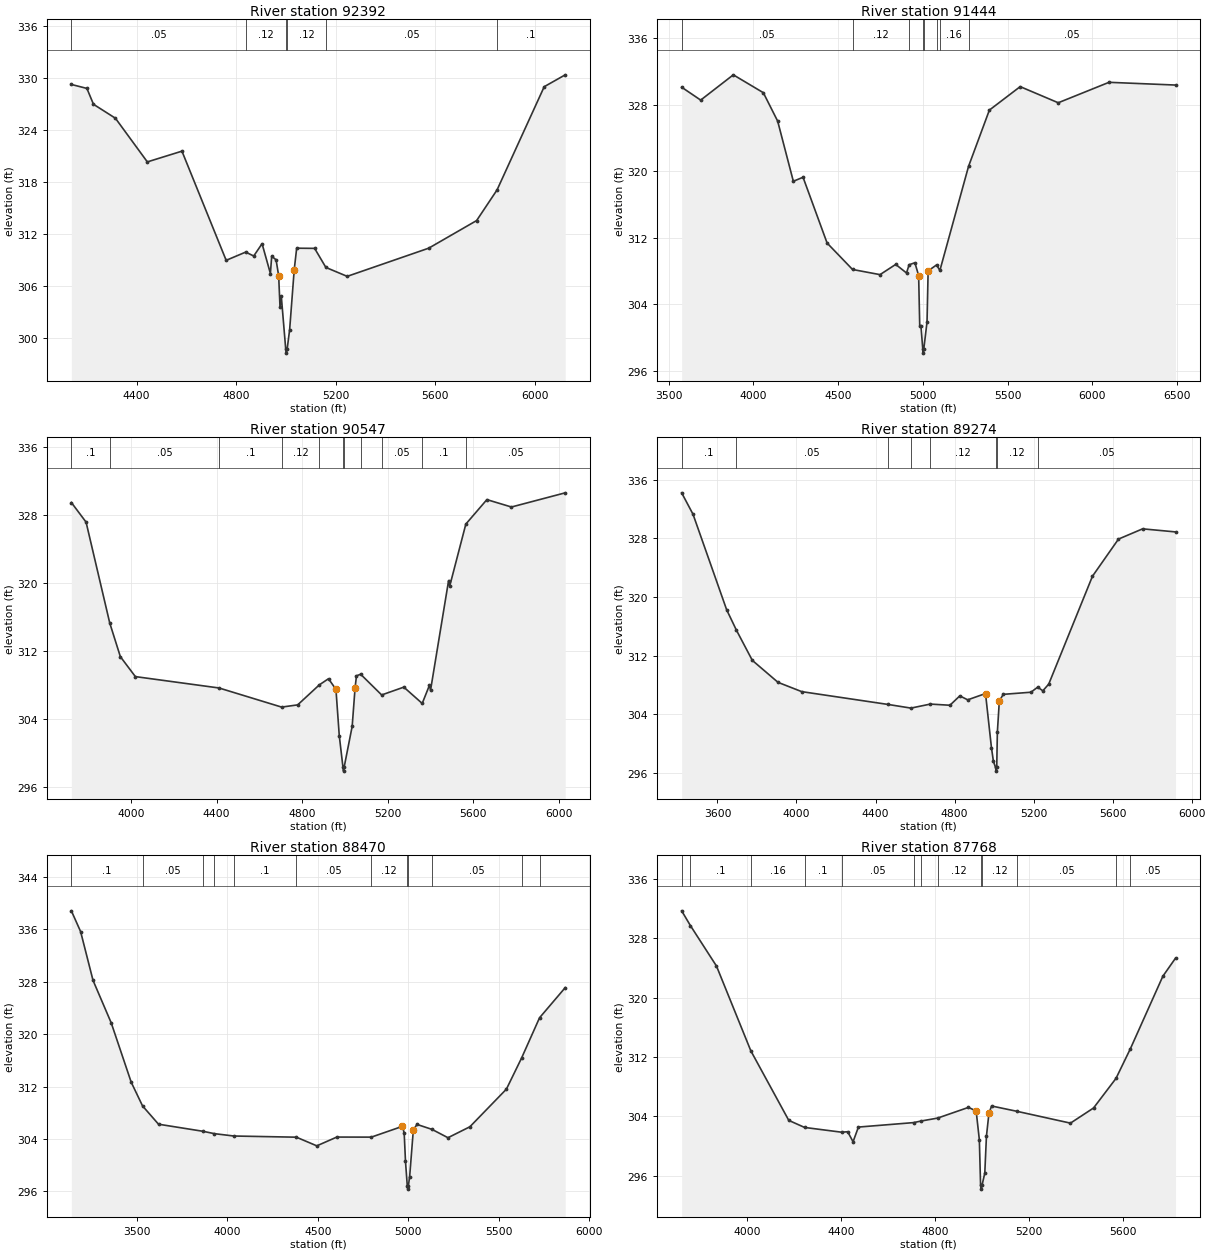
Type RM Length L Ch R = 1 ,92392   ,948,948,948
BEGIN DESCRIPTION:
CEDAR CREEK 72.0
END DESCRIPTION:
XS GIS Cut Line= 3
      3548142.11     10311491.61       3548440.4     10310469.21
      3548579.29     10309559.47
#Sta/Elev= 30
  4138.1  329.22  4200.6  328.76    4227  326.93  4315.2  325.32  4443.5  320.28
  4582.6  321.52  4760.4  308.92  4838.8  309.87  4871.2  309.42  4904.7  310.84
  4938.2   307.4  4943.4  309.39    4961  308.98  4971.4  307.16  4976.9  303.51
  4982.1  304.75  4999.7  298.71  5002.4  298.21  5005.7  298.71  5015.6  300.93
  5033.9  307.82  5043.8  310.32    5116   310.3  5161.2   308.1  5246.9  307.07
  5574.4  310.32  5767.2  313.51  5849.4  317.05  6038.9  328.96  6123.4  330.33
#Mann= 6 ,-1 , 0
  4138.1     .05       0  4838.8     .12       0  4999.7     .07       0
  5005.7     .12       0  5161.2     .05       0  5849.4      .1       0
Bank Sta=4971.4,5033.9
XS Rating Curve= 0 ,0
Exp/Cntr=0.3,0.1

Type RM Length L Ch R = 1 ,91444   ,897,897,897
BEGIN DESCRIPTION:
CEDAR CREEK 71.0
END DESCRIPTION:
XS GIS Cut Line= 3
      3548037.62      10312295.6      3549086.23     10311038.65
      3549537.62     10309844.22
#Sta/Elev= 30
  3577.3  330.13  3689.5  328.58    3882  331.62  4059.1  329.47  4143.7  326.05
  4236.1  318.82  4293.4   319.3  4435.3  311.39  4585.4  308.21  4747.6  307.59
  4840.1  308.82  4903.8  307.79  4919.3  308.78  4953.3  309.02  4975.4  307.48
  4981.9   301.4  4988.9  301.42  4999.8  298.65  5002.5  298.15  5005.8  298.65
  5024.9  301.91  5031.4  308.04  5081.2  308.76  5100.7  308.09  5269.8  320.61
  5392.8  327.38  5574.5   330.2    5799  328.26  6098.6  330.72  6491.1  330.39
#Mann= 8 ,-1 , 0
  3577.3     .05       0  4585.4     .12       0  4919.3     .07       0
  4999.8     .07       0  5005.8     .07       0  5081.2     .12       0
  5100.7     .16       0  5269.8     .05       0
Bank Sta=4975.4,5031.4
XS Rating Curve= 0 ,0
Exp/Cntr=0.3,0.1

Type RM Length L Ch R = 1 ,90547   ,1273,1273,1273
BEGIN DESCRIPTION:
CEDAR CREEK 70.0
END DESCRIPTION:
XS GIS Cut Line= 3
      3549454.29     10313080.34      3549398.73     10312184.48
      3549558.45     10310781.72
#Sta/Elev= 30
  3720.7  329.48  3789.5  327.17  3900.2  315.29  3949.8  311.33    4020  308.98
  4411.3  307.64  4703.8  305.39  4778.9  305.65  4880.3  308.01  4923.1  308.73
  4957.9  307.48  4973.4  302.04  4990.5  298.35  4993.3  297.85  4996.5  298.35
  5033.8  303.12  5047.4  307.66  5053.9  309.07  5073.3  309.26  5171.7  306.82
  5275.3  307.74  5361.3  305.82  5395.3  307.97  5400.3  307.38  5484.7  320.29
  5489.8  319.63  5565.3  326.94  5663.7  329.82  5778.6  328.95  6030.1  330.62
#Mann= 11 ,-1 , 0
  3720.7      .1       0  3900.2     .05       0  4411.3      .1       0
  4703.8     .12       0  4880.3     .07       0  4990.5     .07       0
  4996.5     .07       0  5073.3     .12       0  5171.7     .05       0
  5361.3      .1       0  5565.3     .05       0
Bank Sta=4957.9,5047.4
XS Rating Curve= 0 ,0
Exp/Cntr=0.3,0.1

Type RM Length L Ch R = 1 ,89274   ,804,804,804
BEGIN DESCRIPTION:
CEDAR CREEK 68.0
END DESCRIPTION:
XS GIS Cut Line= 3
      3550239.01     10313219.16      3550273.73     10311253.93
      3550190.44      10310726.4
#Sta/Elev= 30
  3418.9  334.23  3476.4   331.3  3646.5  318.26  3695.9  315.47  3776.5  311.34
  3906.5  308.34  4026.5  307.07  4460.9  305.33  4579.3  304.82  4677.5  305.37
  4776.6  305.21  4826.6  306.49  4866.6  305.95  4956.7  306.81  4986.7  299.43
  4996.7  297.55  5007.5  296.71  5010.2  296.21  5013.5  296.71  5016.7  301.55
  5026.7  305.81  5046.7   306.7  5186.7  306.99  5221.1  307.69  5246.7  307.18
  5276.7   308.1  5498.1  322.84  5629.7  327.91  5751.9  329.31  5918.5  328.89
#Mann= 8 ,-1 , 0
  3418.9      .1       0  3695.9     .05       0  4460.9      .1       0
  4579.3     .05       0  4677.5     .12       0  5007.5     .07       0
  5013.5     .12       0  5221.1     .05       0
Bank Sta=4956.7,5026.7
XS Rating Curve= 0 ,0
Exp/Cntr=0.3,0.1

Type RM Length L Ch R = 1 ,88470   ,702,702,702
BEGIN DESCRIPTION:
CEDAR CREEK 67.0
END DESCRIPTION:
XS GIS Cut Line= 3
      3551182.39     10313180.58      3550982.38     10311380.53
      3550857.08     10310469.33
#Sta/Elev= 30
  3137.5  338.79  3188.6  335.63  3257.2  328.19  3357.8  321.71  3468.5  312.65
  3531.1  309.04  3619.4  306.25  3865.2  305.17  3928.2  304.81  4035.7  304.45
  4381.9  304.27  4494.7  302.95  4605.4  304.29  4796.3  304.28  4967.7  305.92
  4977.8  304.94  4985.1  300.57    4995  296.85  4997.7  296.35    5001  296.85
  5008.1  298.26  5028.3  305.33  5048.4  306.22  5131.7  305.46    5220  304.19
  5341.2  305.86  5543.1   311.6  5626.6  316.32  5726.3  322.48  5868.4  327.08
#Mann= 12 ,-1 , 0
  3137.5      .1       0  3531.1     .05       0  3865.2      .1       0
  3928.2     .05       0  4035.7      .1       0  4381.9     .05       0
  4796.3     .12       0    4995     .07       0    5001     .12       0
  5131.7     .05       0  5626.6     .16       0  5726.3     .05       0
Bank Sta=4967.7,5028.3
XS Rating Curve= 0 ,0
Exp/Cntr=0.3,0.1

Type RM Length L Ch R = 1 ,87768   ,742,742,742
BEGIN DESCRIPTION:
CEDAR CREEK 66.0
END DESCRIPTION:
XS GIS Cut Line= 3
      3552242.09     10312291.61      3551780.68     10311448.37
      3551315.39     10310406.69
#Sta/Elev= 30
  3721.7  331.69  3758.9   329.7  3869.9  324.25  4016.1  312.83  4177.6  303.46
  4244.9  302.51    4402  301.87  4428.4  301.93  4451.2  300.58    4474  302.56
  4708.6  303.16    4742  303.38  4811.2  303.77  4942.3  305.21  4975.1  304.73
  4988.7  300.86    4994   294.7  4996.7   294.2    5000   294.7  5011.9  296.36
  5018.9  301.33  5029.6  304.43  5040.8   305.4  5149.1  304.68  5376.5  303.09
  5474.8  305.13  5570.2  309.11    5632  313.14  5769.8  322.88  5823.8  325.32
#Mann= 13 ,-1 , 0
  3721.7     .16       0  3758.9      .1       0  4016.1     .16       0
  4244.9      .1       0    4402     .05       0  4708.6     .12       0
    4742     .05       0  4811.2     .12       0    4994     .07       0
    5000     .12       0  5149.1     .05       0  5570.2      .1       0
    5632     .05       0
Bank Sta=4975.1,5029.6
XS Rating Curve= 0 ,0
Exp/Cntr=0.3,0.1

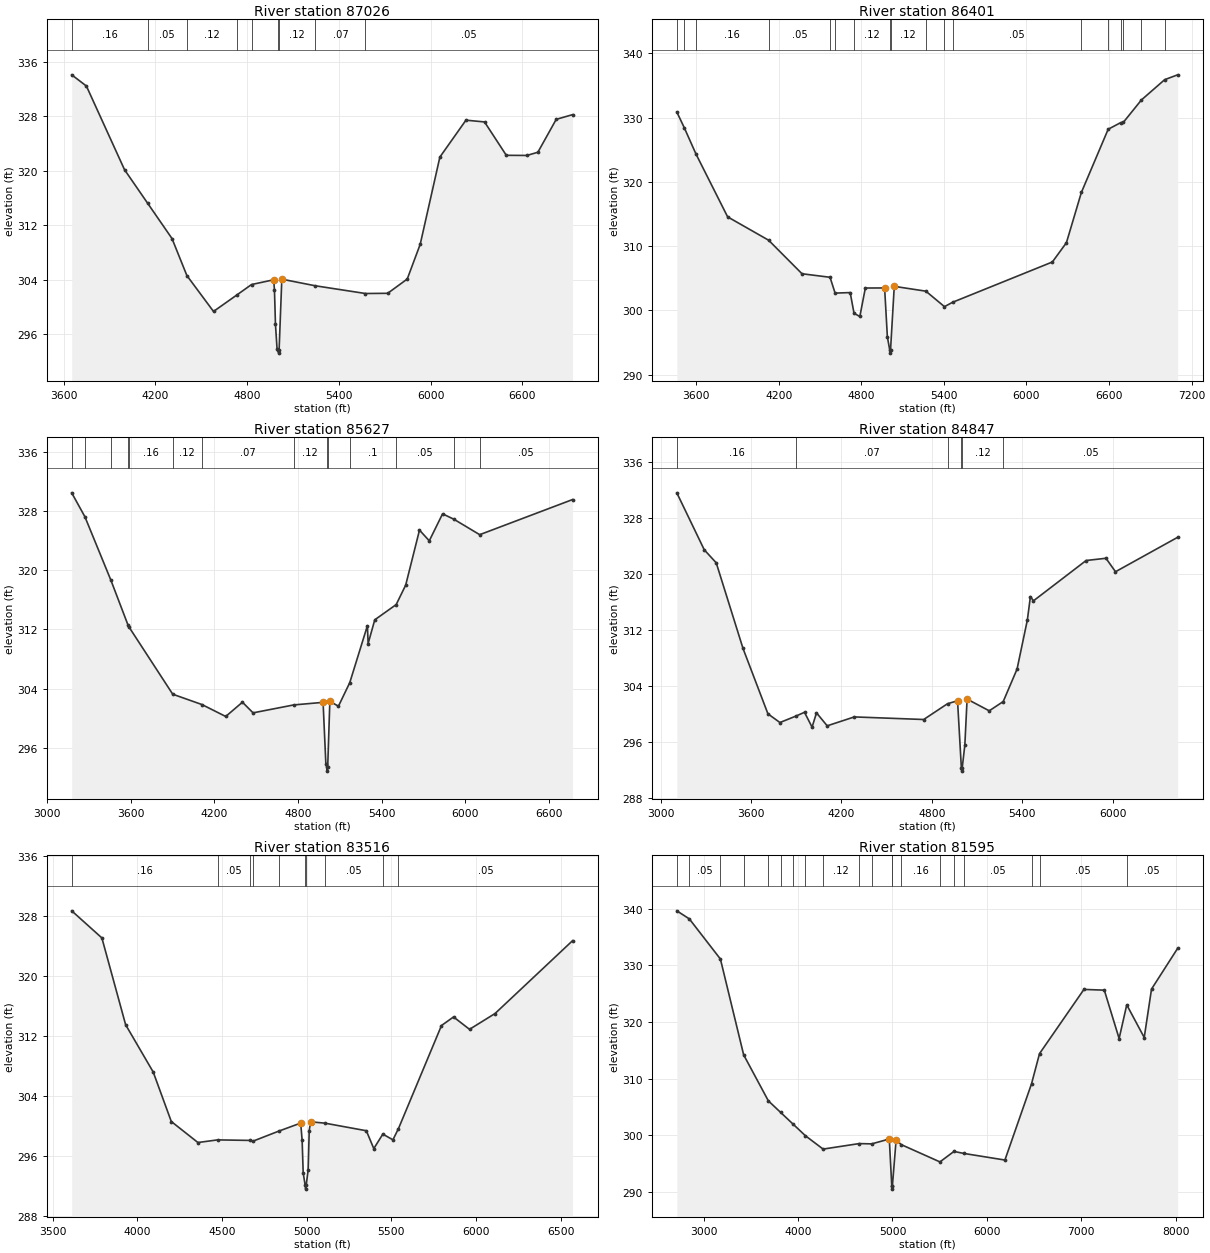
Type RM Length L Ch R = 1 ,87026   ,625,625,625
BEGIN DESCRIPTION:
CEDAR CREEK 64.0
END DESCRIPTION:
XS GIS Cut Line= 3
      3552655.67     10312094.17      3552218.18     10310538.65
      3550926.84     10309497.25
#Sta/Elev= 30
  3652.7  334.11  3748.8  332.46  3998.1  320.15  4149.2  315.22  4308.4  310.03
  4405.8  304.58  4579.9   299.3  4734.7  301.76  4828.4  303.26  4973.2  303.96
  4978.4  302.47    4985  297.39  4995.4  293.79  5002.8  293.67  5005.5  293.17
  5008.8  293.67  5026.5  304.05  5244.7  303.08  5573.5  301.94  5718.7  301.97
  5846.6  304.07  5931.5  309.19    6060  322.01  6230.5  327.44    6352  327.18
  6494.4  322.27  6628.7  322.25  6700.7  322.72  6820.7  327.56  6927.5  328.25
#Mann= 9 ,-1 , 0
  3652.7     .16       0  4149.2     .05       0  4405.8     .12       0
  4734.7     .07       0  4828.4     .12       0  5002.8     .07       0
  5008.8     .12       0  5244.7     .07       0  5573.5     .05       0
Bank Sta=4973.2,5026.5
XS Rating Curve= 0 ,0
Exp/Cntr=0.3,0.1

Type RM Length L Ch R = 1 ,86401   ,774,774,774
BEGIN DESCRIPTION:
CEDAR CREEK 63.0
END DESCRIPTION:
XS GIS Cut Line= 3
      3552773.73     10311920.64      3552732.07     10309934.48
      3551850.13     10308538.66
#Sta/Elev= 30
  3460.3  330.87  3513.8  328.45  3599.9  324.31  3829.4  314.55  4126.9  310.92
  4369.5   305.7  4573.2  305.15  4609.9  302.69  4719.6  302.77  4747.4  299.55
  4789.6  299.05  4829.6  303.48  4969.6  303.49  4989.6  295.88  5006.6  293.85
  5009.4  293.35  5012.6  293.85  5039.6  303.74  5269.1  302.99  5404.3  300.58
  5463.1  301.26  6187.9  307.53  6290.1  310.53  6398.7  318.35  6593.2  328.18
    6683   329.2    6704  329.27  6834.7  332.74  7003.8   335.9    7098  336.65
#Mann= 18 ,-1 , 0
  3460.3     .16       0  3513.8      .1       0  3599.9     .16       0
  4126.9     .05       0  4573.2     .12       0  4609.9     .07       0
  4747.4     .12       0  5006.6     .07       0  5012.6     .12       0
  5269.1     .05       0  5404.3     .12       0  5463.1     .05       0
  6398.7      .1       0  6593.2     .05       0    6683      .1       0
    6704     .05       0  6834.7      .1       0  7003.8     .16       0
Bank Sta=4969.6,5039.6
XS Rating Curve= 0 ,0
Exp/Cntr=0.3,0.1

Type RM Length L Ch R = 1 ,85627   ,780,780,780
BEGIN DESCRIPTION:
CEDAR CREEK 62.0
END DESCRIPTION:
XS GIS Cut Line= 3
       3552877.9      10311858.1      3553447.34     10310524.76
      3553287.65     10308386.27
#Sta/Elev= 30
  3176.2  330.47    3271  327.23  3457.3  318.66  3581.3  312.54  3585.5  312.38
  3901.2  303.24  4111.2  301.84  4281.5  300.23  4401.4  302.16  4477.7  300.72
  4769.2  301.79  4980.2  302.14  5000.2  293.79  5007.2  293.34    5010  292.84
  5013.2  293.34  5028.7  302.27  5090.5  301.62  5171.8  304.81  5298.4  312.51
  5303.4  310.09  5351.2   313.3  5504.8  315.36    5573  317.99  5672.1  325.43
  5742.3  323.98  5837.7  327.63  5919.8  326.89  6104.2  324.81  6770.5  329.56
#Mann= 14 ,-1 , 0
  3176.2     .16       0    3271      .1       0  3457.3     .16       0
  3581.3      .1       0  3585.5     .16       0  3901.2     .12       0
  4111.2     .07       0  4769.2     .12       0  5007.2     .07       0
  5013.2     .12       0  5171.8      .1       0  5504.8     .05       0
  5919.8      .1       0  6104.2     .05       0
Bank Sta=4980.2,5028.7
XS Rating Curve= 0 ,0
Exp/Cntr=0.3,0.1

Type RM Length L Ch R = 1 ,84847   ,1331,1331,1331
BEGIN DESCRIPTION:
CEDAR CREEK 61.0
END DESCRIPTION:
XS GIS Cut Line= 3
      3554982.05     10311906.69      3554183.45     10310809.48
      3553884.97     10308865.83
#Sta/Elev= 30
  3108.1  331.56  3290.1  323.44  3369.6  321.58  3547.4  309.37  3712.7  300.05
  3792.3  298.81  3899.8  299.74  3955.4  300.27  4005.6  298.15    4035  300.19
    4106  298.34  4286.1  299.61  4746.3  299.24  4904.3  301.49    4971  301.91
  4996.2  292.38  4998.9  291.88  5002.2  292.38  5019.4  295.61  5034.3  302.15
  5181.3  300.48    5274   301.8  5365.9  306.43  5434.3  313.44  5454.5  316.77
  5474.7  316.16  5824.2  321.91  5955.8  322.23  6019.1  320.31  6431.6  325.22
#Mann= 6 ,-1 , 0
  3108.1     .16       0  3899.8     .07       0  4904.3     .12       0
  4996.2     .07       0  5002.2     .12       0    5274     .05       0
Bank Sta=4971,5034.3
XS Rating Curve= 0 ,0
Exp/Cntr=0.3,0.1

Type RM Length L Ch R = 1 ,83516   ,1921,1921,1921
BEGIN DESCRIPTION:
CEDAR CREEK 60.0
END DESCRIPTION:
XS GIS Cut Line= 3
      3555718.16     10311531.67      3555232.07      10310545.6
      3554142.09     10309041.62
#Sta/Elev= 30
  3613.3  328.72  3791.4  325.11  3931.7  313.54  4094.5  307.24  4201.2  300.65
  4358.4  297.85  4474.4   298.2  4667.2  298.13  4681.2  298.01  4834.8  299.36
  4965.2  300.44  4973.7  298.13  4979.9  293.81  4991.6  292.14  4994.4  291.64
  4997.6  292.14  5009.3  294.24  5015.5  299.45    5024  300.61    5108  300.43
  5352.6  299.42  5396.7  297.04    5450  298.97  5509.6  298.21  5542.5  299.71
  5796.4  313.44  5867.6  314.58  5961.9  312.93  6112.7  315.04  6570.1  324.74
#Mann= 10 ,-1 , 0
  3613.3     .16       0  4474.4     .05       0  4667.2     .16       0
  4681.2     .07       0  4834.8     .12       0  4991.6     .07       0
  4997.6     .12       0    5108     .05       0    5450     .16       0
  5542.5     .05       0
Bank Sta=4965.2,5024
XS Rating Curve= 0 ,0
Exp/Cntr=0.3,0.1

Type RM Length L Ch R = 1 ,81595   ,687,687,687
BEGIN DESCRIPTION:
CEDAR CREEK 59.0
END DESCRIPTION:
XS GIS Cut Line= 3
      3557391.79     10311496.99      3556148.73     10309969.21
      3553447.38      10308010.9
#Sta/Elev= 30
  2715.4  339.59  2847.9  338.17  3177.2  331.09  3423.5  314.19  3685.1  306.08
  3815.9  304.03  3946.7  301.98  4077.5  299.93  4265.3  297.57  4646.9  298.54
  4779.8  298.49  4966.5  299.35  4992.9  291.01  4995.7  290.51  4998.9  291.01
    5039  299.25  5091.8  298.37  5503.1  295.31  5651.5  297.16  5754.2  296.81
  6191.3  295.64  6473.2  309.08  6558.1  314.41  7028.6  325.73  7244.4   325.6
  7401.3  317.07  7482.2  323.01  7667.3  317.25  7744.6  325.79  8021.5  332.98
#Mann= 20 ,-1 , 0
  2715.4      .1       0  2847.9     .05       0  3177.2     .16       0
  3423.5      .1       0  3685.1     .05       0  3815.9     .05       0
  3946.7     .05       0  4077.5     .05       0  4265.3     .12       0
  4646.9     .16       0  4779.8     .12       0  4992.9     .07       0
  4998.9     .12       0  5091.8     .16       0  5503.1     .05       0
  5651.5      .1       0  5754.2     .05       0  6473.2      .1       0
  6558.1     .05       0  7482.2     .05       0
Bank Sta=4966.5,5039
XS Rating Curve= 0 ,0
Exp/Cntr=0.3,0.1

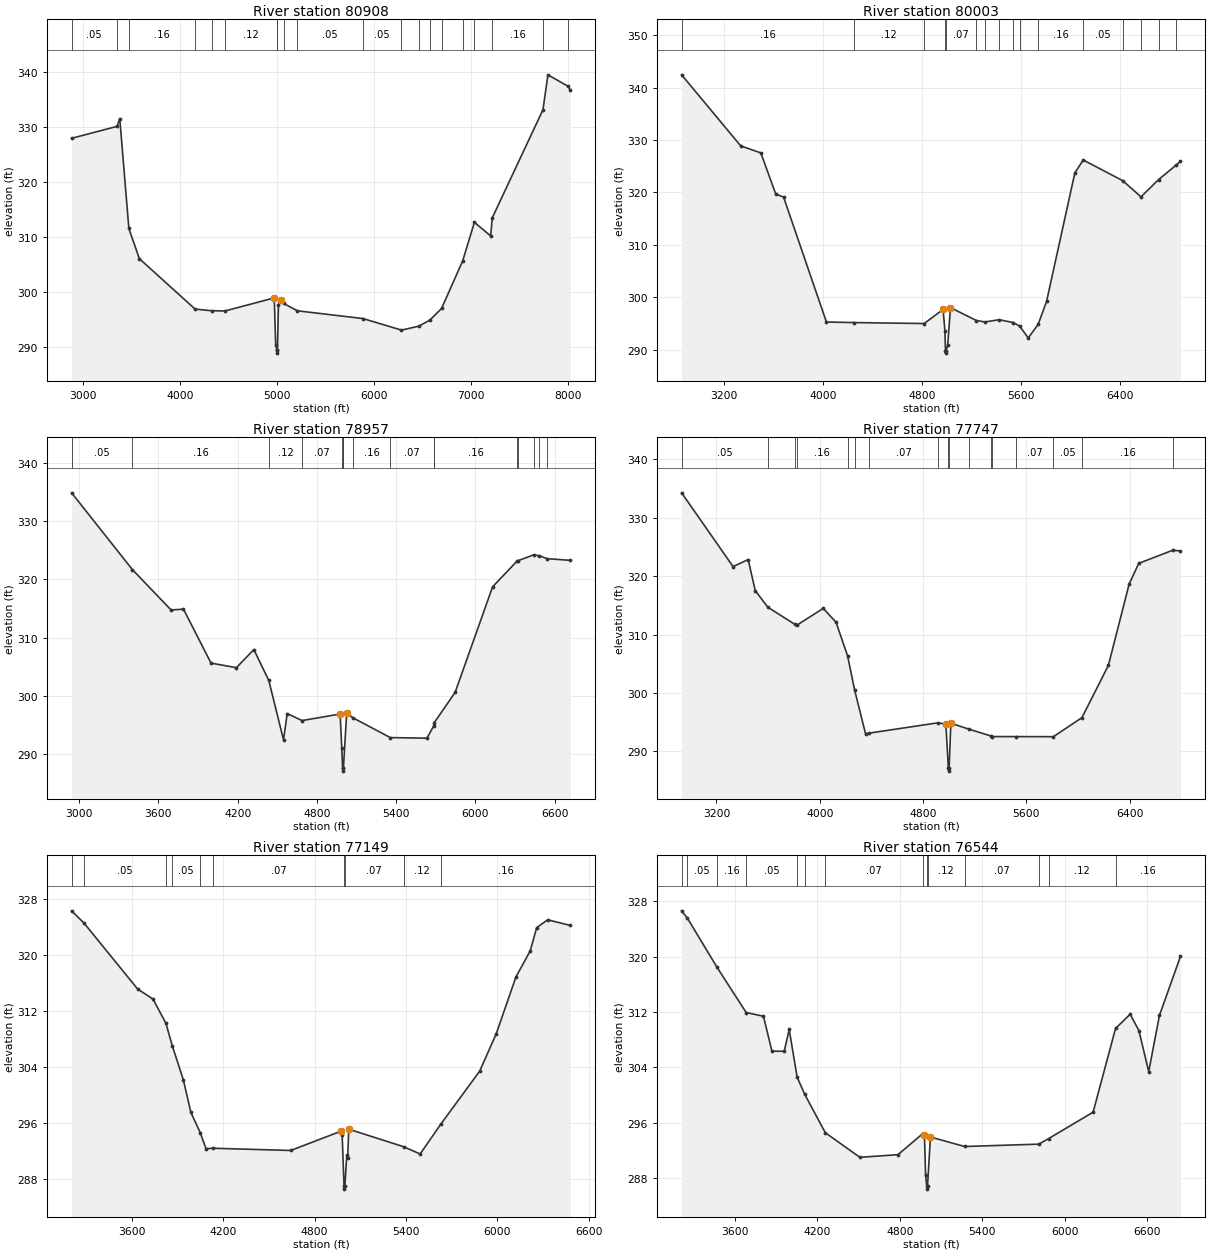
Type RM Length L Ch R = 1 ,80908   ,905,905,905
BEGIN DESCRIPTION:
CEDAR CREEK 58.0
END DESCRIPTION:
XS GIS Cut Line= 3
      3557560.17     10311151.47       3556149.6     10309079.02
      3554880.05     10306778.63
#Sta/Elev= 30
  2886.1  327.88  3353.3  330.05  3381.8  331.48  3475.4  311.48  3583.1  305.99
  4157.2  296.81    4330  296.51  4464.5  296.47  4971.7  298.85  4986.7  290.34
  4998.6   289.3  5001.4   288.8  5004.6   289.3  5014.9  297.58  5037.5  298.51
  5067.8  297.84  5210.2   296.5  5885.2  295.09  6281.2  292.99  6458.5   293.7
  6573.2   294.8  6694.4  296.94  6911.7  305.61  7031.9   312.6  7199.6  310.11
  7215.1  313.39  7737.4  333.07  7788.6  339.43  7995.3  337.35  8020.5  336.64
#Mann= 20 ,-1 , 0
  2886.1     .05       0  3353.3      .1       0  3475.4     .16       0
  4157.2     .05       0    4330     .07       0  4464.5     .12       0
  4998.6     .07       0  5004.6     .12       0  5067.8     .07       0
  5210.2     .05       0  5885.2     .05       0  6281.2     .16       0
  6458.5     .16       0  6573.2     .05       0  6694.4     .16       0
  6911.7     .05       0  7031.9     .05       0  7215.1     .16       0
  7737.4     .05       0  7995.3     .16       0
Bank Sta=4971.7,5037.5
XS Rating Curve= 0 ,0
Exp/Cntr=0.3,0.1

Type RM Length L Ch R = 1 ,80003   ,1046,1046,1046
BEGIN DESCRIPTION:
CEDAR CREEK 56.0
END DESCRIPTION:
XS GIS Cut Line= 3
      3558130.36     10310329.47      3557230.39     10309429.49
      3555943.94     10306985.78
#Sta/Elev= 30
    2856  342.46  3334.1  328.89  3496.7  327.56  3616.9  319.71  3680.5  319.12
    4027  295.28  4253.8  295.17  4817.7  294.99  4970.6  297.67  4985.2  293.64
  4989.7  289.84  4992.4  289.34  4995.7  289.84  5007.8  290.87  5030.4  298.03
    5240  295.56  5310.5  295.29  5423.8  295.72  5537.2  295.18  5588.9  294.52
  5658.8  292.25  5739.2  294.81  5807.4   299.2  6036.2  323.74  6103.9   326.2
  6423.4  322.26  6570.8  319.17  6713.6  322.47  6855.9  325.24  6890.4  325.96
#Mann= 16 ,-1 , 0
    2856     .16       0  4253.8     .12       0  4817.7     .07       0
  4989.7     .07       0  4995.7     .07       0    5240     .16       0
  5310.5     .07       0  5423.8     .16       0  5537.2     .05       0
  5588.9     .12       0  5739.2     .16       0  6103.9     .05       0
  6423.4     .16       0  6570.8     .05       0  6713.6     .16       0
  6855.9     .05       0
Bank Sta=4970.6,5030.4
XS Rating Curve= 0 ,0
Exp/Cntr=0.3,0.1

Type RM Length L Ch R = 1 ,78957   ,1210,1210,1210
BEGIN DESCRIPTION:
CEDAR CREEK 55.0
END DESCRIPTION:
XS GIS Cut Line= 3
      3558352.27     10309838.53      3557245.52     10307755.23
      3556160.46     10306843.78
#Sta/Elev= 30
  2942.9  334.86  3403.4  321.66  3696.2  314.73  3789.7  314.88  3998.2  305.61
  4190.4  304.82  4322.3  307.94  4435.5  302.63  4547.1  292.42  4574.7  296.93
  4687.6  295.74  4975.4  296.86  4987.9  290.99  4994.4  287.55  4997.1  287.05
  5000.4  287.55    5025  297.02  5075.9  296.17  5355.4  292.81  5632.9  292.71
  5683.3   294.8    5688  295.38  5846.1  300.58  6129.7  318.72  6315.5  323.15
  6322.9  323.21  6440.3   324.2  6483.2  324.06    6542  323.55    6719  323.26
#Mann= 16 ,-1 , 0
  2942.9     .05       0  3403.4     .16       0  4435.5     .12       0
  4687.6     .07       0  4987.9     .12       0  4994.4     .07       0
  5000.4     .12       0  5075.9     .16       0  5355.4     .07       0
  5683.3     .05       0    5688     .16       0  6315.5      .1       0
  6322.9     .16       0  6440.3     .05       0  6483.2      .1       0
    6542     .16       0
Bank Sta=4975.4,5025
XS Rating Curve= 0 ,0
Exp/Cntr=0.3,0.1

Type RM Length L Ch R = 1 ,77747   ,598,598,598
BEGIN DESCRIPTION:
CEDAR CREEK 54.0
END DESCRIPTION:
XS GIS Cut Line= 3
      3559176.94     10309361.13       3558417.4     10307852.89
      3556442.15     10306941.66
#Sta/Elev= 30
  2930.4  334.27  3328.8  321.64  3445.9  322.84  3500.8  317.51  3599.2  314.66
    3809  311.73  3824.3  311.62  4027.1  314.48  4126.4  312.11  4216.3  306.32
  4270.9  300.45  4355.2  292.99  4383.1  293.12  4918.2  294.89  4977.3  294.63
  4996.4  287.11  4999.1  286.61  5002.4  287.11  5015.9  294.81  5155.6   293.8
  5324.6  292.64  5336.2  292.53  5523.2  292.52  5810.2  292.51  6031.2  295.77
  6235.9  304.71  6396.5  318.61  6470.9  322.19  6738.3  324.47  6794.4  324.28
#Mann= 17 ,-1 , 0
  2930.4     .05       0  3599.2     .16       0    3809     .12       0
  3824.3     .16       0  4216.3      .1       0  4270.9     .16       0
  4383.1     .07       0  4918.2     .12       0  4996.4     .07       0
  5002.4     .12       0  5155.6     .05       0  5324.6     .07       0
  5336.2     .05       0  5523.2     .07       0  5810.2     .05       0
  6031.2     .16       0  6738.3      .1       0
Bank Sta=4977.3,5015.9
XS Rating Curve= 0 ,0
Exp/Cntr=0.3,0.1

Type RM Length L Ch R = 1 ,77149   ,605,605,605
BEGIN DESCRIPTION:
CEDAR CREEK 53.0
END DESCRIPTION:
XS GIS Cut Line= 3
       3559292.1     10308441.64      3558373.99      10307277.8
      3556876.87     10306290.57
#Sta/Elev= 30
  3204.3   326.3  3287.3  324.51  3637.9  315.13    3739  313.69  3823.4  310.24
  3866.2  306.96  3937.8  302.18  3987.5   297.5  4048.7  294.63  4086.9  292.32
  4132.7  292.39  4643.3  292.07  4974.9  294.84  4980.9  294.34    4993  287.05
  4995.7  286.55    4999  287.05  5011.1  291.45    5017  291.03  5024.3  295.11
  5384.3  292.61  5492.8  291.57  5628.3  295.82  5884.2  303.41  5992.6  308.74
  6122.1  316.86  6215.4  320.56  6258.1  323.89    6330  325.02    6480  324.21
#Mann= 10 ,-1 , 0
  3204.3     .16       0  3287.3     .05       0  3823.4      .1       0
  3866.2     .05       0  4048.7      .1       0  4132.7     .07       0
    4993     .07       0    4999     .07       0  5384.3     .12       0
  5628.3     .16       0
Bank Sta=4974.9,5024.3
XS Rating Curve= 0 ,0
Exp/Cntr=0.3,0.1

Type RM Length L Ch R = 1 ,76544   ,826,826,826
BEGIN DESCRIPTION:
CEDAR CREEK 52.0
END DESCRIPTION:
XS GIS Cut Line= 3
      3559392.11     10308391.65      3558592.11     10306791.64
      3557386.82     10305400.91
#Sta/Elev= 30
  3212.5   326.6  3255.2  325.52    3469  318.49  3681.9  311.93  3807.9  311.39
  3869.4  306.36  3958.8  306.33  3995.1  309.48  4052.9   302.6  4107.6  300.15
  4257.6  294.59  4509.4  291.04  4786.1  291.42  4967.1  294.46    4979  294.29
  4987.4  288.44  4995.6  286.95  4998.3  286.45  5001.6  286.95  5022.7  293.97
  5271.1   292.6  5811.5  292.94  5881.6  293.73  6206.1  297.55  6369.4  309.63
  6475.8  311.69  6539.4  309.32  6610.7   303.4  6688.6   311.5  6841.7  320.03
#Mann= 14 ,-1 , 0
  3212.5     .16       0  3255.2     .05       0    3469     .16       0
  3681.9     .05       0  4052.9      .1       0  4107.6     .05       0
  4257.6     .07       0  4967.1     .12       0  4995.6     .07       0
  5001.6     .12       0  5271.1     .07       0  5811.5     .16       0
  5881.6     .12       0  6369.4     .16       0
Bank Sta=4979,5022.7
XS Rating Curve= 0 ,0
Exp/Cntr=0.3,0.1

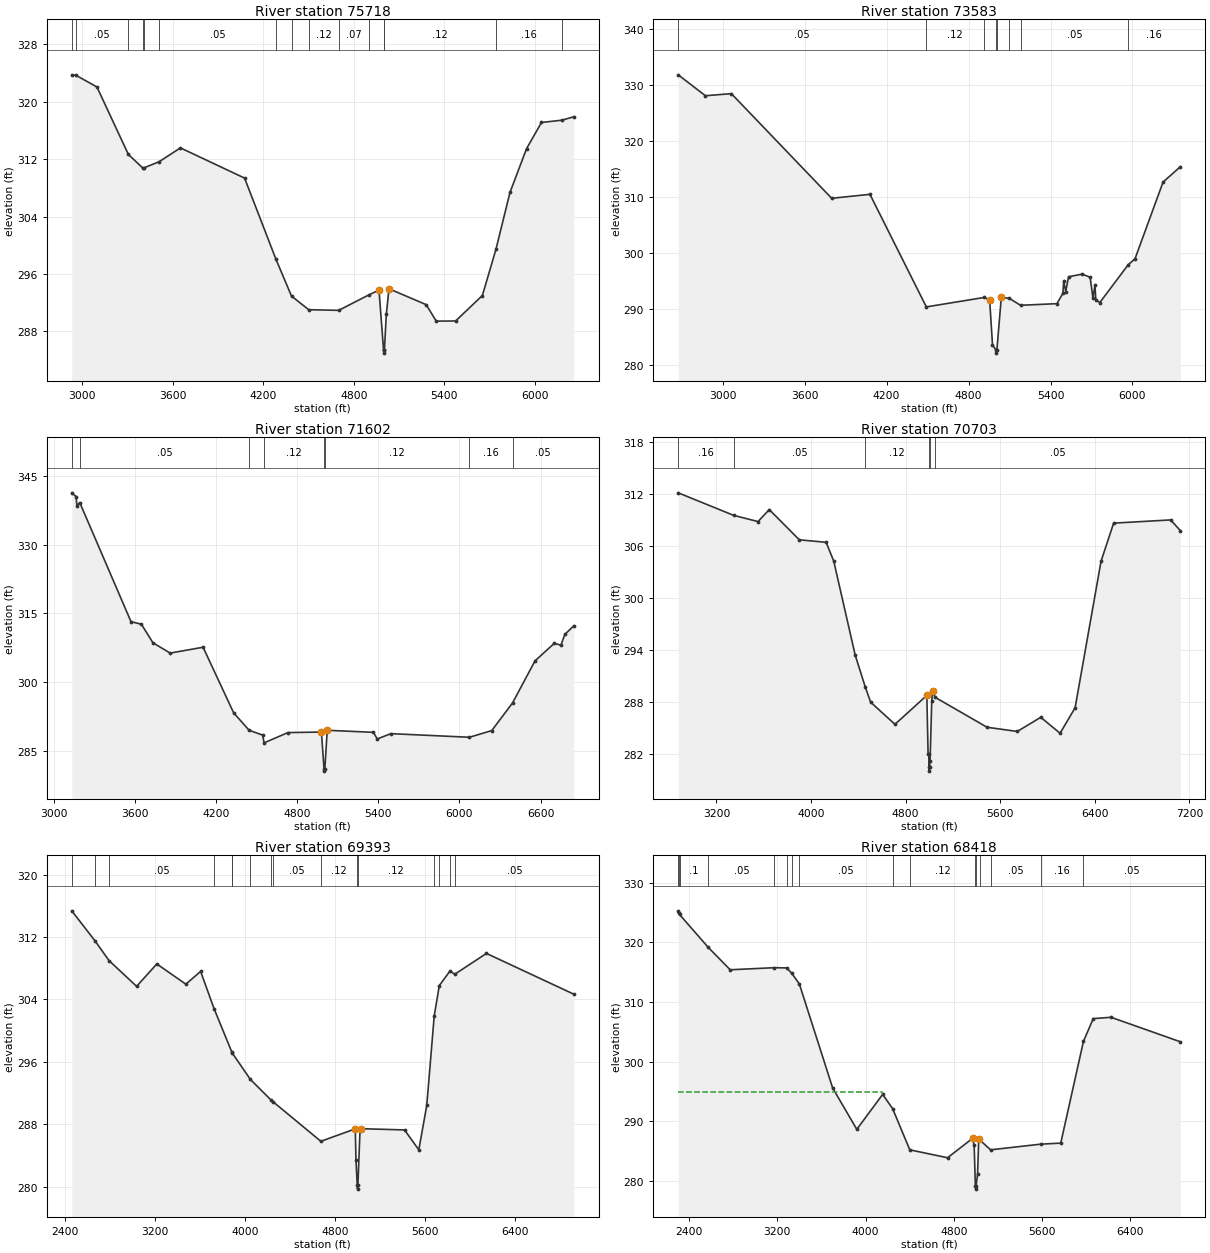
Type RM Length L Ch R = 1 ,75718   ,2135,2135,2135
BEGIN DESCRIPTION:
CEDAR CREEK 51.0
END DESCRIPTION:
XS GIS Cut Line= 3
      3559882.23     10308156.68      3559198.65     10306431.45
      3558775.48     10305020.89
#Sta/Elev= 30
  2930.1  323.76  2959.6  323.67  3096.9  322.07  3305.2  312.67  3401.5  310.76
  3411.5  310.82  3509.8  311.66  3650.3  313.58  4075.7  309.37  4283.7  298.06
  4386.8  292.93  4500.7  291.03  4699.5  290.94  4899.4  293.09  4966.8  293.76
  4996.8  285.48  4999.6  284.98  5002.8  285.48  5015.3  290.37  5032.9  293.95
    5280  291.73  5346.1  289.44  5474.7  289.46  5652.2  293.01  5742.3  299.46
  5835.1  307.37  5944.7  313.46  6043.9  317.12    6180  317.44  6258.5  317.92
#Mann= 15 ,-1 , 0
  2930.1      .1       0  2959.6     .05       0  3305.2      .1       0
  3401.5     .05       0  3411.5      .1       0  3509.8     .05       0
  4283.7     .16       0  4386.8     .07       0  4500.7     .12       0
  4699.5     .07       0  4899.4     .12       0  4996.8     .07       0
  5002.8     .12       0  5742.3     .16       0    6180     .05       0
Bank Sta=4966.8,5032.9
XS Rating Curve= 0 ,0
Exp/Cntr=0.3,0.1

Type RM Length L Ch R = 1 ,73583   ,1981,1981,1981
BEGIN DESCRIPTION:
CEDAR CREEK 50.0
END DESCRIPTION:
XS GIS Cut Line= 3
      3561564.09     10307570.76      3560533.28       10305737.
      3559578.41     10304489.15
#Sta/Elev= 30
  2675.2  331.88    2874  328.14  3064.2  328.51  3798.4  309.79  4078.3   310.5
  4491.1  290.36  4914.7  292.05  4954.5  291.63  4975.4  283.59  5001.4  282.59
  5004.2  282.09  5007.4  282.59  5039.8  292.05    5098  291.89  5180.5  290.65
  5446.9  290.94  5490.5  292.79  5496.8  295.04  5511.3   293.1  5532.1  295.75
  5631.9  296.23    5690  295.66  5710.8  291.92  5725.3  294.27  5731.6  291.66
  5760.6  291.13  5969.6  297.93  6018.2  298.95    6224   312.7  6350.1  315.43
#Mann= 8 ,-1 , 0
  2675.2     .05       0  4491.1     .12       0  4914.7     .05       0
  5001.4     .04       0  5007.4     .05       0    5098     .16       0
  5180.5     .05       0  5969.6     .16       0
Bank Sta=4954.5,5039.8
XS Rating Curve= 0 ,0
Exp/Cntr=0.3,0.1

Type RM Length L Ch R = 1 ,71602   ,899,899,899
BEGIN DESCRIPTION:
CEDAR CREEK 48.0
END DESCRIPTION:
XS GIS Cut Line= 3
      3562192.11     10306591.66      3561555.21     10305158.63
      3559893.72     10303806.09
#Sta/Elev= 30
  3134.7  341.34  3166.9  340.51  3172.3  338.56  3193.7  339.21  3572.4  313.19
    3649  312.63  3734.5  308.58  3861.8  306.32  4105.2   307.6  4330.9  293.28
  4444.8  289.47  4545.7   288.4  4555.9   286.7    4732  288.95  4979.7  289.07
    4999  281.03  5001.8  280.53    5005  281.03  5022.8  289.45  5364.5  289.01
    5392  287.55  5492.5  288.72  6073.7  287.93  6238.7  289.39  6392.4  295.44
  6558.3  304.62  6700.5  308.45    6750  308.05  6778.8  310.41  6845.3  312.28
#Mann= 8 ,-1 , 0
  3134.7      .1       0  3193.7     .05       0  4444.8     .16       0
  4555.9     .12       0    4999     .07       0    5005     .12       0
  6073.7     .16       0  6392.4     .05       0
Bank Sta=4979.7,5022.8
XS Rating Curve= 0 ,0
Exp/Cntr=0.3,0.1

Type RM Length L Ch R = 1 ,70703   ,1310,1310,1310
BEGIN DESCRIPTION:
CEDAR CREEK 47.0
END DESCRIPTION:
XS GIS Cut Line= 3
      3562887.88     10306051.67      3561792.11     10304241.64
      3560393.48     10302635.14
#Sta/Elev= 30
  2876.9  312.12  3346.6  309.52  3551.7  308.81  3646.7  310.19  3900.8  306.71
  4127.7  306.42  4191.7  304.27  4373.2  293.44  4457.4  289.81    4504  288.01
  4709.6  285.46  4979.2  288.79  4989.9  282.01  4996.1  282.01  4996.9  280.57
  4999.6  280.07  5002.9  280.57  5006.5  281.23  5020.8  288.14  5028.4  289.26
  5049.3  288.57  5488.9  285.12  5744.3  284.64  5942.7  286.27    6106  284.43
  6233.2  287.37  6452.5  304.24  6558.9  308.63  7041.2     309  7122.8  307.77
#Mann= 6 ,-1 , 0
  2876.9     .16       0  3346.6     .05       0  4457.4     .12       0
  4996.9     .07       0  5002.9     .12       0  5049.3     .05       0
Bank Sta=4979.2,5028.4
XS Rating Curve= 0 ,0
Exp/Cntr=0.3,0.1

Type RM Length L Ch R = 1 ,69393   ,975,975,975
BEGIN DESCRIPTION:
CEDAR CREEK 46.0
END DESCRIPTION:
XS GIS Cut Line= 3
      3563792.11     10305591.65      3562367.69     10303484.53
      3561043.26     10302091.16
#Sta/Elev= 30
  2456.6  315.35  2665.5  311.46  2787.3  308.98  3033.4  305.67  3213.2  308.54
    3471  305.95  3602.8  307.58  3722.1  302.81  3878.9  297.29  3883.4  297.13
  4045.6  293.73    4225  291.15  4248.8  290.85  4672.5   285.8  4978.3   287.4
  4984.3  283.46  4995.7  280.17  4998.5  279.67  5001.7  280.17    5020  287.06
  5027.3  287.42  5416.4  287.26  5543.4  284.71  5614.2   290.4  5680.3  301.85
  5725.7  305.77  5821.1  307.64  5863.4  307.22  6144.9  309.89  6922.4  304.66
#Mann= 16 ,-1 , 0
  2456.6     .05       0  2665.5      .1       0  2787.3     .05       0
  3722.1      .1       0  3878.9     .05       0  3883.4     .16       0
  4045.6     .05       0    4225     .16       0  4248.8     .05       0
  4672.5     .12       0  4995.7     .07       0  5001.7     .12       0
  5680.3     .16       0  5725.7     .05       0  5821.1     .16       0
  5863.4     .05       0
Bank Sta=4978.3,5027.3
XS Rating Curve= 0 ,0
Exp/Cntr=0.3,0.1

Type RM Length L Ch R = 1 ,68418   ,1240,1240,1240
BEGIN DESCRIPTION:
CEDAR CREEK 44.0
END DESCRIPTION:
XS GIS Cut Line= 3
      3564927.85     10304630.26      3562892.11     10302841.64
      3561282.02     10301950.13
#Sta/Elev= 30
  2301.7  325.31  2308.7  324.89  2313.3   324.7  2574.2  319.16  2772.7  315.41
  3173.1  315.76  3284.3  315.72  3328.6  314.87  3399.3  313.03  3700.7  295.58
    3920  288.61  4154.3  294.48  4244.5  292.09  4400.3  285.17  4742.6  283.84
  4969.3   287.1  4983.6  285.93  4994.8  279.07  4997.6  278.57  5000.8  279.07
  5014.4  281.07  5025.3  287.05    5033  286.86  5132.3  285.17  5586.3  286.12
  5768.4   286.3  5974.3   303.4  6063.2  307.21  6224.1  307.43    6852  303.32
#Mann= 16 ,-1 , 0
  2301.7      .1       0  2308.7     .05       0  2313.3      .1       0
  2574.2     .05       0  3173.1     .16       0  3284.3     .05       0
  3328.6     .16       0  3399.3     .05       0  4244.5     .16       0
  4400.3     .12       0  4994.8     .07       0  5000.8     .12       0
    5033     .16       0  5132.3     .05       0  5586.3     .16       0
  5974.3     .05       0
#XS Ineff= 2 , 0
         4147.53  294.91
Permanent Ineff=
       F       F
Bank Sta=4969.3,5025.3
XS Rating Curve= 0 ,0
Exp/Cntr=0.3,0.1