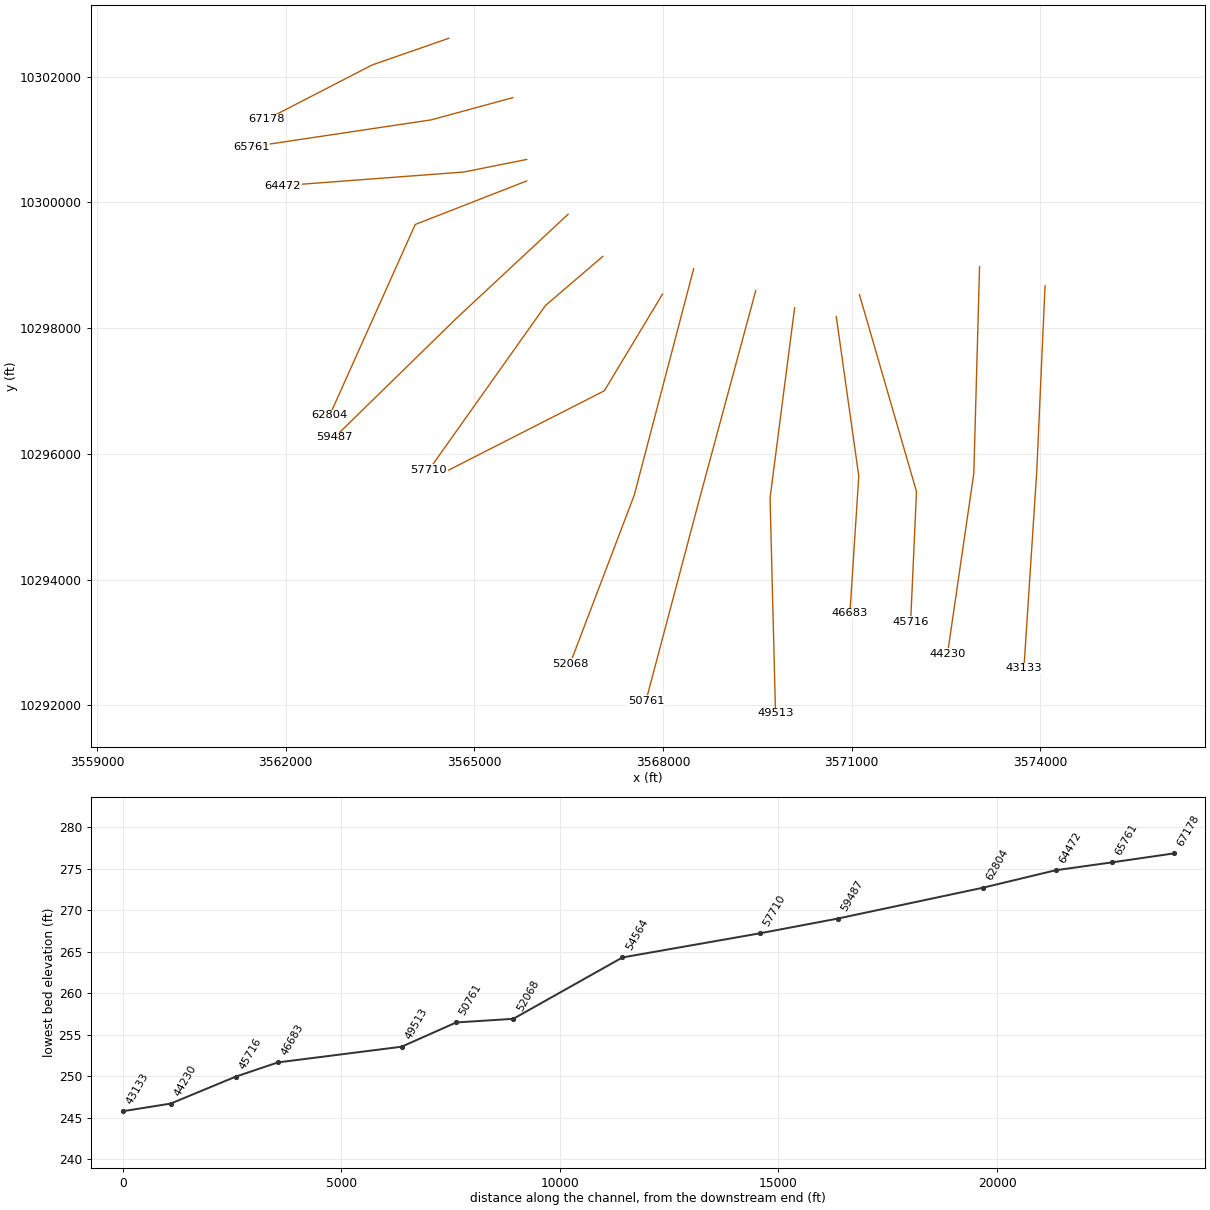
HEC-RAS study CEDAR CREEK.prj: CEDAR CREEK Base Level Engineering

--- CEDAR CREEK.g01 (geometry) --- (continued)

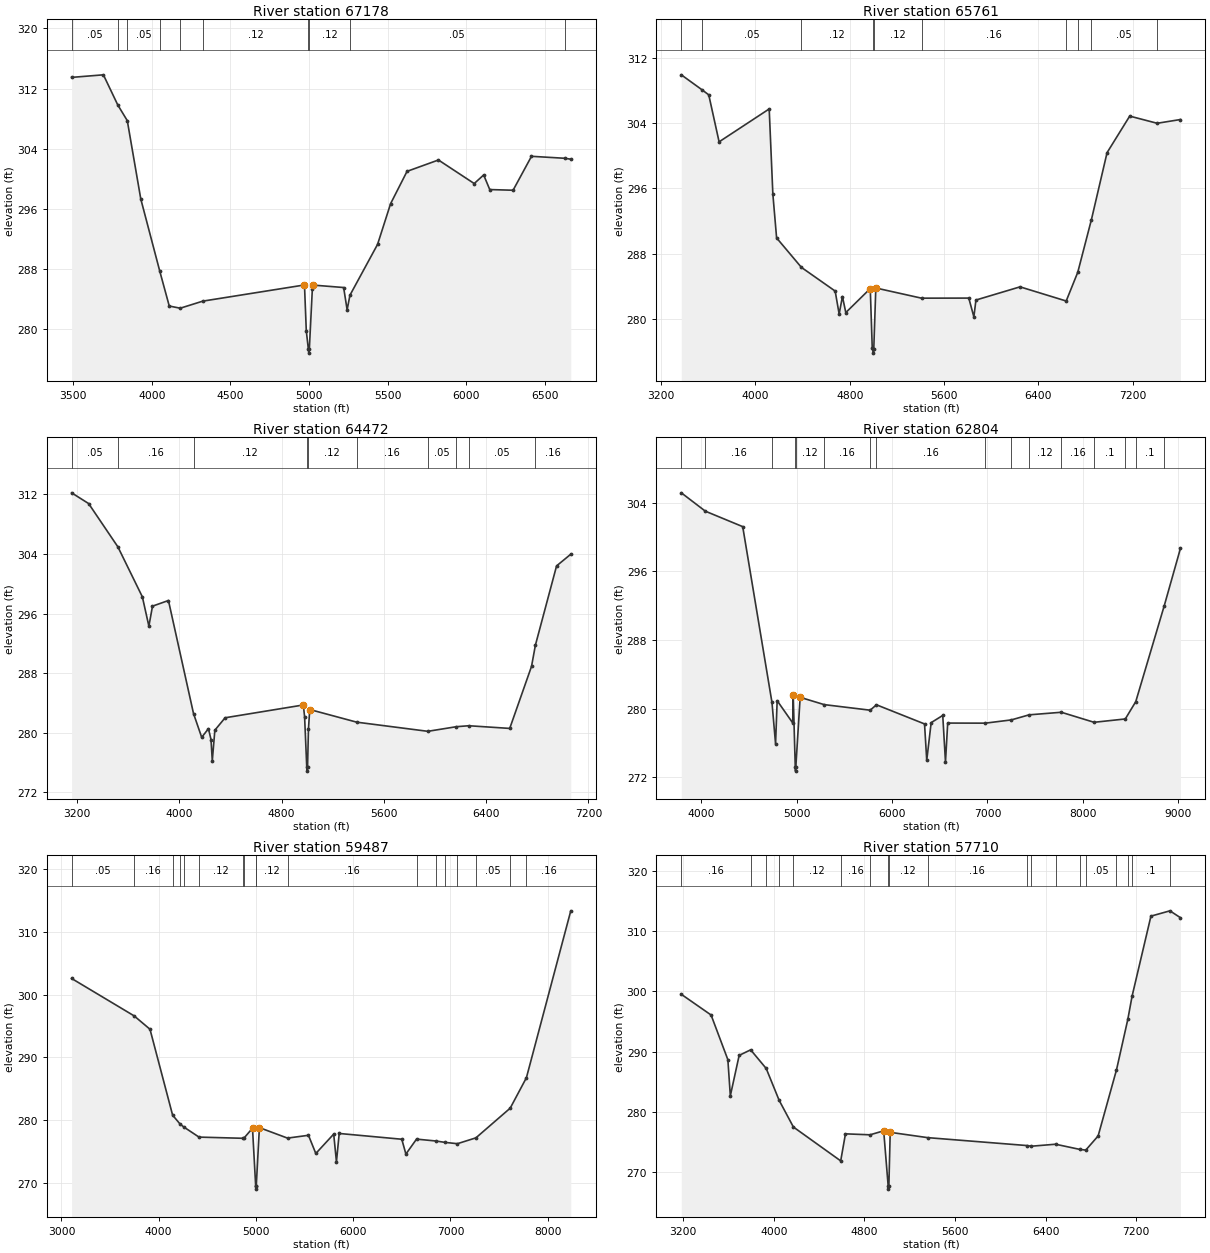
Type RM Length L Ch R = 1 ,67178   ,1417,1417,1417
BEGIN DESCRIPTION:
CEDAR CREEK 43.0
END DESCRIPTION:
XS GIS Cut Line= 3
      3564591.44       10302612.      3563376.16     10302188.82
      3561695.74     10301321.51
#Sta/Elev= 30
  3488.6   313.5  3690.9  313.84  3782.8  309.82    3843  307.75    3929  297.33
  4049.7  287.75  4110.2  283.11  4180.1  282.82  4323.6  283.76  4971.1  285.91
  4982.6  279.83  4995.9  277.35  4998.6  276.85  5001.9  277.35    5021  285.31
  5027.6  285.89  5220.4  285.57  5242.6  282.61  5260.6  284.55  5436.3   291.3
  5519.3  296.71    5624  301.01  5823.9  302.52  6051.7  299.39  6111.9  300.53
  6150.6  298.59  6299.2   298.5  6416.4  303.01  6626.6  302.75  6666.5  302.63
#Mann= 10 ,-1 , 0
  3488.6     .05       0  3782.8     .16       0    3843     .05       0
  4049.7     .12       0  4180.1     .07       0  4323.6     .12       0
  4995.9     .07       0  5001.9     .12       0  5260.6     .05       0
  6626.6     .16       0
Bank Sta=4971.1,5027.6
XS Rating Curve= 0 ,0
Exp/Cntr=0.3,0.1

Type RM Length L Ch R = 1 ,65761   ,1289,1289,1289
BEGIN DESCRIPTION:
CEDAR CREEK 42.0
END DESCRIPTION:
XS GIS Cut Line= 3
      3565611.43       10301668.      3564315.28     10301314.81
      3561456.34     10300886.85
#Sta/Elev= 30
  3370.9  309.95  3543.9  308.14  3603.8  307.49  3691.5  301.72  4116.5  305.76
  4147.5  295.31  4179.3  289.92  4389.8   286.3  4676.1  283.39  4709.9  280.57
  4737.7  282.72  4766.3  280.75  4973.8   283.7  4990.5  276.46  4997.6  276.27
  5000.4  275.77  5003.6  276.27  5020.9  283.77  5408.5  282.52  5809.6  282.53
  5852.7  280.22  5870.2  282.29  6244.3  283.91  6635.9  282.17    6734   285.7
  6850.1  292.18  6982.5  300.39  7174.6  304.88  7407.3     304  7605.1  304.46
#Mann= 10 ,-1 , 0
  3370.9     .16       0  3543.9     .05       0  4389.8     .12       0
  4997.6     .07       0  5003.6     .12       0  5408.5     .16       0
  6635.9     .05       0    6734     .16       0  6850.1     .05       0
  7407.3     .16       0
Bank Sta=4973.8,5020.9
XS Rating Curve= 0 ,0
Exp/Cntr=0.3,0.1

Type RM Length L Ch R = 1 ,64472   ,1668,1668,1668
BEGIN DESCRIPTION:
CEDAR CREEK 41.0
END DESCRIPTION:
XS GIS Cut Line= 3
      3565832.33     10300684.62       3564832.3     10300484.61
      3561955.95     10300268.34
#Sta/Elev= 30
  3157.4  312.22  3290.2  310.78  3519.2  304.96  3710.7  298.24  3761.7   294.3
  3789.9  296.99  3914.7  297.75  4110.8  282.56  4174.8  279.36  4227.6  280.53
  4247.6  279.07  4257.7  276.22  4277.7  280.32  4357.9  281.99  4969.7  283.71
  4979.7  282.12  4996.7  275.32  4999.5  274.82  5002.7  275.32  5009.8  280.45
  5019.8   283.1  5387.4   281.4  5943.5  280.17  6166.8  280.79  6263.9  280.92
  6584.2  280.56  6754.7   288.9    6785  291.75  6950.6   302.4  7061.7  303.97
#Mann= 10 ,-1 , 0
  3157.4     .05       0  3519.2     .16       0  4110.8     .12       0
  4996.7     .07       0  5002.7     .12       0  5387.4     .16       0
  5943.5     .05       0  6166.8     .16       0  6263.9     .05       0
    6785     .16       0
Bank Sta=4969.7,5019.8
XS Rating Curve= 0 ,0
Exp/Cntr=0.3,0.1

Type RM Length L Ch R = 1 ,62804   ,3317,3317,3317
BEGIN DESCRIPTION:
CEDAR CREEK 40.0
END DESCRIPTION:
XS GIS Cut Line= 3
      3565832.44     10300342.56      3564059.76     10299649.76
      3562698.98     10296611.86
#Sta/Elev= 30
  3791.4  305.14  4043.6     303  4435.1   301.2  4741.9  280.71  4779.5  275.88
  4796.1  280.92  4959.1  278.33  4964.4  281.57  4985.9  273.21  4988.7  272.71
  4991.9  273.21  5037.2  281.31  5289.3  280.46  5771.2  279.81  5836.9  280.44
  6340.9  278.21    6364  273.97  6410.4  278.36  6531.8   279.2  6560.5  273.77
  6583.7  278.31  6977.5   278.3  7251.1  278.68  7437.4  279.27  7774.6  279.57
  8117.9   278.4  8445.4  278.79    8555  280.81  8853.7  291.99  9023.4  298.67
#Mann= 16 ,-1 , 0
  3791.4     .05       0  4043.6     .16       0  4741.9     .12       0
  4985.9     .07       0  4991.9     .12       0  5289.3     .16       0
  5771.2     .05       0  5836.9     .16       0  6977.5     .05       0
  7251.1     .16       0  7437.4     .12       0  7774.6     .16       0
  8117.9      .1       0  8445.4     .05       0    8555      .1       0
  8853.7     .05       0
Bank Sta=4964.4,5037.2
XS Rating Curve= 0 ,0
Exp/Cntr=0.3,0.1

Type RM Length L Ch R = 1 ,59487   ,1777,1777,1777
BEGIN DESCRIPTION:
CEDAR CREEK 38.0
END DESCRIPTION:
XS GIS Cut Line= 3
      3566490.34     10299812.55      3564709.28     10298151.36
      3562780.56      10296265.5
#Sta/Elev= 30
  3104.8  302.57  3747.5  296.61  3910.6  294.48  4143.3  280.79  4218.3   279.4
  4258.4   278.9  4414.9  277.29  4870.8   277.1  4877.6  277.14  4964.9  278.71
  4997.5   269.5  5000.3     269  5003.5   269.5  5035.7   278.8  5324.9  277.13
  5540.3  277.58  5615.9  274.68  5799.8  277.77  5828.1  273.36  5856.4  277.87
  6499.9  276.95  6542.3  274.59  6651.7  276.97  6850.5  276.67  6944.5  276.45
  7071.8  276.24  7262.2  277.17  7614.7   281.9  7781.5  286.75  8237.8  313.35
#Mann= 18 ,-1 , 0
  3104.8     .05       0  3747.5     .16       0  4143.3     .05       0
  4218.3     .12       0  4258.4     .07       0  4414.9     .12       0
  4870.8     .07       0  4877.6     .12       0  4997.5     .07       0
  5003.5     .12       0  5324.9     .16       0  6651.7     .05       0
  6850.5      .1       0  6944.5     .05       0  7071.8      .1       0
  7262.2     .05       0  7614.7      .1       0  7781.5     .16       0
Bank Sta=4964.9,5035.7
XS Rating Curve= 0 ,0
Exp/Cntr=0.3,0.1

Type RM Length L Ch R = 1 ,57710   ,3146,3146,3146
BEGIN DESCRIPTION:
CEDAR CREEK 36.0
END DESCRIPTION:
XS GIS Cut Line= 3
      3567042.12     10299141.66      3566131.54     10298361.16
      3564276.75     10295743.48
#Sta/Elev= 30
  3183.2  299.51  3446.1  296.08  3594.3  288.68  3616.2   282.7  3694.1  289.39
  3795.6  290.31  3932.9  287.22  4047.2  281.94    4173  277.52  4590.7  271.91
  4632.7  276.39    4850  276.23  4970.2  276.89    5010  267.73  5012.7  267.23
    5016  267.73  5027.8  276.64  5358.7  275.76    6235  274.45  6273.6  274.34
  6487.8  274.67  6702.3  273.81  6754.8   273.7  6863.7  276.04  7025.9  286.99
  7126.3  295.39  7163.3  299.18    7330  312.46  7497.8  313.34  7590.7   312.2
#Mann= 19 ,-1 , 0
  3183.2     .16       0  3795.6     .05       0  3932.9     .16       0
  4047.2     .05       0    4173     .12       0  4590.7     .16       0
    4850     .12       0    5010     .07       0    5016     .12       0
  5358.7     .16       0    6235     .05       0  6273.6     .16       0
  6487.8     .05       0  6702.3     .07       0  6754.8     .05       0
  7025.9      .1       0  7126.3     .05       0  7163.3      .1       0
  7497.8     .05       0
Bank Sta=4970.2,5027.8
XS Rating Curve= 0 ,0
Exp/Cntr=0.3,0.1

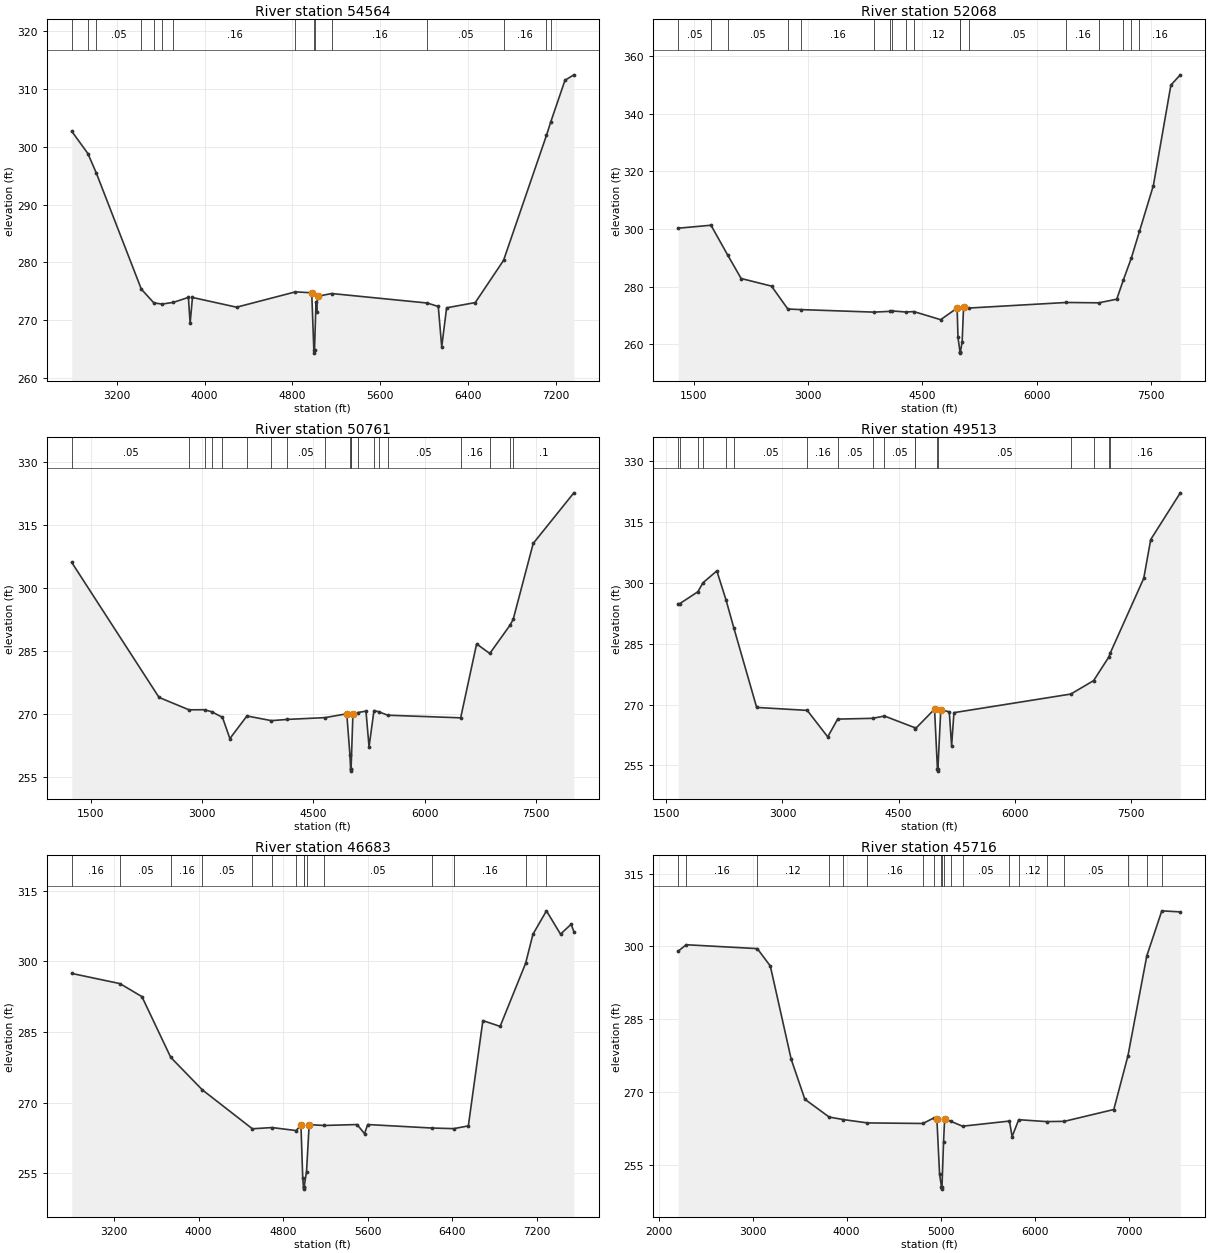
Type RM Length L Ch R = 1 ,54564   ,2496,2496,2496
BEGIN DESCRIPTION:
CEDAR CREEK 35.0
END DESCRIPTION:
XS GIS Cut Line= 3
      3567992.11     10298541.65       3567065.4     10297002.19
      3564592.08     10295741.63
#Sta/Elev= 30
  2790.7  302.66  2937.4  298.82  3014.6  295.43  3424.2  275.38  3538.6     273
  3613.7   272.8  3716.7   273.1  3853.1  273.95  3868.6  269.47    3890  273.94
    4292  272.26  4828.2  274.91  4976.3  274.75  4995.6  264.82  4998.3  264.32
  5001.6  264.82  5015.2   273.2  5020.8  271.45    5029  274.14  5157.9  274.62
  6028.4  272.98  6128.9  272.38  6160.2   265.4  6204.7  272.15  6465.7  273.06
  6723.3  280.35  7113.9  301.94  7153.7  304.31  7282.9  311.48  7363.6  312.42
#Mann= 15 ,-1 , 0
  2790.7     .05       0  2937.4     .16       0  3014.6     .05       0
  3424.2     .12       0  3538.6     .05       0  3613.7     .12       0
  3716.7     .16       0  4828.2     .12       0  4995.6     .07       0
  5001.6     .12       0  5157.9     .16       0  6028.4     .05       0
  6723.3     .16       0  7113.9      .1       0  7153.7     .05       0
Bank Sta=4976.3,5029
XS Rating Curve= 0 ,0
Exp/Cntr=0.3,0.1

Type RM Length L Ch R = 1 ,52068   ,1307,1307,1307
BEGIN DESCRIPTION:
CEDAR CREEK 34.0
END DESCRIPTION:
XS GIS Cut Line= 3
      3568486.85     10298944.51      3567542.11     10295341.64
      3566522.86     10292661.91
#Sta/Elev= 30
  1296.1  300.29  1726.1  301.32  1947.9  290.85    2122  282.83  2520.7  280.19
  2735.1  272.23  2907.5  272.04    3868  271.16  4081.9  271.44  4105.6  271.57
  4287.1   271.2  4389.7  271.35  4741.6  268.54  4957.6  272.57  4969.1  262.36
    4995  257.43  4997.7  256.93    5001  257.43  5023.4  260.81  5042.2  273.01
  5113.7  272.58  6391.5  274.51  6818.2  274.39  7053.6  275.66  7138.3   282.2
    7245  289.94  7351.7  299.22    7534   315.1  7764.2  349.97  7887.8  353.52
#Mann= 18 ,-1 , 0
  1296.1     .05       0  1726.1     .16       0  1947.9     .05       0
  2735.1     .12       0  2907.5     .16       0    3868      .1       0
  4081.9     .05       0  4105.6      .1       0  4287.1     .16       0
  4389.7     .12       0    4995     .07       0    5001     .12       0
  5113.7     .05       0  6391.5     .16       0  6818.2     .12       0
  7138.3     .16       0    7245     .12       0  7351.7     .16       0
Bank Sta=4957.6,5042.2
XS Rating Curve= 0 ,0
Exp/Cntr=0.3,0.1

Type RM Length L Ch R = 1 ,50761   ,1248,1248,1248
BEGIN DESCRIPTION:
CEDAR CREEK 32.0
END DESCRIPTION:
XS GIS Cut Line= 3
      3569474.25     10298597.23      3568583.03     10295294.73
      3567727.49     10292065.89
#Sta/Elev= 30
  1246.3  306.04  2421.2     274  2824.6  271.05  3033.9  271.07  3128.7   270.6
  3275.5  269.27  3375.4  264.22  3605.2  269.59  3934.5  268.48  4148.1  268.77
  4659.9   269.2  4949.4  270.11  4991.7  260.43  5001.4  256.99  5004.1  256.49
  5007.4  256.99  5032.2  270.04  5101.1  270.41  5208.1  270.74  5249.5  262.26
  5315.8  270.88  5380.9  270.58  5499.8  269.77  6483.2  269.15  6697.8   286.7
  6875.3  284.43  7147.6  291.15  7190.4  292.53  7460.1  310.57  8007.2  322.58
#Mann= 20 ,-1 , 0
  1246.3     .05       0  2824.6     .16       0  3033.9     .05       0
  3128.7     .16       0  3275.5     .12       0  3605.2     .05       0
  3934.5     .16       0  4148.1     .05       0  4659.9     .16       0
  4991.7      .1       0  5001.4     .07       0  5007.4      .1       0
  5101.1     .16       0  5315.8     .05       0  5380.9     .16       0
  5499.8     .05       0  6483.2     .16       0  6875.3      .1       0
  7147.6     .05       0  7190.4      .1       0
Bank Sta=4949.4,5032.2
XS Rating Curve= 0 ,0
Exp/Cntr=0.3,0.1

Type RM Length L Ch R = 1 ,49513   ,2830,2830,2830
BEGIN DESCRIPTION:
CEDAR CREEK 31.0
END DESCRIPTION:
XS GIS Cut Line= 3
      3570092.74     10298325.99      3569702.12     10295298.63
      3569788.92     10291869.79
#Sta/Elev= 30
    1654  294.89    1675  294.92  1907.7  297.84  1973.6  300.06  2152.4  302.99
  2272.2  295.74  2371.8  288.92  2666.7  269.29  3319.4  268.56  3584.2  262.03
  3712.6  266.41  4163.5   266.6  4316.3  267.17  4710.3  264.28  4711.5  263.95
  4963.5  268.87  5000.5  254.07  5003.3  253.57  5006.5  254.07  5043.6  268.73
  5153.6  268.19  5183.6  259.74  5213.6     268  6722.5  272.59  7017.4  275.91
  7213.7  281.75  7232.1  282.72  7664.4  301.16  7754.4  310.73  8136.4  322.25
#Mann= 18 ,-1 , 0
    1654      .1       0    1675     .05       0  1907.7      .1       0
  1973.6     .05       0  2272.2      .1       0  2371.8     .05       0
  3319.4     .16       0  3712.6     .05       0  4163.5      .1       0
  4316.3     .05       0  4710.3      .1       0  4711.5     .05       0
  5000.5     .03       0  5006.5     .05       0  6722.5      .1       0
  7017.4     .16       0  7213.7     .12       0  7232.1     .16       0
Bank Sta=4963.5,5043.6
XS Rating Curve= 0 ,0
Exp/Cntr=0.3,0.1

Type RM Length L Ch R = 1 ,46683   ,967,967,967
BEGIN DESCRIPTION:
CEDAR CREEK 29.0
END DESCRIPTION:
XS GIS Cut Line= 3
      3570754.64     10298184.92      3571112.71     10295645.86
      3570971.71      10293465.8
#Sta/Elev= 30
  2800.7  297.46  3256.7   295.3  3464.2  292.54  3736.8  279.65  4034.6  272.77
  4508.8  264.49  4695.7  264.75  4922.4  264.11  4968.5  265.25  4985.4  253.96
  4992.5  252.18  4995.2  251.68  4998.5  252.18  5021.1  255.41    5046  265.37
  5186.3  265.19  5499.4  265.39  5569.5  263.45  5599.6  265.39  6205.1  264.65
    6414  264.52  6551.6   265.1    6689  287.45  6852.2  286.22  7093.1   299.6
  7162.9  305.79  7290.5  310.75  7423.4   305.8  7523.6   307.9  7549.5  306.36
#Mann= 15 ,-1 , 0
  2800.7     .16       0  3256.7     .05       0  3736.8     .16       0
  4034.6     .05       0  4508.8     .16       0  4695.7     .05       0
  4922.4     .12       0  4992.5     .07       0  4998.5     .12       0
  5021.1     .16       0  5186.3     .05       0  6205.1      .1       0
    6414     .16       0  7093.1      .1       0  7290.5     .16       0
Bank Sta=4968.5,5046
XS Rating Curve= 0 ,0
Exp/Cntr=0.3,0.1

Type RM Length L Ch R = 1 ,45716   ,1486,1486,1486
BEGIN DESCRIPTION:
CEDAR CREEK 27.0
END DESCRIPTION:
XS GIS Cut Line= 3
      3571123.56     10298532.13      3572030.53     10295399.28
      3571937.43     10293325.26
#Sta/Elev= 30
  2209.2  299.02  2294.1  300.33  3049.7  299.53    3188  295.95  3410.4  276.71
  3555.2  268.49  3813.5  264.82  3965.8  264.29  4220.7  263.61  4810.2  263.49
  4928.4  264.65  4959.1  264.36  4987.5  253.08  5007.2  250.46  5009.9  249.96
  5013.2  250.46  5029.5  259.59  5041.4  264.48  5108.1  263.93  5231.7  262.93
  5730.3  263.99  5758.6  260.79  5828.8  264.27  6124.3  263.88  6313.2  263.93
  6839.7  266.37  6990.6  277.49  7190.6  298.04  7350.3  307.32  7546.8   307.1
#Mann= 20 ,-1 , 0
  2209.2     .05       0  2294.1     .16       0  3049.7     .12       0
  3813.5     .16       0  3965.8     .12       0  4220.7     .16       0
  4810.2     .12       0  4928.4     .16       0  5007.2     .07       0
  5013.2     .16       0  5029.5     .12       0  5108.1     .16       0
  5231.7     .05       0  5730.3      .1       0  5828.8     .12       0
  6124.3      .1       0  6313.2     .05       0  6990.6      .1       0
  7190.6      .1       0  7350.3     .05       0
Bank Sta=4959.1,5041.4
XS Rating Curve= 0 ,0
Exp/Cntr=0.3,0.1

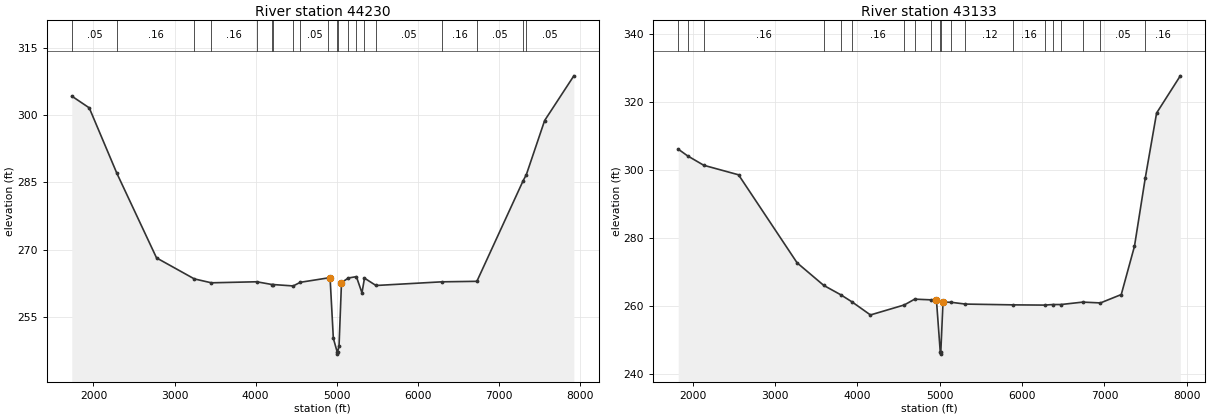
Type RM Length L Ch R = 1 ,44230   ,1097,1097,1097
BEGIN DESCRIPTION:
CEDAR CREEK 26.0
END DESCRIPTION:
XS GIS Cut Line= 3
      3573033.28     10298977.01      3572942.11     10295691.64
      3572523.51     10292815.28
#Sta/Elev= 30
  1732.3  304.24  1947.8  301.62  2289.1  287.01  2778.1  268.17  3244.2  263.49
  3454.3  262.62    4014  262.85  4204.8  262.23  4209.5  262.24  4463.9  261.92
  4551.1  262.73  4898.1  263.72  4918.9  263.66  4958.9  250.25  5005.9  247.22
  5008.7  246.72  5011.9  247.22    5029  248.48  5059.4  262.65  5143.5  263.69
  5243.3  263.99    5312  260.38  5343.1  263.66  5484.7  262.02  6298.6  262.84
  6729.5  262.95    7301  285.41  7339.6  286.73  7565.5   298.8  7925.6  308.76
#Mann= 20 ,-1 , 0
  1732.3     .05       0  2289.1     .16       0  3244.2     .12       0
  3454.3     .16       0    4014     .05       0  4204.8     .16       0
  4209.5     .05       0  4463.9     .16       0  4551.1     .05       0
  4898.1     .16       0  5005.9     .07       0  5011.9     .16       0
  5143.5      .1       0  5243.3     .05       0  5343.1      .1       0
  5484.7     .05       0  6298.6     .16       0  6729.5     .05       0
    7301      .1       0  7339.6     .05       0
Bank Sta=4918.9,5059.4
XS Rating Curve= 0 ,0
Exp/Cntr=0.3,0.1

Type RM Length L Ch R = 1 ,43133   ,1184,1184,1184
BEGIN DESCRIPTION:
CEDAR CREEK 25.0
END DESCRIPTION:
XS GIS Cut Line= 3
      3574074.95     10298673.17      3573942.99     10295724.78
       3573738.6     10292586.27
#Sta/Elev= 30
    1825  306.13  1938.2  304.16  2135.2  301.38  2557.3  298.58    3268  272.68
  3592.5  266.02    3800  263.25  3938.6  261.12  4158.9  257.33  4570.5  260.28
  4695.9  261.98  4893.1  261.78  4959.9  261.86    5007   246.3  5009.7   245.8
    5013   246.3    5040  261.14  5140.5  261.05  5312.5  260.53  5893.7   260.3
  6274.7  260.23  6373.3   260.4    6472   260.4  6737.5  261.11  6951.8  260.87
  7204.6  263.34  7364.9  277.55  7495.1  297.51  7633.6  316.76  7921.5  327.71
#Mann= 20 ,-1 , 0
    1825     .05       0  1938.2     .05       0  2135.2     .16       0
  3592.5     .16       0    3800     .05       0  3938.6     .16       0
  4570.5      .1       0  4695.9     .05       0  4893.1     .12       0
    5007     .07       0    5013     .12       0  5140.5     .16       0
  5312.5     .12       0  5893.7     .16       0  6274.7      .1       0
  6373.3     .05       0    6472     .16       0  6737.5     .16       0
  6951.8     .05       0  7495.1     .16       0
Bank Sta=4959.9,5040
XS Rating Curve= 0 ,0
Exp/Cntr=0.3,0.1