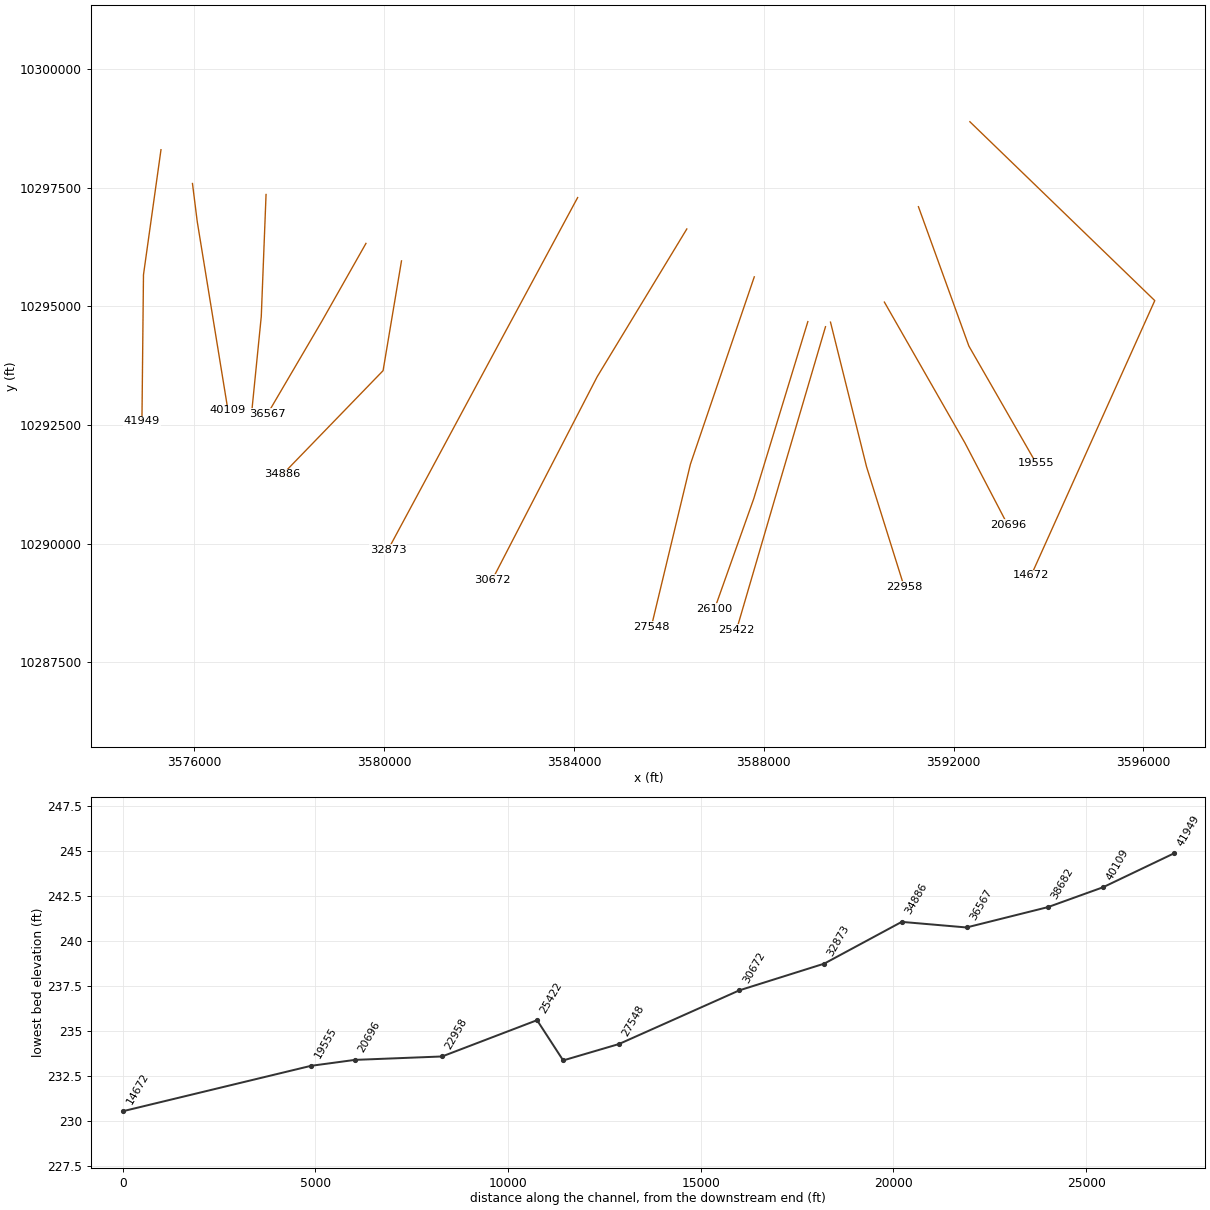
HEC-RAS study CEDAR CREEK.prj: CEDAR CREEK Base Level Engineering

--- CEDAR CREEK.g01 (geometry) --- (continued)

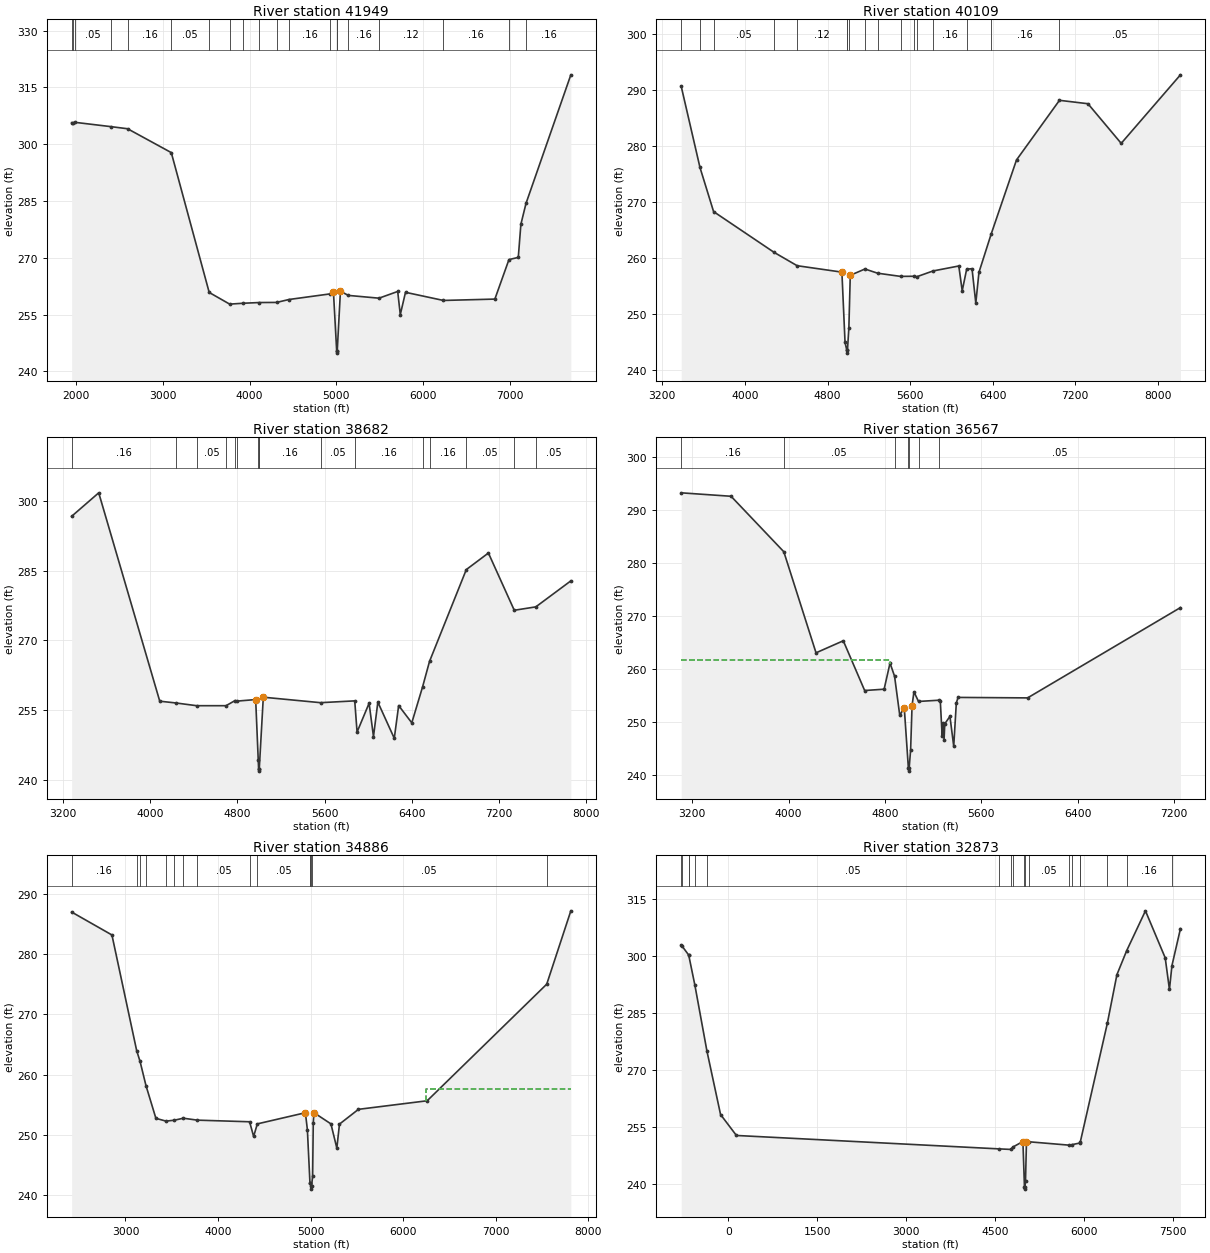
Type RM Length L Ch R = 1 ,41949   ,1840,1840,1840
BEGIN DESCRIPTION:
CEDAR CREEK 24.0
END DESCRIPTION:
XS GIS Cut Line= 3
      3575301.07     10298304.25      3574932.15     10295667.56
      3574899.61     10292575.91
#Sta/Elev= 30
  1948.3   305.7  1969.8  305.62  1985.7   305.8  2400.3  304.66  2593.6   304.1
  3097.1   297.8  3534.1  260.87  3770.1  257.79  3924.3  258.02  4112.6  258.21
  4311.3  258.24  4453.1  259.01  4926.9  260.49  4966.6  260.86  5003.6  245.35
  5006.4  244.85  5009.6  245.35  5046.6  261.19  5138.6  260.09  5491.3  259.36
  5706.7  261.13  5736.7  255.03  5796.7  260.91    6234  258.76  6826.7  259.12
  6989.1  269.55  7096.7  270.13  7126.7  278.88  7185.7  284.39  7702.5  318.34
#Mann= 20 ,-1 , 0
  1948.3     .05       0  1969.8     .16       0  1985.7     .05       0
  2400.3     .16       0  2593.6     .16       0  3097.1     .05       0
  3534.1     .07       0  3770.1     .16       0  3924.3     .05       0
  4112.6     .16       0  4311.3     .05       0  4453.1     .16       0
  4926.9     .12       0  5003.6     .07       0  5009.6     .12       0
  5138.6     .16       0  5491.3     .12       0    6234     .16       0
  6989.1      .1       0  7185.7     .16       0
Bank Sta=4966.6,5046.6
XS Rating Curve= 0 ,0
Exp/Cntr=0.3,0.1

Type RM Length L Ch R = 1 ,40109   ,1427,1427,1427
BEGIN DESCRIPTION:
CEDAR CREEK 22.0
END DESCRIPTION:
XS GIS Cut Line= 3
      3575964.47     10297591.81      3576064.47     10296791.83
      3576711.44     10292815.23
#Sta/Elev= 30
  3383.4  290.68  3564.8  276.19  3696.7  268.29  4281.8  261.01  4505.8  258.61
  4939.5  257.46  4969.9  244.88  4987.2  243.47  4989.9  242.97  4993.2  243.47
    5007  247.51  5020.6  256.89  5162.5  258.02  5285.1  257.27  5507.1   256.7
    5635  256.72  5666.8  256.65  5822.1  257.67  6071.7  258.56  6104.7  254.12
    6148     258  6199.8  258.07  6236.4  251.92  6266.8  257.42  6384.4  264.23
  6630.6  277.53  7046.7   288.2  7322.6  287.59  7644.6   280.5  8218.5  292.76
#Mann= 17 ,-1 , 0
  3383.4     .05       0  3564.8     .16       0  3696.7     .05       0
  4281.8     .16       0  4505.8     .12       0  4987.2     .07       0
  4993.2     .12       0    5007     .16       0  5162.5     .12       0
  5285.1     .16       0  5507.1     .05       0    5635     .16       0
  5666.8     .05       0  5822.1     .16       0    6148     .12       0
  6384.4     .16       0  7046.7     .05       0
Bank Sta=4939.5,5020.6
XS Rating Curve= 0 ,0
Exp/Cntr=0.3,0.1

Type RM Length L Ch R = 1 ,38682   ,2115,2115,2115
BEGIN DESCRIPTION:
CEDAR CREEK 21.0
END DESCRIPTION:
XS GIS Cut Line= 3
      3577514.62     10297360.22      3577414.04     10294788.47
      3577214.04     10292788.46
#Sta/Elev= 30
  3277.6  296.74  3526.4   301.8  4086.8  256.93  4234.6  256.55  4425.7  255.96
  4695.6  255.96  4778.5  257.07  4796.8  256.95  4967.5  257.28  4990.9  244.36
  4994.5  242.37  4997.2  241.87  5000.5  242.37  5037.5  257.79  5562.8  256.61
  5877.1     257  5898.4  250.28  6008.9  256.49  6049.1  249.31  6089.3  256.73
  6240.1  248.94  6280.3  255.99  6400.9  252.27  6500.2  260.03  6563.7   265.5
  6901.4  285.27  7104.4  288.84  7341.8  276.51  7539.6  277.24  7861.3  282.84
#Mann= 16 ,-1 , 0
  3277.6     .16       0  4234.6     .12       0  4425.7     .05       0
  4695.6     .16       0  4778.5     .05       0  4796.8     .12       0
  4990.9     .16       0  4994.5     .07       0  5000.5     .16       0
  5562.8     .05       0  5877.1     .16       0  6500.2     .12       0
  6563.7     .16       0  6901.4     .05       0  7341.8      .1       0
  7539.6     .05       0
Bank Sta=4967.5,5037.5
XS Rating Curve= 0 ,0
Exp/Cntr=0.3,0.1

Type RM Length L Ch R = 1 ,36567   ,1681,1681,1681
BEGIN DESCRIPTION:
CEDAR CREEK 19.0
END DESCRIPTION:
XS GIS Cut Line= 3
      3579619.63     10296329.42      3578692.11     10294691.64
      3577547.18     10292737.88
#Sta/Elev= 30
  3108.2  293.22  3522.1  292.57  3960.3  282.11  4227.8  263.05  4454.3  265.32
  4631.8  255.94  4793.4  256.19  4842.5  261.12  4880.2  258.63  4923.3  251.27
  4960.8  252.69  4995.2  241.24    4998  240.74  5001.2  241.24  5013.6  244.78
  5025.5   253.1  5041.2  255.69  5079.2  253.88  5247.6  254.11  5260.1  253.95
  5275.8  247.27  5281.6  249.76  5291.4  246.68  5297.2  249.66  5340.2  251.07
  5371.6  245.43  5393.1  253.58  5407.6  254.64  5985.3  254.55  7254.9  271.58
#Mann= 7 ,-1 , 0
  3108.2     .16       0  3960.3     .05       0  4880.2     .12       0
  4995.2     .07       0  5001.2     .12       0  5079.2     .16       0
  5247.6     .05       0
#XS Ineff= 2 , 0
         4845.93  261.72
Permanent Ineff=
       F       F
Bank Sta=4960.8,5025.5
XS Rating Curve= 0 ,0
Exp/Cntr=0.3,0.1

Type RM Length L Ch R = 1 ,34886   ,2013,2013,2013
BEGIN DESCRIPTION:
CEDAR CREEK 18.0
END DESCRIPTION:
XS GIS Cut Line= 3
      3580368.35     10295960.49      3579980.19     10293646.31
      3577861.87     10291457.52
#Sta/Elev= 30
  2418.6  286.96  2853.9  283.16  3121.3  263.99  3157.8  262.21  3221.6  258.21
  3328.9  252.78    3438  252.32  3528.8  252.47  3625.2   252.8    3775  252.48
    4341  252.21  4384.5  249.78  4424.6  251.86  4943.8  253.71  4965.2   250.9
    4993  242.08  4993.8  242.06  5004.6  241.55  5007.4  241.05  5010.6  241.55
  5021.8  243.18  5028.7  252.03  5035.9  253.72  5219.6  251.86  5283.4  247.84
  5311.7  251.82  5516.7  254.27  6259.3  255.69  7550.7  275.01  7811.1  287.16
#Mann= 15 ,-1 , 0
  2418.6     .16       0  3121.3     .05       0  3157.8     .16       0
  3221.6     .05       0    3438      .1       0  3528.8     .05       0
  3625.2      .1       0    3775     .05       0    4341      .1       0
  4424.6     .05       0    4993     .16       0  4993.8     .05       0
  5004.6     .03       0  5010.6     .05       0  7550.7     .16       0
#XS Ineff= 2 , 0
                         6242.73          257.58
Permanent Ineff=
       F       F
Bank Sta=4943.8,5035.9
XS Rating Curve= 0 ,0
Exp/Cntr=0.3,0.1

Type RM Length L Ch R = 1 ,32873   ,2201,2201,2201
BEGIN DESCRIPTION:
CEDAR CREEK 17.0
END DESCRIPTION:
XS GIS Cut Line= 3
      3584079.31      10297295.2      3581865.75     10293182.75
      3580087.56     10289875.75
#Sta/Elev= 30
  -793.9  302.83    -781  302.66  -670.6  300.34  -667.1  300.22  -564.1   292.4
  -359.9  275.01  -130.3  258.35   137.4  252.84  4572.8  249.31  4767.1  249.17
  4802.5  249.79  4972.5  251.25  4998.7  239.23  5001.5  238.73  5004.7  239.23
  5016.3  240.95  5032.5  251.22  5074.7  251.18  5754.6  250.29  5807.2  250.45
    5933  250.85  5941.8  251.19  6397.5  282.35  6559.1  295.13  6723.6  301.43
  7040.4  311.91  7373.9  299.55  7445.3  291.24  7487.5   297.5  7631.2  307.23
#Mann= 19 ,-1 , 0
  -793.9     .05       0    -781      .1       0  -670.6     .16       0
  -667.1      .1       0  -564.1     .16       0  -359.9     .05       0
  4572.8      .1       0  4767.1     .05       0  4802.5     .16       0
  4998.7     .07       0  5004.7     .16       0  5074.7     .05       0
  5754.6      .1       0  5807.2     .05       0    5933      .1       0
  5941.8     .05       0  6397.5      .1       0  6723.6     .16       0
  7487.5     .05       0
Bank Sta=4972.5,5032.5
XS Rating Curve= 0 ,0
Exp/Cntr=0.3,0.1

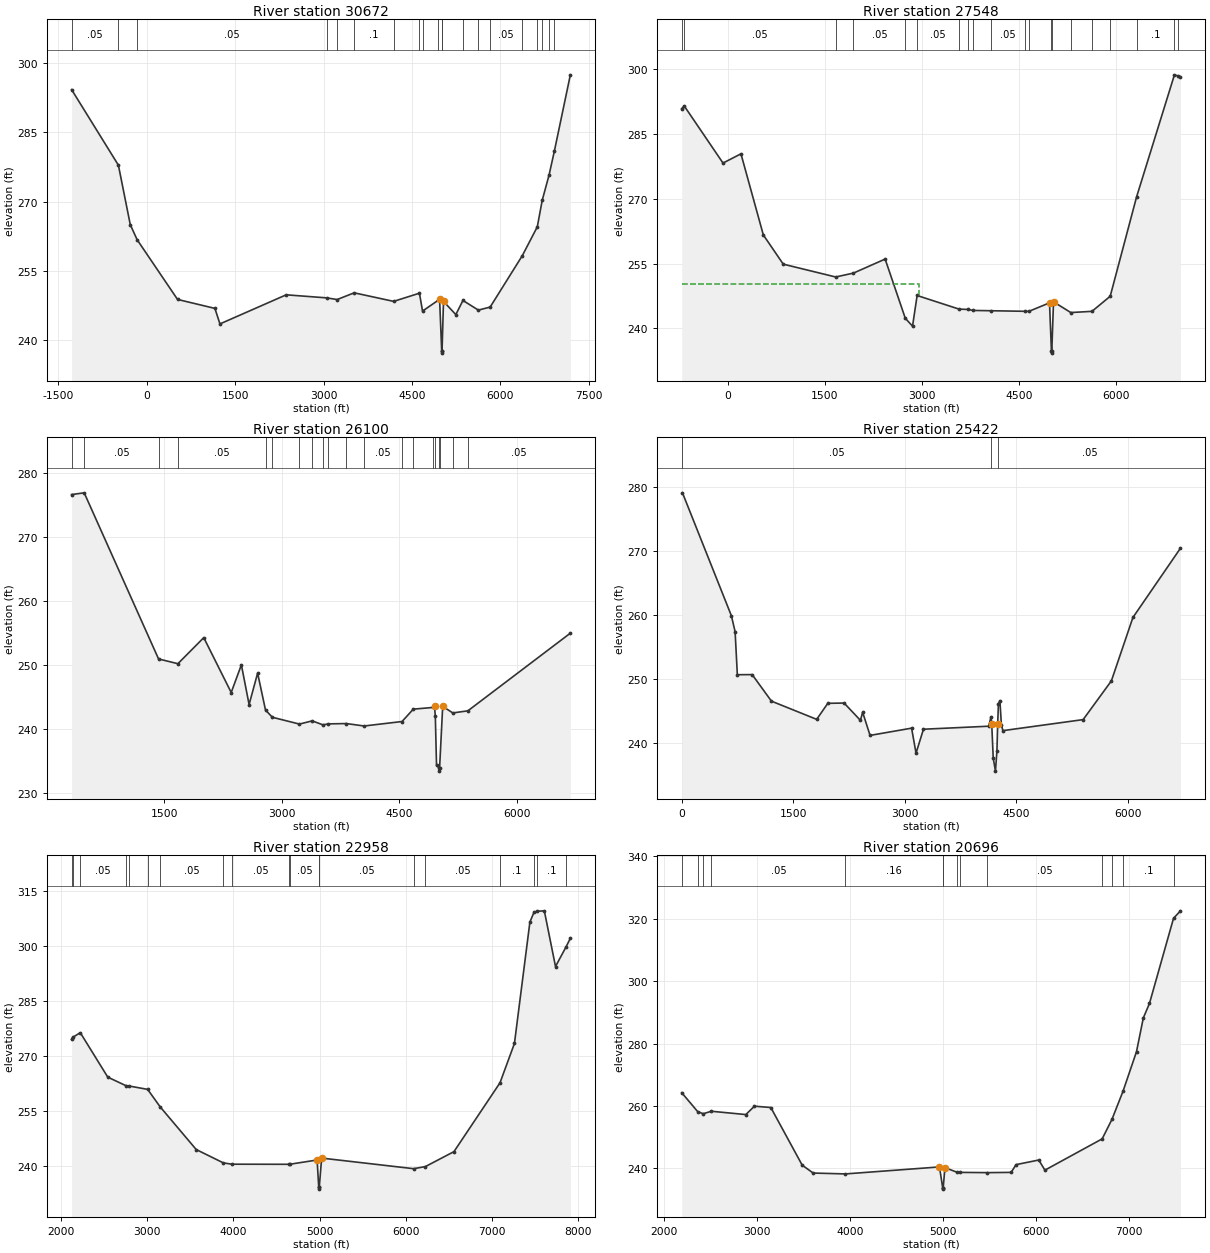
Type RM Length L Ch R = 1 ,30672   ,3124,3124,3124
BEGIN DESCRIPTION:
CEDAR CREEK 16.0
END DESCRIPTION:
XS GIS Cut Line= 3
      3586379.62     10296633.24      3584491.61     10293519.12
        3582279.     10289234.89
#Sta/Elev= 30
 -1277.5  294.28  -483.5  277.93  -281.6  265.04  -165.3  261.79   520.3  248.87
  1154.3  246.93  1239.7  243.57  2364.2  249.87  3050.1  249.21  3229.2  248.85
  3517.9   250.3  4187.3  248.45  4625.3  250.22  4677.7  246.35    4939  248.65
  4967.2  248.91  5002.8  237.75  5005.6  237.25  5008.8  237.75  5033.6  248.45
  5242.7  245.59  5363.3  248.65  5625.2  246.56  5825.2  247.22  6370.2  258.33
  6625.1  264.58  6708.7  270.32  6825.1  275.81  6914.7  280.96  7186.1  297.48
#Mann= 20 ,-1 , 0
 -1277.5     .05       0  -483.5      .1       0  -165.3     .05       0
  3050.1     .12       0  3229.2     .05       0  3517.9      .1       0
  4187.3     .05       0  4625.3      .1       0  4677.7     .16       0
    4939     .12       0  5002.8     .07       0  5008.8     .12       0
  5363.3     .16       0  5625.2      .1       0  5825.2     .05       0
  6370.2      .1       0  6625.1     .05       0  6708.7      .1       0
  6825.1      .1       0  6914.7     .16       0
Bank Sta=4967.2,5033.6
XS Rating Curve= 0 ,0
Exp/Cntr=0.3,0.1

Type RM Length L Ch R = 1 ,27548   ,1448,1448,1448
BEGIN DESCRIPTION:
CEDAR CREEK 15.0
END DESCRIPTION:
XS GIS Cut Line= 3
      3587801.08     10295624.16      3586455.59      10291674.5
      3585631.06      10288246.2
#Sta/Elev= 30
  -709.2   290.9  -670.9  291.54     -72   278.3   204.9  280.44   550.6  261.64
     858  254.88  1666.9  251.91  1941.5  252.81  2430.5  256.06  2741.8  242.34
  2853.6  240.52  2924.3  247.62  3570.6  244.47  3714.8  244.38  3784.4  244.16
  4068.7  244.09  4588.9  243.96  4648.5  243.94  4967.9  245.92  4997.2  234.77
  4999.9  234.27  5003.2  234.77  5029.6  246.16  5296.4  243.67  5623.5  243.95
  5904.5  247.44  6312.4  270.49  6896.1  298.74  6944.9  298.51  6989.4   298.3
#Mann= 20 ,-1 , 0
  -709.2      .1       0  -670.9     .05       0  1666.9     .07       0
  1941.5     .05       0  2741.8      .1       0  2924.3     .05       0
  3570.6      .1       0  3714.8     .05       0  3784.4      .1       0
  4068.7     .05       0  4588.9      .1       0  4648.5     .05       0
  4997.2     .03       0  5003.2     .05       0  5296.4     .12       0
  5623.5      .1       0  5904.5     .16       0  6312.4      .1       0
  6896.1     .05       0  6944.9     .05       0
#XS Ineff= 2 , 0
          2956.4  250.17
Permanent Ineff=
       F       F
Bank Sta=4967.9,5029.6
XS Rating Curve= 0 ,0
Exp/Cntr=0.3,0.1

Type RM Length L Ch R = 1 ,26100   ,678,678,678
BEGIN DESCRIPTION:
CEDAR CREEK 14.0
END DESCRIPTION:
XS GIS Cut Line= 3
      3588929.54      10294680.1      3587790.23      10290947.5
      3586965.79     10288626.06
#Sta/Elev= 30
   318.6  276.56   479.4  276.83  1428.6  250.88  1675.5  250.14  2005.5  254.21
  2355.8  245.64  2485.7  249.96  2584.1  243.76    2693  248.67  2793.6   242.9
  2881.5  241.77  3226.8  240.71  3389.7  241.21  3526.4  240.59  3597.6  240.74
  3826.1  240.79  4052.6  240.41  4536.3  241.11  4680.1  243.04  4933.7  243.31
    4951  243.47  4961.2  241.92  4976.6  234.27  5009.7  233.86  5012.5  233.36
  5015.7  233.86  5055.2  243.47  5184.5  242.45  5376.9  242.78  6684.7  254.91
#Mann= 20 ,-1 , 0
   318.6     .16       0   479.4     .05       0  1428.6      .1       0
  1675.5     .05       0  2793.6      .1       0  2881.5     .05       0
  3226.8      .1       0  3389.7     .05       0  3526.4     .12       0
  3597.6     .05       0  3826.1      .1       0  4052.6     .05       0
  4536.3      .1       0  4680.1     .05       0  4933.7      .1       0
  4961.2     .05       0  5009.7    .035       0  5015.7     .05       0
  5184.5     .16       0  5376.9     .05       0
Bank Sta=4951,5055.2
XS Rating Curve= 0 ,0
Exp/Cntr=0.3,0.1

Type RM Length L Ch R = 1 ,25422   ,2464,2464,2464
XS GIS Cut Line= 3
     3589301.561    10294572.993     3588306.008    10291189.028
     3587426.561    10288179.365
#Sta/Elev= 30
9.977377279.0947668.4843259.8749718.3711 257.384748.3032250.6639947.8508250.6818
1207.263246.53111815.883243.68591965.543246.19252185.045246.23432404.548243.5305
 2434.48244.79932534.254241.17793092.987242.31153152.851238.40193252.625242.1436
4131.389242.61524161.385244.09964171.384242.98224191.382237.64024221.379235.5937
4241.376238.76564251.375242.90154261.375246.10554281.373246.6129 4301.37242.8466
4321.368241.92175401.253243.64645781.212249.69876071.182259.61076711.113270.4386
#Mann= 3 ,-1 , 0
       0     .05       04161.385    .035       04261.375     .05       0
Bank Sta=4171.384,4251.375
XS Rating Curve= 0 ,0
Exp/Cntr=0.3,0.1

Type RM Length L Ch R = 1 ,22958   ,2262,2262,2262
BEGIN DESCRIPTION:
CEDAR CREEK 12.0
END DESCRIPTION:
XS GIS Cut Line= 3
      3589406.99     10294669.26      3590166.53     10291620.25
      3590958.63     10289092.02
#Sta/Elev= 30
  2120.5  274.53  2132.9  275.08  2221.4  276.37  2540.6  264.21  2751.2  261.88
  2782.7  261.81  3003.7  260.86  3147.5  256.12  3567.5  244.41  3882.5  240.76
  3981.4   240.4  4648.1  240.37  4661.2  240.41  4971.5  241.55  4990.3  234.08
  4993.1  233.58  4996.3  234.08  5024.2  242.07  6091.6  239.17  6228.3  239.74
  6560.7  243.84  7095.3  262.67  7262.8  273.42  7442.4  306.64  7489.3  309.26
  7524.8  309.58  7609.9   309.7  7739.7  294.47  7858.8  299.69  7912.1  302.19
#Mann= 19 ,-1 , 0
  2120.5     .05       0  2132.9     .16       0  2221.4     .05       0
  2751.2     .16       0  2782.7     .05       0  3003.7      .1       0
  3147.5     .05       0  3882.5      .1       0  3981.4     .05       0
  4648.1      .1       0  4661.2     .05       0  4990.3    .035       0
  4996.3     .05       0  6091.6      .1       0  6228.3     .05       0
  7095.3      .1       0  7489.3     .05       0  7524.8      .1       0
  7858.8     .16       0
Bank Sta=4971.5,5024.2
XS Rating Curve= 0 ,0
Exp/Cntr=0.3,0.1

Type RM Length L Ch R = 1 ,20696   ,1141,1141,1141
BEGIN DESCRIPTION:
CEDAR CREEK 11.0
END DESCRIPTION:
XS GIS Cut Line= 3
      3590542.09     10295091.67      3592239.01     10292123.29
      3593142.12     10290391.62
#Sta/Elev= 30
    2187  264.28  2358.9  258.21  2418.5  257.54  2506.4  258.33  2877.3  257.27
  2970.3  259.95  3146.5  259.53  3484.8  241.06  3602.8  238.54  3950.8  238.26
  4963.2   240.5  4997.6  233.89  5000.4  233.39  5003.6  233.89  5022.2  240.28
  5152.7  238.79  5184.8  238.75  5480.2  238.67  5734.8  238.75  5788.5  241.24
  6032.8  242.71    6099  239.47  6715.7  249.49  6821.1  255.73  6940.7  264.77
  7085.5  277.41  7158.9  288.21  7225.2  292.86  7484.4  320.13  7559.2  322.52
#Mann= 14 ,-1 , 0
    2187     .16       0  2358.9     .05       0  2418.5     .16       0
  2506.4     .05       0  3950.8     .16       0  4997.6     .07       0
  5003.6     .16       0  5152.7     .05       0  5184.8      .1       0
  5480.2     .05       0  6715.7      .1       0  6821.1     .05       0
  6940.7      .1       0  7484.4     .05       0
Bank Sta=4963.2,5022.2
XS Rating Curve= 0 ,0
Exp/Cntr=0.3,0.1

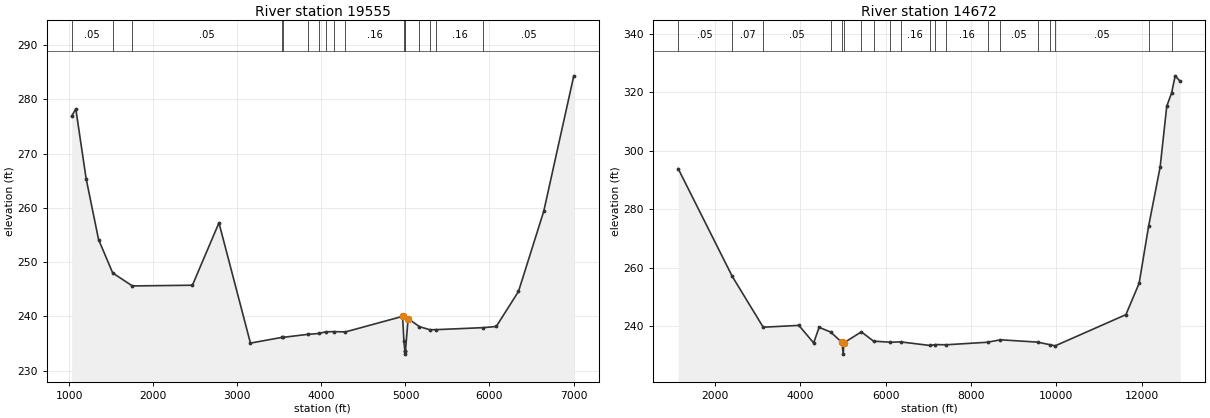
Type RM Length L Ch R = 1 ,19555   ,4883,4883,4883
BEGIN DESCRIPTION:
CEDAR CREEK 10.0
END DESCRIPTION:
XS GIS Cut Line= 3
      3591259.85     10297102.43      3592322.34     10294164.95
      3593742.12     10291691.62
#Sta/Elev= 30
  1027.4  276.91  1077.1  278.21  1199.7  265.39  1347.7  254.17  1516.1  248.01
  1749.8  245.62  2464.5  245.75  2780.4  257.24  3155.1  235.09  3527.6  236.14
  3547.7  236.16  3836.5   236.7  3975.3  236.87  4051.6  237.18  4152.8   237.2
    4285  237.15    4966  240.02  4981.5   235.4  4993.7  233.56  4996.4  233.06
  4999.7  233.56  5031.3   239.6  5166.6  238.12  5290.7  237.55  5367.1  237.57
  5927.7  237.94  6080.5  238.15  6345.1  244.61  6645.5  259.37    7003  284.32
#Mann= 17 ,-1 , 0
  1027.4     .05       0  1516.1     .07       0  1749.8     .05       0
  3527.6     .16       0  3547.7     .05       0  3836.5     .16       0
  3975.3     .05       0  4051.6     .16       0  4152.8     .07       0
    4285     .16       0  4981.5     .12       0  4993.7     .07       0
  4999.7     .12       0  5166.6     .16       0  5290.7     .05       0
  5367.1     .16       0  5927.7     .05       0
Bank Sta=4966,5031.3
XS Rating Curve= 0 ,0
Exp/Cntr=0.3,0.1

Type RM Length L Ch R = 1 ,14672   ,0,0,0
BEGIN DESCRIPTION:
CEDAR CREEK 1.0
END DESCRIPTION:
XS GIS Cut Line= 3
      3592343.21     10298894.09      3596239.01     10295123.29
      3593634.85     10289331.64
#Sta/Elev= 30
  1135.4  293.91  2403.6   257.1    3129  239.74  3965.1  240.36  4311.6  234.37
    4439   239.7    4708   238.1  4976.4  234.52  5004.4  230.54  5018.8  234.38
  5429.7  238.15  5715.4  234.98  6109.9   234.6  6348.3  234.73  7040.8  233.49
  7166.4   233.8  7421.4  233.74  8388.7   234.6  8688.2  235.44  9565.4  234.64
  9861.9  233.72  9973.6  233.37   11632  244.03 11942.5  254.77 12163.2  274.17
 12434.5  294.45 12589.9  315.26   12704  319.81 12786.8  325.63 12907.4  323.71
#Mann= 20 ,-1 , 0
  1135.4     .05       0  2403.6     .07       0    3129     .05       0
    4708     .16       0  4976.4     .07       0  5018.8     .16       0
  5429.7     .05       0  5715.4     .16       0  6109.9      .1       0
  6348.3     .16       0  7040.8     .12       0  7166.4     .12       0
  7421.4     .16       0  8388.7     .16       0  8688.2     .05       0
  9565.4     .16       0  9861.9     .16       0  9973.6     .05       0
 12163.2     .16       0   12704      .1       0
Bank Sta=4976.4,5018.8
XS Rating Curve= 0 ,0
Exp/Cntr=0.3,0.1

Chan Stop Cuts=-1
Use User Specified Reach Order=0
Composite Channel Slope=5