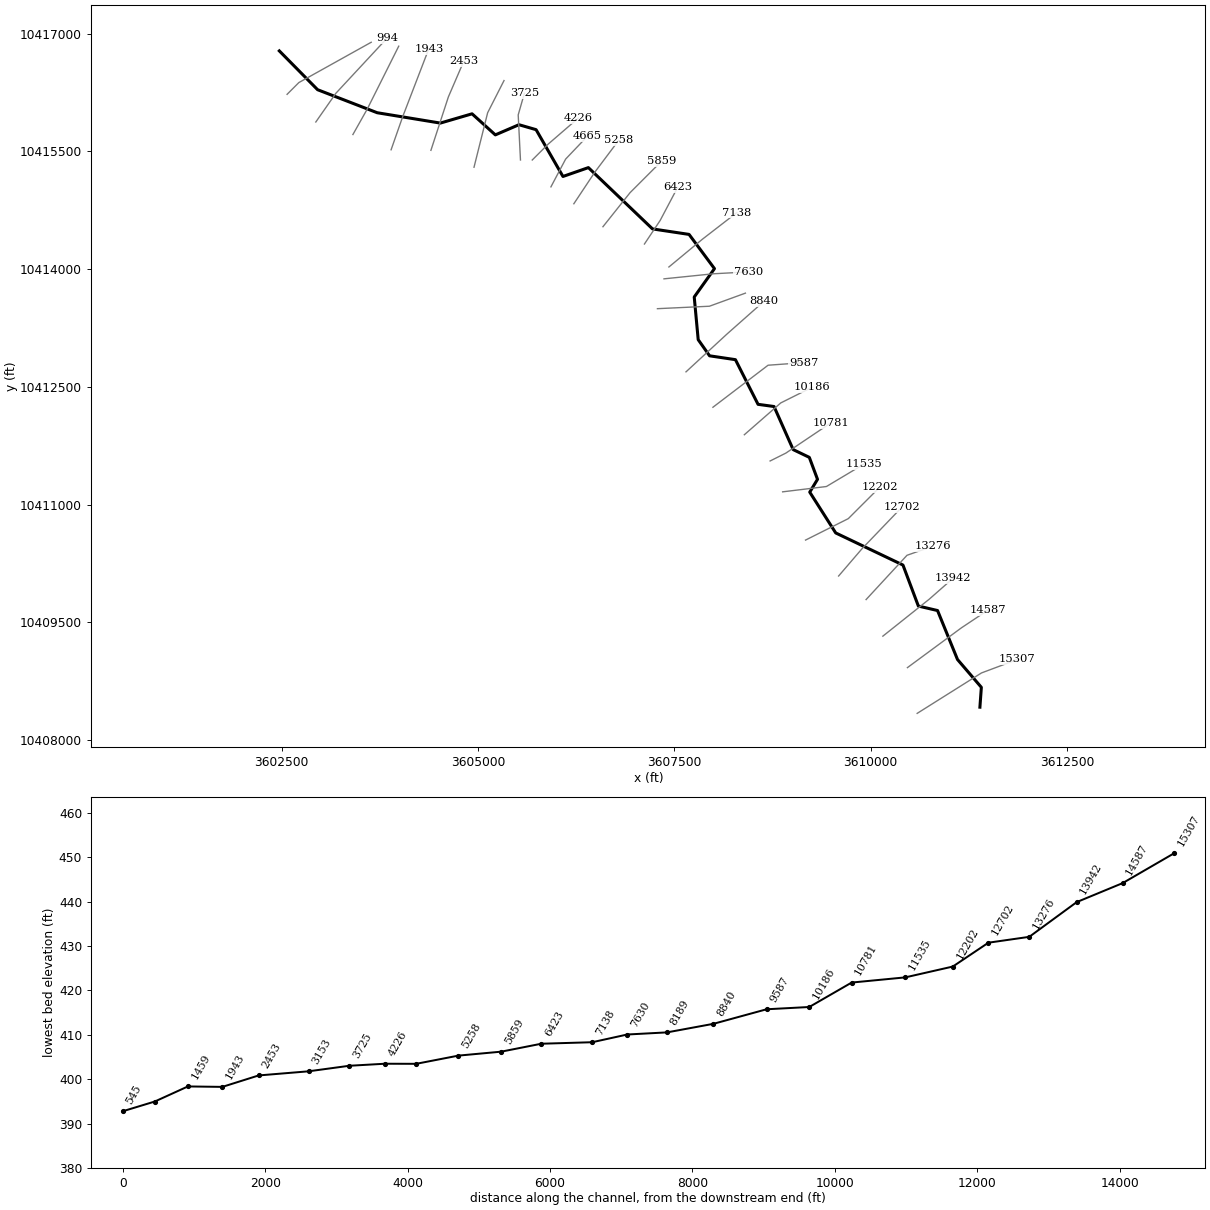
--- CERCEY BRANCH.prj (project) ---

Proj Title=CERCEY BRANCH Base Level Engineering
Current Plan=p01
Default Exp/Contr=0.3,0.1
English Units
Geom File=g01
Flow File=f01
Plan File=p01
BEGIN DESCRIPTION:
CERCEY BRANCH
END DESCRIPTION:

--- CERCEY BRANCH.p01 (plan) ---

Plan Title=Multiple Run
Short Identifier=Multiple
Geom File=g01
Flow File=f01
Subcritical Flow
K Sum by GR= 0
Std Step Tol= 0.01
Critical Tol= 0.01
Num of Std Step Trials= 20
Max Error Tol= 0.3
Flow Tol Ratio= 0.001
Split Flow NTrial= 30
Split Flow Tol= 0.02
Split Flow Ratio= 0.02
Log Output Level= 0
Friction Slope Method= 1
Unsteady Friction Slope Method= 2
Unsteady Bridges Friction Slope Method= 1
Parabolic Critical Depth
Global Vel Dist=  1 , 1 , 1
Global Log Level= 0
CheckData=True
Encroach Param= -1, 0, 0, 0
BEGIN DESCRIPTION:
Multiple Run
END DESCRIPTION:

--- CERCEY BRANCH.f01 (steady flow) ---

Flow Title=Multiple
Number of Profiles=7
Profile Names=10-year,25-year,50-year,1pct_min,100-year,1pct_plu,500-year
River Rch & RM= CERCEY BRANCH,Reach-1,15307
    1668    2354    2935    2666    3606    4876    5428
River Rch & RM= CERCEY BRANCH,Reach-1,10781
    1946    2754    3440    3127    4229    5719    6376
River Rch & RM= CERCEY BRANCH,Reach-1,3153
    2359    3368    4231    3866    5228    7070    7965
Boundary for River Rch & Prof#=CERCEY BRANCH,Reach-1,1
Up Type=0
Dn Type=3
Dn Slope=0.005
Boundary for River Rch & Prof#=CERCEY BRANCH,Reach-1,2
Up Type=0
Dn Type=3
Dn Slope=0.005
Boundary for River Rch & Prof#=CERCEY BRANCH,Reach-1,3
Up Type=0
Dn Type=3
Dn Slope=0.005
Boundary for River Rch & Prof#=CERCEY BRANCH,Reach-1,4
Up Type=0
Dn Type=3
Dn Slope=0.005
Boundary for River Rch & Prof#=CERCEY BRANCH,Reach-1,5
Up Type=0
Dn Type=3
Dn Slope=0.005
Boundary for River Rch & Prof#=CERCEY BRANCH,Reach-1,6
Up Type=0
Dn Type=3
Dn Slope=0.005
Boundary for River Rch & Prof#=CERCEY BRANCH,Reach-1,7
Up Type=0
Dn Type=3
Dn Slope=0.005

--- CERCEY BRANCH.g01 (geometry) ---

Geom Title=Existing Conditions

River Reach=CERCEY BRANCH,Reach-1
Reach XY= 30
      3611390.93     10408420.58      3611409.25     10408673.57
      3611105.68     10409027.96      3610851.63     10409651.86
      3610607.47     10409708.79      3610411.39     10410231.35
      3609555.33     10410640.36      3609224.60     10411160.33
      3609323.56     10411323.52      3609219.17     10411603.25
      3609013.61     10411702.20      3608769.93     10412251.04
      3608566.48     10412278.92      3608278.57     10412847.97
      3607949.47     10412896.99      3607804.59     10413102.76
      3607754.14     10413646.17      3608011.73     10414007.67
      3607688.28     10414443.66      3607222.98     10414513.72
      3606406.64     10415294.64      3606082.85     10415181.79
      3605740.84     10415778.14      3605522.65     10415841.07
      3605222.11     10415711.64      3604925.81     10415980.08
      3604521.97     10415861.95      3603718.08     10415993.89
      3602959.51     10416287.10      3602472.11     10416781.64

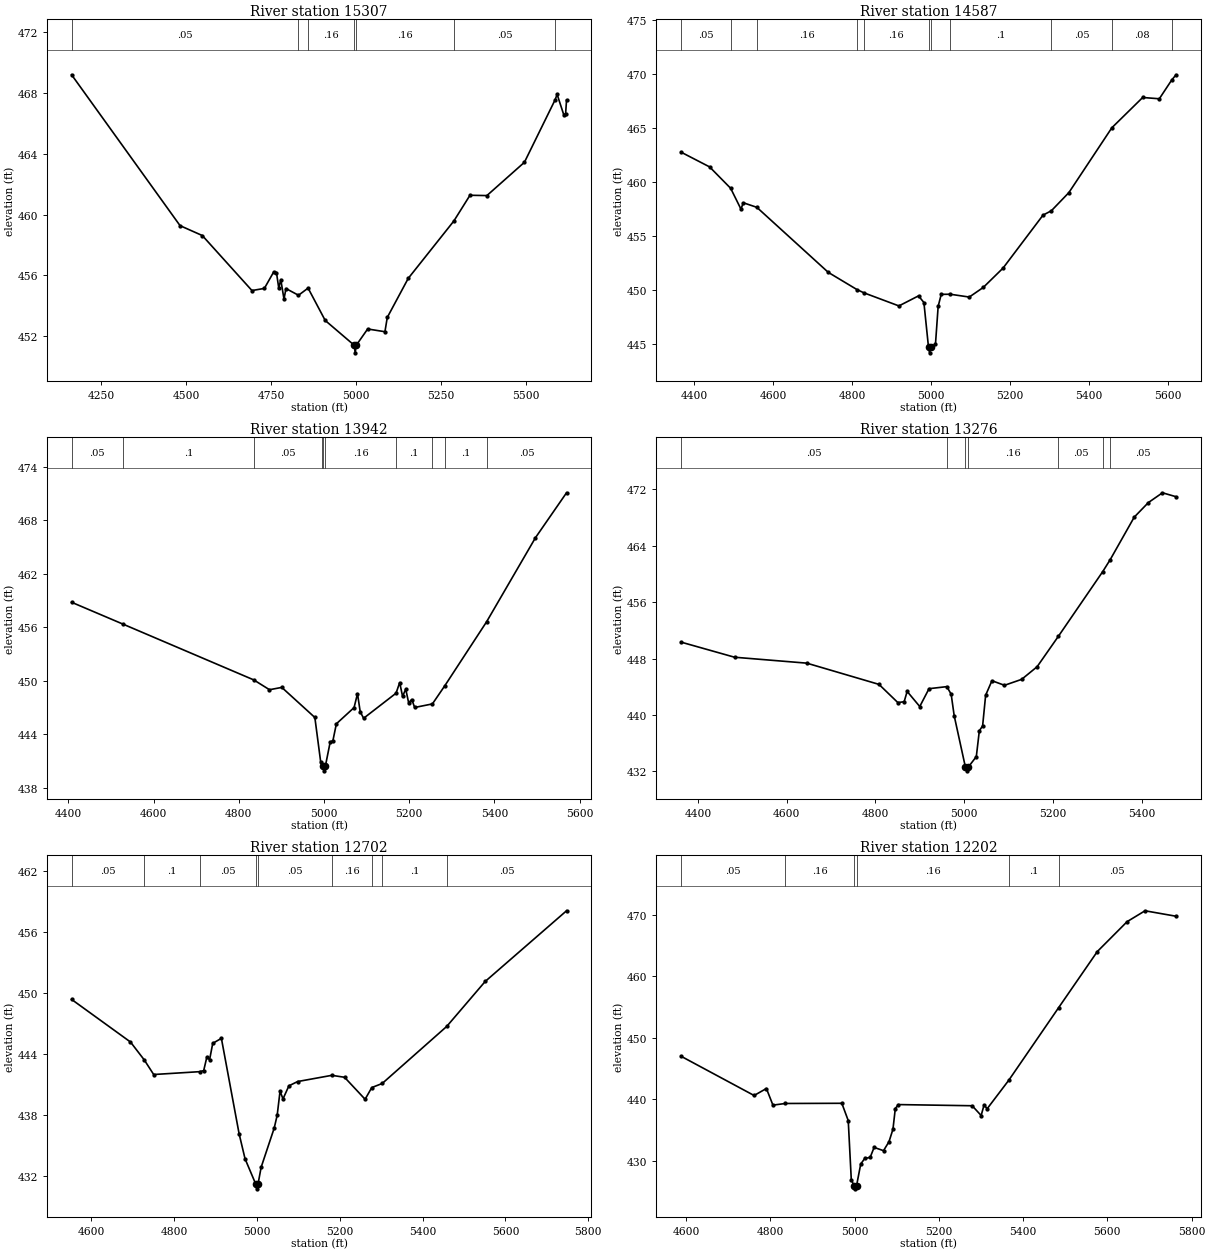
Type RM Length L Ch R = 1,15307,720,720,720
BEGIN DESCRIPTION:
CERCEY BRANCH 32.0
END DESCRIPTION:
XS GIS Cut Line= 3
      3610592.15     10408341.67      3611410.78     10408856.79
      3611868.07     10409028.27
#Sta/Elev= 30
  4163.2  469.20  4482.2  459.27  4547.6  458.62  4693.6  455.00  4730.1  455.14
  4757.2  456.21  4765.7  456.18  4772.5  455.16  4778.4  455.72  4787.8  454.44
  4793.7  455.13  4830.5  454.69  4858.7  455.16  4909.1  453.03  4994.4  451.40
  4997.2  450.90  5000.4  451.40  5033.9  452.47  5084.7  452.29  5091.6  453.23
  5153.2  455.80  5287.5  459.58  5334.8  461.27  5384.6  461.25  5494.9  463.44
  5584.7  467.53  5591.1  467.91  5610.6  466.57  5616.0  466.61  5618.8  467.53
#Mann=7,-1,0
  4163.2    0.05       0  4830.5    0.08       0  4858.7    0.16       0
  4994.4    0.07       0  5000.4    0.16       0  5287.5    0.05       0
  5584.7    0.08       0
Bank Sta=4994.4,5000.4
Exp/Cntr=0.3,0.1

Type RM Length L Ch R = 1,14587,645,645,645
BEGIN DESCRIPTION:
CERCEY BRANCH 30.0
END DESCRIPTION:
XS GIS Cut Line= 3
      3610468.11     10408924.52      3611153.56     10409430.18
      3611488.02     10409653.07
#Sta/Elev= 30
  4366.3  462.76  4438.4  461.40  4491.8  459.42  4517.8  457.50  4524.0  458.08
  4558.1  457.66  4739.2  451.64  4811.8  450.05  4829.4  449.75  4918.0  448.54
  4967.7  449.47  4981.3  448.85  4993.0  444.70  4995.7  444.20  4999.0  444.70
  5010.6  445.00  5017.4  448.50  5025.2  449.61  5048.2  449.62  5096.2  449.36
  5131.7  450.25  5181.8  452.04  5283.1  456.94  5304.1  457.34  5348.5  459.02
  5457.4  465.02  5535.5  467.82  5577.6  467.70  5609.1  469.44  5620.0  469.92
#Mann=11,-1,0
  4366.3    0.05       0  4491.8    0.08       0  4558.1    0.16       0
  4811.8    0.05       0  4829.4    0.16       0  4993.0    0.07       0
  4999.0    0.16       0  5048.2     0.1       0  5304.1    0.05       0
  5457.4    0.08       0  5609.1    0.05       0
Bank Sta=4993,4999
Exp/Cntr=0.3,0.1

Type RM Length L Ch R = 1,13942,666,666,666
BEGIN DESCRIPTION:
CERCEY BRANCH 29.0
END DESCRIPTION:
XS GIS Cut Line= 3
      3610155.59     10409325.55      3610745.23     10409795.81
      3611051.43     10410065.15
#Sta/Elev= 30
  4407.3  458.81  4528.0  456.36  4835.0  450.11  4871.9  449.01  4900.8  449.27
  4978.4  445.90  4992.0  440.95  4995.3  440.60  4997.0  440.42  4999.8  439.92
  5003.0  440.42  5014.4  443.15  5020.8  443.30  5028.9  445.19  5070.5  447.01
  5078.5  448.57  5084.9  446.54  5092.9  445.81  5169.0  448.62  5177.6  449.81
  5184.3  448.27  5191.8  449.07  5198.5  447.57  5206.1  447.91  5212.7  447.02
  5254.4  447.42  5283.7  449.47  5381.7  456.63  5496.4  466.05  5569.3  471.08
#Mann=10,-1,0
  4407.3    0.05       0  4528.0     0.1       0  4835.0    0.05       0
  4995.3    0.16       0  4997.0    0.07       0  5003.0    0.16       0
  5169.0     0.1       0  5254.4    0.05       0  5283.7     0.1       0
  5381.7    0.05       0
Bank Sta=4997,5003
Exp/Cntr=0.3,0.1

Type RM Length L Ch R = 1,13276,574,574,574
BEGIN DESCRIPTION:
CERCEY BRANCH 27.0
END DESCRIPTION:
XS GIS Cut Line= 3
      3609942.10     10409791.63      3610462.66     10410355.60
      3610790.96     10410471.36
#Sta/Elev= 30
  4362.2  450.34  4482.7  448.20  4645.5  447.36  4808.2  444.35  4850.7  441.77
  4864.9  441.89  4871.7  443.35  4900.1  441.21  4921.0  443.74  4961.1  444.03
  4970.9  442.96  4977.7  439.91  5003.1  432.59  5005.8  432.09  5009.1  432.59
  5027.6  434.11  5034.4  437.77  5041.8  438.46  5048.6  442.81  5062.8  444.87
  5091.1  444.22  5129.7  445.06  5164.6  446.85  5212.8  451.19  5312.5  460.34
  5329.5  462.05  5383.6  468.07  5415.4  470.13  5447.2  471.52  5477.8  470.96
#Mann=7,-1,0
  4362.2    0.05       0  4961.1    0.16       0  5003.1    0.07       0
  5009.1    0.16       0  5212.8    0.05       0  5312.5     0.1       0
  5329.5    0.05       0
Bank Sta=5003.1,5009.1
Exp/Cntr=0.3,0.1

Type RM Length L Ch R = 1,12702,500,500,500
BEGIN DESCRIPTION:
CERCEY BRANCH 26.0
END DESCRIPTION:
XS GIS Cut Line= 3
      3609592.08     10410091.61      3609892.11     10410441.64
      3610400.33     10410971.34
#Sta/Elev= 30
  4552.5  449.36  4694.7  445.18  4728.0  443.42  4750.7  441.99  4861.8  442.27
  4871.4  442.37  4879.1  443.70  4885.7  443.44  4893.3  445.05  4914.2  445.54
  4957.0  436.17  4971.3  433.72  4996.8  431.27  4999.5  430.77  5002.8  431.27
  5010.2  432.89  5041.7  436.73  5048.9  437.99  5055.8  440.35  5063.0  439.60
  5077.2  440.88  5098.3  441.30  5180.8  441.91  5211.5  441.72  5261.2  439.56
  5277.3  440.71  5302.5  441.11  5458.3  446.71  5551.1  451.12  5747.6  458.06
#Mann=9,-1,0
  4552.5    0.05       0  4728.0     0.1       0  4861.8    0.05       0
  4996.8    0.03       0  5002.8    0.05       0  5180.8    0.16       0
  5277.3    0.05       0  5302.5     0.1       0  5458.3    0.05       0
Bank Sta=4996.8,5002.8
Exp/Cntr=0.3,0.1

Type RM Length L Ch R = 1,12202,667,667,667
BEGIN DESCRIPTION:
CERCEY BRANCH 25.0
END DESCRIPTION:
XS GIS Cut Line= 3
      3609171.19     10410549.49      3609715.34     10410822.57
      3610115.33     10411222.56
#Sta/Elev= 30
  4588.5  446.99  4761.7  440.60  4790.9  441.74  4806.4  439.03  4835.9  439.30
  4969.9  439.33  4985.1  436.51  4992.3  426.91  4998.8  425.89  5001.6  425.39
  5004.8  425.89  5014.7  429.43  5024.2  430.34  5037.1  430.51  5046.5  432.14
  5068.8  431.61  5081.8  433.07  5091.2  435.10  5096.8  438.48  5104.2  439.12
  5279.2  438.93  5300.5  437.34  5307.5  439.08  5314.6  438.43  5366.2  443.10
  5484.5  454.93  5576.2  464.06  5646.9  468.93  5689.4  470.70  5763.0  469.81
#Mann=6,-1,0
  4588.5    0.05       0  4835.9    0.16       0  4998.8    0.07       0
  5004.8    0.16       0  5366.2     0.1       0  5484.5    0.05       0
Bank Sta=4998.8,5004.8
Exp/Cntr=0.3,0.1

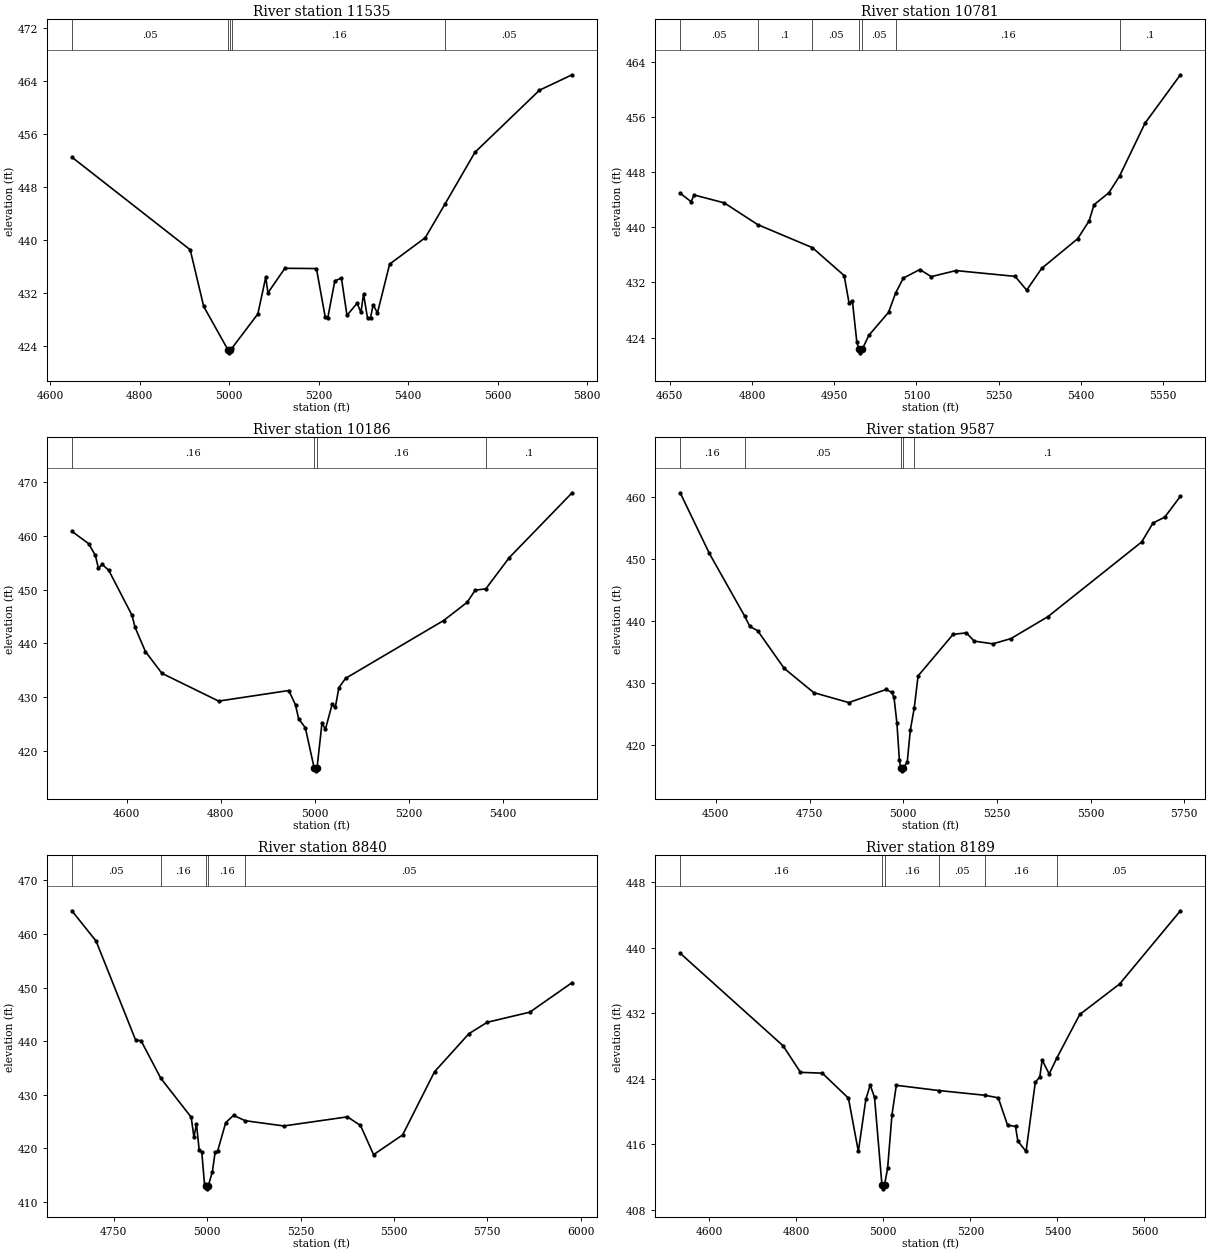
Type RM Length L Ch R = 1,11535,754,754,754
BEGIN DESCRIPTION:
CERCEY BRANCH 23.0
END DESCRIPTION:
XS GIS Cut Line= 3
      3608879.51     10411164.08      3609436.83     10411231.79
      3609914.64     10411517.44
#Sta/Elev= 30
  4648.6  452.53  4913.1  438.53  4943.3  429.96  4997.1  423.45  4999.9  422.95
  5003.1  423.45  5006.4  423.66  5064.2  428.82  5081.9  434.35  5086.9  432.02
  5124.7  435.73  5195.2  435.69  5214.9  428.35  5220.7  428.27  5236.3  433.83
  5251.1  434.25  5263.5  428.61  5286.1  430.45  5294.7  429.06  5300.5  431.84
  5309.4  428.20  5316.1  428.24  5321.9  430.22  5331.6  428.97  5358.8  436.36
  5438.6  440.36  5483.0  445.49  5549.5  453.26  5693.8  462.65  5766.7  464.98
#Mann=5,-1,0
  4648.6    0.05       0  4997.1    0.03       0  5003.1    0.05       0
  5006.4    0.16       0  5483.0    0.05       0
Bank Sta=4997.1,5003.1
Exp/Cntr=0.3,0.1

Type RM Length L Ch R = 1,10781,595,595,595
BEGIN DESCRIPTION:
CERCEY BRANCH 22.0
END DESCRIPTION:
XS GIS Cut Line= 3
      3608720.23     10411557.27      3608920.23     10411657.27
      3609492.14     10412041.67
#Sta/Elev= 30
  4668.9  444.95  4688.8  443.72  4694.4  444.69  4749.3  443.55  4810.4  440.39
  4910.1  437.05  4968.1  433.00  4977.1  428.99  4983.1  429.36  4991.2  423.35
  4995.1  422.28  4997.8  421.78  5001.1  422.28  5013.1  424.32  5049.1  427.66
  5061.9  430.44  5076.1  432.63  5106.1  433.87  5127.1  432.84  5171.9  433.72
  5280.0  432.88  5301.1  430.88  5328.5  434.04  5394.1  438.34  5415.1  440.94
  5424.0  443.28  5451.1  445.01  5470.6  447.44  5517.1  455.12  5581.6  462.14
#Mann=7,-1,0
  4668.9    0.05       0  4810.4     0.1       0  4910.1    0.05       0
  4995.1    0.03       0  5001.1    0.05       0  5061.9    0.16       0
  5470.6     0.1       0
Bank Sta=4995.1,5001.1
Exp/Cntr=0.3,0.1

Type RM Length L Ch R = 1,10186,599,599,599
BEGIN DESCRIPTION:
CERCEY BRANCH 20.0
END DESCRIPTION:
XS GIS Cut Line= 3
      3608392.08     10411891.62      3608855.65     10412296.85
      3609255.44     10412496.75
#Sta/Elev= 30
  4483.8  460.85  4519.4  458.55  4533.7  456.37  4540.3  453.94  4547.9  454.70
  4562.1  453.60  4611.5  445.23  4618.1  442.97  4640.0  438.48  4675.1  434.42
  4795.6  429.25  4944.7  431.22  4958.9  428.54  4965.5  425.96  4979.8  424.28
  4998.6  416.77  5001.4  416.27  5004.6  416.77  5015.1  425.14  5022.5  424.03
  5036.7  428.65  5043.4  428.06  5051.0  431.73  5065.2  433.48  5273.4  444.24
  5323.7  447.64  5340.5  449.89  5363.1  450.14  5413.1  455.96  5546.5  468.02
#Mann=4,-1,0
  4483.8    0.16       0  4998.6    0.07       0  5004.6    0.16       0
  5363.1     0.1       0
Bank Sta=4998.6,5004.6
Exp/Cntr=0.3,0.1

Type RM Length L Ch R = 1,9587,747,747,747
BEGIN DESCRIPTION:
CERCEY BRANCH 19.0
END DESCRIPTION:
XS GIS Cut Line= 3
      3607992.08     10412241.63      3608694.19     10412777.06
      3609145.12     10412809.91
#Sta/Elev= 30
  4404.7  460.66  4482.7  450.86  4576.6  440.77  4590.7  439.07  4611.5  438.39
  4682.3  432.31  4761.2  428.39  4854.7  426.78  4954.5  428.90  4969.0  428.43
  4975.3  427.68  4983.2  423.47  4989.8  417.50  4993.1  416.26  4995.9  415.76
  4999.1  416.26  5010.7  417.11  5018.9  422.31  5029.5  425.92  5039.7  431.09
  5133.2  437.80  5168.6  438.04  5189.4  436.71  5239.3  436.27  5287.3  437.11
  5385.8  440.64  5636.5  452.72  5666.6  455.77  5698.2  456.74  5739.8  460.09
#Mann=5,-1,0
  4404.7    0.16       0  4576.6    0.05       0  4993.1    0.03       0
  4999.1    0.05       0  5029.5     0.1       0
Bank Sta=4993.1,4999.1
Exp/Cntr=0.3,0.1

Type RM Length L Ch R = 1,8840,651,651,651
BEGIN DESCRIPTION:
CERCEY BRANCH 18.0
END DESCRIPTION:
XS GIS Cut Line= 3
      3607649.39     10412692.68      3608171.20     10413174.50
      3608642.09     10413591.62
#Sta/Elev= 30
  4637.6  464.31  4702.5  458.66  4808.5  440.17  4822.7  440.11  4875.6  433.10
  4957.1  425.83  4964.4  422.12  4971.2  424.57  4978.6  419.65  4985.4  419.37
  4992.8  413.30  4996.6  412.98  4999.3  412.48  5002.6  412.98  5013.8  415.67
  5021.1  419.29  5028.0  419.55  5049.5  424.82  5070.5  426.17  5101.8  425.18
  5204.9  424.20  5375.2  425.90  5410.3  424.30  5445.4  418.85  5523.2  422.54
  5608.5  434.30  5700.5  441.39  5749.8  443.53  5863.6  445.41  5976.9  450.92
#Mann=5,-1,0
  4637.6    0.05       0  4875.6    0.16       0  4996.6    0.07       0
  5002.6    0.16       0  5101.8    0.05       0
Bank Sta=4996.6,5002.6
Exp/Cntr=0.3,0.1

Type RM Length L Ch R = 1,8189,559,559,559
BEGIN DESCRIPTION:
CERCEY BRANCH 16.0
END DESCRIPTION:
XS GIS Cut Line= 3
      3607285.78     10413497.42      3607947.24     10413528.67
      3608405.58     10413695.33
#Sta/Elev= 30
  4532.9  439.31  4769.5  428.01  4809.5  424.77  4859.6  424.67  4919.7  421.62
  4942.5  415.12  4959.7  421.46  4969.7  423.23  4979.7  421.71  4996.7  411.05
  4999.5  410.55  5002.7  411.05  5009.8  413.06  5019.8  419.60  5029.8  423.19
  5127.4  422.55  5233.7  421.97  5264.1  421.66  5285.4  418.33  5303.8  418.16
  5309.1  416.39  5328.0  415.11  5349.2  423.54  5359.7  424.23  5365.0  426.27
  5381.2  424.57  5398.7  426.52  5451.4  431.83  5543.2  435.56  5682.8  444.49
#Mann=6,-1,0
  4532.9    0.16       0  4996.7    0.07       0  5002.7    0.16       0
  5127.4    0.05       0  5233.7    0.16       0  5398.7    0.05       0
Bank Sta=4996.7,5002.7
Exp/Cntr=0.3,0.1

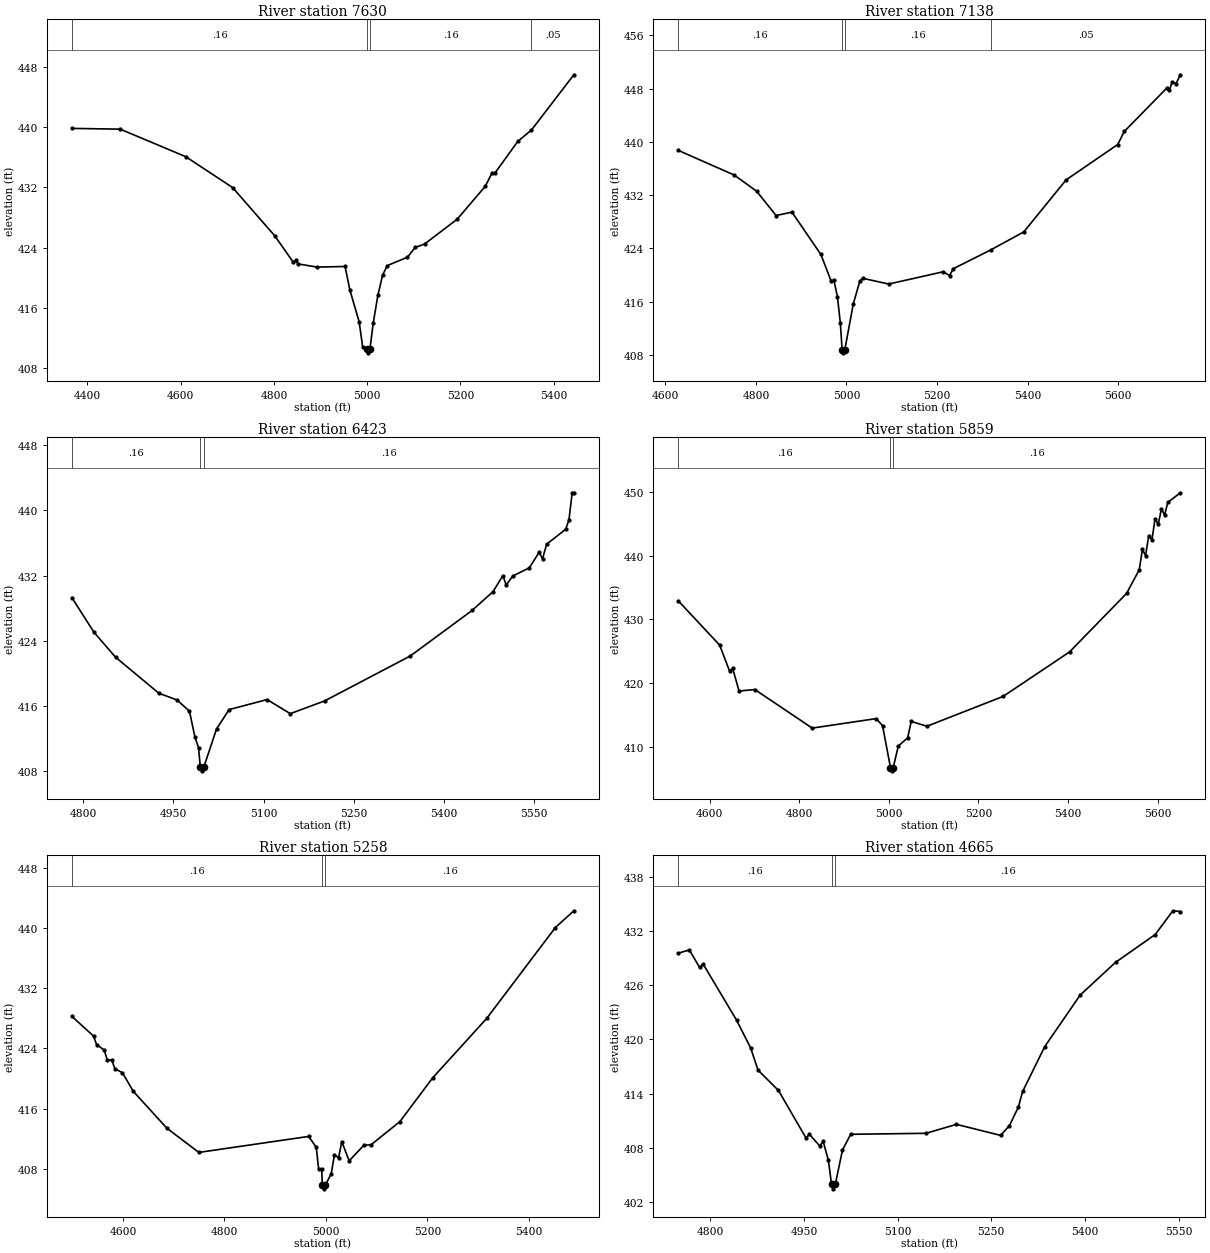
Type RM Length L Ch R = 1,7630,492,492,492
BEGIN DESCRIPTION:
CERCEY BRANCH 15.0
END DESCRIPTION:
XS GIS Cut Line= 3
      3607369.14     10413877.63      3607992.11     10413941.64
      3608441.99     10413966.16
#Sta/Elev= 30
  4366.7  439.83  4470.2  439.73  4610.9  436.08  4711.5  431.98  4801.9  425.58
  4841.7  422.07  4846.7  422.32  4852.2  421.86  4892.4  421.44  4952.7  421.52
  4962.8  418.44  4982.9  414.18  4990.4  410.85  5000.0  410.57  5002.7  410.07
  5006.0  410.57  5013.0  413.99  5023.0  417.68  5033.0  420.34  5043.0  421.63
  5086.5  422.75  5103.1  424.05  5123.1  424.49  5193.2  427.79  5253.3  432.14
  5268.5  433.98  5273.5  433.85  5323.4  438.12  5352.5  439.61  5443.5  446.94
#Mann=4,-1,0
  4366.7    0.16       0  5000.0    0.07       0  5006.0    0.16       0
  5352.5    0.05       0
Bank Sta=5000,5006
Exp/Cntr=0.3,0.1

Type RM Length L Ch R = 1,7138,715,715,715
BEGIN DESCRIPTION:
CERCEY BRANCH 14.0
END DESCRIPTION:
XS GIS Cut Line= 3
      3607431.61     10414028.66      3607858.70     10414382.83
      3608296.19     10414721.36
#Sta/Elev= 30
  4629.0  438.72  4752.1  435.03  4801.6  432.60  4844.6  428.95  4879.7  429.45
  4943.5  423.10  4965.7  419.18  4972.2  419.23  4980.0  416.78  4986.5  412.77
  4990.4  408.83  4993.1  408.33  4996.4  408.83  5015.2  415.72  5029.5  419.09
  5036.0  419.52  5093.3  418.66  5213.4  420.50  5227.6  419.94  5235.7  420.96
  5319.8  423.83  5391.5  426.49  5484.7  434.29  5598.8  439.61  5613.3  441.57
  5706.6  448.05  5712.9  447.76  5719.2  449.05  5727.4  448.73  5737.0  450.08
#Mann=4,-1,0
  4629.0    0.16       0  4990.4    0.07       0  4996.4    0.16       0
  5319.8    0.05       0
Bank Sta=4990.4,4996.4
Exp/Cntr=0.3,0.1

Type RM Length L Ch R = 1,6423,564,564,564
BEGIN DESCRIPTION:
CERCEY BRANCH 12.0
END DESCRIPTION:
XS GIS Cut Line= 3
      3607120.23     10414321.23      3607320.21     10414621.19
      3607542.09     10415041.62
#Sta/Elev= 30
  4780.9  429.27  4817.5  425.03  4853.5  421.96  4925.6  417.53  4955.6  416.71
  4976.6  415.33  4985.6  412.18  4991.7  410.83  4994.7  408.49  4997.5  407.99
  5000.7  408.49  5021.7  413.14  5042.7  415.52  5105.9  416.75  5144.5  415.02
  5201.6  416.58  5344.4  422.11  5447.2  427.70  5482.2  430.02  5498.5  431.98
  5504.2  430.83  5514.9  431.93  5542.6  432.94  5558.9  434.84  5564.6  434.07
  5571.6  435.86  5603.0  437.67  5608.6  438.82  5614.0  442.17  5616.8  442.17
#Mann=3,-1,0
  4780.9    0.16       0  4994.7    0.07       0  5000.7    0.16       0
Bank Sta=4994.7,5000.7
Exp/Cntr=0.3,0.1

Type RM Length L Ch R = 1,5859,601,601,601
BEGIN DESCRIPTION:
CERCEY BRANCH 11.0
END DESCRIPTION:
XS GIS Cut Line= 3
      3606592.10     10414541.63      3606937.94     10414976.36
      3607337.51     10415375.94
#Sta/Elev= 30
  4530.3  432.87  4622.4  425.94  4644.9  421.80  4651.2  422.34  4665.7  418.73
  4700.9  418.97  4829.0  412.91  4971.6  414.40  4986.0  413.31  5003.8  406.70
  5006.6  406.20  5009.8  406.70  5021.3  410.10  5042.1  411.38  5050.1  413.96
  5085.1  413.20  5255.1  417.88  5403.6  424.87  5530.9  434.06  5559.2  437.77
  5566.3  440.97  5573.3  440.00  5580.4  443.14  5587.5  442.43  5594.5  445.79
  5601.6  444.89  5608.7  447.35  5615.8  446.35  5622.8  448.34  5650.9  449.86
#Mann=3,-1,0
  4530.3    0.16       0  5003.8    0.07       0  5009.8    0.16       0
Bank Sta=5003.8,5009.8
Exp/Cntr=0.3,0.1

Type RM Length L Ch R = 1,5258,593,593,593
BEGIN DESCRIPTION:
CERCEY BRANCH 10.0
END DESCRIPTION:
XS GIS Cut Line= 3
      3606221.57     10414834.26      3606492.11     10415241.64
      3606792.09     10415641.62
#Sta/Elev= 30
  4499.5  428.27  4542.0  425.66  4548.0  424.53  4563.1  423.78  4569.1  422.49
  4578.1  422.44  4584.1  421.30  4599.1  420.77  4620.2  418.31  4686.3  413.40
  4749.5  410.16  4966.0  412.29  4981.0  410.83  4985.5  407.96  4991.7  407.96
  4992.8  405.81  4995.6  405.31  4998.8  405.81  5010.4  407.32  5016.7  409.82
  5025.0  409.47  5031.2  411.59  5045.8  409.04  5075.0  411.14  5088.5  411.16
  5145.8  414.27  5210.4  420.10  5316.7  428.00  5452.1  440.11  5488.5  442.34
#Mann=3,-1,0
  4499.5    0.16       0  4992.8    0.07       0  4998.8    0.16       0
Bank Sta=4992.8,4998.8
Exp/Cntr=0.3,0.1

Type RM Length L Ch R = 1,4665,439,439,439
BEGIN DESCRIPTION:
CERCEY BRANCH 9.0
END DESCRIPTION:
XS GIS Cut Line= 3
      3605929.86     10415049.46      3606117.38     10415403.67
      3606395.19     10415695.36
#Sta/Elev= 30
  4749.1  429.56  4766.6  429.91  4782.9  427.99  4788.6  428.36  4842.1  422.15
  4864.7  419.07  4876.6  416.60  4909.3  414.35  4953.3  409.10  4958.9  409.49
  4975.3  408.21  4980.9  408.71  4989.2  406.61  4994.3  403.96  4997.0  403.46
  5000.3  403.96  5011.8  407.76  5024.9  409.50  5145.6  409.61  5194.2  410.60
  5265.0  409.38  5279.1  410.46  5293.3  412.50  5300.2  414.24  5335.7  419.22
  5392.4  424.92  5449.0  428.54  5512.5  431.62  5540.8  434.25  5552.7  434.17
#Mann=3,-1,0
  4749.1    0.16       0  4994.3    0.07       0  5000.3    0.16       0
Bank Sta=4994.3,5000.3
Exp/Cntr=0.3,0.1

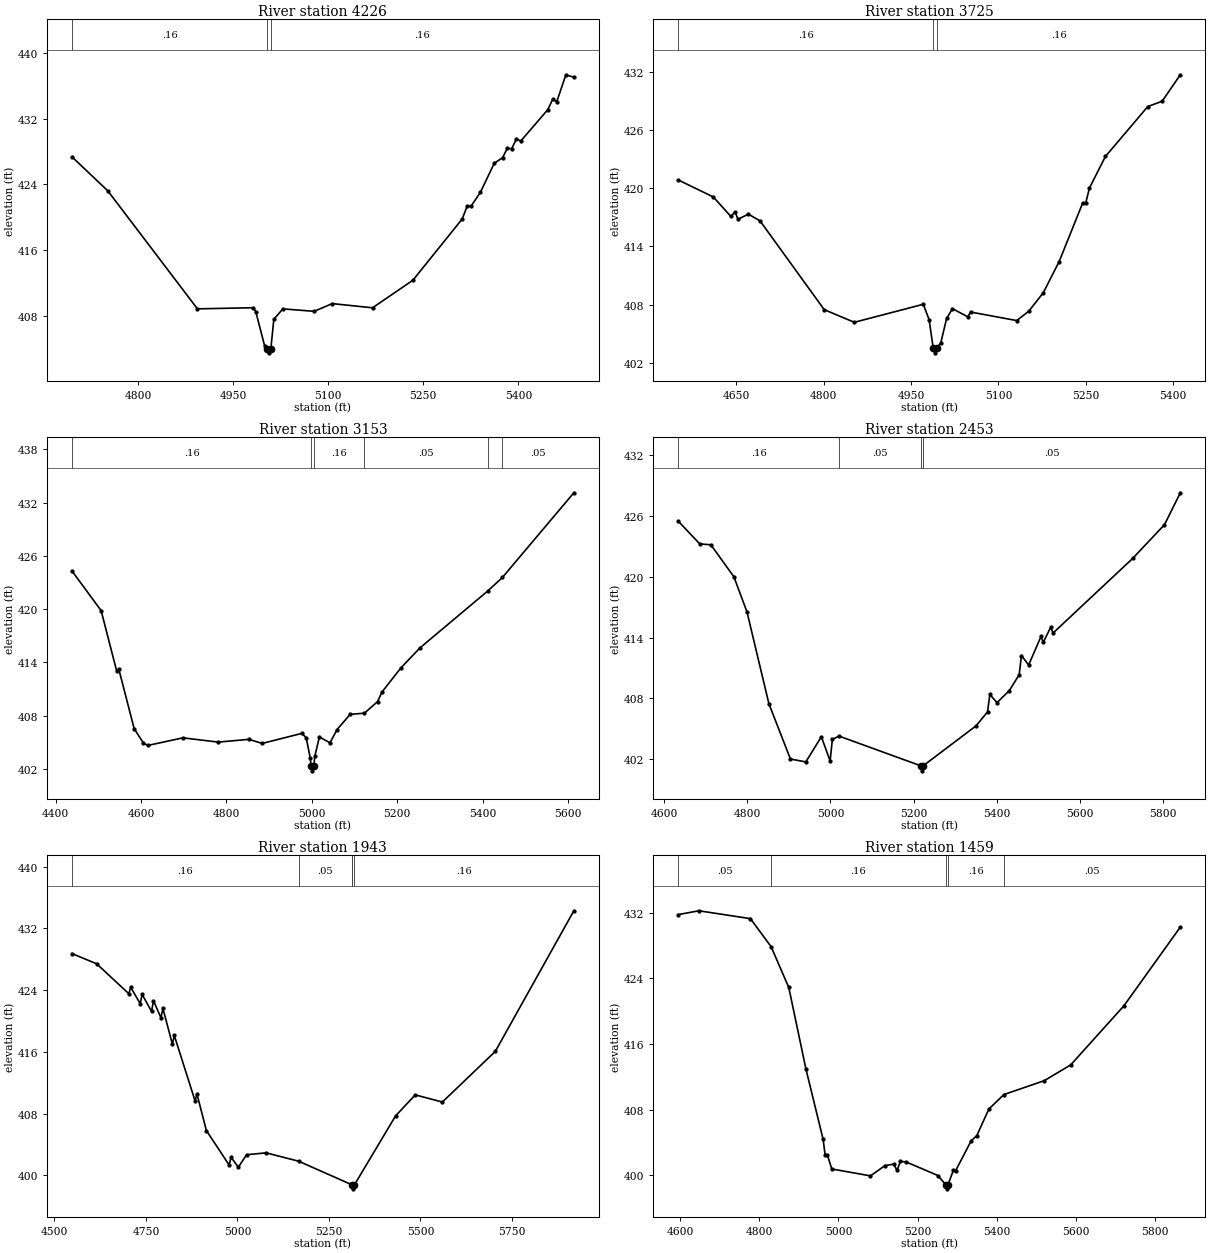
Type RM Length L Ch R = 1,4226,501,501,501
BEGIN DESCRIPTION:
CERCEY BRANCH 8.0
END DESCRIPTION:
XS GIS Cut Line= 3
      3605692.11     10415391.65      3605892.11     10415591.64
      3606277.12     10415924.51
#Sta/Elev= 30
  4695.7  427.37  4752.3  423.22  4893.7  408.84  4981.8  408.98  4985.7  408.50
  4999.9  404.26  5003.5  403.98  5006.3  403.48  5009.5  403.98  5014.2  407.57
  5028.4  408.84  5077.8  408.54  5106.3  409.48  5169.9  408.97  5233.6  412.33
  5311.5  419.81  5319.1  421.35  5325.7  421.39  5340.0  423.04  5361.9  426.58
  5375.1  427.27  5382.7  428.43  5389.3  428.34  5397.0  429.58  5403.6  429.28
  5446.4  433.12  5454.0  434.37  5460.6  434.10  5474.9  437.37  5487.5  437.07
#Mann=3,-1,0
  4695.7    0.16       0  5003.5    0.07       0  5009.5    0.16       0
Bank Sta=5003.5,5009.5
Exp/Cntr=0.3,0.1

Type RM Length L Ch R = 1,3725,572,572,572
BEGIN DESCRIPTION:
CERCEY BRANCH 7.0
END DESCRIPTION:
XS GIS Cut Line= 3
      3605542.10     10415391.67      3605513.22     10415966.17
      3605592.11     10416241.67
#Sta/Elev= 30
  4550.5  420.85  4610.5  419.10  4640.6  417.09  4647.8  417.57  4652.8  416.80
  4670.6  417.33  4690.6  416.64  4800.8  407.48  4852.5  406.17  4971.0  408.03
  4981.0  406.43  4988.0  403.52  4990.8  403.02  4994.0  403.52  5001.0  404.04
  5011.0  406.57  5021.1  407.58  5047.2  406.74  5052.2  407.23  5131.4  406.35
  5152.2  407.32  5177.2  409.24  5204.2  412.43  5244.7  418.49  5249.9  418.48
  5256.2  420.02  5283.7  423.28  5356.4  428.43  5381.1  428.98  5412.3  431.71
#Mann=3,-1,0
  4550.5    0.16       0  4988.0    0.07       0  4994.0    0.16       0
Bank Sta=4988,4994
Exp/Cntr=0.3,0.1

Type RM Length L Ch R = 1,3153,700,700,700
BEGIN DESCRIPTION:
CERCEY BRANCH 6.0
END DESCRIPTION:
XS GIS Cut Line= 3
      3604950.71     10415299.49      3605124.33     10415993.94
      3605332.67     10416403.69
#Sta/Elev= 30
  4438.2  424.31  4506.6  419.83  4542.7  413.07  4547.8  413.26  4583.9  406.53
  4605.3  404.92  4615.7  404.63  4698.1  405.49  4780.6  405.01  4852.7  405.32
  4883.7  404.86  4976.4  405.99  4986.7  405.52  4996.2  403.26  4998.4  402.27
  5001.1  401.77  5004.4  402.27  5007.3  403.47  5017.7  405.59  5042.6  404.93
  5058.9  406.41  5089.8  408.14  5123.2  408.27  5154.0  409.58  5164.2  410.65
  5208.7  413.38  5253.2  415.63  5412.3  422.06  5446.3  423.57  5613.7  433.12
#Mann=6,-1,0
  4438.2    0.16       0  4998.4    0.07       0  5004.4    0.16       0
  5123.2    0.05       0  5412.3    0.16       0  5446.3    0.05       0
Bank Sta=4998.4,5004.4
Exp/Cntr=0.3,0.1

Type RM Length L Ch R = 1,2453,510,510,510
BEGIN DESCRIPTION:
CERCEY BRANCH 5.0
END DESCRIPTION:
XS GIS Cut Line= 3
      3604402.12     10415514.81      3604624.33     10416195.33
      3604818.74     10416646.66
#Sta/Elev= 30
  4634.4  425.47  4685.8  423.24  4712.4  423.16  4767.8  420.00  4799.4  416.52
  4852.0  407.47  4903.8  402.01  4940.9  401.72  4978.2  404.21  4999.3  401.82
  5004.7  403.94  5020.7  404.27  5217.2  401.34  5219.9  400.84  5223.2  401.34
  5350.3  405.28  5378.0  406.66  5383.5  408.38  5400.7  407.57  5430.5  408.77
  5454.1  410.33  5459.5  412.22  5476.9  411.29  5506.6  414.11  5512.0  413.52
  5530.1  415.03  5535.5  414.44  5727.4  421.82  5803.6  425.14  5841.7  428.29
#Mann=4,-1,0
  4634.4    0.16       0  5020.7    0.05       0  5217.2    0.07       0
  5223.2    0.05       0
Bank Sta=5217.2,5223.2
Exp/Cntr=0.3,0.1

Type RM Length L Ch R = 1,1943,484,484,484
BEGIN DESCRIPTION:
CERCEY BRANCH 4.0
END DESCRIPTION:
XS GIS Cut Line= 3
      3603895.15     10415521.69      3604042.11     10415941.64
      3604374.31     10416806.41
#Sta/Elev= 30
  4548.0  428.73  4615.6  427.40  4703.4  423.53  4708.7  424.36  4734.5  422.24
  4739.8  423.43  4765.5  421.24  4770.8  422.62  4791.2  420.41  4796.5  421.63
  4822.3  417.01  4827.6  418.12  4884.3  409.67  4889.6  410.53  4915.3  405.81
  4977.4  401.35  4982.7  402.36  5002.6  401.06  5025.1  402.68  5078.6  402.92
  5167.2  401.84  5313.2  398.78  5313.6  398.76  5316.4  398.26  5319.6  398.76
  5432.1  407.70  5486.0  410.43  5560.0  409.50  5704.7  416.06  5919.3  434.27
#Mann=5,-1,0
  4548.0    0.16       0  5167.2    0.05       0  5313.2    0.16       0
  5313.6    0.07       0  5319.6    0.16       0
Bank Sta=5313.6,5319.6
Exp/Cntr=0.3,0.1

Type RM Length L Ch R = 1,1459,465,465,465
BEGIN DESCRIPTION:
CERCEY BRANCH 3.0
END DESCRIPTION:
XS GIS Cut Line= 3
      3603409.05     10415716.17      3603592.11     10416041.64
      3603992.13     10416841.69
#Sta/Elev= 30
  4595.9  431.79  4647.7  432.25  4777.8  431.29  4830.0  427.88  4874.7  422.90
  4918.0  412.97  4961.4  404.40  4966.5  402.51  4972.1  402.51  4983.3  400.78
  5081.1  399.94  5117.5  401.19  5139.8  401.37  5148.2  400.61  5156.6  401.70
  5170.6  401.65  5251.6  399.98  5271.0  398.86  5273.7  398.36  5277.0  398.86
  5290.8  400.67  5296.3  400.58  5335.5  404.22  5349.5  404.83  5380.2  408.09
  5418.1  409.85  5520.0  411.54  5587.0  413.47  5721.2  420.66  5863.8  430.26
#Mann=5,-1,0
  4595.9    0.05       0  4830.0    0.16       0  5271.0    0.07       0
  5277.0    0.16       0  5418.1    0.05       0
Bank Sta=5271,5277
Exp/Cntr=0.3,0.1

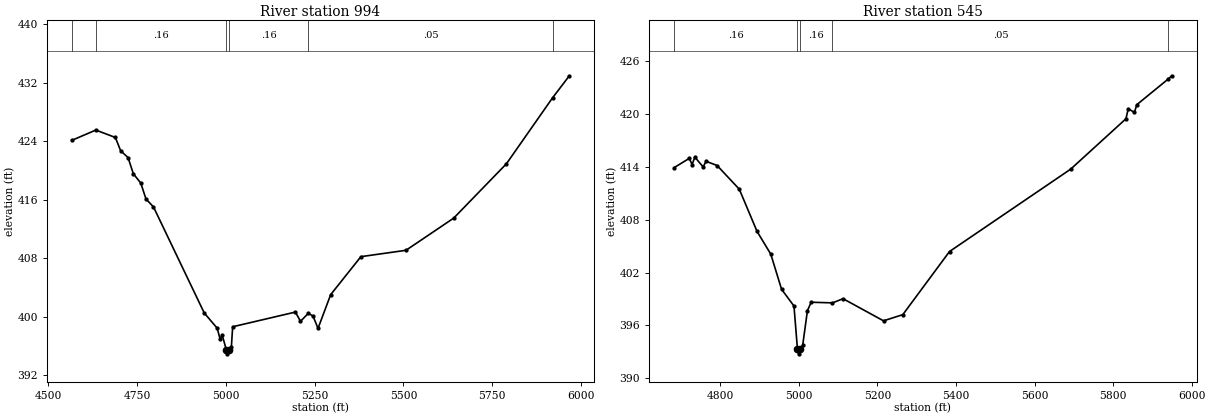
Type RM Length L Ch R = 1,994,449,449,449
BEGIN DESCRIPTION:
CERCEY BRANCH 2.0
END DESCRIPTION:
XS GIS Cut Line= 3
      3602936.80     10415875.85      3603192.11     10416241.64
      3603842.09     10416941.62
#Sta/Elev= 30
  4565.9  424.13  4633.7  425.54  4688.8  424.53  4703.6  422.72  4724.5  421.78
  4739.4  419.57  4760.3  418.30  4775.1  416.11  4796.1  415.04  4939.1  400.54
  4975.4  398.47  4983.6  397.00  4989.7  397.50  5001.6  395.46  5004.3  394.96
  5007.6  395.46  5015.4  395.86  5019.1  398.66  5195.9  400.67  5210.1  399.40
  5232.1  400.50  5245.3  400.13  5259.5  398.44  5295.1  403.05  5380.2  408.24
  5507.2  409.11  5641.6  413.51  5790.1  420.94  5919.8  429.94  5967.2  432.96
#Mann=6,-1,0
  4565.9    0.05       0  4633.7    0.16       0  5001.6    0.07       0
  5007.6    0.16       0  5232.1    0.05       0  5919.8    0.16       0
Bank Sta=5001.6,5007.6
Exp/Cntr=0.3,0.1

Type RM Length L Ch R = 1,545,0,0,0
BEGIN DESCRIPTION:
CERCEY BRANCH 1.0
END DESCRIPTION:
XS GIS Cut Line= 3
      3602571.00     10416228.24      3602721.00     10416378.23
      3603642.15     10416891.67
#Sta/Elev= 30
  4682.7  413.92  4721.2  414.97  4728.3  414.27  4735.4  415.11  4756.6  413.99
  4763.7  414.64  4792.0  414.16  4848.5  411.47  4893.7  406.67  4928.7  404.09
  4956.1  400.10  4987.7  398.20  4996.6  393.27  4999.3  392.77  5002.6  393.27
  5009.8  393.72  5022.0  397.69  5031.5  398.63  5085.7  398.56  5112.7  399.03
  5215.6  396.52  5264.7  397.22  5383.6  404.39  5692.2  413.75  5832.8  419.47
  5838.5  420.59  5854.5  420.20  5860.2  421.06  5940.6  423.99  5949.4  424.35
#Mann=5,-1,0
  4682.7    0.16       0  4996.6    0.07       0  5002.6    0.16       0
  5085.7    0.05       0  5940.6    0.16       0
Bank Sta=4996.6,5002.6
Exp/Cntr=0.3,0.1

Chan Stop Cuts=-1