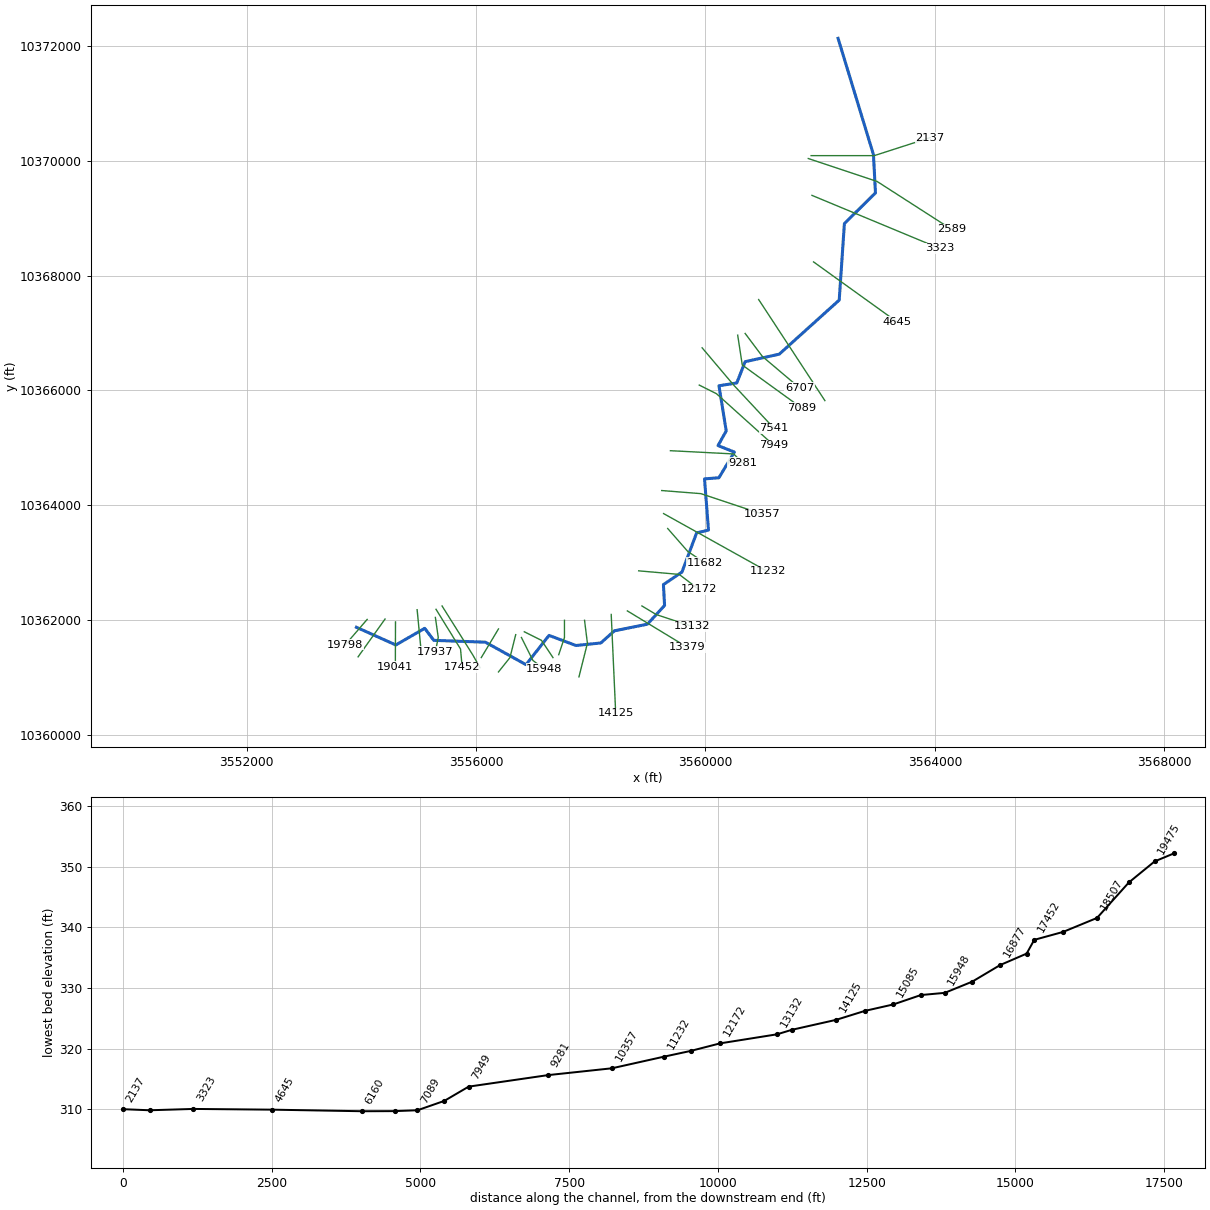
--- COBB BRANCH 1.prj (project) ---

Proj Title=COBB BRANCH 1 Base Level Engineering
Current Plan=p01
Default Exp/Contr=0.3,0.1
English Units
Geom File=g01
Flow File=f01
Plan File=p01
Y Axis Title=Elevation
X Axis Title(PF)=Main Channel Distance
X Axis Title(XS)=Station
BEGIN DESCRIPTION:
COBB BRANCH 1
END DESCRIPTION:
DSS Export Rating Curves= 0
DSS Export Rating Curve Sorted= 0
DSS Export Volume Flow Curves= 0
DXF OffsetX= 0
DXF OffsetY= 0
DXF ScaleX= 1
DXF ScaleY= 10

--- COBB BRANCH 1.p01 (plan) ---

Plan Title=Multiple Run
Short Identifier=Multiple
Geom File=g01
Flow File=f01
Subcritical Flow
K Sum by GR= 0
Std Step Tol= 0.01
Critical Tol= 0.01
Num of Std Step Trials= 20
Max Error Tol= 0.3
Flow Tol Ratio= 0.001
Split Flow NTrial= 30
Split Flow Tol= 0.02
Split Flow Ratio= 0.02
Log Output Level= 0
Friction Slope Method= 1
Unsteady Friction Slope Method= 2
Unsteady Bridges Friction Slope Method= 1
Parabolic Critical Depth
Global Vel Dist=  1 , 1 , 1
Global Log Level= 0
CheckData=True
Encroach Param= -1, 0, 0, 0
BEGIN DESCRIPTION:
Multiple Run
END DESCRIPTION:

--- COBB BRANCH 1.f01 (steady flow) ---

Flow Title=Multiple
Program Version=4.10
Number of Profiles= 7
Profile Names=10-year,25-year,50-year,1pct_min,100-year,1pct_plu,500-year
River Rch & RM=COBB BRANCH 1,Reach-1         ,19798
    1564    2225    2788    2548    3446    4661    5252
River Rch & RM=COBB BRANCH 1,Reach-1         ,17937
    1564    2225    2788    2548    3446    4661    5252
River Rch & RM=COBB BRANCH 1,Reach-1         ,15948
    2838    4140    5278    4895    6620    8953   10397
River Rch & RM=COBB BRANCH 1,Reach-1         ,9281
    2955    4291    5450    5033    6807    9205   10600
River Rch & RM=COBB BRANCH 1,Reach-1         ,2589
    3002    4351    5519    5088    6881    9306   10681
Boundary for River Rch & Prof#=COBB BRANCH 1,Reach-1         , 1
Up Type= 0
Dn Type= 3
Dn Slope=0.005
Boundary for River Rch & Prof#=COBB BRANCH 1,Reach-1         , 2
Up Type= 0
Dn Type= 3
Dn Slope=0.005
Boundary for River Rch & Prof#=COBB BRANCH 1,Reach-1         , 3
Up Type= 0
Dn Type= 3
Dn Slope=0.005
Boundary for River Rch & Prof#=COBB BRANCH 1,Reach-1         , 4
Up Type= 0
Dn Type= 3
Dn Slope=0.005
Boundary for River Rch & Prof#=COBB BRANCH 1,Reach-1         , 5
Up Type= 0
Dn Type= 3
Dn Slope=0.005
Boundary for River Rch & Prof#=COBB BRANCH 1,Reach-1         , 6
Up Type= 0
Dn Type= 3
Dn Slope=0.005
Boundary for River Rch & Prof#=COBB BRANCH 1,Reach-1         , 7
Up Type= 0
Dn Type= 3
Dn Slope=0.005
DSS Import GetInterval= 0
DSS Import GetPeak= 0
DSS Import FillOption= 0

--- COBB BRANCH 1.g01 (geometry) ---

Geom Title=Existing Conditions
Program Version=4.10

River Reach=COBB BRANCH 1   ,Reach-1
Reach XY= 30
       3553916.1     10361869.74      3554602.56     10361561.57
      3555106.03     10361851.85      3555264.36     10361642.12
      3556164.27     10361610.11      3556871.83     10361218.01
      3557273.37     10361728.58      3557741.44     10361552.51
      3558175.47     10361596.37      3558413.35     10361808.47
      3558988.85     10361923.94      3559287.19     10362249.99
      3559267.38     10362614.18      3559590.03      10362832.3
      3559845.78     10363514.87      3560052.81     10363563.48
      3559983.66     10364457.05      3560234.37     10364476.43
      3560504.16     10364924.34      3560219.26     10365037.36
      3560361.97     10365292.57      3560235.41     10366080.07
      3560545.78     10366128.81      3560692.34     10366500.17
      3561286.09     10366630.55      3562331.64     10367573.34
      3562421.91     10368906.68      3562963.58      10369441.4
      3562928.86     10370108.07      3562311.56     10372136.44

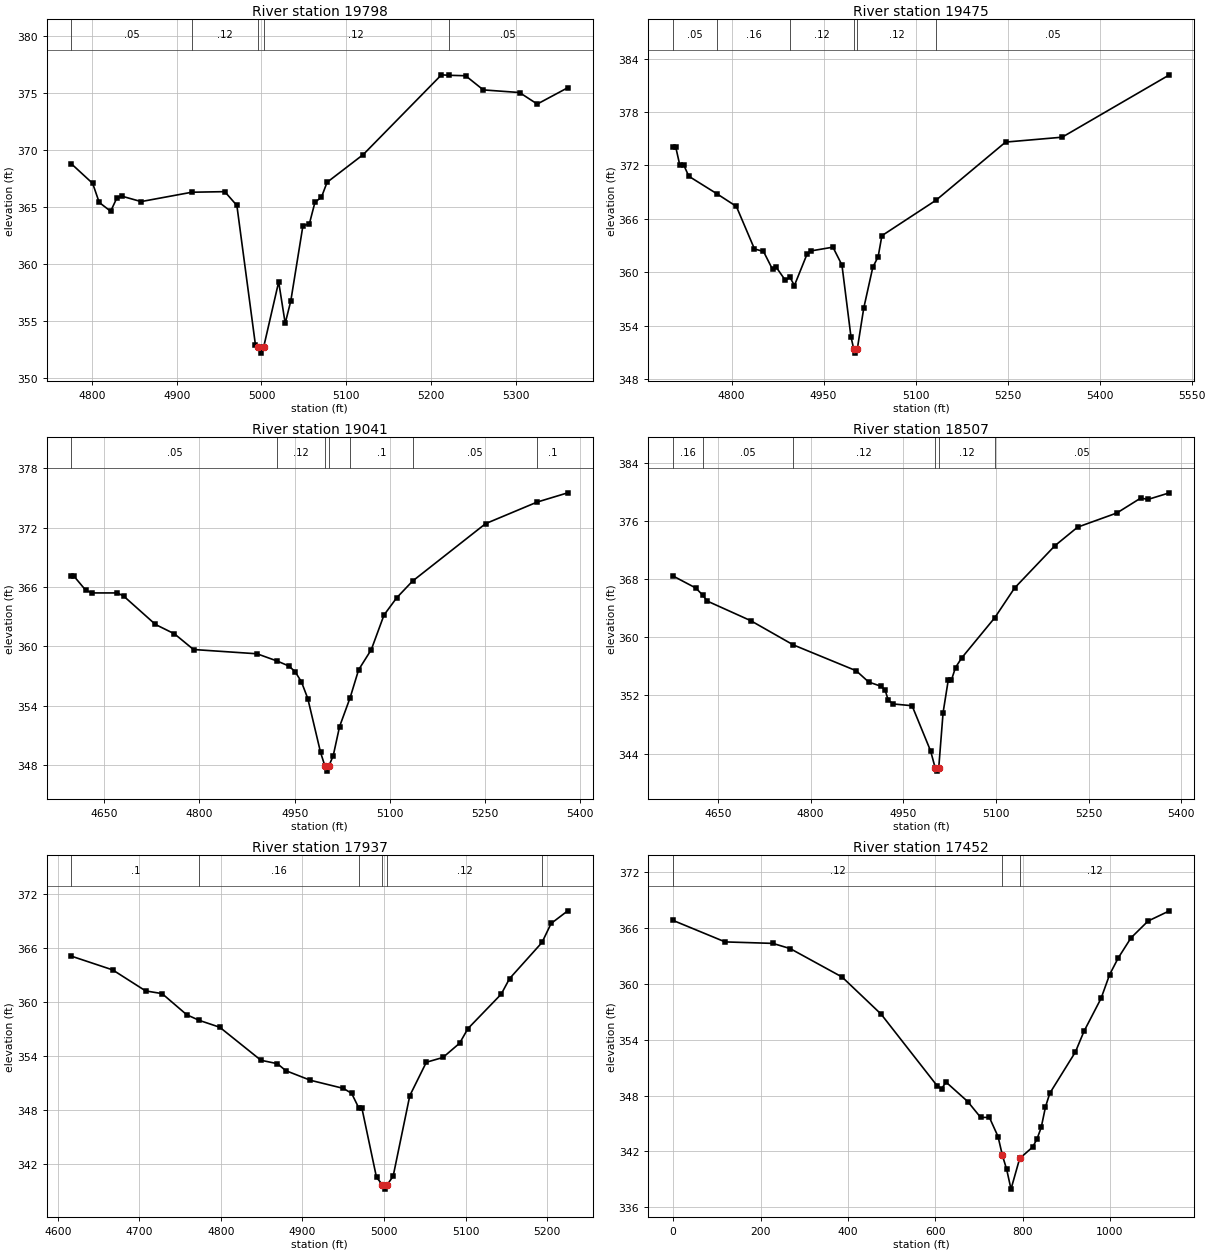
Type RM Length L Ch R = 1 ,19798   ,323,323,323
BEGIN DESCRIPTION:
Mapping XS c39efd71
END DESCRIPTION:
XS GIS Cut Line= 2
      3554102.53     10362006.65      3553720.09     10361563.45
#Sta/Elev= 30
  4775.9  368.79  4800.9  367.08  4808.6  365.42  4822.1  364.64  4829.4   365.8
    4836  365.95    4858  365.49  4917.9  366.31  4956.7  366.36    4971  365.15
  4992.9  352.93  4996.5  352.72  4999.2  352.22  5002.5  352.72  5020.3  358.46
    5028  354.83  5034.6  356.79  5048.9  363.37  5056.5  363.54  5063.1  365.43
  5070.8  365.88  5077.4  367.18  5120.1  369.61  5212.3  376.59  5220.9  376.55
  5240.8  376.51  5261.7  375.27  5304.4  375.04  5325.3  374.03  5361.3  375.46
#Mann= 5 ,-1 , 0
  4775.9     .05       0  4917.9     .12       0  4996.5     .07       0
  5002.5     .12       0  5220.9     .05       0
Bank Sta=4996.5,5002.5
XS Rating Curve= 0 ,0
Exp/Cntr=0.3,0.1

Type RM Length L Ch R = 1 ,19475   ,434,434,434
BEGIN DESCRIPTION:
Mapping XS 85ca5548
END DESCRIPTION:
XS GIS Cut Line= 2
      3554414.66     10362013.61      3553944.89     10361355.11
#Sta/Elev= 30
  4704.9  374.02  4709.2  374.02  4715.7  372.03  4721.8  372.09  4730.4  370.78
  4776.2  368.81  4807.9  367.39  4837.4  362.61  4852.1  362.33  4866.9  360.31
    4873  360.54  4887.8  359.08  4895.3  359.42  4902.5   358.5  4923.4  362.08
  4929.6  362.39  4965.3  362.81    4980   360.8  4994.7  352.73  4999.1   351.4
  5001.9   350.9  5005.1   351.4  5015.6  355.99  5030.3  360.55    5039  361.74
  5045.1   364.1  5133.4  368.09  5246.7  374.62  5338.9  375.17  5513.8  382.18
#Mann= 6 ,-1 , 0
  4704.9     .05       0  4776.2     .16       0  4895.3     .12       0
  4999.1     .07       0  5005.1     .12       0  5133.4     .05       0
Bank Sta=4999.1,5005.1
XS Rating Curve= 0 ,0
Exp/Cntr=0.3,0.1

Type RM Length L Ch R = 1 ,19041   ,534,534,534
BEGIN DESCRIPTION:
Mapping XS 46732714
END DESCRIPTION:
XS GIS Cut Line= 2
      3554596.92     10361963.85      3554594.16     10361182.25
#Sta/Elev= 30
  4598.5  367.11  4602.1  367.11  4620.7  365.69  4630.7   365.4  4670.7   365.4
  4680.7  365.08  4730.7  362.22  4760.7  361.27  4790.7  359.69  4890.7  359.26
  4922.8  358.52  4940.7  358.03  4950.7  357.46  4960.7  356.42  4970.7  354.74
  4990.7  349.33  4997.7  347.92  5000.5  347.42  5003.7  347.92  5010.7  348.97
  5020.7  351.91  5037.4  354.84  5050.7  357.64  5070.7  359.68  5090.7  363.17
  5110.7  364.91  5135.6  366.59  5250.7  372.39    5332  374.57  5380.1   375.5
#Mann= 7 ,-1 , 0
  4598.5     .05       0  4922.8     .12       0  4997.7     .07       0
  5003.7     .12       0  5037.4      .1       0  5135.6     .05       0
    5332      .1       0
Bank Sta=4997.7,5003.7
XS Rating Curve= 0 ,0
Exp/Cntr=0.3,0.1

Type RM Length L Ch R = 1 ,18507   ,570,570,570
BEGIN DESCRIPTION:
Mapping XS 4d7b2d6b
END DESCRIPTION:
XS GIS Cut Line= 2
       3554973.9     10362176.55      3555051.23     10361376.98
#Sta/Elev= 30
  4577.5  368.47  4614.2  366.82  4625.1  365.86  4632.7  365.02    4703  362.32
  4771.9  358.98  4873.8  355.41  4893.9  353.86    4914  353.27  4920.7   352.7
  4925.7  351.34  4934.1  350.83  4964.2  350.59  4994.3  344.33  5001.4  342.07
  5004.1  341.57  5007.4  342.07  5014.4  349.64  5022.9   354.2  5027.9  354.13
  5034.5  355.86  5044.6  357.19    5098  362.72  5130.1  366.82  5195.3  372.65
  5232.2  375.22  5295.7  377.17  5334.4  379.23    5346  379.04  5380.8  379.95
#Mann= 6 ,-1 , 0
  4577.5     .16       0  4625.1     .05       0  4771.9     .12       0
  5001.4     .07       0  5007.4     .12       0    5098     .05       0
Bank Sta=5001.4,5007.4
XS Rating Curve= 0 ,0
Exp/Cntr=0.3,0.1

Type RM Length L Ch R = 1 ,17937   ,485,485,485
BEGIN DESCRIPTION:
COBB BRANCH 1 39.0
END DESCRIPTION:
XS GIS Cut Line= 3
       3555292.1     10362041.65      3555342.11     10361691.64
      3555292.11     10361441.66
#Sta/Elev= 30
  4616.8  365.09  4667.3  363.57  4707.7  361.24  4727.9  360.94  4758.2  358.59
  4773.6  357.97  4798.6  357.21  4849.1  353.55  4869.3  353.17  4879.5   352.4
  4909.8  351.33  4950.2  350.43  4960.3  349.88  4969.2  348.24  4972.9  348.24
  4990.8  340.56    4998  339.76  5000.7  339.26    5004  339.76  5011.2  340.69
  5031.6  349.62  5051.9  353.33  5072.3  353.86  5092.7  355.44  5102.9  357.06
  5143.7  360.88  5153.9   362.6  5193.7  366.61  5204.9  368.72  5225.3  370.12
#Mann= 6 ,-1 , 0
  4616.8      .1       0  4773.6     .16       0  4969.2     .12       0
    4998     .07       0    5004     .12       0  5193.7     .05       0
Bank Sta=4998,5004
XS Rating Curve= 0 ,0
Exp/Cntr=0.3,0.1

Type RM Length L Ch R = 1 ,17452   ,128,128,128
XS GIS Cut Line= 3
     3555303.389    10362183.479     3555730.472     10361490.77
     3555759.118    10361175.666
#Sta/Elev= 30
       0366.8129119.0122364.5099228.1068364.3511267.7775363.7946386.7898360.7363
 476.049356.7523604.9789 349.019614.8965348.7562624.8143349.4459674.4027347.3611
704.1558345.6478723.9911345.6629743.8265343.6048753.7442341.5959763.6619340.0613
773.5795337.9511793.4149341.2437 823.168342.4737832.9553343.3217842.7426344.5788
852.5299346.7839862.3172348.2464 921.041 352.684940.6156354.8991979.7648358.4423
999.3394360.99521018.914362.77121048.276 364.9421087.425366.75161136.362367.8487
#Mann= 3 , 0 , 0
       0     .12       0753.7442     .07       0793.4149     .12       0
Bank Sta=753.7442,793.4149
XS Rating Curve= 0 ,0
Exp/Cntr=0.3,0.1

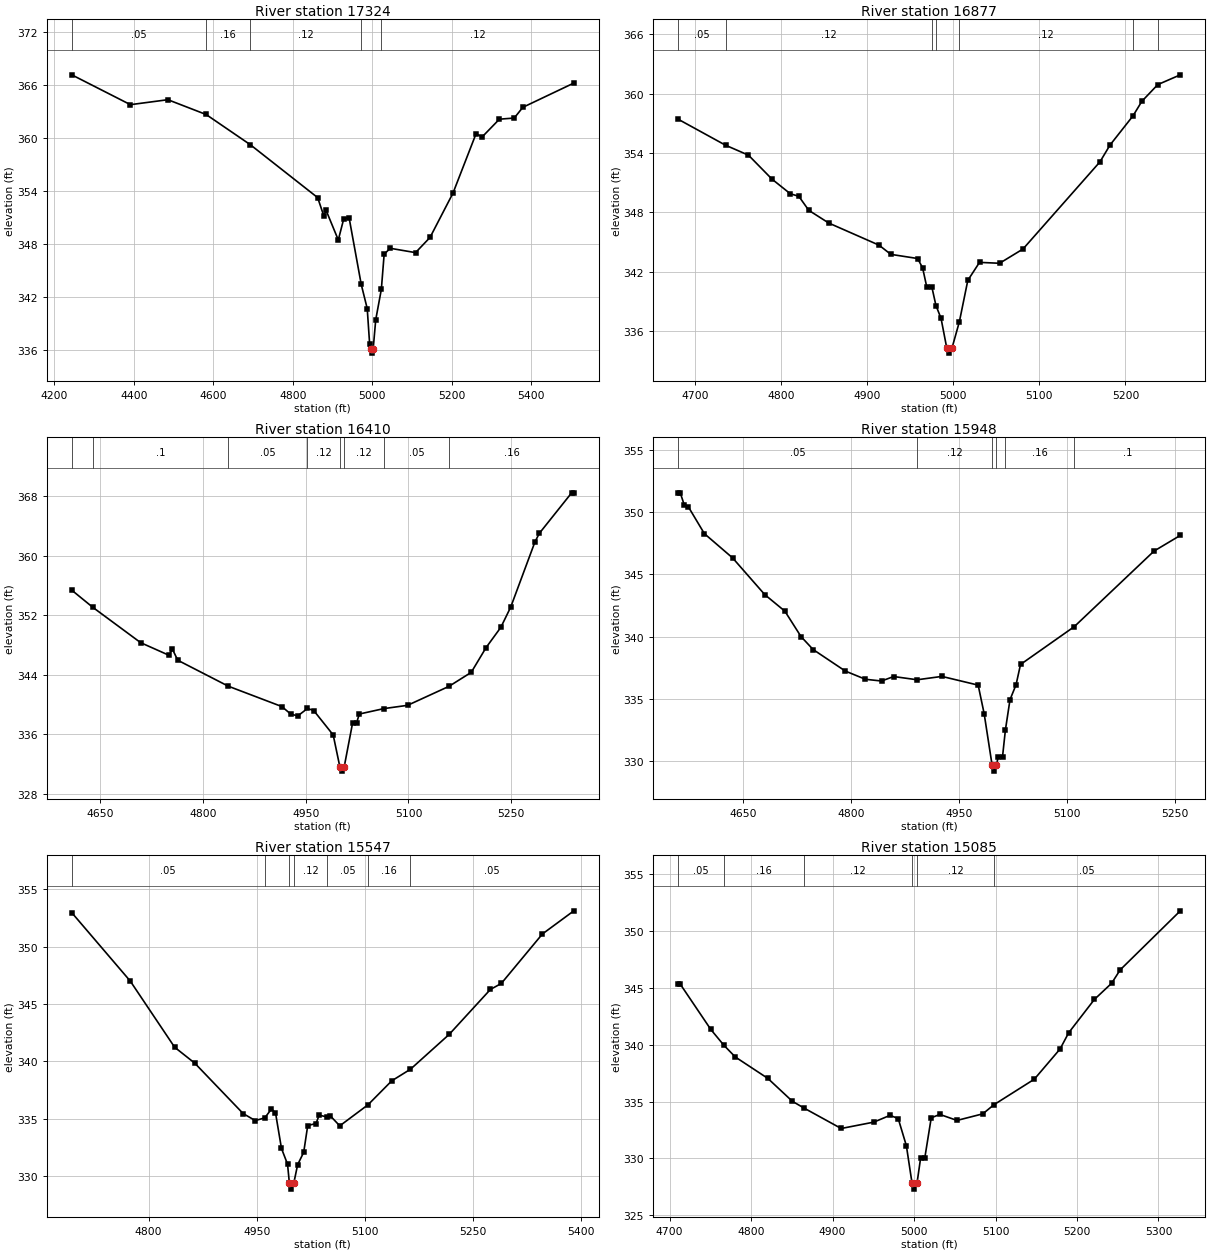
Type RM Length L Ch R = 1 ,17324   ,447,447,447
BEGIN DESCRIPTION:
Mapping XS ec252a37
END DESCRIPTION:
XS GIS Cut Line= 3
      3555408.63      10362241.6      3555943.37     10361389.15
       3556071.4     10361165.95
#Sta/Elev= 30
  4243.5  367.11  4391.1  363.74  4485.4   364.3  4581.6  362.63  4692.8  359.22
  4862.4  353.24  4877.7  351.19  4883.6   351.8  4914.3  348.46  4928.1  350.87
  4941.4  350.99    4972  343.44  4987.1  340.71  4993.2  336.67  4996.1  336.18
  4998.9  335.68  5002.1  336.18  5008.5  339.45  5022.6  342.88  5029.7  346.86
    5045  347.52  5108.7  347.03  5145.2  348.75  5202.9  353.75  5260.8  360.44
  5276.6  360.11  5319.7   362.1  5357.1  362.23  5378.7  363.44  5507.1  366.18
#Mann= 5 ,-1 , 0
  4243.5     .05       0  4581.6     .16       0  4692.8     .12       0
    4972     .07       0  5022.6     .12       0
Bank Sta=4996.1,5002.1
XS Rating Curve= 0 ,0
Exp/Cntr=0.3,0.1

Type RM Length L Ch R = 1 ,16877   ,467,467,467
BEGIN DESCRIPTION:
COBB BRANCH 1 37.0
END DESCRIPTION:
XS GIS Cut Line= 3
      3556392.11     10361841.65      3556242.11     10361591.64
      3556092.11     10361341.65
#Sta/Elev= 30
  4680.7  357.41  4735.6  354.79  4762.3  353.78  4789.6  351.36  4810.9  349.88
  4820.7  349.63  4832.3  348.21  4855.6  346.92  4913.9  344.69  4927.6  343.76
  4958.7  343.34  4964.5   342.4  4969.3  340.48  4975.2  340.48    4980  338.59
  4985.9   337.3  4992.6  334.28  4995.3  333.78  4998.6  334.28  5007.2  336.95
    5017  341.13  5030.6  342.95  5053.9  342.86  5081.1   344.3  5170.5  353.11
  5182.2  354.81  5208.9  357.76  5219.1  359.22  5237.6  360.91  5263.8   361.9
#Mann= 7 ,-1 , 0
  4680.7     .05       0  4735.6     .12       0  4975.2     .05       0
    4980     .07       0  5007.2     .12       0  5208.9     .16       0
  5237.6     .05       0
Bank Sta=4992.6,4998.6
XS Rating Curve= 0 ,0
Exp/Cntr=0.3,0.1

Type RM Length L Ch R = 1 ,16410   ,462,462,462
BEGIN DESCRIPTION:
COBB BRANCH 1 36.0
END DESCRIPTION:
XS GIS Cut Line= 3
       3556692.1     10361741.63      3556592.11     10361341.64
      3556392.08      10361091.6
#Sta/Elev= 30
  4608.8  355.36  4639.6  353.05  4709.3  348.31  4750.5  346.62  4755.7  347.43
  4763.4  345.95  4837.2  342.46  4915.4  339.72  4928.3  338.71  4938.6  338.47
  4952.7  339.47  4961.8  339.19  4990.2  335.91  5000.1  331.55  5002.8  331.05
  5006.1  331.55  5018.5  337.52  5024.3  337.52  5028.3  338.72  5064.1  339.45
  5098.7  339.89  5159.1  342.44  5191.6  344.32  5213.2  347.64  5234.8  350.37
  5249.2  353.09  5284.4  361.81  5290.8  362.98  5338.1  368.44  5341.3  368.44
#Mann= 8 ,-1 , 0
  4608.8     .05       0  4639.6      .1       0  4837.2     .05       0
  4952.7     .12       0  5000.1     .07       0  5006.1     .12       0
  5064.1     .05       0  5159.1     .16       0
Bank Sta=5000.1,5006.1
XS Rating Curve= 0 ,0
Exp/Cntr=0.3,0.1

Type RM Length L Ch R = 1 ,15948   ,401,401,401
BEGIN DESCRIPTION:
COBB BRANCH 1 35.0
END DESCRIPTION:
XS GIS Cut Line= 3
      3556792.11     10361691.63      3556992.11     10361291.64
       3557192.1     10361141.64
#Sta/Elev= 30
  4559.9  351.56  4562.7  351.56  4568.3  350.58  4573.9  350.44  4596.2  348.28
  4635.4  346.33  4680.1  343.38    4708  342.05  4730.4  340.01  4747.2  338.97
  4791.9  337.24  4819.8  336.58  4842.2  336.44    4859   336.8  4891.7  336.54
    4926  336.81  4976.4  336.11  4984.7  333.82  4995.7   329.7  4998.5   329.2
  5001.7   329.7  5004.3  330.35  5010.2  330.35  5014.2   332.5  5020.6  334.94
    5029  336.14  5035.2  337.77  5109.9  340.81  5220.6  346.88  5257.1  348.14
#Mann= 6 ,-1 , 0
  4559.9     .05       0  4891.7     .12       0  4995.7     .07       0
  5001.7     .12       0  5014.2     .16       0  5109.9      .1       0
Bank Sta=4995.7,5001.7
XS Rating Curve= 0 ,0
Exp/Cntr=0.3,0.1

Type RM Length L Ch R = 1 ,15547   ,462,462,462
BEGIN DESCRIPTION:
COBB BRANCH 1 34.0
END DESCRIPTION:
XS GIS Cut Line= 3
      3556842.06     10361791.66      3557142.11     10361641.64
       3557342.1     10361341.65
#Sta/Elev= 30
  4693.6  352.96  4774.7  346.99  4836.2  341.22  4864.1  339.83  4931.2  335.43
    4948  334.82  4961.2  335.06  4970.4  335.83    4976  335.51  4984.3  332.39
  4992.7  331.02  4995.3  329.34  4998.1  328.84  5001.3  329.34  5006.7  330.97
  5015.1  332.05  5020.7  334.39  5032.1  334.56  5036.6  335.29  5048.1  335.13
  5051.6  335.26  5065.1  334.36  5104.3   336.2  5137.2  338.29  5163.1   339.3
  5216.8  342.34  5273.9  346.26    5289  346.78    5346   351.1  5389.6  353.12
#Mann= 7 ,-1 , 0
  4693.6     .05       0  4961.2     .12       0  4995.3     .07       0
  5001.3     .12       0  5048.1     .05       0  5104.3     .16       0
  5163.1     .05       0
Bank Sta=4995.3,5001.3
XS Rating Curve= 0 ,0
Exp/Cntr=0.3,0.1

Type RM Length L Ch R = 1 ,15085   ,480,480,480
BEGIN DESCRIPTION:
COBB BRANCH 1 33.0
END DESCRIPTION:
XS GIS Cut Line= 3
      3557542.11     10361991.61      3557542.11     10361691.64
       3557442.1     10361391.64
#Sta/Elev= 30
  4710.6  345.34  4713.1  345.34  4750.6  341.35  4766.5  339.97  4780.6  338.93
  4820.6  337.04  4850.6  335.03  4864.7  334.44  4910.6  332.63  4950.6  333.19
  4970.6  333.79  4980.6   333.5  4990.6  331.11  4997.6  327.79  5000.3  327.29
  5003.6  327.79  5008.1  330.04  5013.2  330.04  5021.1  333.57  5031.7  333.87
  5052.7  333.34  5084.4  333.92    5098  334.72  5147.6  336.97  5179.2  339.63
  5189.8  341.06  5221.4     344  5242.5  345.42    5253   346.6  5326.8   351.8
#Mann= 6 ,-1 , 0
  4710.6     .05       0  4766.5     .16       0  4864.7     .12       0
  4997.6     .07       0  5003.6     .12       0    5098     .05       0
Bank Sta=4997.6,5003.6
XS Rating Curve= 0 ,0
Exp/Cntr=0.3,0.1

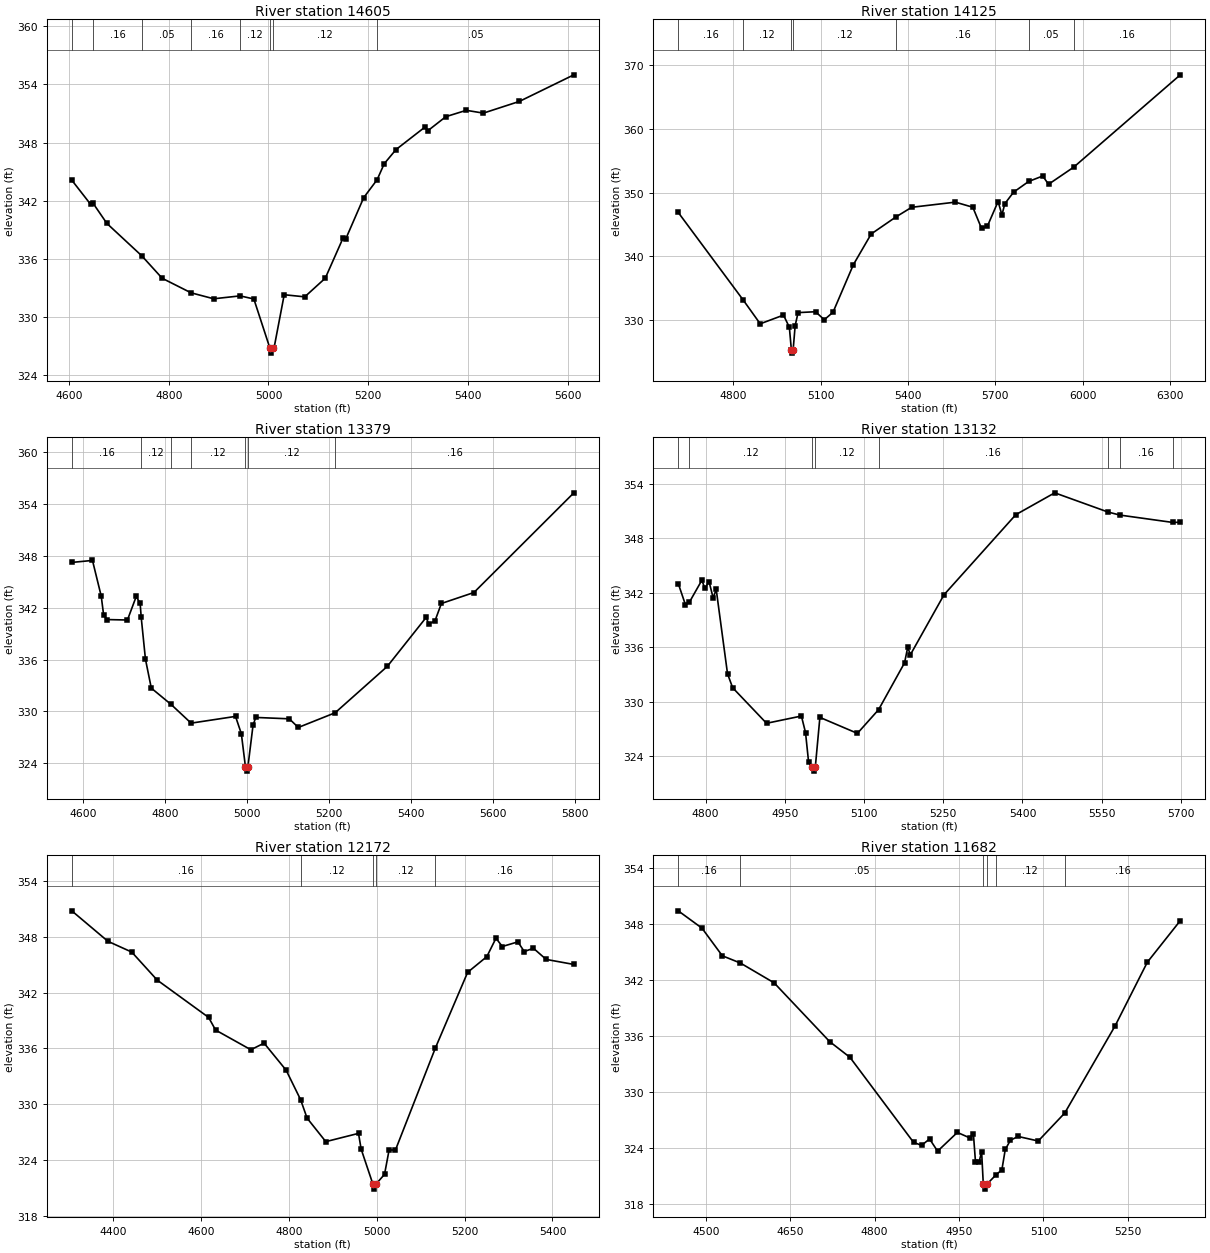
Type RM Length L Ch R = 1 ,14605   ,480,480,480
BEGIN DESCRIPTION:
COBB BRANCH 1 32.0
END DESCRIPTION:
XS GIS Cut Line= 3
      3557892.11     10361991.62      3557942.11     10361591.64
      3557795.01     10361005.61
#Sta/Elev= 30
  4605.4  344.11  4643.2  341.61  4647.7  341.75  4675.9  339.63  4746.1  336.27
  4786.8  333.96  4844.6  332.46  4890.1  331.84  4943.1  332.14  4970.7  331.82
    5003  326.72  5005.7  326.22    5009  326.72  5011.1  326.72  5031.6  332.26
  5072.8  332.04    5114  333.97    5150  338.16  5155.1  338.03  5191.1   342.3
  5218.1  344.16  5232.3  345.81  5255.9  347.27  5314.6  349.62  5319.8  349.22
  5355.8  350.67  5396.9  351.33  5431.2  351.04  5503.4  352.25  5612.7     355
#Mann= 8 ,-1 , 0
  4605.4     .05       0  4647.7     .16       0  4746.1     .05       0
  4844.6     .16       0  4943.1     .12       0    5003     .07       0
    5009     .12       0  5218.1     .05       0
Bank Sta=5003,5009
XS Rating Curve= 0 ,0
Exp/Cntr=0.3,0.1

Type RM Length L Ch R = 1 ,14125   ,746,746,746
BEGIN DESCRIPTION:
COBB BRANCH 1 31.0
END DESCRIPTION:
XS GIS Cut Line= 2
      3558357.25      10362093.1      3558435.38     10360369.17
#Sta/Elev= 30
  4610.1  346.87  4833.4   333.1  4891.9  329.36  4971.9  330.73    4992  328.82
    4999  325.25  5001.7  324.75    5005  325.25    5012  329.08    5022  331.12
    5082  331.26  5112.1     330  5142.1  331.18  5212.2  338.67  5273.4  343.49
  5359.2  346.19  5412.4  347.68  5562.5  348.49  5622.6  347.69  5652.6  344.36
  5672.7  344.71  5709.5  348.59  5722.7  346.48  5732.7  348.25  5762.7  350.06
  5814.5  351.74  5862.8   352.6  5882.9   351.3  5969.7     354  6335.8  368.51
#Mann= 7 ,-1 , 0
  4610.1     .16       0  4833.4     .12       0    4999     .07       0
    5005     .12       0  5359.2     .16       0  5814.5     .05       0
  5969.7     .16       0
Bank Sta=4999,5005
XS Rating Curve= 0 ,0
Exp/Cntr=0.3,0.1

Type RM Length L Ch R = 1 ,13379   ,247,247,247
BEGIN DESCRIPTION:
COBB BRANCH 1 30.0
END DESCRIPTION:
XS GIS Cut Line= 2
      3558638.51      10362155.6      3559685.36      10361520.2
#Sta/Elev= 30
  4573.1  347.24  4623.6  347.47  4644.9  343.35  4650.8  341.17  4659.2  340.63
  4708.9  340.58  4730.3   343.3  4739.9   342.5  4742.5  340.87  4752.8  336.05
  4767.1   332.7  4815.4  330.81  4864.2  328.65  4972.5  329.43  4986.7  327.43
  4996.7   323.6  4999.4   323.1  5002.7   323.6  5015.2   328.4  5021.8  329.31
  5103.7  329.15  5125.6  328.15  5215.5  329.85  5342.8  335.22  5437.7  340.89
  5443.6   340.1  5459.1  340.49  5474.6  342.49    5554  343.76  5797.7  355.29
#Mann= 7 ,-1 , 0
  4573.1     .16       0  4742.5     .12       0  4815.4     .16       0
  4864.2     .12       0  4996.7     .07       0  5002.7     .12       0
  5215.5     .16       0
Bank Sta=4996.7,5002.7
XS Rating Curve= 0 ,0
Exp/Cntr=0.3,0.1

Type RM Length L Ch R = 1 ,13132   ,960,960,960
BEGIN DESCRIPTION:
COBB BRANCH 1 29.0
END DESCRIPTION:
XS GIS Cut Line= 3
       3558892.1     10362241.65      3559142.11     10362091.64
      3559767.93     10361885.03
#Sta/Elev= 30
  4748.3  343.03  4761.9   340.7  4769.6  340.99    4793  343.39  4798.8  342.49
  4806.6  343.25  4814.4  341.44  4820.2  342.38  4841.6  333.09  4851.3  331.55
  4915.5  327.63  4981.5  328.43  4989.3  326.61  4995.1  323.36  5001.9  322.86
  5004.6  322.36  5007.9  322.86  5016.5  328.28  5087.5  326.52  5127.6  329.13
  5176.8  334.29  5182.7  335.98    5188   335.2  5251.5  341.79  5387.4  350.61
  5461.1  353.02  5561.7  350.91  5584.3  350.57  5684.3  349.76  5698.9  349.78
#Mann= 8 ,-1 , 0
  4748.3     .16       0  4769.6     .12       0  5001.9     .07       0
  5007.9     .12       0  5127.6     .16       0  5561.7     .12       0
  5584.3     .16       0  5684.3     .12       0
Bank Sta=5001.9,5007.9
XS Rating Curve= 0 ,0
Exp/Cntr=0.3,0.1

Type RM Length L Ch R = 1 ,12172   ,490,490,490
BEGIN DESCRIPTION:
COBB BRANCH 1 27.0
END DESCRIPTION:
XS GIS Cut Line= 3
        3558836.     10362853.95      3559542.11     10362791.64
      3559887.79     10362528.98
#Sta/Elev= 30
  4305.7  350.81    4388  347.53  4442.3  346.37  4500.1  343.36  4617.2  339.34
  4633.1  337.98  4713.4  335.86  4743.5  336.57  4793.7  333.66  4826.7  330.48
  4841.4   328.5    4884  325.97  4958.5  326.86  4964.4  325.18  4991.5  321.36
  4994.2  320.86  4997.5  321.36  5017.7  322.45  5028.1  325.07  5042.6  325.07
  5133.5  336.05  5206.9  344.19  5250.6  345.88  5271.4  347.86  5285.9  346.97
  5321.3  347.47  5335.8  346.43  5356.7  346.78  5385.7  345.58  5448.7  345.04
#Mann= 5 ,-1 , 0
  4305.7     .16       0  4826.7     .12       0  4991.5     .07       0
  4997.5     .12       0  5133.5     .16       0
Bank Sta=4991.5,4997.5
XS Rating Curve= 0 ,0
Exp/Cntr=0.3,0.1

Type RM Length L Ch R = 1 ,11682   ,450,450,450
BEGIN DESCRIPTION:
COBB BRANCH 1 26.0
END DESCRIPTION:
XS GIS Cut Line= 3
      3559342.13     10363591.61      3559692.11     10363191.64
      3559992.09     10362991.66
#Sta/Elev= 30
  4451.1  349.46  4493.3   347.6  4529.4  344.64  4561.6  343.86  4621.4  341.74
  4720.1  335.44  4756.2  333.75  4869.1  324.64  4883.4  324.31  4897.6     325
  4911.9  323.69    4947   325.7  4968.8  325.12  4975.5  325.55  4979.2  322.54
  4985.6  322.54  4990.1  323.63  4993.1  320.12  4995.8  319.62  4999.1  320.12
  5015.6  321.15  5026.1  321.69  5032.1  323.87  5041.2  324.85  5054.7  325.27
  5090.7  324.78  5137.8  327.78  5227.4  337.14  5284.5  343.95  5343.1  348.41
#Mann= 6 ,-1 , 0
  4451.1     .16       0  4561.6     .05       0  4993.1     .03       0
  4999.1     .05       0  5015.6     .12       0  5137.8     .16       0
Bank Sta=4993.1,4999.1
XS Rating Curve= 0 ,0
Exp/Cntr=0.3,0.1

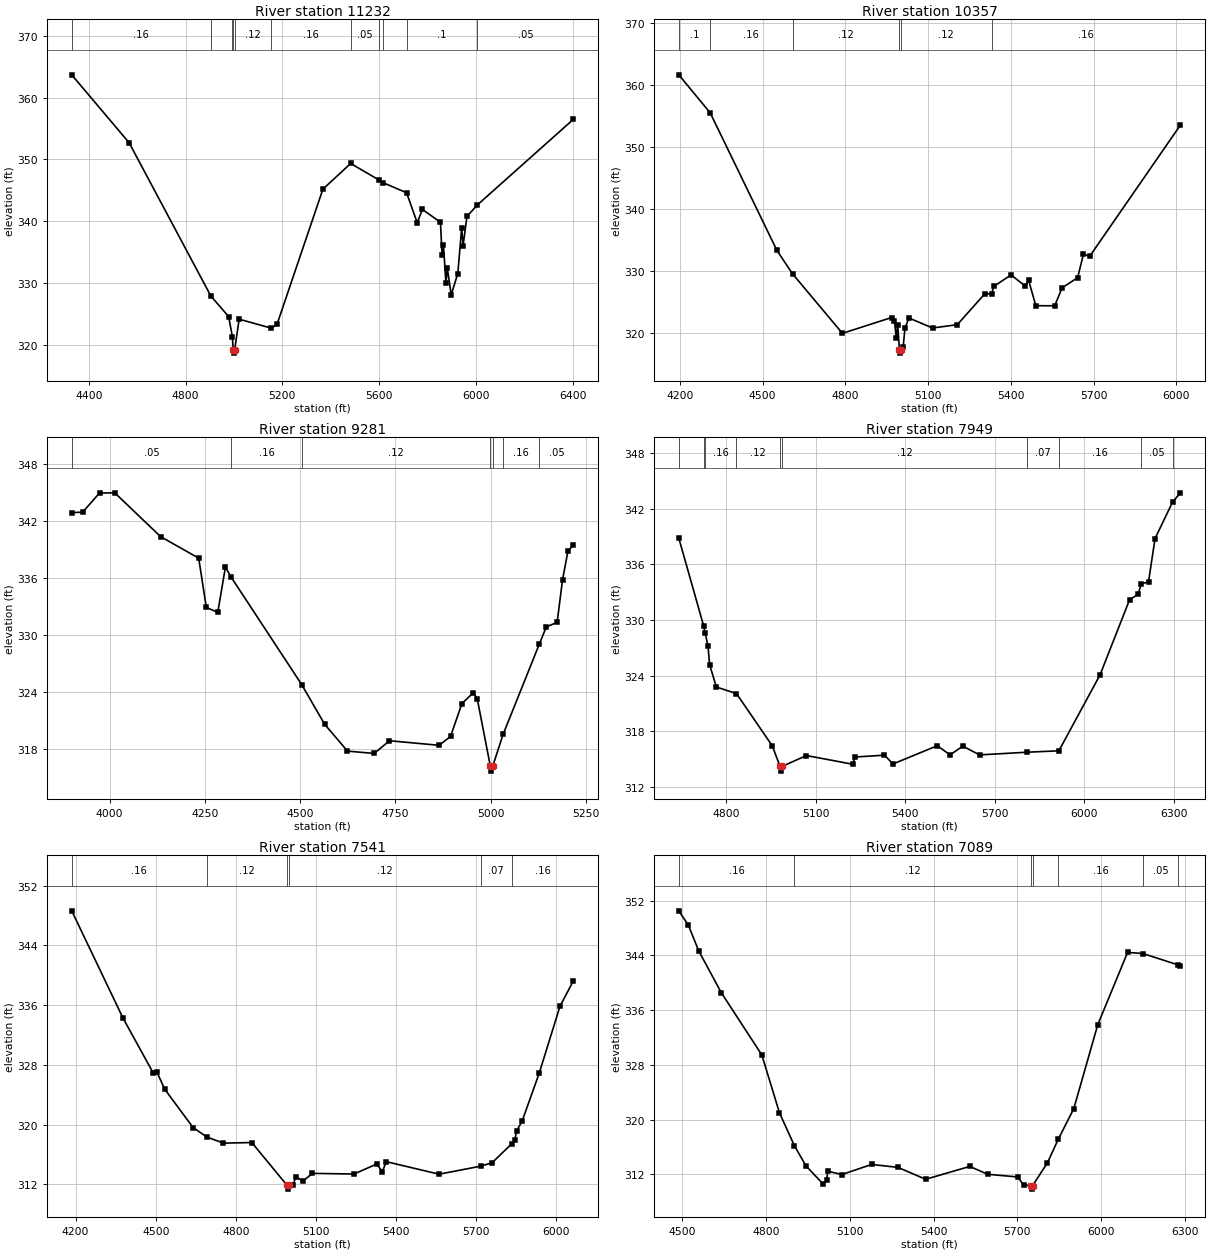
Type RM Length L Ch R = 1 ,11232   ,875,875,875
BEGIN DESCRIPTION:
COBB BRANCH 1 25.0
END DESCRIPTION:
XS GIS Cut Line= 2
      3559269.98     10363852.24      3561082.05     10362843.12
#Sta/Elev= 30
  4329.1  363.69  4566.4   352.7  4904.5   327.9    4978  324.58  4993.6  321.28
  4996.7  319.17  4999.5  318.67  5002.7  319.17  5021.4  324.16  5154.3  322.71
  5178.1  323.33  5367.8   345.2  5482.7  349.35  5598.3  346.71  5615.6  346.26
  5713.9  344.61  5757.7  339.77  5779.4  341.91  5853.9  339.84  5860.6  334.48
  5866.3  336.18  5876.6  329.94  5882.3  332.43  5898.3  328.11  5925.7  331.55
  5941.7  338.98  5947.5  336.06  5963.5  340.79    6007  342.66  6403.2  356.48
#Mann= 11 ,-1 , 0
  4329.1     .16       0  4904.5     .05       0  4993.6     .12       0
  4996.7     .07       0  5002.7     .12       0  5154.3     .16       0
  5482.7     .05       0  5598.3      .1       0  5615.6     .05       0
  5713.9      .1       0    6007     .05       0
Bank Sta=4996.7,5002.7
XS Rating Curve= 0 ,0
Exp/Cntr=0.3,0.1

Type RM Length L Ch R = 1 ,10357   ,1076,1076,1076
BEGIN DESCRIPTION:
COBB BRANCH 1 23.0
END DESCRIPTION:
XS GIS Cut Line= 3
      3559237.42      10364253.7      3559921.05     10364199.44
      3560995.26     10363841.37
#Sta/Elev= 30
  4196.1  361.62    4310  355.48  4551.9   333.3  4608.3  329.54  4789.3  319.94
  4967.3  322.49  4977.9  321.92  4984.4  319.18  4989.6  321.33  4995.9  317.25
  4998.7  316.75  5001.9  317.25  5009.5  317.79    5016  320.79  5030.6  322.41
  5116.1   320.8  5205.7  321.34  5305.9  326.34  5330.2  326.29  5337.5   327.5
  5400.7  329.36  5452.2  327.55    5464  328.53  5490.3   324.4  5558.9  324.38
  5585.2  327.26  5641.9  328.92    5663  332.71  5685.3  332.34  6014.2   353.5
#Mann= 6 ,-1 , 0
  4196.1      .1       0    4310     .16       0  4608.3     .12       0
  4995.9     .07       0  5001.9     .12       0  5330.2     .16       0
Bank Sta=4995.9,5001.9
XS Rating Curve= 0 ,0
Exp/Cntr=0.3,0.1

Type RM Length L Ch R = 1 ,9281    ,1332,1332,1332
BEGIN DESCRIPTION:
COBB BRANCH 1 21.0
END DESCRIPTION:
XS GIS Cut Line= 3
      3559389.34     10364948.14      3560492.11     10364891.64
      3560642.07     10364741.67
#Sta/Elev= 30
  3900.8  342.85  3929.4  342.89  3973.7  344.91  4013.7  344.93  4133.9  340.32
    4234  338.05    4254  332.86  4284.1  332.34  4304.1  337.11    4319  336.06
  4504.4  324.73  4564.4  320.56  4624.5  317.73  4694.6  317.48  4734.7  318.82
  4864.8  318.34  4894.9  319.27  4924.9  322.74  4954.9  323.88    4965  323.25
  4999.5  316.12  5002.3  315.62  5005.5  316.12  5032.9  319.49  5128.2  329.02
  5146.4  330.82  5174.7  331.28  5188.9  335.77    5203  338.77  5217.1  339.45
#Mann= 7 ,-1 , 0
  3900.8     .05       0    4319     .16       0  4504.4     .12       0
  4999.5     .07       0  5005.5     .12       0  5032.9     .16       0
  5128.2     .05       0
Bank Sta=4999.5,5005.5
XS Rating Curve= 0 ,0
Exp/Cntr=0.3,0.1

Type RM Length L Ch R = 1 ,7949    ,408,408,408
BEGIN DESCRIPTION:
COBB BRANCH 1 18.0
END DESCRIPTION:
XS GIS Cut Line= 3
      3559892.13     10366091.63      3560192.11     10365941.64
      3561192.07     10365041.67
#Sta/Elev= 30
  4641.6  338.84  4724.8  329.38  4730.1   328.6  4739.4   327.2    4745  325.18
  4767.4  322.79  4834.8  322.08  4954.6  316.46  4981.1  314.22  4983.8  313.72
  4987.1  314.22  5069.3   315.4  5224.8  314.46  5232.2  315.24  5330.9  315.44
  5359.3  314.49    5508  316.46  5550.6  315.47  5593.2  316.41  5649.7  315.47
  5809.2  315.76  5915.3  315.91  6053.3   324.1  6152.3  332.21  6180.7  332.77
    6191  333.87  6215.8  334.15  6237.5  338.79  6296.1  342.71  6322.3  343.72
#Mann= 10 ,-1 , 0
  4641.6     .15       0  4724.8     .05       0  4730.1     .16       0
  4834.8     .12       0  4981.1     .07       0  4987.1     .12       0
  5809.2     .07       0  5915.3     .16       0    6191     .05       0
  6296.1     .16       0
Bank Sta=4981.1,4987.1
XS Rating Curve= 0 ,0
Exp/Cntr=0.3,0.1

Type RM Length L Ch R = 1 ,7541    ,452,452,452
BEGIN DESCRIPTION:
COBB BRANCH 1 17.0
END DESCRIPTION:
XS GIS Cut Line= 3
      3559942.12     10366741.63      3560492.11     10366091.64
      3561192.13     10365341.62
#Sta/Elev= 30
  4185.7  348.64  4377.4  334.29  4490.5  326.94  4504.8  327.03  4533.4  324.77
    4640  319.61    4692  318.34  4753.1  317.53  4859.7  317.61  4991.9  311.87
  4994.6  311.37  4997.9  311.87  5015.7  311.95  5023.5  313.05  5051.1  312.45
  5086.7  313.48  5242.3  313.39  5327.1  314.73  5348.6   313.7  5362.8  315.05
  5560.6  313.37  5716.1  314.44    5759   314.9  5833.1  317.45    5844  317.92
  5850.8  319.14  5871.8   320.5  5935.8  326.92  6013.5  335.88  6063.1  339.24
#Mann= 6 ,-1 , 0
  4185.7     .16       0    4692     .12       0  4991.9     .07       0
  4997.9     .12       0  5716.1     .07       0  5833.1     .16       0
Bank Sta=4991.9,4997.9
XS Rating Curve= 0 ,0
Exp/Cntr=0.3,0.1

Type RM Length L Ch R = 1 ,7089    ,382,382,382
BEGIN DESCRIPTION:
COBB BRANCH 1 16.0
END DESCRIPTION:
XS GIS Cut Line= 3
      3560562.11     10366962.04      3560642.11     10366441.64
      3561671.29     10365696.55
#Sta/Elev= 30
  4487.2  350.52  4521.5  348.42  4558.4  344.68  4639.4  338.55  4784.7  329.45
    4848  320.97  4901.3  316.18  4942.9  313.22  5003.6  310.59  5016.8  311.09
  5021.1  312.44  5071.3  311.95    5178  313.43  5272.4     313  5371.7  311.26
  5529.9  313.14    5594  311.99  5701.6   311.6  5722.5  310.44  5748.9  310.32
  5751.6  309.82  5754.9  310.32  5808.3  313.69  5846.9  317.12  5902.6   321.6
  5988.5  333.88  6095.3  344.44  6150.6  344.27  6276.1  342.61  6284.3  342.48
#Mann= 7 ,-1 , 0
  4487.2     .16       0  4901.3     .12       0  5748.9     .07       0
  5754.9     .12       0  5846.9     .16       0  6150.6     .05       0
  6276.1     .08       0
Bank Sta=5748.9,5754.9
XS Rating Curve= 0 ,0
Exp/Cntr=0.3,0.1

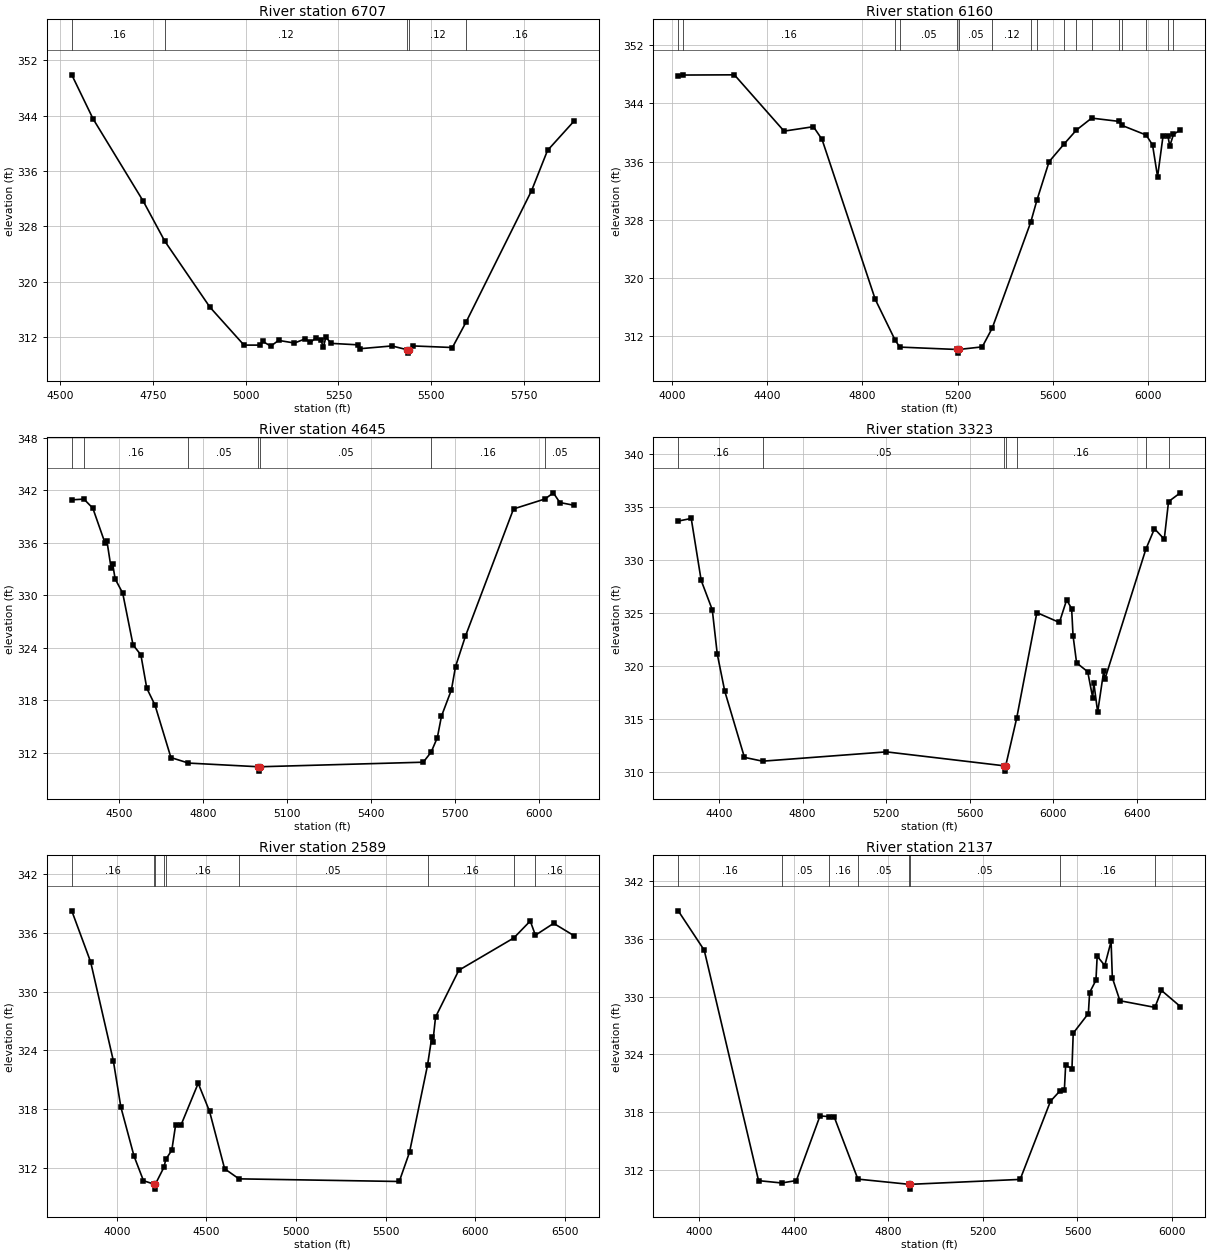
Type RM Length L Ch R = 1 ,6707    ,547,547,547
BEGIN DESCRIPTION:
COBB BRANCH 1 15.0
END DESCRIPTION:
XS GIS Cut Line= 3
      3560692.08     10366991.67      3560992.11     10366591.64
       3561642.1     10366041.64
#Sta/Elev= 30
  4532.1   349.9  4589.4  343.54  4724.8  331.61  4782.6  325.85    4904  316.32
  4995.7  310.84  5039.3  310.84  5045.8  311.38  5067.9  310.69  5088.7  311.52
  5131.6  311.14  5160.2  311.74  5174.4  311.22  5188.7  311.86  5202.4  311.52
  5209.6   310.6  5216.1  311.98  5230.4  311.09  5301.9  310.88  5308.4  310.32
  5394.2  310.72    5434  310.18  5436.8  309.68    5440  310.18  5451.3  310.72
  5556.7  310.49  5594.3  314.25  5769.9  333.17  5812.7  338.97  5883.6  343.18
#Mann= 5 ,-1 , 0
  4532.1     .16       0  4782.6     .12       0    5434     .07       0
    5440     .12       0  5594.3     .16       0
Bank Sta=5434,5440
XS Rating Curve= 0 ,0
Exp/Cntr=0.3,0.1

Type RM Length L Ch R = 1 ,6160    ,1515,1515,1515
BEGIN DESCRIPTION:
COBB BRANCH 1 13.0
END DESCRIPTION:
XS GIS Cut Line= 2
      3560927.56     10367583.13      3562082.09     10365820.95
#Sta/Elev= 30
  4026.9  347.76  4045.3  347.89  4262.5  347.92    4471  340.18  4594.1  340.79
  4630.3  339.04  4853.6  317.05  4936.3  311.49  4956.3  310.49  5197.3  310.16
    5200  309.66  5203.3  310.16  5302.6  310.52  5344.4   313.1  5505.8  327.64
  5532.8  330.78    5583  335.98  5647.2  338.46  5697.7  340.33  5761.6  341.97
    5876  341.52  5889.5  340.96  5990.5  339.64  6017.1  338.28  6038.2  333.91
    6061  339.48  6081.3  339.53  6089.5  338.13  6104.9  339.73  6133.6  340.34
#Mann= 17 ,-1 , 0
  4026.9     .05       0  4045.3     .16       0  4936.3     .12       0
  4956.3     .05       0  5197.3    .033       0  5203.3     .05       0
  5344.4     .12       0  5505.8     .16       0  5532.8     .05       0
  5647.2     .16       0  5697.7     .05       0  5761.6     .16       0
    5876     .05       0  5889.5     .08       0  5990.5     .16       0
  6081.3     .05       0  6104.9     .16       0
Bank Sta=5197.3,5203.3
XS Rating Curve= 0 ,0
Exp/Cntr=0.3,0.1

Type RM Length L Ch R = 1 ,4645    ,1322,1322,1322
BEGIN DESCRIPTION:
COBB BRANCH 1 9.0
END DESCRIPTION:
XS GIS Cut Line= 2
      3561884.16     10368239.37       3563342.5     10367190.76
#Sta/Elev= 30
  4329.3  340.93  4372.9  341.01  4404.7  339.97  4448.8  335.94    4455  336.24
  4469.7  333.19  4475.9  333.55  4484.4  331.89  4511.5  330.27  4548.5  324.35
  4576.5  323.21  4597.7  319.39  4626.9  317.48    4684  311.47  4746.8  310.84
    4997  310.42  4999.8  309.92    5003  310.42  5586.8  310.94  5615.1   312.1
  5637.2  313.76  5651.9   316.2  5687.5  319.21  5702.2  321.87  5737.8  325.36
  5909.7  339.89  6022.5  341.03  6052.1  341.73  6075.4  340.62  6125.5  340.31
#Mann= 7 ,-1 , 0
  4329.3     .05       0  4372.9     .16       0  4746.8     .05       0
    4997    .033       0    5003     .05       0  5615.1     .16       0
  6022.5     .05       0
Bank Sta=4997,5003
XS Rating Curve= 0 ,0
Exp/Cntr=0.3,0.1

Type RM Length L Ch R = 1 ,3323    ,734,734,734
BEGIN DESCRIPTION:
COBB BRANCH 1 7.0
END DESCRIPTION:
XS GIS Cut Line= 2
      3561856.35     10369399.11      3564076.43     10368476.39
#Sta/Elev= 30
  4204.9  333.67  4267.1  333.92  4314.8  328.06  4367.9  325.29  4391.8   321.1
  4427.7  317.59  4521.9  311.34  4608.7  310.98  5201.7  311.86  5766.9  310.54
  5769.7  310.04  5772.9  310.54  5825.4  315.03  5922.2  325.02  6030.1  324.09
  6064.8  326.22  6088.7   325.4  6095.4  322.85  6112.5  320.27  6165.7  319.43
  6189.5  316.99  6194.9  318.38  6213.4  315.61  6242.6  319.53  6248.1  318.74
  6443.9     331  6485.3  332.95  6532.2  331.96  6552.7  335.51  6609.1  336.34
#Mann= 7 ,-1 , 0
  4204.9     .16       0  4608.7     .05       0  5766.9    .033       0
  5772.9     .05       0  5825.4     .16       0  6443.9     .05       0
  6552.7     .16       0
Bank Sta=5766.9,5772.9
XS Rating Curve= 0 ,0
Exp/Cntr=0.3,0.1

Type RM Length L Ch R = 1 ,2589    ,452,452,452
BEGIN DESCRIPTION:
COBB BRANCH 1 6.0
END DESCRIPTION:
XS GIS Cut Line= 3
      3561792.12     10370041.64      3562992.11     10369641.64
      3564286.91     10368808.84
#Sta/Elev= 30
  3747.6  338.25    3853  333.03  3979.5  322.96  4021.7  318.21  4095.4  313.19
  4148.1  310.68  4208.4  310.32  4211.1  309.82  4214.4  310.32  4262.4  312.05
  4272.9  312.87  4306.3  313.79  4327.3  316.33    4359  316.42  4453.8  320.63
  4517.1  317.77  4601.4   311.9  4681.4  310.87  5576.8   310.6  5634.2  313.59
  5734.6  322.47  5758.4  325.31  5764.3   324.8  5779.5   327.4  5909.6  332.18
  6216.8  335.48  6308.5  337.21  6337.3  335.76  6439.2  336.97    6552  335.72
#Mann= 9 ,-1 , 0
  3747.6     .16       0  4208.4    .033       0  4214.4     .16       0
  4262.4     .05       0  4272.9     .16       0  4681.4     .05       0
  5734.6     .16       0  6216.8     .05       0  6337.3     .16       0
Bank Sta=4208.4,4214.4
XS Rating Curve= 0 ,0
Exp/Cntr=0.3,0.1

Type RM Length L Ch R = 1 ,2137    ,429,429,429
BEGIN DESCRIPTION:
COBB BRANCH 1 5.0
END DESCRIPTION:
XS GIS Cut Line= 3
       3561842.1     10370091.64      3562942.11     10370091.64
        3563918.     10370405.75
#Sta/Elev= 30
  3910.1  338.91  4020.1  334.82  4250.1  310.88  4347.8  310.64  4410.1  310.89
  4510.1   317.6  4547.5  317.54  4570.1  317.51  4670.6  311.04  4887.1   310.5
  4889.9     310  4893.1   310.5  5357.4  311.01  5485.7  319.13  5525.8   320.2
  5544.6  320.33  5549.9  322.86  5576.7  322.53    5582   326.2  5646.1  328.24
  5651.4  330.42  5678.2   331.7  5683.4   334.2  5715.5  333.23  5742.3  335.73
  5747.6  331.95  5779.7  329.57  5927.7  328.88  5955.6  330.64  6035.3  328.97
#Mann= 8 ,-1 , 0
  3910.1     .16       0  4347.8     .05       0  4547.5     .16       0
  4670.6     .05       0  4887.1    .033       0  4893.1     .05       0
  5525.8     .16       0  5927.7     .05       0
Bank Sta=4887.1,4893.1
XS Rating Curve= 0 ,0
Exp/Cntr=0.3,0.1