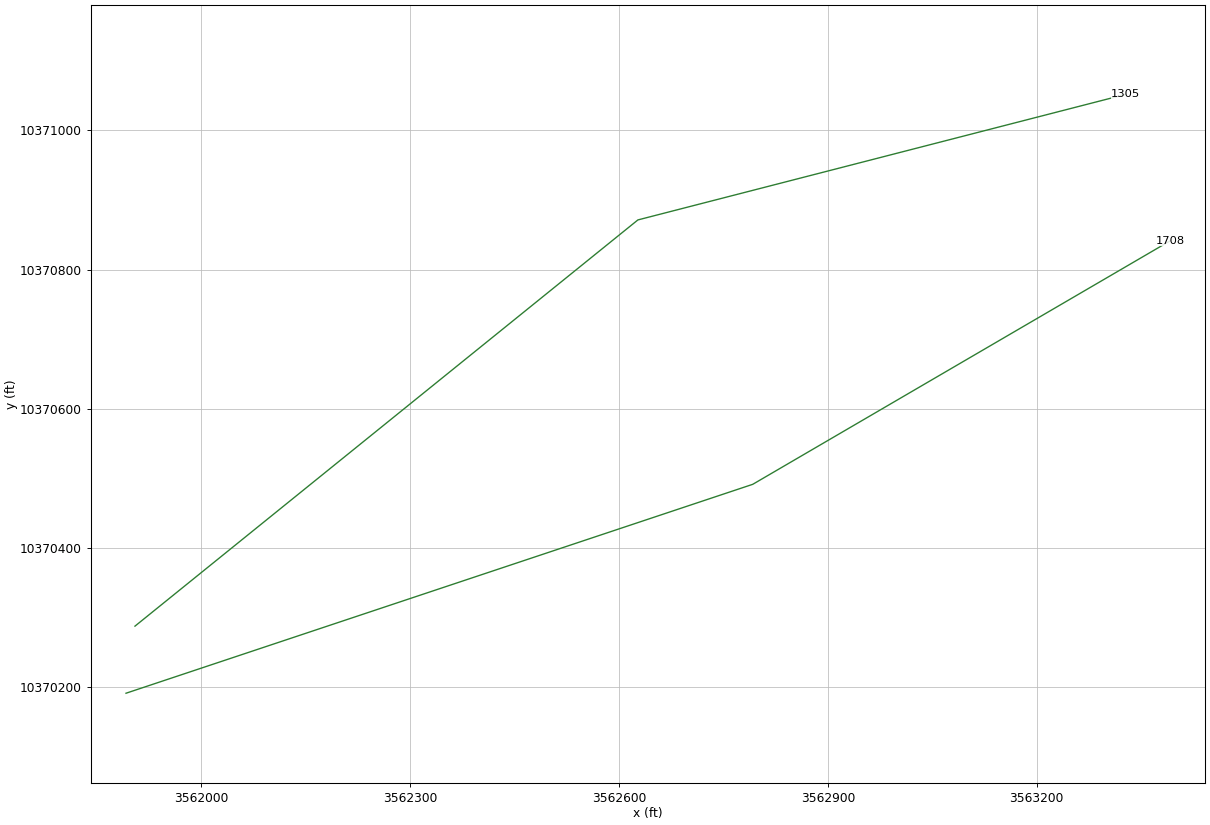
HEC-RAS study COBB BRANCH 1.prj: COBB BRANCH 1 Base Level Engineering

--- COBB BRANCH 1.g01 (geometry) --- (continued)

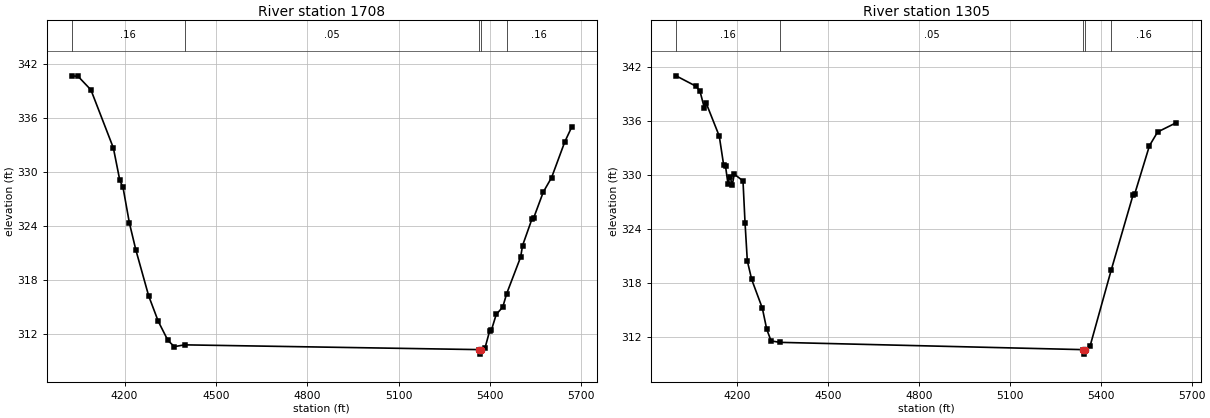
Type RM Length L Ch R = 1 ,1708    ,403,403,403
BEGIN DESCRIPTION:
COBB BRANCH 1 4.0
END DESCRIPTION:
XS GIS Cut Line= 3
      3561892.13     10370191.65      3562792.11     10370491.64
      3563392.12     10370841.65
#Sta/Elev= 30
  4026.2  340.71  4047.3  340.65  4089.4  339.15  4163.2   332.7  4184.3  329.11
  4194.8  328.33  4215.9  324.36    4237  321.38  4279.2  316.27  4310.8  313.44
  4342.4  311.33  4363.5  310.64  4396.9  310.84  5365.5  310.31  5368.2  309.81
  5371.5  310.31  5383.8  310.45  5399.5  312.41  5405.3  312.49    5421  314.22
  5442.5  315.04  5455.1  316.51  5501.2  320.59  5507.4  321.86  5538.4  324.82
  5544.2  324.95  5575.6  327.81  5602.9  329.42  5646.3  333.39  5669.5  335.06
#Mann= 5 ,-1 , 0
  4026.2     .16       0  4396.9     .05       0  5365.5    .033       0
  5371.5     .05       0  5455.1     .16       0
Bank Sta=5365.5,5371.5
XS Rating Curve= 0 ,0
Exp/Cntr=0.3,0.1

Type RM Length L Ch R = 1 ,1305    ,0,0,0
BEGIN DESCRIPTION:
COBB BRANCH 1 1.0
END DESCRIPTION:
XS GIS Cut Line= 3
        3561905.     10370287.99      3562627.22     10370871.32
       3563327.9     10371051.69
#Sta/Elev= 30
  3997.4  341.02  4061.6  339.89    4076  339.35  4090.4  337.49  4096.8  337.98
    4140  334.31  4154.4  331.12  4160.8  330.94  4168.8  328.98  4175.2   329.8
  4183.2   328.9  4189.6  330.08  4218.4  329.32  4225.1  324.68  4232.7  320.41
  4247.1  318.35  4282.3  315.15  4296.7  312.82  4311.1  311.51  4340.8  311.35
  5340.5  310.54  5343.2  310.04  5346.5  310.54  5364.5  310.92  5434.1  319.36
  5506.3  327.73  5511.5  327.81  5560.7  333.24  5587.7  334.77  5649.3   335.8
#Mann= 5 ,-1 , 0
  3997.4     .16       0  4340.8     .05       0  5340.5    .033       0
  5346.5     .05       0  5434.1     .16       0
Bank Sta=5340.5,5346.5
XS Rating Curve= 0 ,0
Exp/Cntr=0.3,0.1

Chan Stop Cuts=-1
Use User Specified Reach Order=0
Composite Channel Slope=5