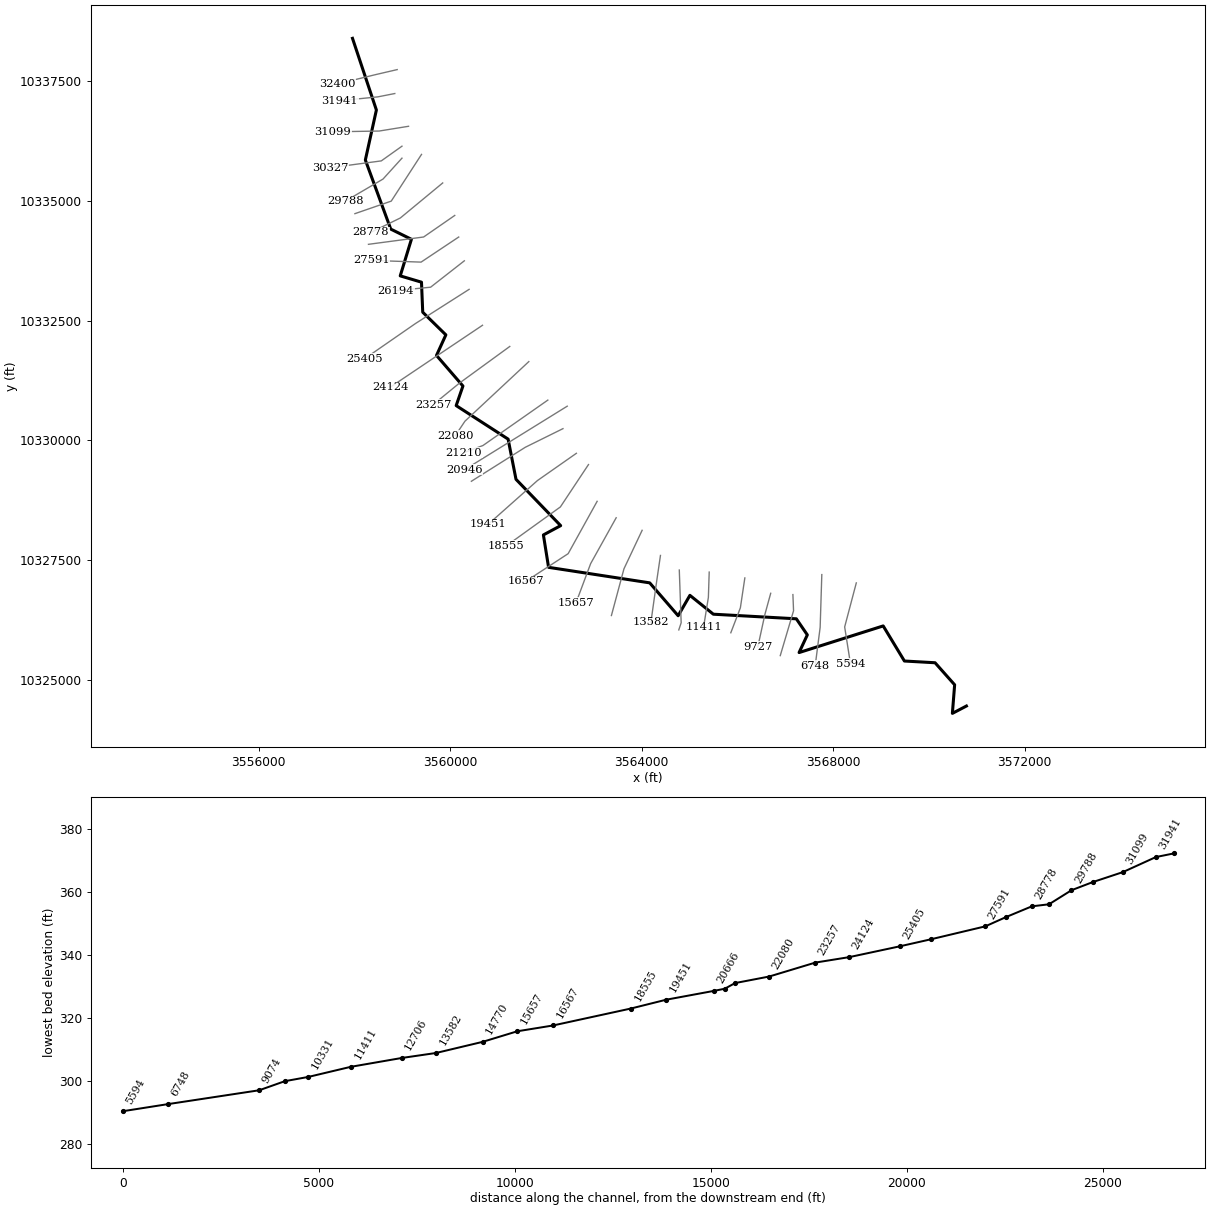
--- COBB BRANCH 2.prj (project) ---

Proj Title=COBB BRANCH 2 Base Level Engineering
Current Plan=p01
Default Exp/Contr=0.3,0.1
English Units
Geom File=g01
Flow File=f01
Plan File=p01
Y Axis Title=Elevation
X Axis Title(PF)=Main Channel Distance
X Axis Title(XS)=Station
BEGIN DESCRIPTION:
COBB BRANCH 2
END DESCRIPTION:
DSS Export Rating Curves= 0
DSS Export Rating Curve Sorted= 0
DSS Export Volume Flow Curves= 0
DXF OffsetX= 0
DXF OffsetY= 0
DXF ScaleX= 1
DXF ScaleY= 10

--- COBB BRANCH 2.p01 (plan) ---

Plan Title=Multiple Run
Short Identifier=Multiple
Geom File=g01
Flow File=f01
Subcritical Flow
K Sum by GR= 0
Std Step Tol= 0.01
Critical Tol= 0.01
Num of Std Step Trials= 20
Max Error Tol= 0.3
Flow Tol Ratio= 0.001
Split Flow NTrial= 30
Split Flow Tol= 0.02
Split Flow Ratio= 0.02
Log Output Level= 0
Friction Slope Method= 1
Unsteady Friction Slope Method= 2
Unsteady Bridges Friction Slope Method= 1
Parabolic Critical Depth
Global Vel Dist=  1 , 1 , 1
Global Log Level= 0
CheckData=True
Encroach Param= -1, 0, 0, 0
BEGIN DESCRIPTION:
Multiple Run
END DESCRIPTION:

--- COBB BRANCH 2.f01 (steady flow) ---

Flow Title=Multiple
Program Version=4.10
Number of Profiles= 7
Profile Names=10-year,25-year,50-year,1pct_min,100-year,1pct_plu,500-year
River Rch & RM=COBB BRANCH 2,Reach-1         ,32400
     824    1137    1397    1257    1700    2300    2526
River Rch & RM=COBB BRANCH 2,Reach-1         ,25405
    1317    1853    2306    2099    2838    3838    4311
River Rch & RM=COBB BRANCH 2,Reach-1         ,23257
    1317    1853    2306    2099    2838    3838    4311
River Rch & RM=COBB BRANCH 2,Reach-1         ,11411
    1372    1929    2399    2180    2949    3988    4468
River Rch & RM=COBB BRANCH 2,Reach-1         ,3323
    1556    2200    2746    2504    3387    4580    5166
Boundary for River Rch & Prof#=COBB BRANCH 2,Reach-1         , 1
Up Type= 0
Dn Type= 3
Dn Slope=0.005
Boundary for River Rch & Prof#=COBB BRANCH 2,Reach-1         , 2
Up Type= 0
Dn Type= 3
Dn Slope=0.005
Boundary for River Rch & Prof#=COBB BRANCH 2,Reach-1         , 3
Up Type= 0
Dn Type= 3
Dn Slope=0.005
Boundary for River Rch & Prof#=COBB BRANCH 2,Reach-1         , 4
Up Type= 0
Dn Type= 3
Dn Slope=0.005
Boundary for River Rch & Prof#=COBB BRANCH 2,Reach-1         , 5
Up Type= 0
Dn Type= 3
Dn Slope=0.005
Boundary for River Rch & Prof#=COBB BRANCH 2,Reach-1         , 6
Up Type= 0
Dn Type= 3
Dn Slope=0.005
Boundary for River Rch & Prof#=COBB BRANCH 2,Reach-1         , 7
Up Type= 0
Dn Type= 3
Dn Slope=0.005
DSS Import GetInterval= 0
DSS Import GetPeak= 0
DSS Import FillOption= 0

--- COBB BRANCH 2.g01 (geometry) ---

Geom Title=Existing Conditions
Program Version=4.10

River Reach=COBB BRANCH 2   ,Reach-1
Reach XY= 30
      3557958.39     10338394.73      3558457.57     10336897.47
      3558227.05     10335852.99      3558757.73     10334409.24
      3559189.14     10334196.63      3558955.71     10333432.44
       3559399.7     10333300.53      3559425.73     10332673.12
      3559908.89     10332200.04      3559713.39     10331770.57
      3560265.65     10331131.29      3560124.24     10330722.28
      3561209.25     10330022.24      3561374.22     10329182.45
      3562307.13     10328214.55      3561946.71     10328020.59
      3562054.64     10327343.39      3564167.28     10327019.25
      3564761.72     10326332.45      3565007.28     10326758.24
      3565497.08     10326364.26      3567230.47     10326268.22
      3567460.37     10325932.04      3567287.81     10325562.68
      3569045.06     10326119.37      3569488.46     10325386.28
      3570128.74     10325350.17      3570537.76     10324889.75
      3570490.54     10324292.53      3570783.63     10324445.95

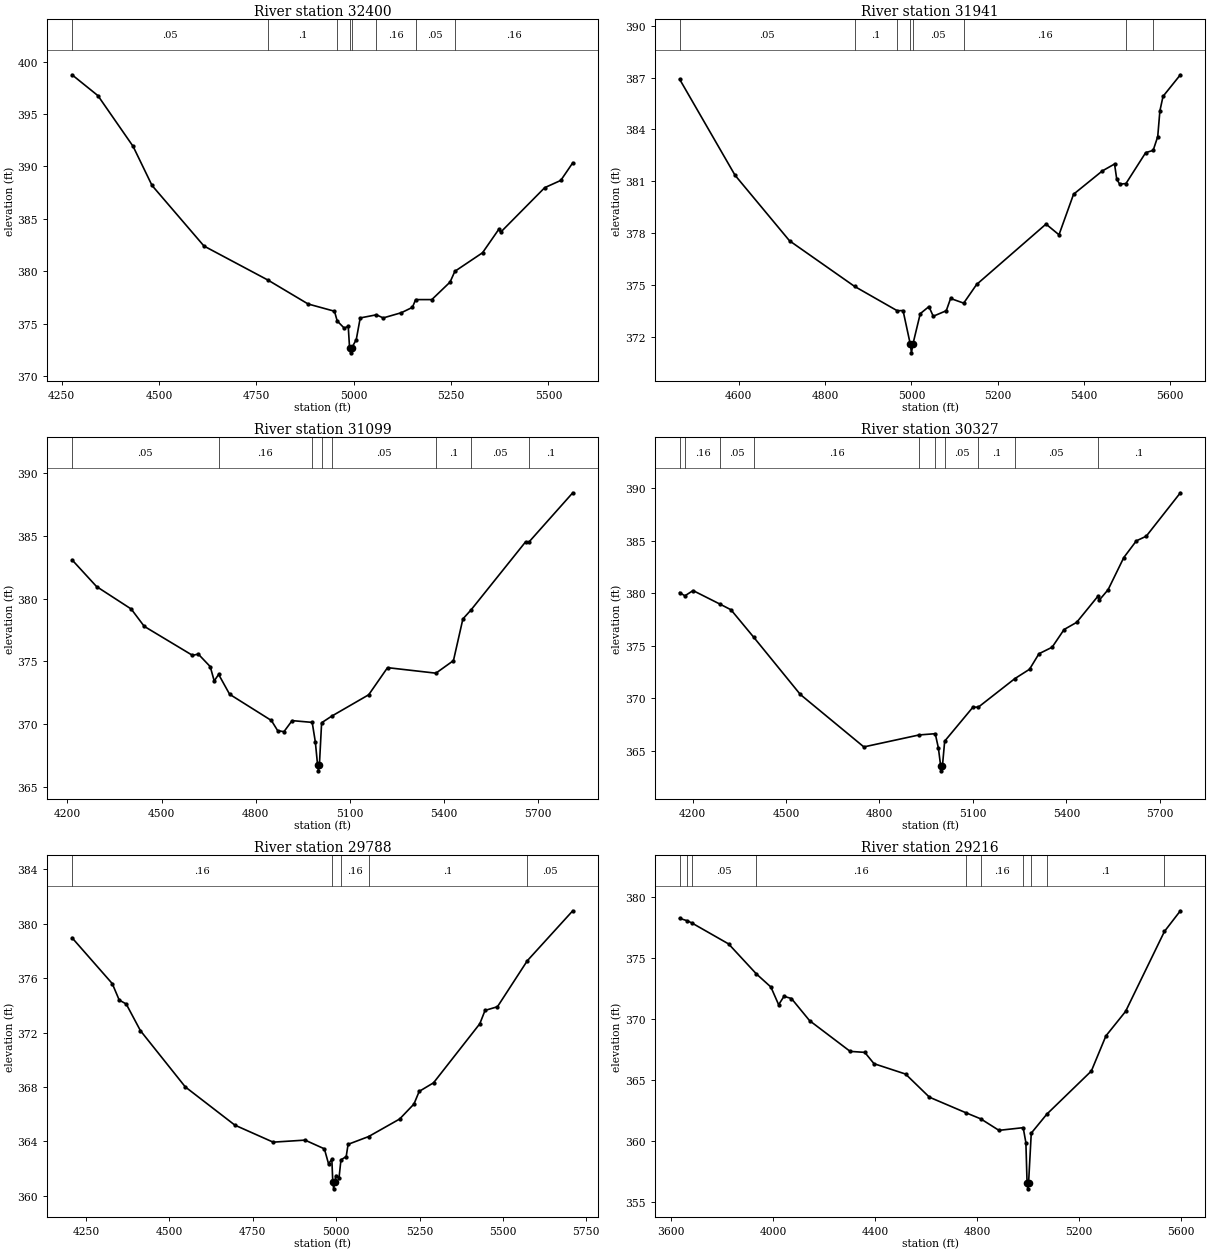
Type RM Length L Ch R = 1 ,32400   ,459,459,459
BEGIN DESCRIPTION:
COBB BRANCH 2 47.0
END DESCRIPTION:
XS GIS Cut Line= 3
      3558892.13     10337741.65      3558424.37     10337632.76
      3557642.14     10337441.65
#Sta/Elev= 30
  4276.8  398.75  4343.3  396.76  4433.6  391.92  4482.2  388.19  4615.6  382.41
  4780.4  379.15  4882.9  376.88  4950.6  376.19  4957.6  375.26  4975.6  374.58
  4985.9  374.75  4989.3  372.72    4992  372.22  4995.3  372.72  5006.5  373.48
  5016.7  375.55  5058.3  375.85  5075.6  375.55  5122.4  376.05  5150.6  376.56
    5159   377.3  5200.5   377.3  5247.3  378.97  5259.7     380  5330.7  381.77
  5372.3     384  5377.5  383.74  5490.3  387.98  5531.5  388.67  5562.3  390.35
#Mann= 8 ,-1 , 0
  4276.8     .05       0  4780.4      .1       0  4957.6     .05       0
  4989.3     .03       0  4995.3     .05       0  5058.3     .16       0
    5159     .05       0  5259.7     .16       0
Bank Sta=4989.3,4995.3
XS Rating Curve= 0 ,0
Exp/Cntr=0.3,0.1

Type RM Length L Ch R = 1 ,31941   ,842,842,842
BEGIN DESCRIPTION:
COBB BRANCH 2 46.0
END DESCRIPTION:
XS GIS Cut Line= 3
       3558842.1     10337241.64      3558487.62     10337171.89
      3557692.13     10337091.64
#Sta/Elev= 30
  4462.7  386.91  4591.1  381.35  4717.5  377.55  4868.2  374.91  4967.1   373.5
  4980.6  373.51  4997.4  371.56  5000.1  371.06  5003.4  371.56  5020.5  373.33
  5040.6  373.74  5050.6  373.18  5080.8   373.5  5090.8  374.21  5121.2  373.94
  5151.1  375.02    5312  378.52  5342.1   377.9  5375.9  380.25  5442.6   381.6
  5470.9     382  5475.9  381.13  5482.8  380.83  5497.4  380.87  5543.1  382.66
  5560.4  382.79    5571  383.59    5576  385.08  5583.3  385.92  5623.5  387.17
#Mann= 8 ,-1 , 0
  4462.7     .05       0  4868.2      .1       0  4967.1     .05       0
  4997.4     .04       0  5003.4     .05       0  5121.2     .16       0
  5497.4     .05       0  5560.4     .16       0
Bank Sta=4997.4,5003.4
XS Rating Curve= 0 ,0
Exp/Cntr=0.3,0.1

Type RM Length L Ch R = 1 ,31099   ,772,772,772
BEGIN DESCRIPTION:
COBB BRANCH 2 45.0
END DESCRIPTION:
XS GIS Cut Line= 3
      3559129.28     10336557.39      3558514.73     10336457.98
      3557542.11     10336441.64
#Sta/Elev= 30
  4214.9  383.09  4293.1  380.96  4403.5  379.17    4445  377.79  4598.7  375.48
  4617.2  375.58  4655.3  374.58  4667.9  373.44    4682  373.96    4717  372.38
  4850.1  370.29  4870.1  369.48  4890.1   369.4  4916.1  370.28  4980.1  370.14
  4990.1  368.58  4997.1  366.78  4999.8  366.28  5003.1  366.78  5010.1  370.11
  5041.8  370.63  5160.1  372.34  5220.1   374.5  5374.2  374.06  5430.1  375.06
  5460.2  378.38  5486.2   379.1  5660.2  384.53  5670.4   384.5  5810.2  388.43
#Mann= 8 ,-1 , 0
  4214.9     .05       0    4682     .16       0  4980.1     .07       0
  5010.1     .16       0  5041.8     .05       0  5374.2      .1       0
  5486.2     .05       0  5670.4      .1       0
Bank Sta=4997.1,5003.1
XS Rating Curve= 0 ,0
Exp/Cntr=0.3,0.1

Type RM Length L Ch R = 1 ,30327   ,539,539,539
BEGIN DESCRIPTION:
COBB BRANCH 2 43.0
END DESCRIPTION:
XS GIS Cut Line= 3
      3558992.11     10336141.65      3558559.92     10335834.44
      3557492.08     10335691.64
#Sta/Elev= 30
  4158.6  380.08  4175.4  379.77  4201.7  380.27  4288.7  378.97  4323.4  378.44
  4396.8  375.81    4546  370.37    4750  365.37  4927.3  366.51  4979.2  366.63
  4989.3  365.27  4996.4  363.59  4999.2  363.09  5002.4  363.59  5009.5  365.92
  5100.3  369.16  5117.6  369.16  5234.8  371.88  5281.9  372.77  5312.2  374.25
  5354.4  374.87  5392.9  376.56  5433.2  377.24  5500.9  379.71  5505.5  379.35
  5534.1  380.35  5584.6  383.42  5624.9  385.01  5656.6  385.45  5766.2  389.59
#Mann= 10 ,-1 , 0
  4158.6     .05       0  4175.4     .16       0  4288.7     .05       0
  4396.8     .16       0  4927.3     .05       0  4979.2     .07       0
  5009.5     .05       0  5117.6      .1       0  5234.8     .05       0
  5500.9      .1       0
Bank Sta=4996.4,5002.4
XS Rating Curve= 0 ,0
Exp/Cntr=0.3,0.1

Type RM Length L Ch R = 1 ,29788   ,572,572,572
BEGIN DESCRIPTION:
COBB BRANCH 2 42.0
END DESCRIPTION:
XS GIS Cut Line= 3
      3558992.07     10335891.61      3558596.07      10335454.9
      3557809.82     10334993.99
#Sta/Elev= 30
  4208.4  378.97    4329   375.6  4349.9  374.39  4370.9   374.1  4413.5  372.14
  4547.9  368.01  4696.6   365.2  4811.3  363.95  4906.8   364.1  4964.8  363.46
  4977.3  362.36  4987.2   362.7    4990  361.02  4992.7  360.52    4996  361.02
  4999.6   361.5  5008.7  361.32  5014.5  362.65  5030.2  362.89  5035.9  363.79
  5097.3  364.36  5190.4  365.65  5233.3  366.75    5249  367.68    5292  368.31
  5430.7  372.65  5446.4  373.63  5483.6   373.9  5573.1  377.28  5709.3  380.95
#Mann= 5 ,-1 , 0
  4208.4     .16       0  4987.2     .07       0  5014.5     .16       0
  5097.3      .1       0  5573.1     .05       0
Bank Sta=4990,4996
XS Rating Curve= 0 ,0
Exp/Cntr=0.3,0.1

Type RM Length L Ch R = 1 ,29216   ,438,438,438
BEGIN DESCRIPTION:
COBB BRANCH 2 41.0
END DESCRIPTION:
XS GIS Cut Line= 3
      3559400.34     10335969.99      3558767.76     10334994.02
      3558008.67     10334731.95
#Sta/Elev= 30
  3632.5  378.26  3662.5  378.06  3680.4  377.88  3824.7  376.16  3933.7   373.7
  3990.9  372.62  4021.2  371.17  4042.3  371.86  4071.4  371.68  4142.9  369.86
  4302.1  367.34  4359.4  367.26  4395.7  366.33  4519.6  365.48  4613.3  363.58
  4755.8  362.31  4815.1   361.8  4886.2  360.86  4981.4  361.08    4992  359.85
  4996.6  356.56  4999.4  356.06  5002.6  356.56  5013.1  360.63  5074.3  362.19
  5249.1  365.73  5306.2  368.61  5383.4  370.62  5536.2  377.19  5598.6  378.88
#Mann= 10 ,-1 , 0
  3632.5     .05       0  3662.5     .16       0  3680.4     .05       0
  3933.7     .16       0  4755.8      .1       0  4815.1     .16       0
  4981.4     .07       0  5013.1     .05       0  5074.3      .1       0
  5536.2     .05       0
Bank Sta=4996.6,5002.6
XS Rating Curve= 0 ,0
Exp/Cntr=0.3,0.1

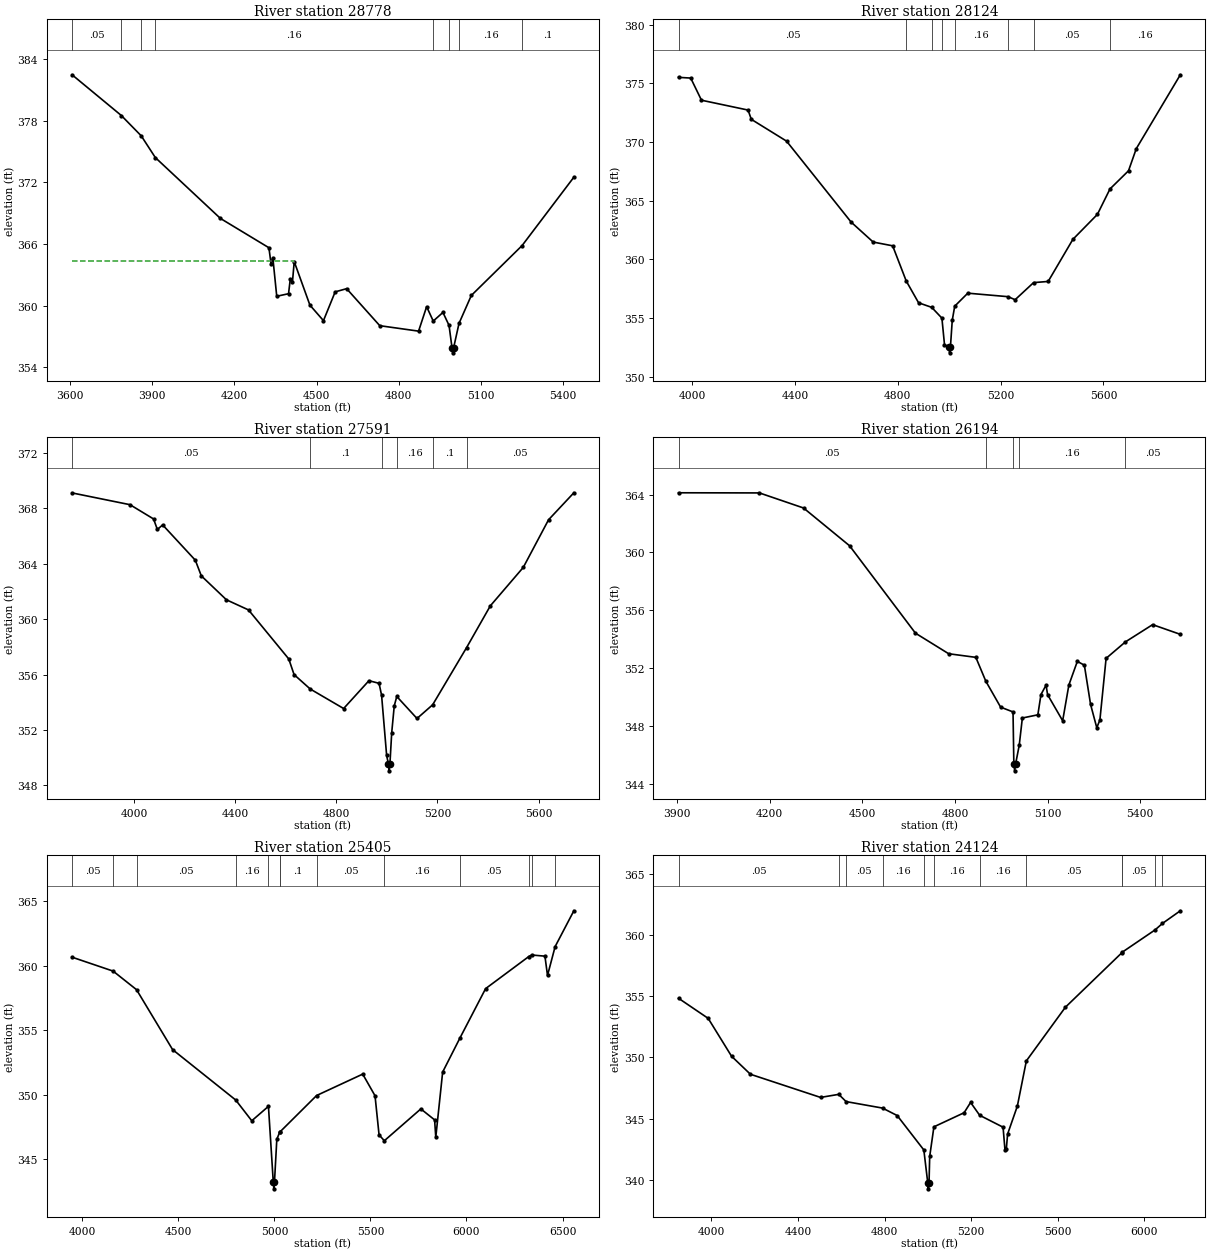
Type RM Length L Ch R = 1 ,28778   ,654,654,654
BEGIN DESCRIPTION:
COBB BRANCH 2 40.0
END DESCRIPTION:
XS GIS Cut Line= 3
      3559843.13     10335373.55      3558957.54     10334641.58
      3558342.08     10334341.63
#Sta/Elev= 30
  3606.7  382.45  3786.7  378.49  3859.5  376.51  3910.9   374.4  4148.8  368.48
    4326  365.63  4333.8  364.06  4340.3  364.66  4354.6  360.91  4397.7  361.16
  4404.1  362.58    4412   362.3  4418.5  364.28  4475.8  360.05  4525.3  358.54
  4568.1  361.34    4610  361.65  4731.1  358.05  4872.9  357.52  4902.3   359.9
  4926.5   358.5  4961.9  359.34  4984.2  358.08    4995  355.91  4997.8  355.41
    5001  355.91  5020.6  358.27  5065.6  360.99  5251.1  365.84  5440.3  372.49
#Mann= 8 ,-1 , 0
  3606.7     .05       0  3786.7     .16       0  3859.5     .05       0
  3910.9     .16       0  4926.5     .05       0  4984.2     .07       0
  5020.6     .16       0  5251.1      .1       0
#XS Ineff= 2 , 0
         4418.18  364.31
Permanent Ineff=
       F       F
Bank Sta=4995,5001
XS Rating Curve= 0 ,0
Exp/Cntr=0.3,0.1

Type RM Length L Ch R = 1 ,28124   ,533,533,533
BEGIN DESCRIPTION:
COBB BRANCH 2 38.0
END DESCRIPTION:
XS GIS Cut Line= 3
      3560094.56     10334694.69      3559444.54     10334244.67
      3558292.15     10334091.65
#Sta/Elev= 30
  3946.3  375.52  3993.7  375.46  4035.6  373.57  4216.9  372.73  4229.5  371.94
  4366.7  370.08  4618.2  363.17  4703.9  361.47  4779.7  361.15  4832.5  358.15
  4880.6  356.29  4931.7   355.9  4971.4  354.98  4981.5  352.72  4998.6  352.52
  5001.4  352.02  5004.6  352.52  5011.7   354.8  5021.3     356  5072.2  357.11
  5229.1  356.81  5256.3  356.55  5328.2  358.01    5385  358.11  5481.2   361.7
  5576.6  363.83  5625.6     366  5697.7  367.55    5728  369.44  5899.4  375.74
#Mann= 8 ,-1 , 0
  3946.3     .05       0  4832.5      .1       0  4931.7     .16       0
  4971.4     .07       0  5021.3     .16       0  5229.1      .1       0
  5328.2     .05       0  5625.6     .16       0
Bank Sta=4998.6,5004.6
XS Rating Curve= 0 ,0
Exp/Cntr=0.3,0.1

Type RM Length L Ch R = 1 ,27591   ,1397,1397,1397
BEGIN DESCRIPTION:
COBB BRANCH 2 37.0
END DESCRIPTION:
XS GIS Cut Line= 3
      3560177.47     10334243.94       3559391.3     10333719.83
      3558352.09     10333755.98
#Sta/Elev= 30
  3754.8  369.12  3983.9  368.27  4077.1  367.24  4092.1  366.48  4113.1  366.81
  4242.3  364.26    4266  363.13  4365.5   361.4  4452.7  360.67  4611.9  357.13
  4632.9     356  4696.7  354.96  4828.9  353.55    4929  355.56    4969  355.37
    4979  354.51    4999  350.16    5006  349.55  5008.8  349.05    5012  349.55
    5019  351.79  5029.1  353.74  5039.1  354.42  5119.1  352.83    5181  353.82
  5314.9  357.94  5409.3  360.97  5539.4  363.74  5639.4  367.18  5739.5  369.13
#Mann= 6 ,-1 , 0
  3754.8     .05       0  4696.7      .1       0    4979     .07       0
  5039.1     .16       0    5181      .1       0  5314.9     .05       0
Bank Sta=5006,5012
XS Rating Curve= 0 ,0
Exp/Cntr=0.3,0.1

Type RM Length L Ch R = 1 ,26194   ,789,789,789
BEGIN DESCRIPTION:
COBB BRANCH 2 36.0
END DESCRIPTION:
XS GIS Cut Line= 3
      3560294.98     10333746.94      3559590.11      10333195.7
      3558862.74     10333124.26
#Sta/Elev= 30
  3904.3  364.12  4166.4  364.11  4309.2  363.07  4458.4  360.46  4671.9  354.42
  4779.5     353  4867.5  352.75  4899.9   351.1  4947.8  349.31    4988  348.98
  4990.6  345.41  4993.3  344.91  4996.6  345.41  5008.1  346.68  5018.2  348.56
  5068.4  348.78  5078.5  350.18    5095  350.83    5100  350.17  5148.8  348.37
  5168.9  350.84  5196.3  352.47  5219.1  352.21  5239.2   349.5  5259.3  347.89
  5269.4  348.42  5289.5  352.68  5352.2  353.82  5440.2  355.01    5530  354.34
#Mann= 5 ,-1 , 0
  3904.3     .05       0  4899.9     .16       0    4988     .07       0
  5008.1     .16       0  5352.2     .05       0
Bank Sta=4990.6,4996.6
XS Rating Curve= 0 ,0
Exp/Cntr=0.3,0.1

Type RM Length L Ch R = 1 ,25405   ,1281,1281,1281
BEGIN DESCRIPTION:
COBB BRANCH 2 35.0
END DESCRIPTION:
XS GIS Cut Line= 3
       3560394.4     10333150.52      3559273.83      10332436.6
      3558218.27     10331705.83
#Sta/Elev= 30
  3946.6  360.66  4160.3  359.58  4282.2  358.14    4470  353.49  4798.6  349.58
  4882.2  347.97    4969  349.09  4994.3  343.19  4997.1  342.69  5000.3  343.19
  5012.6  346.54  5027.8  347.09    5028  347.09  5219.8  349.93  5459.8  351.59
  5523.9  349.91  5544.9  346.88  5572.3  346.42  5762.4  348.89  5834.1  348.04
  5840.2  346.69    5876  351.75  5966.7  354.41  6099.6  358.22  6323.6   360.7
  6339.3  360.83  6408.5  360.74  6421.9  359.24  6461.5  361.48  6559.1  364.26
#Mann= 13 ,-1 , 0
  3946.6     .05       0  4160.3     .16       0  4282.2     .05       0
  4798.6     .16       0    4969     .07       0  5027.8     .16       0
    5028      .1       0  5219.8     .05       0  5572.3     .16       0
  5966.7     .05       0  6323.6      .1       0  6339.3     .05       0
  6461.5      .1       0
#Block Obstruct= 2 , 0
                         5454.83          351.58
Bank Sta=4994.3,5000.3
XS Rating Curve= 0 ,0
Exp/Cntr=0.3,0.1

Type RM Length L Ch R = 1 ,24124   ,867,867,867
BEGIN DESCRIPTION:
COBB BRANCH 2 34.0
END DESCRIPTION:
XS GIS Cut Line= 3
      3560674.55     10332400.47      3559692.11     10331741.64
       3558749.7      10331108.2
#Sta/Elev= 30
  3847.8  354.83  3984.8  353.19  4092.8   350.1  4179.9  348.63    4504  346.74
    4588  346.99  4621.8   346.4  4790.3  345.87  4858.1  345.26  4981.2  342.45
  4999.2  339.78  5001.9  339.28  5005.2  339.78  5008.2  341.92  5027.7  344.34
  5167.2  345.49  5197.2  346.33  5239.2  345.28  5347.2  344.31    5356  342.47
  5362.2  342.52  5368.2  343.75  5413.2  346.03  5454.8  349.72  5635.2   354.1
  5896.9  358.56  5897.8  358.59  6049.6  360.41  6083.8  360.94  6166.2  361.97
#Mann= 12 ,-1 , 0
  3847.8     .05       0    4588      .1       0  4621.8     .05       0
  4790.3     .16       0  4981.2     .07       0  5027.7     .16       0
  5239.2     .16       0  5454.8     .05       0  5896.9      .1       0
  5897.8     .05       0  6049.6      .1       0  6083.8     .05       0
#Block Obstruct= 2 , 0
                         5194.32          346.38
Bank Sta=4999.2,5005.2
XS Rating Curve= 0 ,0
Exp/Cntr=0.3,0.1

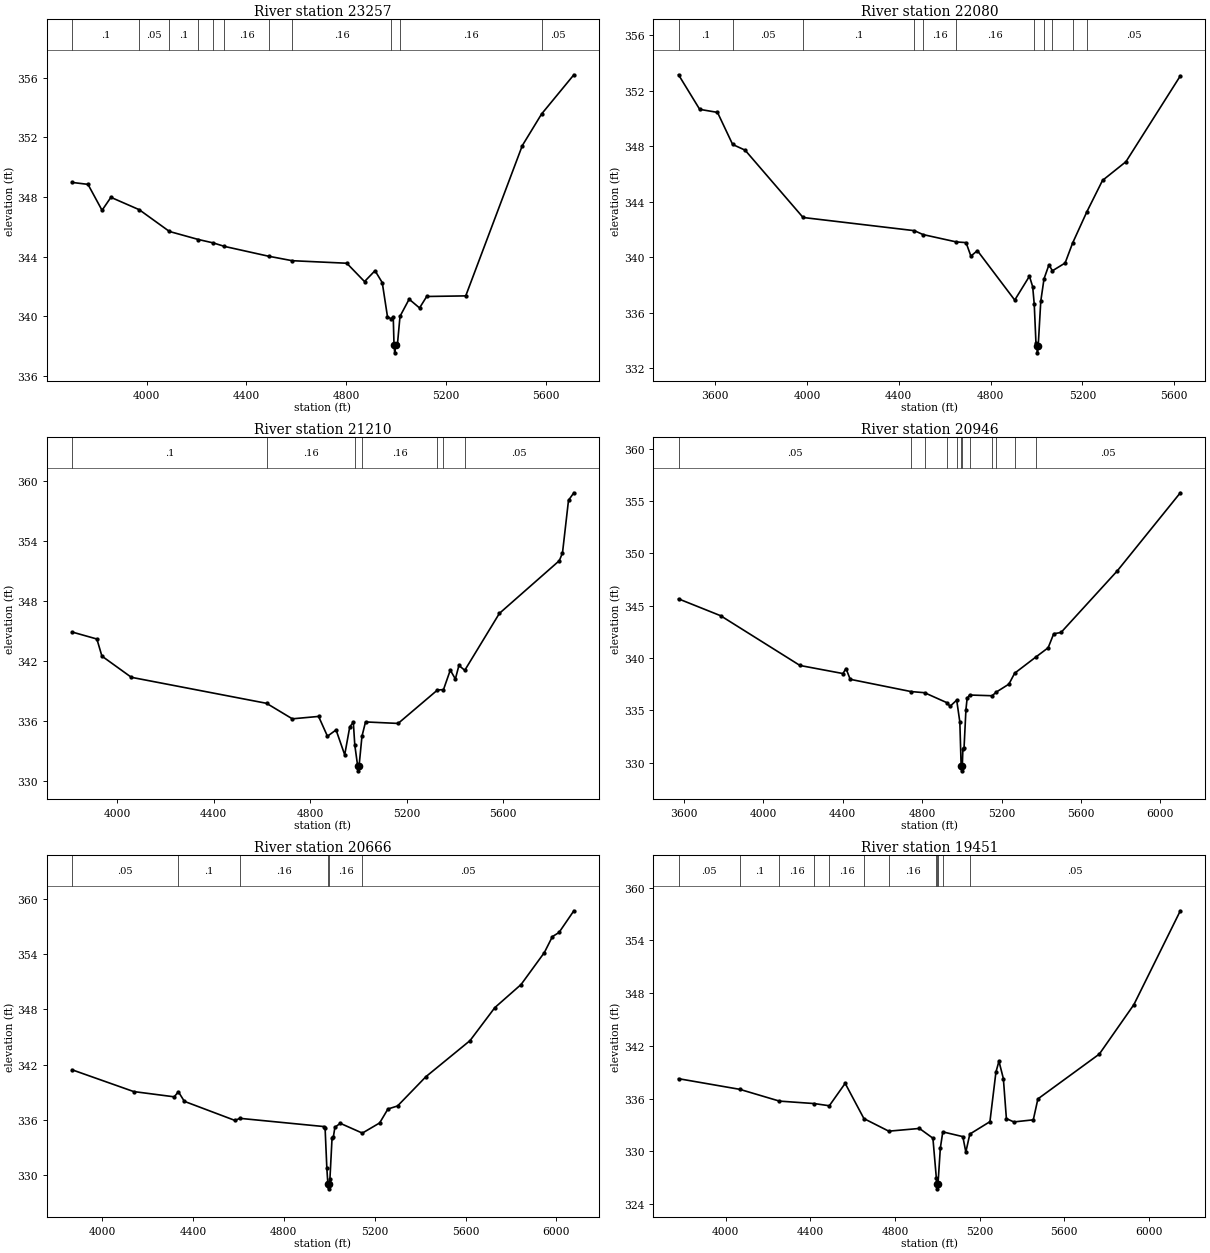
Type RM Length L Ch R = 1 ,23257   ,1177,1177,1177
BEGIN DESCRIPTION:
COBB BRANCH 2 33.0
END DESCRIPTION:
XS GIS Cut Line= 3
      3561243.89     10331957.68      3560192.11     10331191.64
      3559642.11     10330741.65
#Sta/Elev= 30
  3701.1  348.97  3764.9  348.84  3821.3   347.1  3856.8  347.97  3970.4  347.14
  4091.5  345.68  4207.9  345.14  4267.9  344.91  4311.8  344.68    4489  344.02
  4583.6  343.72  4802.5  343.55  4873.6  342.32  4915.7  343.05  4944.7  342.25
  4965.6  339.97  4980.3  339.82  4988.8  339.94  4991.9  338.04  4994.7  337.54
  4997.9  338.04  5005.5   338.1  5015.9  339.99  5052.5  341.14  5094.2  340.55
  5122.9  341.32  5279.4  341.36  5506.2  351.44  5583.5  353.56  5712.9  356.19
#Mann= 11 ,-1 , 0
  3701.1      .1       0  3970.4     .05       0  4091.5      .1       0
  4207.9     .05       0  4267.9      .1       0  4311.8     .16       0
    4489      .1       0  4583.6     .16       0  4980.3     .07       0
  5015.9     .16       0  5583.5     .05       0
Bank Sta=4991.9,4997.9
XS Rating Curve= 0 ,0
Exp/Cntr=0.3,0.1

Type RM Length L Ch R = 1 ,22080   ,870,870,870
BEGIN DESCRIPTION:
COBB BRANCH 2 31.0
END DESCRIPTION:
XS GIS Cut Line= 3
      3561642.08     10331641.62      3560307.74     10330396.46
      3560107.81     10330096.56
#Sta/Elev= 30
    3441  353.14  3533.1  350.65  3610.7  350.43  3676.7  348.12  3730.9  347.71
  3983.4  342.86  4468.3  341.91  4505.8  341.63  4650.8   341.1  4693.3  341.05
  4714.3  340.08  4742.7  340.47  4905.3  336.91  4969.3  338.63  4983.5  337.87
  4990.3   336.6  4997.7  333.82  5001.5  333.61  5004.3  333.11  5007.5  333.61
  5018.7  336.83  5032.8  338.44  5054.3  339.45  5069.4  339.02  5124.7  339.58
  5157.4  341.02  5219.7  343.28  5287.6  345.53  5389.7  346.88  5626.5  353.06
#Mann= 11 ,-1 , 0
    3441      .1       0  3676.7     .05       0  3983.4      .1       0
  4468.3     .05       0  4505.8     .16       0  4650.8     .16       0
  4990.3     .07       0  5032.8     .16       0  5069.4     .05       0
  5157.4      .1       0  5219.7     .05       0
Bank Sta=5001.5,5007.5
XS Rating Curve= 0 ,0
Exp/Cntr=0.3,0.1

Type RM Length L Ch R = 1 ,21210   ,264,264,264
BEGIN DESCRIPTION:
COBB BRANCH 2 30.0
END DESCRIPTION:
XS GIS Cut Line= 3
      3562039.12     10330837.12      3560684.26     10329888.61
      3560285.65     10329739.13
#Sta/Elev= 30
  3812.8  344.91  3915.6  344.21  3936.5   342.5  4058.6  340.38  4618.9  337.78
  4725.6  336.23  4834.5  336.47  4871.2  334.49  4906.9  335.12  4942.7  332.63
  4963.6  335.42  4978.4   335.9  4984.5  333.61  4996.3  331.53  4999.1  331.03
  5002.3  331.53  5014.2  334.48    5029  335.92  5164.1  335.77  5327.1  339.11
  5352.1  339.15  5380.3   341.1  5401.3  340.21  5416.1  341.57  5440.3  341.08
  5583.7  346.77  5832.1  352.04  5845.3  352.82  5870.2  358.08  5892.4  358.83
#Mann= 7 ,-1 , 0
  3812.8      .1       0  4618.9     .16       0  4984.5     .07       0
  5014.2     .16       0  5327.1     .05       0  5352.1     .16       0
  5440.3     .05       0
Bank Sta=4996.3,5002.3
XS Rating Curve= 0 ,0
Exp/Cntr=0.3,0.1

Type RM Length L Ch R = 1 ,20946   ,280,280,280
BEGIN DESCRIPTION:
Mapping XS 5b191510
END DESCRIPTION:
XS GIS Cut Line= 2
      3562444.55     10330709.94      3560296.14     10329380.63
#Sta/Elev= 30
  3573.6  345.65  3785.6  344.04  4185.1  339.29  4401.3  338.52  4416.7     339
  4437.9  337.97    4744   336.8  4812.2  336.69  4925.6  335.73  4940.6  335.39
  4974.1  335.98  4989.9  333.89  4996.4  329.73  4999.1  329.23  5002.4  329.73
  5005.3  331.35  5011.1  331.43  5020.6  335.07  5026.5  336.14    5039  336.47
  5152.4   336.4  5173.4  336.75  5236.9  337.51  5265.8  338.55  5372.8   340.1
  5434.5  340.98  5462.6  342.32  5499.3  342.44  5782.9  348.33    6100  355.78
#Mann= 12 ,-1 , 0
  3573.6     .05       0    4744      .1       0  4812.2     .05       0
  4925.6     .08       0  4974.1     .16       0  4996.4     .07       0
  5002.4     .16       0    5039     .05       0  5152.4     .08       0
  5173.4     .05       0  5265.8     .08       0  5372.8     .05       0
Bank Sta=4996.4,5002.4
XS Rating Curve= 0 ,0
Exp/Cntr=0.3,0.1

Type RM Length L Ch R = 1 ,20666   ,1215,1215,1215
BEGIN DESCRIPTION:
COBB BRANCH 2 29.0
END DESCRIPTION:
XS GIS Cut Line= 3
      3562355.34     10330240.64      3561569.17     10329852.08
      3560442.14     10329141.67
#Sta/Elev= 30
  3867.5  341.44  4138.8  339.08  4317.3  338.51  4335.5  339.06  4361.9  338.02
    4585  335.95    4606  336.18  4975.6  335.29  4981.5   335.1  4989.2  330.78
  4993.8  329.04  4996.5  328.54  4999.8  329.04  5002.7  329.59  5012.1  334.04
    5018  334.18  5024.7  335.21  5048.3  335.64  5145.5  334.58  5221.6  335.68
  5258.1  337.19  5300.5  337.52  5425.2  340.69  5619.5   344.6  5728.9  348.18
  5844.3  350.68  5946.7  354.14  5982.2  355.87  6011.4  356.32  6076.7  358.67
#Mann= 6 ,-1 , 0
  3867.5     .05       0  4335.5      .1       0    4606     .16       0
  4993.8     .07       0  4999.8     .16       0  5145.5     .05       0
Bank Sta=4993.8,4999.8
XS Rating Curve= 0 ,0
Exp/Cntr=0.3,0.1

Type RM Length L Ch R = 1 ,19451   ,896,896,896
BEGIN DESCRIPTION:
COBB BRANCH 2 28.0
END DESCRIPTION:
XS GIS Cut Line= 3
      3562635.51     10329725.56       3561822.2     10329156.25
       3560792.1     10328241.64
#Sta/Elev= 30
  3777.9  338.27  4066.9  337.06  4254.4  335.72  4418.9  335.44  4490.1  335.19
    4565  337.74  4653.6  333.73    4771   332.3  4915.9  332.61  4979.5   331.5
  4995.7  326.97  4997.4  326.24  5000.2  325.74  5003.4  326.24  5014.6  330.39
  5026.2  332.22  5120.8  331.68    5135  329.93  5153.9  331.97  5248.8  333.38
  5277.2  339.02  5291.4  340.26  5312.3  338.28  5326.6  333.73  5361.7  333.35
  5453.7  333.59  5475.4  335.97  5765.6  341.07  5928.7  346.69  6148.2  357.37
#Mann= 12 ,-1 , 0
  3777.9     .05       0  4066.9      .1       0  4254.4     .16       0
  4418.9     .05       0  4490.1     .16       0  4653.6     .05       0
    4771     .16       0  4995.7     .12       0  4997.4     .07       0
  5003.4     .12       0  5026.2     .16       0  5153.9     .05       0
Bank Sta=4997.4,5003.4
XS Rating Curve= 0 ,0
Exp/Cntr=0.3,0.1

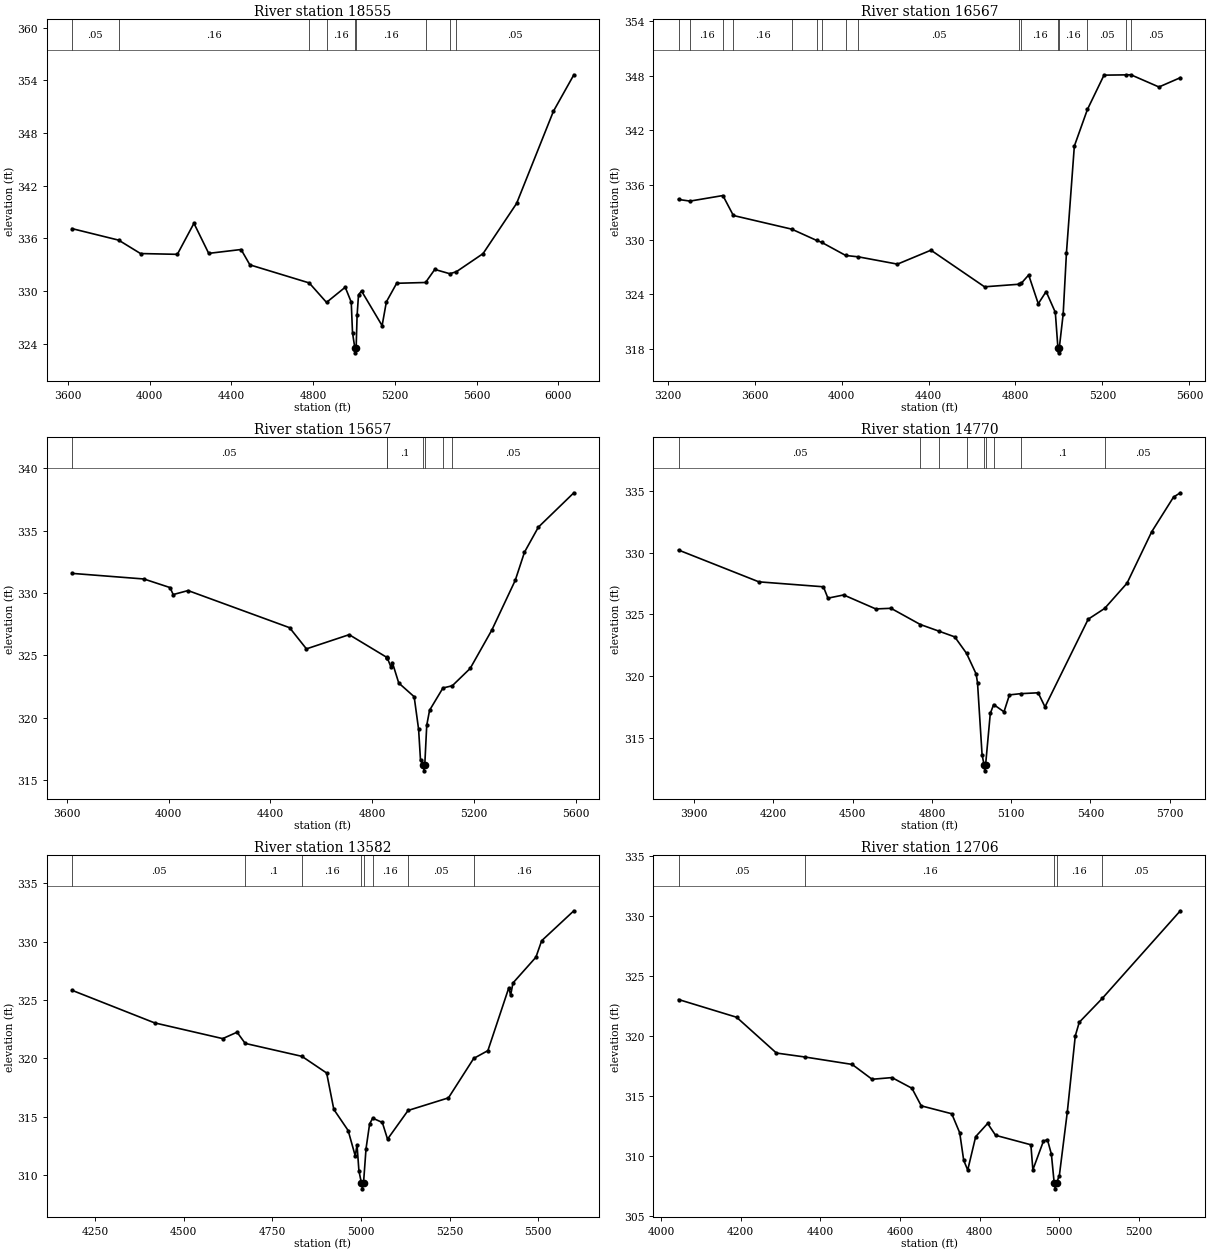
Type RM Length L Ch R = 1 ,18555   ,1988,1988,1988
BEGIN DESCRIPTION:
COBB BRANCH 2 27.0
END DESCRIPTION:
XS GIS Cut Line= 3
      3562888.56     10329490.63      3562301.15       10328605.
      3561171.52     10327791.67
#Sta/Elev= 30
  3620.5  337.11  3848.2   335.8  3955.3  334.27  4135.5  334.18  4216.7  337.72
  4288.9  334.29  4447.3  334.73  4490.4  332.98  4780.6  330.92  4865.2   328.7
  4956.8  330.43  4986.2  328.73  4992.4  325.24  5004.1  323.45  5006.8  322.95
  5010.1  323.45  5014.8  327.21  5021.8  329.57  5036.5     330  5137.2  326.05
    5158  328.76  5208.4  330.88  5349.7  330.97  5394.9  332.46  5468.1  331.97
    5500  332.19  5630.9  334.26    5795  339.98  5975.4   350.5  6075.2  354.65
#Mann= 9 ,-1 , 0
  3620.5     .05       0  3848.2     .16       0  4780.6      .1       0
  4865.2     .16       0  5004.1     .07       0  5010.1     .16       0
  5349.7     .05       0  5468.1      .1       0    5500     .05       0
Bank Sta=5004.1,5010.1
XS Rating Curve= 0 ,0
Exp/Cntr=0.3,0.1

Type RM Length L Ch R = 1 ,16567   ,910,910,910
BEGIN DESCRIPTION:
COBB BRANCH 2 26.0
END DESCRIPTION:
XS GIS Cut Line= 3
      3563069.27     10328722.46      3562463.82     10327629.03
      3561578.21     10327050.67
#Sta/Elev= 30
  3250.4   334.4  3303.2  334.22  3454.4  334.83  3502.5  332.64    3771  331.14
  3885.7   329.9  3907.9   329.7  4019.3  328.25  4077.4   328.1  4257.2   327.3
  4411.2  328.83  4657.6  324.81  4814.6  325.09  4826.8   325.2  4860.6  326.11
  4904.7  322.95  4940.9  324.29  4983.1  322.01  4995.2  318.06  4997.9  317.56
  5001.2  318.06  5019.3  321.83  5034.4  328.57  5070.6  340.26  5130.7  344.28
    5207  348.05  5306.5  348.08  5330.7  348.09  5459.7  346.75    5558  347.77
#Mann= 16 ,-1 , 0
  3250.4     .05       0  3303.2     .16       0  3454.4     .05       0
  3502.5     .16       0    3771     .05       0  3885.7      .1       0
  3907.9     .05       0  4019.3      .1       0  4077.4     .05       0
  4814.6      .1       0  4826.8     .16       0  4995.2     .07       0
  5001.2     .16       0  5130.7     .05       0  5306.5      .1       0
  5330.7     .05       0
Bank Sta=4995.2,5001.2
XS Rating Curve= 0 ,0
Exp/Cntr=0.3,0.1

Type RM Length L Ch R = 1 ,15657   ,887,887,887
BEGIN DESCRIPTION:
COBB BRANCH 2 25.0
END DESCRIPTION:
XS GIS Cut Line= 3
      3563466.89     10328379.07      3562933.73     10327421.18
      3562626.81     10326599.71
#Sta/Elev= 30
  3619.8  331.57  3902.2  331.12  4005.1  330.43  4017.4  329.87    4076  330.19
  4475.2  327.21  4541.4  325.51  4709.5  326.65  4856.5  324.84  4858.7  324.81
  4859.1   324.8  4874.1  324.03  4879.4  324.41  4904.4  322.77    4965  321.67
  4982.5  319.05    4990  316.57  5000.8  316.22  5003.6  315.72  5006.8  316.22
  5014.5  319.38  5025.6  320.58  5078.2  322.37  5114.9  322.55  5185.3  323.94
  5270.7  327.03  5362.5  331.01  5398.8  333.27  5453.4  335.28    5593  338.04
#Mann= 8 ,-1 , 0
  3619.8     .05       0  4856.5      .1       0  4858.7     .16       0
  4859.1      .1       0  5000.8     .07       0  5006.8      .1       0
  5078.2     .16       0  5114.9     .05       0
Bank Sta=5000.8,5006.8
XS Rating Curve= 0 ,0
Exp/Cntr=0.3,0.1

Type RM Length L Ch R = 1 ,14770   ,1188,1188,1188
BEGIN DESCRIPTION:
COBB BRANCH 2 23.0
END DESCRIPTION:
XS GIS Cut Line= 3
      3564009.11     10328117.01      3563629.56     10327312.74
      3563367.49     10326336.74
#Sta/Elev= 30
  3840.5   330.2  4144.6  327.63    4389  327.23  4406.2  326.31  4465.7  326.57
  4587.3  325.44    4645  325.49    4756  324.18  4828.1  323.63  4886.3  323.18
  4930.9  321.85  4967.3  320.18  4972.5  319.47  4989.8  313.65  4997.2  312.85
  4999.9  312.35  5003.2  312.85  5020.9  316.99  5033.6  317.71  5072.7  317.12
  5093.4  318.49  5136.4  318.59  5202.1  318.66    5228  317.52  5391.6  324.61
  5453.9  325.48  5538.6  327.52  5631.8  331.67  5714.6  334.48  5740.4  334.83
#Mann= 9 ,-1 , 0
  3840.5     .05       0    4756      .1       0  4828.1     .16       0
  4930.9      .1       0  4997.2     .07       0  5003.2      .1       0
  5033.6     .05       0  5136.4      .1       0  5453.9     .05       0
Bank Sta=4997.2,5003.2
XS Rating Curve= 0 ,0
Exp/Cntr=0.3,0.1

Type RM Length L Ch R = 1 ,13582   ,876,876,876
BEGIN DESCRIPTION:
COBB BRANCH 2 21.0
END DESCRIPTION:
XS GIS Cut Line= 3
      3564392.11     10327591.66      3564316.68     10327079.02
      3564192.11     10326191.68
#Sta/Elev= 30
  4185.9  325.84  4418.4  323.05  4610.4   321.7  4650.9  322.25  4673.8  321.29
  4833.7  320.18  4903.4  318.75  4923.6  315.63    4964  313.82  4983.9  311.65
    4989  312.58  4994.3  310.38  5001.3  309.32  5004.1  308.82  5007.3  309.32
  5014.4  312.27  5024.5  314.39  5033.2  314.88  5060.3  314.51    5075  313.08
  5132.9  315.54  5246.7  316.62  5317.8     320  5357.8  320.67  5416.8  326.06
  5421.9  325.42  5428.5  326.47  5493.2  328.68  5509.3  330.09  5600.1  332.66
#Mann= 8 ,-1 , 0
  4185.9     .05       0  4673.8      .1       0  4833.7     .16       0
  5001.3     .07       0  5007.3     .16       0  5033.2     .16       0
  5132.9     .05       0  5317.8     .16       0
Bank Sta=5001.3,5007.3
XS Rating Curve= 0 ,0
Exp/Cntr=0.3,0.1

Type RM Length L Ch R = 1 ,12706   ,1295,1295,1295
BEGIN DESCRIPTION:
COBB BRANCH 2 19.0
END DESCRIPTION:
XS GIS Cut Line= 3
      3564785.43     10327287.33      3564824.74     10326185.39
      3564774.95     10326036.01
#Sta/Elev= 30
  4043.9  323.04  4189.7  321.56  4289.7  318.57  4361.2  318.24  4479.9  317.62
  4529.9  316.38  4579.9  316.52    4630  315.63  4653.4  314.16    4730   313.5
    4750  311.91    4760  309.61  4770.1   308.8  4790.1  311.59  4820.1  312.69
  4840.1   311.7  4928.7  310.91  4933.7  308.82  4960.2  311.21  4970.2  311.34
  4980.2  310.13  4987.2  307.73  4989.9  307.23  4993.2  307.73  5000.2  308.34
  5020.2  313.65  5040.2     320  5050.2  321.14  5107.9  323.13    5304  330.45
#Mann= 5 ,-1 , 0
  4043.9     .05       0  4361.2     .16       0  4987.2     .07       0
  4993.2     .16       0  5107.9     .05       0
Bank Sta=4987.2,4993.2
XS Rating Curve= 0 ,0
Exp/Cntr=0.3,0.1

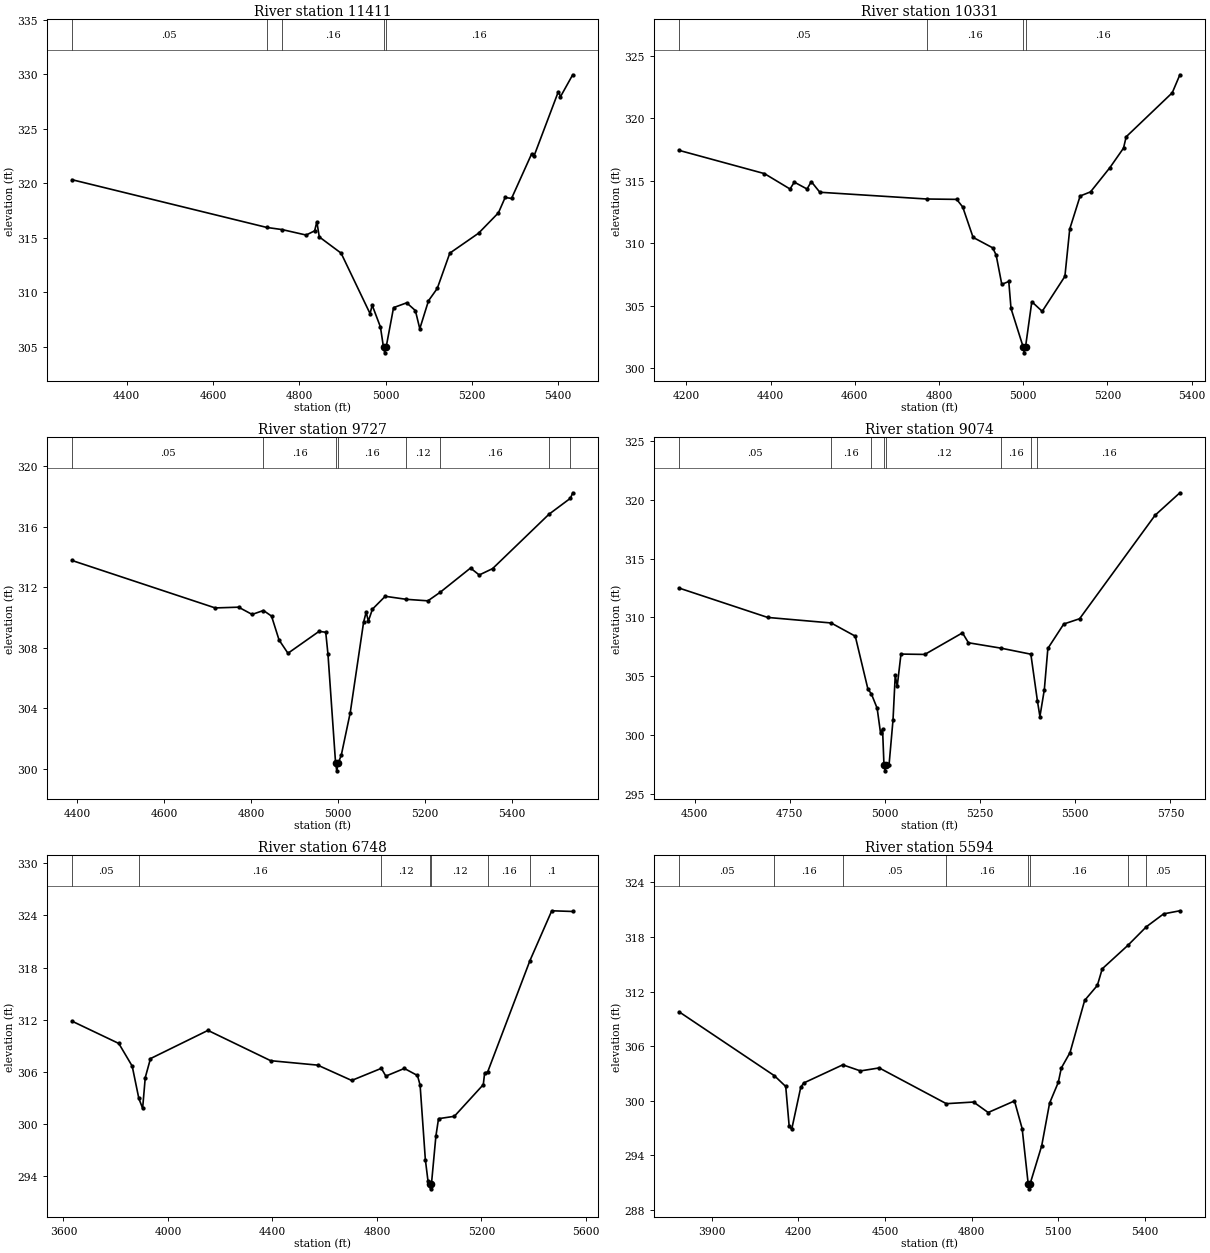
Type RM Length L Ch R = 1 ,11411   ,1080,1080,1080
BEGIN DESCRIPTION:
COBB BRANCH 2 17.0
END DESCRIPTION:
XS GIS Cut Line= 3
      3565410.43     10327243.95      3565393.07     10326714.43
      3565292.11     10326091.67
#Sta/Elev= 30
  4273.2  320.32  4724.6  315.94  4760.5  315.74    4816  315.24  4835.7  315.63
  4840.8  316.46  4846.4  315.07    4897  313.58  4964.1  308.03  4969.1   308.8
  4988.2   306.8  4995.3  304.93  4998.1  304.43  5001.3  304.93  5018.6  308.58
    5049  309.02  5069.2  308.31  5079.4  306.64  5099.6  309.21  5119.9  310.34
    5149  313.58  5215.7  315.41  5261.7  317.28  5277.3  318.69  5292.1   318.6
  5338.9  322.71    5344  322.47  5400.6   328.4  5405.6  327.94  5433.9  329.95
#Mann= 5 ,-1 , 0
  4273.2     .05       0  4724.6      .1       0  4760.5     .16       0
  4995.3     .07       0  5001.3     .16       0
Bank Sta=4995.3,5001.3
XS Rating Curve= 0 ,0
Exp/Cntr=0.3,0.1

Type RM Length L Ch R = 1 ,10331   ,604,604,604
BEGIN DESCRIPTION:
COBB BRANCH 2 15.0
END DESCRIPTION:
XS GIS Cut Line= 3
      3566154.94     10327122.03      3566061.47     10326497.42
      3565861.84     10325976.64
#Sta/Elev= 30
  4182.7  317.43  4385.3  315.57    4446  314.34  4456.1  314.89  4486.4  314.34
  4496.5  314.93  4516.8  314.08  4770.4  313.54  4841.9  313.51  4856.2   312.9
  4880.8  310.47  4927.5  309.63  4935.6  309.05    4949  306.71  4965.6  306.94
  4970.9  304.78  4999.5  301.73  5002.3  301.23  5005.5  301.73  5020.3  305.32
    5045  304.55  5098.9  307.35  5110.4  311.14  5135.1  313.78  5159.8  314.11
    5206  316.06  5238.1  317.61  5244.5  318.52  5353.9  322.04    5372  323.48
#Mann= 4 ,-1 , 0
  4182.7     .05       0  4770.4     .16       0  4999.5     .07       0
  5005.5     .16       0
Bank Sta=4999.5,5005.5
XS Rating Curve= 0 ,0
Exp/Cntr=0.3,0.1

Type RM Length L Ch R = 1 ,9727    ,653,653,653
BEGIN DESCRIPTION:
COBB BRANCH 2 13.0
END DESCRIPTION:
XS GIS Cut Line= 3
      3566695.16     10326801.28      3566573.63     10326358.53
      3566426.06     10325681.45
#Sta/Elev= 30
  4387.5  313.78    4717  310.64  4770.8  310.69  4801.9  310.21    4828  310.47
  4846.6   310.1  4863.9  308.52  4884.4  307.64    4956  309.09  4971.3  309.03
  4976.5  307.57    4994  300.36  4996.7  299.86    5000  300.36  5007.2  300.91
  5027.7  303.71  5058.4  309.69  5064.3  310.36  5069.4  309.77  5078.8  310.56
  5108.2  311.41  5156.7  311.21  5206.4  311.11  5234.4  311.67  5304.5  313.28
  5324.5  312.82  5355.2  313.24    5485  316.84  5534.5   317.9  5539.6  318.26
#Mann= 8 ,-1 , 0
  4387.5     .05       0    4828     .16       0    4994     .07       0
    5000     .16       0  5156.7     .12       0  5234.4     .16       0
    5485      .1       0  5534.5     .16       0
Bank Sta=4994,5000
XS Rating Curve= 0 ,0
Exp/Cntr=0.3,0.1

Type RM Length L Ch R = 1 ,9074    ,2326,2326,2326
BEGIN DESCRIPTION:
COBB BRANCH 2 12.0
END DESCRIPTION:
XS GIS Cut Line= 3
      3567159.12     10326773.98      3567172.58     10326436.66
       3566894.8     10325499.13
#Sta/Elev= 30
  4459.4  312.49  4691.9     310  4858.6  309.53    4922  308.41  4955.3  303.91
  4964.2  303.52  4979.5  302.29  4988.5  300.16  4993.7  300.54  4997.4  297.48
  5000.1  296.98  5003.4  297.48  5010.8   297.5  5021.2  301.31    5027  305.08
  5032.2  304.16  5042.1  306.89  5104.7  306.86  5203.6  308.69  5219.4  307.85
  5305.2  307.39  5383.3  306.88  5400.6   302.9  5407.1  301.59  5418.7  303.87
    5428  307.37  5469.7  309.44  5511.4  309.89  5709.6  318.67  5774.8  320.58
#Mann= 8 ,-1 , 0
  4459.4     .05       0  4858.6     .16       0  4964.2     .12       0
  4997.4     .07       0  5003.4     .12       0  5305.2     .16       0
  5383.3     .12       0  5400.6     .16       0
Bank Sta=4997.4,5003.4
XS Rating Curve= 0 ,0
Exp/Cntr=0.3,0.1

Type RM Length L Ch R = 1 ,6748    ,1154,1154,1154
BEGIN DESCRIPTION:
COBB BRANCH 2 10.0
END DESCRIPTION:
XS GIS Cut Line= 3
      3567762.86     10327191.88      3567728.14     10326089.43
      3567623.97     10325282.12
#Sta/Elev= 30
  3632.7  311.84  3811.8  309.28  3863.1  306.68  3888.6  302.96  3903.1  301.83
  3913.1  305.36  3933.1  307.54  4153.2  310.78  4393.3   307.3  4573.4  306.79
  4703.5  305.03  4816.9  306.42  4834.3  305.53    4905  306.41  4955.3   305.6
  4965.4   304.5  4985.5  295.94  4995.6  293.49  5002.7  293.08  5005.5  292.58
  5008.7  293.08  5025.9  298.64    5036  300.64  5096.5  300.91  5207.4  304.55
  5212.5  305.89    5224     306    5386   318.8  5469.5  324.52  5549.7  324.44
#Mann= 7 ,-1 , 0
  3632.7     .05       0  3888.6     .16       0  4816.9     .12       0
  5002.7     .07       0  5008.7     .12       0    5224     .16       0
    5386      .1       0
Bank Sta=5002.7,5008.7
XS Rating Curve= 0 ,0
Exp/Cntr=0.3,0.1

Type RM Length L Ch R = 1 ,5594    ,910,910,910
BEGIN DESCRIPTION:
COBB BRANCH 2 9.0
END DESCRIPTION:
XS GIS Cut Line= 3
      3568483.34     10327018.24      3568240.29     10326098.11
      3568361.73     10325326.09
#Sta/Elev= 30
  3787.4  309.77  4117.1  302.75  4156.2  301.57    4168  297.26  4176.9  296.86
  4208.2  301.48  4218.3  301.95  4353.7  303.95  4414.8  303.28  4479.8  303.61
  4712.2  299.68  4806.4  299.86    4857  298.71  4948.1  299.98  4974.7  296.93
  4995.7  290.82  4998.5  290.32  5001.7  290.82  5042.3  295.05  5069.6  299.74
  5099.8  302.03  5110.1  303.59  5140.4   305.3    5191  311.03    5235  312.68
  5251.8   314.5  5340.6  317.08  5404.8  319.13  5464.4  320.54  5520.6  320.88
#Mann= 8 ,-1 , 0
  3787.4     .05       0  4117.1     .16       0  4353.7     .05       0
  4712.2     .16       0  4995.7     .07       0  5001.7     .16       0
  5340.6      .1       0  5404.8     .05       0
Bank Sta=4995.7,5001.7
XS Rating Curve= 0 ,0
Exp/Cntr=0.3,0.1