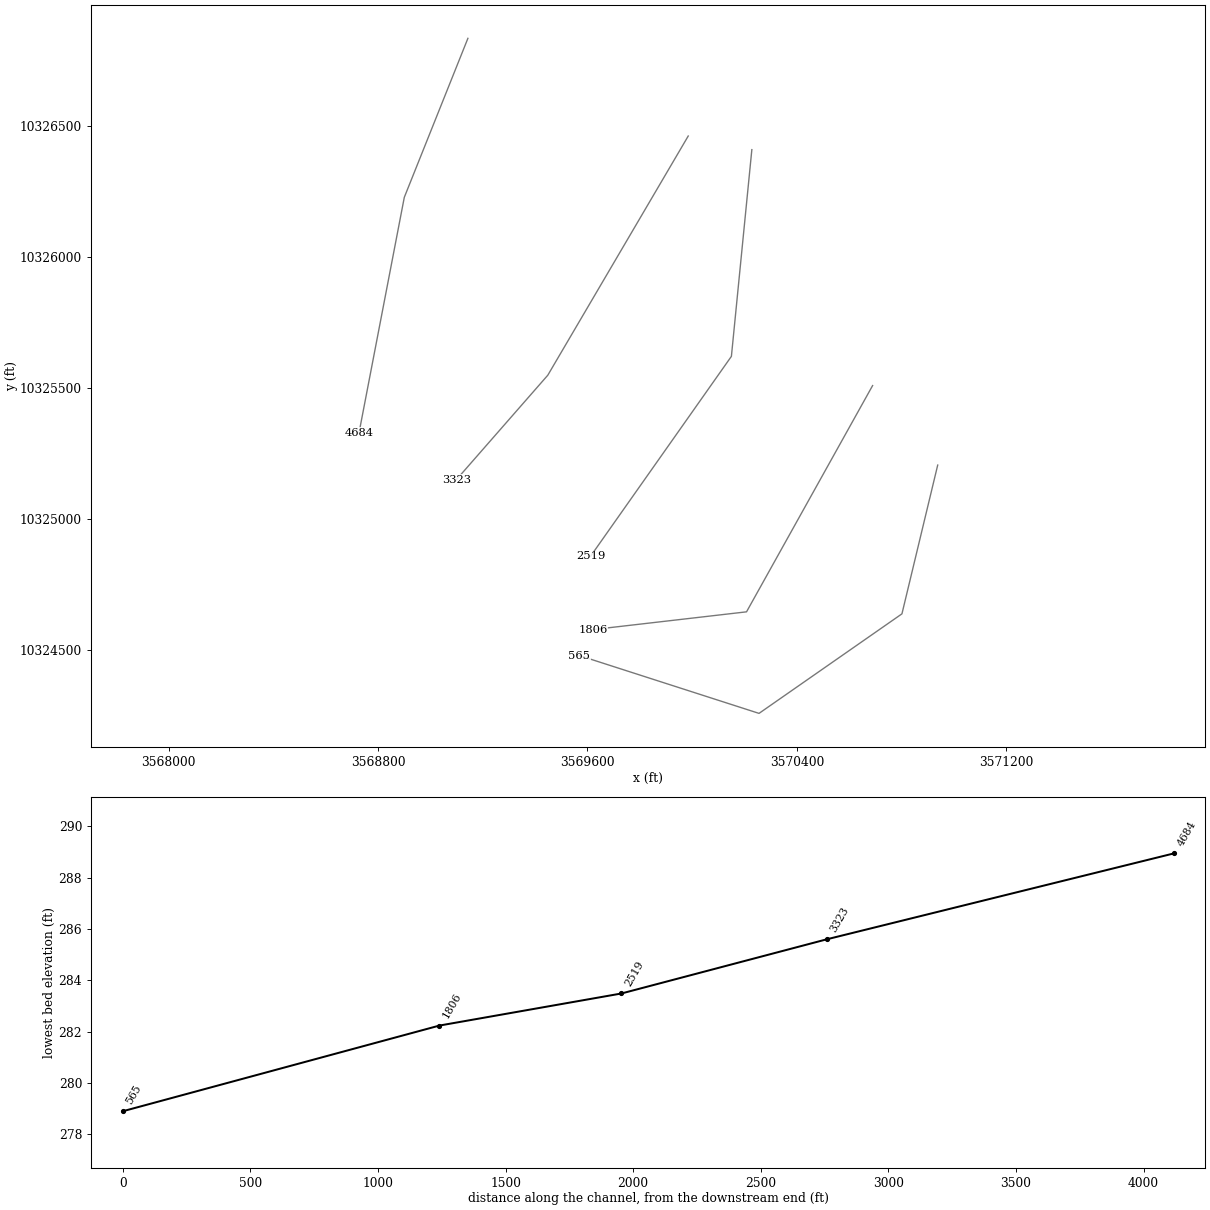
HEC-RAS study COBB BRANCH 2.prj: COBB BRANCH 2 Base Level Engineering

--- COBB BRANCH 2.g01 (geometry) --- (continued)

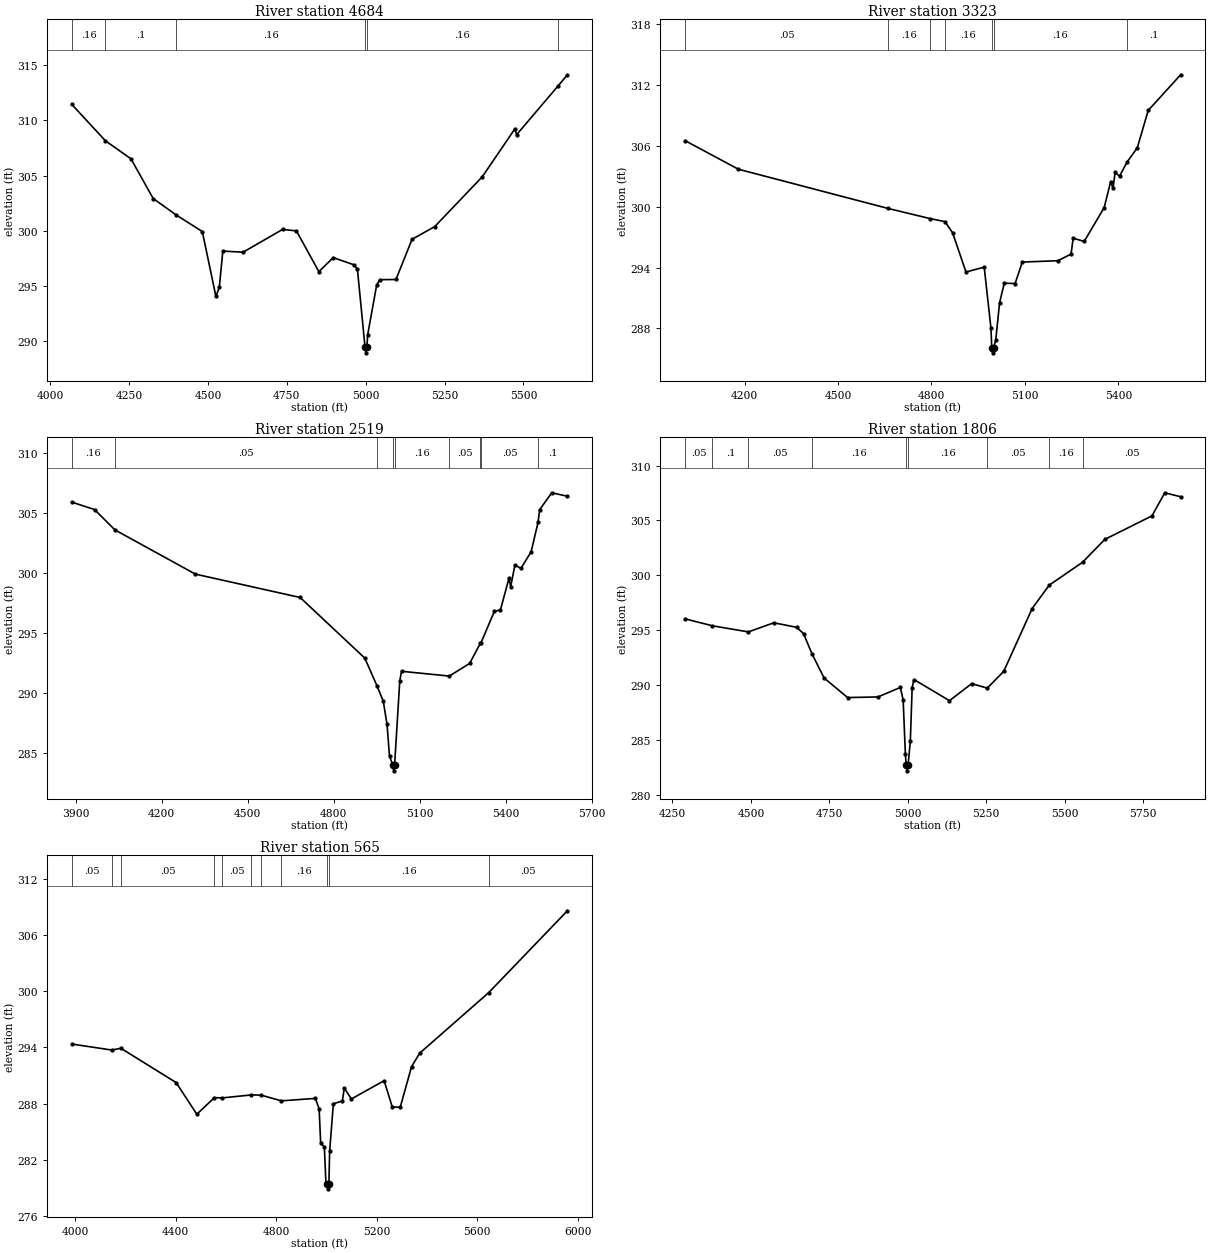
Type RM Length L Ch R = 1 ,4684    ,1361,1361,1361
BEGIN DESCRIPTION:
COBB BRANCH 2 7.0
END DESCRIPTION:
XS GIS Cut Line= 3
      3569143.07     10326835.95      3568900.01     10326228.32
      3568726.87     10325327.96
#Sta/Elev= 30
  4068.1  311.44  4174.7  308.15  4255.8  306.51  4326.2  302.92  4399.1  301.43
    4482  299.93  4525.1  294.05  4535.9  294.89    4547  298.16  4611.3  298.06
  4736.2  300.12  4780.3  299.99  4851.5   296.3  4897.1  297.57  4963.6  296.91
  4973.7  296.52  4997.9  289.45  5000.7  288.95  5003.9  289.45    5006  290.56
  5034.8   295.1    5045  295.57  5095.9  295.59  5146.9  299.23  5218.9  300.38
  5369.6  304.89  5472.7  309.22  5478.5   308.7  5609.2  313.09  5639.4  314.12
#Mann= 6 ,-1 , 0
  4068.1     .16       0  4174.7      .1       0  4399.1     .16       0
  4997.9     .07       0  5003.9     .16       0  5609.2      .1       0
Bank Sta=4997.9,5003.9
XS Rating Curve= 0 ,0
Exp/Cntr=0.3,0.1

Type RM Length L Ch R = 1 ,3323    ,804,804,804
BEGIN DESCRIPTION:
COBB BRANCH 2 5.0
END DESCRIPTION:
XS GIS Cut Line= 3
      3569985.06     10326462.66      3569448.36     10325548.59
      3569098.36     10325148.59
#Sta/Elev= 30
  4008.5   306.5    4180  303.68  4660.3  299.82  4795.4  298.82  4843.1  298.52
  4867.7  297.43  4910.7  293.56  4969.3  294.04  4990.8  288.06  4993.6   286.1
  4996.3   285.6  4999.6   286.1  5006.4  286.87  5018.6  290.52  5033.7  292.46
  5068.5  292.42  5091.6  294.54  5205.5  294.67  5248.2  295.32  5254.9  296.89
  5290.3  296.57  5354.5   299.9  5375.4  302.46    5383  301.79  5389.6  303.37
  5403.9  302.99  5427.7  304.38  5460.8  305.79  5495.9  309.47    5600  312.98
#Mann= 7 ,-1 , 0
  4008.5     .05       0  4660.3     .16       0  4795.4     .05       0
  4843.1     .16       0  4993.6     .07       0  4999.6     .16       0
  5427.7      .1       0
Bank Sta=4993.6,4999.6
XS Rating Curve= 0 ,0
Exp/Cntr=0.3,0.1

Type RM Length L Ch R = 1 ,2519    ,713,713,713
BEGIN DESCRIPTION:
COBB BRANCH 2 4.0
END DESCRIPTION:
XS GIS Cut Line= 3
      3570228.14     10326410.61      3570150.01     10325620.68
      3569611.83     10324856.81
#Sta/Elev= 30
  3886.2  305.92  3965.6   305.3  4036.8   303.6  4317.3  299.91  4682.5  297.96
  4907.9   292.9  4950.6  290.58  4972.4   289.3  4985.5  287.36  4994.1   284.7
  5005.9  283.99  5008.7  283.49  5011.9  283.99  5029.9     291    5036   291.8
  5202.6   291.4  5273.7  292.46  5310.9  294.14  5312.6  294.15  5359.9  296.81
  5380.9  296.92  5410.5  299.55  5416.6  298.87  5431.4  300.67  5452.3  300.39
    5488  301.78  5512.2  304.26  5517.6  305.28  5559.6   306.7  5614.4  306.41
#Mann= 9 ,-1 , 0
  3886.2     .16       0  4036.8     .05       0  4950.6     .16       0
  5005.9     .07       0  5011.9     .16       0  5202.6     .05       0
  5310.9     .16       0  5312.6     .05       0  5512.2      .1       0
Bank Sta=5005.9,5011.9
XS Rating Curve= 0 ,0
Exp/Cntr=0.3,0.1

Type RM Length L Ch R = 1 ,1806    ,1241,1241,1241
BEGIN DESCRIPTION:
Mapping XS 549b9a5b
END DESCRIPTION:
XS GIS Cut Line= 3
      3570689.61     10325508.98      3570207.81     10324644.35
      3569621.91     10324576.65
#Sta/Elev= 30
  4289.9  296.06  4376.9  295.43  4491.8  294.87    4573   295.7  4645.9  295.29
  4667.6  294.72  4694.8  292.87  4733.3  290.68  4808.2   288.9    4905  288.96
  4976.2  289.82  4985.2  288.69  4992.2   283.8  4994.9  282.74  4997.7  282.24
  5000.9  282.74  5008.1  284.96  5013.9  289.81  5019.7  290.54  5132.8  288.62
  5203.7  290.17  5253.2  289.76  5305.6  291.28  5396.2  296.99  5450.6  299.12
  5557.3  301.21  5627.7  303.28  5778.1  305.42    5819  307.52  5869.5  307.16
#Mann= 9 ,-1 , 0
  4289.9     .05       0  4376.9      .1       0  4491.8     .05       0
  4694.8     .16       0  4994.9     .07       0  5000.9     .16       0
  5253.2     .05       0  5450.6     .16       0  5557.3     .05       0
Bank Sta=4994.9,5000.9
XS Rating Curve= 0 ,0
Exp/Cntr=0.3,0.1

Type RM Length L Ch R = 1 ,565     ,0,0,0
BEGIN DESCRIPTION:
COBB BRANCH 2 1.0
END DESCRIPTION:
XS GIS Cut Line= 4
      3570938.42     10325205.22      3570801.71     10324636.68
      3570255.56     10324256.33       3569569.2     10324477.18
#Sta/Elev= 30
    3987  294.35  4146.5  293.71  4182.2   293.9  4402.1  290.24  4484.4  286.86
  4554.3  288.63  4583.9   288.6  4701.1  288.92  4739.5   288.9  4820.9  288.29
  4955.9  288.55  4970.8  287.44  4976.9  283.83  4991.7  283.34  4997.8  279.56
  5003.6   279.4  5006.3   278.9  5009.6   279.4  5012.7  282.97  5027.5  287.98
  5063.3  288.28  5070.9  289.65  5099.1  288.49  5229.3  290.44  5261.9  287.63
  5293.4  287.61  5338.5  291.94  5370.6  293.37  5645.8  299.85  5958.3  308.57
#Mann= 11 ,-1 , 0
    3987     .05       0  4146.5      .1       0  4182.2     .05       0
  4554.3     .16       0  4583.9     .05       0  4701.1     .16       0
  4739.5     .05       0  4820.9     .16       0  5003.6     .07       0
  5009.6     .16       0  5645.8     .05       0
Bank Sta=5003.6,5009.6
XS Rating Curve= 0 ,0
Exp/Cntr=0.3,0.1

Chan Stop Cuts=-1
Use User Specified Reach Order=0
Composite Channel Slope=5