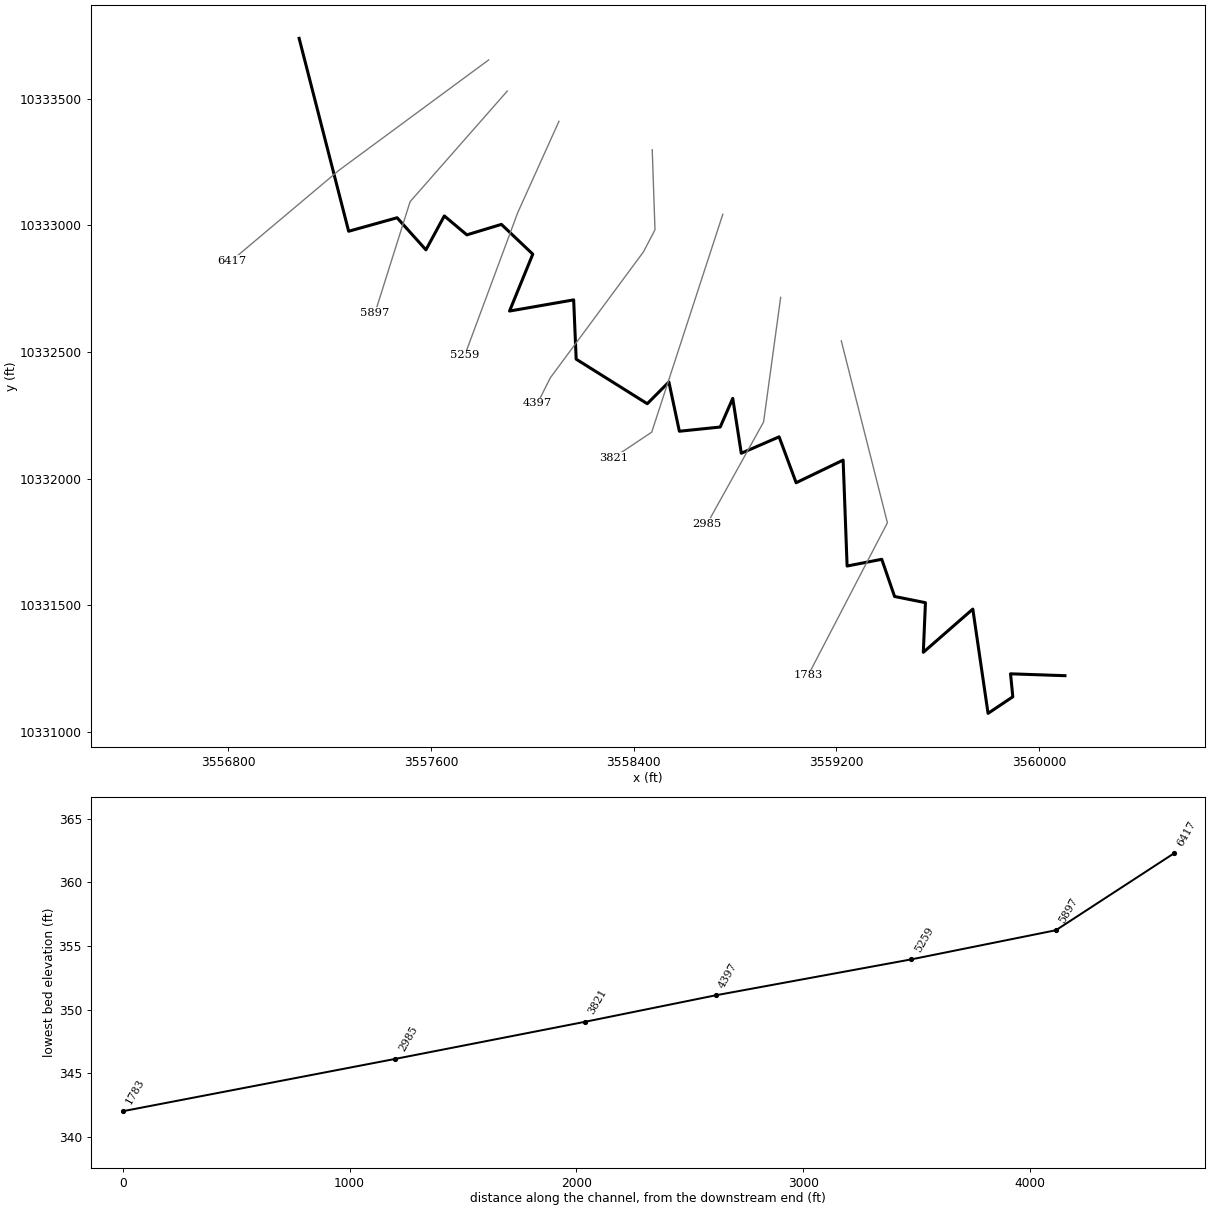
--- COBB BRANCH SOUTH.prj (project) ---

Proj Title=COBB BRANCH SOUTH Base Level Engineering
Current Plan=p01
Default Exp/Contr=0.3,0.1
English Units
Geom File=g01
Flow File=f01
Plan File=p01
BEGIN DESCRIPTION:
COBB BRANCH SOUTH
END DESCRIPTION:

--- COBB BRANCH SOUTH.p01 (plan) ---

Plan Title=Multiple Run
Short Identifier=Multiple
Geom File=g01
Flow File=f01
Subcritical Flow
K Sum by GR= 0
Std Step Tol= 0.01
Critical Tol= 0.01
Num of Std Step Trials= 20
Max Error Tol= 0.3
Flow Tol Ratio= 0.001
Split Flow NTrial= 30
Split Flow Tol= 0.02
Split Flow Ratio= 0.02
Log Output Level= 0
Friction Slope Method= 1
Unsteady Friction Slope Method= 2
Unsteady Bridges Friction Slope Method= 1
Parabolic Critical Depth
Global Vel Dist=  1 , 1 , 1
Global Log Level= 0
CheckData=True
Encroach Param= -1, 0, 0, 0
BEGIN DESCRIPTION:
Multiple Run
END DESCRIPTION:

--- COBB BRANCH SOUTH.f01 (steady flow) ---

Flow Title=Multiple
Number of Profiles=7
Profile Names=10-year,25-year,50-year,1pct_min,100-year,1pct_plu,500-year
River Rch & RM= COBB BRANCH SOUT,Reach-1,6417
     477     637     765     674     912    1233    1299
Boundary for River Rch & Prof#=COBB BRANCH SOUT,Reach-1,1
Up Type=0
Dn Type=3
Dn Slope=0.005
Boundary for River Rch & Prof#=COBB BRANCH SOUT,Reach-1,2
Up Type=0
Dn Type=3
Dn Slope=0.005
Boundary for River Rch & Prof#=COBB BRANCH SOUT,Reach-1,3
Up Type=0
Dn Type=3
Dn Slope=0.005
Boundary for River Rch & Prof#=COBB BRANCH SOUT,Reach-1,4
Up Type=0
Dn Type=3
Dn Slope=0.005
Boundary for River Rch & Prof#=COBB BRANCH SOUT,Reach-1,5
Up Type=0
Dn Type=3
Dn Slope=0.005
Boundary for River Rch & Prof#=COBB BRANCH SOUT,Reach-1,6
Up Type=0
Dn Type=3
Dn Slope=0.005
Boundary for River Rch & Prof#=COBB BRANCH SOUT,Reach-1,7
Up Type=0
Dn Type=3
Dn Slope=0.005

--- COBB BRANCH SOUTH.g01 (geometry) ---

Geom Title=Existing Conditions

River Reach=COBB BRANCH SOUT,Reach-1
Reach XY= 30
      3557079.86     10333738.05      3557275.34     10332976.70
      3557466.50     10333030.00      3557580.27     10332903.36
      3557652.87     10333037.20      3557741.77     10332962.49
      3557878.10     10333003.84      3558001.98     10332886.32
      3557910.20     10332661.79      3558163.28     10332705.89
      3558173.18     10332471.93      3558453.77     10332296.09
      3558539.12     10332381.94      3558580.41     10332187.47
      3558741.68     10332204.14      3558791.11     10332317.12
      3558824.76     10332100.62      3558974.11     10332165.38
      3559041.24     10331984.31      3559226.71     10332073.54
      3559242.38     10331655.58      3559379.09     10331682.15
      3559429.78     10331535.40      3559551.53     10331510.96
      3559543.13     10331315.06      3559738.47     10331485.63
      3559798.64     10331074.10      3559896.30     10331139.53
      3559887.39     10331230.24      3560102.12     10331222.80

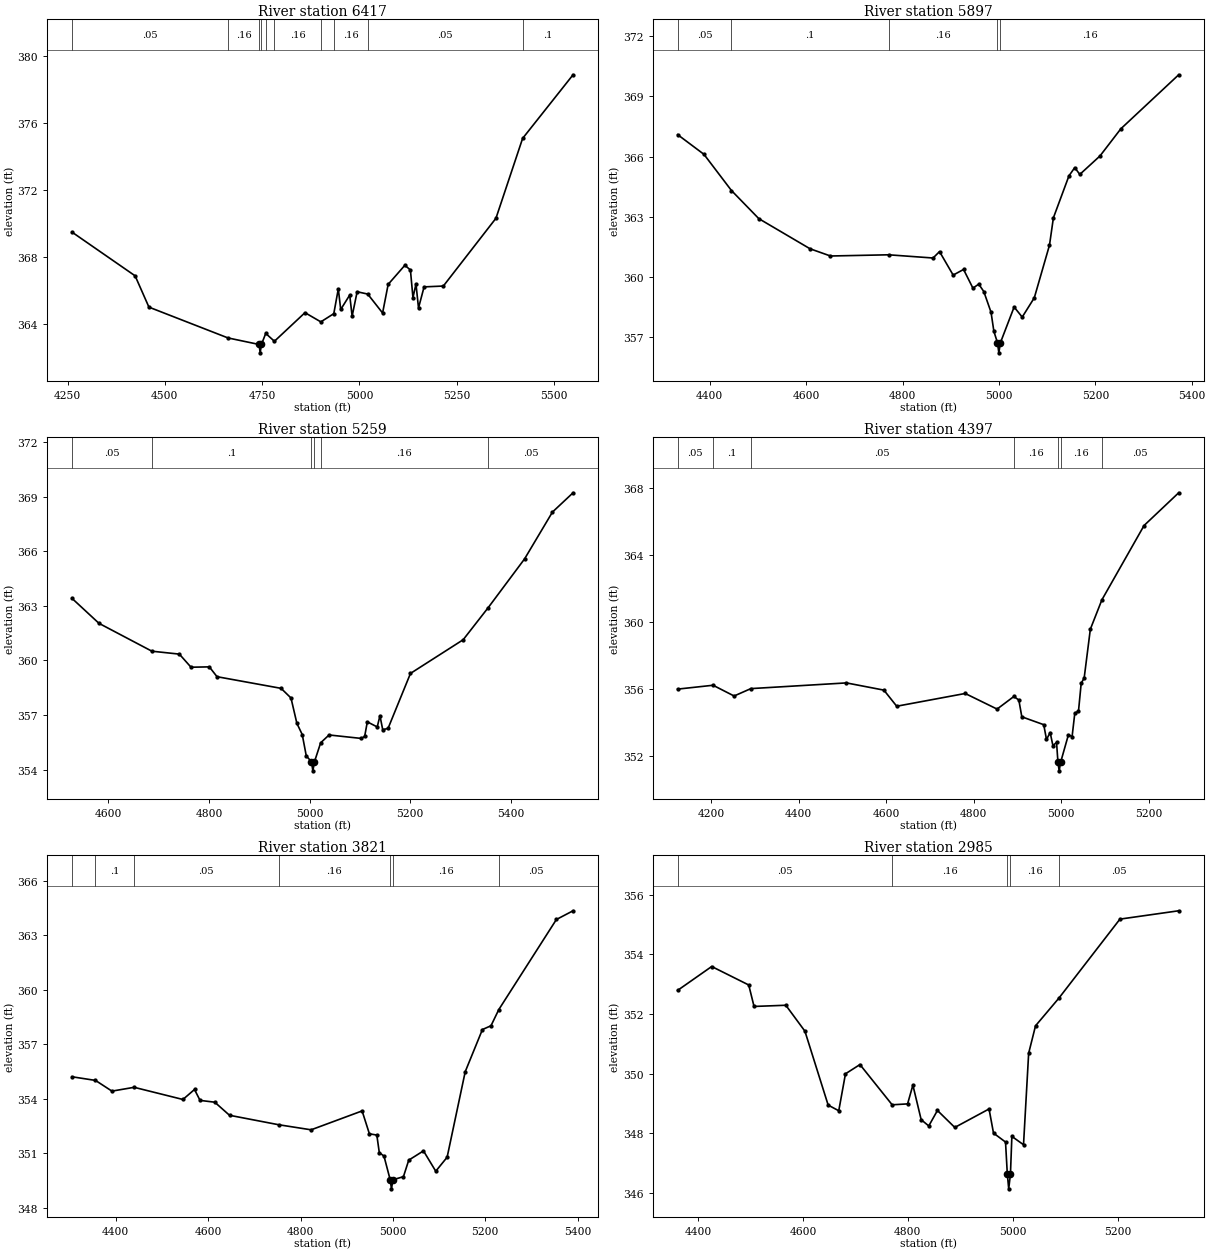
Type RM Length L Ch R = 1,6417,520,520,520
BEGIN DESCRIPTION:
COBB BRANCH SOUTH 7.0
END DESCRIPTION:
XS GIS Cut Line= 3
      3557827.72     10333652.71      3557238.04     10333218.03
      3556813.47     10332860.86
#Sta/Elev= 30
  4261.6  369.47  4423.7  366.86  4459.2  364.99  4662.4  363.15  4742.3  362.76
  4745.0  362.26  4748.3  362.76  4759.3  363.42  4781.6  362.95  4860.2  364.66
  4900.9  364.11  4934.2  364.60  4945.8  366.08  4952.0  364.85  4975.1  365.71
  4981.3  364.45  4994.2  365.91  5021.4  365.77  5059.6  364.64  5073.9  366.35
  5116.8  367.49  5131.1  367.21  5137.6  365.56  5145.4  366.37  5151.9  364.94
  5166.2  366.20  5215.7  366.25  5350.9  370.30  5419.4  375.07  5549.0  378.87
#Mann=10,-1,0
  4261.6    0.05       0  4662.4    0.16       0  4742.3    0.07       0
  4748.3    0.16       0  4759.3    0.05       0  4781.6    0.16       0
  4900.9    0.05       0  4934.2    0.16       0  5021.4    0.05       0
  5419.4     0.1       0
Bank Sta=4742.3,4748.3
Exp/Cntr=0.3,0.1

Type RM Length L Ch R = 1,5897,638,638,638
BEGIN DESCRIPTION:
COBB BRANCH SOUTH 6.0
END DESCRIPTION:
XS GIS Cut Line= 3
      3557901.19     10333529.88      3557517.72     10333093.35
      3557379.77     10332655.93
#Sta/Elev= 30
  4333.3  367.09  4387.9  366.11  4444.9  364.31  4501.7  362.91  4608.0  361.41
  4650.4  361.05  4771.0  361.11  4863.3  360.95  4876.7  361.27  4905.0  360.10
  4926.6  360.38  4946.0  359.45  4958.1  359.65  4968.6  359.28  4983.6  358.25
  4989.5  357.30  4997.0  356.73  4999.8  356.23  5003.0  356.73  5031.5  358.51
  5048.3  358.01  5073.4  358.97  5104.9  361.59  5113.0  362.95  5145.3  365.04
  5157.3  365.45  5167.8  365.11  5209.7  366.03  5252.9  367.38  5373.0  370.07
#Mann=5,-1,0
  4333.3    0.05       0  4444.9     0.1       0  4771.0    0.16       0
  4997.0    0.07       0  5003.0    0.16       0
Bank Sta=4997,5003
Exp/Cntr=0.3,0.1

Type RM Length L Ch R = 1,5259,862,862,862
BEGIN DESCRIPTION:
COBB BRANCH SOUTH 5.0
END DESCRIPTION:
XS GIS Cut Line= 3
      3558105.19     10333410.51      3557942.31     10333049.55
      3557733.38     10332486.79
#Sta/Elev= 30
  4527.6  363.41  4581.2  362.04  4686.4  360.51  4741.0  360.35  4764.2  359.63
  4800.6  359.65  4815.9  359.11  4943.3  358.47  4963.0  357.94  4974.7  356.55
  4985.4  355.93  4993.4  354.76  5003.7  354.44  5006.5  353.94  5009.7  354.44
  5022.0  355.48  5038.7  355.91  5102.7  355.72  5109.5  355.83  5114.8  356.63
  5134.5  356.35  5139.9  356.97  5145.4  356.20  5156.0  356.27  5200.6  359.29
  5305.4  361.14  5355.1  362.90  5427.5  365.58  5482.9  368.15  5523.9  369.21
#Mann=6,-1,0
  4527.6    0.05       0  4686.4     0.1       0  5003.7    0.07       0
  5009.7     0.1       0  5022.0    0.16       0  5355.1    0.05       0
Bank Sta=5003.7,5009.7
Exp/Cntr=0.3,0.1

Type RM Length L Ch R = 1,4397,576,576,576
BEGIN DESCRIPTION:
COBB BRANCH SOUTH 4.0
END DESCRIPTION:
XS GIS Cut Line= 5
      3558473.36     10333298.43      3558484.20     10332982.37
      3558438.55     10332895.13      3558070.79     10332397.84
      3558020.80     10332297.84
#Sta/Elev= 30
  4123.7  355.99  4204.6  356.22  4252.7  355.58  4291.0  356.02  4509.4  356.36
  4595.0  355.93  4624.3  354.97  4780.8  355.73  4853.7  354.80  4892.0  355.55
  4903.4  355.34  4910.2  354.34  4960.3  353.87  4966.6  352.99  4975.0  353.40
  4981.2  352.63  4989.6  352.81  4992.8  351.62  4995.6  351.12  4998.8  351.62
  5016.7  353.27  5025.1  353.16  5031.3  354.56  5039.7  354.67  5045.9  356.34
  5052.7  356.65  5066.8  359.56  5093.2  361.31  5189.6  365.74  5268.7  367.69
#Mann=7,-1,0
  4123.7    0.05       0  4204.6     0.1       0  4291.0    0.05       0
  4892.0    0.16       0  4992.8    0.07       0  4998.8    0.16       0
  5093.2    0.05       0
Bank Sta=4992.8,4998.8
Exp/Cntr=0.3,0.1

Type RM Length L Ch R = 1,3821,836,836,836
BEGIN DESCRIPTION:
COBB BRANCH SOUTH 3.0
END DESCRIPTION:
XS GIS Cut Line= 3
      3558751.91     10333043.81      3558471.34     10332183.81
      3558321.33     10332083.80
#Sta/Elev= 30
  4305.2  355.21  4356.0  355.01  4391.6  354.42  4439.7  354.63  4545.3  353.96
  4570.4  354.51  4582.4  353.91  4614.3  353.81  4646.2  353.09  4752.5  352.57
  4822.9  352.29  4933.3  353.33  4949.1  352.07  4965.2  352.00  4970.5  351.04
  4980.7  350.84  4994.1  349.54  4996.9  349.04  5000.1  349.54  5022.8  349.71
  5034.3  350.62  5066.2  351.13  5092.8  350.01  5117.4  350.78  5156.6  355.49
  5193.8  357.81  5212.4  358.02  5229.3  358.91  5354.0  363.87  5390.1  364.35
#Mann=7,-1,0
  4305.2    0.05       0  4356.0     0.1       0  4439.7    0.05       0
  4752.5    0.16       0  4994.1    0.07       0  5000.1    0.16       0
  5229.3    0.05       0
Bank Sta=4994.1,5000.1
Exp/Cntr=0.3,0.1

Type RM Length L Ch R = 1,2985,1202,1202,1202
BEGIN DESCRIPTION:
COBB BRANCH SOUTH 2.0
END DESCRIPTION:
XS GIS Cut Line= 3
      3558980.19     10332715.91      3558912.80     10332223.96
      3558690.40     10331822.96
#Sta/Elev= 30
  4361.2  352.79  4426.1  353.59  4496.7  352.97  4506.8  352.25  4567.4  352.29
  4603.8  351.42  4648.1  348.94  4668.3  348.75  4681.1  349.99  4708.7  350.30
  4770.1  348.95  4799.5  348.98  4809.6  349.61  4825.4  348.45  4839.9  348.24
  4856.4  348.76  4889.5  348.19  4954.8  348.81  4963.3  348.00  4986.2  347.70
  4989.6  346.63  4992.3  346.13  4995.6  346.63  4998.3  347.89  5020.5  347.61
  5030.3  350.68  5043.4  351.60  5088.0  352.53  5204.3  355.18  5316.3  355.46
#Mann=5,-1,0
  4361.2    0.05       0  4770.1    0.16       0  4989.6    0.07       0
  4995.6    0.16       0  5088.0    0.05       0
Bank Sta=4989.6,4995.6
Exp/Cntr=0.3,0.1

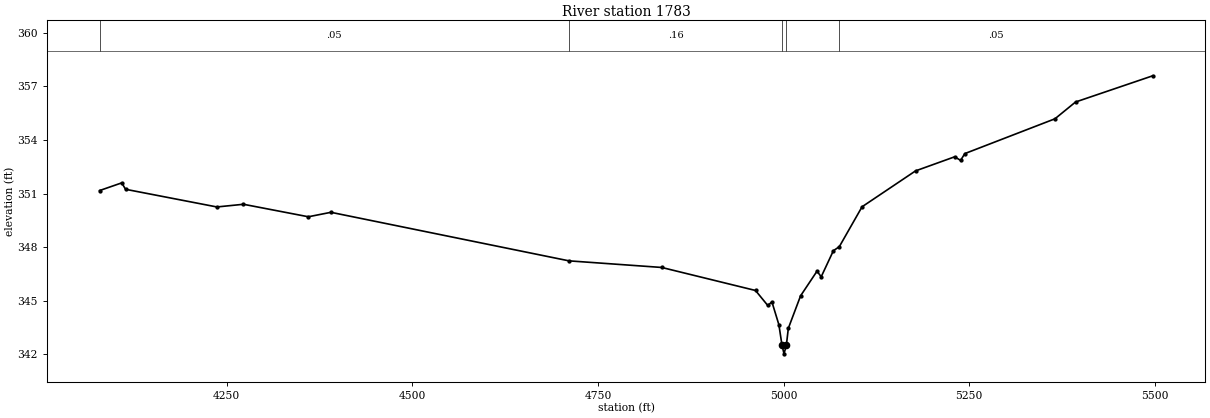
Type RM Length L Ch R = 1,1783,0,0,0
BEGIN DESCRIPTION:
COBB BRANCH SOUTH 1.0
END DESCRIPTION:
XS GIS Cut Line= 3
      3559219.44     10332544.12      3559401.41     10331826.33
      3559088.92     10331224.86
#Sta/Elev= 30
  4078.9  351.17  4108.7  351.60  4113.8  351.24  4236.8  350.25  4272.6  350.40
  4360.0  349.70  4390.4  349.95  4711.0  347.23  4835.9  346.86  4962.2  345.57
  4978.7  344.73  4984.3  344.93  4993.7  343.65  4997.8  342.52  5000.6  342.02
  5003.8  342.52  5006.4  343.45  5022.9  345.27  5045.0  346.65  5050.7  346.34
  5067.1  347.80  5075.0  348.02  5105.7  350.26  5177.7  352.27  5230.4  353.06
  5238.4  352.86  5244.1  353.24  5365.5  355.19  5393.2  356.13  5497.2  357.60
#Mann=5,-1,0
  4078.9    0.05       0  4711.0    0.16       0  4997.8    0.07       0
  5003.8    0.16       0  5075.0    0.05       0
Bank Sta=4997.8,5003.8
Exp/Cntr=0.3,0.1

Chan Stop Cuts=-1