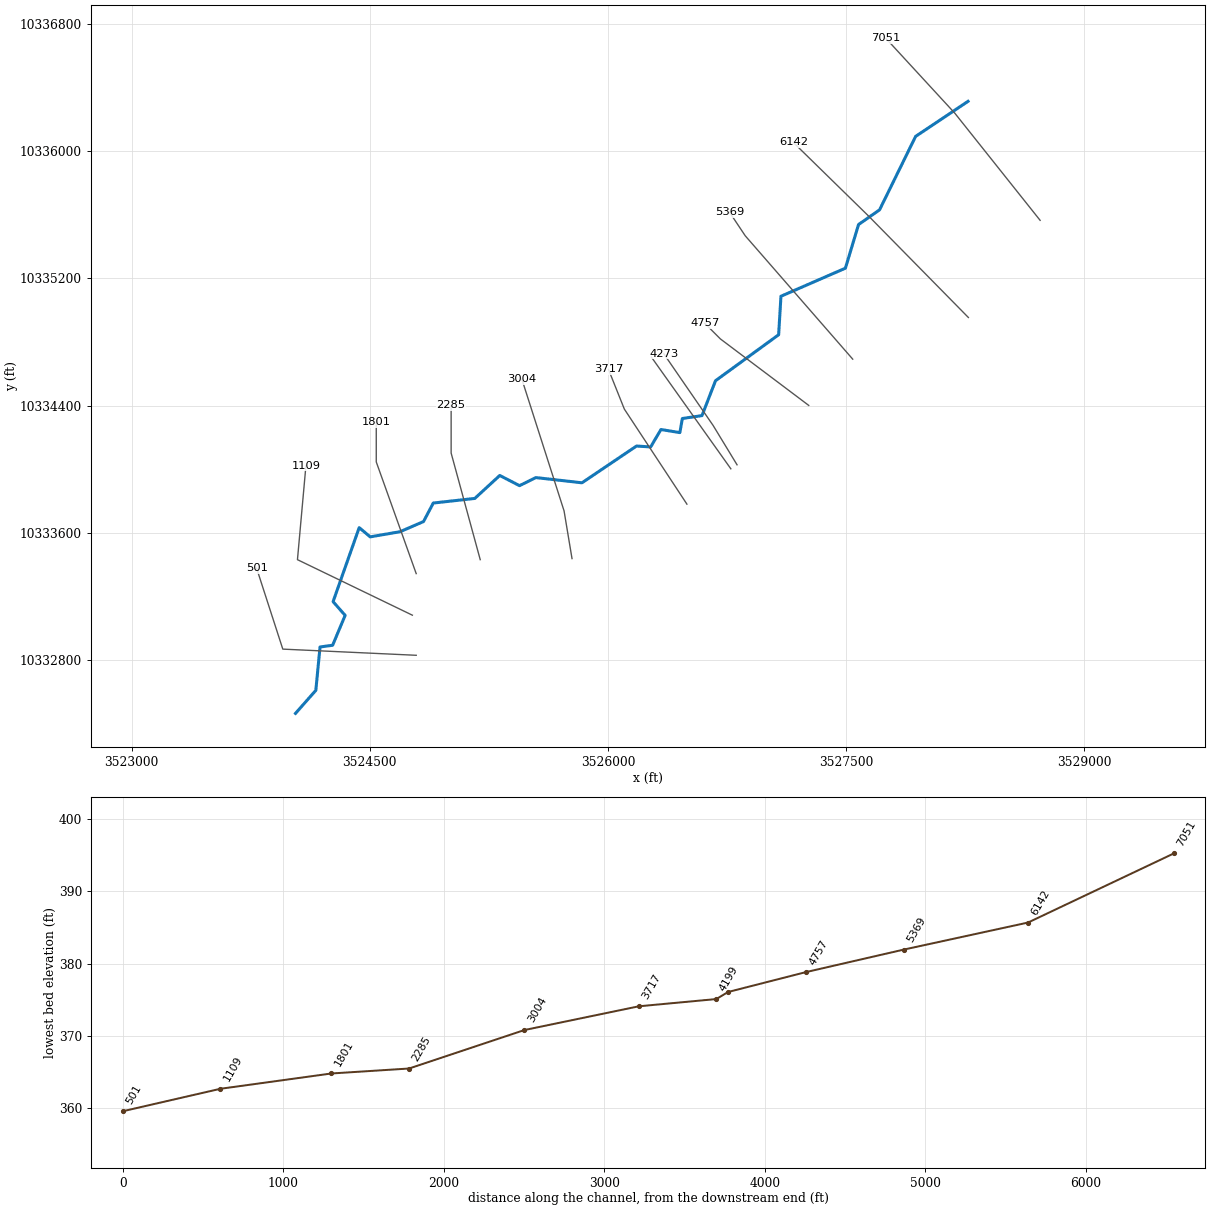
--- COOK BRANCH.prj (project) ---

Proj Title=COOK BRANCH Base Level Engineering
Current Plan=p01
Default Exp/Contr=0.3,0.1
English Units
Geom File=g01
Flow File=f01
Plan File=p01
BEGIN DESCRIPTION:
COOK BRANCH
END DESCRIPTION:

--- COOK BRANCH.p01 (plan) ---

Plan Title=Multiple Run
Short Identifier=Multiple
Geom File=g01
Flow File=f01
Subcritical Flow
K Sum by GR= 0
Std Step Tol= 0.01
Critical Tol= 0.01
Num of Std Step Trials= 20
Max Error Tol= 0.3
Flow Tol Ratio= 0.001
Split Flow NTrial= 30
Split Flow Tol= 0.02
Split Flow Ratio= 0.02
Log Output Level= 0
Friction Slope Method= 1
Unsteady Friction Slope Method= 2
Unsteady Bridges Friction Slope Method= 1
Parabolic Critical Depth
Global Vel Dist=  1 , 1 , 1
Global Log Level= 0
CheckData=True
Encroach Param= -1, 0, 0, 0
BEGIN DESCRIPTION:
Multiple Run
END DESCRIPTION:

--- COOK BRANCH.f01 (steady flow) ---

Flow Title=Multiple
Number of Profiles=7
Profile Names=10-year,25-year,50-year,1pct_min,100-year,1pct_plu,500-year
River Rch & RM= COOK BRANCH,Reach-1,7051
     551     751     916     820    1109    1500    1630
Boundary for River Rch & Prof#=COOK BRANCH,Reach-1,1
Up Type=0
Dn Type=3
Dn Slope=0.005
Boundary for River Rch & Prof#=COOK BRANCH,Reach-1,2
Up Type=0
Dn Type=3
Dn Slope=0.005
Boundary for River Rch & Prof#=COOK BRANCH,Reach-1,3
Up Type=0
Dn Type=3
Dn Slope=0.005
Boundary for River Rch & Prof#=COOK BRANCH,Reach-1,4
Up Type=0
Dn Type=3
Dn Slope=0.005
Boundary for River Rch & Prof#=COOK BRANCH,Reach-1,5
Up Type=0
Dn Type=3
Dn Slope=0.005
Boundary for River Rch & Prof#=COOK BRANCH,Reach-1,6
Up Type=0
Dn Type=3
Dn Slope=0.005
Boundary for River Rch & Prof#=COOK BRANCH,Reach-1,7
Up Type=0
Dn Type=3
Dn Slope=0.005

--- COOK BRANCH.g01 (geometry) ---

Geom Title=Existing Conditions

River Reach=COOK BRANCH,Reach-1
Reach XY= 30
      3528266.84     10336315.53      3527936.75     10336094.60
      3527709.88     10335632.51      3527577.39     10335539.66
      3527494.67     10335264.83      3527088.76     10335088.09
      3527074.31     10334845.74      3526676.77     10334556.21
      3526591.70     10334336.60      3526467.88     10334318.39
      3526452.39     10334229.47      3526333.25     10334249.04
      3526268.44     10334139.22      3526179.36     10334145.04
      3525836.07     10333913.55      3525545.36     10333946.30
      3525442.87     10333895.48      3525318.19     10333959.60
      3525161.00     10333815.05      3524899.72     10333786.09
      3524838.09     10333669.34      3524690.34     10333605.45
      3524502.48     10333573.11      3524433.26     10333631.21
      3524268.74     10333165.29      3524344.70     10333078.64
      3524265.73     10332890.48      3524186.62     10332879.67
      3524160.05     10332606.62      3524032.11     10332461.64

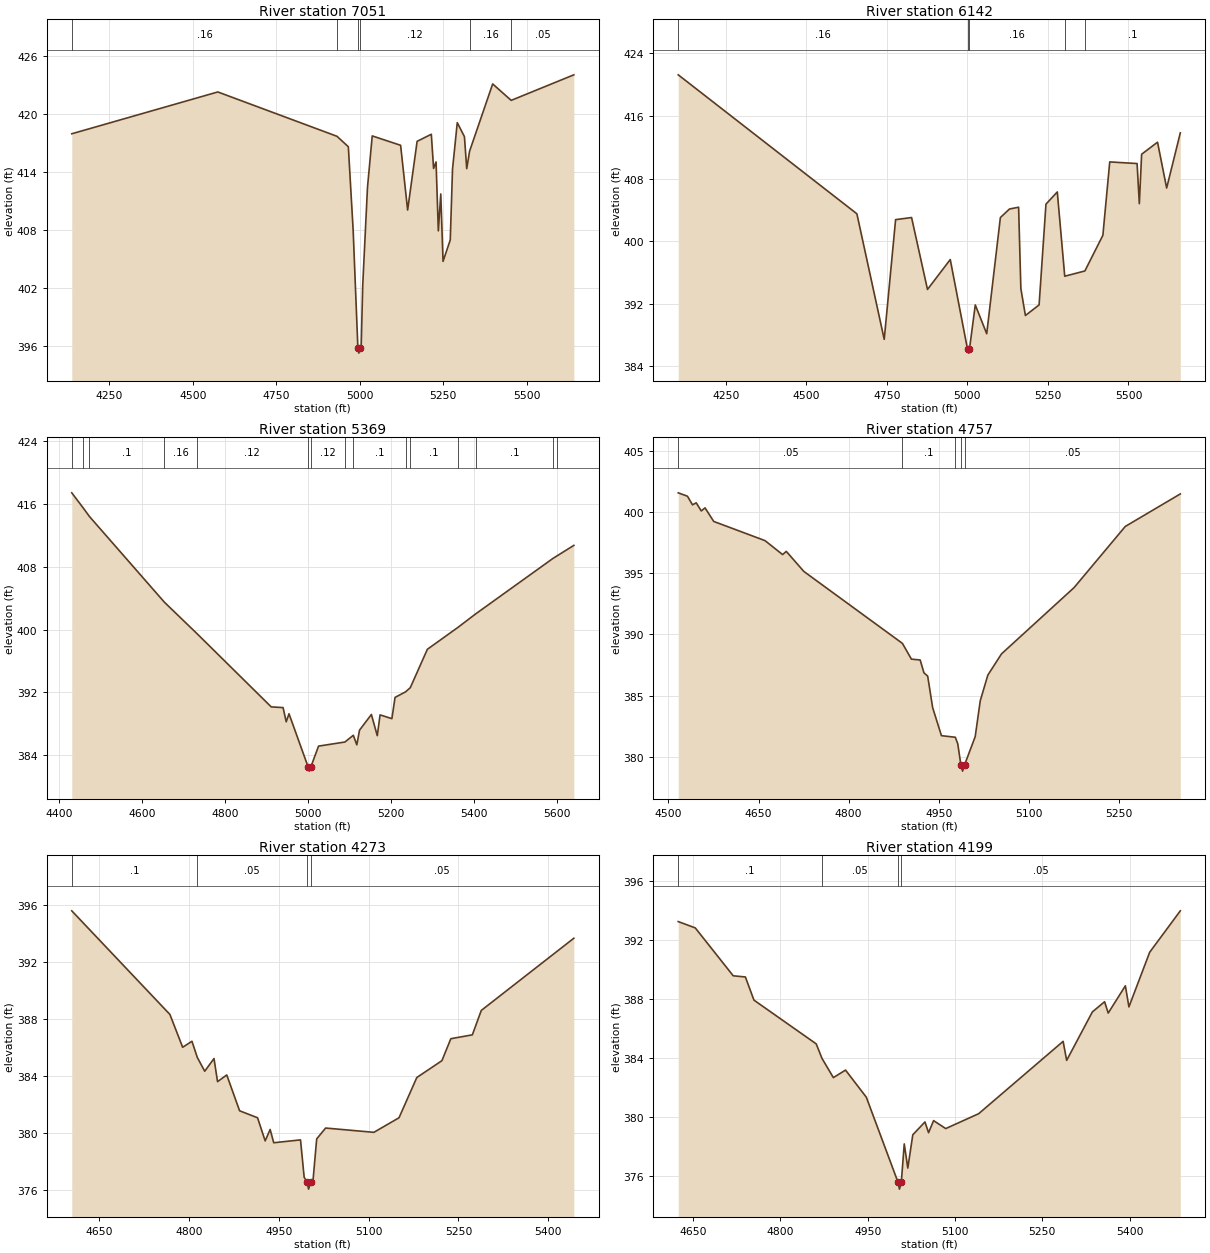
Type RM Length L Ch R = 1,7051,909,909,909
BEGIN DESCRIPTION:
COOK BRANCH 15.0
END DESCRIPTION:
XS GIS Cut Line= 3
      3528720.71     10335566.16      3528183.65     10336240.66
      3527749.54     10336712.15
#Sta/Elev= 30
  4137.8  417.93  4575.0  422.25  4931.8  417.67  4965.8  416.59  4980.2  407.97
  4994.4  395.77  4997.2  395.27  5000.4  395.77  5004.1  395.77  5008.9  402.30
  5023.1  412.38  5037.3  417.71  5122.3  416.74  5143.3  410.05  5171.7  417.15
  5214.2  417.88  5221.0  414.35  5228.4  415.02  5235.2  407.90  5242.5  411.71
  5249.3  404.75  5270.9  406.96  5277.7  414.28  5291.9  419.08  5313.4  417.63
  5320.2  414.33  5328.8  416.13  5397.9  423.08  5453.3  421.38  5640.9  424.02
#Mann=6,-1,0
  4137.8    0.16       0  4931.8    0.12       0  4994.4    0.07       0
  5000.4    0.12       0  5328.8    0.16       0  5453.3    0.05       0
Bank Sta=4994.4,5000.4
Exp/Cntr=0.3,0.1

Type RM Length L Ch R = 1,6142,773,773,773
BEGIN DESCRIPTION:
COOK BRANCH 13.0
END DESCRIPTION:
XS GIS Cut Line= 3
      3528269.09     10334954.32      3527642.11     10335591.64
      3527166.98     10336056.44
#Sta/Elev= 30
  4102.3  421.26  4656.9  403.50  4741.8  387.45  4777.1  402.75  4826.7  403.02
  4876.1  393.83  4946.8  397.65  5000.4  386.19  5003.2  385.69  5006.4  386.19
  5024.5  391.85  5060.0  388.17  5102.4  403.02  5130.7  404.11  5159.0  404.34
  5166.0  393.93  5180.1  390.50  5222.6  391.85  5243.9  404.73  5279.1  406.29
  5302.2  395.52  5364.7  396.19  5420.6  400.75  5441.9  410.13  5526.8  409.92
  5533.8  404.79  5540.9  411.11  5590.3  412.65  5618.6  406.79  5661.0  413.84
#Mann=5,-1,0
  4102.3    0.16       0  5000.4    0.07       0  5006.4    0.16       0
  5302.2    0.05       0  5364.7     0.1       0
Bank Sta=5000.4,5006.4
Exp/Cntr=0.3,0.1

Type RM Length L Ch R = 1,5369,612,612,612
BEGIN DESCRIPTION:
COOK BRANCH 11.0
END DESCRIPTION:
XS GIS Cut Line= 3
      3527540.70     10334692.09      3526863.87     10335468.97
      3526764.67     10335617.78
#Sta/Elev= 30
  4431.0  417.43  4458.6  415.50  4473.6  414.41  4654.0  403.49  4731.4  399.54
  4911.4  390.14  4939.9  390.05  4947.5  388.24  4954.2  389.26  5000.5  382.45
  5003.3  381.95  5006.5  382.45  5025.4  385.14  5088.8  385.66  5109.1  386.52
  5117.5  385.30  5124.1  387.18  5152.6  389.17  5166.8  386.47  5173.5  389.12
  5202.0  388.64  5209.6  391.35  5235.0  392.06  5246.3  392.59  5287.4  397.48
  5360.9  400.27  5403.9  402.00  5589.7  409.06  5599.6  409.39  5640.2  410.73
#Mann=15,-1,0
  4431.0    0.16       0  4458.6    0.05       0  4473.6     0.1       0
  4654.0    0.16       0  4731.4    0.12       0  5000.5    0.07       0
  5006.5    0.12       0  5088.8    0.05       0  5109.1     0.1       0
  5235.0    0.12       0  5246.3     0.1       0  5360.9    0.16       0
  5403.9     0.1       0  5589.7    0.05       0  5599.6    0.16       0
Bank Sta=5000.5,5006.5
Exp/Cntr=0.3,0.1

Type RM Length L Ch R = 1,4757,484,484,484
BEGIN DESCRIPTION:
COOK BRANCH 10.0
END DESCRIPTION:
XS GIS Cut Line= 3
      3527263.89     10334400.75      3526707.58     10334819.34
      3526608.94     10334917.98
#Sta/Elev= 30
  4516.4  401.58  4531.8  401.30  4540.1  400.60  4546.4  400.76  4554.7  400.10
  4561.0  400.35  4575.5  399.24  4660.9  397.67  4690.1  396.53  4696.3  396.79
  4725.5  395.15  4889.5  389.27  4904.5  387.98  4919.1  387.91  4925.4  386.86
  4931.6  386.59  4939.9  384.01  4954.5  381.72  4977.6  381.59  4981.7  381.05
  4986.9  379.32  4989.7  378.82  4992.9  379.32  5010.7  381.64  5019.1  384.57
  5031.7  386.67  5054.5  388.41  5175.3  393.83  5260.5  398.83  5352.1  401.49
#Mann=5,-1,0
  4516.4    0.05       0  4889.5     0.1       0  4977.6    0.05       0
  4986.9    0.03       0  4992.9    0.05       0
Bank Sta=4986.9,4992.9
Exp/Cntr=0.3,0.1

Type RM Length L Ch R = 1,4273,74,74,74
BEGIN DESCRIPTION:
COOK BRANCH 9.0
END DESCRIPTION:
XS GIS Cut Line= 3
      3526812.29     10334026.85      3526661.78     10334274.47
      3526350.99     10334726.09
#Sta/Elev= 30
  4604.6  395.57  4768.4  388.31  4789.7  386.01  4805.2  386.43  4814.1  385.30
  4826.5  384.33  4842.0  385.22  4847.9  383.60  4863.3  384.07  4884.7  381.56
  4914.7  381.07  4927.4  379.45  4935.7  380.25  4941.7  379.32  4986.4  379.52
  4992.5  376.90  4997.2  376.57  4999.9  376.07  5003.2  376.57  5007.4  376.75
  5013.4  379.59  5028.3  380.35  5108.8  380.05  5150.8  381.07  5180.5  383.89
  5222.4  385.07  5237.3  386.61  5273.2  386.88  5288.1  388.59  5442.6  393.65
#Mann=4,-1,0
  4604.6     0.1       0  4814.1    0.05       0  4997.2    0.03       0
  5003.2    0.05       0
Bank Sta=4997.2,5003.2
Exp/Cntr=0.3,0.1

Type RM Length L Ch R = 1,4199,482,482,482
BEGIN DESCRIPTION:
Mapping XS 6b1c5cea
END DESCRIPTION:
XS GIS Cut Line= 2
      3526773.24     10334001.63      3526273.23     10334704.78
#Sta/Elev= 30
  4624.3  393.25  4653.6  392.82  4718.8  389.57  4739.7  389.49  4754.4  387.92
  4861.4  384.95  4871.4  383.96  4890.9  382.66  4911.8  383.17  4947.5  381.33
  5001.7  375.59  5004.5  375.09  5007.7  375.59  5012.7  378.16  5018.8  376.52
  5027.4  378.78  5048.3  379.65  5054.5  378.92  5063.1  379.74  5084.0  379.20
  5140.6  380.21  5285.7  385.12  5291.8  383.83  5336.0  387.12  5357.0  387.81
  5363.2  387.04  5392.7  388.89  5398.8  387.46  5434.5  391.17  5487.1  393.98
#Mann=4,-1,0
  4624.3     0.1       0  4871.4    0.05       0  5001.7    0.03       0
  5007.7    0.05       0
Bank Sta=5001.7,5007.7
Exp/Cntr=0.3,0.1

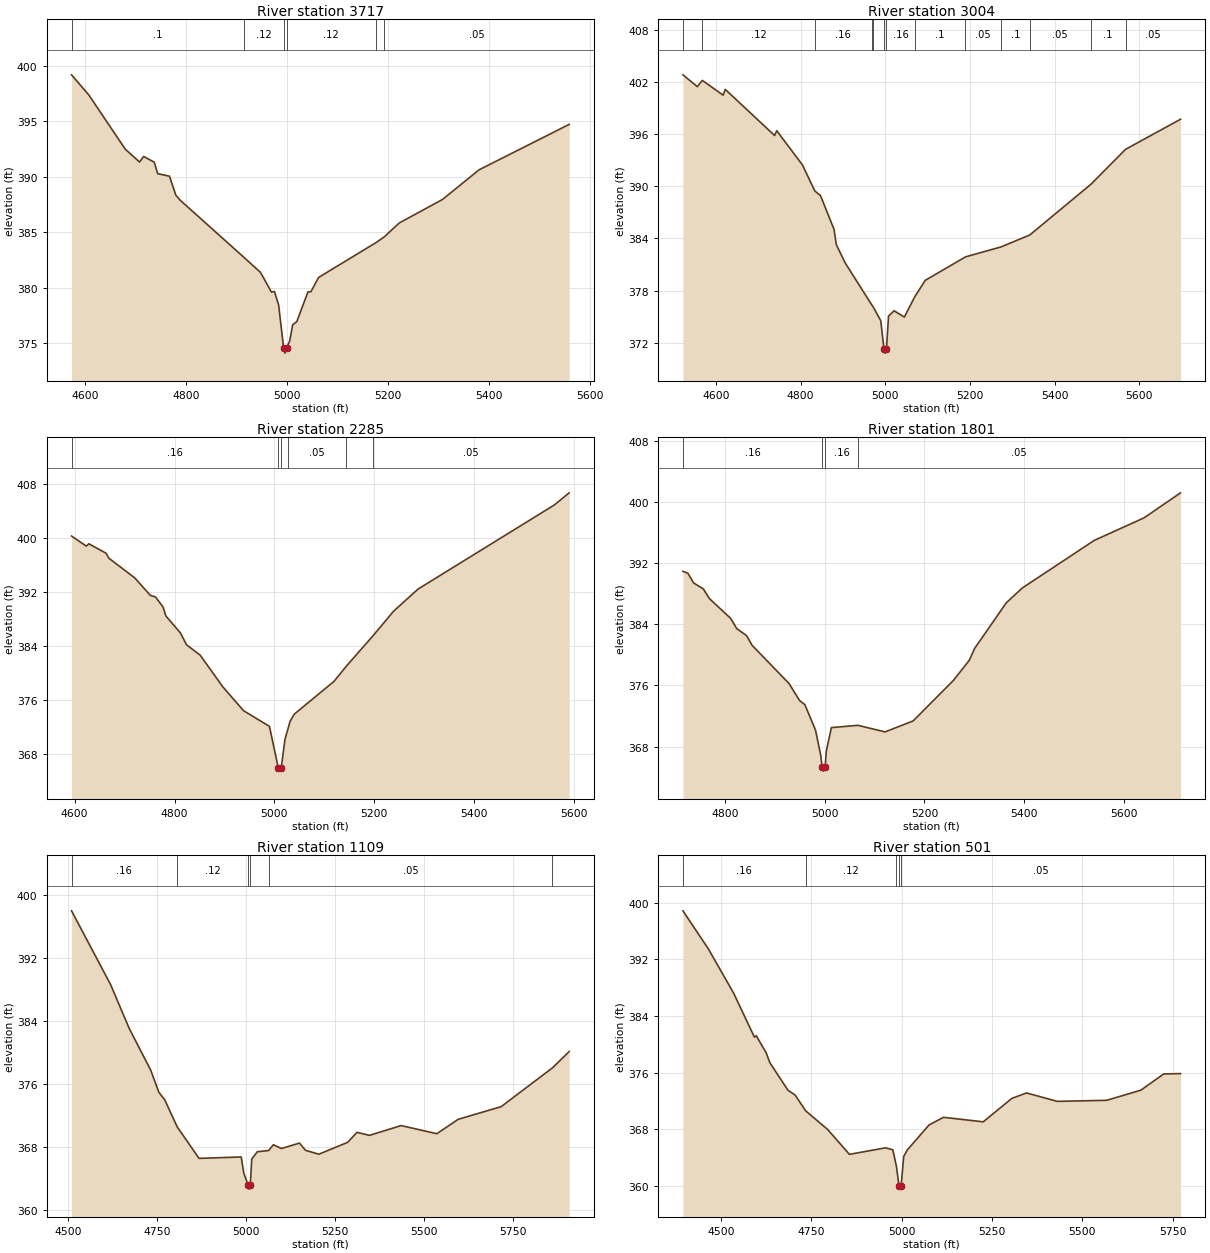
Type RM Length L Ch R = 1,3717,713,713,713
BEGIN DESCRIPTION:
COOK BRANCH 8.0
END DESCRIPTION:
XS GIS Cut Line= 3
      3526496.68     10333779.15      3526102.72     10334377.61
      3526002.92     10334627.10
#Sta/Elev= 30
  4573.3  399.18  4607.6  397.36  4679.8  392.47  4708.0  391.32  4716.0  391.82
  4737.1  391.30  4743.9  390.27  4767.2  390.04  4779.8  388.33  4788.3  387.88
  4915.2  382.70  4947.4  381.37  4969.0  379.60  4975.0  379.65  4983.3  378.43
  4993.1  374.59  4995.8  374.09  4999.1  374.59  5005.2  375.18  5011.1  376.64
  5019.3  376.93  5041.3  379.60  5047.3  379.63  5062.4  380.91  5176.3  384.06
  5192.7  384.58  5222.0  385.82  5307.6  387.94  5380.3  390.62  5558.5  394.71
#Mann=6,-1,0
  4573.3     0.1       0  4915.2    0.12       0  4993.1    0.07       0
  4999.1    0.12       0  5176.3     0.1       0  5192.7    0.05       0
Bank Sta=4993.1,4999.1
Exp/Cntr=0.3,0.1

Type RM Length L Ch R = 1,3004,719,719,719
BEGIN DESCRIPTION:
COOK BRANCH 6.0
END DESCRIPTION:
XS GIS Cut Line= 3
      3525773.22     10333436.21      3525723.22     10333736.25
      3525457.49     10334565.86
#Sta/Elev= 30
  4522.0  402.81  4556.0  401.45  4567.8  402.17  4616.9  400.47  4621.9  401.14
  4738.5  395.83  4743.6  396.38  4804.4  392.44  4833.4  389.46  4846.9  388.92
  4879.0  385.02  4884.3  383.28  4905.3  381.17  4967.5  376.39  4971.4  376.12
  4989.3  374.52  4996.8  371.30  4999.6  370.80  5002.8  371.30  5007.6  375.05
  5020.8  375.67  5045.0  374.95  5069.3  377.26  5094.3  379.17  5189.4  381.87
  5272.9  383.01  5341.0  384.38  5485.4  390.21  5567.4  394.24  5697.3  397.70
#Mann=13,-1,0
  4522.0    0.16       0  4567.8    0.12       0  4833.4    0.16       0
  4967.5     0.1       0  4971.4    0.16       0  4996.8    0.07       0
  5002.8    0.16       0  5069.3     0.1       0  5189.4    0.05       0
  5272.9     0.1       0  5341.0    0.05       0  5485.4     0.1       0
  5567.4    0.05       0
Bank Sta=4996.8,5002.8
Exp/Cntr=0.3,0.1

Type RM Length L Ch R = 1,2285,484,484,484
BEGIN DESCRIPTION:
COOK BRANCH 4.0
END DESCRIPTION:
XS GIS Cut Line= 3
      3525195.27     10333429.55      3525012.06     10334100.98
      3525012.06     10334401.00
#Sta/Elev= 30
  4593.9  400.34  4623.4  398.85  4628.6  399.19  4663.2  397.78  4668.6  397.05
  4720.5  394.13  4751.6  391.54  4761.9  391.31  4777.2  389.80  4782.7  388.49
  4811.7  385.98  4824.1  384.21  4851.4  382.67  4896.7  377.97  4938.1  374.44
  4990.0  372.11  5007.7  365.97  5010.4  365.47  5013.7  365.97  5021.1  370.19
  5026.7  371.64  5031.4  372.86  5039.7  373.92  5119.2  378.78  5144.1  381.05
  5197.6  385.57  5238.7  389.21  5287.6  392.48  5560.5  404.96  5589.9  406.75
#Mann=6,-1,0
  4593.9    0.16       0  5007.7    0.07       0  5013.7    0.16       0
  5026.7    0.05       0  5144.1     0.1       0  5197.6    0.05       0
Bank Sta=5007.7,5013.7
Exp/Cntr=0.3,0.1

Type RM Length L Ch R = 1,1801,692,692,692
BEGIN DESCRIPTION:
COOK BRANCH 3.0
END DESCRIPTION:
XS GIS Cut Line= 3
      3524792.12     10333341.60      3524540.67     10334044.69
      3524540.67     10334294.69
#Sta/Elev= 30
  4716.3  390.92  4726.4  390.65  4737.6  389.40  4757.2  388.61  4769.4  387.34
  4811.9  384.76  4824.1  383.42  4843.8  382.50  4854.8  381.24  4928.8  376.24
  4950.0  374.01  4960.6  373.47  4981.9  370.14  4992.5  366.80  4995.1  365.28
  4997.9  364.78  5001.1  365.28  5003.4  367.38  5013.7  370.47  5066.8  370.77
  5121.2  369.91  5177.5  371.35  5258.0  376.64  5289.8  379.27  5300.6  380.83
  5364.2  386.81  5396.0  388.73  5540.0  394.95  5640.0  397.91  5713.0  401.18
#Mann=4,-1,0
  4716.3    0.16       0  4995.1    0.07       0  5001.1    0.16       0
  5066.8    0.05       0
Bank Sta=4995.1,5001.1
Exp/Cntr=0.3,0.1

Type RM Length L Ch R = 1,1109,608,608,608
BEGIN DESCRIPTION:
COOK BRANCH 2.0
END DESCRIPTION:
XS GIS Cut Line= 3
      3524767.95     10333079.90      3524044.41     10333429.53
      3524097.82     10334021.94
#Sta/Elev= 30
  4509.7  397.96  4619.4  388.61  4671.7  383.05  4732.4  377.73  4755.0  374.95
  4771.6  373.99  4806.6  370.56  4868.0  366.56  4986.5  366.74  4993.8  364.68
  5006.1  363.16  5008.9  362.66  5012.1  363.16  5016.0  366.47  5031.7  367.40
  5063.8  367.56  5076.9  368.29  5099.5  367.81  5150.3  368.50  5167.3  367.58
  5204.8  367.09  5285.9  368.60  5311.8  369.86  5347.0  369.48  5435.9  370.72
  5536.3  369.69  5596.5  371.52  5717.0  373.12  5861.2  378.04  5908.1  380.11
#Mann=6,-1,0
  4509.7    0.16       0  4806.6    0.12       0  5006.1    0.07       0
  5012.1    0.12       0  5063.8    0.05       0  5861.2     0.1       0
Bank Sta=5006.1,5012.1
Exp/Cntr=0.3,0.1

Type RM Length L Ch R = 1,501,0,0,0
BEGIN DESCRIPTION:
COOK BRANCH 1.0
END DESCRIPTION:
XS GIS Cut Line= 3
      3524792.23     10332827.39      3523952.14     10332866.23
      3523787.08     10333375.99
#Sta/Elev= 30
  4394.7  398.84  4464.9  393.48  4535.0  387.22  4592.6  381.00  4597.6  381.20
  4625.1  378.79  4635.1  377.41  4685.1  373.53  4705.2  372.83  4734.4  370.60
  4795.2  367.97  4855.3  364.46  4955.4  365.38  4975.4  365.11  4985.5  362.75
  4992.5  360.05  4995.2  359.55  4998.5  360.05  5005.5  364.15  5015.5  365.08
  5075.5  368.60  5115.6  369.69  5225.7  369.05  5304.4  372.35  5345.3  373.13
  5430.6  371.94  5567.2  372.09  5661.8  373.52  5724.9  375.81  5771.5  375.86
#Mann=5,-1,0
  4394.7    0.16       0  4734.4    0.12       0  4985.5    0.05       0
  4992.5    0.03       0  4998.5    0.05       0
Bank Sta=4992.5,4998.5
Exp/Cntr=0.3,0.1

Chan Stop Cuts=-1