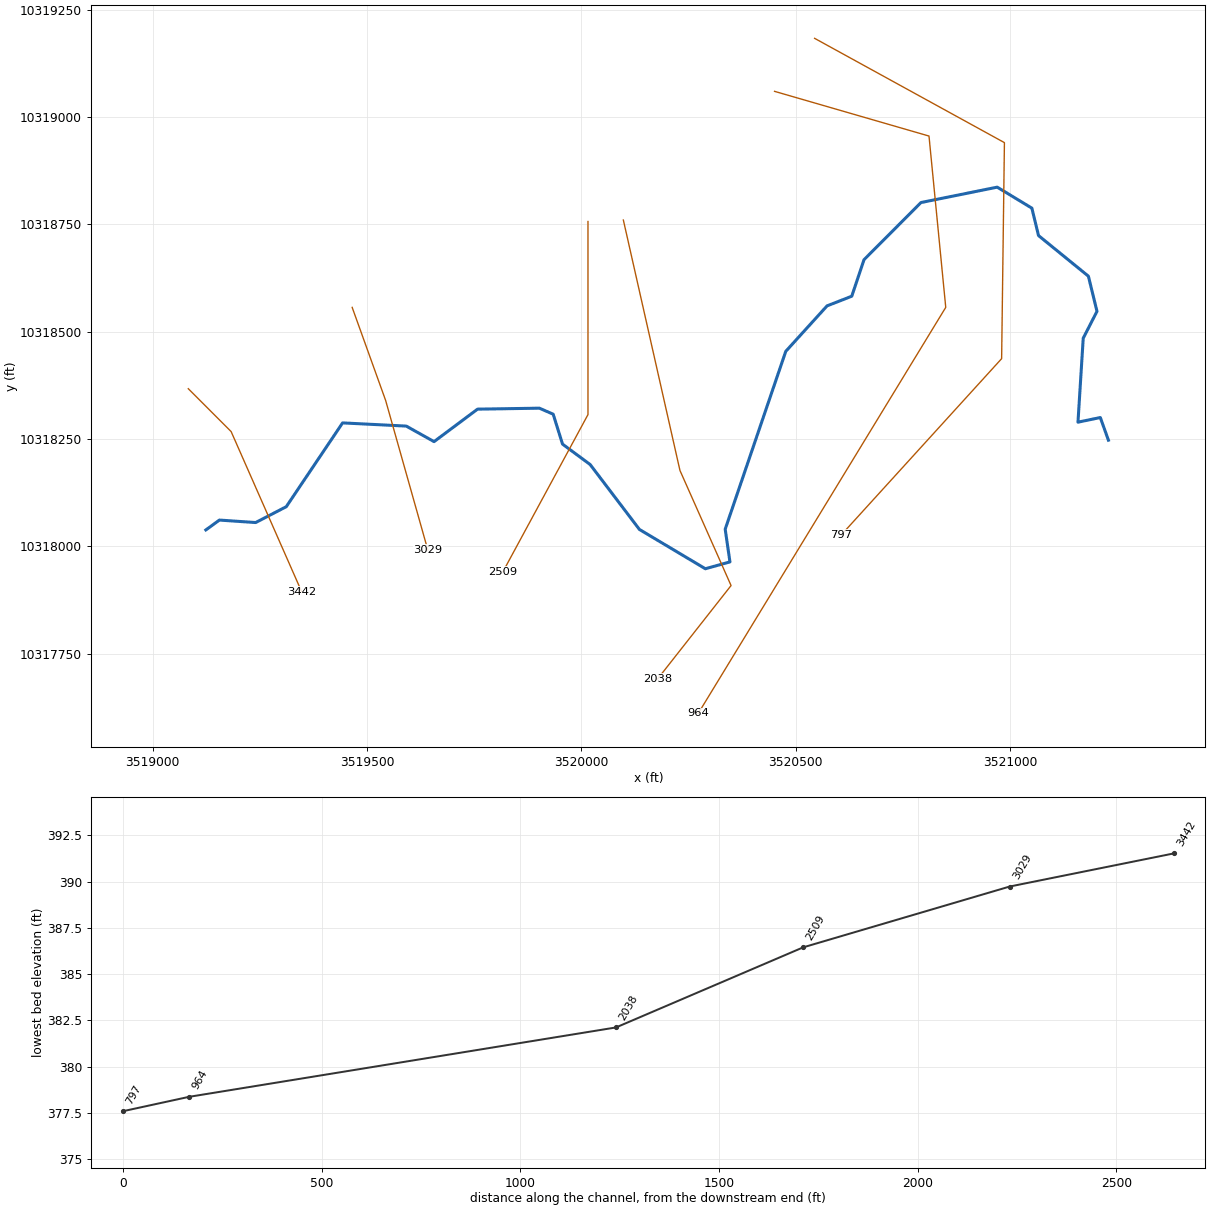
--- COPPERAS CREEK TRIBUTARY 10 1.prj (project) ---

Proj Title=COPPERAS CREEK TRIBUTARY 10 1 Base Level Engineering
Current Plan=p01
Default Exp/Contr=0.3,0.1
English Units
Geom File=g01
Flow File=f01
Plan File=p01
Y Axis Title=Elevation
X Axis Title(PF)=Main Channel Distance
X Axis Title(XS)=Station
BEGIN DESCRIPTION:
COPPERAS CREEK TRIBUTARY 10 1
END DESCRIPTION:
DSS Export Rating Curves= 0
DSS Export Rating Curve Sorted= 0
DSS Export Volume Flow Curves= 0
DXF OffsetX= 0
DXF OffsetY= 0
DXF ScaleX= 1
DXF ScaleY= 10

--- COPPERAS CREEK TRIBUTARY 10 1.p01 (plan) ---

Plan Title=Multiple Run
Short Identifier=Multiple
Geom File=g01
Flow File=f01
Subcritical Flow
K Sum by GR= 0
Std Step Tol= 0.01
Critical Tol= 0.01
Num of Std Step Trials= 20
Max Error Tol= 0.3
Flow Tol Ratio= 0.001
Split Flow NTrial= 30
Split Flow Tol= 0.02
Split Flow Ratio= 0.02
Log Output Level= 0
Friction Slope Method= 1
Unsteady Friction Slope Method= 2
Unsteady Bridges Friction Slope Method= 1
Parabolic Critical Depth
Global Vel Dist=  1 , 1 , 1
Global Log Level= 0
CheckData=True
Encroach Param= -1, 0, 0, 0
BEGIN DESCRIPTION:
Multiple Run
END DESCRIPTION:

--- COPPERAS CREEK TRIBUTARY 10 1.f01 (steady flow) ---

Flow Title=Multiple
Number of Profiles=7
Profile Names=10-year,25-year,50-year,1pct_min,100-year,1pct_plu,500-year
River Rch & RM= COPPERAS CREEK T,Reach-1,3442
     278     362     429     374     505     684     702
Boundary for River Rch & Prof#=COPPERAS CREEK T,Reach-1,1
Up Type=0
Dn Type=3
Dn Slope=0.005
Boundary for River Rch & Prof#=COPPERAS CREEK T,Reach-1,2
Up Type=0
Dn Type=3
Dn Slope=0.005
Boundary for River Rch & Prof#=COPPERAS CREEK T,Reach-1,3
Up Type=0
Dn Type=3
Dn Slope=0.005
Boundary for River Rch & Prof#=COPPERAS CREEK T,Reach-1,4
Up Type=0
Dn Type=3
Dn Slope=0.005
Boundary for River Rch & Prof#=COPPERAS CREEK T,Reach-1,5
Up Type=0
Dn Type=3
Dn Slope=0.005
Boundary for River Rch & Prof#=COPPERAS CREEK T,Reach-1,6
Up Type=0
Dn Type=3
Dn Slope=0.005
Boundary for River Rch & Prof#=COPPERAS CREEK T,Reach-1,7
Up Type=0
Dn Type=3
Dn Slope=0.005

--- COPPERAS CREEK TRIBUTARY 10 1.g01 (geometry) ---

Geom Title=Existing Conditions
Program Version=4.10

River Reach=COPPERAS CREEK T,Reach-1
Reach XY= 30
      3519124.43     10318038.14      3519156.08     10318061.13
       3519240.6     10318055.38      3519311.98      10318092.3
      3519443.37     10318287.61      3519591.93     10318280.14
      3519656.68     10318243.97      3519758.14     10318319.65
      3519902.31      10318321.9      3519934.56     10318307.91
      3519956.34      10318238.2       3520020.8     10318190.56
      3520135.73     10318039.29      3520289.55     10317947.67
      3520346.85     10317963.66      3520335.79     10318039.88
      3520477.06     10318454.34      3520573.35     10318560.32
      3520630.98     10318582.83      3520659.59     10318667.94
      3520792.38     10318801.13      3520970.27     10318837.02
      3521051.08     10318788.13      3521066.63     10318724.17
      3521182.95     10318629.55      3521202.99     10318547.62
      3521170.88     10318484.95      3521158.64     10318289.28
      3521210.76      10318300.1      3521229.64     10318247.35

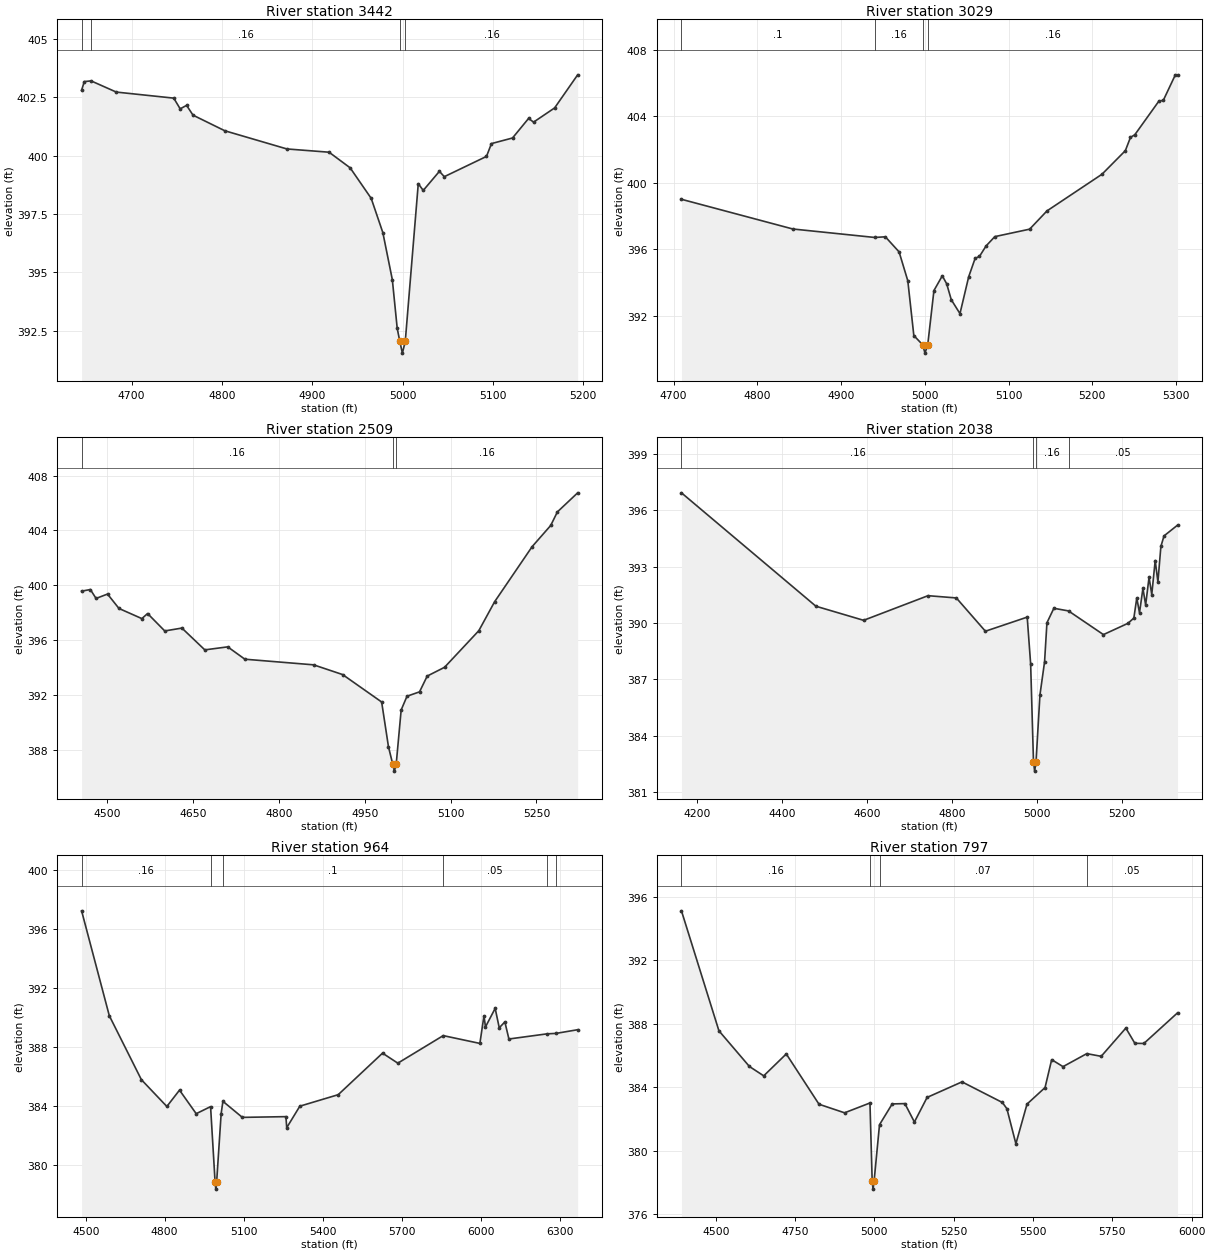
Type RM Length L Ch R = 1 ,3442    ,413,413,413
BEGIN DESCRIPTION:
COPPERAS CREEK TRIBUTARY 10.1 5.0
END DESCRIPTION:
XS GIS Cut Line= 3
      3519083.46      10318367.3      3519183.42     10318267.34
      3519347.81     10317894.33
#Sta/Elev= 30
  4644.7  402.81  4647.7  403.18  4655.2  403.21  4683.1  402.73  4746.7  402.47
  4753.8  402.01  4760.9  402.16    4768  401.74  4803.2  401.07  4871.9  400.29
  4918.6  400.15  4941.9  399.48  4965.2  398.17  4978.1   396.7  4988.6  394.68
    4994  392.59  4996.9  392.03  4999.7  391.53  5002.9  392.03  5017.3   398.8
  5022.8  398.51  5040.7  399.33  5046.1   399.1  5092.8  399.97  5098.3  400.52
  5121.6  400.76  5139.4   401.6  5144.9  401.44  5168.2  402.05  5193.7  403.47
#Mann= 4 ,-1 , 0
  4644.7      .1       0  4655.2     .16       0  4996.9     .07       0
  5002.9     .16       0
Bank Sta=4996.9,5002.9
XS Rating Curve= 0 ,0
Exp/Cntr=0.3,0.1

Type RM Length L Ch R = 1 ,3029    ,520,520,520
BEGIN DESCRIPTION:
COPPERAS CREEK TRIBUTARY 10.1 4.0
END DESCRIPTION:
XS GIS Cut Line= 3
       3519465.7      10318556.8      3519543.81     10318339.82
      3519642.11     10317991.64
#Sta/Elev= 30
  4709.3  399.01  4842.3  397.22  4940.1  396.71  4952.8  396.75  4969.2  395.84
  4979.6   394.1  4986.8   390.8  4997.4  390.24  5000.1  389.74  5003.4  390.24
  5010.8  393.51  5020.8   394.4    5026  393.92  5031.5  392.96  5041.9  392.12
  5052.3  394.34    5060  395.45  5065.2  395.57  5073.1   396.2  5083.5  396.76
  5125.1  397.21  5145.8  398.31  5211.5  400.52  5239.4  401.94  5245.5  402.74
  5250.7   402.9  5279.5  404.93  5284.7  404.97  5299.1  406.51  5301.7  406.51
#Mann= 4 ,-1 , 0
  4709.3      .1       0  4940.1     .16       0  4997.4     .07       0
  5003.4     .16       0
Bank Sta=4997.4,5003.4
XS Rating Curve= 0 ,0
Exp/Cntr=0.3,0.1

Type RM Length L Ch R = 1 ,2509    ,471,471,471
BEGIN DESCRIPTION:
COPPERAS CREEK TRIBUTARY 10.1 3.0
END DESCRIPTION:
XS GIS Cut Line= 3
      3520015.72     10318756.97      3520015.72     10318306.92
      3519817.23     10317940.47
#Sta/Elev= 30
  4455.2  399.57  4470.5  399.69  4480.5  399.04  4500.5  399.36  4520.5  398.31
  4560.5  397.57  4570.5  397.94  4600.5  396.67  4630.5  396.88  4670.5  395.29
  4710.5  395.51  4740.5  394.61  4860.5   394.2  4911.3  393.49  4979.5  391.49
  4991.4  388.23  4998.9  386.95  5001.7  386.45  5004.9  386.95  5013.6  390.91
  5023.8  391.91  5045.7  392.23  5059.1  393.38  5089.4  394.02  5149.3  396.69
  5176.9   398.8  5242.5  402.82  5274.9  404.36  5286.6  405.35    5322  406.74
#Mann= 3 ,-1 , 0
  4455.2     .16       0  4998.9     .07       0  5004.9     .16       0
Bank Sta=4998.9,5004.9
XS Rating Curve= 0 ,0
Exp/Cntr=0.3,0.1

Type RM Length L Ch R = 1 ,2038    ,1074,1074,1074
BEGIN DESCRIPTION:
COPPERAS CREEK TRIBUTARY 10.1 3.01
END DESCRIPTION:
XS GIS Cut Line= 4
      3520098.25     10318760.31      3520230.21     10318176.93
      3520349.48     10317908.56      3520178.11      10317690.8
#Sta/Elev= 30
  4162.2  396.92    4479  390.89  4591.4  390.14  4743.2  391.45  4809.9  391.33
  4878.4  389.56  4976.9  390.31    4985  387.82  4991.7  382.62  4994.4  382.12
  4997.7  382.62  5006.9  386.17  5017.8  387.93  5023.4  390.01  5039.7  390.78
  5074.2  390.64  5156.5  389.38  5214.3  389.98  5228.2  390.26  5235.1  391.33
  5241.5  390.54  5249.6  391.84    5256  390.96    5264  392.43  5270.4  391.51
  5278.5  393.32  5284.9  392.18  5291.9  394.07  5299.3  394.63  5331.1   395.2
#Mann= 4 ,-1 , 0
  4162.2     .16       0  4991.7     .07       0  4997.7     .16       0
  5074.2     .05       0
Bank Sta=4991.7,4997.7
XS Rating Curve= 0 ,0
Exp/Cntr=0.3,0.1

Type RM Length L Ch R = 1 ,964     ,167,167,167
BEGIN DESCRIPTION:
COPPERAS CREEK TRIBUTARY 10.1 1.0
END DESCRIPTION:
XS GIS Cut Line= 4
      3520450.94      10319060.3      3520811.17     10318956.14
      3520850.23     10318556.83      3520272.96     10317610.62
#Sta/Elev= 30
  4484.4  397.26  4589.7  390.14  4711.5   385.8  4808.3  383.98  4856.4  385.09
  4919.8  383.49  4974.4  383.97  4991.5  378.87  4994.3  378.37  4997.5  378.87
  5014.6   383.5  5021.3  384.33    5095  383.24  5260.6  383.29  5263.7  382.54
  5313.5     384  5459.3  384.78  5627.7   387.6  5685.8  386.92  5858.3  388.79
  5997.5  388.26    6013  390.13  6018.8  389.38  6055.6  390.64  6071.1  389.32
  6092.4  389.72  6107.8  388.56  6252.7  388.91  6286.5  388.94    6369  389.19
#Mann= 6 ,-1 , 0
  4484.4     .16       0  4974.4     .05       0  5021.3      .1       0
  5858.3     .05       0  6252.7     .16       0  6286.5     .05       0
Bank Sta=4991.5,4997.5
XS Rating Curve= 0 ,0
Exp/Cntr=0.3,0.1

Type RM Length L Ch R = 1 ,797     ,0,0,0
BEGIN DESCRIPTION:
COPPERAS CREEK TRIBUTARY 10.1 1.01
END DESCRIPTION:
XS GIS Cut Line= 4
      3520544.33     10319183.87      3520987.08      10318940.8
      3520980.57     10318437.33      3520606.84     10318026.88
#Sta/Elev= 30
  4391.8  395.13  4509.9  387.57    4606  385.32  4651.1  384.73  4722.2  386.11
  4825.4  382.94    4906   382.4    4986  383.02    4993  378.09  4995.8  377.59
    4999  378.09  5016.1  381.65  5056.1  382.96  5096.1  382.98  5126.1  381.82
  5166.1  383.37  5276.1  384.35  5403.4  383.05  5417.6  382.66    5446  380.45
  5481.1  382.95  5537.9  383.99  5558.8  385.75  5594.6  385.31  5669.5  386.13
  5714.9  385.96  5792.6  387.74    5821  386.78  5849.4  386.77  5955.5   388.7
#Mann= 4 ,-1 , 0
  4391.8     .16       0    4986     .05       0  5016.1     .07       0
  5669.5     .05       0
Bank Sta=4993,4999
XS Rating Curve= 0 ,0
Exp/Cntr=0.3,0.1

Chan Stop Cuts=-1
Use User Specified Reach Order=0
Composite Channel Slope=5