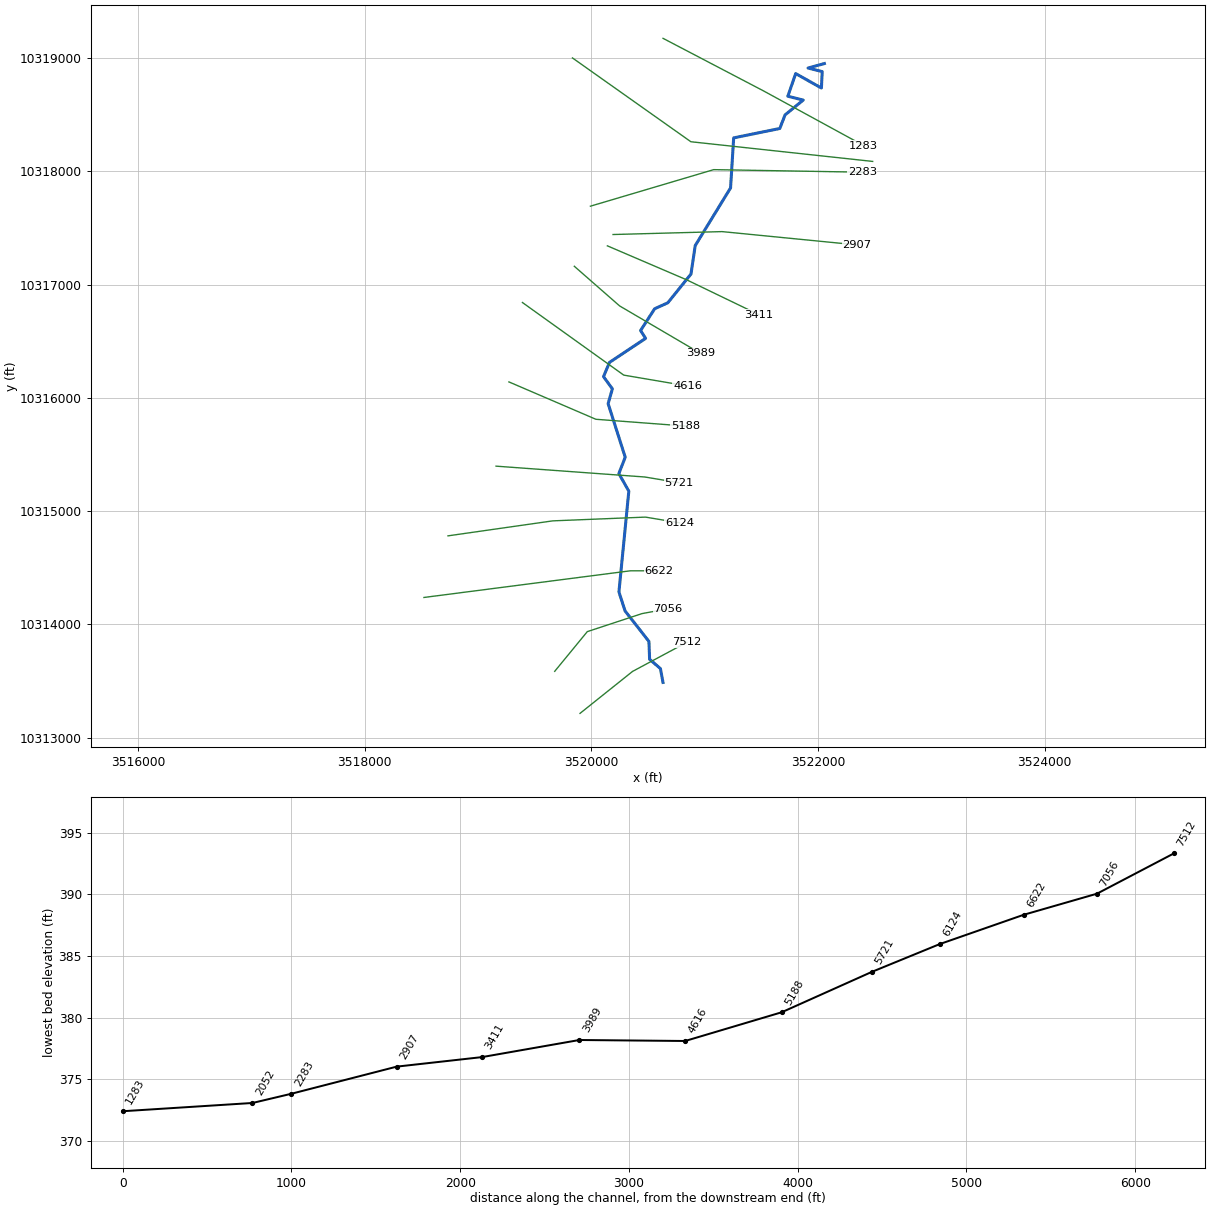
--- COPPERAS CREEK TRIBUTARY 10.prj (project) ---

Proj Title=COPPERAS CREEK TRIBUTARY 10 Base Level Engineering
Current Plan=p01
Default Exp/Contr=0.3,0.1
English Units
Geom File=g01
Flow File=f01
Plan File=p01
Y Axis Title=Elevation
X Axis Title(PF)=Main Channel Distance
X Axis Title(XS)=Station
BEGIN DESCRIPTION:
COPPERAS CREEK TRIBUTARY 10
END DESCRIPTION:
DSS Export Rating Curves= 0
DSS Export Rating Curve Sorted= 0
DSS Export Volume Flow Curves= 0
DXF OffsetX= 0
DXF OffsetY= 0
DXF ScaleX= 1
DXF ScaleY= 10

--- COPPERAS CREEK TRIBUTARY 10.p01 (plan) ---

Plan Title=Multiple Run
Short Identifier=Multiple
Geom File=g01
Flow File=f01
Subcritical Flow
K Sum by GR= 0
Std Step Tol= 0.01
Critical Tol= 0.01
Num of Std Step Trials= 20
Max Error Tol= 0.3
Flow Tol Ratio= 0.001
Split Flow NTrial= 30
Split Flow Tol= 0.02
Split Flow Ratio= 0.02
Log Output Level= 0
Friction Slope Method= 1
Unsteady Friction Slope Method= 2
Unsteady Bridges Friction Slope Method= 1
Parabolic Critical Depth
Global Vel Dist=  1 , 1 , 1
Global Log Level= 0
CheckData=True
Encroach Param= -1, 0, 0, 0
BEGIN DESCRIPTION:
Multiple Run
END DESCRIPTION:

--- COPPERAS CREEK TRIBUTARY 10.f01 (steady flow) ---

Flow Title=Multiple
Program Version=4.10
Number of Profiles= 7
Profile Names=10-year,25-year,50-year,1pct_min,100-year,1pct_plu,500-year
River Rch & RM=COPPERAS CREEK T,Reach-1         ,7512
     751    1040    1282    1157    1565    2117    2342
River Rch & RM=COPPERAS CREEK T,Reach-1         ,4616
     772    1067    1313    1183    1600    2164    2382
River Rch & RM=COPPERAS CREEK T,Reach-1         ,2052
     992    1390    1726    1569    2122    2869    3216
River Rch & RM=COPPERAS CREEK T,Reach-1         ,1283
     992    1390    1726    1569    2122    2869    3216
Boundary for River Rch & Prof#=COPPERAS CREEK T,Reach-1         , 1
Up Type= 0
Dn Type= 3
Dn Slope=0.005
Boundary for River Rch & Prof#=COPPERAS CREEK T,Reach-1         , 2
Up Type= 0
Dn Type= 3
Dn Slope=0.005
Boundary for River Rch & Prof#=COPPERAS CREEK T,Reach-1         , 3
Up Type= 0
Dn Type= 3
Dn Slope=0.005
Boundary for River Rch & Prof#=COPPERAS CREEK T,Reach-1         , 4
Up Type= 0
Dn Type= 3
Dn Slope=0.005
Boundary for River Rch & Prof#=COPPERAS CREEK T,Reach-1         , 5
Up Type= 0
Dn Type= 3
Dn Slope=0.005
Boundary for River Rch & Prof#=COPPERAS CREEK T,Reach-1         , 6
Up Type= 0
Dn Type= 3
Dn Slope=0.005
Boundary for River Rch & Prof#=COPPERAS CREEK T,Reach-1         , 7
Up Type= 0
Dn Type= 3
Dn Slope=0.005
DSS Import GetInterval= 0
DSS Import GetPeak= 0
DSS Import FillOption= 0

--- COPPERAS CREEK TRIBUTARY 10.g01 (geometry) ---

Geom Title=Existing Conditions
Program Version=4.10

River Reach=COPPERAS CREEK T,Reach-1
Reach XY= 30
      3520632.88     10313488.57      3520609.93     10313610.81
      3520514.74     10313692.54      3520508.66     10313850.28
      3520297.96     10314119.56      3520243.97     10314287.41
      3520331.25     10315176.46      3520243.42     10315332.03
      3520299.61     10315476.13      3520148.61     10315948.61
      3520185.93     10316079.69      3520107.81     10316187.32
      3520160.76     10316313.19      3520479.34       10316525.
      3520435.06     10316594.44       3520559.2     10316786.28
      3520675.52     10316839.23      3520879.84     10317092.76
      3520917.28     10317344.01      3521229.15     10317852.87
      3521256.71     10318294.58      3521663.64      10318377.5
      3521710.36     10318497.45      3521870.48     10318628.25
      3521734.75     10318662.21      3521803.98     10318862.12
      3522031.01     10318734.56      3522038.13     10318879.58
      3521912.87     10318911.03      3522057.28     10318950.54

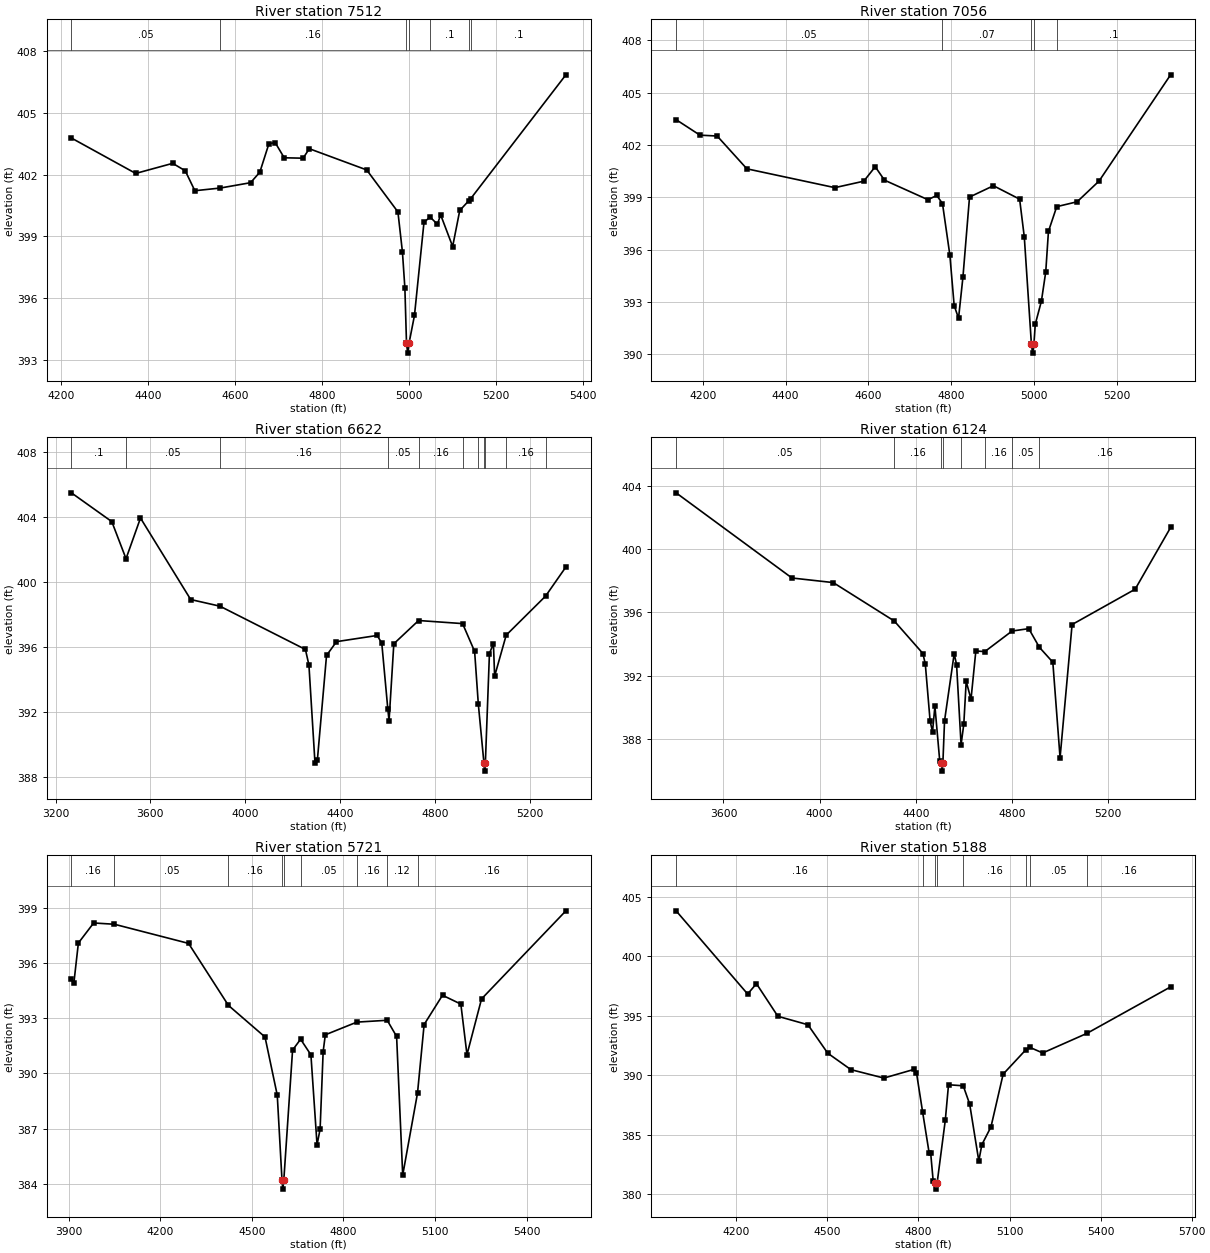
Type RM Length L Ch R = 1 ,7512    ,456,456,456
BEGIN DESCRIPTION:
COPPERAS CREEK TRIBUTARY 10 13.0
END DESCRIPTION:
XS GIS Cut Line= 3
      3519900.62      10313215.3      3520364.25     10313585.65
      3520842.11     10313841.65
#Sta/Elev= 30
  4224.2  403.78  4371.9  402.06  4456.8  402.55  4485.6  402.19  4507.7  401.22
    4566  401.35  4635.7  401.61  4656.9  402.12  4677.7   403.5  4692.1  403.56
  4712.9  402.82  4756.2   402.8  4770.6  403.26  4902.3  402.23    4974  400.19
  4984.4  398.24    4990  396.49  4993.7  393.83  4996.4  393.33  4999.7  393.83
    5012  395.16  5033.9  399.69    5048  399.94  5064.7  399.59  5072.1  400.05
  5099.7  398.51    5116  400.26  5136.2  400.72    5141  400.83  5359.7  406.85
#Mann= 7 ,-1 , 0
  4224.2     .05       0    4566     .16       0  4993.7     .07       0
  4999.7     .16       0    5048      .1       0  5136.2     .16       0
    5141      .1       0
Bank Sta=4993.7,4999.7
XS Rating Curve= 0 ,0
Exp/Cntr=0.3,0.1

Type RM Length L Ch R = 1 ,7056    ,434,434,434
BEGIN DESCRIPTION:
COPPERAS CREEK TRIBUTARY 10 12.0
END DESCRIPTION:
XS GIS Cut Line= 4
      3519677.09      10313586.4      3519964.67     10313936.68
      3520448.39     10314096.09      3520676.24     10314138.06
#Sta/Elev= 30
  4135.8  403.45  4193.4  402.56    4235  402.51  4306.7  400.63  4519.2  399.55
    4589  399.92  4616.7  400.75    4639  399.98  4743.8  398.86  4765.3   399.1
  4779.1  398.64  4796.9  395.69  4807.3  392.79  4817.9  392.06  4828.5  394.42
  4844.4  399.01  4902.2  399.66  4965.4  398.89  4976.7  396.72  4993.9  390.56
  4996.7  390.06  4999.9  390.56  5003.2  391.72    5018  393.04  5028.5  394.72
    5035  397.04    5055  398.46  5104.3  398.74  5157.3  399.93    5330  406.02
#Mann= 5 ,-1 , 0
  4135.8     .05       0  4779.1     .07       0  4993.9     .07       0
  4999.9     .07       0    5055      .1       0
Bank Sta=4993.9,4999.9
XS Rating Curve= 0 ,0
Exp/Cntr=0.3,0.1

Type RM Length L Ch R = 1 ,6622    ,498,498,498
BEGIN DESCRIPTION:
COPPERAS CREEK TRIBUTARY 10 11.0
END DESCRIPTION:
XS GIS Cut Line= 3
      3518522.97     10314238.29      3520344.04     10314473.56
      3520594.03     10314473.56
#Sta/Elev= 30
  3266.6  405.46  3437.1  403.69  3497.1  401.41  3558.1  403.91  3769.9   398.9
  3893.5  398.49  4253.9  395.83  4268.7  394.88  4294.2  388.87  4304.3  389.02
    4343  395.46    4385  396.31  4556.4  396.69    4576  396.23  4601.7  392.15
  4606.8  391.44  4626.9  396.18  4731.4  397.61    4917  397.42  4967.8  395.71
  4983.4  392.47  5007.1  388.85  5009.9  388.35  5013.1  388.85  5030.3  395.58
  5047.1  396.19  5052.2  394.19    5101  396.71  5267.1  399.11  5352.8   400.9
#Mann= 11 ,-1 , 0
  3266.6      .1       0  3497.1     .05       0  3893.5     .16       0
  4601.7     .05       0  4731.4     .16       0    4917     .05       0
  4983.4      .1       0  5007.1     .07       0  5013.1      .1       0
    5101     .16       0  5267.1      .1       0
Bank Sta=5007.1,5013.1
XS Rating Curve= 0 ,0
Exp/Cntr=0.3,0.1

Type RM Length L Ch R = 1 ,6124    ,403,403,403
BEGIN DESCRIPTION:
COPPERAS CREEK TRIBUTARY 10 10.0
END DESCRIPTION:
XS GIS Cut Line= 4
       3518735.2     10314782.12       3519659.9     10314914.37
      3520477.99     10314947.54      3520777.59     10314897.61
#Sta/Elev= 30
  3403.1  403.55  3884.9  398.17  4056.6  397.88  4310.7  395.45  4429.5   393.4
  4439.5  392.74  4459.5  389.14  4469.5  388.46  4479.5  390.07  4499.5  386.62
  4506.6  386.47  4509.3  385.97  4512.6  386.47  4519.6  389.16  4559.6  393.38
  4569.6   392.7  4588.3  387.64  4599.6  388.93  4609.6  391.64  4629.6  390.51
  4649.7  393.56    4687  393.52  4800.3  394.82  4869.8  394.97  4914.1  393.79
  4969.9  392.85    5000  386.82    5050  395.23  5312.2  397.46  5459.7  401.36
#Mann= 8 ,-1 , 0
  3403.1     .05       0  4310.7     .16       0  4506.6     .07       0
  4512.6     .16       0  4588.3     .05       0    4687     .16       0
  4800.3     .05       0  4914.1     .16       0
Bank Sta=4506.6,4512.6
XS Rating Curve= 0 ,0
Exp/Cntr=0.3,0.1

Type RM Length L Ch R = 1 ,5721    ,533,533,533
BEGIN DESCRIPTION:
COPPERAS CREEK TRIBUTARY 10 9.0
END DESCRIPTION:
XS GIS Cut Line= 3
      3519159.26     10315397.26      3520471.99      10315301.6
      3520772.04      10315251.6
#Sta/Elev= 30
  3908.5  395.14  3916.7  394.93  3931.4  397.09  3981.5  398.18  4049.5  398.11
  4292.4  397.07    4423   393.7    4543  391.98  4583.1  388.82  4598.6  384.21
  4601.3  383.71  4604.6  384.21  4633.3  391.27  4659.6  391.86  4693.4  391.01
  4713.5  386.12  4723.5  386.97  4733.5  391.19  4740.6   392.1    4844  392.79
  4943.4  392.89  4974.2  392.01  4994.2  384.47  5042.7  388.93  5064.4  392.66
  5124.6  394.25  5184.7  393.77  5204.8  391.02  5252.5  394.05  5528.9  398.84
#Mann= 9 ,-1 , 0
  3908.5     .16       0  4049.5     .05       0    4423     .16       0
  4598.6     .07       0  4604.6     .16       0  4659.6     .05       0
    4844     .16       0  4943.4     .12       0  5042.7     .16       0
Bank Sta=4598.6,4604.6
XS Rating Curve= 0 ,0
Exp/Cntr=0.3,0.1

Type RM Length L Ch R = 1 ,5188    ,572,572,572
BEGIN DESCRIPTION:
COPPERAS CREEK TRIBUTARY 10 8.0
END DESCRIPTION:
XS GIS Cut Line= 3
      3519273.12     10316140.79      3520040.65       10315811.
      3520832.19     10315751.03
#Sta/Elev= 30
  4001.4  403.82  4237.1  396.83  4266.1   397.7  4336.7  394.96  4435.7  394.25
    4501  391.86  4577.2  390.48    4686  389.77    4784  390.49  4793.3  390.23
  4813.7   386.9  4834.9  383.51    4840  383.51  4848.3  381.15  4855.3  380.94
  4858.1  380.44  4861.3  380.94  4888.4  386.25  4898.9  389.21  4947.4  389.12
  4968.6  387.59  4998.7  382.81  5008.7  384.17  5038.8  385.67  5078.9   390.1
  5153.8  392.15  5166.9  392.35  5209.3  391.88  5354.5  393.52  5630.6  397.43
#Mann= 8 ,-1 , 0
  4001.4     .16       0  4813.7     .12       0  4855.3     .07       0
  4861.3     .12       0  4947.4     .16       0  5153.8     .12       0
  5166.9     .05       0  5354.5     .16       0
Bank Sta=4855.3,4861.3
XS Rating Curve= 0 ,0
Exp/Cntr=0.3,0.1

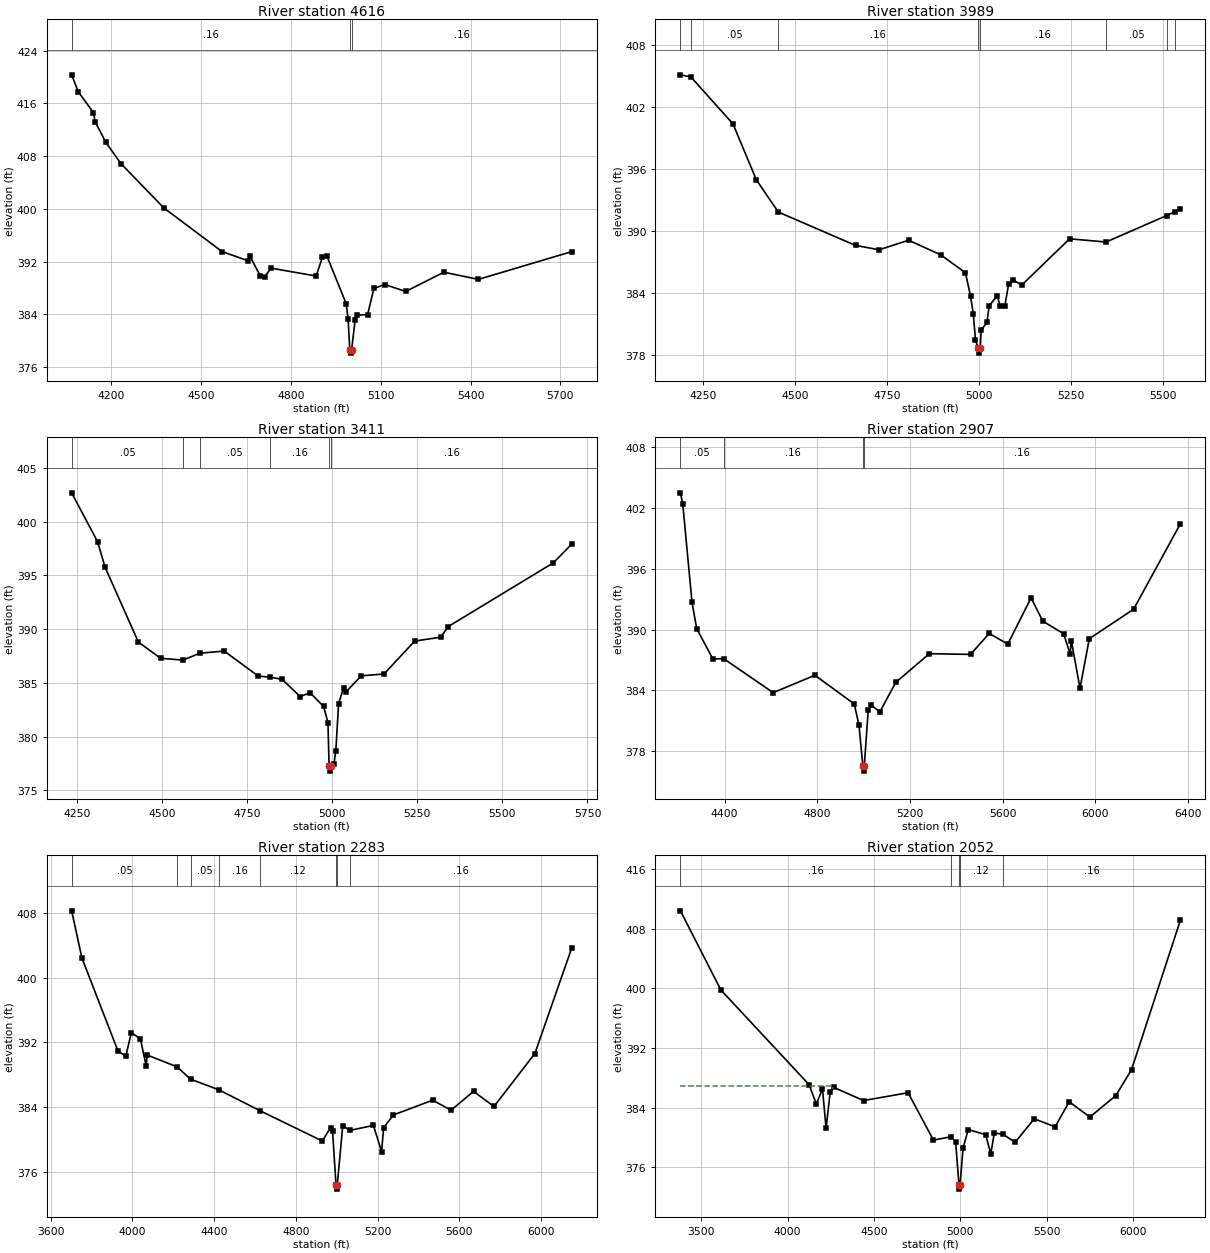
Type RM Length L Ch R = 1 ,4616    ,627,627,627
BEGIN DESCRIPTION:
COPPERAS CREEK TRIBUTARY 10 7.0
END DESCRIPTION:
XS GIS Cut Line= 3
      3519392.09     10316841.65      3520286.49     10316200.75
      3520848.58     10316105.07
#Sta/Elev= 30
  4067.3  420.34  4089.4  417.76  4139.8  414.62  4145.9   413.2  4181.6  410.09
  4231.9  406.87  4374.9  400.16  4569.7  393.52  4655.7  392.14  4661.8  392.91
  4697.4  389.84  4712.2  389.67    4733  391.01  4884.1  389.81    4905  392.64
  4919.7  392.88  4984.8  385.58    4991  383.22  4996.6  378.61  4999.3  378.11
  5002.6  378.61  5014.3  383.09  5020.5  383.87  5056.1  383.95    5077  387.92
    5113  388.52  5183.5  387.47  5310.8  390.39  5426.2   389.3  5737.8  393.51
#Mann= 3 ,-1 , 0
  4067.3     .16       0  4996.6     .07       0  5002.6     .16       0
Bank Sta=4996.6,5002.6
XS Rating Curve= 0 ,0
Exp/Cntr=0.3,0.1

Type RM Length L Ch R = 1 ,3989    ,578,578,578
BEGIN DESCRIPTION:
COPPERAS CREEK TRIBUTARY 10 6.0
END DESCRIPTION:
XS GIS Cut Line= 3
      3519850.15     10317161.36      3520250.13     10316811.37
       3520964.1      10316392.6
#Sta/Elev= 30
  4188.8  405.14  4217.1  404.94  4331.8  400.38  4395.4  394.96  4454.9  391.85
  4664.9  388.62    4729   388.2  4809.1  389.12  4896.5  387.71  4963.5  385.97
  4977.6   383.7    4985  381.98  4990.8   379.5  4997.7  378.69  5000.4  378.19
  5003.7  378.69  5006.5  380.39  5022.2  381.19    5028  382.76  5049.4  383.73
  5058.8  382.73  5070.9   382.8  5080.8  384.85  5093.6  385.27  5116.7  384.78
  5246.8  389.26  5345.8  388.95  5510.5  391.51  5533.7  391.89    5548  392.19
#Mann= 8 ,-1 , 0
  4188.8     .16       0  4217.1     .05       0  4454.9     .16       0
  4997.7     .07       0  5003.7     .16       0  5345.8     .05       0
  5510.5     .16       0  5533.7     .05       0
Bank Sta=4997.7,5003.7
XS Rating Curve= 0 ,0
Exp/Cntr=0.3,0.1

Type RM Length L Ch R = 1 ,3411    ,504,504,504
BEGIN DESCRIPTION:
COPPERAS CREEK TRIBUTARY 10 4.0
END DESCRIPTION:
XS GIS Cut Line= 3
      3520142.09     10317341.65      3520842.11     10317041.64
      3521478.36      10316734.5
#Sta/Elev= 30
  4235.4  402.67  4311.6  398.12  4333.3  395.77  4431.2   388.8  4496.5  387.29
  4562.4  387.12  4611.3  387.76  4683.3  387.96    4783  385.64  4819.1  385.53
  4853.7  385.33  4906.3  383.73  4935.3  384.09  4975.2  382.81  4987.9  381.31
  4991.3   377.3    4994   376.8  4997.3   377.3  5005.5  377.46  5011.1   378.7
  5019.2  383.08  5033.7  384.53  5041.4  384.18  5085.8  385.66  5152.5  385.83
  5242.7  388.89    5319  389.25  5341.2  390.24  5649.6  396.16  5703.5  397.89
#Mann= 6 ,-1 , 0
  4235.4     .05       0  4562.4     .16       0  4611.3     .05       0
  4819.1     .16       0  4991.3     .07       0  4997.3     .16       0
Bank Sta=4991.3,4997.3
XS Rating Curve= 0 ,0
Exp/Cntr=0.3,0.1

Type RM Length L Ch R = 1 ,2907    ,624,624,624
BEGIN DESCRIPTION:
COPPERAS CREEK TRIBUTARY 10 3.0
END DESCRIPTION:
XS GIS Cut Line= 3
      3520192.07     10317441.64      3521154.05     10317467.42
      3522343.27     10317350.24
#Sta/Elev= 30
  4209.5  403.52  4219.5  402.42  4259.5   392.7  4279.6  390.11  4349.6  387.11
  4396.1  387.14  4609.7  383.78  4789.7   385.5  4959.8  382.66  4979.8  380.56
  4996.8  376.53  4999.6  376.03  5002.8  376.53  5019.8  382.08  5029.8  382.59
  5069.8  381.88  5138.8   384.8  5283.6  387.63  5461.3  387.56  5541.7  389.63
    5622  388.58  5722.5  393.15  5772.8  390.85  5863.2  389.59    5891   387.6
    5896  388.93  5933.5  384.22  5973.7  389.11  6164.7  392.02  6366.8  400.47
#Mann= 4 ,-1 , 0
  4209.5     .05       0  4396.1     .16       0  4996.8     .07       0
  5002.8     .16       0
Bank Sta=4996.8,5002.8
XS Rating Curve= 0 ,0
Exp/Cntr=0.3,0.1

Type RM Length L Ch R = 1 ,2283    ,231,231,231
BEGIN DESCRIPTION:
COPPERAS CREEK TRIBUTARY 10 2.0
END DESCRIPTION:
XS GIS Cut Line= 3
      3519992.14     10317691.65      3521080.27      10318014.3
      3522392.12     10317991.64
#Sta/Elev= 30
  3702.4  408.25  3752.2  402.44  3928.8  390.93  3967.3  390.26  3994.4  393.17
  4038.9  392.42    4067  389.06  4072.2  390.42  4218.2  388.95  4284.2  387.43
  4421.9  386.12  4625.5  383.51  4929.2  379.78  4969.2  381.43  4979.2  381.06
  4996.2  374.33    4999  373.83  5002.2  374.33  5029.2  381.69  5063.7  381.09
  5179.2  381.71  5219.2  378.47  5229.3  381.44  5277.5  383.01  5469.3  384.83
  5559.3  383.59  5669.3  385.92  5769.3  384.05  5969.4   390.6  6149.4  403.63
#Mann= 8 ,-1 , 0
  3702.4     .05       0  4218.2     .12       0  4284.2     .05       0
  4421.9     .16       0  4625.5     .12       0  4996.2     .07       0
  5002.2     .12       0  5063.7     .16       0
Bank Sta=4996.2,5002.2
XS Rating Curve= 0 ,0
Exp/Cntr=0.3,0.1

Type RM Length L Ch R = 1 ,2052    ,769,769,769
BEGIN DESCRIPTION:
COPPERAS CREEK TRIBUTARY 10 2.01
END DESCRIPTION:
XS GIS Cut Line= 3
      3519833.87     10319000.11        3520879.     10318260.53
      3522483.19     10318086.92
#Sta/Elev= 30
  3379.5  410.41  3613.4   399.8  4124.2  387.09    4166  384.51  4201.7   386.5
  4222.6  381.24  4246.1  386.05    4267  386.72  4439.3  384.96  4697.1  386.01
    4844  379.65  4945.1  380.11  4972.3  379.43  4991.9  373.58  4994.6  373.08
  4997.9  373.58    5015  378.56  5045.2  381.07  5145.8  380.39  5175.9  377.82
  5196.1  380.58  5244.4  380.48  5316.8  379.36  5427.4  382.52  5548.1  381.43
  5629.5   384.8  5749.3  382.75  5899.7  385.63  5990.7  389.12  6273.4  409.17
#Mann= 5 ,-1 , 0
  3379.5     .16       0  4945.1     .12       0  4991.9     .07       0
  4997.9     .12       0  5244.4     .16       0
#XS Ineff= 2 , 0
          4260.8  386.95
Permanent Ineff=
       F       F
Bank Sta=4991.9,4997.9
XS Rating Curve= 0 ,0
Exp/Cntr=0.3,0.1

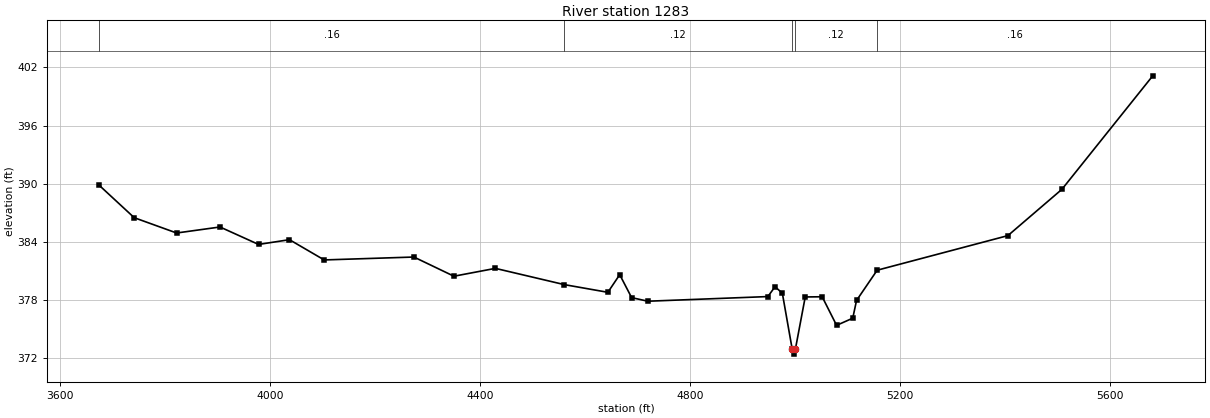
Type RM Length L Ch R = 1 ,1283    ,0,0,0
BEGIN DESCRIPTION:
COPPERAS CREEK TRIBUTARY 10 1.0
END DESCRIPTION:
XS GIS Cut Line= 3
       3520633.2     10319173.16      3521520.92     10318708.83
      3522404.09     10318226.95
#Sta/Elev= 30
  3674.2  389.82  3740.7  386.49  3821.5  384.91  3904.2  385.53  3977.7  383.73
  4036.6  384.22  4102.8  382.13  4273.8  382.43  4350.1  380.45  4429.1  381.26
  4560.8  379.58  4643.5  378.79  4666.1  380.61  4688.8  378.24  4719.8  377.87
  4948.5  378.35  4962.2  379.37  4976.1  378.69  4994.9  372.91  4997.7  372.41
  5000.9  372.91  5019.7  378.31    5052  378.33  5079.5  375.38  5110.3  376.12
  5117.5  377.95  5156.8  381.07    5406  384.64    5509  389.42  5682.1  401.13
#Mann= 5 ,-1 , 0
  3674.2     .16       0  4560.8     .12       0  4994.9     .07       0
  5000.9     .12       0  5156.8     .16       0
Bank Sta=4994.9,5000.9
XS Rating Curve= 0 ,0
Exp/Cntr=0.3,0.1

Chan Stop Cuts=-1
Use User Specified Reach Order=0
Composite Channel Slope=5