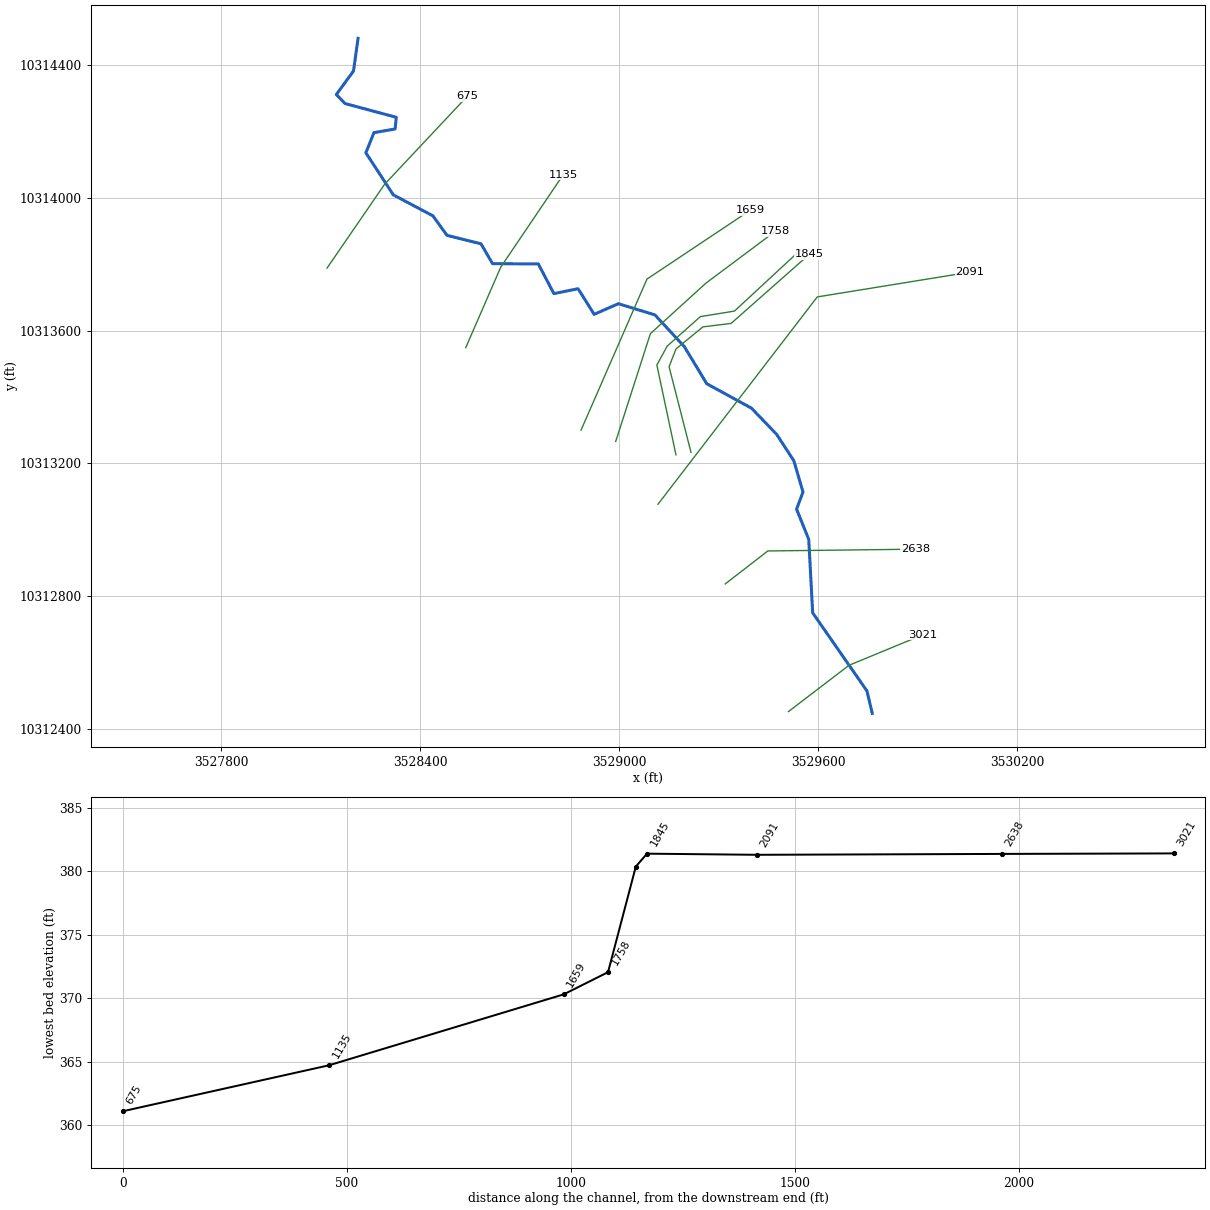
--- COPPERAS CREEK TRIBUTARY 5 1.prj (project) ---

Proj Title=COPPERAS CREEK TRIBUTARY 5 1 Base Level Engineering
Current Plan=p01
Default Exp/Contr=0.3,0.1
English Units
Geom File=g01
Flow File=f01
Plan File=p01
BEGIN DESCRIPTION:
COPPERAS CREEK TRIBUTARY 5 1
END DESCRIPTION:

--- COPPERAS CREEK TRIBUTARY 5 1.p01 (plan) ---

Plan Title=Multiple Run
Short Identifier=Multiple
Geom File=g01
Flow File=f01
Subcritical Flow
K Sum by GR= 0
Std Step Tol= 0.01
Critical Tol= 0.01
Num of Std Step Trials= 20
Max Error Tol= 0.3
Flow Tol Ratio= 0.001
Split Flow NTrial= 30
Split Flow Tol= 0.02
Split Flow Ratio= 0.02
Log Output Level= 0
Friction Slope Method= 1
Unsteady Friction Slope Method= 2
Unsteady Bridges Friction Slope Method= 1
Parabolic Critical Depth
Global Vel Dist=  1 , 1 , 1
Global Log Level= 0
CheckData=True
Encroach Param= -1, 0, 0, 0
BEGIN DESCRIPTION:
Multiple Run
END DESCRIPTION:

--- COPPERAS CREEK TRIBUTARY 5 1.f01 (steady flow) ---

Flow Title=Multiple
Number of Profiles=7
Profile Names=10-year,25-year,50-year,1pct_min,100-year,1pct_plu,500-year
River Rch & RM= COPPERAS CREEK T,Reach-1,3021
     431     579     699     619     838    1133    1206
Boundary for River Rch & Prof#=COPPERAS CREEK T,Reach-1,1
Up Type=0
Dn Type=3
Dn Slope=0.005
Boundary for River Rch & Prof#=COPPERAS CREEK T,Reach-1,2
Up Type=0
Dn Type=3
Dn Slope=0.005
Boundary for River Rch & Prof#=COPPERAS CREEK T,Reach-1,3
Up Type=0
Dn Type=3
Dn Slope=0.005
Boundary for River Rch & Prof#=COPPERAS CREEK T,Reach-1,4
Up Type=0
Dn Type=3
Dn Slope=0.005
Boundary for River Rch & Prof#=COPPERAS CREEK T,Reach-1,5
Up Type=0
Dn Type=3
Dn Slope=0.005
Boundary for River Rch & Prof#=COPPERAS CREEK T,Reach-1,6
Up Type=0
Dn Type=3
Dn Slope=0.005
Boundary for River Rch & Prof#=COPPERAS CREEK T,Reach-1,7
Up Type=0
Dn Type=3
Dn Slope=0.005

--- COPPERAS CREEK TRIBUTARY 5 1.g01 (geometry) ---

Geom Title=Existing Conditions

River Reach=COPPERAS CREEK T,Reach-1
Reach XY= 30
      3529762.21     10312446.68      3529746.18     10312514.18
      3529582.56     10312749.83      3529570.71     10312971.08
      3529534.01     10313062.25      3529553.42     10313113.95
      3529525.73     10313208.37      3529473.73     10313288.04
      3529398.03     10313366.76      3529263.30     10313440.39
      3529195.59     10313552.37      3529107.05     10313647.85
      3528996.80     10313681.71      3528923.89     10313649.59
      3528875.28     10313726.85      3528802.36     10313712.09
      3528755.49     10313801.50      3528617.46     10313802.37
      3528582.74     10313862.26      3528480.12     10313887.81
      3528437.75     10313946.50      3528318.39     10314009.70
      3528235.53     10314136.75      3528260.10     10314197.38
      3528323.75     10314208.38      3528327.29     10314243.54
      3528172.68     10314285.14      3528146.60     10314312.24
      3528198.28     10314383.12      3528212.11     10314481.64

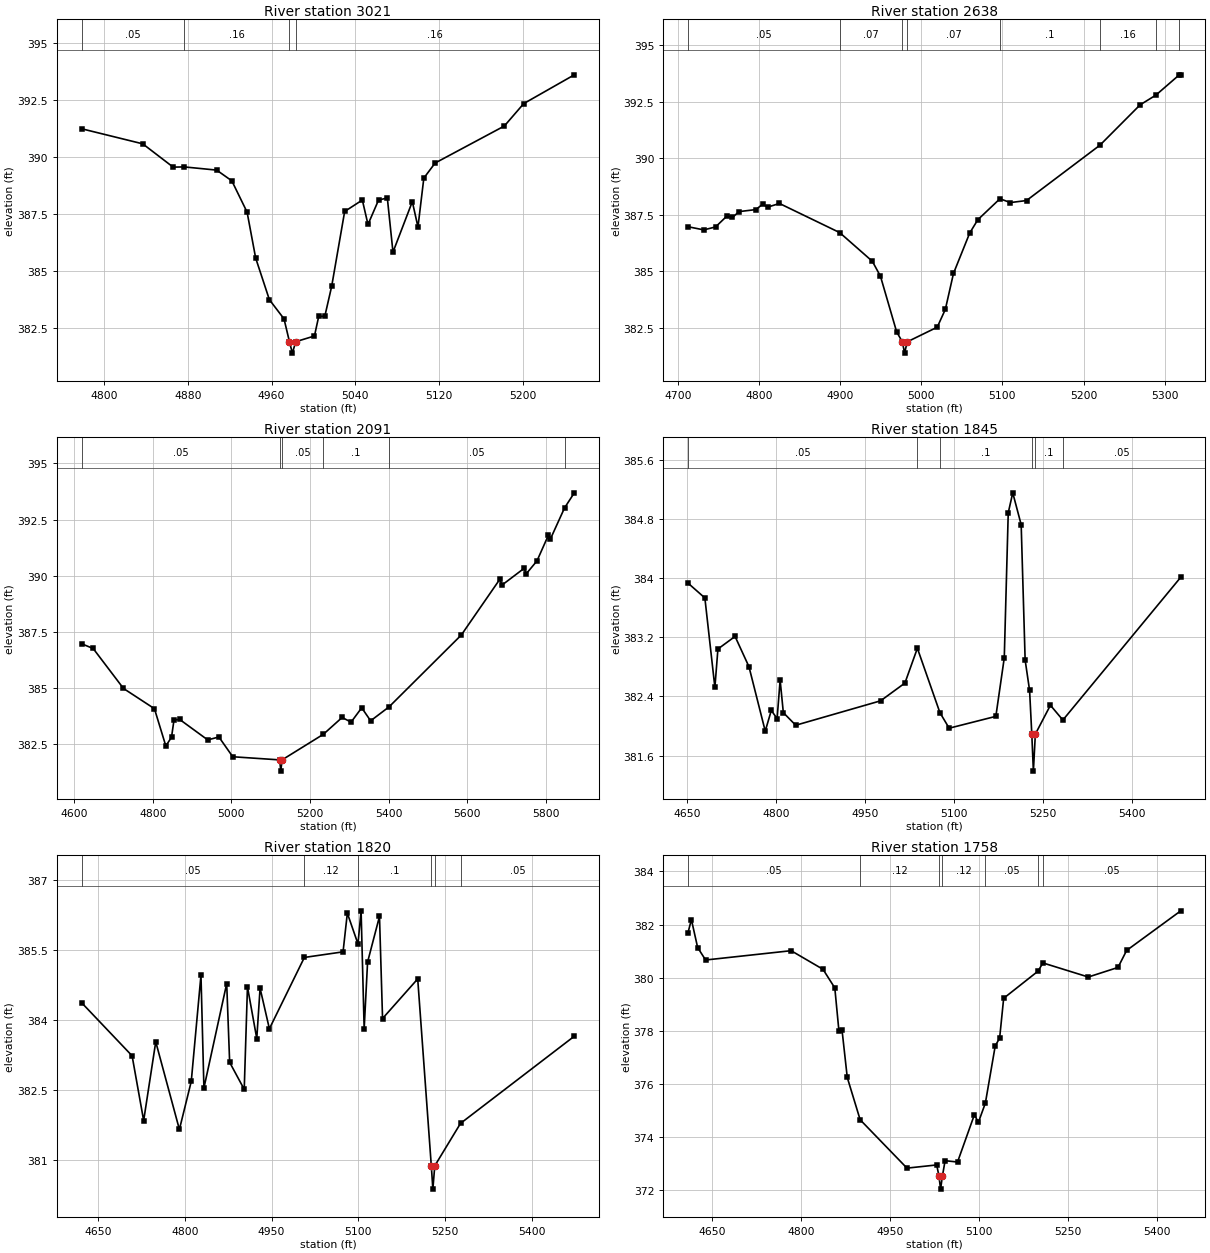
Type RM Length L Ch R = 1,3021,383,383,383
BEGIN DESCRIPTION:
COPPERAS CREEK TRIBUTARY 5.1 6.0
END DESCRIPTION:
XS GIS Cut Line= 3
      3529509.45     10312452.01      3529692.11     10312591.64
      3529915.10     10312683.80
#Sta/Elev= 30
  4778.3  391.23  4836.8  390.57  4865.9  389.55  4876.5  389.56  4907.5  389.42
  4922.0  388.95  4936.6  387.58  4944.8  385.57  4957.9  383.75  4971.9  382.91
  4977.1  381.91  4979.9  381.41  4983.1  381.91  5001.0  382.16  5005.1  383.02
  5010.9  383.02  5017.5  384.34  5029.9  387.61  5046.8  388.11  5052.2  387.04
  5062.3  388.11  5070.7  388.20  5076.1  385.83  5094.6  388.04  5100.0  386.93
  5105.6  389.07  5116.4  389.73  5182.6  391.35  5201.1  392.33  5249.5  393.59
#Mann=4,-1,0
  4778.3    0.05       0  4876.5    0.16       0  4977.1    0.07       0
  4983.1    0.16       0
Bank Sta=4977.1,4983.1
Exp/Cntr=0.3,0.1

Type RM Length L Ch R = 1,2638,547,547,547
BEGIN DESCRIPTION:
COPPERAS CREEK TRIBUTARY 5.1 5.0
END DESCRIPTION:
XS GIS Cut Line= 3
      3529318.96     10312836.92      3529447.32     10312936.30
      3529892.15     10312941.64
#Sta/Elev= 30
  4712.6  386.97  4732.0  386.83  4746.5  386.96  4761.0  387.46  4767.3  387.38
  4775.5  387.64  4796.3  387.73  4804.5  387.97  4810.8  387.84  4825.3  388.00
  4899.5  386.71  4939.7  385.44  4949.7  384.78  4969.7  382.31  4976.7  381.87
  4979.5  381.37  4982.7  381.87  5019.7  382.52  5029.7  383.31  5039.7  384.90
  5059.7  386.69  5069.7  387.28  5097.0  388.21  5109.7  388.04  5129.7  388.13
  5220.1  390.58  5269.7  392.37  5289.1  392.80  5318.0  393.70  5319.8  393.70
#Mann=8,-1,0
  4712.6    0.05       0  4899.5    0.07       0  4976.7    0.07       0
  4982.7    0.07       0  5097.0     0.1       0  5220.1    0.16       0
  5289.1     0.1       0  5318.0    0.16       0
Bank Sta=4976.7,4982.7
Exp/Cntr=0.3,0.1

Type RM Length L Ch R = 1,2091,246,246,246
BEGIN DESCRIPTION:
COPPERAS CREEK TRIBUTARY 5.1 4.0
END DESCRIPTION:
XS GIS Cut Line= 3
      3529116.17     10313077.06      3529596.34     10313702.10
      3530055.85     10313776.62
#Sta/Elev= 30
  4619.0  386.97  4648.5  386.76  4725.7  384.98  4804.4  384.08  4833.4  382.42
  4847.9  382.81  4854.2  383.58  4868.7  383.60  4940.0  382.69  4968.4  382.82
  5003.7  381.94  5123.1  381.80  5125.9  381.30  5129.1  381.80  5234.2  382.94
  5282.0  383.69  5304.7  383.48  5331.8  384.12  5354.5  383.54  5401.3  384.16
  5585.2  387.36  5683.5  389.85  5688.5  389.58  5745.1  390.33  5750.2  390.08
  5777.7  390.66  5806.7  391.80  5811.8  391.63  5847.9  393.02  5872.7  393.69
#Mann=6,-1,0
  4619.0    0.05       0  5123.1   0.033       0  5129.1    0.05       0
  5234.2     0.1       0  5401.3    0.05       0  5847.9     0.1       0
Bank Sta=5123.1,5129.1
Exp/Cntr=0.3,0.1

Type RM Length L Ch R = 1,1845,25,25,25
BEGIN DESCRIPTION:
COPPERAS CREEK TRIBUTARY 5.1 4.03
END DESCRIPTION:
XS GIS Cut Line= 6
      3529215.77     10313233.70      3529149.63     10313491.50
      3529170.46     10313545.15      3529251.71     10313611.81
      3529336.61     10313622.23      3529573.03     10313831.06
#Sta/Elev= 30
  4651.9  383.93  4680.3  383.73  4697.2  382.52  4702.3  383.04  4731.2  383.21
  4754.7  382.80  4782.1  381.93  4792.3  382.21  4802.1  382.10  4807.2  382.62
  4812.6  382.18  4833.5  382.01  4976.6  382.34  5017.6  382.58  5038.6  383.05
  5076.6  382.18  5092.2  381.97  5170.9  382.13  5185.1  382.92  5191.8  384.88
  5199.4  385.15  5213.6  384.72  5220.3  382.89  5227.8  382.48  5231.5  381.89
  5234.2  381.39  5237.5  381.89  5262.9  382.28  5283.9  382.08  5482.7  384.01
#Mann=6,-1,0
  4651.9    0.05       0  5038.6    0.12       0  5076.6     0.1       0
  5231.5   0.033       0  5237.5     0.1       0  5283.9    0.05       0
Bank Sta=5231.5,5237.5
Exp/Cntr=0.3,0.1

Type RM Length L Ch R = 1,1820,62,62,62
BEGIN DESCRIPTION:
COPPERAS CREEK TRIBUTARY 5.1 4.02
END DESCRIPTION:
XS GIS Cut Line= 6
      3529170.42     10313226.13      3529112.79     10313496.92
      3529144.04     10313553.86      3529244.04     10313642.75
      3529346.81     10313659.42      3529545.46     10313843.48
#Sta/Elev= 30
  4621.4  384.37  4708.8  383.23  4728.8  381.84  4749.7  383.53  4790.6  381.65
  4811.1  382.68  4827.9  384.96  4833.0  382.54  4872.4  384.78  4877.5  383.09
  4902.7  382.51  4908.3  384.71  4924.4  383.60  4930.1  384.68  4946.2  383.81
  5006.7  385.34  5073.6  385.46  5081.0  386.29  5099.4  385.63  5104.8  386.34
  5110.1  383.81  5116.0  385.24  5136.6  386.22  5141.9  384.03  5202.7  384.88
  5226.2  380.87  5228.9  380.37  5232.2  380.87  5276.7  381.78  5473.5  383.65
#Mann=6,-1,0
  4621.4    0.05       0  5006.7    0.12       0  5099.4     0.1       0
  5226.2   0.033       0  5232.2     0.1       0  5276.7    0.05       0
Bank Sta=5226.2,5232.2
Exp/Cntr=0.3,0.1

Type RM Length L Ch R = 1,1758,99,99,99
BEGIN DESCRIPTION:
COPPERAS CREEK TRIBUTARY 5.1 4.01
END DESCRIPTION:
XS GIS Cut Line= 4
      3528988.73     10313266.25      3529093.36     10313591.44
      3529260.46     10313743.35      3529470.94     10313900.66
#Sta/Elev= 30
  4610.0  381.70  4615.7  382.19  4626.2  381.14  4639.6  380.67  4783.7  381.02
  4837.4  380.32  4857.3  379.62  4864.2  378.01  4869.5  378.03  4878.3  376.25
  4900.0  374.66  4978.9  372.84  5029.0  372.96  5032.7  372.55  5035.5  372.05
  5038.7  372.55  5043.1  373.12  5064.1  373.07  5092.5  374.85  5099.2  374.56
  5111.0  375.29  5127.6  377.44  5135.0  377.73  5141.8  379.23  5199.7  380.25
  5207.9  380.56  5284.4  380.03  5334.4  380.39  5349.0  381.03  5440.2  382.52
#Mann=7,-1,0
  4610.0    0.05       0  4900.0    0.12       0  5032.7    0.07       0
  5038.7    0.12       0  5111.0    0.05       0  5199.7     0.1       0
  5207.9    0.05       0
Bank Sta=5032.7,5038.7
Exp/Cntr=0.3,0.1

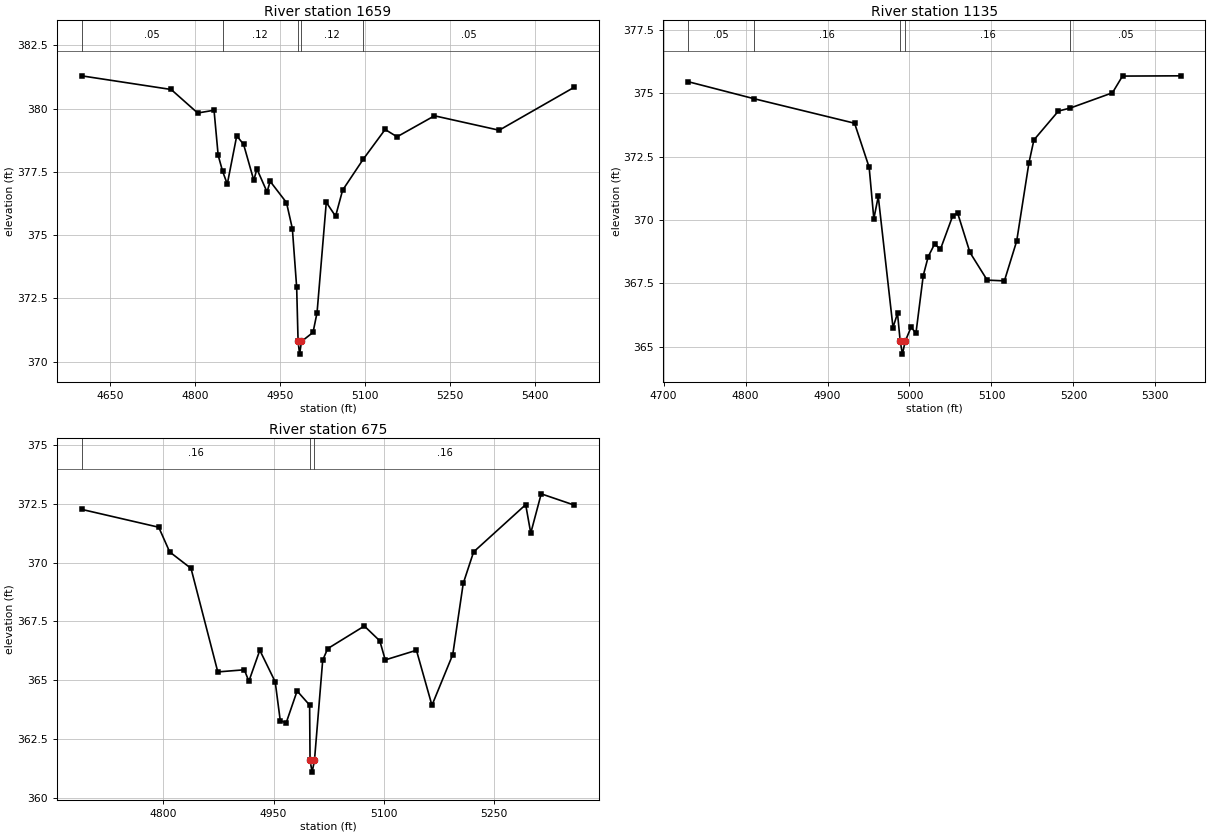
Type RM Length L Ch R = 1,1659,524,524,524
BEGIN DESCRIPTION:
COPPERAS CREEK TRIBUTARY 5.1 3.0
END DESCRIPTION:
XS GIS Cut Line= 3
      3528884.34     10313300.54      3529083.05     10313755.92
      3529393.53     10313962.91
#Sta/Elev= 30
  4598.9  381.30  4757.1  380.76  4803.9  379.83  4832.8  379.94  4840.1  378.16
  4847.9  377.53  4856.2  377.02  4872.9  378.93  4885.0  378.59  4903.0  377.17
  4908.5  377.62  4926.4  376.71  4931.9  377.13  4960.7  376.29  4971.1  375.26
  4978.7  372.94  4981.2  370.80  4983.9  370.30  4987.2  370.80  5007.6  371.16
  5014.7  371.94  5031.0  376.30  5047.4  375.75  5059.8  376.78  5096.1  378.00
  5134.9  379.18  5155.9  378.89  5222.0  379.72  5336.2  379.15  5468.9  380.85
#Mann=5,-1,0
  4598.9    0.05       0  4847.9    0.12       0  4981.2    0.07       0
  4987.2    0.12       0  5096.1    0.05       0
Bank Sta=4981.2,4987.2
Exp/Cntr=0.3,0.1

Type RM Length L Ch R = 1,1135,460,460,460
BEGIN DESCRIPTION:
COPPERAS CREEK TRIBUTARY 5.1 2.0
END DESCRIPTION:
XS GIS Cut Line= 3
      3528536.65     10313548.98      3528642.11     10313791.64
      3528830.56     10314070.55
#Sta/Elev= 30
  4729.8  375.46  4810.0  374.79  4933.0  373.82  4950.8  372.08  4956.5  370.05
  4961.9  370.93  4979.9  365.76  4985.4  366.32  4988.7  365.21  4991.4  364.71
  4994.7  365.21  5001.9  365.77  5007.9  365.54  5016.8  367.81  5022.9  368.56
  5030.6  369.05  5037.8  368.85  5052.8  370.17  5058.8  370.27  5073.8  368.72
  5094.8  367.63  5115.8  367.60  5130.8  369.17  5145.7  372.25  5151.8  373.16
  5181.7  374.30  5196.3  374.42  5247.6  375.02  5259.9  375.68  5331.0  375.69
#Mann=5,-1,0
  4729.8    0.05       0  4810.0    0.16       0  4988.7    0.07       0
  4994.7    0.16       0  5196.3    0.05       0
Bank Sta=4988.7,4994.7
Exp/Cntr=0.3,0.1

Type RM Length L Ch R = 1,675,0,0,0
BEGIN DESCRIPTION:
COPPERAS CREEK TRIBUTARY 5.1 1.0
END DESCRIPTION:
XS GIS Cut Line= 3
      3528118.53     10313789.00      3528292.11     10314041.64
      3528540.77     10314306.47
#Sta/Elev= 30
  4689.0  372.26  4793.9  371.50  4808.8  370.45  4837.8  369.75  4874.2  365.35
  4910.3  365.44  4916.4  364.95  4931.3  366.27  4952.2  364.93  4959.1  363.28
  4967.1  363.18  4982.0  364.54  4999.0  363.94  4999.6  361.59  5002.4  361.09
  5005.6  361.59  5016.8  365.85  5023.6  366.34  5073.4  367.30  5094.4  366.67
  5101.8  365.86  5144.2  366.27  5165.3  363.93  5193.6  366.09  5207.8  369.11
  5221.9  370.45  5292.7  372.46  5299.6  371.25  5313.8  372.92  5358.8  372.44
#Mann=3,-1,0
  4689.0    0.16       0  4999.6    0.07       0  5005.6    0.16       0
Bank Sta=4999.6,5005.6
Exp/Cntr=0.3,0.1

Chan Stop Cuts=-1