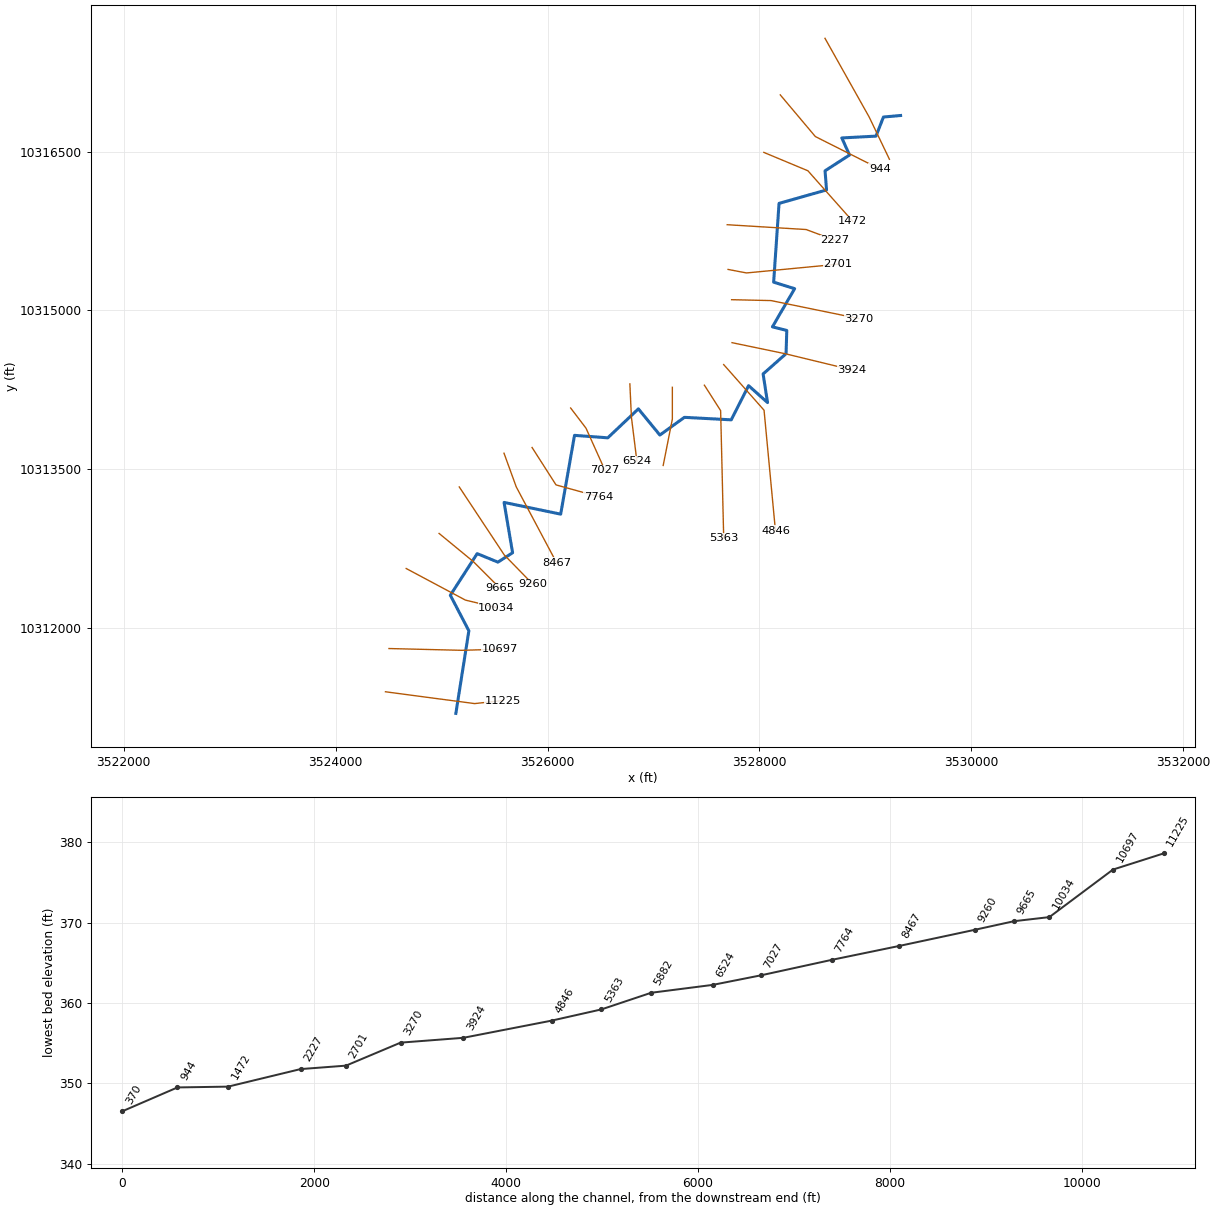
--- COPPERAS CREEK TRIBUTARY 5.prj (project) ---

Proj Title=COPPERAS CREEK TRIBUTARY 5 Base Level Engineering
Current Plan=p01
Default Exp/Contr=0.3,0.1
English Units
Geom File=g01
Flow File=f01
Plan File=p01
BEGIN DESCRIPTION:
COPPERAS CREEK TRIBUTARY 5
END DESCRIPTION:

--- COPPERAS CREEK TRIBUTARY 5.p01 (plan) ---

Plan Title=Multiple Run
Short Identifier=Multiple
Geom File=g01
Flow File=f01
Subcritical Flow
K Sum by GR= 0
Std Step Tol= 0.01
Critical Tol= 0.01
Num of Std Step Trials= 20
Max Error Tol= 0.3
Flow Tol Ratio= 0.001
Split Flow NTrial= 30
Split Flow Tol= 0.02
Split Flow Ratio= 0.02
Log Output Level= 0
Friction Slope Method= 1
Unsteady Friction Slope Method= 2
Unsteady Bridges Friction Slope Method= 1
Parabolic Critical Depth
Global Vel Dist=  1 , 1 , 1
Global Log Level= 0
CheckData=True
Encroach Param= -1, 0, 0, 0
BEGIN DESCRIPTION:
Multiple Run
END DESCRIPTION:

--- COPPERAS CREEK TRIBUTARY 5.f01 (steady flow) ---

Flow Title=Multiple
Number of Profiles=7
Profile Names=10-year,25-year,50-year,1pct_min,100-year,1pct_plu,500-year
River Rch & RM= COPPERAS CREEK T,Reach-1,11225
     672     920    1125    1008    1363    1843    2005
River Rch & RM= COPPERAS CREEK T,Reach-1,10034
     715     976    1191    1063    1438    1945    2104
River Rch & RM= COPPERAS CREEK T,Reach-1,3924
    1015    1411    1741    1571    2124    2872    3173
Boundary for River Rch & Prof#=COPPERAS CREEK T,Reach-1,1
Up Type=0
Dn Type=3
Dn Slope=0.005
Boundary for River Rch & Prof#=COPPERAS CREEK T,Reach-1,2
Up Type=0
Dn Type=3
Dn Slope=0.005
Boundary for River Rch & Prof#=COPPERAS CREEK T,Reach-1,3
Up Type=0
Dn Type=3
Dn Slope=0.005
Boundary for River Rch & Prof#=COPPERAS CREEK T,Reach-1,4
Up Type=0
Dn Type=3
Dn Slope=0.005
Boundary for River Rch & Prof#=COPPERAS CREEK T,Reach-1,5
Up Type=0
Dn Type=3
Dn Slope=0.005
Boundary for River Rch & Prof#=COPPERAS CREEK T,Reach-1,6
Up Type=0
Dn Type=3
Dn Slope=0.005
Boundary for River Rch & Prof#=COPPERAS CREEK T,Reach-1,7
Up Type=0
Dn Type=3
Dn Slope=0.005

--- COPPERAS CREEK TRIBUTARY 5.g01 (geometry) ---

Geom Title=Existing Conditions

River Reach=COPPERAS CREEK T,Reach-1
Reach XY= 30
      3525134.91     10311196.40      3525257.70     10311975.84
      3525082.77     10312311.29      3525335.99     10312704.31
      3525532.04     10312624.01      3525670.35     10312712.50
      3525590.06     10313187.80      3526124.30     10313077.00
      3526254.93     10313820.76      3526569.04     10313797.48
      3526857.77     10314070.69      3527060.53     10313823.57
      3527292.43     10313990.81      3527734.29     10313967.27
      3527898.01     10314289.84      3528077.04     10314130.08
      3528035.21     10314400.29      3528251.84     10314591.75
      3528258.57     10314810.84      3528123.31     10314845.13
      3528332.78     10315205.33      3528134.58     10315266.77
      3528185.53     10316010.36      3528633.77     10316137.22
      3528619.92     10316318.02      3528850.97     10316466.87
      3528778.20     10316628.14      3529100.81     10316645.29
      3529171.05     10316825.75      3529332.90     10316839.92

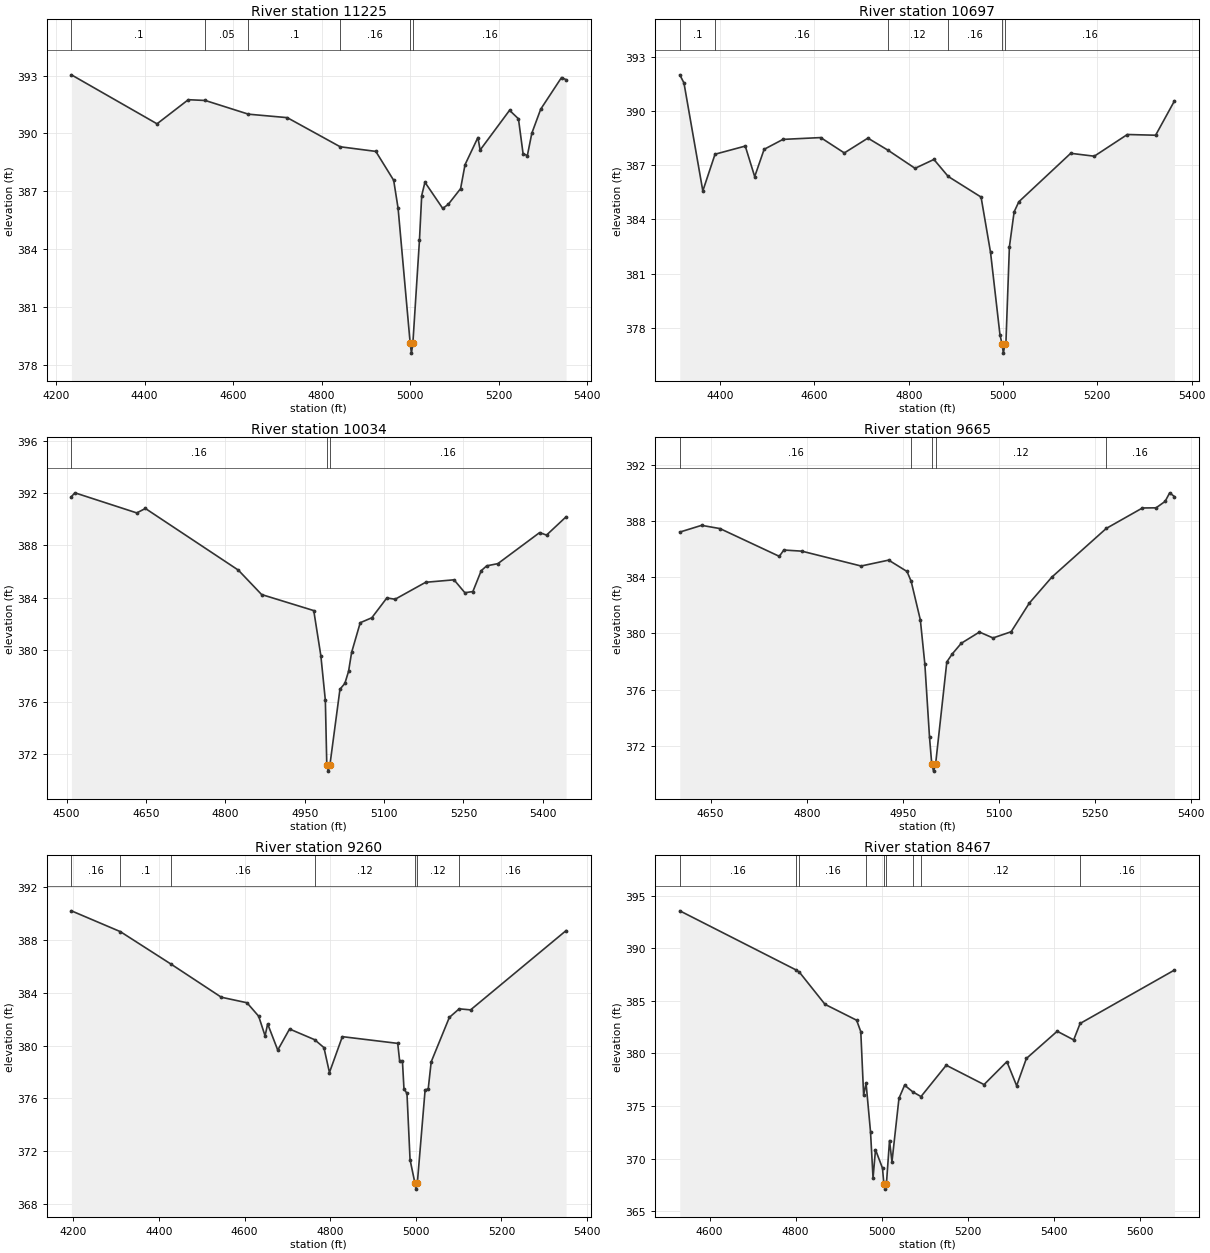
Type RM Length L Ch R = 1,11225,528,528,528
BEGIN DESCRIPTION:
COPPERAS CREEK TRIBUTARY 5 22.0
END DESCRIPTION:
XS GIS Cut Line= 3
      3524470.25     10311400.20      3525311.98     10311288.79
      3525579.06     10311317.55
#Sta/Elev= 30
  4234.7  393.04  4428.2  390.50  4498.8  391.75  4537.2  391.71  4634.6  391.00
  4722.4  390.82  4842.0  389.31  4922.5  389.07  4962.9  387.57  4972.9  386.11
  5000.2  379.11  5003.0  378.61  5006.2  379.11  5021.1  384.45  5026.2  386.78
  5033.5  387.47  5073.8  386.11  5086.4  386.33  5114.1  387.14  5124.1  388.38
  5153.2  389.79  5158.2  389.14  5224.7  391.20  5244.8  390.76  5255.2  388.96
  5264.9  388.85  5275.0  390.01  5295.1  391.26  5342.1  392.90  5352.4  392.79
#Mann=6,-1,0
  4234.7     0.1       0  4537.2    0.05       0  4634.6     0.1       0
  4842.0    0.16       0  5000.2    0.07       0  5006.2    0.16       0
Bank Sta=5000.2,5006.2
Exp/Cntr=0.3,0.1

Type RM Length L Ch R = 1,10697,663,663,663
BEGIN DESCRIPTION:
COPPERAS CREEK TRIBUTARY 5 21.0
END DESCRIPTION:
XS GIS Cut Line= 3
      3524503.35     10311808.48      3525192.11     10311791.64
      3525552.09     10311802.08
#Sta/Elev= 30
  4314.5  391.99  4323.3  391.54  4363.3  385.57  4389.2  387.60  4453.3  388.05
  4473.3  386.36  4493.3  387.87  4533.3  388.42  4613.3  388.52  4663.4  387.67
  4713.4  388.49  4756.1  387.82  4813.4  386.82  4853.4  387.31  4883.7  386.37
  4953.4  385.23  4973.5  382.17  4993.5  377.61  4998.0  377.10  5000.7  376.60
  5004.0  377.10  5006.0  377.10  5013.5  382.48  5023.5  384.41  5033.5  384.97
  5143.5  387.65  5193.5  387.49  5263.6  388.69  5323.6  388.65  5363.6  390.55
#Mann=6,-1,0
  4314.5     0.1       0  4389.2    0.16       0  4756.1    0.12       0
  4883.7    0.16       0  4998.0    0.07       0  5004.0    0.16       0
Bank Sta=4998,5004
Exp/Cntr=0.3,0.1

Type RM Length L Ch R = 1,10034,369,369,369
BEGIN DESCRIPTION:
COPPERAS CREEK TRIBUTARY 5 20.0
END DESCRIPTION:
XS GIS Cut Line= 3
      3524666.22     10312563.75      3525225.06     10312265.71
      3525518.02     10312195.56
#Sta/Elev= 30
  4509.2  391.74  4515.9  392.03  4632.7  390.49  4649.0  390.83  4824.7  386.10
  4868.6  384.23  4967.1  383.00  4980.5  379.54  4989.0  376.12  4991.7  371.19
  4994.4  370.69  4997.7  371.19  5016.6  376.97  5025.9  377.42  5032.9  378.35
  5038.6  379.79  5054.9  382.07  5076.8  382.45  5105.2  383.97  5120.8  383.87
  5178.5  385.17  5232.1  385.36  5252.6  384.37  5267.7  384.46  5283.5  386.06
  5293.8  386.43  5314.9  386.60  5393.8  388.98  5406.9  388.79  5443.8  390.19
#Mann=3,-1,0
  4509.2    0.16       0  4991.7    0.07       0  4997.7    0.16       0
Bank Sta=4991.7,4997.7
Exp/Cntr=0.3,0.1

Type RM Length L Ch R = 1,9665,405,405,405
BEGIN DESCRIPTION:
COPPERAS CREEK TRIBUTARY 5 19.0
END DESCRIPTION:
XS GIS Cut Line= 3
      3524976.72     10312894.87      3525300.06     10312628.90
      3525550.04     10312378.92
#Sta/Elev= 30
  4601.9  387.23  4635.9  387.71  4664.6  387.48  4757.2  385.50  4764.3  385.95
  4792.3  385.87  4884.9  384.81  4927.9  385.23  4956.6  384.42  4963.1  383.71
  4977.4  380.96  4984.4  377.82  4991.7  372.59  4995.2  370.68  4998.0  370.18
  5001.2  370.68  5018.7  377.97  5027.2  378.54  5041.3  379.30  5069.6  380.10
  5090.8  379.68  5119.1  380.12  5147.4  382.16  5182.7  384.02  5267.6  387.49
  5324.1  388.95  5345.4  388.96  5359.5  389.42  5366.6  390.03  5374.1  389.76
#Mann=5,-1,0
  4601.9    0.16       0  4963.1    0.12       0  4995.2    0.07       0
  5001.2    0.12       0  5267.6    0.16       0
Bank Sta=4995.2,5001.2
Exp/Cntr=0.3,0.1

Type RM Length L Ch R = 1,9260,793,793,793
BEGIN DESCRIPTION:
COPPERAS CREEK TRIBUTARY 5 18.0
END DESCRIPTION:
XS GIS Cut Line= 3
      3525167.12     10313333.66      3525592.11     10312691.64
      3525861.63     10312415.65
#Sta/Elev= 30
  4195.4  390.22  4309.9  388.64  4429.1  386.16  4545.6  383.67  4605.6  383.25
  4632.9  382.23  4647.9  380.74  4653.9  381.65  4677.5  379.66  4705.1  381.26
  4763.7  380.45  4785.4  379.85  4798.3  377.96  4828.4  380.68  4957.8  380.17
  4962.3  378.83  4968.8  378.83  4972.4  376.71  4979.4  376.38  4986.6  371.35
  4997.7  369.62  5000.4  369.12  5003.7  369.62  5021.8  376.65  5029.0  376.71
  5036.0  378.77  5078.4  382.14  5101.4  382.79  5128.0  382.71  5351.1  388.72
#Mann=7,-1,0
  4195.4    0.16       0  4309.9     0.1       0  4429.1    0.16       0
  4763.7    0.12       0  4997.7    0.07       0  5003.7    0.12       0
  5101.4    0.16       0
Bank Sta=4997.7,5003.7
Exp/Cntr=0.3,0.1

Type RM Length L Ch R = 1,8467,703,703,703
BEGIN DESCRIPTION:
COPPERAS CREEK TRIBUTARY 5 17.0
END DESCRIPTION:
XS GIS Cut Line= 3
      3525589.33     10313652.42      3525705.23     10313333.69
      3526086.05     10312617.60
#Sta/Elev= 30
  4530.7  393.56  4800.5  387.95  4808.9  387.72  4868.3  384.67  4941.8  383.16
  4951.5  382.07  4958.1  376.05  4963.8  377.16  4974.1  372.56  4980.0  368.15
  4985.7  370.85  5002.0  369.09  5005.1  367.60  5007.8  367.10  5011.1  367.60
  5018.3  371.72  5024.0  369.70  5040.3  375.74  5053.4  376.98  5072.7  376.34
  5091.5  375.90  5150.2  378.88  5238.1  377.04  5291.2  379.22  5313.9  376.93
  5336.5  379.52  5408.2  382.11  5446.5  381.29  5461.5  382.85  5680.9  387.93
#Mann=9,-1,0
  4530.7    0.16       0  4800.5     0.1       0  4808.9    0.16       0
  4963.8    0.12       0  5005.1    0.07       0  5011.1    0.12       0
  5072.7     0.1       0  5091.5    0.12       0  5461.5    0.16       0
Bank Sta=5005.1,5011.1
Exp/Cntr=0.3,0.1

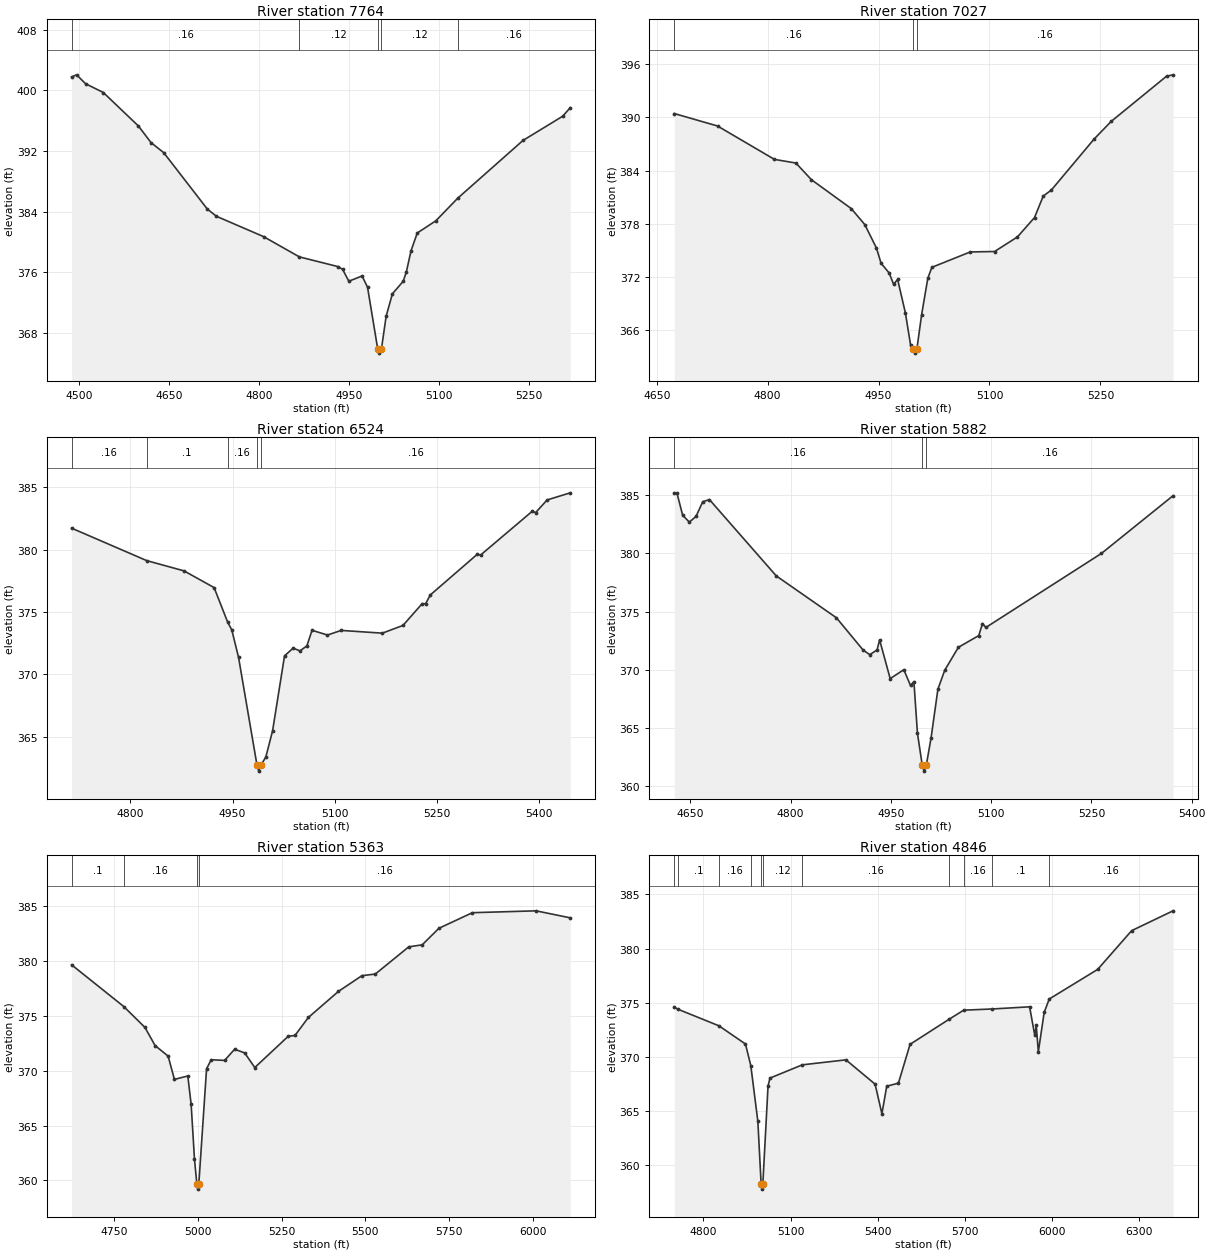
Type RM Length L Ch R = 1,7764,737,737,737
BEGIN DESCRIPTION:
COPPERAS CREEK TRIBUTARY 5 15.0
END DESCRIPTION:
XS GIS Cut Line= 3
      3525854.27     10313706.22      3526080.34     10313353.08
      3526478.18     10313242.94
#Sta/Elev= 30
  4487.3  401.78  4495.6  402.06  4510.8  400.88  4540.2  399.73  4598.7  395.32
  4619.9  393.12  4641.0  391.80  4713.8  384.36  4729.0  383.41  4807.6  380.73
  4867.3  378.06  4932.6  376.76  4939.6  376.40  4949.9  374.85  4972.0  375.54
  4981.1  374.06  4998.2  365.87  5000.9  365.37  5004.2  365.87  5012.2  370.25
  5022.6  373.19  5040.6  374.84  5045.8  376.05  5053.7  378.87  5064.1  381.21
  5095.2  382.82  5131.4  385.78  5240.5  393.41  5306.7  396.60  5319.4  397.73
#Mann=5,-1,0
  4487.3    0.16       0  4867.3    0.12       0  4998.2    0.07       0
  5004.2    0.12       0  5131.4    0.16       0
Bank Sta=4998.2,5004.2
Exp/Cntr=0.3,0.1

Type RM Length L Ch R = 1,7027,503,503,503
BEGIN DESCRIPTION:
COPPERAS CREEK TRIBUTARY 5 13.0
END DESCRIPTION:
XS GIS Cut Line= 3
      3526218.52     10314078.81      3526363.41     10313888.38
      3526542.10     10313491.65
#Sta/Elev= 30
  4673.8  390.42  4732.2  389.02  4809.2  385.26  4838.2  384.85  4859.1  382.98
  4913.1  379.72  4931.4  377.92  4947.2  375.27  4953.4  373.56  4964.3  372.48
  4970.3  371.21  4975.8  371.74  4986.3  367.97  4993.4  364.32  4995.9  363.95
  4998.7  363.45  5001.9  363.95  5008.2  367.76  5016.6  371.88  5022.1  373.11
  5074.0  374.84  5106.9  374.89  5137.8  376.53  5160.9  378.71  5172.7  381.13
  5183.7  381.81  5241.3  387.53  5264.5  389.53  5339.4  394.62  5348.2  394.78
#Mann=3,-1,0
  4673.8    0.16       0  4995.9    0.07       0  5001.9    0.16       0
Bank Sta=4995.9,5001.9
Exp/Cntr=0.3,0.1

Type RM Length L Ch R = 1,6524,642,642,642
BEGIN DESCRIPTION:
COPPERAS CREEK TRIBUTARY 5 12.0
END DESCRIPTION:
XS GIS Cut Line= 3
      3526777.36     10314306.44      3526792.11     10313991.64
      3526843.60     10313577.88
#Sta/Elev= 30
  4713.7  381.72  4824.0  379.12  4878.7  378.30  4922.9  376.96  4942.9  374.18
  4948.8  373.58  4958.8  371.37  4985.8  362.76  4988.5  362.26  4991.8  362.76
  4998.8  363.38  5008.8  365.50  5026.3  371.49  5038.9  372.11  5049.0  371.89
  5059.1  372.29  5066.7  373.54  5089.3  373.16  5109.5  373.53  5169.9  373.31
  5200.2  373.93  5228.3  375.67  5233.4  375.67  5240.5  376.38  5309.1  379.62
  5314.2  379.57  5389.9  383.07  5395.0  382.97  5411.8  383.98  5445.8  384.55
#Mann=5,-1,0
  4713.7    0.16       0  4824.0     0.1       0  4942.9    0.16       0
  4985.8    0.07       0  4991.8    0.16       0
Bank Sta=4985.8,4991.8
Exp/Cntr=0.3,0.1

Type RM Length L Ch R = 1,5882,519,519,519
BEGIN DESCRIPTION:
COPPERAS CREEK TRIBUTARY 5 11.0
END DESCRIPTION:
XS GIS Cut Line= 3
      3527178.38     10314274.14      3527178.38     10313974.11
      3527091.97     10313536.60
#Sta/Elev= 30
  4626.1  385.20  4629.9  385.20  4638.6  383.27  4648.6  382.68  4658.6  383.18
  4668.6  384.43  4678.6  384.62  4778.6  378.06  4868.6  374.46  4908.6  371.68
  4918.6  371.29  4929.4  371.70  4933.2  372.56  4949.0  369.23  4969.4  370.00
  4979.4  368.64  4984.5  368.97  4989.8  364.53  4997.0  361.78  4999.8  361.28
  5003.0  361.78  5010.2  364.14  5020.4  368.32  5030.6  369.95  5051.0  371.92
  5081.5  372.93  5087.1  373.96  5092.2  373.63  5265.0  379.99  5372.1  384.95
#Mann=3,-1,0
  4626.1    0.16       0  4997.0    0.07       0  5003.0    0.16       0
Bank Sta=4997,5003
Exp/Cntr=0.3,0.1

Type RM Length L Ch R = 1,5363,517,517,517
BEGIN DESCRIPTION:
COPPERAS CREEK TRIBUTARY 5 9.1
END DESCRIPTION:
XS GIS Cut Line= 3
      3527481.08     10314294.03      3527634.23     10314053.96
      3527663.21     10312849.37
#Sta/Elev= 30
  4622.7  379.65  4778.5  375.85  4841.7  373.95  4872.2  372.29  4911.1  371.33
  4929.8  369.21  4969.8  369.52  4979.8  366.94  4989.8  361.94  4996.8  359.71
  4999.6  359.21  5002.8  359.71  5025.9  370.18  5039.8  371.00  5079.8  370.94
  5109.8  371.96  5139.8  371.62  5169.9  370.29  5269.9  373.14  5289.9  373.21
  5329.9  374.85  5419.9  377.23  5489.9  378.66  5530.0  378.81  5630.0  381.29
  5670.0  381.47  5720.0  382.98  5820.0  384.40  6010.1  384.57  6112.4  383.93
#Mann=4,-1,0
  4622.7     0.1       0  4778.5    0.16       0  4996.8    0.07       0
  5002.8    0.16       0
Bank Sta=4996.8,5002.8
Exp/Cntr=0.3,0.1

Type RM Length L Ch R = 1,4846,922,922,922
BEGIN DESCRIPTION:
COPPERAS CREEK TRIBUTARY 5 9.0
END DESCRIPTION:
XS GIS Cut Line= 3
      3527663.23     10314488.57      3528044.04     10314058.10
      3528151.67     10312919.71
#Sta/Elev= 30
  4699.5  374.59  4711.7  374.41  4853.1  372.88  4944.6  371.20  4963.0  369.21
  4987.3  364.07  4998.5  358.32  5001.3  357.82  5004.5  358.32  5022.4  367.34
  5029.2  368.06  5140.5  369.28  5290.8  369.74  5391.2  367.50  5414.7  364.77
  5431.4  367.31  5471.6  367.59  5511.7  371.17  5646.1  373.48  5696.5  374.32
  5794.7  374.43  5923.6  374.63  5941.5  371.99  5946.5  372.92  5953.7  370.48
  5973.8  374.11  5991.3  375.35  6158.2  378.08  6275.1  381.65  6417.7  383.48
#Mann=11,-1,0
  4699.5    0.05       0  4711.7     0.1       0  4853.1    0.16       0
  4963.0    0.12       0  4998.5    0.07       0  5004.5    0.12       0
  5140.5    0.16       0  5646.1     0.1       0  5696.5    0.16       0
  5794.7     0.1       0  5991.3    0.16       0
Bank Sta=4998.5,5004.5
Exp/Cntr=0.3,0.1

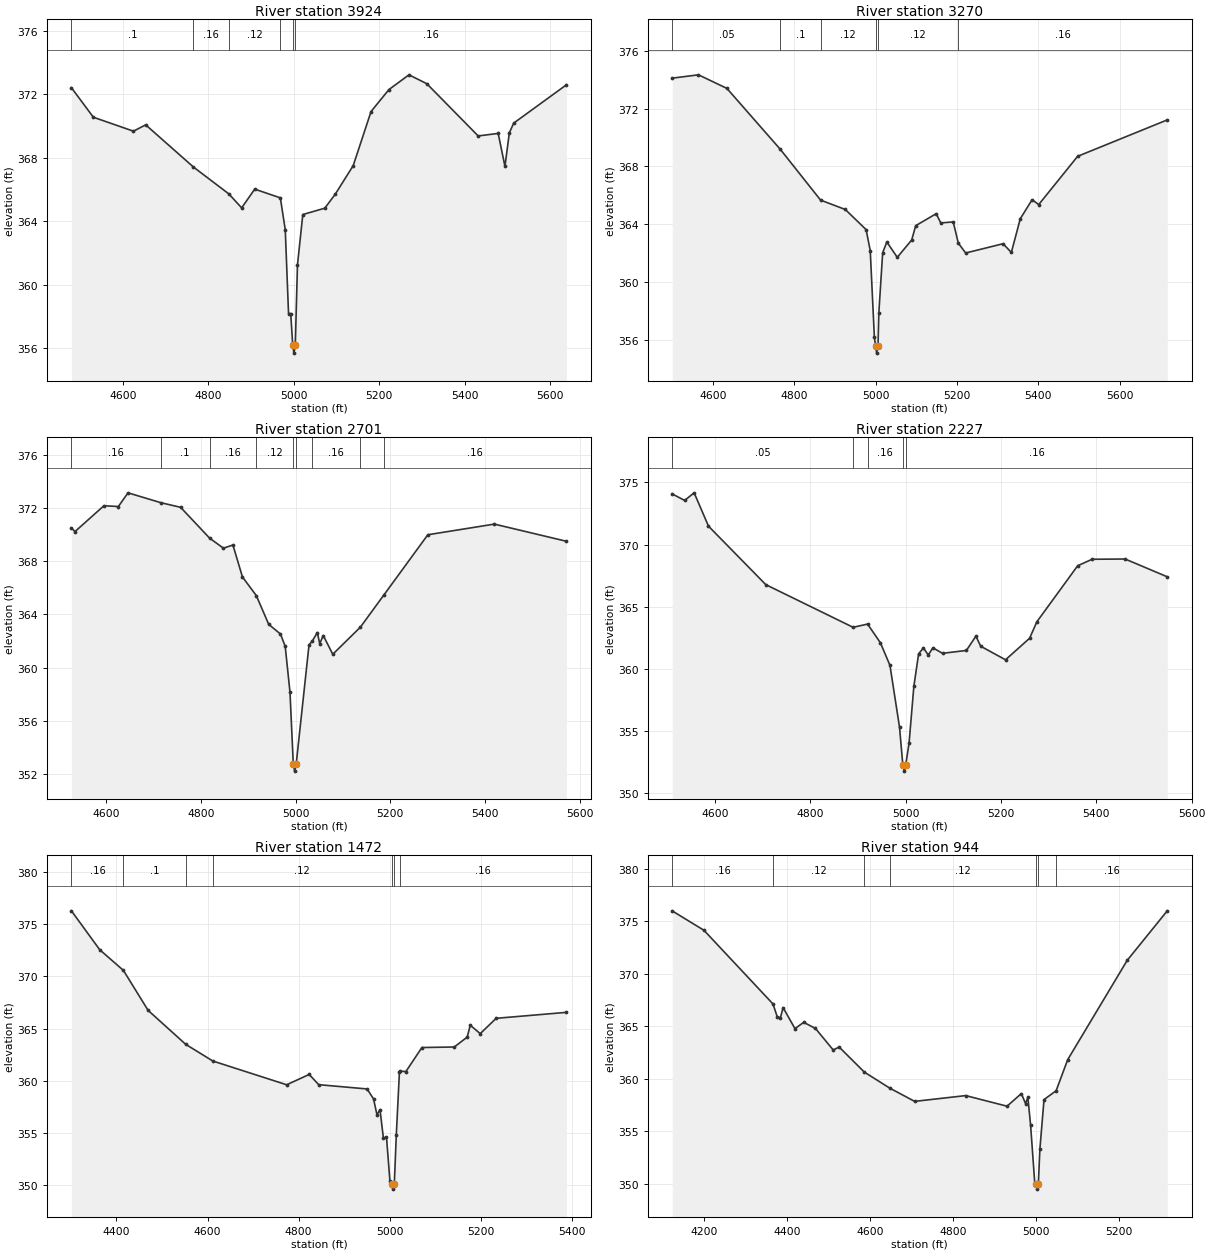
Type RM Length L Ch R = 1,3924,654,654,654
BEGIN DESCRIPTION:
COPPERAS CREEK TRIBUTARY 5 8.0
END DESCRIPTION:
XS GIS Cut Line= 3
      3527741.84     10314695.58      3528242.11     10314591.64
      3528871.91     10314438.94
#Sta/Elev= 30
  4479.2  372.40  4530.5  370.54  4624.5  369.66  4653.1  370.06  4765.0  367.40
  4847.8  365.71  4877.8  364.83  4908.4  366.01  4968.4  365.46  4979.9  363.46
  4987.6  358.17  4992.7  358.17  4997.4  356.18  5000.2  355.68  5003.4  356.18
  5008.5  361.24  5021.0  364.41  5072.5  364.81  5097.2  365.70  5139.0  367.49
  5180.8  370.90  5222.6  372.28  5269.6  373.21  5311.4  372.65  5431.6  369.36
  5478.5  369.52  5494.3  367.44  5504.6  369.56  5514.9  370.17  5638.2  372.58
#Mann=6,-1,0
  4479.2     0.1       0  4765.0    0.16       0  4847.8    0.12       0
  4968.4    0.16       0  4997.4    0.07       0  5003.4    0.16       0
Bank Sta=4997.4,5003.4
Exp/Cntr=0.3,0.1

Type RM Length L Ch R = 1,3270,569,569,569
BEGIN DESCRIPTION:
COPPERAS CREEK TRIBUTARY 5 7.0
END DESCRIPTION:
XS GIS Cut Line= 3
      3527737.76     10315101.25      3528110.27     10315092.97
      3528937.66     10314923.35
#Sta/Elev= 30
  4499.8  374.11  4564.2  374.34  4634.2  373.40  4765.6  369.18  4864.5  365.67
  4925.3  365.02  4976.4  363.63  4986.6  362.18  4996.8  356.18  4999.7  355.58
  5002.4  355.08  5005.7  355.58  5007.8  357.89  5017.2  362.03  5027.4  362.77
  5053.1  361.71  5088.6  362.91  5098.4  363.90  5148.8  364.73  5160.1  364.09
  5190.7  364.16  5203.2  362.69  5221.3  362.01  5313.2  362.65  5333.6  362.05
  5355.6  364.38  5384.7  365.70  5400.9  365.36  5496.6  368.70  5717.0  371.22
#Mann=6,-1,0
  4499.8    0.05       0  4765.6     0.1       0  4864.5    0.12       0
  4999.7    0.07       0  5005.7    0.12       0  5203.2    0.16       0
Bank Sta=4999.7,5005.7
Exp/Cntr=0.3,0.1

Type RM Length L Ch R = 1,2701,474,474,474
BEGIN DESCRIPTION:
COPPERAS CREEK TRIBUTARY 5 6.0
END DESCRIPTION:
XS GIS Cut Line= 3
      3527704.65     10315386.86      3527878.46     10315353.75
      3528743.57     10315436.54
#Sta/Elev= 30
  4526.2  370.49  4533.8  370.22  4594.9  372.16  4625.4  372.10  4645.8  373.13
  4715.1  372.39  4757.0  372.04  4818.1  369.73  4847.4  368.97  4867.5  369.21
  4887.6  366.81  4916.9  365.41  4943.1  363.25  4968.0  362.52  4978.0  361.59
  4988.1  358.14  4995.1  352.72  4997.9  352.22  5001.1  352.72  5028.3  361.70
  5035.3  362.00  5045.9  362.63  5050.9  361.80  5058.4  362.41  5078.5  361.00
  5136.9  363.04  5186.8  365.47  5279.4  369.98  5420.0  370.78  5572.2  369.49
#Mann=9,-1,0
  4526.2    0.16       0  4715.1     0.1       0  4818.1    0.16       0
  4916.9    0.12       0  4995.1    0.07       0  5001.1    0.12       0
  5035.3    0.16       0  5136.9    0.12       0  5186.8    0.16       0
Bank Sta=4995.1,5001.1
Exp/Cntr=0.3,0.1

Type RM Length L Ch R = 1,2227,755,755,755
BEGIN DESCRIPTION:
COPPERAS CREEK TRIBUTARY 5 5.0
END DESCRIPTION:
XS GIS Cut Line= 3
      3527696.29     10315809.10      3528441.43     10315763.56
      3528714.95     10315661.70
#Sta/Elev= 30
  4510.4  374.07  4536.3  373.55  4556.3  374.16  4586.4  371.48  4706.6  366.78
  4889.8  363.35  4920.1  363.61  4947.0  362.11  4967.1  360.29  4987.1  355.33
  4994.1  352.29  4996.9  351.79  5000.1  352.29  5007.1  354.02  5017.2  358.60
  5027.2  361.22  5037.2  361.69  5047.4  361.13  5057.2  361.70  5077.3  361.26
  5127.4  361.49  5147.4  362.64  5157.4  361.83  5209.5  360.74  5260.0  362.47
  5275.2  363.79  5360.9  368.30  5391.2  368.82  5460.4  368.84  5548.8  367.41
#Mann=5,-1,0
  4510.4    0.05       0  4889.8    0.12       0  4920.1    0.16       0
  4994.1    0.07       0  5000.1    0.16       0
Bank Sta=4994.1,5000.1
Exp/Cntr=0.3,0.1

Type RM Length L Ch R = 1,1472,528,528,528
BEGIN DESCRIPTION:
COPPERAS CREEK TRIBUTARY 5 3.0
END DESCRIPTION:
XS GIS Cut Line= 3
      3528042.13     10316491.63      3528457.99     10316318.25
      3528880.24     10315842.18
#Sta/Elev= 30
  4301.1  376.28  4363.3  372.55  4415.3  370.57  4469.5  366.74  4552.0  363.49
  4611.4  361.89  4773.8  359.61  4823.2  360.60  4844.1  359.62  4950.3  359.21
  4964.5  358.26  4972.0  356.74  4978.7  357.23  4986.2  354.48  4992.9  354.63
  5000.5  350.37  5004.1  350.11  5006.9  349.61  5010.1  350.11  5014.5  354.81
  5021.4  360.87  5022.2  360.91  5035.6  360.88  5070.7  363.18  5141.8  363.23
  5170.2  364.18  5176.9  365.32  5198.7  364.51  5233.8  365.98  5388.0  366.55
#Mann=7,-1,0
  4301.1    0.16       0  4415.3     0.1       0  4552.0    0.16       0
  4611.4    0.12       0  5004.1    0.07       0  5010.1    0.12       0
  5022.2    0.16       0
Bank Sta=5004.1,5010.1
Exp/Cntr=0.3,0.1

Type RM Length L Ch R = 1,944,574,574,574
BEGIN DESCRIPTION:
COPPERAS CREEK TRIBUTARY 5 2.0
END DESCRIPTION:
XS GIS Cut Line= 3
      3528197.17     10317034.42      3528528.36     10316641.13
      3529136.85     10316334.82
#Sta/Elev= 30
  4122.2  375.98  4198.7  374.14  4365.4  367.13  4375.6  365.92  4383.4  365.82
  4389.9  366.78  4418.5  364.78  4439.6  365.38  4468.0  364.80  4510.9  362.75
  4525.2  363.03  4586.2  360.64  4647.9  359.11  4707.6  357.86  4830.9  358.41
  4930.7  357.40  4965.2  358.60  4975.4  357.65  4981.0  358.24  4987.6  355.59
  4997.7  350.04  5000.3  350.01  5003.0  349.51  5006.3  350.01  5010.0  353.33
  5020.0  358.03  5049.2  358.87  5077.2  361.83  5220.9  371.28  5317.6  375.99
#Mann=7,-1,0
  4122.2    0.16       0  4365.4    0.12       0  4586.2     0.1       0
  4647.9    0.12       0  5000.3    0.07       0  5006.3    0.12       0
  5049.2    0.16       0
Bank Sta=5000.3,5006.3
Exp/Cntr=0.3,0.1

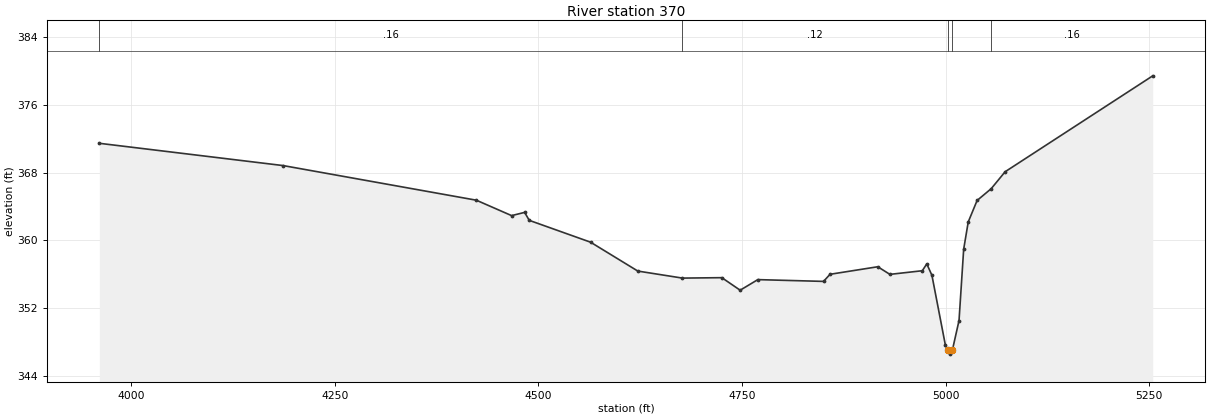
Type RM Length L Ch R = 1,370,0,0,0
BEGIN DESCRIPTION:
COPPERAS CREEK TRIBUTARY 5 1.0
END DESCRIPTION:
XS GIS Cut Line= 3
      3528619.43     10317568.36      3529037.51     10316823.27
      3529227.35     10316427.08
#Sta/Elev= 30
  3960.8  371.45  4186.5  368.82  4423.8  364.73  4467.1  362.91  4483.1  363.29
  4488.8  362.35  4564.1  359.77  4622.1  356.36  4676.9  355.53  4725.3  355.58
  4747.8  354.10  4769.5  355.35  4850.2  355.14  4858.2  355.98  4916.8  356.87
  4931.7  355.97  4971.5  356.40  4977.0  357.21  4983.3  355.86  4999.7  347.68
  5002.5  347.05  5005.2  346.55  5008.5  347.05  5016.6  350.52  5022.3  358.94
  5027.9  362.16  5038.8  364.70  5056.1  366.09  5073.2  368.09  5254.5  379.42
#Mann=5,-1,0
  3960.8    0.16       0  4676.9    0.12       0  5002.5    0.07       0
  5008.5    0.12       0  5056.1    0.16       0
Bank Sta=5002.5,5008.5
Exp/Cntr=0.3,0.1

Chan Stop Cuts=-1