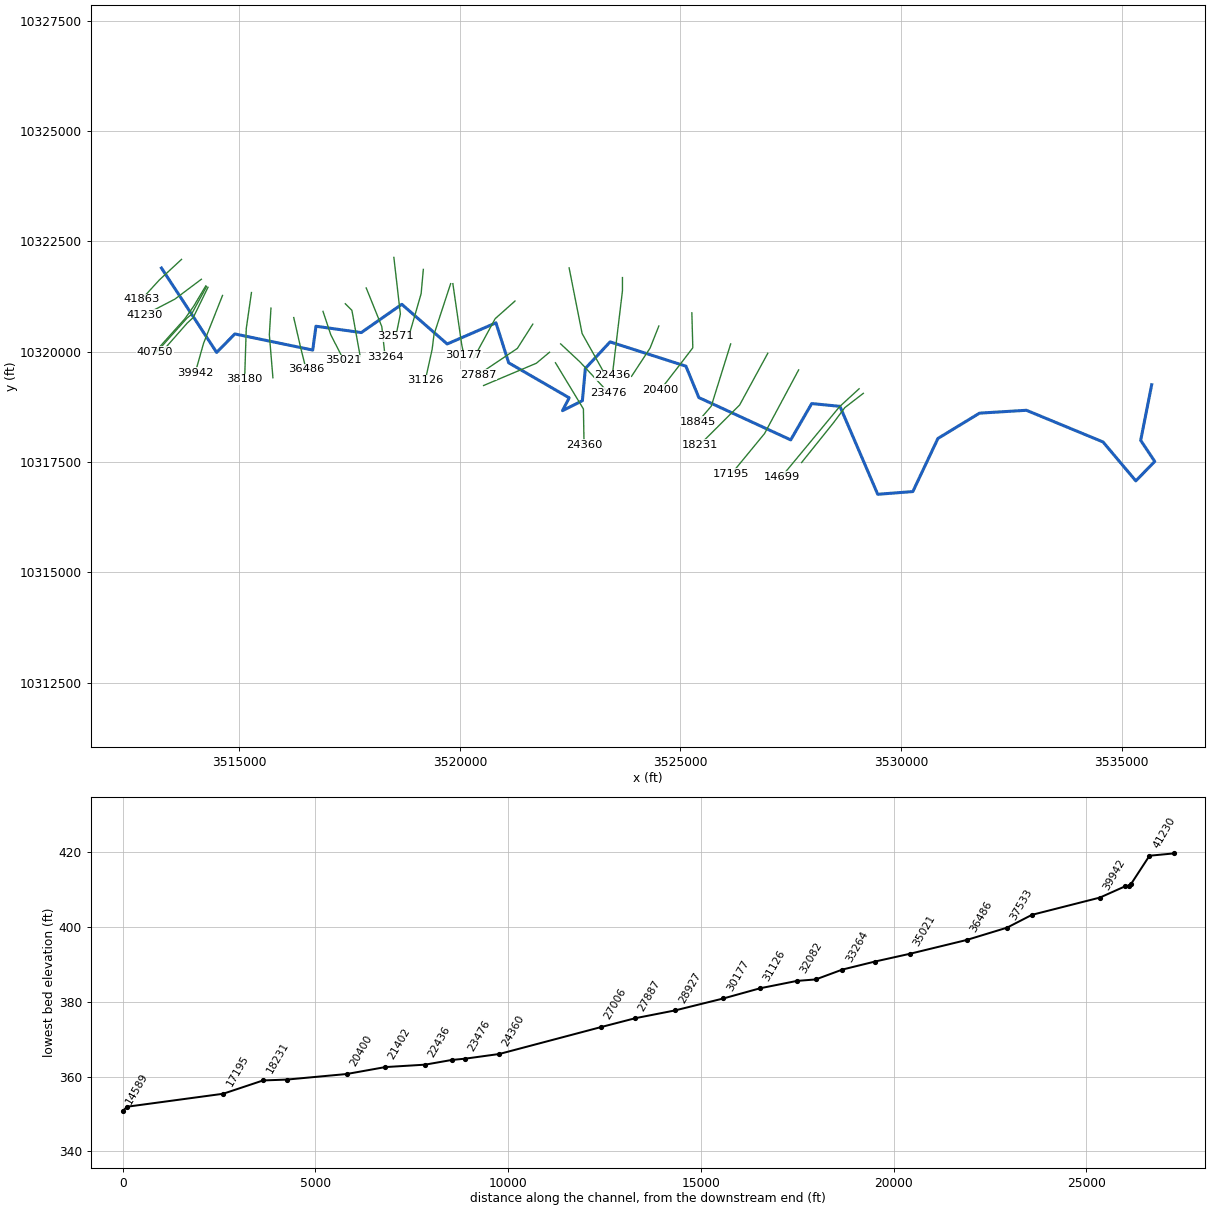
--- COPPERAS CREEK.prj (project) ---

Proj Title=COPPERAS CREEK Base Level Engineering
Current Plan=p01
Default Exp/Contr=0.3,0.1
English Units
Geom File=g01
Flow File=f01
Plan File=p01
Y Axis Title=Elevation
X Axis Title(PF)=Main Channel Distance
X Axis Title(XS)=Station
BEGIN DESCRIPTION:
COPPERAS CREEK
END DESCRIPTION:
DSS Export Rating Curves= 0
DSS Export Rating Curve Sorted= 0
DSS Export Volume Flow Curves= 0
DXF OffsetX= 0
DXF OffsetY= 0
DXF ScaleX= 1
DXF ScaleY= 10

--- COPPERAS CREEK.p01 (plan) ---

Plan Title=Multiple Run
Short Identifier=Multiple
Geom File=g01
Flow File=f01
Subcritical Flow
K Sum by GR= 0
Std Step Tol= 0.01
Critical Tol= 0.01
Num of Std Step Trials= 20
Max Error Tol= 0.3
Flow Tol Ratio= 0.001
Split Flow NTrial= 30
Split Flow Tol= 0.02
Split Flow Ratio= 0.02
Log Output Level= 0
Friction Slope Method= 1
Unsteady Friction Slope Method= 2
Unsteady Bridges Friction Slope Method= 1
Parabolic Critical Depth
Global Vel Dist=  1 , 1 , 1
Global Log Level= 0
CheckData=True
Encroach Param= -1, 0, 0, 0
BEGIN DESCRIPTION:
Multiple Run
END DESCRIPTION:

--- COPPERAS CREEK.f01 (steady flow) ---

Flow Title=Multiple
Program Version=4.10
Number of Profiles= 7
Profile Names=10-year,25-year,50-year,1pct_min,100-year,1pct_plu,500-year
River Rch & RM=COPPERAS CREEK,Reach-1         ,41863
     670     927    1142    1032    1395    1887    2089
River Rch & RM=COPPERAS CREEK,Reach-1         ,38180
     891    1238    1529    1381    1868    2526    2799
River Rch & RM=COPPERAS CREEK,Reach-1         ,24360
    1640    2336    2931    2685    3632    4912    5598
River Rch & RM=COPPERAS CREEK,Reach-1         ,14699
    1739    2480    3115    2855    3861    5221    5956
River Rch & RM=COPPERAS CREEK,Reach-1         ,12051
    2365    3402    4297    3958    5352    7238    8335
River Rch & RM=COPPERAS CREEK,Reach-1         ,1559
    2404    3456    4363    4015    5429    7342    8442
Boundary for River Rch & Prof#=COPPERAS CREEK,Reach-1         , 1
Up Type= 0
Dn Type= 3
Dn Slope=0.00149
Boundary for River Rch & Prof#=COPPERAS CREEK,Reach-1         , 2
Up Type= 0
Dn Type= 3
Dn Slope=0.00149
Boundary for River Rch & Prof#=COPPERAS CREEK,Reach-1         , 3
Up Type= 0
Dn Type= 3
Dn Slope=0.00149
Boundary for River Rch & Prof#=COPPERAS CREEK,Reach-1         , 4
Up Type= 0
Dn Type= 3
Dn Slope=0.00149
Boundary for River Rch & Prof#=COPPERAS CREEK,Reach-1         , 5
Up Type= 0
Dn Type= 3
Dn Slope=0.00149
Boundary for River Rch & Prof#=COPPERAS CREEK,Reach-1         , 6
Up Type= 0
Dn Type= 3
Dn Slope=0.00149
Boundary for River Rch & Prof#=COPPERAS CREEK,Reach-1         , 7
Up Type= 0
Dn Type= 3
Dn Slope=0.00149
DSS Import GetInterval= 0
DSS Import GetPeak= 0
DSS Import FillOption= 0

--- COPPERAS CREEK.g01 (geometry) ---

Geom Title=Existing Conditions
Program Version=4.10

River Reach=COPPERAS CREEK  ,Reach-1
Reach XY= 30
       3513237.2      10321895.9      3514487.81     10319982.88
      3514900.35     10320401.97      3516665.93     10320036.61
      3516739.57     10320576.28      3517766.41     10320432.97
      3518685.17     10321073.51      3519713.62      10320174.5
      3520819.16     10320653.77      3521107.24      10319747.9
      3522478.72     10318954.02      3522327.87      10318663.1
      3522777.92     10318888.71      3522845.39     10319620.08
      3523406.01     10320221.76      3525124.66     10319671.47
      3525417.63     10318959.66      3527500.23     10318000.42
       3527975.7       10318824.       3528615.5     10318761.03
      3529472.16     10316767.48      3530268.18     10316829.42
       3530836.9      10318033.4      3531779.86      10318606.7
      3532842.43     10318671.74      3534578.44     10317953.83
      3535322.11     10317071.64      3535751.56     10317511.71
      3535432.28     10317990.02      3535682.11     10319251.64

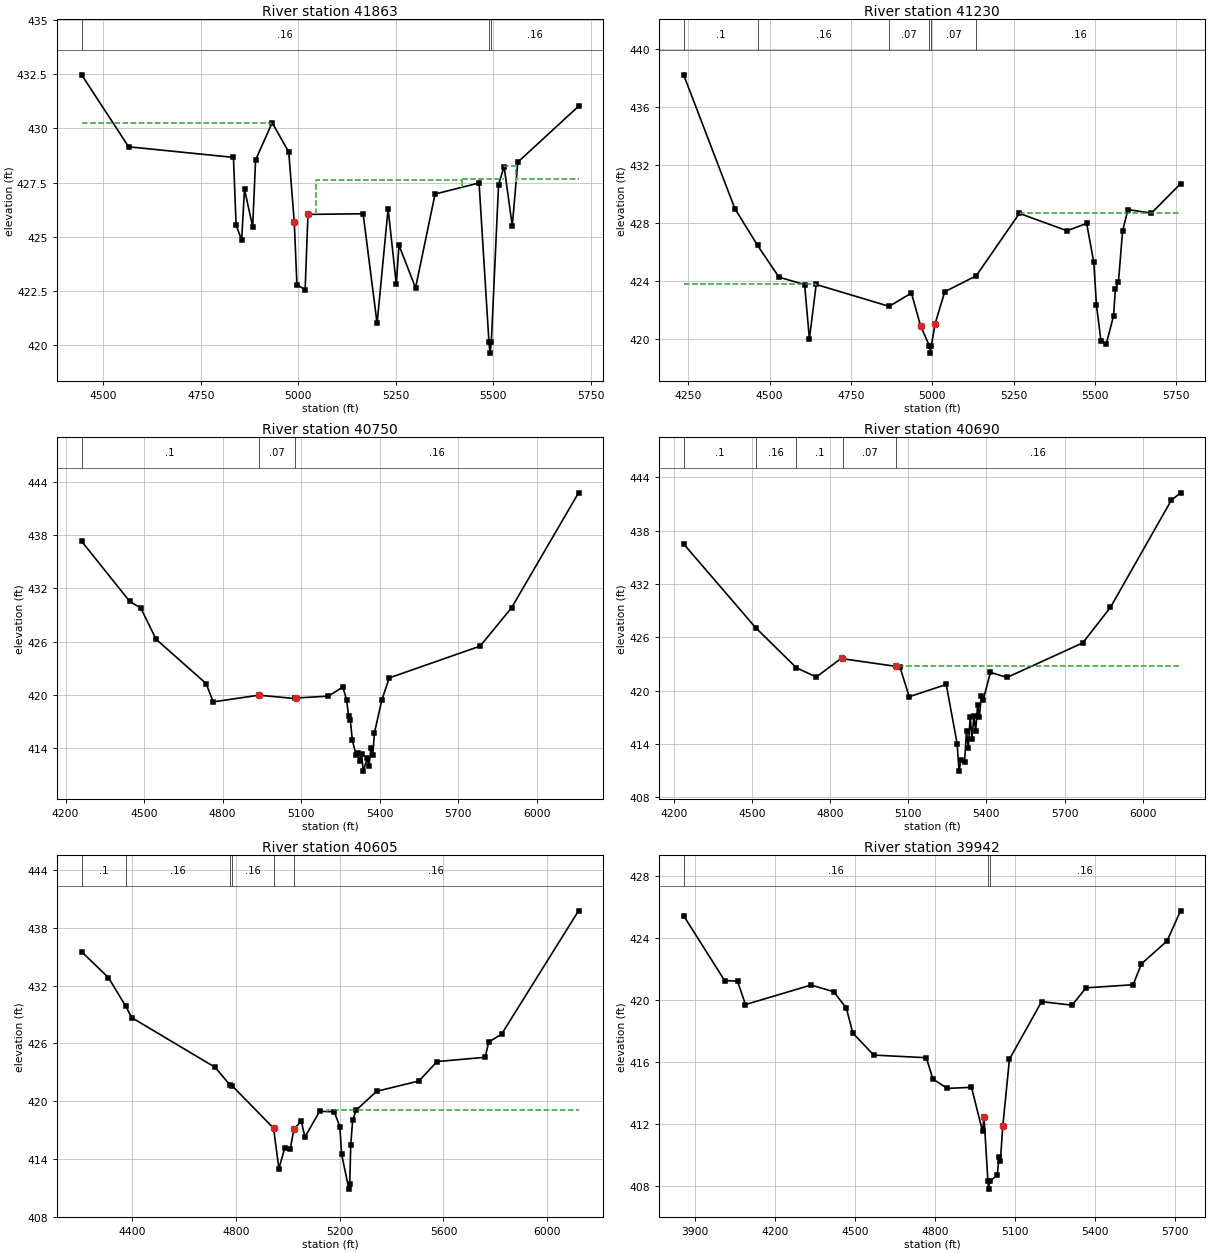
Type RM Length L Ch R = 1 ,41863   ,633,633,633
BEGIN DESCRIPTION:
COPPERAS CREEK 61.0
END DESCRIPTION:
XS GIS Cut Line= 3
      3513692.07     10322091.61      3513191.82     10321628.08
      3512792.11     10321191.65
#Sta/Elev= 30
  4444.6  432.47    4565  429.15  4833.8  428.66  4840.6  425.53  4854.8  424.85
  4862.1  427.19  4883.1  425.46  4890.5  428.54    4933  430.26  4975.5  428.91
  4989.7  425.67  4996.5  422.79  5017.5  422.55  5024.8  426.03  5166.2  426.06
    5202     421  5230.2  426.29  5251.3  422.81  5258.1  424.61  5300.6  422.64
  5350.6  426.97  5463.4  427.48  5488.8  420.13  5491.5  419.63  5494.8  420.13
  5513.4   427.4  5527.6  428.24  5548.5   425.5  5562.7  428.44  5718.4  431.02
#Mann= 3 ,-1 , 0
  4444.6     .16       0  5488.8     .07       0  5494.8     .16       0
#XS Ineff= 5 ,-1
  4444.6 4930.57  430.26 5045.91 5419.77  427.63 5419.77 5527.16  427.67
 5527.16 5558.18  428.27 5558.18  5718.4  427.67
Permanent Ineff=
       F       F       F       F       F
Bank Sta=4989.7,5024.8
XS Rating Curve= 0 ,0
Exp/Cntr=0.3,0.1

Type RM Length L Ch R = 1 ,41230   ,480,480,480
BEGIN DESCRIPTION:
COPPERAS CREEK 60.0
END DESCRIPTION:
XS GIS Cut Line= 3
      3514142.08     10321641.63      3513542.11     10321191.64
      3512852.86     10320832.22
#Sta/Elev= 30
  4235.9  438.23  4393.2  428.99    4463  426.45  4528.6  424.26  4607.7  423.74
  4622.3  419.98  4643.2  423.75  4867.6  422.24  4935.9  423.16    4964   420.9
  4991.1  419.51  4993.9  419.01  4997.1  419.51  5008.4  421.01  5038.3  423.25
  5135.1  424.35  5267.8  428.66  5414.4  427.46  5474.5  427.97  5496.6  425.27
  5504.7   422.3  5518.7  419.83  5535.1  419.67  5557.2  421.58  5562.8  423.42
  5572.3  423.93  5584.9  427.44  5601.4  428.92  5673.8  428.68  5763.2  430.71
#Mann= 6 ,-1 , 0
  4235.9      .1       0    4463     .16       0  4867.6     .07       0
  4991.1     .07       0  4997.1     .07       0  5135.1     .16       0
#XS Ineff= 2 , 0
         4642.73  423.79 5269.09           428.7
Permanent Ineff=
       F       F
Bank Sta=4964,5008.4
XS Rating Curve= 0 ,0
Exp/Cntr=0.3,0.1

Type RM Length L Ch R = 1 ,40750   ,60,60,60
BEGIN DESCRIPTION:
COPPERAS CREEK 59.0
END DESCRIPTION:
XS GIS Cut Line= 4
      3514242.11     10321491.65      3513965.92     10321027.49
      3513768.01     10320745.37      3513092.13     10319991.67
#Sta/Elev= 30
  4261.6  437.31  4444.7  430.56  4487.5  429.79  4545.9  426.28  4736.8  421.29
    4764  419.23    4938  419.98  5074.9  419.61    5081  419.67    5203  419.87
    5259   420.9  5273.2  419.45  5280.7  417.67  5287.4  417.18  5294.9  414.97
  5309.1  413.24  5315.8   413.5  5323.3  412.56  5330.1  413.31  5337.3  411.43
  5351.7  412.87  5358.5  411.98    5366  413.99  5372.7  413.23  5379.7  415.76
  5407.8  419.46  5436.2  421.93  5783.1  425.51  5903.5  429.85  6158.7  442.77
#Mann= 3 ,-1 , 0
  4261.6      .1       0    4938     .07       0  5074.9     .16       0
#Block Obstruct= 2 , 0
                         5099.43          419.42
Bank Sta=4938,5081
XS Rating Curve= 0 ,0
Exp/Cntr=0.3,0.1

Type RM Length L Ch R = 1 ,40690   ,85,85,85
BEGIN DESCRIPTION:
COPPERAS CREEK 59.01
END DESCRIPTION:
XS GIS Cut Line= 4
      3514258.87     10321476.06      3513913.06     10320839.81
      3513818.01     10320762.99      3513111.39     10319972.16
#Sta/Elev= 30
  4238.5  436.49  4514.4  427.09    4671  422.58  4747.4  421.54  4845.3  423.68
    4851  423.58  5053.9  422.73  5068.2  422.68    5104  419.32  5246.1   420.7
  5287.9  414.06  5295.2  410.96  5302.1  412.16  5316.4  411.96  5323.9  415.45
  5330.6  413.61  5338.1  417.08  5344.8  414.62  5352.3  417.14    5359  415.42
  5366.5   418.4  5373.2  417.02  5380.7  419.38  5387.4  418.91  5415.8  422.06
  5479.4  421.49  5770.3  425.38  5876.4  429.37  6109.7   441.4  6145.4  442.24
#Mann= 5 ,-1 , 0
  4238.5      .1       0  4514.4     .16       0    4671      .1       0
    4851     .07       0  5053.9     .16       0
#XS Ineff= 2 , 0
                          5069.6          422.83
Permanent Ineff=
       F       F
#Block Obstruct= 2 , 0
                         5018.47          422.22
Bank Sta=4845.3,5053.9
XS Rating Curve= 0 ,0
Exp/Cntr=0.3,0.1

Type RM Length L Ch R = 1 ,40605   ,663,663,663
BEGIN DESCRIPTION:
COPPERAS CREEK 59.02
END DESCRIPTION:
XS GIS Cut Line= 4
      3514292.24     10321459.86      3513959.18     10320776.04
      3513819.08     10320645.83       3513182.6     10319922.19
#Sta/Elev= 30
    4205   435.5  4308.4  432.82  4374.5  429.87  4398.5  428.66  4719.7  423.51
  4777.1  421.67  4785.4  421.59  4945.1  417.19  4965.3     413  4988.1  415.13
  5009.1  415.03  5023.3   417.1  5051.6  417.92  5065.8  416.27  5122.5  418.95
  5178.7  418.89  5200.5  417.36  5207.2  414.49  5235.4  410.87  5238.6  411.37
  5242.4  415.44  5249.9  418.07  5264.1  419.08  5341.9  421.02  5505.1  422.09
  5575.3  424.11  5760.3  424.55  5774.5  426.13  5823.9  426.95  6120.6  439.75
#Mann= 6 ,-1 , 0
    4205      .1       0  4374.5     .16       0  4777.1      .1       0
  4785.4     .16       0  4945.1     .07       0  5023.3     .16       0
#XS Ineff= 2 , 0
                         5150.57          419.05
Permanent Ineff=
       F       F
Bank Sta=4945.1,5023.3
XS Rating Curve= 0 ,0
Exp/Cntr=0.3,0.1

Type RM Length L Ch R = 1 ,39942   ,1762,1762,1762
BEGIN DESCRIPTION:
COPPERAS CREEK 57.0
END DESCRIPTION:
XS GIS Cut Line= 3
      3514621.43     10321274.33      3514192.11     10320191.64
      3514002.44     10319520.53
#Sta/Elev= 30
  3857.8  425.46  4011.3  421.28  4059.6  421.24  4089.3  419.73  4335.1  420.99
  4420.1  420.56  4467.4   419.5  4491.7  417.89  4570.1  416.47  4767.2   416.3
  4791.6  414.93  4845.6  414.32  4936.4  414.39  4977.9  411.54  4983.3  412.48
    4998  408.32  5000.7  407.82    5004  408.32  5032.9  408.72  5039.5  409.89
  5044.7  409.66  5053.7  411.89  5078.7  416.21  5199.2  419.92  5313.5  419.69
  5365.4  420.81  5542.1  421.01  5573.3  422.36    5669  423.83  5719.9  425.78
#Mann= 3 ,-1 , 0
  3857.8     .16       0    4998     .07       0    5004     .16       0
Bank Sta=4983.3,5053.7
XS Rating Curve= 0 ,0
Exp/Cntr=0.3,0.1

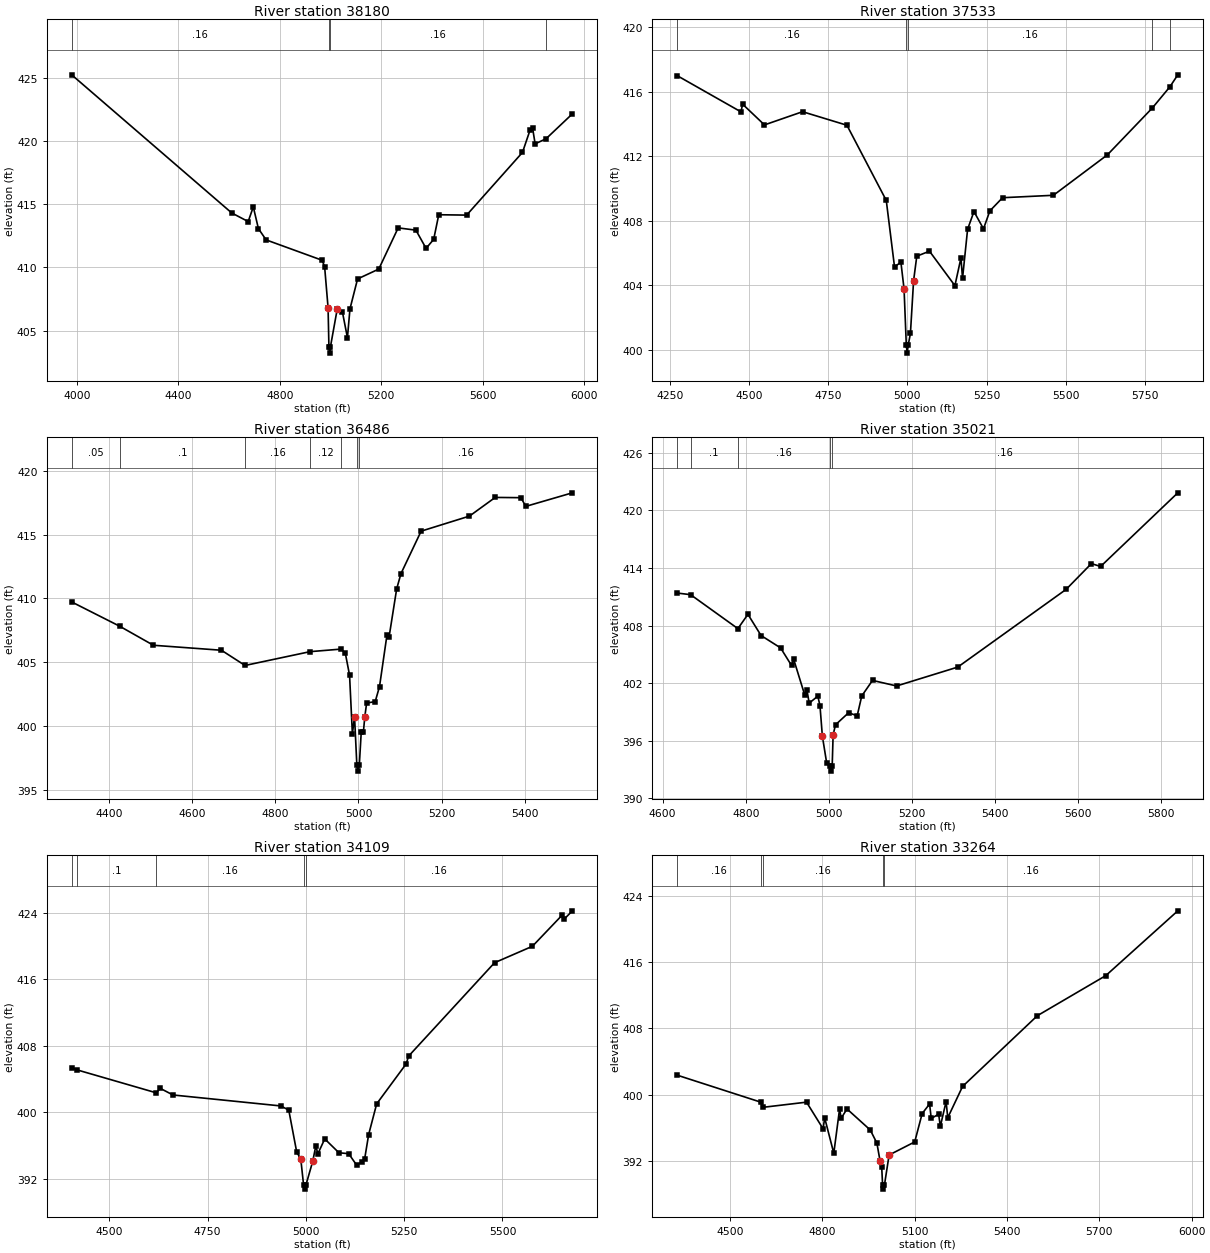
Type RM Length L Ch R = 1 ,38180   ,647,647,647
BEGIN DESCRIPTION:
COPPERAS CREEK 56.0
END DESCRIPTION:
XS GIS Cut Line= 3
      3515277.29     10321340.65      3515159.39      10320522.7
       3515122.6      10319374.9
#Sta/Elev= 30
  3978.8  425.23  4610.1   414.3  4674.9  413.62  4695.1  414.78  4715.3  413.06
  4745.7  412.17  4966.3  410.56  4976.4  410.06 4990.06   406.8  4993.4  403.71
  4996.1  403.21  4999.4  403.71  5026.4  406.72  5046.4  406.49  5066.4  404.43
  5076.4  406.71  5106.4  409.08    5190  409.86  5266.5  413.12  5336.5  412.94
  5376.6   411.5  5406.6  412.21  5426.6  414.16  5536.6  414.13  5756.8  419.09
  5786.8  420.86  5796.8  421.01  5806.8  419.77  5849.7  420.17  5953.6  422.14
#Mann= 4 ,-1 , 0
  3978.8     .16       0  4993.4     .07       0  4999.4     .16       0
  5849.7      .1       0
Bank Sta=4990.06,5026.4
XS Rating Curve= 0 ,0
Exp/Cntr=0.3,0.1

Type RM Length L Ch R = 1 ,37533   ,1047,1047,1047
BEGIN DESCRIPTION:
COPPERAS CREEK 53.0
END DESCRIPTION:
XS GIS Cut Line= 3
      3515719.45     10320986.96       3515682.6     10320382.69
      3515763.66     10319409.95
#Sta/Elev= 30
  4272.6  417.01  4474.3  414.76  4479.3  415.24  4548.4  413.95  4668.7  414.77
  4808.9  413.93  4933.2  409.26  4959.3  405.13  4979.4  405.43  4989.4  403.76
  4996.5  400.28  4999.2  399.78  5002.5  400.28  5009.5     401  5019.5  404.28
  5029.6   405.8  5069.7  406.11    5150  403.97  5169.1  405.69  5174.1  404.42
  5190.1  407.47  5210.2  408.57  5240.3   407.5  5260.4  408.61  5300.5  409.43
  5461.1  409.58  5631.6  412.09  5773.6     415  5828.9  416.31  5854.1  417.06
#Mann= 5 ,-1 , 0
  4272.6     .16       0  4996.5     .07       0  5002.5     .16       0
  5773.6      .1       0  5828.9     .16       0
Bank Sta=4989.4,5019.5
XS Rating Curve= 0 ,0
Exp/Cntr=0.3,0.1

Type RM Length L Ch R = 1 ,36486   ,1465,1465,1465
BEGIN DESCRIPTION:
COPPERAS CREEK 51.0
END DESCRIPTION:
XS GIS Cut Line= 3
      3516235.29     10320773.24      3516392.11     10320091.64
      3516515.31      10319601.6
#Sta/Elev= 30
    4310  409.73  4425.5  407.83  4506.6  406.34  4670.3  405.95  4727.1  404.76
  4883.5  405.84    4958  406.04  4968.4  405.72  4978.6     404  4985.4  399.41
  4990.6  400.75  4996.1  396.99  4998.9  396.49  5002.1  396.99  5006.8  399.59
    5012  399.59 5015.34  400.76  5019.7  401.82  5040.3  401.93  5050.7  403.11
  5068.5  407.12  5073.7  406.99  5091.9  410.74  5102.2  411.94  5150.8  415.27
  5267.2  416.45  5329.1  417.91  5390.9  417.89  5402.7  417.21  5514.7  418.27
#Mann= 7 ,-1 , 0
    4310     .05       0  4425.5      .1       0  4727.1     .16       0
  4883.5     .12       0    4958     .16       0  4996.1     .07       0
  5002.1     .16       0
Bank Sta=4990.6,5015.34
XS Rating Curve= 0 ,0
Exp/Cntr=0.3,0.1

Type RM Length L Ch R = 1 ,35021   ,912,912,912
BEGIN DESCRIPTION:
COPPERAS CREEK 49.0
END DESCRIPTION:
XS GIS Cut Line= 3
      3516898.52     10320913.27      3517075.38     10320382.69
      3517370.12     10319807.94
#Sta/Elev= 30
    4635  411.39  4667.4  411.22  4781.2  407.68  4805.4  409.17    4837  406.96
    4884  405.67  4910.3  403.84  4915.6  404.47  4941.9  400.79  4947.2  401.32
  4952.9  399.91  4973.6  400.64  4978.8  399.66  4984.6  396.46  4995.1  393.63
  5002.2  393.32  5004.9  392.82  5008.2  393.32  5010.5  396.61  5016.2  397.65
  5047.8  398.91  5068.4  398.59  5079.4  400.66  5105.3  402.28  5163.3   401.7
  5310.6  403.67  5571.3  411.77  5632.2  414.46  5654.4  414.16  5840.2  421.84
#Mann= 5 ,-1 , 0
    4635     .05       0  4667.4      .1       0  4781.2     .16       0
  5002.2     .07       0  5008.2     .16       0
Bank Sta=4984.6,5010.5
XS Rating Curve= 0 ,0
Exp/Cntr=0.3,0.1

Type RM Length L Ch R = 1 ,34109   ,845,845,845
BEGIN DESCRIPTION:
COPPERAS CREEK 48.0
END DESCRIPTION:
XS GIS Cut Line= 3
      3517404.26     10321086.38      3517554.23     10320936.41
       3517742.1     10319891.65
#Sta/Elev= 30
  4404.2  405.37  4418.7  405.08  4619.3  402.33  4629.4  402.87  4661.8  402.07
  4936.1  400.75  4956.4  400.25  4976.7  395.17  4986.9  394.38  4994.1  391.23
  4996.8  390.73  5000.1  391.23  5017.4  394.09  5025.3  395.96  5030.3  394.97
  5047.9  396.78    5084  395.11  5108.8     395  5129.2  393.61  5142.7  394.02
  5149.5  394.38  5159.6   397.3    5180     401  5255.1  405.82  5261.2  406.75
  5479.9     418  5576.2  419.98    5651  423.69  5657.5  423.27  5677.8  424.25
#Mann= 5 ,-1 , 0
  4404.2     .16       0  4418.7      .1       0  4619.3     .16       0
  4994.1     .07       0  5000.1     .16       0
Bank Sta=4986.9,5017.4
XS Rating Curve= 0 ,0
Exp/Cntr=0.3,0.1

Type RM Length L Ch R = 1 ,33264   ,693,693,693
BEGIN DESCRIPTION:
COPPERAS CREEK 47.0
END DESCRIPTION:
XS GIS Cut Line= 3
      3517878.62     10321443.84      3518232.34     10320566.92
      3518306.03     10319888.99
#Sta/Elev= 30
  4327.6  402.35  4598.7   399.1  4607.5  398.47  4748.2  399.09  4801.9  395.88
  4807.3  397.18  4836.8  392.92  4855.6  398.25    4861  397.16  4879.7  398.27
  4955.4  395.73  4976.9  394.15  4987.1  392.02  4992.5  391.29  4995.5  389.09
  4998.3  388.59  5001.5  389.09  5016.6  392.71  5099.9  394.29    5124  397.71
  5148.2  398.87  5153.6  397.12  5177.7  397.64  5183.1  396.16  5201.9  399.16
  5207.3  397.21  5255.5  400.99  5498.6  409.53  5721.1  414.37  5955.1  422.19
#Mann= 5 ,-1 , 0
  4327.6     .16       0  4598.7      .1       0  4607.5     .16       0
  4995.5     .07       0  5001.5     .16       0
Bank Sta=4987.1,5016.6
XS Rating Curve= 0 ,0
Exp/Cntr=0.3,0.1

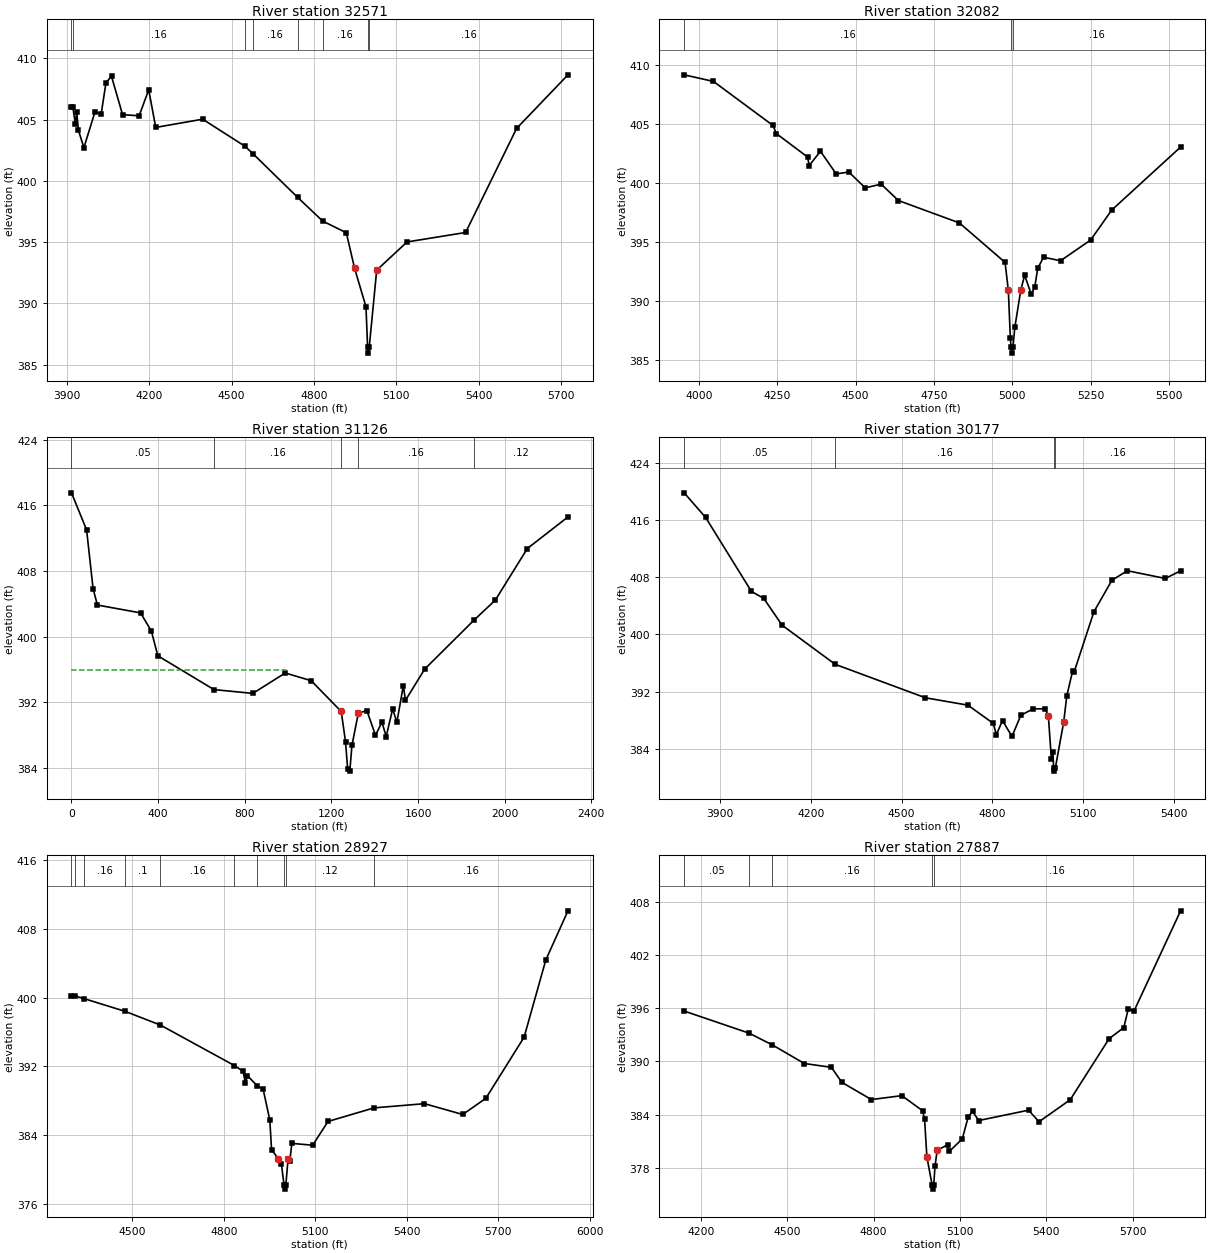
Type RM Length L Ch R = 1 ,32571   ,489,489,489
BEGIN DESCRIPTION:
COPPERAS CREEK 45.0
END DESCRIPTION:
XS GIS Cut Line= 3
        3518505.     10322136.52      3518652.38     10320854.32
      3518549.29     10320346.22
#Sta/Elev= 30
  3916.6     406  3921.5     406  3930.8  404.66  3935.8  405.63  3941.6  404.14
  3961.8  402.71    4002  405.61  4024.9  405.48  4042.3  408.01  4062.4  408.53
  4102.7   405.4  4163.1  405.31    4198  407.43  4223.5  404.36  4394.6  405.03
  4548.3  402.83  4577.1  402.23  4740.9  398.65  4831.9  396.72    4918  395.77
  4948.2  392.87  4989.7  389.73  4995.6  386.45  4998.3  385.95  5001.6  386.45
  5028.8  392.72  5139.5  395.02  5352.8  395.79  5538.6  404.28  5725.7  408.65
#Mann= 8 ,-1 , 0
  3916.6      .1       0  3921.5     .16       0  4548.3      .1       0
  4577.1     .16       0  4740.9      .1       0  4831.9     .16       0
  4995.6     .07       0  5001.6     .16       0
Bank Sta=4948.2,5028.8
XS Rating Curve= 0 ,0
Exp/Cntr=0.3,0.1

Type RM Length L Ch R = 1 ,32082   ,956,956,956
BEGIN DESCRIPTION:
COPPERAS CREEK 44.0
END DESCRIPTION:
XS GIS Cut Line= 3
      3519173.16     10321864.84      3519123.17     10321314.85
       3518836.6      10320323.7
#Sta/Elev= 30
  3952.8  409.17  4046.4  408.61  4236.4  404.87  4247.2  404.18  4346.8  402.19
  4351.9  401.47  4387.8  402.68    4438  400.76  4478.2  400.92  4530.6  399.58
  4581.3  399.89  4636.7   398.5  4831.1   396.6  4976.8  393.25  4987.2  390.88
  4993.7  386.82  4995.9  386.05  4998.6  385.55  5001.9  386.05  5008.1  387.78
  5027.3  390.95  5039.3  392.16  5060.1  390.56  5071.3  391.12  5080.9  392.75
  5099.7  393.69  5153.8  393.39  5249.8  395.15    5317  397.69  5536.8  403.04
#Mann= 3 ,-1 , 0
  3952.8     .16       0  4995.9     .07       0  5001.9     .16       0
Bank Sta=4987.2,5027.3
XS Rating Curve= 0 ,0
Exp/Cntr=0.3,0.1

Type RM Length L Ch R = 1 ,31126   ,949,949,949
BEGIN DESCRIPTION:
COPPERAS CREEK 42.0
END DESCRIPTION:
XS GIS Cut Line= 4
      3519792.11     10321541.67      3519415.25     10320393.23
     3519372.948    10320054.849     3519218.324    10319354.125
#Sta/Elev= 30
       0417.528669.76132 413.00999.65903405.8401119.5908403.8406318.9089402.8836
368.7384400.6619398.6361397.6487657.7496393.5282837.1359393.0645986.6245395.5547
1106.215394.61551245.153390.86031264.918387.16161274.801383.80741284.683383.5835
1294.565386.70951324.213390.68731363.742 390.9461403.272387.95171432.919389.5592
1452.684387.79811482.331391.15891502.096389.55951531.743394.00971541.625 392.224
1630.538396.03231857.497 401.9881956.176404.43622104.193410.73442291.681414.5878
#Mann= 5 ,-1 , 0
       0     .05       0657.7496     .16       01245.153     .07       0
1324.213     .16       01857.497     .12       0
#XS Ineff= 2 , 0
          988.64  395.92
Permanent Ineff=
       F       F
Bank Sta=1245.153,1324.213
XS Rating Curve= 0 ,0
Exp/Cntr=0.3,0.1

Type RM Length L Ch R = 1 ,30177   ,1250,1250,1250
BEGIN DESCRIPTION:
COPPERAS CREEK 41.0
END DESCRIPTION:
XS GIS Cut Line= 3
       3519842.1     10321541.68      3520041.07     10320172.15
      3520091.08     10319922.11
#Sta/Elev= 30
  3782.1  419.77  3852.9  416.34  4004.4  405.98  4044.9  405.02  4105.5  401.27
  4280.7   395.8  4578.7  391.12    4719  390.09  4802.7  387.54  4812.8  385.96
  4833.1  387.94  4864.3  385.72  4893.7  388.68  4934.5  389.58  4974.5  389.58
  4984.6  388.52  4994.5  382.52  4999.5  383.54  5001.8  381.37  5004.6  380.87
  5007.8  381.37  5035.2  387.75  5045.3  391.38  5064.6  394.88  5069.7  394.74
  5134.8  403.14  5194.4  407.56  5245.4  408.88  5370.5   407.8    5421  408.87
#Mann= 4 ,-1 , 0
  3782.1     .05       0  4280.7     .16       0  5001.8     .07       0
  5007.8     .16       0
Bank Sta=4984.6,5035.2
XS Rating Curve= 0 ,0
Exp/Cntr=0.3,0.1

Type RM Length L Ch R = 1 ,28927   ,1040,1040,1040
BEGIN DESCRIPTION:
COPPERAS CREEK 39.0
END DESCRIPTION:
XS GIS Cut Line= 3
      3521251.04     10321147.97      3520801.06     10320747.98
      3520310.94     10319845.66
#Sta/Elev= 30
  4300.2  400.14  4313.3  400.18  4342.7  399.87  4475.6  398.41  4592.2   396.8
  4834.5  392.09  4863.3  391.41  4870.8  390.02  4877.5   390.9  4910.4   389.7
    4929  389.32  4950.9  385.73  4956.6  382.29  4978.4  381.23  4988.9  380.62
  4997.5  378.18  5000.3  377.68  5003.5  378.18  5010.7  381.14  5016.4  380.98
  5023.3  383.01  5091.5   382.8  5141.9  385.57  5292.8  387.15  5458.3  387.64
  5583.8  386.38  5659.8  388.27  5785.3   395.4  5856.5   404.4  5929.1  410.12
#Mann= 10 ,-1 , 0
  4300.2     .16       0  4313.3      .1       0  4342.7     .16       0
  4475.6      .1       0  4592.2     .16       0  4834.5      .1       0
  4910.4     .12       0  4997.5     .07       0  5003.5     .12       0
  5292.8     .16       0
Bank Sta=4978.4,5010.7
XS Rating Curve= 0 ,0
Exp/Cntr=0.3,0.1

Type RM Length L Ch R = 1 ,27887   ,881,881,881
BEGIN DESCRIPTION:
COPPERAS CREEK 37.0
END DESCRIPTION:
XS GIS Cut Line= 3
      3521654.23     10320624.29      3521304.23     10320074.29
      3520413.85     10319476.44
#Sta/Elev= 30
  4141.7   395.7  4367.3   393.2  4448.3  391.87  4559.3  389.77  4653.2  389.34
  4689.6  387.64  4792.2   385.7  4897.8  386.14  4969.8  384.44  4976.9  383.48
  4984.8  379.24  5002.8  376.08  5005.6  375.58  5008.8  376.08    5013  378.16
  5020.8  379.98  5056.8  380.58  5062.8  379.84  5107.8  381.25  5128.8  383.78
  5143.8  384.35  5164.8  383.33  5338.2   384.5  5374.3  383.19  5482.8  385.68
  5617.9  392.58  5668.9  393.83  5683.9  395.88  5704.9  395.74  5866.1  407.02
#Mann= 5 ,-1 , 0
  4141.7     .05       0  4367.3      .1       0  4448.3     .16       0
  5002.8     .07       0  5008.8     .16       0
Bank Sta=4984.8,5020.8
XS Rating Curve= 0 ,0
Exp/Cntr=0.3,0.1

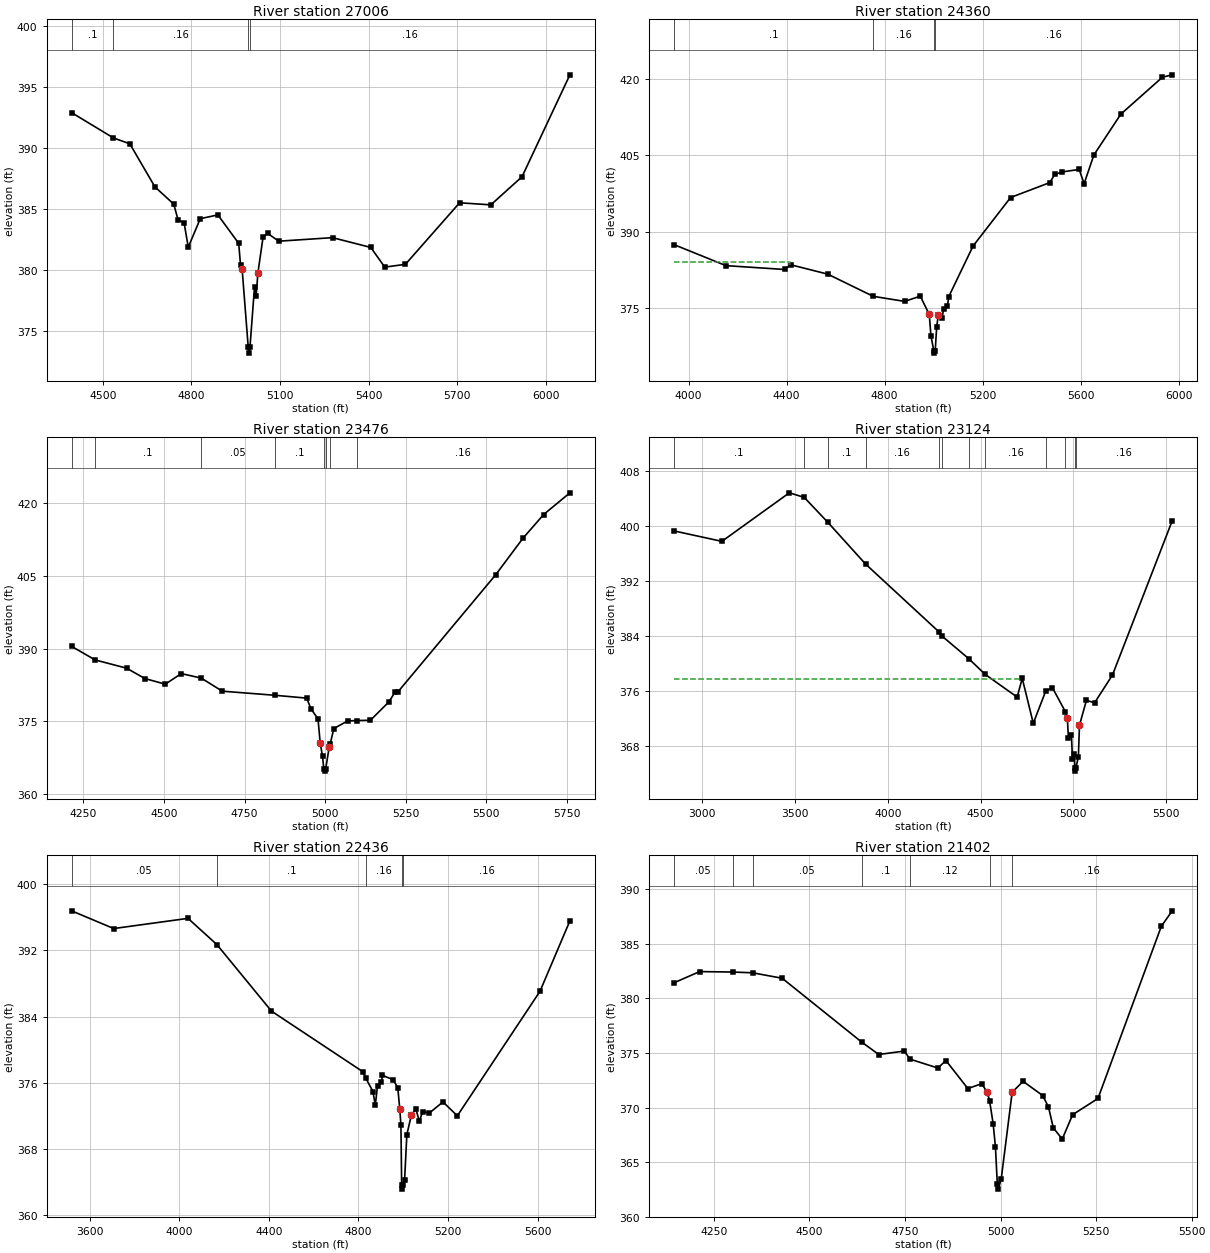
Type RM Length L Ch R = 1 ,27006   ,2646,2646,2646
BEGIN DESCRIPTION:
COPPERAS CREEK 36.0
END DESCRIPTION:
XS GIS Cut Line= 3
      3522033.71     10319987.45       3521733.7     10319737.44
      3520538.91      10319233.1
#Sta/Elev= 30
  4394.5  392.89  4536.3  390.82  4591.8  390.34  4676.7  386.82  4740.5  385.41
  4754.8  384.14  4775.6  383.87  4789.6  381.89  4830.2  384.22  4889.9  384.53
  4960.4   382.2  4966.5  380.45  4971.9  380.13  4992.6  373.73  4995.4  373.23
  4998.6  373.73  5013.9  378.63  5019.3  377.91  5025.6  379.82    5043  382.73
  5058.1  383.03  5095.9  382.38  5278.1  382.67  5407.6  381.87    5455  380.26
  5524.9  380.49  5708.4  385.52  5814.1  385.35  5919.8  387.65  6081.9  395.98
#Mann= 4 ,-1 , 0
  4394.5      .1       0  4536.3     .16       0  4992.6     .07       0
  4998.6     .16       0
Bank Sta=4971.9,5025.6
XS Rating Curve= 0 ,0
Exp/Cntr=0.3,0.1

Type RM Length L Ch R = 1 ,24360   ,884,884,884
BEGIN DESCRIPTION:
COPPERAS CREEK 35.0
END DESCRIPTION:
XS GIS Cut Line= 3
       3522167.5     10319748.91      3522801.23     10318702.52
      3522815.97     10317891.89
#Sta/Elev= 30
  3939.9  387.42  4152.2  383.27  4392.7  382.51    4416  383.45    4568  381.59
  4753.3  377.22  4881.4  376.22  4945.5  377.25  4982.3  373.64  4988.9  369.45
  5000.6  366.52  5003.4  366.02  5006.6  366.52  5012.3   371.1  5019.1  373.56
  5034.6  373.02  5040.5  374.64    5056  375.31  5061.8  377.16  5160.8  387.12
  5314.1   396.7  5474.2  399.64  5494.2  401.24  5524.2  401.74  5594.2  402.24
  5614.2  399.43  5654.2  405.09  5764.2  413.14  5934.2  420.43    5974  420.89
#Mann= 4 ,-1 , 0
  3939.9      .1       0  4753.3     .16       0  5000.6     .07       0
  5006.6     .16       0
#XS Ineff= 2 , 0
         4413.35  384.01
Permanent Ineff=
       F       F
Bank Sta=4982.3,5019.1
XS Rating Curve= 0 ,0
Exp/Cntr=0.3,0.1

Type RM Length L Ch R = 1 ,23476   ,352,352,352
BEGIN DESCRIPTION:
COPPERAS CREEK 33.0
END DESCRIPTION:
XS GIS Cut Line= 3
      3522285.41     10320176.33      3522727.54     10319763.68
      3523367.88     10319071.82
#Sta/Elev= 30
    4213  390.44  4286.1  387.65  4383.9  385.95  4440.6  383.82  4504.1  382.66
  4553.5  384.84  4615.7  383.91    4681  381.22  4845.6  380.37    4943  379.79
  4956.8  377.54  4978.2  375.54    4985  370.61  4992.3  367.78  4996.2  365.27
  4998.9  364.77  5002.2  365.27  5013.3  369.83  5016.1  370.39  5027.5  373.53
    5070  375.09  5098.3  375.18  5140.9  375.23  5197.6  378.96  5218.6  381.12
  5225.9  381.03  5529.9  405.16  5614.9   412.7    5679  417.57  5760.5  422.03
#Mann= 8 ,-1 , 0
    4213     .05       0  4286.1      .1       0  4615.7     .05       0
  4845.6      .1       0  4996.2     .07       0  5002.2      .1       0
  5016.1     .05       0  5098.3     .16       0
Bank Sta=4985,5013.3
XS Rating Curve= 0 ,0
Exp/Cntr=0.3,0.1

Type RM Length L Ch R = 1 ,23124   ,688,688,688
BEGIN DESCRIPTION:
COPPERAS CREEK 31.0
END DESCRIPTION:
XS GIS Cut Line= 3
      3522476.99     10321900.71      3522771.75     10320412.17
      3523342.09     10319391.67
#Sta/Elev= 30
  2846.8  399.32  3105.3   397.8    3469  404.85  3549.2  404.19  3676.8  400.56
  3879.7  394.51  4276.1  384.64  4294.7  383.98  4436.1  380.76  4524.9  378.47
  4697.1  375.18  4724.7  377.89  4784.1  371.37  4850.9  376.03  4886.9  376.56
  4957.8  373.02    4968  372.08  4973.7  369.19  4989.7  369.71  4995.4   366.2
  5005.6  366.93  5008.4  364.92  5011.1  364.42  5014.4  364.92  5027.3  366.52
  5033.1  371.07  5070.8  374.72  5114.2  374.33  5211.2  378.39  5533.3   400.8
#Mann= 12 ,-1 , 0
  2846.8      .1       0  3549.2     .05       0  3676.8      .1       0
  3879.7     .16       0  4276.1      .1       0  4294.7     .16       0
  4436.1      .1       0  4524.9     .16       0  4850.9     .05       0
  4957.8     .16       0  5008.4     .07       0  5014.4     .16       0
#XS Ineff= 2 , 0
         4725.28  377.83
Permanent Ineff=
       F       F
Bank Sta=4968,5033.1
XS Rating Curve= 0 ,0
Exp/Cntr=0.3,0.1

Type RM Length L Ch R = 1 ,22436   ,1034,1034,1034
BEGIN DESCRIPTION:
COPPERAS CREEK 30.0
END DESCRIPTION:
XS GIS Cut Line= 3
      3523686.32     10321679.71      3523686.32     10321379.66
       3523457.1     10319469.01
#Sta/Elev= 30
  3519.5  396.77  3707.6  394.63  4039.1  395.86  4168.3  392.69  4411.8  384.66
    4820  377.34  4833.1  376.54    4865  374.95  4875.1  373.27  4885.2  375.67
  4902.3  376.07  4907.3   376.9  4955.7  376.38  4975.8  375.37  4984.6  372.79
  4989.6  370.91  4992.9  363.67  4995.7  363.17  4998.9  363.67    5006  364.27
  5016.1  369.76  5036.2   372.1  5056.4  372.84  5071.9  371.35  5086.6  372.53
  5116.8  372.36  5177.2   373.7  5241.4  372.02  5610.3  387.05  5743.9  395.56
#Mann= 5 ,-1 , 0
  3519.5     .05       0  4168.3      .1       0  4833.1     .16       0
  4992.9     .07       0  4998.9     .16       0
Bank Sta=4984.6,5036.2
XS Rating Curve= 0 ,0
Exp/Cntr=0.3,0.1

Type RM Length L Ch R = 1 ,21402   ,1002,1002,1002
BEGIN DESCRIPTION:
COPPERAS CREEK 28.0
END DESCRIPTION:
XS GIS Cut Line= 3
       3524510.9      10320581.7      3524311.91     10320080.55
       3523892.1     10319441.64
#Sta/Elev= 30
  4145.5  381.43  4212.7  382.46    4299  382.42  4351.3  382.35  4428.7  381.85
  4636.7     376  4681.4  374.86  4748.7  375.18  4762.6  374.44  4836.1  373.62
  4857.1  374.31  4914.4  371.74  4950.5  372.18  4965.6  371.39  4971.6  370.56
  4980.7  368.51  4986.7  366.38  4991.5  363.02  4994.3  362.52  5001.8  363.46
  5030.4   371.4    5059   372.4  5110.2   371.1  5125.3  370.06  5138.1  368.13
  5161.5  367.11  5188.5  369.34  5254.9  370.83  5420.6  386.61  5449.2  388.03
#Mann= 7 ,-1 , 0
  4145.5     .05       0    4299      .1       0  4351.3     .05       0
  4636.7      .1       0  4762.6     .12       0  4971.6     .07       0
  5030.4     .16       0
Bank Sta=4965.6,5030.4
XS Rating Curve= 0 ,0
Exp/Cntr=0.3,0.1

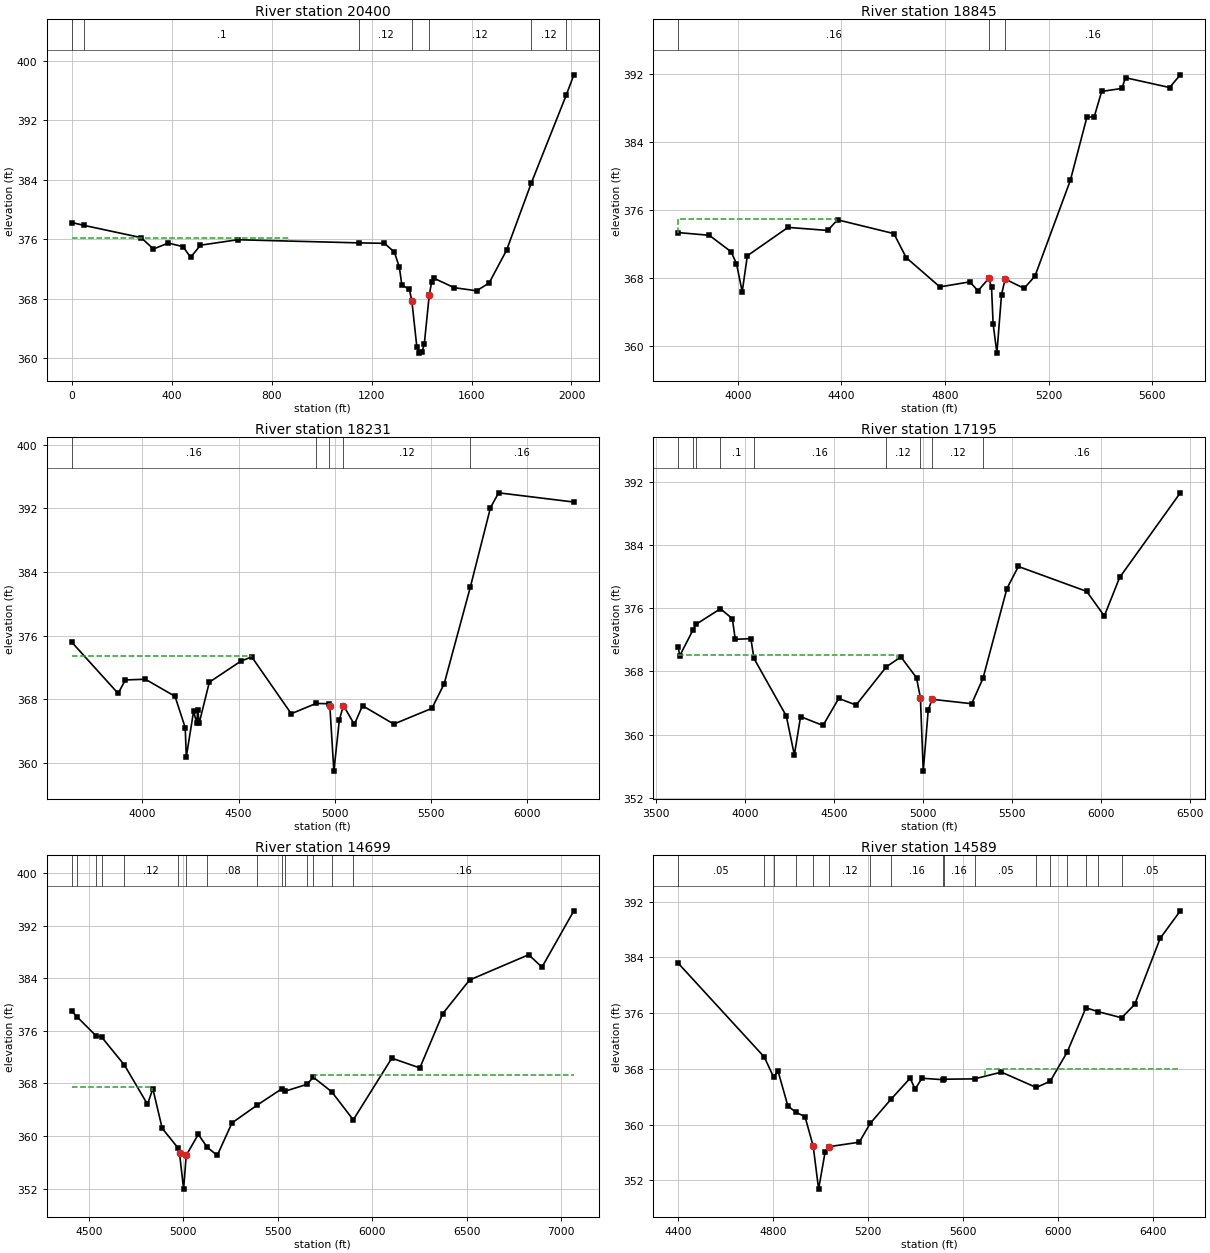
Type RM Length L Ch R = 1 ,20400   ,1555,1555,1555
BEGIN DESCRIPTION:
COPPERAS CREEK 26.0
END DESCRIPTION:
XS GIS Cut Line= 4
     3525259.294    10320881.459      3525280.91     10320088.49
       3525011.6     10319735.86      3524547.72     10319137.29
#Sta/Elev= 30
       0378.257249.52441377.8689277.3367376.2276326.8611374.6908386.2904375.4963
445.7197375.0026475.4344373.5638515.0539375.2037663.6271375.93991151.407375.5145
1251.174375.45761291.081374.28551311.034372.24081321.011369.83531350.941 369.258
1360.917367.74191380.871361.55521390.848360.66741400.824360.76191410.801361.8621
1430.754368.50931440.731370.30241450.708370.73511530.521369.48381620.311369.0644
1670.194370.10941740.031 374.5231839.798383.63631979.471395.46022009.401398.1516
#Mann= 7 ,-1 , 0
       0     .05       049.52441      .1       01151.407     .12       0
1360.917     .07       01430.754     .12       01839.798     .12       0
1979.471     .16       0
#XS Ineff= 2 , 0
          869.32  376.17
Permanent Ineff=
       F       F
Bank Sta=1360.917,1430.754
XS Rating Curve= 0 ,0
Exp/Cntr=0.3,0.1

Type RM Length L Ch R = 1 ,18845   ,614,614,614
BEGIN DESCRIPTION:
COPPERAS CREEK 25.0
END DESCRIPTION:
XS GIS Cut Line= 3
      3526139.46     10320176.33      3525698.92     10318764.78
      3525399.75     10318415.75
#Sta/Elev= 30
  3769.7  373.34  3889.8  373.02  3973.6  371.09  3994.6  369.69  4016.7  366.39
  4036.5  370.62  4193.6  373.95  4346.9  373.59  4384.6  374.84  4602.2  373.22
  4649.8   370.4  4779.8  366.96  4895.5  367.55  4926.9   366.5  4968.8  367.96
  4979.3  366.91  4985.3  362.65    5000  359.18  5017.8  366.04  5031.7  367.88
    5105  366.79  5146.9  368.22  5283.7  379.49  5347.3  386.87  5375.9  386.96
  5404.4  389.92  5482.3  390.27  5496.6  391.53  5666.7  390.38  5708.1  391.87
#Mann= 3 , 0 , 0
  3769.7     .16       0  4968.8     .07       0  5031.7     .16       0
#XS Ineff= 2 , 0
         4377.84  374.92
Permanent Ineff=
       F       F
Bank Sta=4968.8,5031.7
XS Rating Curve= 0 ,0
Exp/Cntr=0.3,0.1

Type RM Length L Ch R = 1 ,18231   ,1036,1036,1036
BEGIN DESCRIPTION:
COPPERAS CREEK 24.0
END DESCRIPTION:
XS GIS Cut Line= 3
      3526979.57     10319962.68      3526342.11     10318791.64
      3525439.41     10317891.92
#Sta/Elev= 30
  3633.8  375.17  3874.4  368.73  3912.4  370.42  4015.9  370.51  4170.1  368.36
    4223  364.42  4228.7  360.75  4266.7   366.5  4282.8  364.97  4288.5  366.66
  4295.3  364.95  4348.3  370.14  4511.7  372.78  4568.6  373.32  4773.8  366.17
  4902.1  367.46  4970.6  367.43  4974.2  367.16  4995.1  358.95  5023.7   365.4
  5044.9   367.2  5101.5  364.83  5143.9  367.18  5306.5  364.87  5504.5  366.85
  5568.1  369.94  5703.6  382.07  5808.6   392.1    5851  393.96  6241.6   392.8
#Mann= 5 ,-1 , 0
  3633.8     .16       0  4902.1     .12       0  4970.6     .07       0
  5044.9     .12       0  5703.6     .16       0
#XS Ineff= 2 , 0
         4567.05  373.47
Permanent Ineff=
       F       F
Bank Sta=4974.2,5044.9
XS Rating Curve= 0 ,0
Exp/Cntr=0.3,0.1

Type RM Length L Ch R = 1 ,17195   ,2496,2496,2496
BEGIN DESCRIPTION:
COPPERAS CREEK 22.0
END DESCRIPTION:
XS GIS Cut Line= 3
      3527679.65     10319586.85      3526905.86     10318142.46
      3526154.21     10317228.69
#Sta/Elev= 30
  3623.1  371.02  3631.6  369.97  3707.3  373.29  3724.9  373.97  3860.5  375.92
  3927.3  374.65  3943.6  372.05  4031.3  372.14  4048.8  369.63  4230.3  362.37
  4275.7  357.44  4310.7  362.28  4436.7  361.16  4525.2  364.58  4622.7  363.74
  4792.5  368.57  4874.6  369.83  4962.3  367.19  4984.2  364.65  5000.2  355.39
  5028.1  363.13    5050  364.47  5272.4  363.91  5336.2  367.14  5470.4  378.47
  5534.7  381.26  5918.8  378.11  6017.8     375  6103.9  379.87  6444.9  390.57
#Mann= 9 ,-1 , 0
  3623.1     .05       0  3707.3     .16       0  3724.9     .05       0
  3860.5      .1       0  4048.8     .16       0  4792.5     .12       0
  4984.2     .07       0    5050     .12       0  5336.2     .16       0
#XS Ineff= 2 , 0
         4853.41  370.12
Permanent Ineff=
       F       F
Bank Sta=4984.2,5050
XS Rating Curve= 0 ,0
Exp/Cntr=0.3,0.1

Type RM Length L Ch R = 1 ,14699   ,110,110,110
BEGIN DESCRIPTION:
COPPERAS CREEK 20.0
END DESCRIPTION:
XS GIS Cut Line= 3
      3529050.26     10319159.37      3528608.14      10318754.1
      3527296.79     10317170.16
#Sta/Elev= 30
  4410.4  378.99  4439.8  378.09  4537.2  375.29  4569.1  375.03  4689.1  370.79
    4811  364.83  4839.4  367.19  4888.7  361.17  4973.8  358.14  4980.6  357.35
    5002  351.92  5015.8  357.05  5079.6  360.25  5126.9  358.29    5180  357.05
  5258.1     362  5392.8  364.73  5522.4   367.2  5540.6  366.83  5654.2  367.86
  5688.4  368.94    5786  366.72  5899.6  362.46  6103.4  371.84  6251.9  370.36
    6373  378.62    6515  383.74  6827.6  387.58  6897.9  385.69  7066.5  394.26
#Mann= 15 ,-1 , 0
  4410.4     .05       0  4439.8     .16       0  4537.2     .05       0
  4569.1     .16       0  4689.1     .12       0  4973.8     .07       0
  5015.8     .12       0  5126.9     .08       0  5392.8     .16       0
  5522.4     .08       0  5540.6     .16       0  5654.2     .08       0
  5688.4     .16       0    5786     .05       0  5899.6     .16       0
#XS Ineff= 2 , 0
         4835.23  367.46 5696.31          369.27
Permanent Ineff=
       F       F
Bank Sta=4980.6,5015.8
XS Rating Curve= 0 ,0
Exp/Cntr=0.3,0.1

Type RM Length L Ch R = 1 ,14589   ,1243,1243,1243
BEGIN DESCRIPTION:
COPPERAS CREEK 19.0
END DESCRIPTION:
XS GIS Cut Line= 4
      3529146.09     10319056.23      3528726.15     10318732.05
      3528476.15     10318397.42      3527746.57     10317487.38
#Sta/Elev= 30
  4401.4  383.17    4764  369.69    4803  366.81  4821.6  367.69  4863.2  362.66
    4898  361.74  4935.3  361.14  4969.9  356.88  4992.6  350.72  5019.9  356.04
  5034.5  356.81  5163.8  357.46    5210  360.17  5297.2  363.62  5378.2  366.66
    5399  365.08  5427.8  366.65  5516.6  366.44  5519.5  366.51  5649.5  366.56
  5762.3  367.53  5909.5  365.32    5968  366.22  6039.5   370.4  6118.5  376.77
  6169.5  376.22  6268.9  375.33    6324  377.26  6431.2  386.75    6516   390.7
#Mann= 17 ,-1 , 0
  4401.4     .05       0    4764     .08       0    4803     .05       0
    4898     .12       0  4969.9     .07       0  5034.5     .12       0
    5210     .08       0  5297.2     .16       0  5516.6     .08       0
  5519.5     .16       0  5649.5     .05       0  5909.5      .1       0
    5968     .05       0  6039.5      .1       0  6118.5     .05       0
  6169.5     .16       0  6268.9     .05       0
#XS Ineff= 2 , 0
                         5692.61          368.02
Permanent Ineff=
       F       F
Bank Sta=4969.9,5034.5
XS Rating Curve= 0 ,0
Exp/Cntr=0.3,0.1