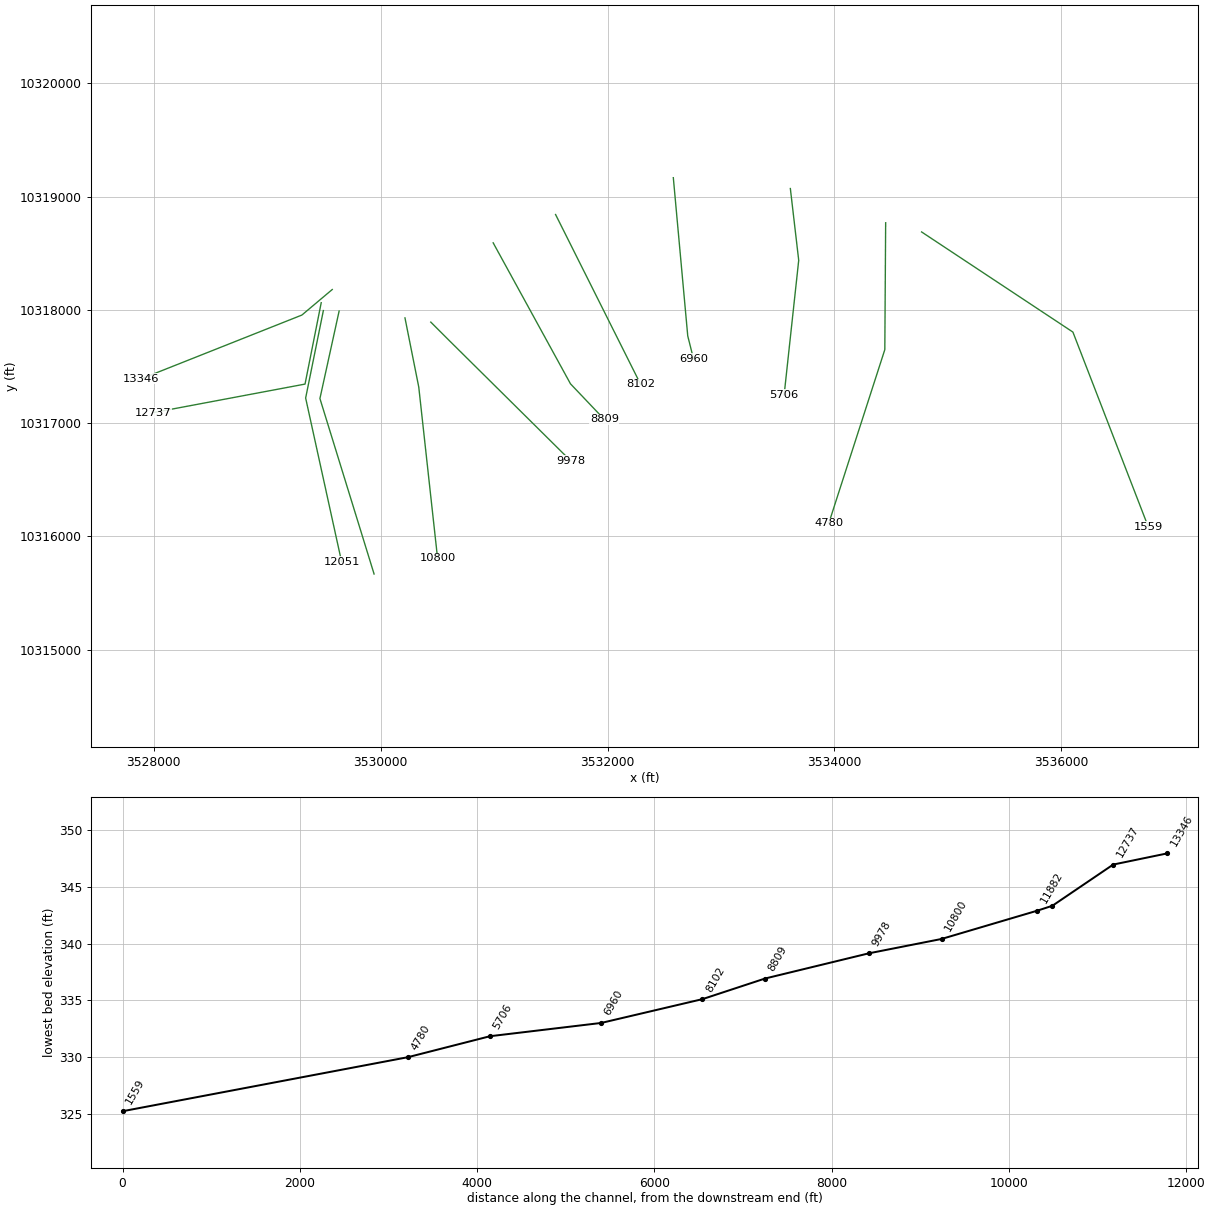
HEC-RAS study COPPERAS CREEK.prj: COPPERAS CREEK Base Level Engineering

--- COPPERAS CREEK.g01 (geometry) --- (continued)

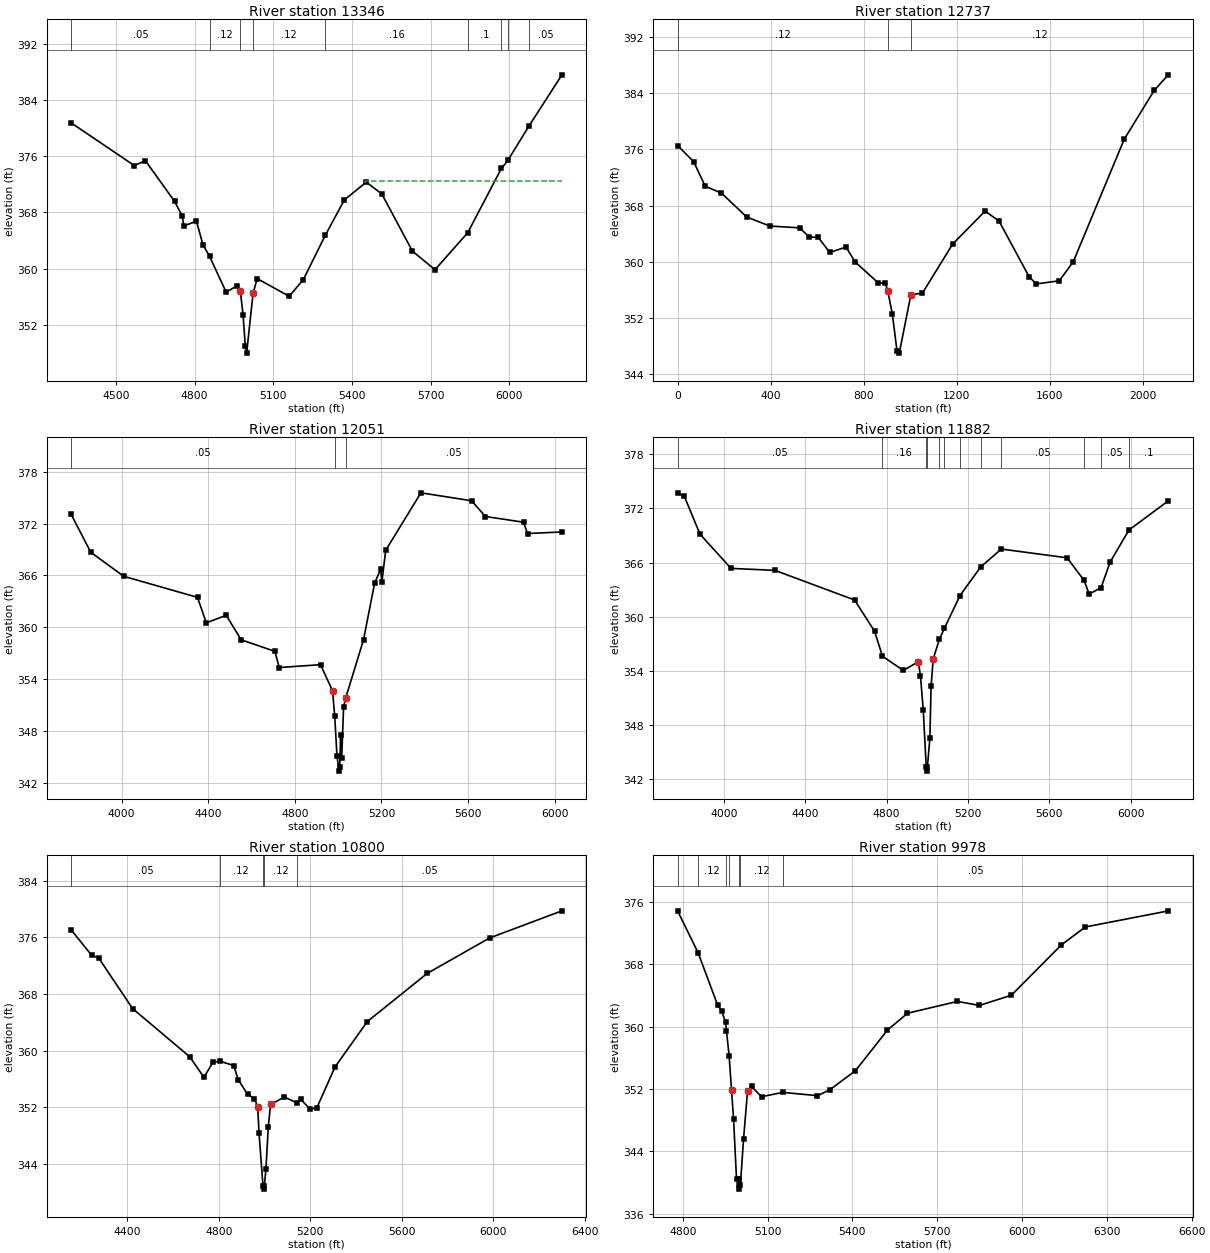
Type RM Length L Ch R = 1 ,13346   ,609,609,609
BEGIN DESCRIPTION:
COPPERAS CREEK 17.0
END DESCRIPTION:
XS GIS Cut Line= 3
      3529573.53     10318179.33      3529305.81     10317953.76
      3527892.14     10317391.66
#Sta/Elev= 30
  4329.6  380.72    4570  374.66  4612.9  375.33  4723.7  369.56  4753.3  367.46
    4759  366.05  4807.3  366.75  4831.6  363.42  4857.1  361.75  4920.6  356.64
  4963.5  357.58  4974.6  356.81    4985  353.36  4993.5  348.97  4998.6  347.97
  5023.2   356.5  5038.8  358.57  5160.8  356.06  5214.8  358.43  5298.2  364.71
  5371.3  369.77  5454.9   372.3  5514.3   370.6  5630.7  362.48  5716.8  359.84
  5841.3  365.08  5970.1  374.24  5994.8  375.39  6074.7  380.25    6201  387.56
#Mann= 9 ,-1 , 0
  4329.6     .05       0  4857.1     .12       0  4974.6     .07       0
  5023.2     .12       0  5298.2     .16       0  5841.3      .1       0
  5970.1     .05       0  5994.8      .1       0  6074.7     .05       0
#XS Ineff= 2 , 0
                          5451.7          372.42
Permanent Ineff=
       F       F
Bank Sta=4974.6,5023.2
XS Rating Curve= 0 ,0
Exp/Cntr=0.3,0.1

Type RM Length L Ch R = 1 ,12737   ,686,686,686
BEGIN DESCRIPTION:
COPPERAS CREEK 16.0
END DESCRIPTION:
XS GIS Cut Line= 3
     3529476.395    10318062.973     3529333.651     10317344.25
     3527992.106    10317091.642
#Sta/Elev= 30
       0376.5548 69.4582374.2416119.0712 370.751188.5294 369.785 297.678366.3689
 396.904365.0846525.8978364.8233565.5882363.5246605.2786363.4641654.8916361.3178
724.3498362.0944764.1484 359.957863.9154356.9716893.8455356.9728903.8222355.8737
923.7756352.6146 943.729347.3371953.7057346.98451003.589355.28321053.473355.5399
 1183.17362.50971322.844367.21241382.704365.80111512.401357.85971542.331356.8355
1642.098357.28851701.958359.98391921.446377.45392051.143384.44082111.003386.6205
#Mann= 3 , 0 , 0
       0     .12       0903.8222     .07       01003.589     .12       0
Bank Sta=903.8222,1003.589
XS Rating Curve= 0 ,0
Exp/Cntr=0.3,0.1

Type RM Length L Ch R = 1 ,12051   ,169,169,169
BEGIN DESCRIPTION:
Mapping XS e5bcbff6
END DESCRIPTION:
XS GIS Cut Line= 3
      3529495.32     10317993.57      3529339.08     10317221.04
      3529655.81     10315776.23
#Sta/Elev= 30
  3766.9  373.06  3857.2  368.68  4009.4   365.9  4350.4  363.46  4391.2  360.51
    4483  361.39  4552.2  358.55    4708  357.21    4728  355.34  4918.7  355.67
  4974.2  352.66  4984.4   349.7  4994.7  345.13  5004.7  343.35  5007.9  343.85
  5011.4  347.53  5016.6  344.91  5025.4  350.78  5035.6  351.86  5117.5  358.56
  5168.7  365.11    5197  366.74  5202.1  365.22  5219.9  368.91  5382.5  375.56
    5617  374.64  5680.6  372.82  5856.6  372.16  5875.1  370.85  6034.2  371.03
#Mann= 3 ,-1 , 0
  3766.9     .05       0  4984.4     .07       0  5035.6     .05       0
Bank Sta=4974.2,5035.6
XS Rating Curve= 0 ,0
Exp/Cntr=0.3,0.1

Type RM Length L Ch R = 1 ,11882   ,1082,1082,1082
BEGIN DESCRIPTION:
COPPERAS CREEK 14.0
END DESCRIPTION:
XS GIS Cut Line= 3
      3529634.23     10317989.31      3529464.95      10317216.7
      3529942.38     10315667.22
#Sta/Elev= 30
  3772.4  373.71  3805.8  373.32  3882.6  369.14  4035.2  365.35  4251.2  365.13
  4642.8  361.85  4740.9  358.39  4779.6  355.63  4882.5  354.06  4955.8  355.02
  4966.3  353.48  4980.1   349.7  4994.6  343.42  4997.4  342.92  5000.6  343.42
  5012.7  346.58  5018.6  352.31    5029  355.34  5059.4   357.5  5084.4  358.74
  5160.9  362.35  5262.4  365.51    5364  367.49  5687.2  366.52  5770.1  364.04
  5795.7  362.51  5854.2  363.22  5898.9  366.06  5991.4   369.6  6184.7  372.82
#Mann= 12 ,-1 , 0
  3772.4     .05       0  4779.6     .16       0  4994.6     .07       0
  5000.6     .16       0  5059.4      .1       0  5084.4     .12       0
  5160.9     .05       0  5262.4      .1       0    5364     .05       0
  5770.1      .1       0  5854.2     .05       0  5991.4      .1       0
Bank Sta=4955.8,5029
XS Rating Curve= 0 ,0
Exp/Cntr=0.3,0.1

Type RM Length L Ch R = 1 ,10800   ,822,822,822
BEGIN DESCRIPTION:
COPPERAS CREEK 12.0
END DESCRIPTION:
XS GIS Cut Line= 3
      3530214.62     10317928.79      3530336.32     10317317.47
      3530502.01     10315806.55
#Sta/Elev= 30
  4155.7  377.07  4244.6   373.5  4275.6  373.11  4423.8  365.95  4672.8  359.15
  4735.5  356.23  4774.3  358.34  4803.8  358.52  4865.4  357.89  4885.5  355.89
  4925.7  353.83  4955.9  353.23  4970.3  352.02    4976  348.36  4993.1  340.92
  4995.9  340.42  4999.1  340.92  5006.2  343.23  5016.3  349.17  5026.3  352.39
  5086.7  353.44  5140.5  352.63  5157.6  353.13  5197.3   351.8  5227.5  351.85
    5308   357.7  5448.8  364.11  5710.4  370.92  5982.9  375.93    6299  379.77
#Mann= 5 ,-1 , 0
  4155.7     .05       0  4803.8     .12       0  4993.1     .07       0
  4999.1     .12       0  5140.5     .05       0
Bank Sta=4970.3,5026.3
XS Rating Curve= 0 ,0
Exp/Cntr=0.3,0.1

Type RM Length L Ch R = 1 ,9978    ,1169,1169,1169
BEGIN DESCRIPTION:
COPPERAS CREEK 10.0
END DESCRIPTION:
XS GIS Cut Line= 3
      3530442.12     10317891.62      3530592.11     10317741.64
      3531673.74     10316668.61
#Sta/Elev= 30
  4781.7  374.88  4854.2  369.51  4923.1  362.81  4937.2  362.05  4951.4   360.6
  4954.8  359.44    4964   356.3 4972.73  351.82  4979.7  348.21  4990.3  340.41
  4997.3  340.41  4997.9  339.65  5000.6  339.15  5003.9  339.65    5015  345.55
  5029.2  351.72  5043.3  352.33  5078.6  351.01  5153.5  351.57  5276.6  351.15
  5319.1  351.88    5411  354.36  5524.1  359.57  5594.9  361.73  5771.6  363.25
  5849.4  362.73  5962.6  364.05  6139.3  370.51  6224.2  372.81  6517.4  374.87
#Mann= 7 ,-1 , 0
  4781.7     .05       0  4854.2     .12       0  4954.8     .16       0
    4964     .12       0  4997.9     .07       0  5003.9     .12       0
  5153.5     .05       0
Bank Sta=4972.73,5029.2
XS Rating Curve= 0 ,0
Exp/Cntr=0.3,0.1

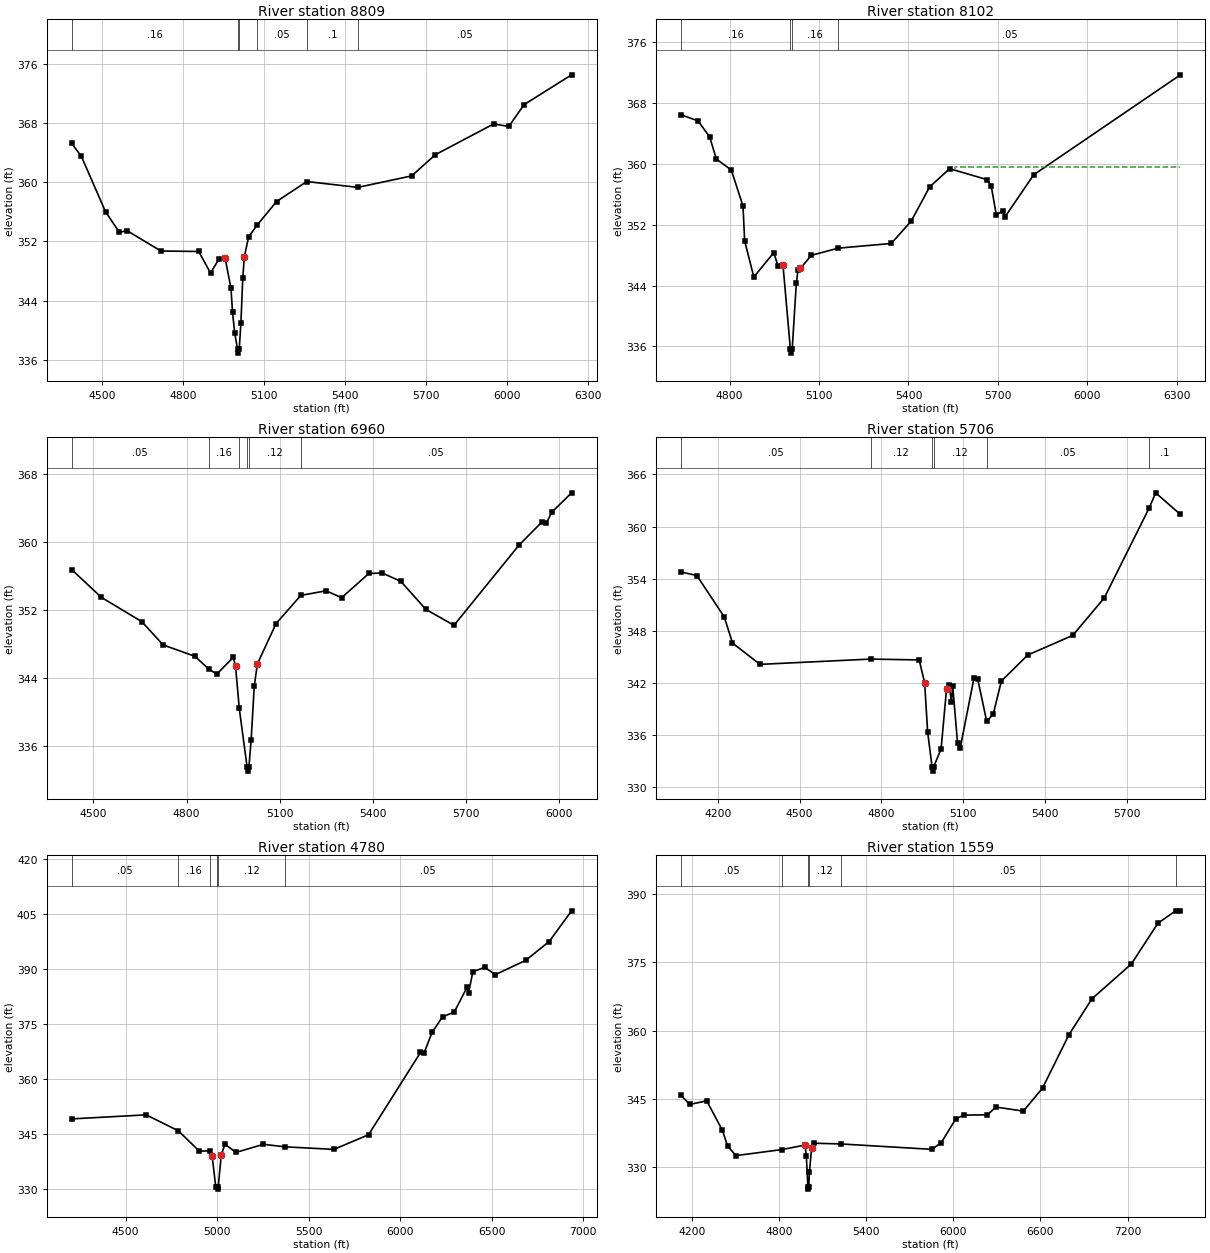
Type RM Length L Ch R = 1 ,8809    ,707,707,707
BEGIN DESCRIPTION:
COPPERAS CREEK 8.0
END DESCRIPTION:
XS GIS Cut Line= 3
      3530992.12     10318591.62      3531673.72     10317346.59
      3531971.64     10317032.64
#Sta/Elev= 30
  4388.6  365.23  4424.1  363.52    4514  356.02  4565.4  353.23  4593.8  353.46
  4719.2  350.71  4859.4  350.65    4903  347.74  4935.3  349.68  4957.1  349.74
  4978.9  345.69  4984.6  342.44  4992.8   339.6  5003.4  337.43  5006.1  336.93
  5009.4  337.43  5015.6  340.97  5022.5  347.01  5028.2   349.9  5044.3  352.63
  5075.8  354.21  5147.7  357.39  5259.8  360.09  5448.6   359.3  5648.4  360.85
  5735.6   363.7    5952  367.86  6008.2  367.52  6064.9  370.47  6240.8  374.49
#Mann= 6 ,-1 , 0
  4388.6     .16       0  5003.4     .07       0  5009.4     .16       0
  5075.8     .05       0  5259.8      .1       0  5448.6     .05       0
Bank Sta=4957.1,5028.2
XS Rating Curve= 0 ,0
Exp/Cntr=0.3,0.1

Type RM Length L Ch R = 1 ,8102    ,1142,1142,1142
BEGIN DESCRIPTION:
COPPERAS CREEK 6.0
END DESCRIPTION:
XS GIS Cut Line= 3
      3531542.12     10318841.61      3531692.11     10318541.64
       3532292.1     10317341.66
#Sta/Elev= 30
  4635.3  366.47    4694  365.65  4733.1  363.54  4755.5  360.63  4805.8  359.18
  4844.9  354.45  4850.5  349.88  4881.2  345.12  4948.3  348.32  4962.3  346.57
  4979.1  346.67    5004  335.61  5006.8  335.11    5010  335.61  5023.8  344.32
  5029.4     346  5037.8  346.26  5074.1  347.97  5164.7  348.91  5342.4  349.53
  5409.5  352.49    5471  356.96  5538.1  359.36  5663.9  357.92  5677.8  357.04
  5694.6  353.31    5717  353.82  5722.6  352.95  5820.4  358.57  6312.3   371.7
#Mann= 4 ,-1 , 0
  4635.3     .16       0    5004     .07       0    5010     .16       0
  5164.7     .05       0
#XS Ineff= 2 , 0
                         5557.27          359.63
Permanent Ineff=
       F       F
Bank Sta=4979.1,5037.8
XS Rating Curve= 0 ,0
Exp/Cntr=0.3,0.1

Type RM Length L Ch R = 1 ,6960    ,1254,1254,1254
BEGIN DESCRIPTION:
COPPERAS CREEK 4.0
END DESCRIPTION:
XS GIS Cut Line= 3
      3532580.14     10319166.73       3532707.4     10317769.46
      3532757.25     10317570.05
#Sta/Elev= 30
  4430.4  356.73  4525.9  353.46  4656.4  350.59  4724.7  347.86  4827.1  346.52
  4871.4  345.02  4897.4  344.43  4950.4  346.39  4957.7  345.36  4969.6  340.43
  4994.8  333.51  4997.6  333.01  5000.8  333.51  5007.9  336.67  5017.9  343.02
    5028  345.63  5088.2  350.38  5167.8  353.69  5248.9  354.23  5299.1  353.42
  5386.8  356.27  5429.6  356.33  5489.9  355.33  5570.2  352.04  5660.6  350.17
  5870.4  359.63  5944.6  362.36    5958  362.21  5975.5  363.48    6039  365.76
#Mann= 6 ,-1 , 0
  4430.4     .05       0  4871.4     .16       0  4969.6     .12       0
  4994.8     .07       0  5000.8     .12       0  5167.8     .05       0
Bank Sta=4957.7,5028
XS Rating Curve= 0 ,0
Exp/Cntr=0.3,0.1

Type RM Length L Ch R = 1 ,5706    ,926,926,926
BEGIN DESCRIPTION:
COPPERAS CREEK 3.0
END DESCRIPTION:
XS GIS Cut Line= 3
      3533611.82     10319070.96      3533685.51     10318437.23
      3533557.01     10317249.36
#Sta/Elev= 30
  4063.2  354.78  4122.9  354.36  4223.6   349.6  4253.8  346.59  4354.5  344.13
  4760.1  344.74  4938.2  344.64  4958.3  342.02  4969.3  336.33  4985.5  332.34
  4988.2  331.84  4991.5  332.34  5018.6   334.4  5038.7  341.35  5048.8   341.8
  5056.1  339.76  5061.1  341.64    5079  335.08    5089  334.56  5139.3  342.58
  5152.9  342.44  5185.8  337.57  5209.7   338.4  5239.6  342.21  5336.4  345.21
  5501.4  347.47  5616.6  351.77  5782.3  362.19  5805.2  363.88    5896  361.39
#Mann= 6 ,-1 , 0
  4063.2     .05       0  4760.1     .12       0  4985.5     .07       0
  4991.5     .12       0  5185.8     .05       0  5782.3      .1       0
Bank Sta=4958.3,5038.7
XS Rating Curve= 0 ,0
Exp/Cntr=0.3,0.1

Type RM Length L Ch R = 1 ,4780    ,3221,3221,3221
BEGIN DESCRIPTION:
COPPERAS CREEK 2.0
END DESCRIPTION:
XS GIS Cut Line= 3
      3534451.91     10318768.81      3534444.54     10317648.72
      3533950.91     10316116.27
#Sta/Elev= 30
  4205.9  349.11  4613.1  350.21  4787.9  345.89  4903.1  340.34  4960.5  340.41
  4973.1  338.97  4993.1   330.5  5000.1  330.49  5002.8  329.99  5006.1  330.49
  5023.1  339.32  5043.1  342.23  5103.1  339.98  5253.1  342.19  5370.4  341.51
  5638.1  340.81  5827.2   344.8  6110.9  367.19  6129.8  366.97  6173.9  372.64
  6231.3  376.89  6295.4  378.21  6364.8  384.93  6373.5  383.44  6396.9  389.16
    6461  390.38  6519.9  388.39  6685.5  392.28  6813.7   397.4    6936  405.76
#Mann= 6 ,-1 , 0
  4205.9     .05       0  4787.9     .16       0  4960.5     .12       0
  5000.1     .07       0  5006.1     .12       0  5370.4     .05       0
Bank Sta=4973.1,5023.1
XS Rating Curve= 0 ,0
Exp/Cntr=0.3,0.1

Type RM Length L Ch R = 1 ,1559    ,0,0,0
BEGIN DESCRIPTION:
COPPERAS CREEK 1.0
END DESCRIPTION:
XS GIS Cut Line= 3
      3534768.81     10318687.76       3536102.6     10317803.48
      3536765.81     10316086.51
#Sta/Elev= 30
  4122.7  345.91  4186.6  343.82  4303.2   344.6  4411.4  338.12  4447.5  334.63
  4504.7  332.58  4823.9  333.92  4979.9   334.9  4988.9  332.42  4999.5  325.72
  5002.3  325.22  5005.5  325.72    5010  328.92    5025  334.26  5038.5   335.3
  5226.3  335.14  5853.6  333.95  5917.9  335.45  6016.4  340.59  6070.9  341.47
  6234.6  341.53  6294.5  343.24  6482.8  342.34  6614.7  347.42    6797  359.16
  6954.5     367  7225.8  374.64    7408  383.57  7530.7  386.32  7563.6  386.23
#Mann= 6 ,-1 , 0
  4122.7     .05       0  4823.9     .12       0  4999.5     .07       0
  5005.5     .12       0  5226.3     .05       0  7530.7      .1       0
Bank Sta=4979.9,5025
XS Rating Curve= 0 ,0
Exp/Cntr=0.3,0.1

Chan Stop Cuts=-1
Use User Specified Reach Order=0
Composite Channel Slope=5