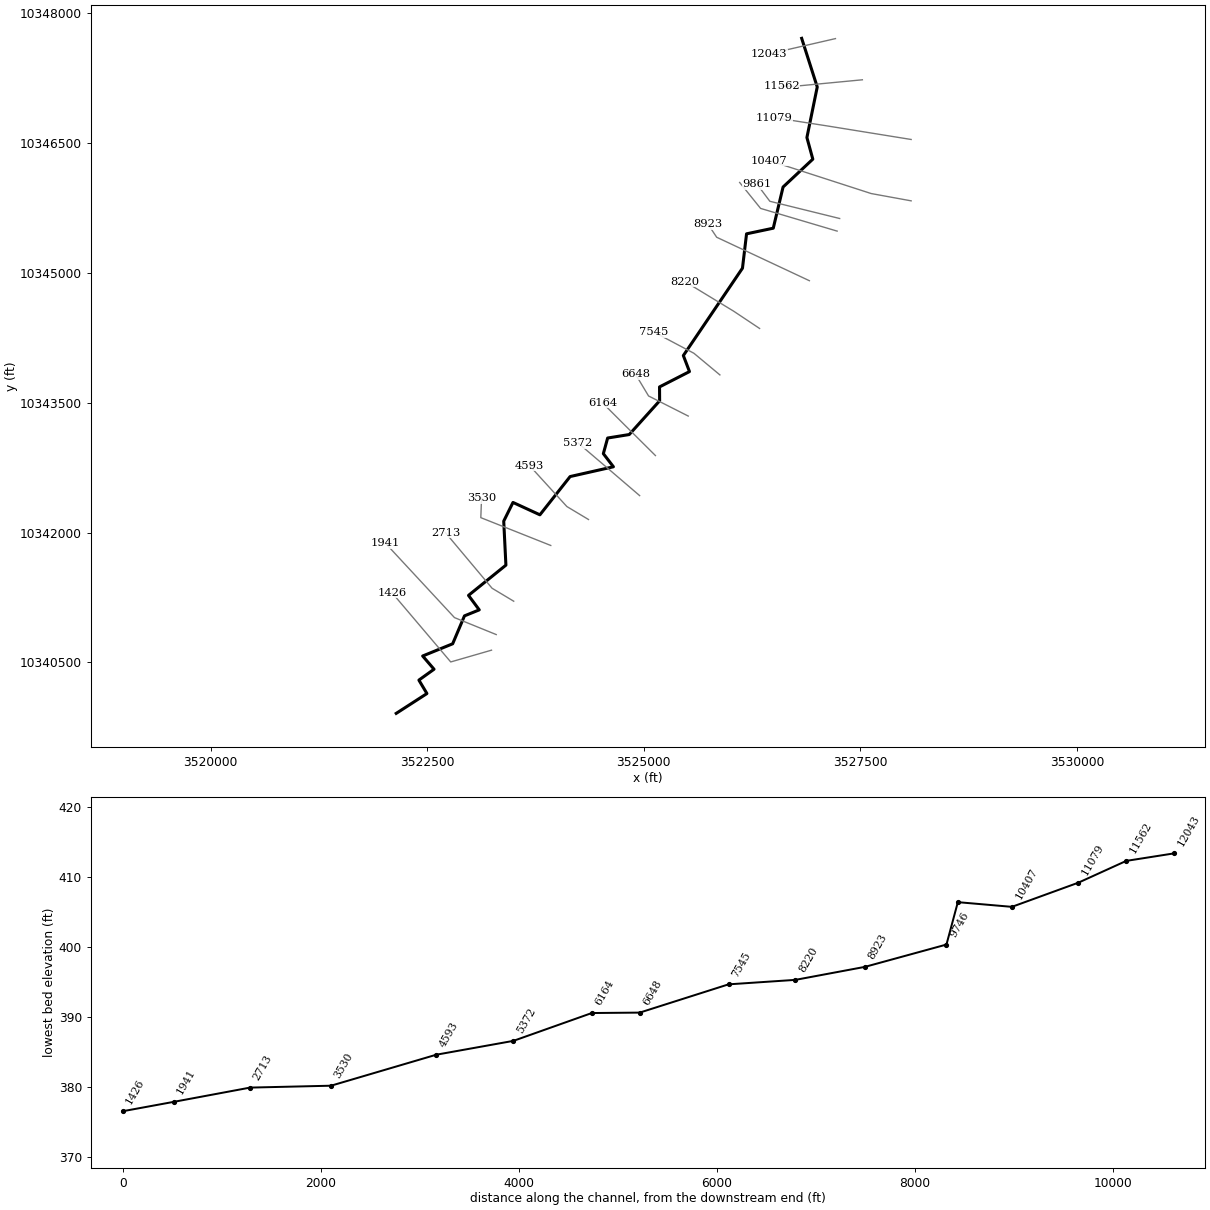
--- CRAZY BRANCH.prj (project) ---

Proj Title=CRAZY BRANCH Base Level Engineering
Current Plan=p01
Default Exp/Contr=0.3,0.1
English Units
Geom File=g01
Flow File=f01
Plan File=p01
BEGIN DESCRIPTION:
CRAZY BRANCH
END DESCRIPTION:

--- CRAZY BRANCH.p01 (plan) ---

Plan Title=Multiple Run
Short Identifier=Multiple
Geom File=g01
Flow File=f01
Subcritical Flow
K Sum by GR= 0
Std Step Tol= 0.01
Critical Tol= 0.01
Num of Std Step Trials= 20
Max Error Tol= 0.3
Flow Tol Ratio= 0.001
Split Flow NTrial= 30
Split Flow Tol= 0.02
Split Flow Ratio= 0.02
Log Output Level= 0
Friction Slope Method= 1
Unsteady Friction Slope Method= 2
Unsteady Bridges Friction Slope Method= 1
Parabolic Critical Depth
Global Vel Dist=  1 , 1 , 1
Global Log Level= 0
CheckData=True
Encroach Param= -1, 0, 0, 0
BEGIN DESCRIPTION:
Multiple Run
END DESCRIPTION:

--- CRAZY BRANCH.f01 (steady flow) ---

Flow Title=Multiple
Number of Profiles=7
Profile Names=10-year,25-year,50-year,1pct_min,100-year,1pct_plu,500-year
River Rch & RM= CRAZY BRANCH,Reach-1,12043
     448     596     715     629     850    1150    1199
River Rch & RM= CRAZY BRANCH,Reach-1,11562
    1457    2087    2630    2420    3273    4427    5079
River Rch & RM= CRAZY BRANCH,Reach-1,8923
    1391    1972    2467    2254    3048    4122    4660
Boundary for River Rch & Prof#=CRAZY BRANCH,Reach-1,1
Up Type=0
Dn Type=3
Dn Slope=0.005
Boundary for River Rch & Prof#=CRAZY BRANCH,Reach-1,2
Up Type=0
Dn Type=3
Dn Slope=0.005
Boundary for River Rch & Prof#=CRAZY BRANCH,Reach-1,3
Up Type=0
Dn Type=3
Dn Slope=0.005
Boundary for River Rch & Prof#=CRAZY BRANCH,Reach-1,4
Up Type=0
Dn Type=3
Dn Slope=0.005
Boundary for River Rch & Prof#=CRAZY BRANCH,Reach-1,5
Up Type=0
Dn Type=3
Dn Slope=0.005
Boundary for River Rch & Prof#=CRAZY BRANCH,Reach-1,6
Up Type=0
Dn Type=3
Dn Slope=0.005
Boundary for River Rch & Prof#=CRAZY BRANCH,Reach-1,7
Up Type=0
Dn Type=3
Dn Slope=0.005

--- CRAZY BRANCH.g01 (geometry) ---

Geom Title=Existing Conditions

River Reach=CRAZY BRANCH,Reach-1
Reach XY= 30
      3526821.98     10347708.05      3527001.68     10347146.29
      3526882.35     10346562.46      3526950.63     10346312.68
      3526607.16     10345990.58      3526494.10     10345515.30
      3526185.74     10345450.18      3526138.70     10345053.51
      3525456.24     10344044.33      3525527.08     10343859.25
      3525181.45     10343682.07      3525182.49     10343521.63
      3524831.81     10343132.03      3524582.50     10343091.89
      3524532.93     10342911.18      3524649.10     10342759.71
      3524149.26     10342646.71      3523800.56     10342204.91
      3523489.89     10342347.90      3523383.00     10342131.76
      3523408.20     10341623.63      3522976.33     10341274.36
      3523100.56     10341107.16      3522929.94     10341037.77
      3522793.62     10340715.29      3522447.38     10340574.35
      3522578.56     10340421.46      3522403.76     10340295.87
      3522496.67     10340140.54      3522142.11     10339911.64

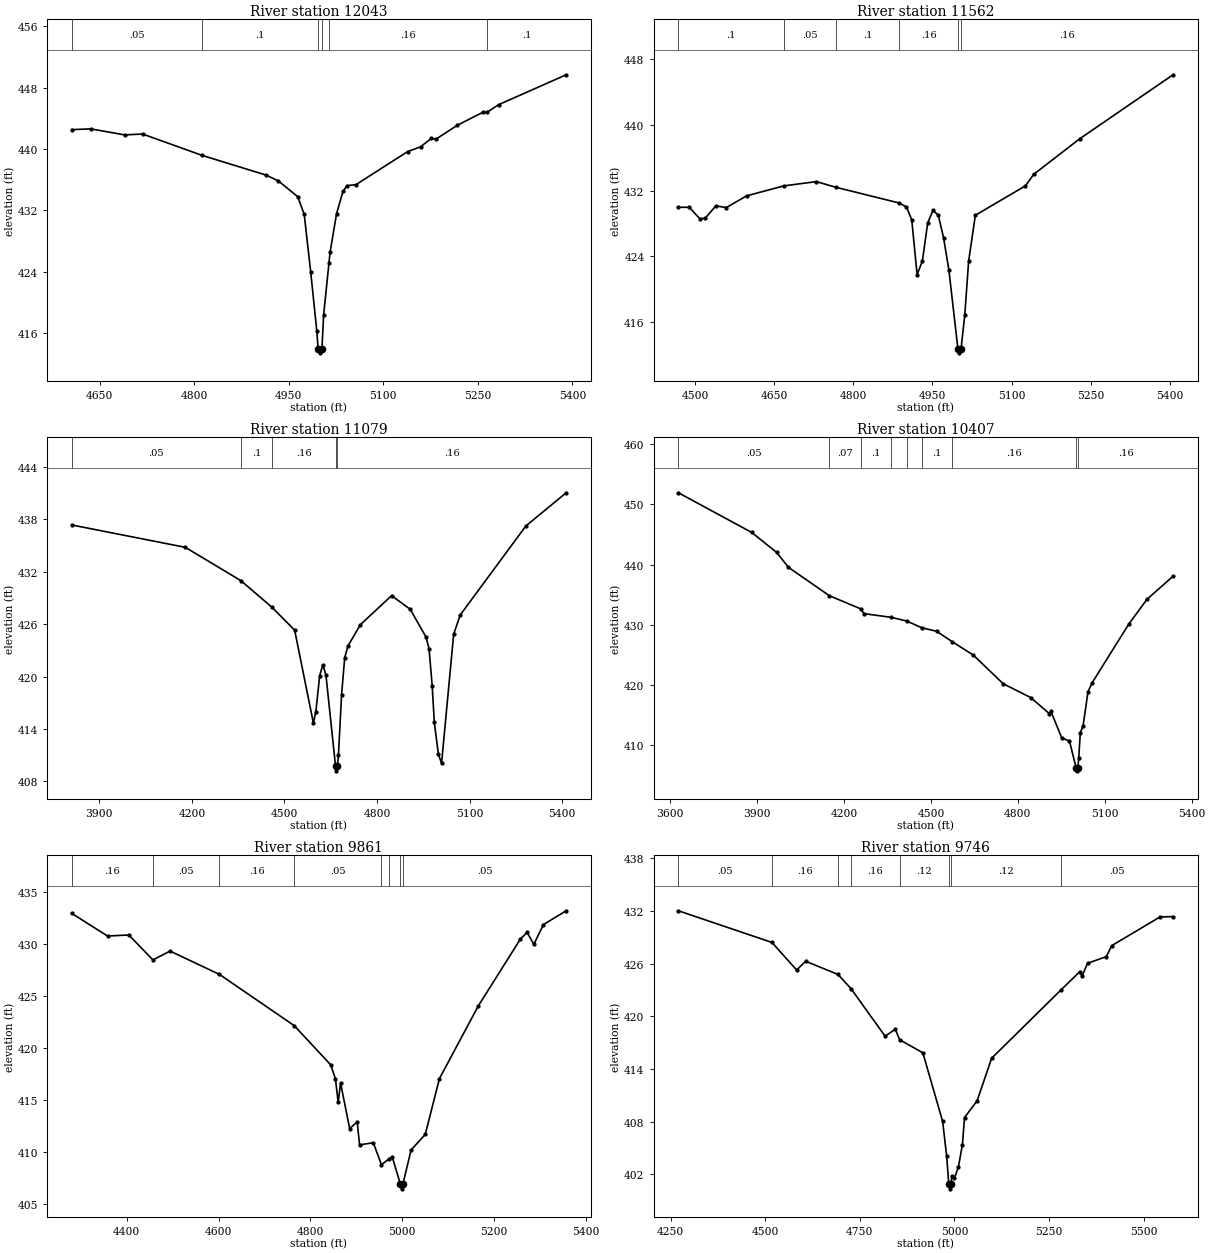
Type RM Length L Ch R = 1,12043,481,481,481
BEGIN DESCRIPTION:
CRAZY BRANCH 22.0
END DESCRIPTION:
XS GIS Cut Line= 3
      3527211.88     10347704.96      3526647.92     10347575.13
      3526447.88     10347525.12
#Sta/Elev= 30
  4605.2  442.52  4635.7  442.62  4689.5  441.83  4717.8  441.95  4812.7  439.15
  4913.8  436.59  4933.3  435.83  4964.1  433.77  4974.4  431.45  4984.6  424.00
  4994.3  416.28  4996.5  413.89  4999.2  413.39  5002.5  413.89  5005.2  418.36
  5013.6  425.06  5015.4  426.50  5025.7  431.55  5035.9  434.46  5042.3  435.21
  5056.5  435.34  5138.6  439.66  5159.1  440.28  5175.8  441.37  5183.9  441.30
  5217.3  443.09  5258.5  444.81  5264.2  444.77  5282.7  445.77  5390.1  449.68
#Mann=6,-1,0
  4605.2    0.05       0  4812.7     0.1       0  4996.5    0.07       0
  5002.5     0.1       0  5013.6    0.16       0  5264.2     0.1       0
Bank Sta=4996.5,5002.5
Exp/Cntr=0.3,0.1

Type RM Length L Ch R = 1,11562,483,483,483
BEGIN DESCRIPTION:
CRAZY BRANCH 21.0
END DESCRIPTION:
XS GIS Cut Line= 3
      3527522.64     10347229.22      3526738.21     10347154.26
      3526588.21     10347154.26
#Sta/Elev= 30
  4468.2  429.97  4488.8  429.96  4508.9  428.57  4519.0  428.64  4539.1  430.14
  4559.1  429.93  4597.4  431.35  4668.0  432.56  4729.9  433.08  4766.8  432.39
  4887.3  430.48  4900.7  430.00  4910.7  428.44  4920.8  421.81  4930.8  423.43
  4940.9  428.06  4950.9  429.58  4961.0  429.02  4971.0  426.27  4981.1  422.38
  4998.2  412.82  5000.9  412.32  5004.2  412.82  5011.2  416.85  5018.6  423.45
  5031.3  429.00  5126.4  432.57  5141.8  433.95  5229.2  438.27  5406.2  446.03
#Mann=6,-1,0
  4468.2     0.1       0  4668.0    0.05       0  4766.8     0.1       0
  4887.3    0.16       0  4998.2    0.07       0  5004.2    0.16       0
Bank Sta=4998.2,5004.2
Exp/Cntr=0.3,0.1

Type RM Length L Ch R = 1,11079,672,672,672
BEGIN DESCRIPTION:
CRAZY BRANCH 20.0
END DESCRIPTION:
XS GIS Cut Line= 3
      3528085.69     10346539.87      3527124.52     10346695.21
      3526503.11     10346792.31
#Sta/Elev= 30
  3810.2  437.35  4178.5  434.79  4358.5  430.98  4459.2  427.94  4533.0  425.31
  4593.8  414.66  4601.8  416.00  4614.1  420.10  4624.2  421.33  4634.3  420.20
  4665.6  409.71  4668.4  409.21  4671.6  409.71  4674.9  410.99  4685.0  417.88
  4695.1  422.15  4705.3  423.47  4745.8  425.93  4847.0  429.26  4907.7  427.69
  4958.4  424.53  4968.5  423.18  4978.6  418.95  4985.5  414.78  4998.8  411.10
  5009.0  410.07  5048.3  424.85  5069.7  427.06  5282.2  437.23  5412.8  441.03
#Mann=5,-1,0
  3810.2    0.05       0  4358.5     0.1       0  4459.2    0.16       0
  4665.6    0.07       0  4671.6    0.16       0
Bank Sta=4665.6,4671.6
Exp/Cntr=0.3,0.1

Type RM Length L Ch R = 1,10407,546,546,546
BEGIN DESCRIPTION:
CRAZY BRANCH 18.0
END DESCRIPTION:
XS GIS Cut Line= 3
      3528085.70     10345831.10      3527624.18     10345915.42
      3526446.78     10346296.52
#Sta/Elev= 30
  3628.8  451.92  3881.8  445.33  3967.9  442.01  4008.6  439.53  4149.7  434.83
  4258.0  432.64  4268.9  431.85  4363.2  431.24  4417.2  430.61  4468.4  429.51
  4519.7  428.92  4573.6  427.19  4646.7  424.96  4749.0  420.23  4845.0  417.90
  4909.0  415.23  4914.2  415.63  4951.5  411.22  4978.2  410.69  5001.1  406.25
  5003.8  405.75  5007.1  406.25  5010.2  407.89  5015.5  412.05  5025.1  413.22
  5042.2  418.91  5056.6  420.39  5182.8  430.11  5245.8  434.24  5335.5  438.06
#Mann=9,-1,0
  3628.8    0.05       0  4149.7    0.07       0  4258.0     0.1       0
  4363.2    0.16       0  4417.2    0.07       0  4468.4     0.1       0
  4573.6    0.16       0  5001.1    0.07       0  5007.1    0.16       0
Bank Sta=5001.1,5007.1
Exp/Cntr=0.3,0.1

Type RM Length L Ch R = 1,9861,115,115,115
BEGIN DESCRIPTION:
CRAZY BRANCH 17.0
END DESCRIPTION:
XS GIS Cut Line= 3
      3527260.45     10345627.21      3526454.72     10345826.12
      3526305.93     10346024.50
#Sta/Elev= 30
  4279.7  432.94  4358.0  430.75  4404.6  430.85  4456.9  428.45  4494.3  429.30
  4601.9  427.06  4765.1  422.12  4844.5  418.35  4854.8  417.00  4860.7  414.73
  4865.9  416.61  4885.7  412.22  4902.2  412.86  4907.3  410.65  4937.2  410.86
  4955.0  408.74  4970.7  409.27  4978.4  409.50  4996.0  406.92  4998.8  406.42
  5002.0  406.92  5019.6  410.16  5050.5  411.66  5081.4  417.03  5166.3  424.04
  5258.0  430.47  5272.5  431.10  5287.1  429.95  5308.0  431.85  5357.6  433.18
#Mann=8,-1,0
  4279.7    0.16       0  4456.9    0.05       0  4601.9    0.16       0
  4765.1    0.05       0  4955.0    0.16       0  4970.7    0.05       0
  4996.0    0.04       0  5002.0    0.05       0
Bank Sta=4996,5002
Exp/Cntr=0.3,0.1

Type RM Length L Ch R = 1,9746,823,823,823
BEGIN DESCRIPTION:
CRAZY BRANCH 16.0
END DESCRIPTION:
XS GIS Cut Line= 3
      3527231.31     10345481.57      3526347.79     10345743.72
      3526106.10     10346043.41
#Sta/Elev= 30
  4270.8  432.02  4518.0  428.41  4582.9  425.28  4607.0  426.27  4692.3  424.77
  4726.5  423.17  4816.8  417.74  4843.7  418.53  4855.1  417.34  4916.5  415.85
  4968.8  408.03  4979.3  404.12  4985.1  400.86  4987.9  400.36  4991.1  400.86
  4993.3  401.81  5000.1  401.58  5010.6  402.87  5021.0  405.40  5026.6  408.48
  5059.8  410.38  5098.2  415.23  5280.5  422.97  5330.7  425.07  5337.2  424.57
  5351.5  426.04  5401.1  426.80  5415.5  428.05  5543.5  431.33  5577.4  431.35
#Mann=8,-1,0
  4270.8    0.05       0  4518.0    0.16       0  4692.3    0.05       0
  4726.5    0.16       0  4855.1    0.12       0  4985.1    0.07       0
  4991.1    0.12       0  5280.5    0.05       0
Bank Sta=4985.1,4991.1
Exp/Cntr=0.3,0.1

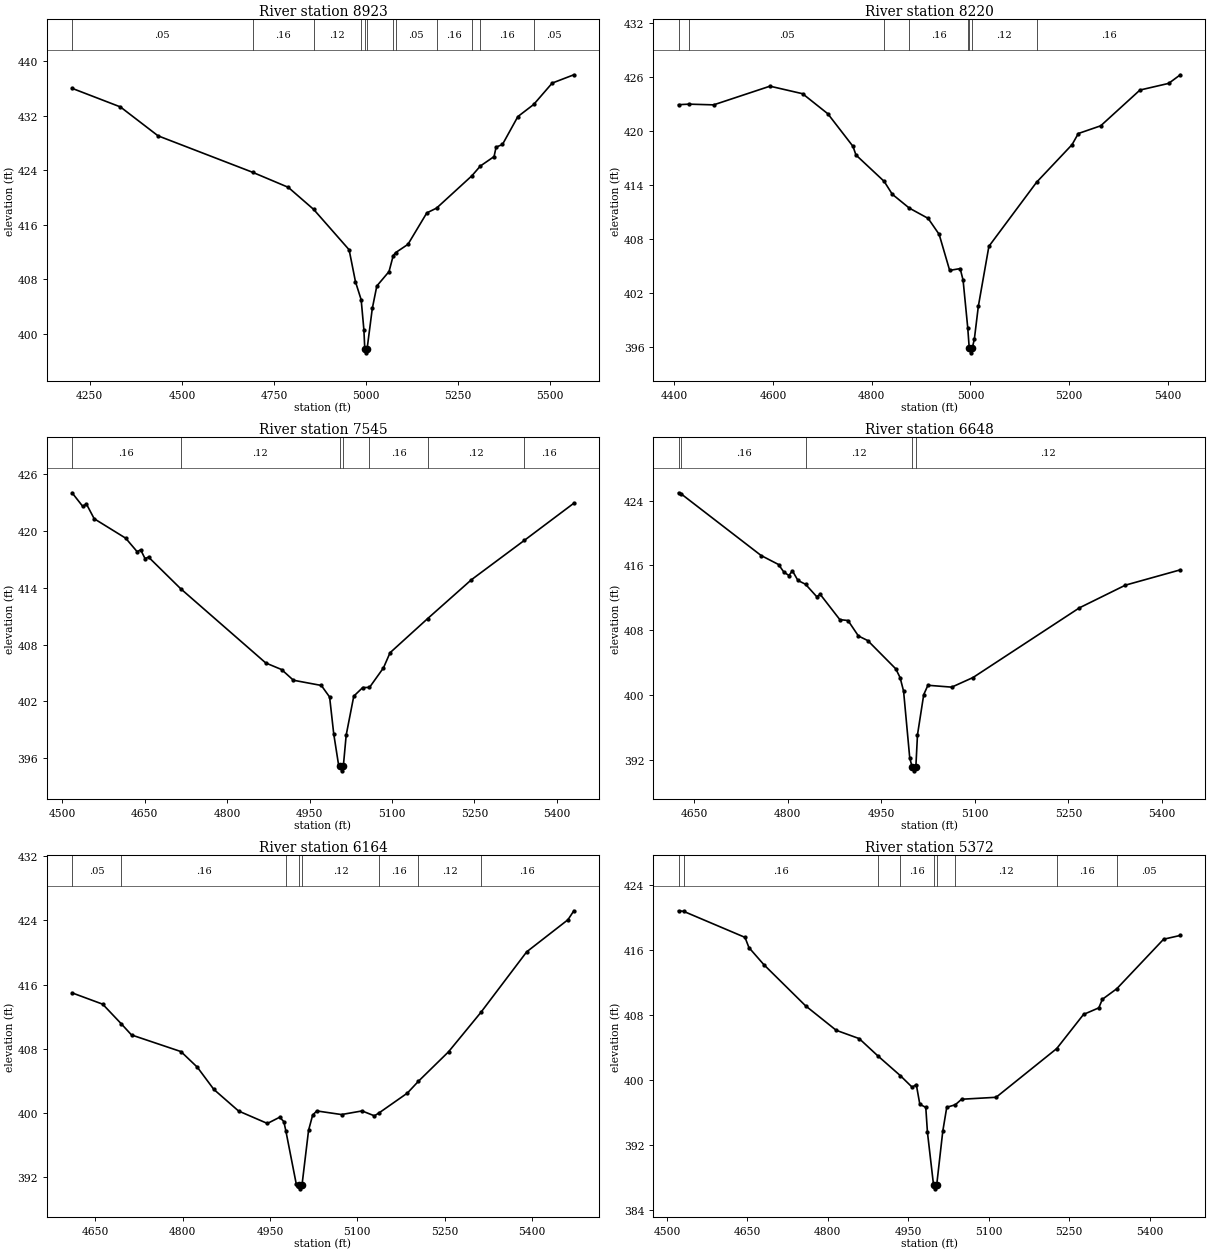
Type RM Length L Ch R = 1,8923,703,703,703
BEGIN DESCRIPTION:
CRAZY BRANCH 15.0
END DESCRIPTION:
XS GIS Cut Line= 3
      3526910.96     10344908.71      3525841.12     10345410.59
      3525741.11     10345560.60
#Sta/Elev= 30
  4201.9  436.03  4333.0  433.30  4435.3  429.05  4691.7  423.70  4788.6  421.49
  4857.7  418.24  4953.9  412.31  4971.2  407.60  4986.6  404.97  4994.0  400.54
  4996.5  397.67  4999.3  397.17  5002.5  397.67  5016.8  403.69  5029.1  406.99
  5062.2  409.11  5073.7  411.47  5080.1  411.89  5113.6  413.11  5164.8  417.73
  5191.2  418.43  5286.9  423.17  5310.2  424.62  5347.3  426.00  5352.8  427.39
  5370.1  427.78  5411.9  431.88  5454.9  433.66  5505.1  436.80  5563.9  438.02
#Mann=12,-1,0
  4201.9    0.05       0  4691.7    0.16       0  4857.7    0.12       0
  4986.6    0.16       0  4996.5    0.07       0  5002.5    0.16       0
  5073.7    0.12       0  5080.1    0.05       0  5191.2    0.16       0
  5286.9    0.05       0  5310.2    0.16       0  5454.9    0.05       0
Bank Sta=4996.5,5002.5
Exp/Cntr=0.3,0.1

Type RM Length L Ch R = 1,8220,675,675,675
BEGIN DESCRIPTION:
CRAZY BRANCH 14.0
END DESCRIPTION:
XS GIS Cut Line= 3
      3526336.26     10344357.19      3526036.29     10344557.17
      3525475.50     10344898.09
#Sta/Elev= 30
  4408.4  422.94  4429.7  423.00  4479.5  422.92  4593.7  425.00  4659.8  424.16
  4710.9  421.93  4761.9  418.30  4767.9  417.34  4825.1  414.40  4841.5  412.97
  4875.9  411.43  4914.2  410.28  4936.5  408.50  4957.8  404.49  4979.1  404.69
  4985.0  403.40  4994.4  398.12  4997.5  395.81  5000.2  395.31  5003.5  395.81
  5007.9  396.86  5015.9  400.49  5037.3  407.17  5134.0  414.31  5205.8  418.49
  5218.5  419.73  5263.9  420.59  5343.4  424.57  5401.5  425.31  5425.2  426.27
#Mann=8,-1,0
  4408.4     0.1       0  4429.7    0.05       0  4825.1    0.12       0
  4875.9    0.16       0  4994.4    0.12       0  4997.5    0.07       0
  5003.5    0.12       0  5134.0    0.16       0
Bank Sta=4997.5,5003.5
Exp/Cntr=0.3,0.1

Type RM Length L Ch R = 1,7545,897,897,897
BEGIN DESCRIPTION:
CRAZY BRANCH 12.0
END DESCRIPTION:
XS GIS Cut Line= 3
      3525878.03     10343820.77      3525578.03     10344070.77
      3525115.90     10344315.85
#Sta/Elev= 30
  4517.5  424.01  4537.0  422.57  4543.5  422.84  4557.8  421.27  4615.1  419.22
  4635.9  417.80  4642.4  417.99  4650.3  417.07  4656.8  417.22  4715.2  413.89
  4870.2  406.05  4898.9  405.36  4920.5  404.23  4971.3  403.68  4986.4  402.46
  4993.9  398.57  5002.8  395.27  5005.4  395.17  5008.2  394.67  5011.4  395.17
  5016.6  398.45  5030.4  402.55  5046.7  403.46  5059.0  403.47  5084.5  405.54
  5096.4  407.13  5164.8  410.73  5244.7  414.84  5341.0  418.99  5431.1  422.91
#Mann=7,-1,0
  4517.5    0.16       0  4715.2    0.12       0  5005.4    0.07       0
  5011.4    0.12       0  5059.0    0.16       0  5164.8    0.12       0
  5341.0    0.16       0
Bank Sta=5005.4,5011.4
Exp/Cntr=0.3,0.1

Type RM Length L Ch R = 1,6648,484,484,484
BEGIN DESCRIPTION:
CRAZY BRANCH 10.0
END DESCRIPTION:
XS GIS Cut Line= 3
      3525512.81     10343345.56      3525054.72     10343577.57
      3524905.00     10343827.11
#Sta/Elev= 30
  4624.8  424.98  4629.4  424.82  4757.2  417.23  4785.1  416.12  4793.7  415.18
  4801.8  414.76  4807.4  415.34  4816.2  414.15  4828.4  413.68  4846.3  412.15
  4852.0  412.43  4883.4  409.31  4896.5  409.20  4913.2  407.29  4928.2  406.72
  4973.1  403.23  4980.0  402.15  4985.6  400.48  4995.5  392.21  4999.3  391.13
  5002.0  390.63  5005.3  391.13  5007.9  395.08  5017.9  400.04  5024.6  401.20
  5062.8  400.97  5097.0  402.16  5267.6  410.77  5341.3  413.57  5429.3  415.46
#Mann=5,-1,0
  4624.8    0.05       0  4629.4    0.16       0  4828.4    0.12       0
  4999.3    0.07       0  5005.3    0.12       0
Bank Sta=4999.3,5005.3
Exp/Cntr=0.3,0.1

Type RM Length L Ch R = 1,6164,792,792,792
BEGIN DESCRIPTION:
CRAZY BRANCH 9.0
END DESCRIPTION:
XS GIS Cut Line= 3
      3525134.13     10342889.25      3524772.69     10343248.44
      3524523.56     10343497.57
#Sta/Elev= 30
  4610.1  414.97  4662.7  413.56  4694.6  411.12  4712.2  409.73  4797.1  407.66
  4825.3  405.71  4853.6  402.95  4896.1  400.26  4945.6  398.71  4966.8  399.49
  4973.9  398.93  4977.3  397.79  4995.1  391.20  4999.1  391.07  5001.9  390.57
  5005.1  391.07  5016.3  397.85  5023.3  399.74  5030.4  400.27  5072.9  399.82
  5108.2  400.27  5129.4  399.66  5137.7  400.04  5186.0  402.49  5205.1  403.97
  5256.7  407.63  5312.2  412.53  5391.0  420.08  5461.8  424.07  5472.0  425.19
#Mann=8,-1,0
  4610.1    0.05       0  4694.6    0.16       0  4977.3    0.12       0
  4999.1    0.07       0  5005.1    0.12       0  5137.7    0.16       0
  5205.1    0.12       0  5312.2    0.16       0
Bank Sta=4999.1,5005.1
Exp/Cntr=0.3,0.1

Type RM Length L Ch R = 1,5372,779,779,779
BEGIN DESCRIPTION:
CRAZY BRANCH 8.0
END DESCRIPTION:
XS GIS Cut Line= 3
      3524951.82     10342426.58      3524601.81     10342726.59
      3524240.93     10343034.85
#Sta/Elev= 30
  4521.6  420.79  4531.1  420.72  4645.5  417.52  4652.9  416.26  4680.6  414.17
  4758.5  409.10  4815.6  406.09  4858.4  405.07  4893.3  402.94  4935.2  400.51
  4957.2  399.09  4964.9  399.42  4971.5  396.99  4982.6  396.61  4985.7  393.54
  4997.0  387.09  4999.7  386.59  5003.0  387.09  5014.3  393.68  5021.7  396.62
  5037.6  396.93  5049.4  397.61  5113.7  397.85  5226.7  403.84  5276.7  408.04
  5305.2  408.85  5311.8  409.90  5338.7  411.20  5426.0  417.29  5457.2  417.76
#Mann=9,-1,0
  4521.6     0.1       0  4531.1    0.16       0  4893.3    0.12       0
  4935.2    0.16       0  4997.0    0.07       0  5003.0    0.16       0
  5037.6    0.12       0  5226.7    0.16       0  5338.7    0.05       0
Bank Sta=4997,5003
Exp/Cntr=0.3,0.1

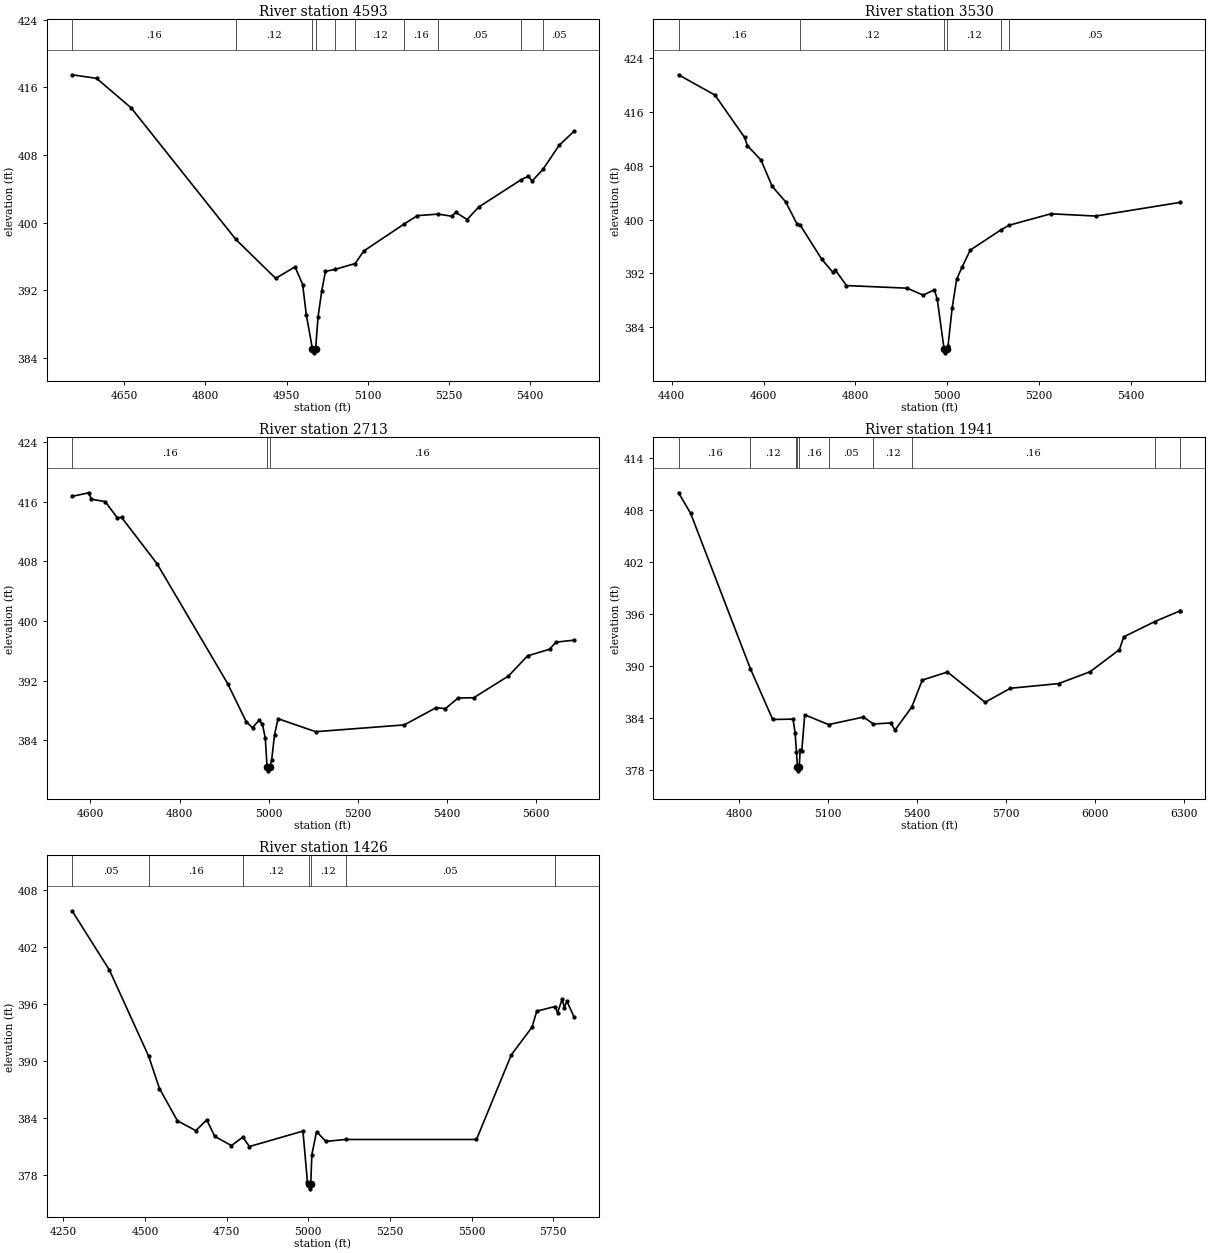
Type RM Length L Ch R = 1,4593,1063,1063,1063
BEGIN DESCRIPTION:
CRAZY BRANCH 6.0
END DESCRIPTION:
XS GIS Cut Line= 3
      3524361.52     10342150.69      3524111.55     10342300.67
      3523682.73     10342771.16
#Sta/Elev= 30
  4553.3  417.48  4598.6  417.06  4662.7  413.56  4856.2  398.02  4929.9  393.41
  4965.7  394.78  4979.8  392.68  4986.6  389.07  4997.8  385.11  5000.5  384.61
  5003.8  385.11  5008.2  388.81  5015.0  391.90  5022.0  394.24  5039.8  394.48
  5077.0  395.17  5092.7  396.64  5168.0  399.86  5192.0  400.83  5230.3  401.01
  5255.5  400.76  5262.9  401.23  5283.9  400.37  5305.5  401.85  5383.6  405.06
  5397.4  405.49  5404.2  404.91  5424.5  406.32  5454.1  409.14  5481.4  410.78
#Mann=10,-1,0
  4553.3    0.16       0  4856.2    0.12       0  4997.8    0.07       0
  5003.8    0.12       0  5039.8    0.16       0  5077.0    0.12       0
  5168.0    0.16       0  5230.3    0.05       0  5383.6     0.1       0
  5424.5    0.05       0
Bank Sta=4997.8,5003.8
Exp/Cntr=0.3,0.1

Type RM Length L Ch R = 1,3530,817,817,817
BEGIN DESCRIPTION:
CRAZY BRANCH 4.0
END DESCRIPTION:
XS GIS Cut Line= 3
      3523925.82     10341851.00      3523118.51     10342172.19
      3523127.13     10342396.17
#Sta/Elev= 30
  4414.7  421.55  4494.0  418.53  4558.6  412.23  4564.6  411.01  4594.3  408.87
  4618.6  404.96  4648.2  402.63  4672.5  399.38  4679.8  399.18  4726.5  394.12
  4750.8  392.17  4756.1  392.52  4780.4  390.19  4912.6  389.80  4947.7  388.76
  4972.0  389.56  4978.3  388.12  4993.3  380.68  4996.0  380.18  4999.3  380.68
  5001.6  381.14  5010.6  386.80  5020.5  391.12  5032.1  392.91  5050.2  395.47
  5118.0  398.52  5135.1  399.17  5225.9  400.87  5323.0  400.53  5507.7  402.57
#Mann=6,-1,0
  4414.7    0.16       0  4679.8    0.12       0  4993.3    0.07       0
  4999.3    0.12       0  5118.0     0.1       0  5135.1    0.05       0
Bank Sta=4993.3,4999.3
Exp/Cntr=0.3,0.1

Type RM Length L Ch R = 1,2713,772,772,772
BEGIN DESCRIPTION:
CRAZY BRANCH 3.0
END DESCRIPTION:
XS GIS Cut Line= 3
      3523498.34     10341206.93      3523248.36     10341356.92
      3522711.35     10341997.60
#Sta/Elev= 30
  4558.6  416.72  4596.0  417.20  4601.8  416.34  4632.9  416.02  4660.1  413.86
  4669.8  413.90  4749.5  407.69  4908.2  391.61  4949.8  386.51  4964.1  385.68
  4978.4  386.68  4986.2  386.18  4992.7  384.33  4996.8  380.41  4999.6  379.91
  5002.8  380.41  5007.0  381.32  5013.6  384.77  5021.4  386.90  5105.9  385.16
  5305.0  386.07  5376.5  388.38  5397.4  388.25  5426.0  389.68  5461.1  389.71
  5539.2  392.63  5582.1  395.33  5631.6  396.22  5645.9  397.17  5686.1  397.43
#Mann=3,-1,0
  4558.6    0.16       0  4996.8    0.07       0  5002.8    0.16       0
Bank Sta=4996.8,5002.8
Exp/Cntr=0.3,0.1

Type RM Length L Ch R = 1,1941,515,515,515
BEGIN DESCRIPTION:
CRAZY BRANCH 2.0
END DESCRIPTION:
XS GIS Cut Line= 3
      3523296.31     10340821.84      3522814.69     10341017.67
      3522017.54     10341877.08
#Sta/Elev= 30
  4595.7  410.03  4636.5  407.65  4837.9  389.69  4913.3  383.81  4981.8  383.85
  4988.9  382.25  4993.3  380.06  4996.7  378.37  4999.4  377.87  5002.7  378.37
  5005.9  380.24  5011.3  380.18  5021.2  384.35  5101.7  383.22  5219.2  384.09
  5253.0  383.29  5311.5  383.41  5325.6  382.58  5382.2  385.25  5417.6  388.37
  5502.6  389.30  5629.6  385.80  5714.6  387.42  5877.4  387.96  5983.4  389.33
  6082.6  391.89  6096.8  393.36  6202.0  395.14  6286.5  396.37  6287.8  396.35
#Mann=10,-1,0
  4595.7    0.16       0  4837.9    0.12       0  4993.3    0.16       0
  4996.7    0.07       0  5002.7    0.16       0  5101.7    0.05       0
  5253.0    0.12       0  5382.2    0.16       0  6202.0    0.05       0
  6286.5    0.16       0
Bank Sta=4996.7,5002.7
Exp/Cntr=0.3,0.1

Type RM Length L Ch R = 1,1426,0,0,0
BEGIN DESCRIPTION:
CRAZY BRANCH 1.0
END DESCRIPTION:
XS GIS Cut Line= 3
      3523242.08     10340641.64      3522771.29     10340505.52
      3522094.19     10341304.15
#Sta/Elev= 30
  4276.3  405.77  4390.8  399.53  4511.1  390.46  4544.0  387.08  4599.0  383.69
  4655.3  382.65  4688.9  383.78  4713.5  382.04  4764.4  381.08  4799.3  381.96
  4819.8  380.98  4983.5  382.60  4997.3  377.25  5001.3  377.03  5004.1  376.53
  5007.3  377.03  5010.9  380.14  5025.2  382.55  5053.7  381.52  5114.0  381.72
  5515.1  381.72  5621.7  390.61  5685.4  393.54  5699.7  395.21  5755.0  395.70
  5763.4  395.05  5777.7  396.48  5784.2  395.58  5791.9  396.27  5813.4  394.65
#Mann=7,-1,0
  4276.3    0.05       0  4511.1    0.16       0  4799.3    0.12       0
  5001.3    0.07       0  5007.3    0.12       0  5114.0    0.05       0
  5755.0    0.16       0
Bank Sta=5001.3,5007.3
Exp/Cntr=0.3,0.1

Chan Stop Cuts=-1