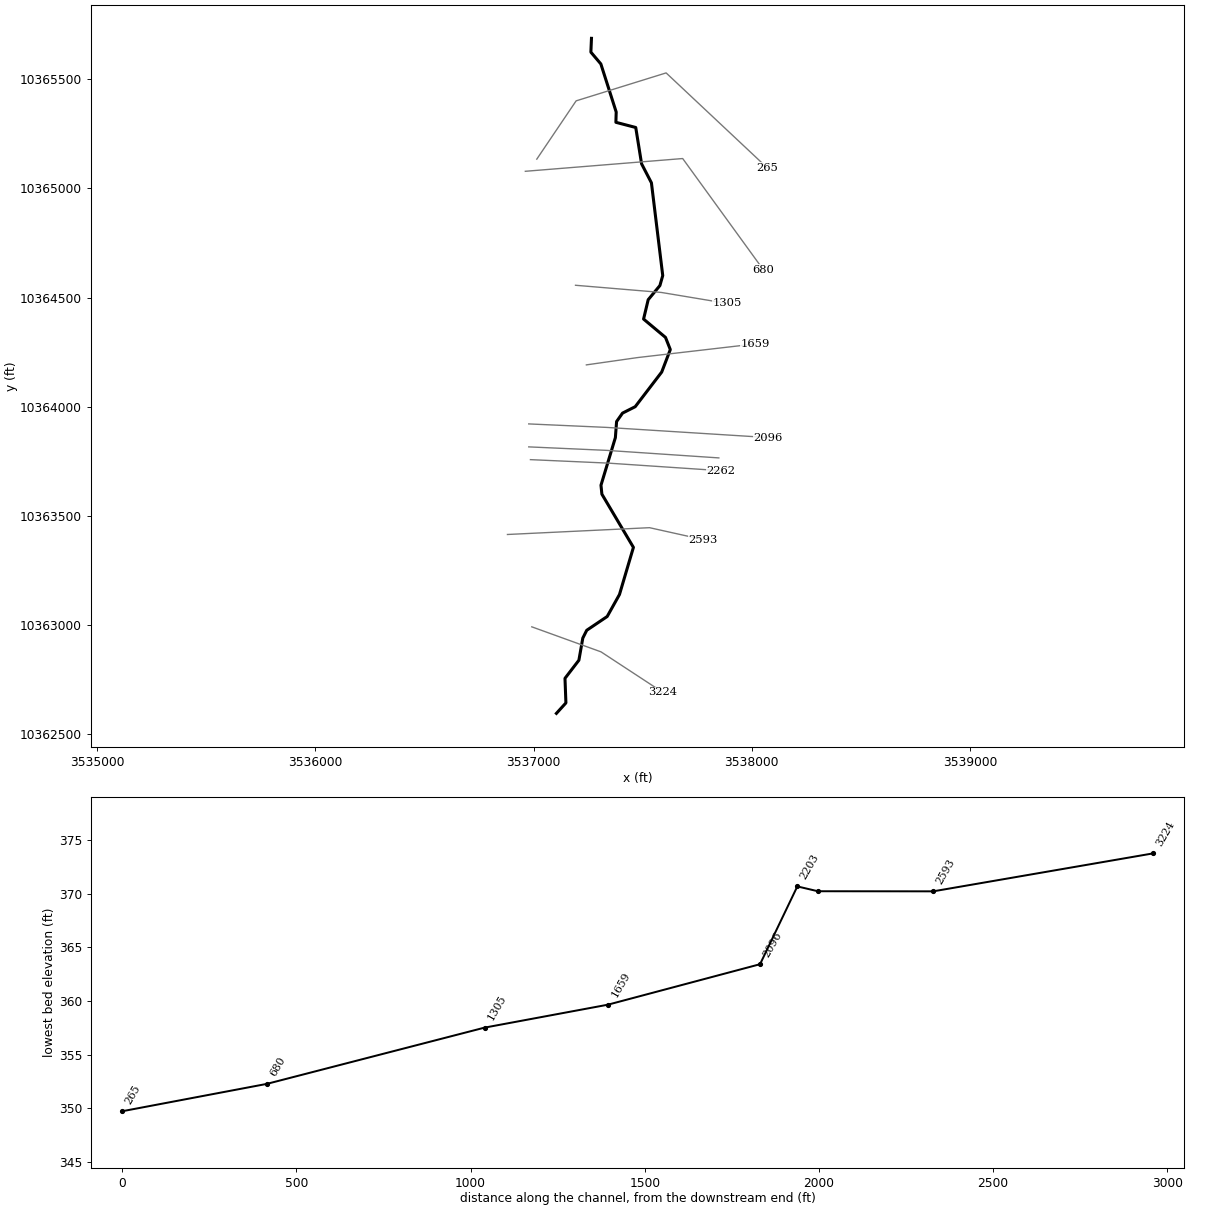
--- DEEP BRANCH.prj (project) ---

Proj Title=DEEP BRANCH Base Level Engineering
Current Plan=p01
Default Exp/Contr=0.3,0.1
English Units
Geom File=g01
Flow File=f01
Plan File=p01
Y Axis Title=Elevation
X Axis Title(PF)=Main Channel Distance
X Axis Title(XS)=Station
BEGIN DESCRIPTION:
DEEP BRANCH
END DESCRIPTION:
DSS Export Rating Curves= 0
DSS Export Rating Curve Sorted= 0
DSS Export Volume Flow Curves= 0
DXF OffsetX= 0
DXF OffsetY= 0
DXF ScaleX= 1
DXF ScaleY= 10

--- DEEP BRANCH.p01 (plan) ---

Plan Title=Multiple Run
Short Identifier=Multiple
Geom File=g01
Flow File=f01
Subcritical Flow
K Sum by GR= 0
Std Step Tol= 0.01
Critical Tol= 0.01
Num of Std Step Trials= 20
Max Error Tol= 0.3
Flow Tol Ratio= 0.001
Split Flow NTrial= 30
Split Flow Tol= 0.02
Split Flow Ratio= 0.02
Log Output Level= 0
Friction Slope Method= 1
Unsteady Friction Slope Method= 2
Unsteady Bridges Friction Slope Method= 1
Parabolic Critical Depth
Global Vel Dist=  1 , 1 , 1
Global Log Level= 0
CheckData=True
Encroach Param= -1, 0, 0, 0
BEGIN DESCRIPTION:
Multiple Run
END DESCRIPTION:

--- DEEP BRANCH.f01 (steady flow) ---

Flow Title=Multiple
Program Version=4.10
Number of Profiles= 7
Profile Names=10-year,25-year,50-year,1pct_min,100-year,1pct_plu,500-year
River Rch & RM=DEEP BRANCH,Reach-1         ,3224
     866    1199    1476    1329    1798    2431    2657
Boundary for River Rch & Prof#=DEEP BRANCH,Reach-1         , 1
Up Type= 0
Dn Type= 3
Dn Slope=0.00845
Boundary for River Rch & Prof#=DEEP BRANCH,Reach-1         , 2
Up Type= 0
Dn Type= 3
Dn Slope=0.00845
Boundary for River Rch & Prof#=DEEP BRANCH,Reach-1         , 3
Up Type= 0
Dn Type= 3
Dn Slope=0.00845
Boundary for River Rch & Prof#=DEEP BRANCH,Reach-1         , 4
Up Type= 0
Dn Type= 3
Dn Slope=0.00845
Boundary for River Rch & Prof#=DEEP BRANCH,Reach-1         , 5
Up Type= 0
Dn Type= 3
Dn Slope=0.00845
Boundary for River Rch & Prof#=DEEP BRANCH,Reach-1         , 6
Up Type= 0
Dn Type= 3
Dn Slope=0.00845
Boundary for River Rch & Prof#=DEEP BRANCH,Reach-1         , 7
Up Type= 0
Dn Type= 3
Dn Slope=0.00845
DSS Import GetInterval= 0
DSS Import GetPeak= 0
DSS Import FillOption= 0

--- DEEP BRANCH.g01 (geometry) ---

Geom Title=Existing Conditions
Program Version=4.10

River Reach=DEEP BRANCH     ,Reach-1
Reach XY= 30
       3537104.9     10362595.17      3537148.42     10362643.09
      3537144.18     10362755.71      3537207.89     10362838.67
      3537225.81     10362940.11      3537243.78      10362975.8
      3537337.53     10363038.99      3537393.78     10363139.68
      3537457.67     10363355.66      3537313.22     10363599.41
      3537309.06     10363640.38      3537375.03     10363858.43
      3537380.58     10363932.05      3537407.84     10363970.76
      3537465.89     10364000.13      3537587.31     10364158.88
       3537626.7     10364261.74      3537604.61     10364317.58
      3537504.23     10364401.52      3537525.37     10364490.28
      3537578.99       10364555.      3537592.01     10364600.83
      3537540.19     10365025.67      3537495.06     10365112.82
      3537468.33     10365279.18      3537377.37      10365302.9
      3537378.77     10365350.14      3537308.51     10365570.23
      3537262.78     10365624.34      3537265.52     10365687.62

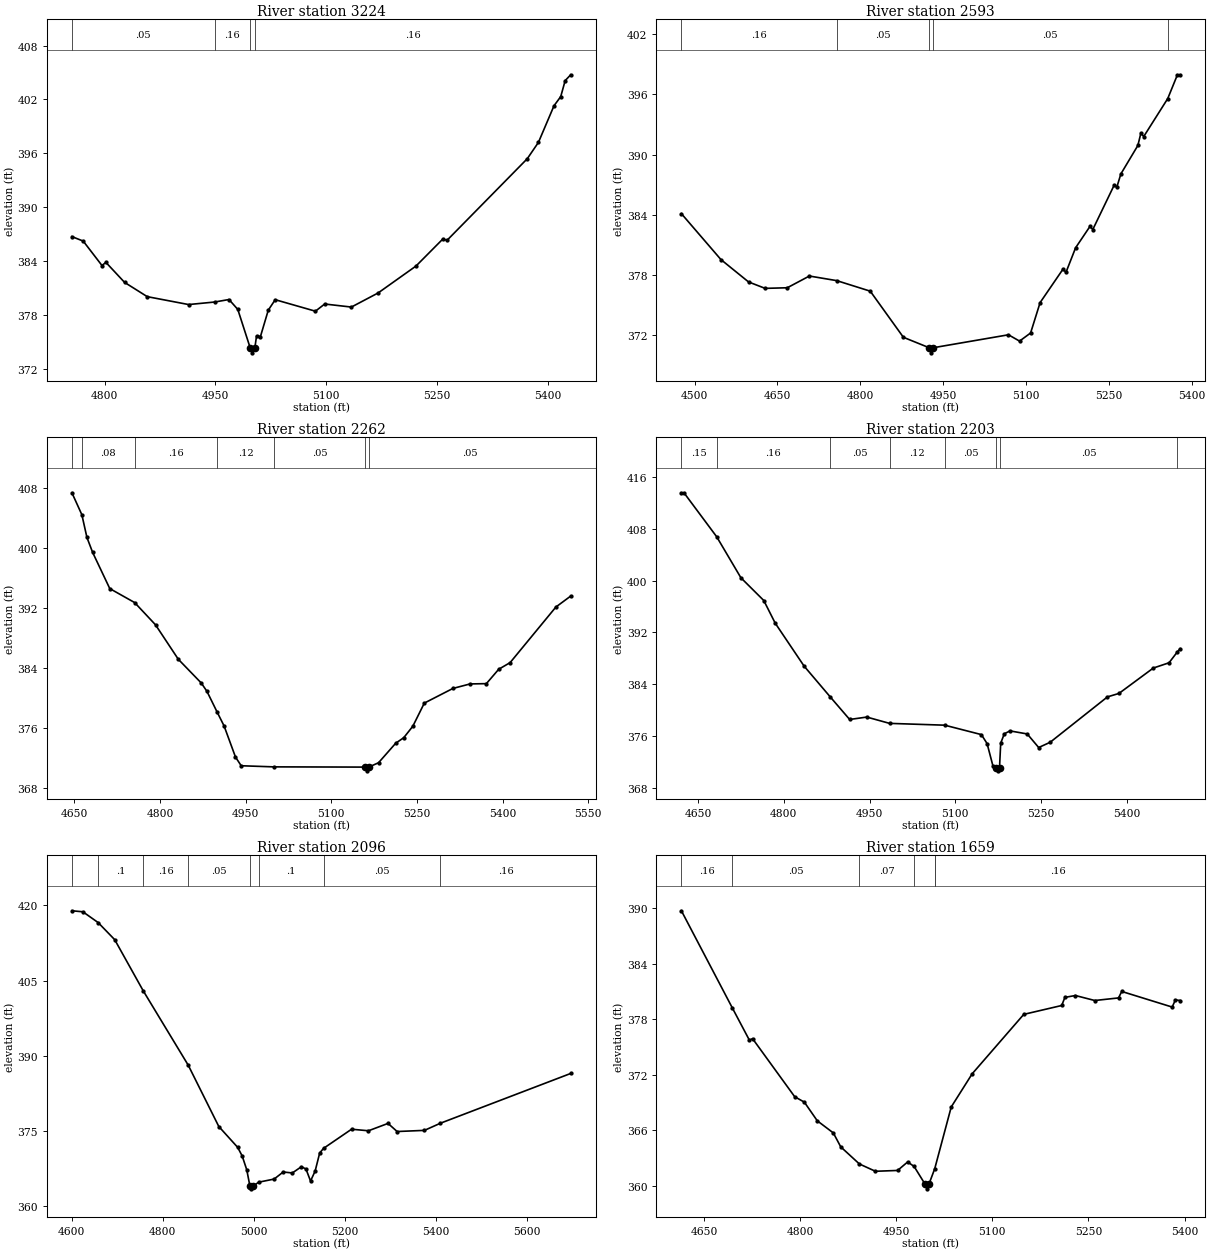
Type RM Length L Ch R = 1 ,3224    ,631,631,631
BEGIN DESCRIPTION:
DEEP BRANCH 7.0
END DESCRIPTION:
XS GIS Cut Line= 3
      3536992.09     10362991.65       3537309.3     10362876.96
      3537592.09     10362691.65
#Sta/Elev= 30
  4755.6  386.72  4770.9  386.22  4796.3   383.5  4801.6  383.85  4826.9  381.62
  4857.6  380.03  4913.6  379.15  4948.7  379.43  4968.3  379.71  4980.2  378.61
  4997.2  374.27  4999.9  373.77  5003.2  374.27  5005.6  375.65  5010.9  375.59
  5021.5  378.53  5030.9  379.69  5085.3  378.41  5097.9  379.21    5134  378.87
  5170.2  380.44  5221.5  383.44  5257.7  386.44  5263.7  386.32  5372.2   395.4
  5387.3  397.22  5408.4   401.3  5417.5  402.32  5423.5   404.1    5431  404.75
#Mann= 4 ,-1 , 0
  4755.6     .05       0  4948.7     .16       0  4997.2     .07       0
  5003.2     .16       0
Bank Sta=4997.2,5003.2
XS Rating Curve= 0 ,0
Exp/Cntr=0.3,0.1

Type RM Length L Ch R = 1 ,2593    ,331,331,331
BEGIN DESCRIPTION:
DEEP BRANCH 6.0
END DESCRIPTION:
XS GIS Cut Line= 3
      3536880.63     10363414.68      3537531.41     10363445.86
       3537776.9      10363391.3
#Sta/Elev= 30
  4476.2  384.11  4547.8  379.53  4597.8   377.3  4627.8  376.66  4667.9  376.72
  4707.9  377.89  4757.5  377.43  4818.1  376.38  4878.1  371.78  4925.2  370.73
  4927.9  370.23  4931.2  370.73  5068.3  372.03  5088.4   371.4  5108.4  372.21
  5125.6  375.24  5167.2  378.59  5172.4  378.25  5189.9  380.71  5215.9  382.84
    5221  382.53  5259.4  386.92  5264.6  386.77  5271.8  388.07  5302.6  390.91
  5308.1  392.15  5313.2   391.8  5356.7  395.59  5374.2  397.96  5379.2  397.96
#Mann= 5 ,-1 , 0
  4476.2     .16       0  4757.5     .05       0  4925.2    .033       0
  4931.2     .05       0  5356.7     .16       0
Bank Sta=4925.2,4931.2
XS Rating Curve= 0 ,0
Exp/Cntr=0.3,0.1

Type RM Length L Ch R = 1 ,2262    ,59,59,59
BEGIN DESCRIPTION:
DEEP BRANCH 5.2
END DESCRIPTION:
XS GIS Cut Line= 3
      3536985.88     10363757.58      3537342.11     10363741.64
      3537857.96     10363706.98
#Sta/Elev= 30
  4645.8  407.39  4663.2  404.46  4672.1  401.42  4682.1  399.42  4712.1  394.59
  4755.7  392.72  4792.2  389.75  4832.2  385.14  4872.3  381.98  4882.3  380.86
  4900.2  378.08  4912.3  376.24  4932.3  372.08  4942.3  370.92  4999.3  370.77
  5159.7  370.74  5162.5  370.24  5165.7  370.74  5182.8  371.32  5212.9  373.93
    5227  374.67  5242.9   376.2    5263  379.29  5313.1  381.25  5343.1  381.85
  5371.7  381.89  5393.3  383.81  5413.3   384.7  5493.5  392.13  5519.4  393.59
#Mann= 7 ,-1 , 0
  4645.8     .15       0  4663.2     .08       0  4755.7     .16       0
  4900.2     .12       0  4999.3     .05       0  5159.7    .033       0
  5165.7     .05       0
Bank Sta=5159.7,5165.7
XS Rating Curve= 0 ,0
Exp/Cntr=0.3,0.1

Type RM Length L Ch R = 1 ,2203    ,107,107,107
BEGIN DESCRIPTION:
DEEP BRANCH 5.1
END DESCRIPTION:
XS GIS Cut Line= 3
      3536978.12     10363816.03      3537334.31     10363800.09
      3537849.01      10363765.5
#Sta/Elev= 30
  4620.8  413.51  4625.3  413.51  4682.5  406.74  4724.9  400.42  4764.9  396.92
  4784.9  393.43  4835.4  386.82  4880.6  382.13  4915.1   378.6  4945.1  378.97
  4984.9     378  5081.4  377.72  5145.5  376.27  5155.5  374.88  5165.6  371.48
  5171.2  371.19    5174  370.69  5177.2  371.19  5179.3  374.95  5185.6   376.4
  5195.6  376.84  5225.7  376.37  5245.7  374.28  5265.8  375.09    5366  382.08
  5386.1  382.61  5446.2  386.52  5473.7  387.33  5488.1  388.99  5493.2   389.5
#Mann= 8 ,-1 , 0
  4620.8     .15       0  4682.5     .16       0  4880.6     .05       0
  4984.9     .12       0  5081.4     .05       0  5171.2     .07       0
  5177.2     .05       0  5488.1     .16       0
Bank Sta=5171.2,5177.2
XS Rating Curve= 0 ,0
Exp/Cntr=0.3,0.1

Type RM Length L Ch R = 1 ,2096    ,437,437,437
BEGIN DESCRIPTION:
DEEP BRANCH 5.0
END DESCRIPTION:
XS GIS Cut Line= 3
      3536978.05     10363921.24      3537334.31      10363905.3
      3538073.04     10363858.89
#Sta/Elev= 30
  4600.3  418.93  4624.4  418.73  4657.9  416.58  4694.4  413.16    4757  402.97
    4856  388.12  4923.3  375.87  4964.7  371.72  4974.7  369.99  4984.8  367.22
  4991.8  363.93  4994.5  363.43  4997.8  363.93  5011.1  364.76  5044.9  365.38
  5064.9  366.79    5085   366.6    5105  367.85    5115  367.38    5125  364.99
  5135.1  366.97  5145.1  370.58  5153.6  371.51  5215.2  375.33  5252.4  375.02
  5295.4  376.49  5315.4  374.87  5375.5   375.1  5410.7  376.53  5697.1  386.46
#Mann= 8 ,-1 , 0
  4600.3     .15       0  4657.9      .1       0    4757     .16       0
    4856     .05       0  4991.8     .04       0  5011.1      .1       0
  5153.6     .05       0  5410.7     .16       0
Bank Sta=4991.8,4997.8
XS Rating Curve= 0 ,0
Exp/Cntr=0.3,0.1

Type RM Length L Ch R = 1 ,1659    ,354,354,354
BEGIN DESCRIPTION:
DEEP BRANCH 4.0
END DESCRIPTION:
XS GIS Cut Line= 3
      3537242.12     10364191.64      3537476.85     10364225.17
      3538014.54     10364287.51
#Sta/Elev= 30
  4614.8  389.74  4694.2  379.24  4720.9  375.74  4725.9   375.9  4791.6  369.62
  4806.7  369.03  4826.9  367.01  4851.9   365.7  4863.5  364.19  4892.6  362.34
  4917.6  361.55  4952.2  361.64  4967.9  362.56    4978  362.07  4995.1  360.15
  4997.9  359.65  5001.1  360.15  5010.2  361.84  5035.9  368.51  5068.6   372.1
  5149.1  378.53  5208.3  379.49  5213.3  380.37  5229.7  380.57  5259.9  380.03
    5297  380.31    5302  381.01  5380.7  379.32  5385.7  380.09  5393.2  380.03
#Mann= 6 ,-1 , 0
  4614.8     .16       0  4694.2     .05       0  4892.6     .07       0
    4978     .04       0  5010.2     .12       0  5010.2     .16       0
Bank Sta=4995.1,5001.1
XS Rating Curve= 0 ,0
Exp/Cntr=0.3,0.1

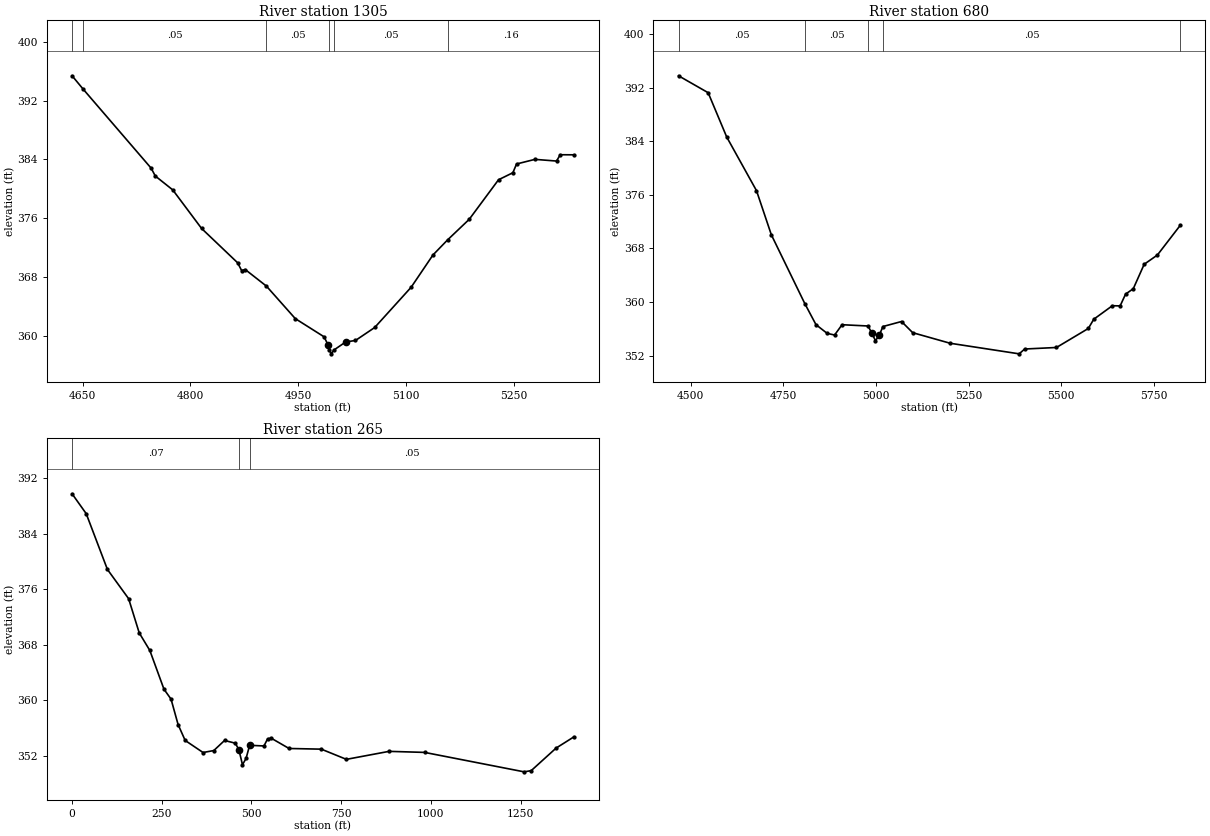
Type RM Length L Ch R = 1 ,1305    ,625,625,625
BEGIN DESCRIPTION:
DEEP BRANCH 3.0
END DESCRIPTION:
XS GIS Cut Line= 3
      3537192.42     10364556.38      3537585.62     10364523.47
      3537885.61     10364473.47
#Sta/Elev= 30
  4635.1   395.4  4650.7  393.56  4745.2  382.81    4751  381.74  4775.3  379.85
  4815.4   374.6  4865.6  369.92  4871.2  368.86  4876.2     369  4905.7  366.74
  4945.9  362.31    4986  359.83  4991.3  358.77  4993.4  358.01  4996.1  357.51
  4999.4  358.01  5016.1  359.13  5029.7  359.33  5056.5   361.1  5107.2  366.58
  5137.6  370.98  5157.9  373.03  5188.1  375.84  5228.9  381.23  5248.9  382.19
    5254  383.38  5279.6  384.01  5309.7  383.78  5314.8  384.64  5333.8  384.63
#Mann= 6 ,-1 , 0
  4635.1     .16       0  4650.7     .05       0  4905.7     .05       0
  4993.4     .03       0  4999.4     .05       0  5157.9     .16       0
Bank Sta=4991.3,5016.1
XS Rating Curve= 0 ,0
Exp/Cntr=0.3,0.1

Type RM Length L Ch R = 1 ,680     ,415,415,415
BEGIN DESCRIPTION:
DEEP BRANCH 1.0
END DESCRIPTION:
XS GIS Cut Line= 3
      3536962.49     10365078.52      3537683.37     10365136.96
      3538053.49     10364626.59
#Sta/Elev= 30
  4467.5   393.8  4547.4  391.27  4597.5  384.65  4677.8  376.64  4717.9  370.04
  4808.2  359.76  4838.3  356.62  4868.4  355.32  4888.5  355.07  4908.6  356.61
  4978.8  356.42  4988.8  355.37  4998.8  354.22  5008.9  355.03  5018.9  356.34
  5069.1  357.09  5099.2  355.42  5200.3  353.84  5386.4  352.26  5401.3  352.98
  5487.1  353.21    5573  356.05  5587.7  357.43  5637.9  359.45  5658.8  359.42
  5673.5  361.18  5694.3  361.99  5723.7  365.64  5759.3  367.02  5821.2  371.47
#Mann= 5 ,-1 , 0
  4467.5     .05       0  4808.2     .05       0  4978.8     .03       0
  5018.9     .05       0  5821.2      .1       0
Bank Sta=4988.8,5008.9
XS Rating Curve= 0 ,0
Exp/Cntr=0.3,0.1

Type RM Length L Ch R = 1 ,265     ,0,0,0
XS GIS Cut Line= 4
     3537015.062     10365134.27     3537195.184    10365401.197
      3537607.51    10365529.236      3538069.75    10365095.208
#Sta/Elev= 30
       0389.788339.40179386.924698.50448378.8826157.6072374.6676187.1585369.7343
216.7099367.2042256.1117361.6189275.8125 360.191295.5134 356.516315.2143354.2323
 365.012352.4948394.9724352.7763424.9329  354.23454.8933353.8387464.8801352.9014
474.8669350.7387484.8537351.6319494.8405353.5329534.7878353.4399544.7746354.4497
554.7614 354.565604.6954 353.075694.5767352.9784764.4844351.5088 883.342352.6599
  982.39352.51081259.724349.70871279.534349.88191348.868353.13121398.392354.7448
#Mann= 3 , 0 , 0
       0     .07       0464.8801     .03       0494.8405     .05       0
Bank Sta=464.8801,494.8405
XS Rating Curve= 0 ,0
Exp/Cntr=0.3,0.1

Chan Stop Cuts=-1
Use User Specified Reach Order=0
Composite Channel Slope=5