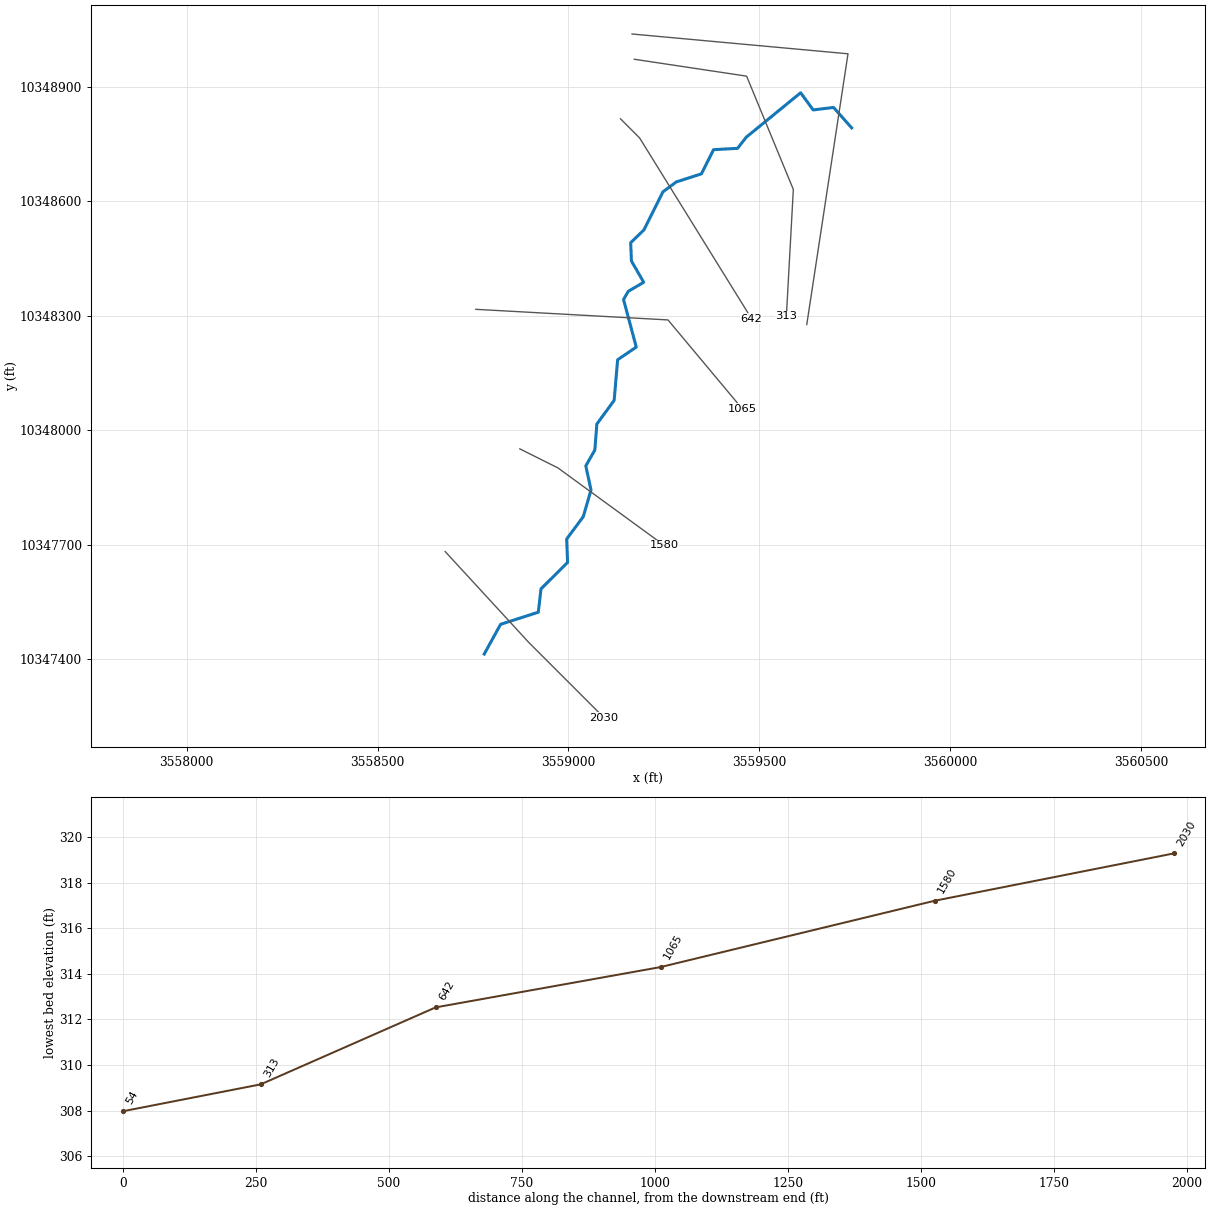
--- DEVILS JUMP CREEK TRIBUTARY 10.prj (project) ---

Proj Title=DEVILS JUMP CREEK TRIBUTARY 10 Base Level Engineering
Current Plan=p01
Default Exp/Contr=0.3,0.1
English Units
Geom File=g01
Flow File=f01
Plan File=p01
BEGIN DESCRIPTION:
DEVILS JUMP CREEK TRIBUTARY 10
END DESCRIPTION:

--- DEVILS JUMP CREEK TRIBUTARY 10.p01 (plan) ---

Plan Title=Multiple Run
Short Identifier=Multiple
Geom File=g01
Flow File=f01
Subcritical Flow
K Sum by GR= 0
Std Step Tol= 0.01
Critical Tol= 0.01
Num of Std Step Trials= 20
Max Error Tol= 0.3
Flow Tol Ratio= 0.001
Split Flow NTrial= 30
Split Flow Tol= 0.02
Split Flow Ratio= 0.02
Log Output Level= 0
Friction Slope Method= 1
Unsteady Friction Slope Method= 2
Unsteady Bridges Friction Slope Method= 1
Parabolic Critical Depth
Global Vel Dist=  1 , 1 , 1
Global Log Level= 0
CheckData=True
Encroach Param= -1, 0, 0, 0
BEGIN DESCRIPTION:
Multiple Run
END DESCRIPTION:

--- DEVILS JUMP CREEK TRIBUTARY 10.f01 (steady flow) ---

Flow Title=Multiple
Number of Profiles=7
Profile Names=10-year,25-year,50-year,1pct_min,100-year,1pct_plu,500-year
River Rch & RM= DEVILS JUMP CREE,Reach-1,2030
     461     623     756     675     913    1234    1330
Boundary for River Rch & Prof#=DEVILS JUMP CREE,Reach-1,1
Up Type=0
Dn Type=3
Dn Slope=0.005
Boundary for River Rch & Prof#=DEVILS JUMP CREE,Reach-1,2
Up Type=0
Dn Type=3
Dn Slope=0.005
Boundary for River Rch & Prof#=DEVILS JUMP CREE,Reach-1,3
Up Type=0
Dn Type=3
Dn Slope=0.005
Boundary for River Rch & Prof#=DEVILS JUMP CREE,Reach-1,4
Up Type=0
Dn Type=3
Dn Slope=0.005
Boundary for River Rch & Prof#=DEVILS JUMP CREE,Reach-1,5
Up Type=0
Dn Type=3
Dn Slope=0.005
Boundary for River Rch & Prof#=DEVILS JUMP CREE,Reach-1,6
Up Type=0
Dn Type=3
Dn Slope=0.005
Boundary for River Rch & Prof#=DEVILS JUMP CREE,Reach-1,7
Up Type=0
Dn Type=3
Dn Slope=0.005

--- DEVILS JUMP CREEK TRIBUTARY 10.g01 (geometry) ---

Geom Title=Existing Conditions

River Reach=DEVILS JUMP CREE,Reach-1
Reach XY= 30
      3558779.49     10347413.11      3558822.31     10347490.98
      3558921.10     10347522.67      3558928.24     10347583.95
      3558997.88     10347652.99      3558995.44     10347714.32
      3559038.86     10347772.94      3559059.25     10347842.88
      3559045.59     10347905.92      3559069.22     10347947.69
      3559074.51     10348015.64      3559119.81     10348077.64
      3559128.96     10348184.14      3559177.79     10348217.26
      3559144.42     10348341.86      3559156.62     10348363.17
      3559197.21     10348387.04      3559165.06     10348443.00
      3559163.19     10348490.74      3559197.78     10348524.20
      3559247.67     10348624.08      3559282.75     10348650.00
      3559348.43     10348671.17      3559380.47     10348734.57
      3559443.06     10348737.97      3559466.10     10348767.35
      3559608.46     10348883.62      3559641.25     10348838.64
      3559694.56     10348845.16      3559742.11     10348791.64

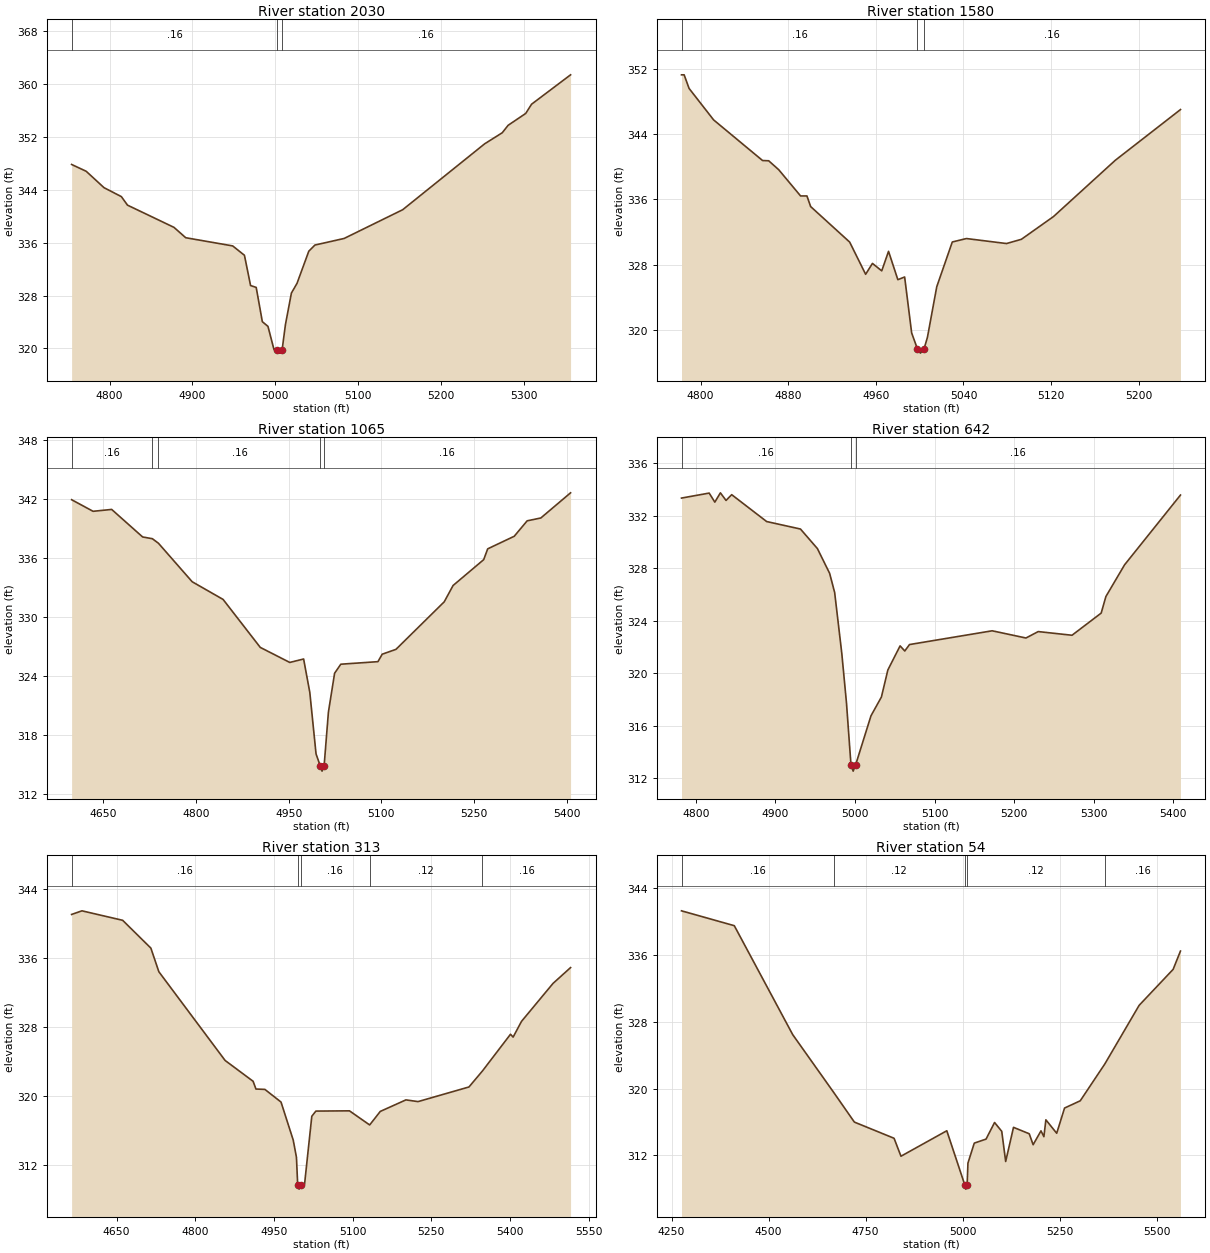
Type RM Length L Ch R = 1,2030,450,450,450
BEGIN DESCRIPTION:
DEVILS JUMP CREEK TRIBUTARY 10 13.0
END DESCRIPTION:
XS GIS Cut Line= 3
      3558677.12     10347681.66      3558895.86     10347443.82
      3559093.41     10347246.28
#Sta/Elev= 30
  4754.1  347.85  4771.7  346.82  4793.2  344.34  4814.2  342.98  4821.6  341.69
  4877.7  338.33  4891.9  336.76  4948.6  335.52  4962.8  334.10  4970.2  329.52
  4977.0  329.24  4984.4  324.05  4991.2  323.34  4998.5  319.82  5002.3  319.79
  5005.1  319.29  5008.3  319.79  5012.3  323.61  5019.5  328.38  5026.3  329.86
  5040.5  334.72  5047.9  335.65  5083.2  336.65  5153.9  341.00  5252.9  350.98
  5274.1  352.65  5281.2  353.78  5302.4  355.57  5309.5  356.97  5356.6  361.42
#Mann=3,-1,0
  4754.1    0.16       0  5002.3    0.07       0  5008.3    0.16       0
Bank Sta=5002.3,5008.3
Exp/Cntr=0.3,0.1

Type RM Length L Ch R = 1,1580,515,515,515
BEGIN DESCRIPTION:
DEVILS JUMP CREEK TRIBUTARY 10 5.0
END DESCRIPTION:
XS GIS Cut Line= 3
      3558872.70     10347950.65      3558972.66     10347900.67
      3559250.44     10347698.19
#Sta/Elev= 30
  4782.6  351.24  4785.0  351.24  4789.5  349.58  4811.9  345.73  4856.6  340.76
  4862.2  340.73  4871.4  339.63  4891.3  336.43  4897.1  336.43  4900.5  335.13
  4936.1  330.79  4950.7  326.85  4956.9  328.18  4965.4  327.27  4971.6  329.66
  4980.1  326.19  4986.3  326.52  4992.7  319.68  4998.0  317.71  5000.7  317.21
  5004.0  317.71  5007.1  319.14  5015.6  325.32  5029.8  330.80  5042.7  331.22
  5079.3  330.61  5092.9  331.13  5122.2  333.91  5178.6  340.79  5238.1  346.99
#Mann=3,-1,0
  4782.6    0.16       0  4998.0    0.07       0  5004.0    0.16       0
Bank Sta=4998,5004
Exp/Cntr=0.3,0.1

Type RM Length L Ch R = 1,1065,423,423,423
BEGIN DESCRIPTION:
DEVILS JUMP CREEK TRIBUTARY 10 4.0
END DESCRIPTION:
XS GIS Cut Line= 3
      3558757.45     10348316.22      3559260.88     10348288.44
      3559455.01     10348056.19
#Sta/Elev= 30
  4599.0  341.92  4633.7  340.74  4663.8  340.93  4713.8  338.13  4729.6  337.95
  4739.4  337.49  4794.0  333.57  4844.0  331.77  4904.1  326.89  4951.8  325.36
  4974.2  325.71  4984.2  322.31  4994.3  316.05  5001.3  314.80  5004.0  314.30
  5007.3  314.80  5014.3  320.31  5024.3  324.26  5034.3  325.18  5094.4  325.44
  5101.3  326.20  5123.5  326.69  5201.6  331.53  5215.9  333.19  5265.4  335.82
  5271.9  336.92  5314.8  338.20  5335.7  339.77  5357.8  340.06  5405.9  342.62
#Mann=5,-1,0
  4599.0    0.16       0  4729.6     0.1       0  4739.4    0.16       0
  5001.3    0.07       0  5007.3    0.16       0
Bank Sta=5001.3,5007.3
Exp/Cntr=0.3,0.1

Type RM Length L Ch R = 1,642,329,329,329
BEGIN DESCRIPTION:
DEVILS JUMP CREEK TRIBUTARY 10 3.0
END DESCRIPTION:
XS GIS Cut Line= 3
      3559136.52     10348815.28      3559186.55     10348765.25
      3559479.64     10348291.89
#Sta/Elev= 30
  4781.8  333.35  4816.6  333.73  4823.7  333.04  4830.7  333.75  4837.8  333.17
  4844.9  333.61  4888.9  331.56  4931.4  330.99  4952.7  329.50  4968.1  327.61
  4974.4  326.15  4983.4  321.50  4989.3  317.71  4994.9  313.03  4997.7  312.53
  5000.9  313.03  5020.1  316.75  5033.2  318.18  5041.3  320.24  5056.7  322.08
  5062.6  321.69  5068.5  322.18  5172.5  323.23  5215.0  322.68  5230.4  323.17
  5272.9  322.89  5309.6  324.58  5315.5  325.84  5339.0  328.26  5409.3  333.58
#Mann=3,-1,0
  4781.8    0.16       0  4994.9    0.07       0  5000.9    0.16       0
Bank Sta=4994.9,5000.9
Exp/Cntr=0.3,0.1

Type RM Length L Ch R = 1,313,259,259,259
BEGIN DESCRIPTION:
Mapping XS 58741c3a
END DESCRIPTION:
XS GIS Cut Line= 4
      3559172.65     10348971.39      3559466.89     10348927.12
      3559589.29     10348630.25      3559571.06     10348298.21
#Sta/Elev= 30
  4564.4  341.04  4584.1  341.46  4661.7  340.36  4715.5  337.13  4730.7  334.39
  4857.0  324.09  4910.4  321.67  4915.8  320.77  4932.8  320.73  4963.6  319.26
  4986.9  314.84  4993.0  312.85  4995.4  309.65  4998.1  309.15  5001.4  309.65
  5008.5  309.73  5022.3  317.61  5030.1  318.21  5094.1  318.24  5132.6  316.60
  5152.8  318.17  5201.7  319.51  5224.8  319.31  5321.9  321.01  5347.5  322.86
  5401.1  327.13  5406.1  326.80  5422.0  328.62  5482.1  333.03  5515.6  334.87
#Mann=5,-1,0
  4564.4    0.16       0  4995.4    0.07       0  5001.4    0.16       0
  5132.6    0.12       0  5347.5    0.16       0
Bank Sta=4995.4,5001.4
Exp/Cntr=0.3,0.1

Type RM Length L Ch R = 1,54,0,0,0
BEGIN DESCRIPTION:
DEVILS JUMP CREEK TRIBUTARY 10 2.0
END DESCRIPTION:
XS GIS Cut Line= 3
      3559166.71     10349037.57      3559732.52     10348985.72
      3559624.49     10348276.37
#Sta/Elev= 30
  4275.6  341.30  4411.6  339.52  4562.2  326.47  4667.8  319.55  4721.0  316.00
  4823.3  314.06  4841.1  311.91  4959.2  314.96  5005.6  308.47  5008.4  307.97
  5011.6  308.47  5013.7  311.09  5030.0  313.48  5060.3  313.96  5082.3  315.95
  5100.8  314.89  5110.9  311.28  5131.1  315.37  5171.6  314.60  5181.7  313.29
  5201.9  314.95  5209.4  314.25  5214.5  316.27  5242.4  314.66  5262.6  317.68
  5303.1  318.55  5366.4  322.96  5454.8  329.98  5542.4  334.29  5561.3  336.48
#Mann=5,-1,0
  4275.6    0.16       0  4667.8    0.12       0  5005.6    0.07       0
  5011.6    0.12       0  5366.4    0.16       0
Bank Sta=5005.6,5011.6
Exp/Cntr=0.3,0.1

Chan Stop Cuts=-1