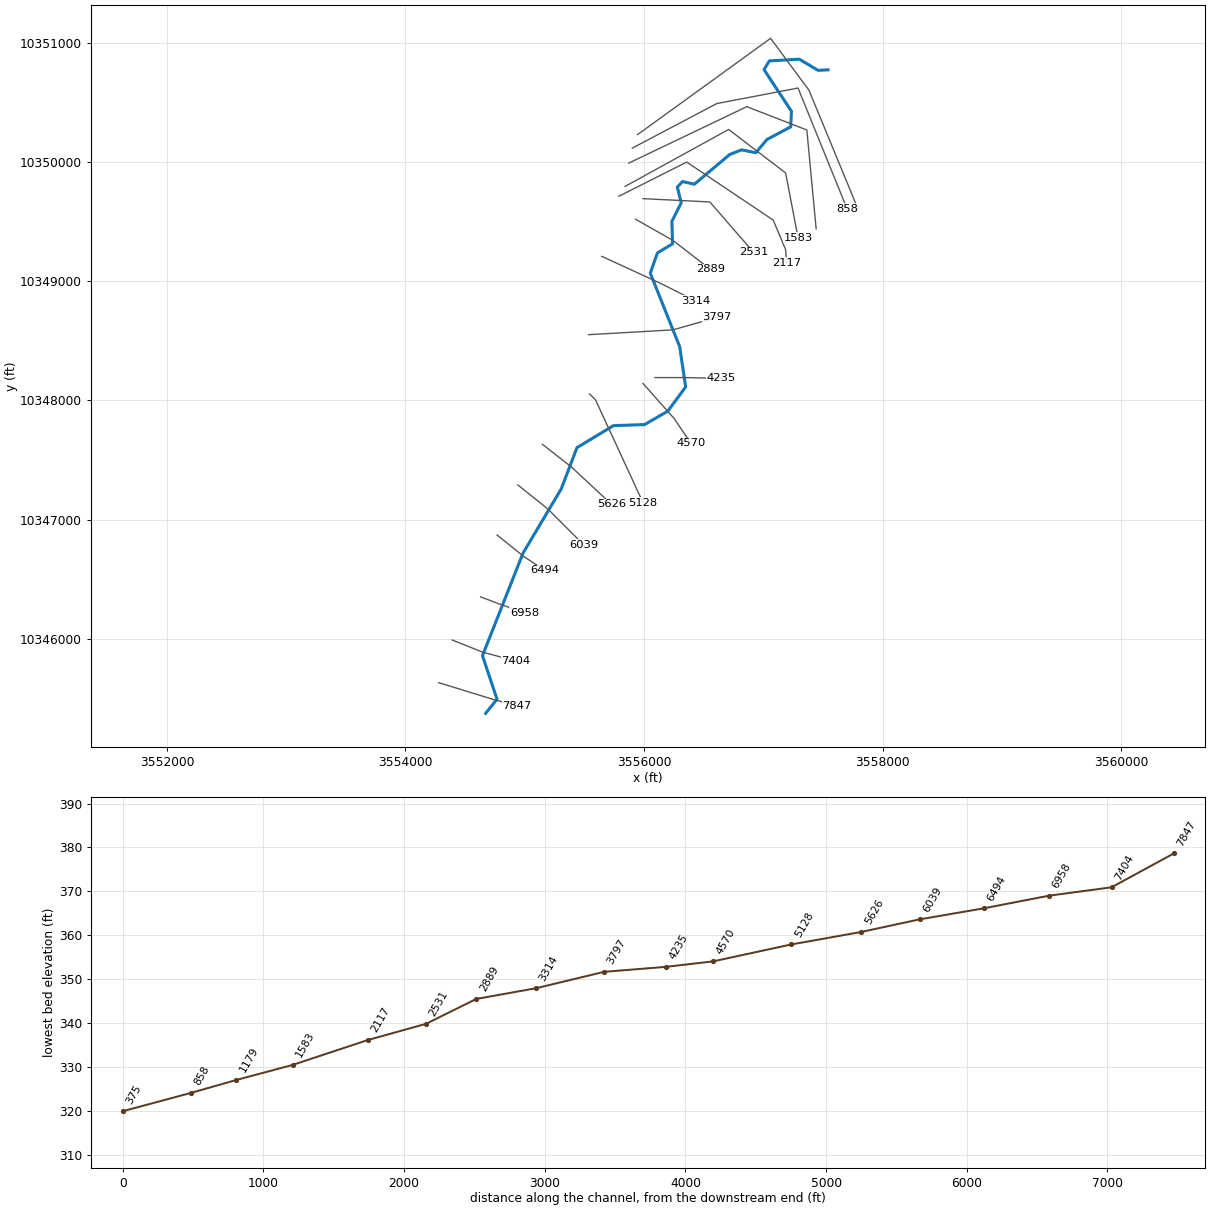
--- DEVILS JUMP CREEK TRIBUTARY 11.prj (project) ---

Proj Title=DEVILS JUMP CREEK TRIBUTARY 11 Base Level Engineering
Current Plan=p01
Default Exp/Contr=0.3,0.1
English Units
Geom File=g01
Flow File=f01
Plan File=p01
Y Axis Title=Elevation
X Axis Title(PF)=Main Channel Distance
X Axis Title(XS)=Station
BEGIN DESCRIPTION:
DEVILS JUMP CREEK TRIBUTARY 11
END DESCRIPTION:
DSS Export Rating Curves= 0
DSS Export Rating Curve Sorted= 0
DSS Export Volume Flow Curves= 0
DXF OffsetX= 0
DXF OffsetY= 0
DXF ScaleX= 1
DXF ScaleY= 10

--- DEVILS JUMP CREEK TRIBUTARY 11.p01 (plan) ---

Plan Title=Multiple Run
Short Identifier=Multiple
Geom File=g01
Flow File=f01
Subcritical Flow
K Sum by GR= 0
Std Step Tol= 0.01
Critical Tol= 0.01
Num of Std Step Trials= 20
Max Error Tol= 0.3
Flow Tol Ratio= 0.001
Split Flow NTrial= 30
Split Flow Tol= 0.02
Split Flow Ratio= 0.02
Log Output Level= 0
Friction Slope Method= 1
Unsteady Friction Slope Method= 2
Unsteady Bridges Friction Slope Method= 1
Parabolic Critical Depth
Global Vel Dist=  1 , 1 , 1
Global Log Level= 0
CheckData=True
Encroach Param= -1, 0, 0, 0
BEGIN DESCRIPTION:
Multiple Run
END DESCRIPTION:

--- DEVILS JUMP CREEK TRIBUTARY 11.f01 (steady flow) ---

Flow Title=Multiple
Number of Profiles=7
Profile Names=10-year,25-year,50-year,1pct_min,100-year,1pct_plu,500-year
River Rch & RM= DEVILS JUMP CREE,Reach-1,7847
     377     501     601     529     716     968    1017
Boundary for River Rch & Prof#=DEVILS JUMP CREE,Reach-1,1
Up Type=0
Dn Type=3
Dn Slope=0.005
Boundary for River Rch & Prof#=DEVILS JUMP CREE,Reach-1,2
Up Type=0
Dn Type=3
Dn Slope=0.005
Boundary for River Rch & Prof#=DEVILS JUMP CREE,Reach-1,3
Up Type=0
Dn Type=3
Dn Slope=0.005
Boundary for River Rch & Prof#=DEVILS JUMP CREE,Reach-1,4
Up Type=0
Dn Type=3
Dn Slope=0.005
Boundary for River Rch & Prof#=DEVILS JUMP CREE,Reach-1,5
Up Type=0
Dn Type=3
Dn Slope=0.005
Boundary for River Rch & Prof#=DEVILS JUMP CREE,Reach-1,6
Up Type=0
Dn Type=3
Dn Slope=0.005
Boundary for River Rch & Prof#=DEVILS JUMP CREE,Reach-1,7
Up Type=0
Dn Type=3
Dn Slope=0.005

--- DEVILS JUMP CREEK TRIBUTARY 11.g01 (geometry) ---

Geom Title=Existing Conditions
Program Version=4.10

River Reach=DEVILS JUMP CREE,Reach-1
Reach XY= 30
      3554672.11     10345376.64      3554767.65     10345495.99
       3554645.6     10345860.09      3554985.84     10346720.27
      3555306.49     10347259.25      3555437.65     10347604.18
      3555743.48     10347788.83       3556004.3     10347797.56
      3556198.09     10347909.33      3556349.17     10348112.86
      3556299.06     10348450.51      3556052.43     10349066.92
      3556112.16     10349236.88      3556238.86     10349312.82
      3556233.56     10349502.09      3556311.72     10349655.64
      3556279.37     10349788.43      3556322.05     10349834.84
      3556422.49     10349812.95        3556717.     10350060.74
      3556817.15     10350100.77      3556937.77     10350076.42
      3557029.73      10350186.9      3557229.58     10350293.54
      3557235.63     10350424.59      3557006.09     10350772.87
      3557049.84     10350846.36       3557301.6     10350860.85
      3557458.93     10350767.18      3557542.11     10350771.64

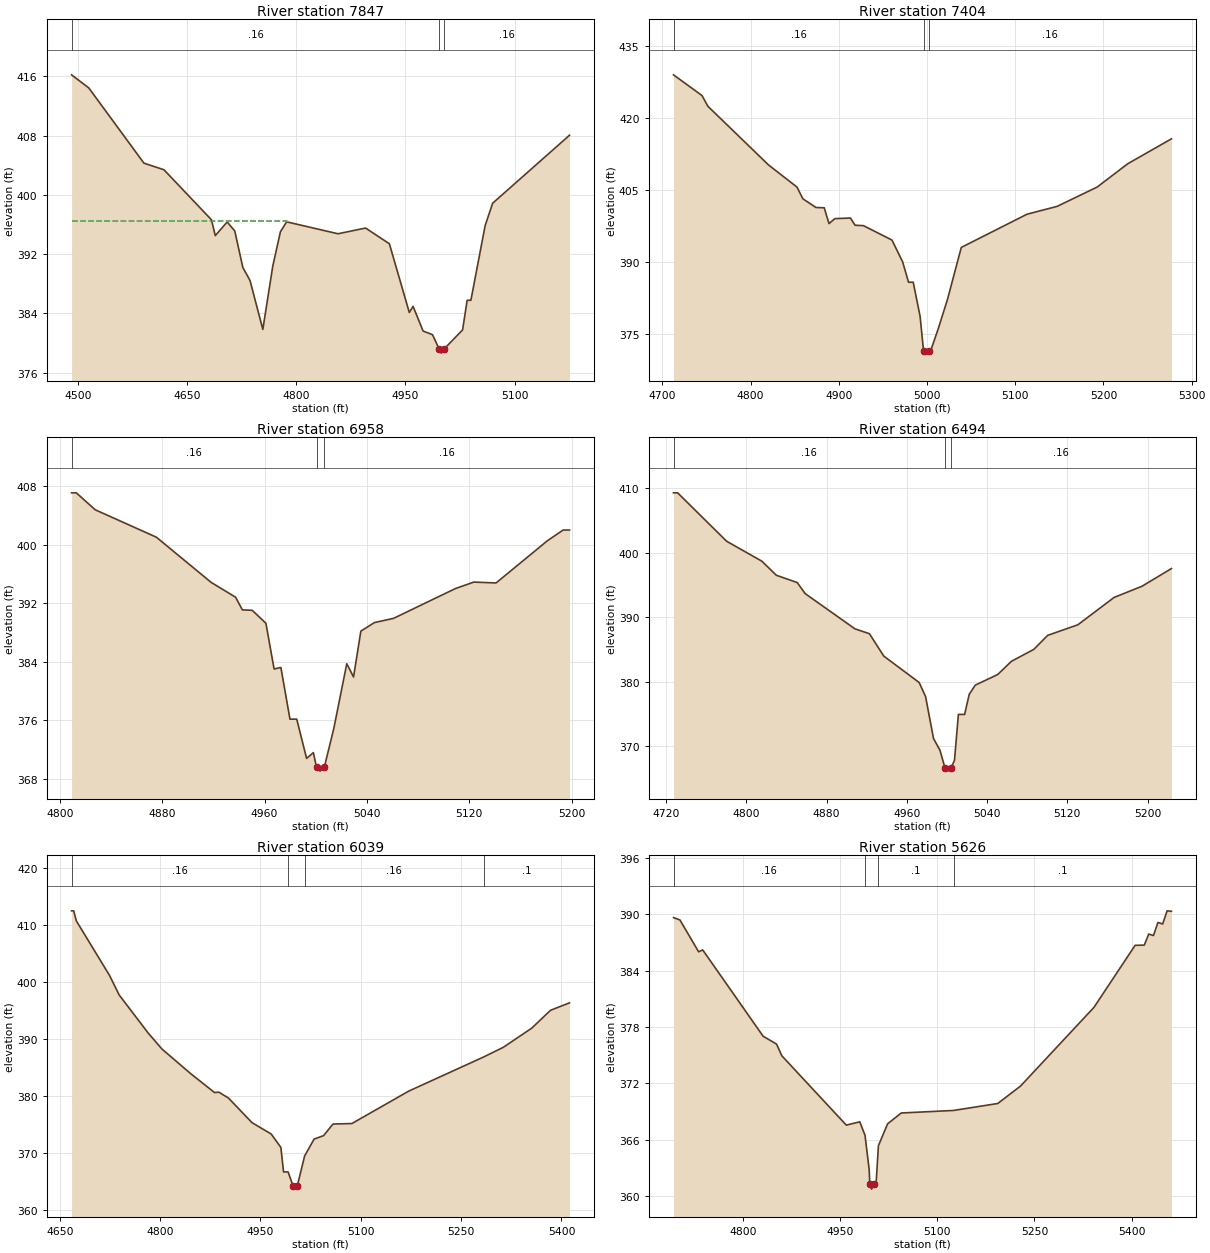
Type RM Length L Ch R = 1 ,7847    ,443,443,443
BEGIN DESCRIPTION:
DEVILS JUMP CREEK TRIBUTARY 11 15.0
END DESCRIPTION:
XS GIS Cut Line= 3
       3554277.6     10345634.57      3554742.11     10345491.64
      3554934.26     10345441.03
#Sta/Elev= 30
  4490.9  416.21  4514.6  414.44  4590.4  404.29  4617.9   403.4  4683.3  396.64
  4688.5  394.51  4704.9  396.35  4715.3  395.14  4726.4  390.21  4736.3  388.45
  4753.9  381.85  4767.6  390.41  4778.1  395.03  4786.6  396.37  4857.2  394.76
  4895.2  395.53  4927.9  393.41  4955.3  384.14  4960.5  384.96  4974.3  381.63
  4987.2  381.14  4996.6  379.15  4999.4  378.65  5002.6  379.15  5028.6  381.79
  5034.8  385.77    5040  385.79  5059.6  395.87  5069.9  398.88  5175.6  408.06
#Mann= 3 ,-1 , 0
  4490.9     .16       0  4996.6     .07       0  5002.6     .16       0
#XS Ineff= 2 , 0
         4786.82  396.47
Permanent Ineff=
       F       F
Bank Sta=4996.6,5002.6
XS Rating Curve= 0 ,0
Exp/Cntr=0.3,0.1

Type RM Length L Ch R = 1 ,7404    ,446,446,446
BEGIN DESCRIPTION:
DEVILS JUMP CREEK TRIBUTARY 11 14.0
END DESCRIPTION:
XS GIS Cut Line= 3
      3554392.15     10345991.62      3554642.11     10345891.64
      3554927.19      10345814.3
#Sta/Elev= 30
  4712.5  429.07  4744.8  424.74  4751.5   422.5  4820.2  410.25  4852.5  405.62
  4859.2  403.17    4874  401.36  4883.4  401.29  4888.8  397.99  4895.5  399.03
  4913.1  399.15  4918.4  397.65  4927.9  397.56  4960.2  394.55  4972.3     390
    4979  385.74  4984.3  385.74  4992.1  378.61    4996  371.43  4998.8  370.93
    5002  371.43  5004.2  371.49  5012.8  376.09  5023.2  382.19  5038.8  393.01
  5113.3  399.95  5147.5  401.59  5192.9  405.63  5227.6   410.5  5277.1   415.7
#Mann= 3 ,-1 , 0
  4712.5     .16       0    4996     .07       0    5002     .16       0
Bank Sta=4996,5002
XS Rating Curve= 0 ,0
Exp/Cntr=0.3,0.1

Type RM Length L Ch R = 1 ,6958    ,464,464,464
BEGIN DESCRIPTION:
DEVILS JUMP CREEK TRIBUTARY 11 13.0
END DESCRIPTION:
XS GIS Cut Line= 3
      3554630.14     10346353.36      3554792.11     10346291.64
      3554996.45     10346222.04
#Sta/Elev= 30
  4809.2  407.08  4812.9  407.08  4827.7  404.76  4875.5  401.01  4918.3  394.83
  4937.4   392.8  4942.7  391.07  4950.4  391.01  4961.1  389.24  4967.5  382.98
  4972.8  383.19  4979.9  376.12  4985.2  376.12  4992.9  370.75  4998.2  371.54
  5000.7  369.51  5003.4  369.01  5006.7  369.51  5014.2  374.87  5024.3   383.7
  5029.6  381.89  5035.3  388.16  5045.9  389.33  5060.9  389.91  5109.3  393.99
  5123.6  394.87    5141  394.75    5181  400.51  5193.4  401.99  5198.4  401.99
#Mann= 3 ,-1 , 0
  4809.2     .16       0  5000.7     .07       0  5006.7     .16       0
Bank Sta=5000.7,5006.7
XS Rating Curve= 0 ,0
Exp/Cntr=0.3,0.1

Type RM Length L Ch R = 1 ,6494    ,455,455,455
BEGIN DESCRIPTION:
DEVILS JUMP CREEK TRIBUTARY 11 12.0
END DESCRIPTION:
XS GIS Cut Line= 3
      3554768.33     10346871.75      3554992.11     10346691.64
      3555166.57     10346576.29
#Sta/Elev= 30
  4727.4  409.28  4731.5  409.28  4780.3  401.78  4815.5  398.68  4829.9   396.5
  4850.7  395.37  4858.7  393.65  4908.3  388.19  4922.7  387.44    4937  383.97
  4972.3  379.87  4978.7  377.68  4986.6  371.19  4993.1  369.34    4998  366.63
  5000.8  366.13    5004  366.63  5007.5   367.8  5011.4  374.92  5017.6  374.92
  5022.2  378.04  5028.2  379.46  5050.6  381.11  5064.3  383.16  5086.6  385.01
  5100.4  387.18  5130.5  388.82  5166.6  393.06  5194.5   394.8  5223.8  397.54
#Mann= 3 ,-1 , 0
  4727.4     .16       0    4998     .07       0    5004     .16       0
Bank Sta=4998,5004
XS Rating Curve= 0 ,0
Exp/Cntr=0.3,0.1

Type RM Length L Ch R = 1 ,6039    ,413,413,413
BEGIN DESCRIPTION:
DEVILS JUMP CREEK TRIBUTARY 11 11.0
END DESCRIPTION:
XS GIS Cut Line= 3
      3554942.12     10347291.63      3555192.11     10347091.64
      3555492.11     10346791.64
#Sta/Elev= 30
  4667.6  412.49  4670.8  412.49  4674.8  410.71  4724.4  401.14  4738.8  397.71
    4782  391.05  4802.8  388.21  4846.1  383.86  4881.3  380.58  4887.7  380.65
  4902.1  379.62  4937.3   375.3  4966.1  373.29  4980.5  370.94  4984.5  366.64
  4991.3  366.64  4998.9  364.12  5001.6  363.62  5004.9  364.12    5016  369.44
  5030.2  372.41  5044.3  373.01  5058.4  375.05  5086.7  375.14  5171.6  380.83
  5283.7  386.83    5313  388.52  5355.4  391.88  5383.7  395.03    5412  396.33
#Mann= 4 ,-1 , 0
  4667.6     .16       0  4991.3     .07       0    5016     .16       0
  5283.7      .1       0
Bank Sta=4998.9,5004.9
XS Rating Curve= 0 ,0
Exp/Cntr=0.3,0.1

Type RM Length L Ch R = 1 ,5626    ,498,498,498
BEGIN DESCRIPTION:
DEVILS JUMP CREEK TRIBUTARY 11 10.0
END DESCRIPTION:
XS GIS Cut Line= 3
      3555148.45     10347632.03      3555392.11     10347441.64
      3555728.09     10347128.36
#Sta/Elev= 30
  4692.9  389.65  4702.8   389.4  4731.7  386.01    4738  386.21  4831.2  377.03
    4852  376.19  4860.1  374.95  4959.6  367.57  4980.4  367.92  4988.5  366.49
  4994.9  362.86  4995.9  361.26  4998.7  360.76  5001.9  361.26  5005.5  361.26
  5009.2  365.38  5023.4  367.71  5044.4  368.86  5125.1  369.13  5193.4  369.87
  5228.6  371.73  5341.9   380.1  5405.4   386.7  5419.6  386.72  5426.4   387.9
  5433.7  387.74  5440.6  389.13  5447.9  388.97  5454.8  390.37  5461.5  390.32
#Mann= 4 ,-1 , 0
  4692.9     .16       0  4988.5     .07       0  5009.2      .1       0
  5125.1      .1       0
Bank Sta=4995.9,5001.9
XS Rating Curve= 0 ,0
Exp/Cntr=0.3,0.1

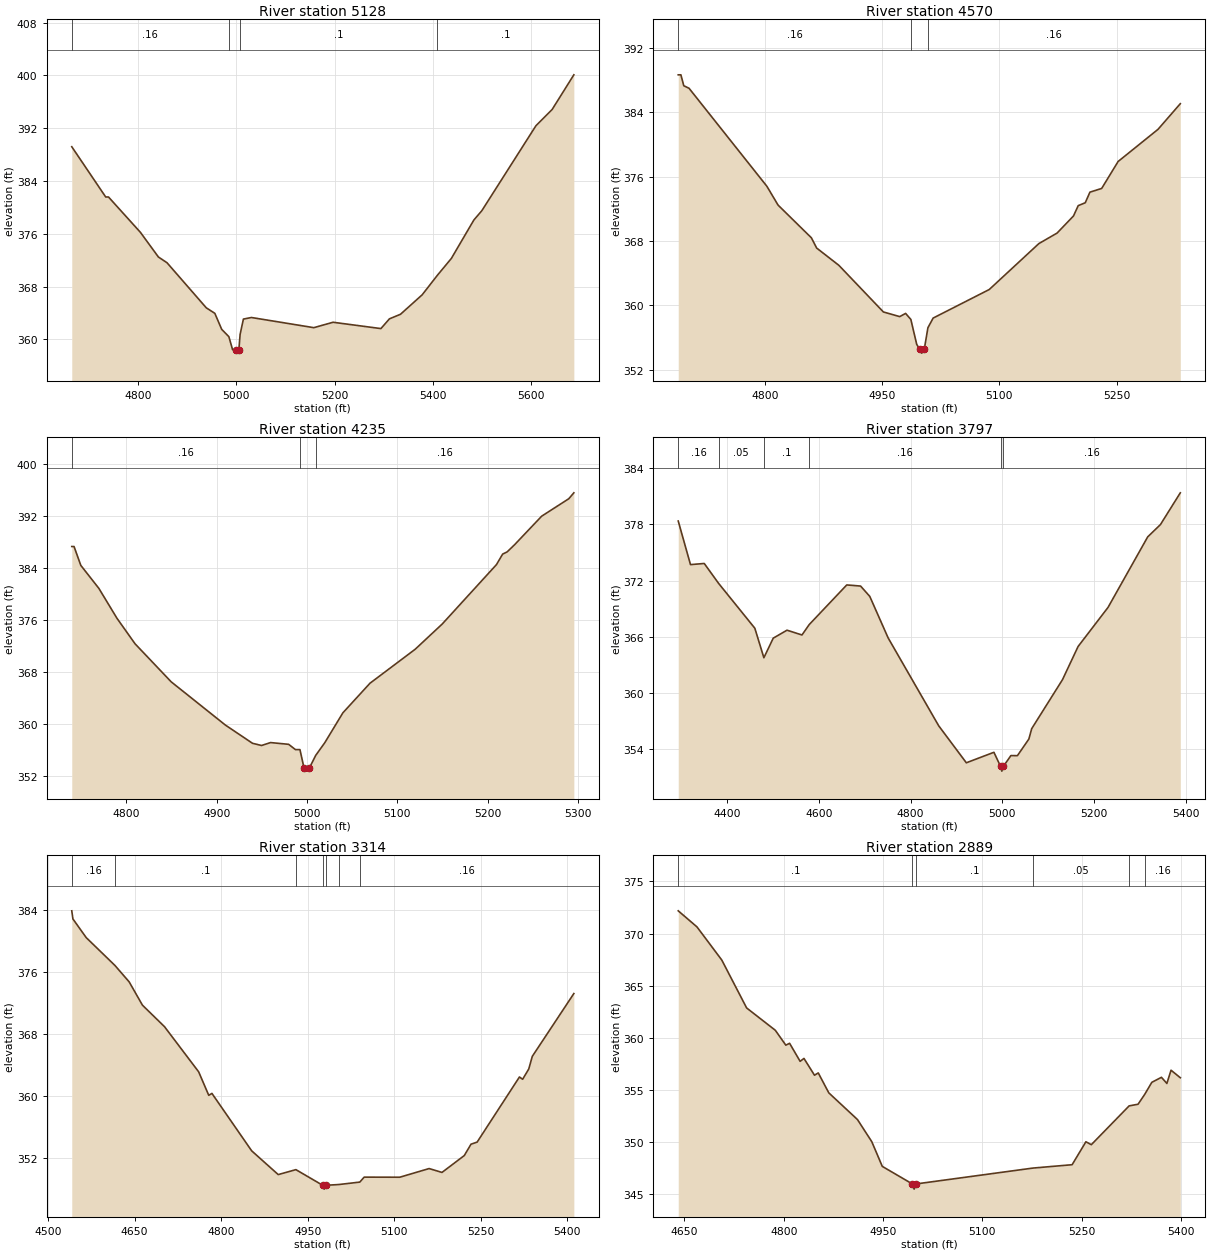
Type RM Length L Ch R = 1 ,5128    ,558,558,558
BEGIN DESCRIPTION:
DEVILS JUMP CREEK TRIBUTARY 11 9.0
END DESCRIPTION:
XS GIS Cut Line= 3
      3555543.72     10348054.29      3555593.72     10348004.28
       3555992.1     10347141.65
#Sta/Elev= 30
  4665.5   389.2  4734.5  381.58  4740.2  381.58  4805.2  376.21  4841.7  372.48
  4859.2  371.61    4939  364.78  4956.4  363.94  4970.4  361.51  4984.9  360.41
  4992.5  358.43  4999.3  358.41  5002.1  357.91  5005.3  358.41  5007.8  360.75
  5014.5  363.07  5030.8  363.31  5157.7  361.77  5196.8  362.59  5294.1  361.63
  5311.5  363.11  5333.9   363.8    5378  366.75  5408.8   369.7  5437.3  372.26
  5483.1  378.09  5499.2  379.49  5609.3  392.38  5642.3  394.85  5686.4   400.1
#Mann= 4 ,-1 , 0
  4665.5     .16       0  4984.9     .06       0  5007.8      .1       0
  5408.8      .1       0
Bank Sta=4999.3,5005.3
XS Rating Curve= 0 ,0
Exp/Cntr=0.3,0.1

Type RM Length L Ch R = 1 ,4570    ,335,335,335
BEGIN DESCRIPTION:
DEVILS JUMP CREEK TRIBUTARY 11 8.0
END DESCRIPTION:
XS GIS Cut Line= 3
      3555992.09     10348141.66      3556254.33     10347846.28
      3556392.11     10347641.63
#Sta/Elev= 30
  4689.5  388.65  4692.9  388.65  4696.6  387.29  4703.3  386.98  4802.8  374.79
  4817.1  372.45  4859.7  368.38  4866.4  367.11  4894.8  364.96  4951.7  359.16
  4972.6  358.58  4980.1  358.98  4986.8  358.23  4994.3  355.13    4998  354.54
  5000.8  354.04    5004  354.54  5008.6  357.19  5015.3   358.4    5087  361.95
  5150.4  367.66  5173.7  368.97  5194.7   371.1  5200.7  372.38  5209.7  372.74
  5215.7  374.06  5230.7  374.52  5251.7  377.87  5302.7  381.87  5331.2  385.06
#Mann= 3 ,-1 , 0
  4689.5     .16       0  4986.8     .06       0  5008.6     .16       0
Bank Sta=4998,5004
XS Rating Curve= 0 ,0
Exp/Cntr=0.3,0.1

Type RM Length L Ch R = 1 ,4235    ,438,438,438
BEGIN DESCRIPTION:
DEVILS JUMP CREEK TRIBUTARY 11 7.0
END DESCRIPTION:
XS GIS Cut Line= 3
      3556092.14     10348191.64      3556342.11     10348191.64
      3556647.67     10348184.96
#Sta/Elev= 30
  4739.7  387.33  4742.2  387.33  4749.7  384.43  4769.7  380.89  4789.7   376.3
  4809.7  372.38  4849.7  366.53  4909.7  359.88  4939.7  357.08  4949.7  356.74
  4959.7  357.19  4979.7  356.92  4987.2  356.11  4992.2  356.11  4996.7   353.3
  4999.4   352.8  5002.7   353.3  5009.7  355.23  5019.7  357.17  5039.7  361.76
  5069.7  366.31  5119.7  371.53  5149.7  375.42  5209.7  384.55  5216.5  386.16
  5221.5   386.5  5229.7   387.6  5259.7  391.99  5289.7  394.67  5295.3  395.58
#Mann= 3 ,-1 , 0
  4739.7     .16       0  4992.2     .06       0  5009.7     .16       0
Bank Sta=4996.7,5002.7
XS Rating Curve= 0 ,0
Exp/Cntr=0.3,0.1

Type RM Length L Ch R = 1 ,3797    ,483,483,483
BEGIN DESCRIPTION:
DEVILS JUMP CREEK TRIBUTARY 11 6.0
END DESCRIPTION:
XS GIS Cut Line= 3
      3555535.47     10348551.26      3556242.11     10348591.64
      3556613.74     10348696.41
#Sta/Elev= 30
  4293.7  378.36  4320.4  373.71  4350.4  373.83  4381.6  371.71  4460.6  366.92
  4480.3  363.77  4500.7  365.86  4530.7  366.71  4563.3   366.2  4579.1  367.31
  4660.9  371.54    4691  371.42    4711  370.32  4751.1  365.88  4861.3   356.5
  4921.4  352.56  4981.5  353.68    4996  352.17  4998.7  351.67    5002  352.17
  5018.5  353.33  5032.7  353.32  5057.7   355.1  5063.8   356.2  5130.9  361.43
  5164.9  364.97  5230.1  369.14  5316.6  376.67  5344.3  377.98  5387.6  381.37
#Mann= 6 ,-1 , 0
  4293.7     .16       0  4381.6     .05       0  4480.3      .1       0
  4579.1     .16       0    4996     .07       0    5002     .16       0
Bank Sta=4996,5002
XS Rating Curve= 0 ,0
Exp/Cntr=0.3,0.1

Type RM Length L Ch R = 1 ,3314    ,425,425,425
BEGIN DESCRIPTION:
DEVILS JUMP CREEK TRIBUTARY 11 5.0
END DESCRIPTION:
XS GIS Cut Line= 3
      3555646.09     10349207.87      3556131.96     10348984.73
      3556431.98     10348834.72
#Sta/Elev= 30
  4541.1  383.93  4543.1  382.88  4566.1  380.47    4616  376.86  4640.6  374.74
  4663.6  371.73  4701.8  368.95    4761  363.11  4778.5  360.07    4784  360.32
  4852.9  352.89  4898.9  349.82  4929.5  350.46  4975.9  348.44  4978.6  347.94
  4981.9  348.44  5003.5  348.53  5040.3  348.85  5047.8  349.49  5109.5  349.48
  5160.4   350.6  5182.7   350.1  5221.3  352.28    5233  353.75  5243.6  354.02
  5316.9  362.44  5322.5  362.15  5333.1  363.48  5339.2  365.11  5411.2  373.23
#Mann= 7 ,-1 , 0
  4541.1     .16       0    4616      .1       0  4929.5     .05       0
  4975.9     .04       0  4981.9     .05       0  5003.5      .1       0
  5040.3     .16       0
Bank Sta=4975.9,4981.9
XS Rating Curve= 0 ,0
Exp/Cntr=0.3,0.1

Type RM Length L Ch R = 1 ,2889    ,358,358,358
BEGIN DESCRIPTION:
DEVILS JUMP CREEK TRIBUTARY 11 4.0
END DESCRIPTION:
XS GIS Cut Line= 3
      3555929.47     10349518.89      3556242.11     10349341.64
       3556557.8     10349097.77
#Sta/Elev= 30
  4640.7  372.18    4669  370.64  4706.5  367.46    4744  362.87  4787.3  360.73
  4803.2   359.3  4808.9  359.48  4824.8  357.75  4830.6  358.03  4846.5  356.42
  4852.2  356.64  4868.1  354.73  4911.4  352.17    4933  350.05  4948.9  347.68
  4994.2     346    4997   345.5  5000.2     346  5176.6  347.52  5235.6  347.84
  5256.4  350.04  5264.6  349.76  5321.7  353.48  5335.2  353.64    5345  354.56
    5356  355.74  5370.5  356.22  5378.7  355.63    5385   356.9    5399  356.18
#Mann= 6 ,-1 , 0
  4640.7      .1       0  4994.2     .07       0  5000.2      .1       0
  5176.6     .05       0  5321.7      .1       0    5345     .16       0
Bank Sta=4994.2,5000.2
XS Rating Curve= 0 ,0
Exp/Cntr=0.3,0.1

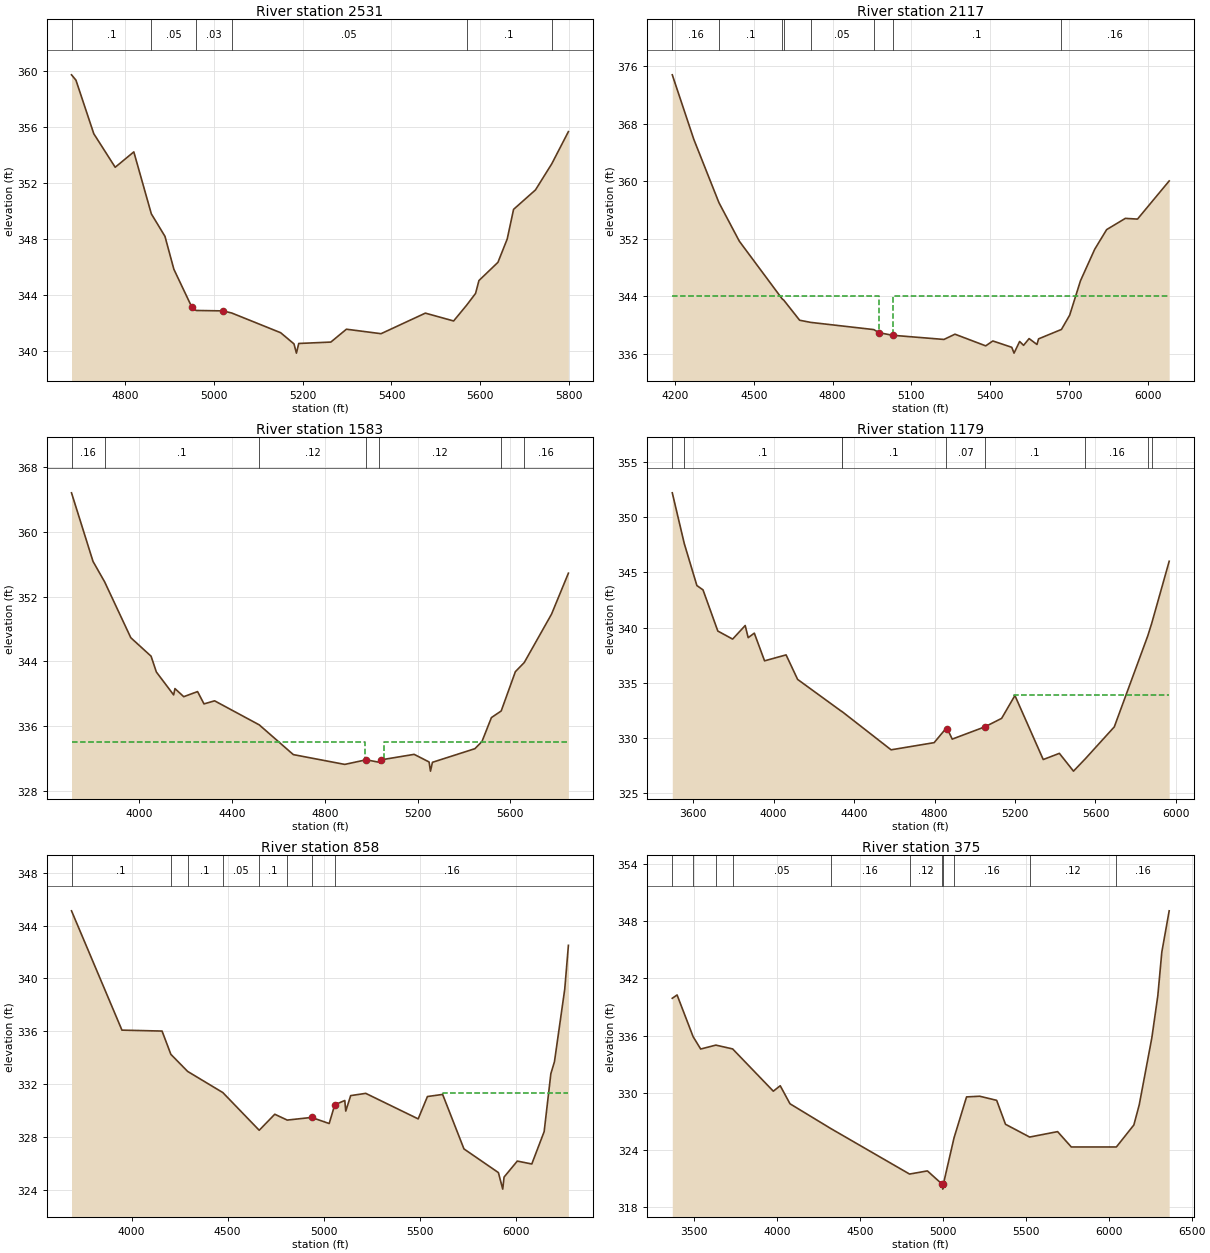
Type RM Length L Ch R = 1 ,2531    ,414,414,414
BEGIN DESCRIPTION:
DEVILS JUMP CREEK TRIBUTARY 11 3.0
END DESCRIPTION:
XS GIS Cut Line= 3
       3555992.1     10349691.64      3556551.52     10349664.03
       3556917.5     10349242.81
#Sta/Elev= 30
    4680  359.72    4690  359.34  4730.1  355.51  4778.3  353.11  4820.2  354.21
  4859.6  349.78  4890.3  348.17  4910.3  345.82  4950.3  343.14  4960.3  342.87
  5020.4  342.84  5040.4  342.69  5150.6  341.28  5180.6  340.48  5186.1  339.82
  5191.3  340.51  5263.5  340.61  5298.6  341.53  5376.5  341.21  5476.2  342.68
  5539.8  342.12  5568.9  343.24  5589.2  344.09  5596.8  345.01  5639.5  346.31
  5660.4  347.98  5674.7   350.1    5724  351.49  5760.7  353.36  5798.1  355.66
#Mann= 6 ,-1 , 0
    4680      .1       0  4859.6     .05       0  4960.3     .03       0
  5040.4     .05       0  5568.9      .1       0  5760.7     .16       0
#Block Obstruct= 2 , 0
       0 5030.23   342.5 5030.91       0   342.5
Bank Sta=4950.3,5020.4
XS Rating Curve= 0 ,0
Exp/Cntr=0.3,0.1

Type RM Length L Ch R = 1 ,2117    ,534,534,534
BEGIN DESCRIPTION:
Mapping XS 54682866
END DESCRIPTION:
XS GIS Cut Line= 5
      3555789.35      10349711.8      3556357.93     10349998.27
      3557082.76     10349512.16      3557186.93     10349264.76
       3557195.6     10349151.94
#Sta/Elev= 30
    4190  374.79  4272.2   365.8  4367.6  357.03  4445.1  351.68  4608.3  343.66
  4614.1   343.5  4674.6   340.7  4716.8   340.4  4956.7   339.4  4977.7  338.96
  5028.7  338.61  5223.8  338.03  5265.8  338.76  5382.8  337.14  5409.9  337.82
  5481.9  336.94  5490.6  336.13  5511.9  337.75  5526.9  337.21  5547.9  338.15
  5577.9  337.33  5583.9  338.11    5671  339.42  5702.4  341.41  5743.4  346.18
  5797.6  350.56    5843  353.29  5914.2  354.85  5960.4  354.75    6081  360.05
#Mann= 8 ,-1 , 0
    4190     .16       0  4367.6      .1       0  4608.3     .05       0
  4614.1      .1       0  4716.8     .05       0  4956.7     .03       0
  5028.7      .1       0    5671     .16       0
#XS Ineff= 2 , 0
       0  4977.7     344  5028.7       0     344
Permanent Ineff=
       T       T
#Block Obstruct= 2 , 0
                         5007.73          338.33
Bank Sta=4977.7,5028.7
XS Rating Curve= 0 ,0
Exp/Cntr=0.3,0.1

Type RM Length L Ch R = 1 ,1583    ,404,404,404
BEGIN DESCRIPTION:
Mapping XS 02720550
END DESCRIPTION:
XS GIS Cut Line= 4
      3555841.47     10349794.29       3556709.5     10350271.71
      3557186.93     10349907.12       3557290.9     10349365.59
#Sta/Elev= 30
  3707.9  364.82  3800.7  356.35  3850.7  353.83  3963.6  346.93    4051  344.65
  4073.8   342.7  4148.3  339.87    4154  340.65  4191.9  339.65  4251.5  340.28
  4279.3  338.76  4324.9  339.14  4517.6  336.17  4664.4   332.5  4886.2  331.29
  4978.7  331.86  5035.9  331.55  5042.1  331.85  5185.5  332.53  5249.9  331.59
  5255.9  330.46  5264.4  331.55  5447.4  333.23    5478  334.12  5518.7  337.07
  5560.9  337.89    5622  342.74  5660.1  343.86  5777.9  349.84  5850.7   354.9
#Mann= 7 ,-1 , 0
  3707.9     .16       0  3850.7      .1       0  4517.6     .12       0
  4978.7     .07       0  5035.9     .12       0  5560.9     .05       0
  5660.1     .16       0
#XS Ineff= 2 , 0
       0  4971.4     334  5056.7       0     334
Permanent Ineff=
       T       T
Bank Sta=4978.7,5042.1
XS Rating Curve= 0 ,0
Exp/Cntr=0.3,0.1

Type RM Length L Ch R = 1 ,1179    ,321,321,321
BEGIN DESCRIPTION:
Mapping XS a9be450f
END DESCRIPTION:
XS GIS Cut Line= 4
      3555871.79     10349989.57      3556861.41     10350462.68
      3557364.88     10350267.37        3557443.     10349438.35
#Sta/Elev= 30
  3496.7  352.21  3556.5   347.6    3619  343.81  3649.4  343.42    3723  339.69
  3796.6  338.96  3859.1  340.19  3873.9  339.09  3904.4   339.5  3955.3  336.99
  4062.3  337.53  4119.6  335.31  4338.3  332.41  4339.4  332.41  4584.2  328.93
  4798.1  329.58  4858.1  330.89  4863.5  330.84    4888   329.9  5051.4  331.02
  5133.6  331.78  5199.6  333.85  5340.3  328.05  5420.6  328.61  5490.7     327
  5549.6  328.12  5693.5  331.01  5860.2  339.27  5879.3  340.38  5966.3  346.01
#Mann= 9 ,-1 , 0
  3496.7     .16       0  3556.5      .1       0  4338.3     .05       0
  4339.4      .1       0  4858.1     .07       0  5051.4      .1       0
  5549.6     .16       0  5860.2      .1       0  5879.3     .16       0
#XS Ineff= 2 , 0
                         5197.16           333.9
Permanent Ineff=
       F       F
#Block Obstruct= 2 , 0
                         4915.91          329.99
Bank Sta=4863.5,5051.4
XS Rating Curve= 0 ,0
Exp/Cntr=0.3,0.1

Type RM Length L Ch R = 1 ,858     ,483,483,483
BEGIN DESCRIPTION:
Mapping XS 8fcce0b9
END DESCRIPTION:
XS GIS Cut Line= 4
      3555902.17     10350115.44      3556609.67     10350488.72
      3557291.09     10350618.93      3557702.73     10349604.99
#Sta/Elev= 30
  3687.5  345.11  3950.2  336.09  4159.1  336.02    4205  334.26  4292.3  332.97
  4475.6  331.37  4665.1  328.52  4746.1  329.73  4811.1  329.29  4937.9  329.49
  5029.5  329.03  5058.7  330.45  5110.8  330.77  5115.9  329.97  5141.5  331.14
  5219.9  331.31  5493.1  329.38  5541.3  331.07 5620.45  331.23  5731.5  327.11
  5910.9  325.32  5933.5  324.07  5940.3  324.98  6009.3  326.19  6084.8  325.97
  6149.2  328.42  6184.1   332.8  6202.8   333.7  6256.3  339.18  6275.5   342.5
#Mann= 8 ,-1 , 0
  3687.5      .1       0    4205     .05       0  4292.3      .1       0
  4475.6     .05       0  4665.1      .1       0  4811.1     .16       0
  4937.9     .07       0  5058.7     .16       0
#XS Ineff= 2 , 0
                         5620.45          331.34
Permanent Ineff=
       F       F
#Block Obstruct= 2 , 0
                         5025.57          328.94
Bank Sta=4937.9,5058.7
XS Rating Curve= 0 ,0
Exp/Cntr=0.3,0.1

Type RM Length L Ch R = 1 ,375     ,0,0,0
BEGIN DESCRIPTION:
DEVILS JUMP CREEK TRIBUTARY 11 1.0
END DESCRIPTION:
XS GIS Cut Line= 4
      3555945.58     10350228.28      3557061.06     10351035.59
      3557382.24     10350601.57      3557793.89     10349604.95
#Sta/Elev= 30
  3369.3  339.92  3398.2  340.27    3495  335.89  3540.5   334.6    3632  335.01
  3733.2  334.61  3978.3  330.18    4020  330.75  4078.8  328.86    4326  326.25
  4799.5  321.49  4907.2  321.82    4997  320.41  4999.7  319.91    5003  320.41
  5067.7  325.29  5143.1  329.58  5222.4  329.65  5324.6  329.22  5377.8  326.71
  5523.4  325.37  5691.9  325.94  5774.4  324.33  6046.2  324.33  6151.7  326.64
  6184.1  328.76  6259.9  335.77    6296  340.19    6320  344.75  6364.5  349.09
#Mann= 11 ,-1 , 0
  3369.3      .1       0    3495     .05       0    3632      .1       0
  3733.2     .05       0    4326     .16       0  4799.5     .12       0
    4997     .07       0    5003     .12       0  5067.7     .16       0
  5523.4     .12       0  6046.2     .16       0
Bank Sta=4997,5003
XS Rating Curve= 0 ,0
Exp/Cntr=0.3,0.1

Chan Stop Cuts=-1
Use User Specified Reach Order=0
Composite Channel Slope=5