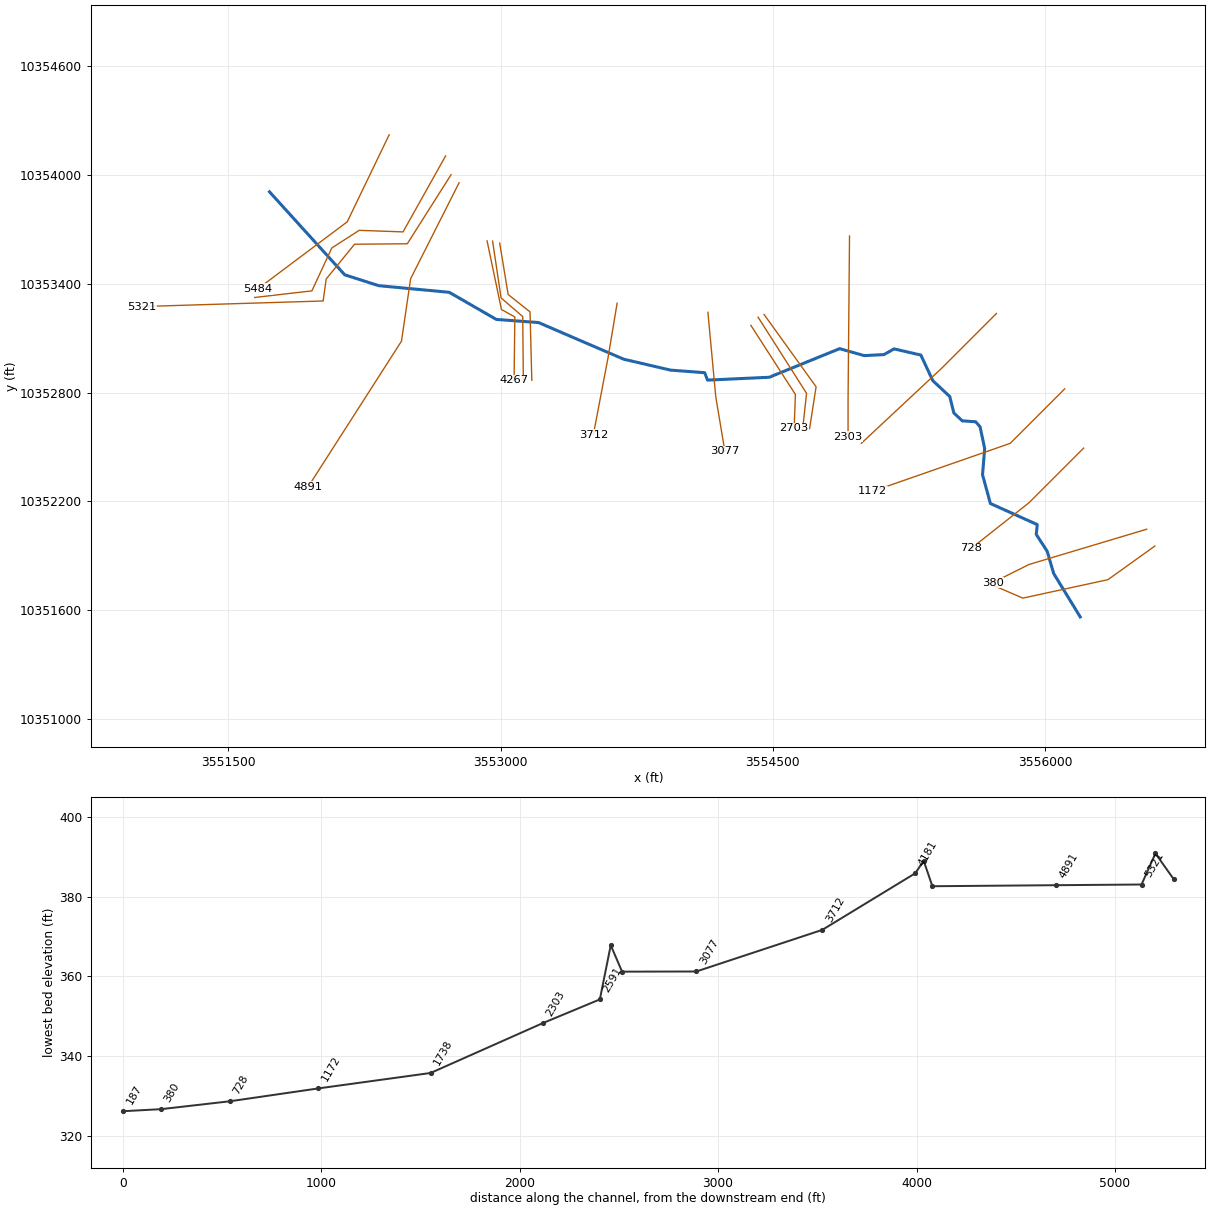
--- DEVILS JUMP CREEK TRIBUTARY 12.prj (project) ---

Proj Title=DEVILS JUMP CREEK TRIBUTARY 12 Base Level Engineering
Current Plan=p01
Default Exp/Contr=0.3,0.1
English Units
Geom File=g01
Flow File=f01
Plan File=p01
Y Axis Title=Elevation
X Axis Title(PF)=Main Channel Distance
X Axis Title(XS)=Station
BEGIN DESCRIPTION:
DEVILS JUMP CREEK TRIBUTARY 12
END DESCRIPTION:
DSS Export Rating Curves= 0
DSS Export Rating Curve Sorted= 0
DSS Export Volume Flow Curves= 0
DXF OffsetX= 0
DXF OffsetY= 0
DXF ScaleX= 1
DXF ScaleY= 10

--- DEVILS JUMP CREEK TRIBUTARY 12.p01 (plan) ---

Plan Title=Multiple Run
Short Identifier=Multiple
Geom File=g01
Flow File=f01
Subcritical Flow
K Sum by GR= 0
Std Step Tol= 0.01
Critical Tol= 0.01
Num of Std Step Trials= 20
Max Error Tol= 0.3
Flow Tol Ratio= 0.001
Split Flow NTrial= 30
Split Flow Tol= 0.02
Split Flow Ratio= 0.02
Log Output Level= 0
Friction Slope Method= 1
Unsteady Friction Slope Method= 2
Unsteady Bridges Friction Slope Method= 1
Parabolic Critical Depth
Global Vel Dist=  1 , 1 , 1
Global Log Level= 0
CheckData=True
Encroach Param= -1, 0, 0, 0
BEGIN DESCRIPTION:
Multiple Run
END DESCRIPTION:

--- DEVILS JUMP CREEK TRIBUTARY 12.f01 (steady flow) ---

Flow Title=Multiple
Program Version=4.10
Number of Profiles= 7
Profile Names=10-year,25-year,50-year,1pct_min,100-year,1pct_plu,500-year
River Rch & RM=DEVILS JUMP CREE,Reach-1         ,5484
    1068    1497    1859    1687    2282    3086    3428
Boundary for River Rch & Prof#=DEVILS JUMP CREE,Reach-1         , 1
Up Type= 0
Dn Type= 3
Dn Slope=0.0067
Boundary for River Rch & Prof#=DEVILS JUMP CREE,Reach-1         , 2
Up Type= 0
Dn Type= 3
Dn Slope=0.0067
Boundary for River Rch & Prof#=DEVILS JUMP CREE,Reach-1         , 3
Up Type= 0
Dn Type= 3
Dn Slope=0.0067
Boundary for River Rch & Prof#=DEVILS JUMP CREE,Reach-1         , 4
Up Type= 0
Dn Type= 3
Dn Slope=0.0067
Boundary for River Rch & Prof#=DEVILS JUMP CREE,Reach-1         , 5
Up Type= 0
Dn Type= 3
Dn Slope=0.0067
Boundary for River Rch & Prof#=DEVILS JUMP CREE,Reach-1         , 6
Up Type= 0
Dn Type= 3
Dn Slope=0.0067
Boundary for River Rch & Prof#=DEVILS JUMP CREE,Reach-1         , 7
Up Type= 0
Dn Type= 3
Dn Slope=0.0067
DSS Import GetInterval= 0
DSS Import GetPeak= 0
DSS Import FillOption= 0

--- DEVILS JUMP CREEK TRIBUTARY 12.g01 (geometry) ---

Geom Title=Existing Conditions
Program Version=4.10

River Reach=DEVILS JUMP CREE,Reach-1
Reach XY= 30
      3551728.03     10353905.03      3552142.18     10353448.11
      3552329.68     10353388.22       3552717.7     10353351.76
      3552976.82     10353202.45      3553209.19     10353185.24
      3553677.91     10352983.58      3553936.71      10352923.2
      3554124.21     10352909.14      3554139.88     10352868.29
      3554479.73     10352883.92      3554867.44     10353041.46
      3555002.39     10353003.15      3555111.75     10353008.75
      3555167.05     10353040.28      3555314.83     10353006.08
      3555380.25     10352865.58      3555473.71     10352778.05
      3555496.23     10352687.41      3555543.04     10352643.84
       3555616.7     10352638.88      3555640.61     10352611.51
      3555666.16      10352491.7      3555654.24     10352347.36
       3555697.7     10352188.77       3555955.7     10352072.54
      3555950.06      10352018.5      3556010.37     10351925.93
      3556046.04     10351803.27      3556192.28     10351564.29

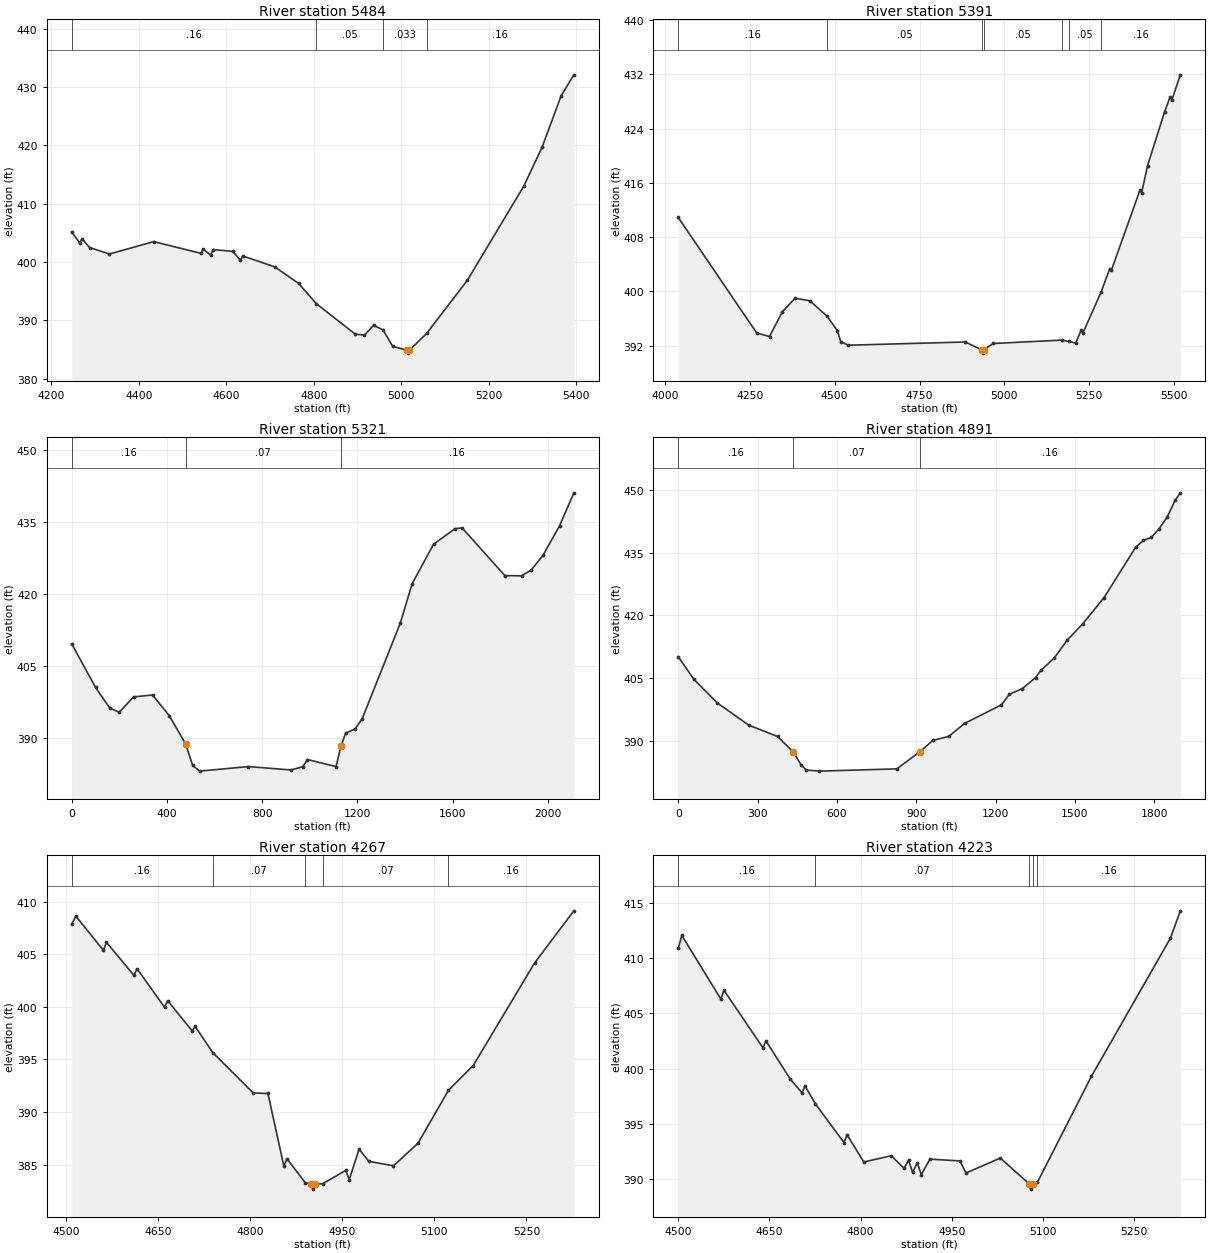
Type RM Length L Ch R = 1 ,5484    ,93,93,93
BEGIN DESCRIPTION:
DEVILS JUMP CREEK TRIBUTARY 12 12.0
END DESCRIPTION:
XS GIS Cut Line= 3
      3552386.83      10354219.1      3552155.91      10353739.9
      3551662.82     10353370.08
#Sta/Elev= 30
  4246.4  405.17  4264.5  403.27  4270.1  403.97  4287.1  402.49  4332.4  401.38
  4433.9   403.5  4541.5   401.5    4547  402.24  4564.1  401.16  4569.7  402.14
  4614.9  401.82    4632  400.28  4637.5  401.04  4710.9  399.16  4765.3  396.32
  4806.1  392.83  4894.9  387.62  4915.7  387.47  4936.6  389.12  4958.1  388.38
  4980.3  385.54  5012.7  384.87  5015.5  384.37  5018.7  384.87  5058.1  387.76
  5151.1  396.86  5280.3  413.04    5322  419.69  5365.7  428.54  5394.7  432.12
#Mann= 4 ,-1 , 0
  4246.4     .16       0  4806.1     .05       0  4958.1    .033       0
  5058.1     .16       0
Bank Sta=5012.7,5018.7
XS Rating Curve= 0 ,0
Exp/Cntr=0.3,0.1

Type RM Length L Ch R = 1 ,5391    ,70,70,70
BEGIN DESCRIPTION:
Mapping XS 4e201061
END DESCRIPTION:
XS GIS Cut Line= 6
      3552697.57     10354102.73       3552463.2     10353684.34
      3552221.88     10353693.02      3552070.84      10353595.8
      3551961.46     10353359.69      3551646.33     10353323.33
#Sta/Elev= 30
  4039.7  410.92  4270.8  393.87  4308.5  393.36  4346.1  397.01  4383.8  399.01
  4427.2  398.63  4478.3  396.34  4508.2  394.23  4517.9  392.62  4540.4  392.08
  4884.4  392.55  4932.9  391.41  4935.6  390.91  4938.9  391.41    4967  392.33
    5169  392.83  5189.3  392.64    5210  392.39  5226.1  394.34  5231.2  393.89
  5285.1  399.98    5310  403.36    5315  403.14  5398.9  414.94    5404  414.56
  5421.4  418.56  5471.7  426.51  5487.8   428.7  5492.9  428.22  5517.8  431.94
#Mann= 7 ,-1 , 0
  4039.7     .16       0  4478.3     .05       0  4932.9    .033       0
  4938.9     .05       0    5169      .1       0  5189.3     .05       0
  5285.1     .16       0
Bank Sta=4932.9,4938.9
XS Rating Curve= 0 ,0
Exp/Cntr=0.3,0.1

Type RM Length L Ch R = 1 ,5321    ,430,430,430
BEGIN DESCRIPTION:
Mapping XS 63cb7dee
END DESCRIPTION:
XS GIS Cut Line= 6
      3552727.66     10353999.38      3552486.75     10353619.13
      3552196.38     10353616.52      3552040.13     10353425.12
       3552023.2     10353304.02     3551025.453    10353273.367
#Sta/Elev= 30
       0409.566799.83571400.5219159.7371396.2108199.6714  395.35259.5728398.5484
339.4414 398.932409.3264394.6529478.5583388.7408 507.856384.2848537.1537383.0928
742.2375384.0408920.8894383.3345970.5149384.0239990.3651385.50881110.431384.0318
 1130.41388.21991150.389390.96751190.347391.87531220.315394.02451380.146413.8733
1430.093422.11881519.999430.30261609.904433.54851639.872 433.7121819.682423.7781
1889.608423.73921929.566424.92141979.513427.96672049.439434.15432109.376441.0075
#Mann= 3 , 0 , 0
       0     .16       0478.5583     .07       0 1130.41     .16       0
Bank Sta=478.5583,1130.41
XS Rating Curve= 0 ,0
Exp/Cntr=0.3,0.1

Type RM Length L Ch R = 1 ,4891    ,624,624,624
BEGIN DESCRIPTION:
DEVILS JUMP CREEK TRIBUTARY 12 11.0
END DESCRIPTION:
XS GIS Cut Line= 4
     3552771.854    10353954.863      3552504.95     10353426.36
     3552454.769    10353082.918     3551941.251    10352281.614
#Sta/Elev= 30
       0410.173859.30239404.7806 148.256399.1457266.8608393.8652375.5818391.1734
434.8842387.5128464.5354 384.412484.3029383.1801533.7216382.9201826.6834383.4601
914.3057387.5668963.4169390.25491023.128391.19521082.839394.27971222.165398.7047
1252.021401.2017 1301.78402.5916 1351.54405.20741371.443406.92521421.203409.8005
1470.962414.11071530.673418.08911610.288424.2486 1729.71436.22621759.566 437.886
1789.422438.59941819.277440.71571849.133443.44521878.988447.40681898.892449.2204
#Mann= 3 , 0 , 0
       0     .16       0434.8842     .07       0914.3057     .16       0
Bank Sta=434.8842,914.3057
XS Rating Curve= 0 ,0
Exp/Cntr=0.3,0.1

Type RM Length L Ch R = 1 ,4267    ,44,44,44
BEGIN DESCRIPTION:
Mapping XS 47313c14
END DESCRIPTION:
XS GIS Cut Line= 4
      3552926.02     10353634.69      3553005.23     10353257.11
      3553079.01     10353215.88      3553074.67     10352867.53
#Sta/Elev= 30
  4508.7  407.89  4515.4  408.63  4560.2  405.39  4565.3  406.14  4610.1     403
  4615.2  403.63    4660  399.96  4665.1  400.59  4704.8  397.73  4709.9  398.15
  4738.6  395.65  4804.6  391.81  4828.6  391.76  4854.5  384.86  4859.6  385.55
  4889.6  383.27  4899.4  383.16  4902.1  382.66  4905.4  383.16  4917.8  383.17
  4955.4  384.44  4961.2  383.57  4977.1  386.46  4993.3   385.3  5033.3  384.88
  5073.3  387.03    5123  392.07  5163.3  394.42  5263.3  404.17  5327.4  409.14
#Mann= 5 ,-1 , 0
  4508.7     .16       0  4738.6     .07       0  4889.6     .07       0
  4917.8     .07       0    5123     .16       0
Bank Sta=4899.4,4905.4
XS Rating Curve= 0 ,0
Exp/Cntr=0.3,0.1

Type RM Length L Ch R = 1 ,4223    ,42,42,42
BEGIN DESCRIPTION:
DEVILS JUMP CREEK TRIBUTARY 12 10.0
END DESCRIPTION:
XS GIS Cut Line= 4
       3552956.4     10353633.66      3553003.06     10353321.13
      3553122.42     10353218.05      3553125.66     10352865.46
#Sta/Elev= 30
  4499.9  410.89  4505.8  412.07    4570   406.3  4575.1   407.1  4639.3  401.88
  4644.3   402.5  4683.9  399.07  4703.5   397.8  4708.5  398.43  4725.7  396.79
  4772.7  393.28  4777.8  393.99  4805.3  391.52  4850.5  392.09  4871.4  390.95
    4879  391.67  4885.6  390.58  4893.3  391.46  4899.9  390.37  4914.1  391.78
  4963.5  391.62  4973.6  390.52    5030  391.88    5077  389.56  5079.8  389.06
    5083  389.56  5090.9  389.67    5180   399.3    5310  411.83  5326.2   414.3
#Mann= 5 ,-1 , 0
  4499.9     .16       0  4725.7     .07       0    5077     .07       0
    5083     .07       0  5090.9     .16       0
Bank Sta=5077,5083
XS Rating Curve= 0 ,0
Exp/Cntr=0.3,0.1

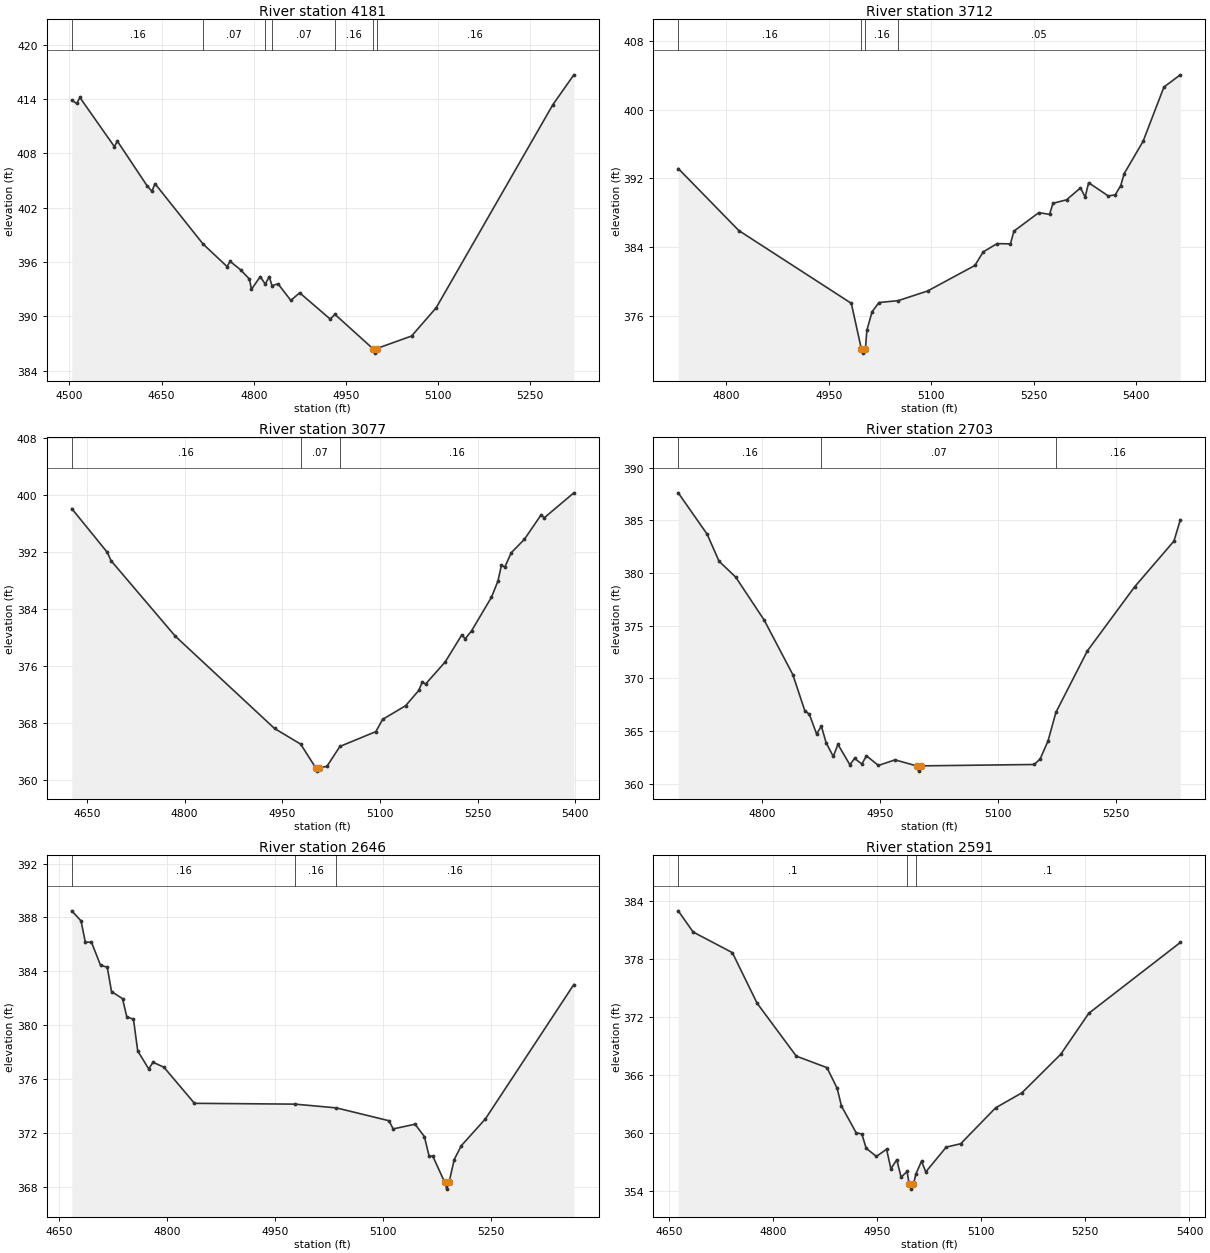
Type RM Length L Ch R = 1 ,4181    ,469,469,469
BEGIN DESCRIPTION:
Mapping XS 8f18ae66
END DESCRIPTION:
XS GIS Cut Line= 4
      3552995.47     10353622.73      3553042.12     10353339.58
      3553162.56     10353244.09      3553172.33     10352867.59
#Sta/Elev= 30
  4503.8  413.84  4511.9   413.5    4517  414.16  4573.1  408.74  4578.1  409.33
  4626.5   404.4  4634.2   403.8  4639.3  404.64  4717.5  397.98  4756.6  395.49
  4761.6  396.06  4778.5  395.14  4793.1   394.1  4796.3  392.98  4810.7  394.38
  4818.8  393.54  4825.2  394.39  4829.7  393.38  4839.6  393.58  4860.4  391.75
  4874.8  392.59  4924.5  389.69  4932.2  390.21  4993.9  386.43  4996.7  385.93
  4999.9  386.43    5057  387.82    5097  390.94    5287  413.37  5321.1  416.66
#Mann= 7 ,-1 , 0
  4503.8     .16       0  4717.5     .07       0  4818.8     .16       0
  4829.7     .07       0  4932.2     .16       0  4993.9     .07       0
  4999.9     .16       0
Bank Sta=4993.9,4999.9
XS Rating Curve= 0 ,0
Exp/Cntr=0.3,0.1

Type RM Length L Ch R = 1 ,3712    ,635,635,635
BEGIN DESCRIPTION:
DEVILS JUMP CREEK TRIBUTARY 12 8.0
END DESCRIPTION:
XS GIS Cut Line= 3
      3553642.11     10353291.66      3553592.11     10352991.64
       3553511.3     10352568.04
#Sta/Elev= 30
  4729.6  393.15  4818.3  385.94  4983.1  377.48  4997.8  372.19  5000.6  371.69
  5003.8  372.19  5005.9  374.34  5013.5   376.5  5023.6  377.57  5051.7  377.79
  5094.8  378.91  5164.1  381.88  5176.3  383.46  5196.6  384.42  5216.2  384.39
  5221.3  385.87  5257.7  388.02  5273.5  387.82  5278.5  389.11  5298.4  389.51
  5318.8   390.9  5325.6  389.84  5330.7   391.5  5359.5  389.96  5369.7  390.09
  5377.7  391.16  5382.8  392.56  5410.4   396.3    5441  402.62    5465  404.04
#Mann= 4 ,-1 , 0
  4729.6     .16       0  4997.8     .07       0  5003.8     .16       0
  5051.7     .05       0
Bank Sta=4997.8,5003.8
XS Rating Curve= 0 ,0
Exp/Cntr=0.3,0.1

Type RM Length L Ch R = 1 ,3077    ,374,374,374
BEGIN DESCRIPTION:
DEVILS JUMP CREEK TRIBUTARY 12 7.0
END DESCRIPTION:
XS GIS Cut Line= 3
       3554142.1     10353241.68      3554185.33     10352776.71
      3554235.33     10352476.73
#Sta/Elev= 30
  4626.7  398.04  4681.4  391.89    4687  390.74  4785.6  380.16  4938.1  367.21
  4978.2  365.02  5001.1  361.73  5003.8  361.23  5007.1  361.73  5018.4  361.88
  5038.5  364.69  5093.7  366.77  5104.2  368.49  5139.4   370.4  5159.6  372.54
    5165  373.71  5170.1  373.44  5200.2  376.54  5225.8  380.34  5230.9  379.78
  5240.7   380.9  5271.2   385.6  5281.3  387.89  5286.6  390.12  5291.7  389.83
  5301.6  391.84  5321.8  393.73  5347.5  397.16  5352.5  396.76  5397.8  400.25
#Mann= 3 ,-1 , 0
  4626.7     .16       0  4978.2     .07       0  5038.5     .16       0
Bank Sta=5001.1,5007.1
XS Rating Curve= 0 ,0
Exp/Cntr=0.3,0.1

Type RM Length L Ch R = 1 ,2703    ,57,57,57
BEGIN DESCRIPTION:
Mapping XS 5fadba79
END DESCRIPTION:
XS GIS Cut Line= 3
      3554378.64     10353169.79      3554623.86     10352789.16
      3554617.06     10352603.57
#Sta/Elev= 30
  4693.3   387.6  4730.1  383.67  4745.2  381.11  4766.4   379.6  4802.7  375.51
    4839  370.35  4854.2  366.94  4860.1  366.57  4869.3  364.71  4875.3  365.47
  4881.4  363.88  4890.5  362.58  4896.4  363.73  4911.6  361.79  4917.5   362.4
  4926.8  361.87  4932.7  362.64  4947.9  361.73    4969  362.26  4996.4  361.69
  4999.1  361.19  5002.4  361.69  5146.1  361.82  5153.6  362.35  5163.6  364.06
  5173.6  366.77  5213.6   372.6  5273.7  378.68  5323.7  383.02  5331.8  385.04
#Mann= 3 ,-1 , 0
  4693.3     .16       0  4875.3     .07       0  5173.6     .16       0
Bank Sta=4996.4,5002.4
XS Rating Curve= 0 ,0
Exp/Cntr=0.3,0.1

Type RM Length L Ch R = 1 ,2646    ,55,55,55
BEGIN DESCRIPTION:
DEVILS JUMP CREEK TRIBUTARY 12 6.0
END DESCRIPTION:
XS GIS Cut Line= 3
       3554418.4     10353214.75      3554685.25     10352795.63
      3554663.67     10352596.36
#Sta/Elev= 30
  4667.7  388.49  4680.6  387.74  4686.5  386.17  4695.1  386.16  4707.7  384.44
    4717  384.31  4722.9   382.5  4738.2  381.97  4744.1  380.63  4753.4  380.44
  4759.3  378.09  4774.6  376.75  4780.5  377.25  4795.7  376.88  4838.1   374.2
  4977.8  374.14  5035.3  373.86  5108.1  372.91  5114.1   372.3  5144.5  372.65
  5157.4  371.73    5164  370.28  5169.1  370.28  5185.7  368.33  5188.4  367.83
  5191.7  368.33  5198.8  370.02  5208.8  371.06  5242.1  373.04    5365  383.02
#Mann= 3 ,-1 , 0
  4667.7     .16       0  4977.8     .16       0  5035.3     .16       0
Bank Sta=5185.7,5191.7
XS Rating Curve= 0 ,0
Exp/Cntr=0.3,0.1

Type RM Length L Ch R = 1 ,2591    ,288,288,288
BEGIN DESCRIPTION:
Mapping XS 45cdf39e
END DESCRIPTION:
XS GIS Cut Line= 3
      3554451.33      10353229.7      3554737.79     10352831.48
      3554701.98      10352601.4
#Sta/Elev= 30
  4663.4  382.96  4684.9  380.77  4741.4  378.64    4777  373.42  4833.5  367.95
  4877.7  366.76  4892.4  364.62  4898.6  362.79  4919.7  360.04    4928   359.9
  4934.2  358.43  4948.9  357.59  4963.6  358.33  4969.8  356.31  4978.3  357.25
  4984.5  355.44  4993.1  356.04  4996.2  354.71    4999  354.21  5002.2  354.71
  5005.9  355.79  5013.9  357.09  5020.1  355.99  5049.5  358.55  5070.4   358.9
  5120.7  362.61  5158.6  364.16  5214.5  368.14    5255  372.38  5386.8  379.69
#Mann= 3 ,-1 , 0
  4663.4      .1       0  4993.1     .07       0  5005.9      .1       0
Bank Sta=4996.2,5002.2
XS Rating Curve= 0 ,0
Exp/Cntr=0.3,0.1

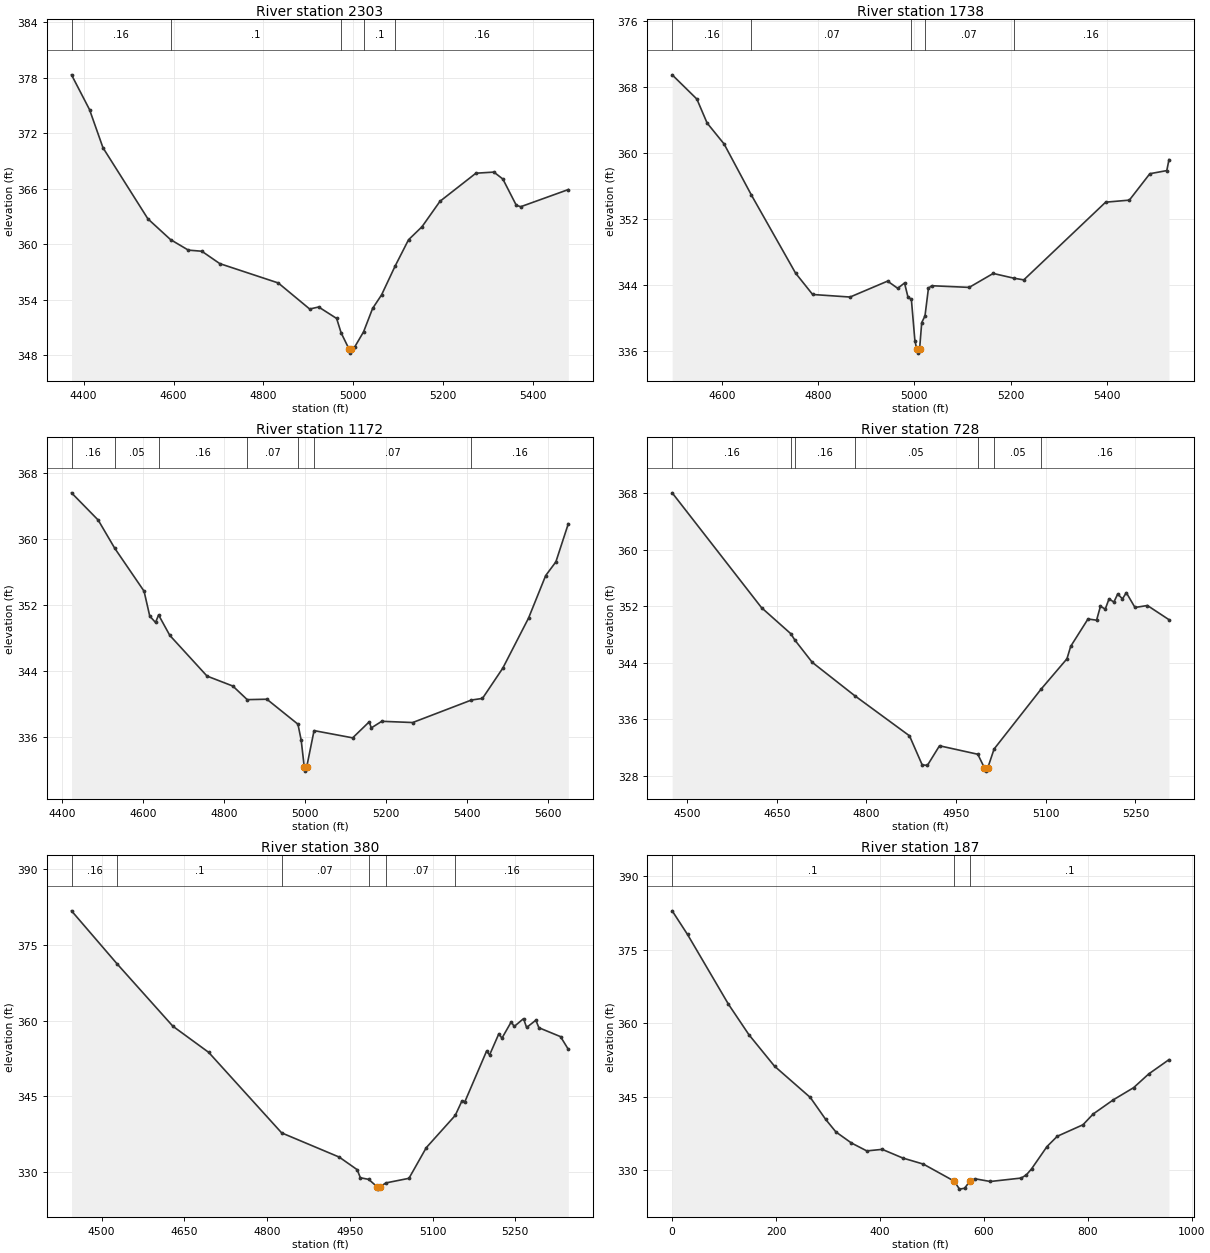
Type RM Length L Ch R = 1 ,2303    ,565,565,565
BEGIN DESCRIPTION:
DEVILS JUMP CREEK TRIBUTARY 12 5.0
END DESCRIPTION:
XS GIS Cut Line= 3
      3554921.89     10353661.78      3554913.81     10352755.18
      3554913.81     10352555.91
#Sta/Elev= 30
  4372.9  378.34    4413  374.58    4443  370.45    4543  362.76  4593.3  360.52
    4633  359.38    4663  359.26    4703  357.92  4833.1  355.83  4903.1  353.01
  4923.1  353.23  4963.1  351.99  4973.1  350.43  4990.1  348.74  4992.8  348.24
  4996.1  348.74  5003.1  348.89  5023.1  350.55  5043.1  353.07  5063.1  354.54
  5093.1  357.64  5123.1   360.5  5153.1  361.91  5193.1  364.66  5273.1   367.7
  5313.1  367.82  5333.1  367.07  5363.1  364.22  5373.1  364.08  5478.8  365.93
#Mann= 5 ,-1 , 0
  4372.9     .16       0  4593.3      .1       0  4973.1     .05       0
  5023.1      .1       0  5093.1     .16       0
Bank Sta=4990.1,4996.1
XS Rating Curve= 0 ,0
Exp/Cntr=0.3,0.1

Type RM Length L Ch R = 1 ,1738    ,566,566,566
BEGIN DESCRIPTION:
DEVILS JUMP CREEK TRIBUTARY 12 4.0
END DESCRIPTION:
XS GIS Cut Line= 3
      3555731.03     10353235.25      3555430.99     10352935.22
      3554987.08     10352520.37
#Sta/Elev= 30
  4496.9  369.46  4548.2  366.52  4569.4  363.62  4604.8  361.07  4661.3   354.9
  4753.2  345.42  4788.6  342.83  4866.4  342.52  4944.3  344.45  4965.3  343.58
  4979.5  344.22  4986.8  342.48  4993.7  342.26    5001  337.25  5004.8  336.22
  5007.6  335.72  5010.8  336.22  5015.2  339.42    5022  340.23  5029.2   343.6
  5036.2  343.89  5113.8  343.69  5163.7  345.38  5206.1  344.81  5227.2   344.6
  5397.2  354.02  5446.5  354.27    5489  357.47  5524.2  357.85  5528.8  359.18
#Mann= 5 ,-1 , 0
  4496.9     .16       0  4661.3     .07       0  4993.7     .04       0
    5022     .07       0  5206.1     .16       0
Bank Sta=5004.8,5010.8
XS Rating Curve= 0 ,0
Exp/Cntr=0.3,0.1

Type RM Length L Ch R = 1 ,1172    ,444,444,444
BEGIN DESCRIPTION:
DEVILS JUMP CREEK TRIBUTARY 12 3.0
END DESCRIPTION:
XS GIS Cut Line= 3
      3556106.88     10352820.13      3555806.86     10352520.11
      3555049.34     10352256.08
#Sta/Elev= 30
  4423.6  365.63  4489.5  362.32  4530.2  358.91  4602.7  353.69  4616.8  350.66
    4631  349.89  4638.6   350.8  4666.3  348.32  4758.2  343.38  4821.9  342.17
  4857.4  340.52  4905.9  340.57  4982.6  337.54  4990.6  335.61  4998.2  332.34
  5000.9  331.84  5004.2  332.34  5022.4  336.76  5117.7  335.88  5158.5  337.82
  5163.8  337.09  5189.6  337.89  5265.9  337.74  5410.8  340.47  5438.2  340.67
  5488.3  344.34  5551.9  350.42  5594.2  355.58  5619.4  357.25  5650.1  361.88
#Mann= 7 ,-1 , 0
  4423.6     .16       0  4530.2     .05       0  4638.6     .16       0
  4857.4     .07       0  4982.6     .04       0  5022.4     .07       0
  5410.8     .16       0
Bank Sta=4998.2,5004.2
XS Rating Curve= 0 ,0
Exp/Cntr=0.3,0.1

Type RM Length L Ch R = 1 ,728     ,348,348,348
BEGIN DESCRIPTION:
DEVILS JUMP CREEK TRIBUTARY 12 2.0
END DESCRIPTION:
XS GIS Cut Line= 3
      3556211.22     10352493.92       3555911.2      10352193.9
      3555592.07     10351941.62
#Sta/Elev= 30
  4475.1  368.04  4624.6  351.77  4673.6  348.08  4680.1  347.21  4709.4  344.03
  4780.1  339.33  4872.1  333.62  4893.3  329.51    4902  329.43  4922.3  332.21
  4986.4  331.01  4997.2  329.12    5000  328.62  5003.2  329.12  5013.6  331.75
  5092.1  340.22  5135.5  344.53  5141.8   346.3  5170.7  350.17  5185.1     350
  5191.5  351.97  5199.6  351.57  5205.9  353.03    5214  352.56  5220.4  353.71
  5228.4  353.02  5234.8   353.9  5249.3   351.8  5270.1  352.08  5306.2  350.07
#Mann= 7 ,-1 , 0
  4475.1     .16       0  4673.6     .05       0  4680.1     .16       0
  4780.1     .05       0  4986.4    .035       0  5013.6     .05       0
  5092.1     .16       0
Bank Sta=4997.2,5003.2
XS Rating Curve= 0 ,0
Exp/Cntr=0.3,0.1

Type RM Length L Ch R = 1 ,380     ,193,193,193
BEGIN DESCRIPTION:
DEVILS JUMP CREEK TRIBUTARY 12 1.0
END DESCRIPTION:
XS GIS Cut Line= 3
      3556558.18      10352047.2      3555909.64     10351852.75
      3555709.61     10351752.74
#Sta/Elev= 30
  4445.3  381.71  4528.3  371.17  4629.1  358.87    4694   353.7  4826.3  337.76
  4930.7  332.97  4963.2  330.48    4969  328.88  4984.1  328.56    4999  327.13
  5001.8  326.63    5005  327.13  5015.4  327.86  5057.1  328.77  5088.5  334.84
    5141  341.22    5153  344.05  5158.6  343.97  5197.7  353.92  5203.3   353.2
  5220.1  357.39  5225.6   356.5  5242.4  359.71    5248  358.83  5264.8  360.37
  5270.4  358.62  5287.1  360.06  5292.7  358.57  5331.9  356.81    5346   354.3
#Mann= 6 ,-1 , 0
  4445.3     .16       0  4528.3      .1       0  4826.3     .07       0
  4984.1    .035       0  5015.4     .07       0    5141     .16       0
Bank Sta=4999,5005
XS Rating Curve= 0 ,0
Exp/Cntr=0.3,0.1

Type RM Length L Ch R = 1 ,187     ,0,0,0
XS GIS Cut Line= 4
     3556602.777     10351954.27     3556344.965    10351769.374
     3555876.215    10351667.812     3555725.173    10351732.916
#Sta/Elev= 30
       0382.956729.54505378.1242108.3319363.8769147.7253357.6496 196.967351.2271
265.9055344.8272295.4505340.3565315.1472337.7912344.8772335.5438374.6071 333.915
404.3371334.2304443.9771332.4587 483.617331.2126543.0769327.7256552.9869326.1061
562.8969326.2873572.8069327.6926582.7169328.2233612.4468327.6661671.9067328.3694
681.8168329.0231691.7267330.2331721.4567334.7957741.2767336.9002790.8266339.2579
810.2999341.4444849.2466344.3534888.1933346.8276917.4033349.6425  956.35352.5558
#Mann= 3 , 0 , 0
       0      .1       0543.0769     .05       0572.8069      .1       0
Bank Sta=543.0769,572.8069
XS Rating Curve= 0 ,0
Exp/Cntr=0.3,0.1

Chan Stop Cuts=-1
Use User Specified Reach Order=0
Composite Channel Slope=5