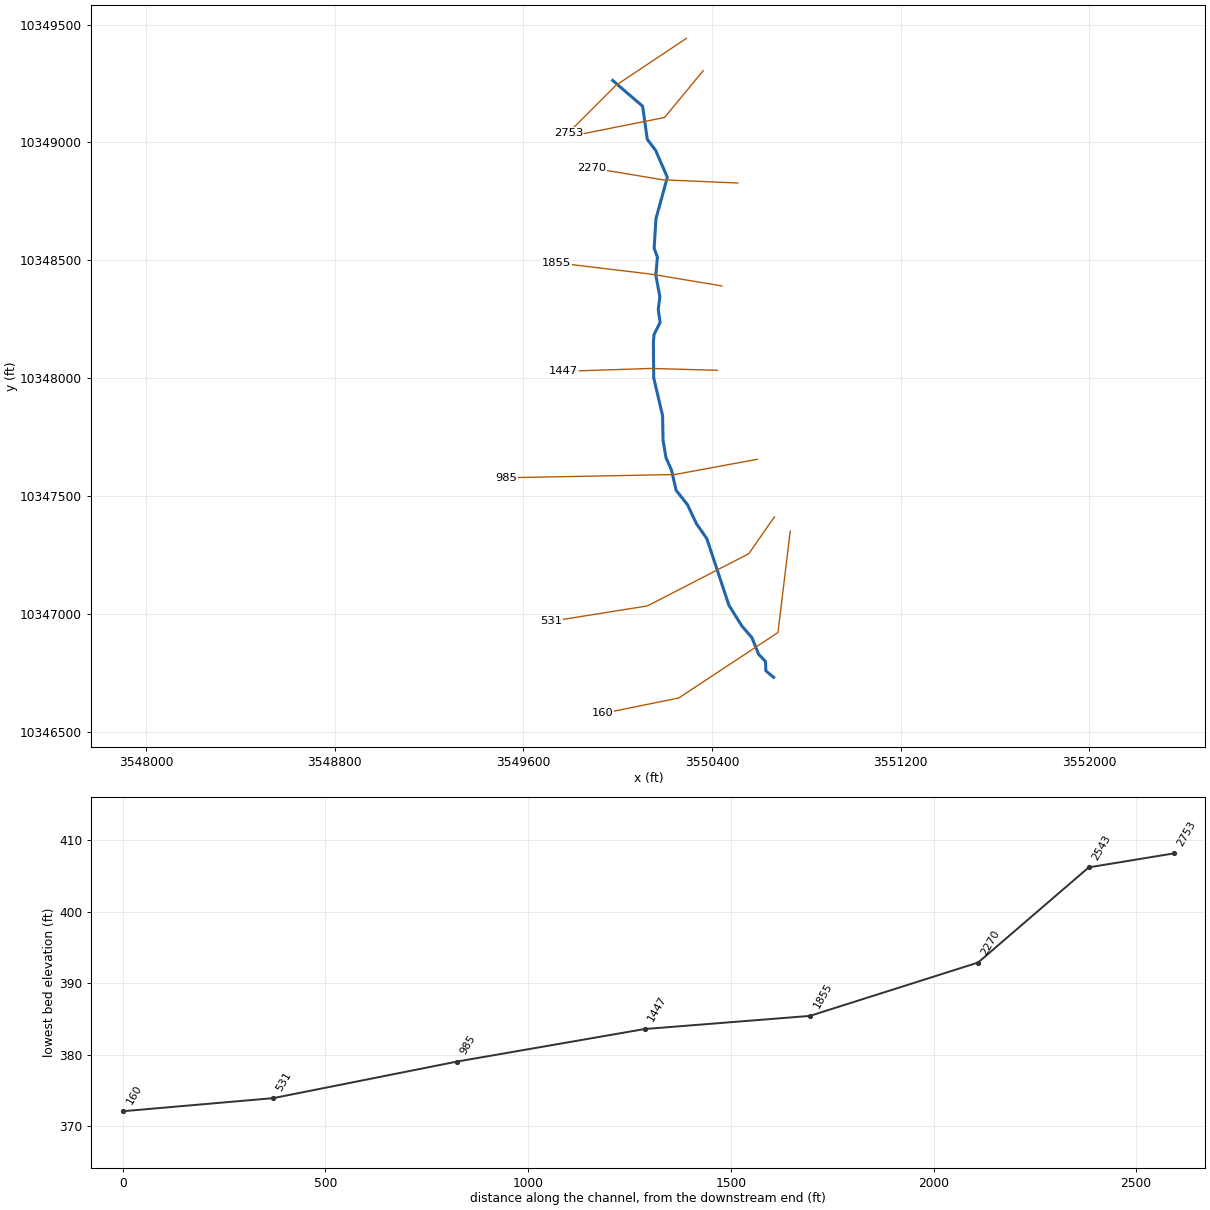
--- DEVILS JUMP CREEK TRIBUTARY 14 1.prj (project) ---

Proj Title=DEVILS JUMP CREEK TRIBUTARY 14 1 Base Level Engineering
Current Plan=p01
Default Exp/Contr=0.3,0.1
English Units
Geom File=g01
Flow File=f01
Plan File=p01
Y Axis Title=Elevation
X Axis Title(PF)=Main Channel Distance
X Axis Title(XS)=Station
BEGIN DESCRIPTION:
DEVILS JUMP CREEK TRIBUTARY 14 1
END DESCRIPTION:
DSS Export Rating Curves= 0
DSS Export Rating Curve Sorted= 0
DSS Export Volume Flow Curves= 0
DXF OffsetX= 0
DXF OffsetY= 0
DXF ScaleX= 1
DXF ScaleY= 10

--- DEVILS JUMP CREEK TRIBUTARY 14 1.p01 (plan) ---

Plan Title=Multiple Run
Short Identifier=Multiple
Geom File=g01
Flow File=f01
Subcritical Flow
K Sum by GR= 0
Std Step Tol= 0.01
Critical Tol= 0.01
Num of Std Step Trials= 20
Max Error Tol= 0.3
Flow Tol Ratio= 0.001
Split Flow NTrial= 30
Split Flow Tol= 0.02
Split Flow Ratio= 0.02
Log Output Level= 0
Friction Slope Method= 1
Unsteady Friction Slope Method= 2
Unsteady Bridges Friction Slope Method= 1
Parabolic Critical Depth
Global Vel Dist=  1 , 1 , 1
Global Log Level= 0
CheckData=True
Encroach Param= -1, 0, 0, 0
BEGIN DESCRIPTION:
Multiple Run
END DESCRIPTION:

--- DEVILS JUMP CREEK TRIBUTARY 14 1.f01 (steady flow) ---

Flow Title=Multiple
Number of Profiles=7
Profile Names=10-year,25-year,50-year,1pct_min,100-year,1pct_plu,500-year
River Rch & RM= DEVILS JUMP CREE,Reach-1,2753
     410     549     661     586     792    1072    1138
Boundary for River Rch & Prof#=DEVILS JUMP CREE,Reach-1,1
Up Type=0
Dn Type=3
Dn Slope=0.005
Boundary for River Rch & Prof#=DEVILS JUMP CREE,Reach-1,2
Up Type=0
Dn Type=3
Dn Slope=0.005
Boundary for River Rch & Prof#=DEVILS JUMP CREE,Reach-1,3
Up Type=0
Dn Type=3
Dn Slope=0.005
Boundary for River Rch & Prof#=DEVILS JUMP CREE,Reach-1,4
Up Type=0
Dn Type=3
Dn Slope=0.005
Boundary for River Rch & Prof#=DEVILS JUMP CREE,Reach-1,5
Up Type=0
Dn Type=3
Dn Slope=0.005
Boundary for River Rch & Prof#=DEVILS JUMP CREE,Reach-1,6
Up Type=0
Dn Type=3
Dn Slope=0.005
Boundary for River Rch & Prof#=DEVILS JUMP CREE,Reach-1,7
Up Type=0
Dn Type=3
Dn Slope=0.005

--- DEVILS JUMP CREEK TRIBUTARY 14 1.g01 (geometry) ---

Geom Title=Existing Conditions
Program Version=4.10

River Reach=DEVILS JUMP CREE,Reach-1
Reach XY= 30
       3549979.2     10349262.98        3550106.     10349153.92
      3550125.98     10349013.26      3550161.44     10348966.36
      3550211.11     10348852.19      3550162.81     10348676.94
      3550155.08     10348551.69      3550168.96     10348513.35
       3550162.2     10348436.78      3550179.36     10348346.15
      3550172.52     10348291.62      3550180.52     10348236.65
       3550154.7     10348185.63      3550151.78     10348151.79
       3550153.3     10348002.14      3550190.96     10347841.17
      3550192.81     10347736.93      3550205.38       10347663.
      3550228.71     10347610.23       3550248.3     10347524.78
      3550296.38     10347463.98      3550334.81     10347382.76
       3550378.4     10347320.11      3550472.42     10347036.77
      3550527.29     10346949.08      3550569.47     10346900.53
      3550598.16     10346829.53      3550627.42     10346799.35
      3550628.81     10346759.18      3550662.11     10346731.64

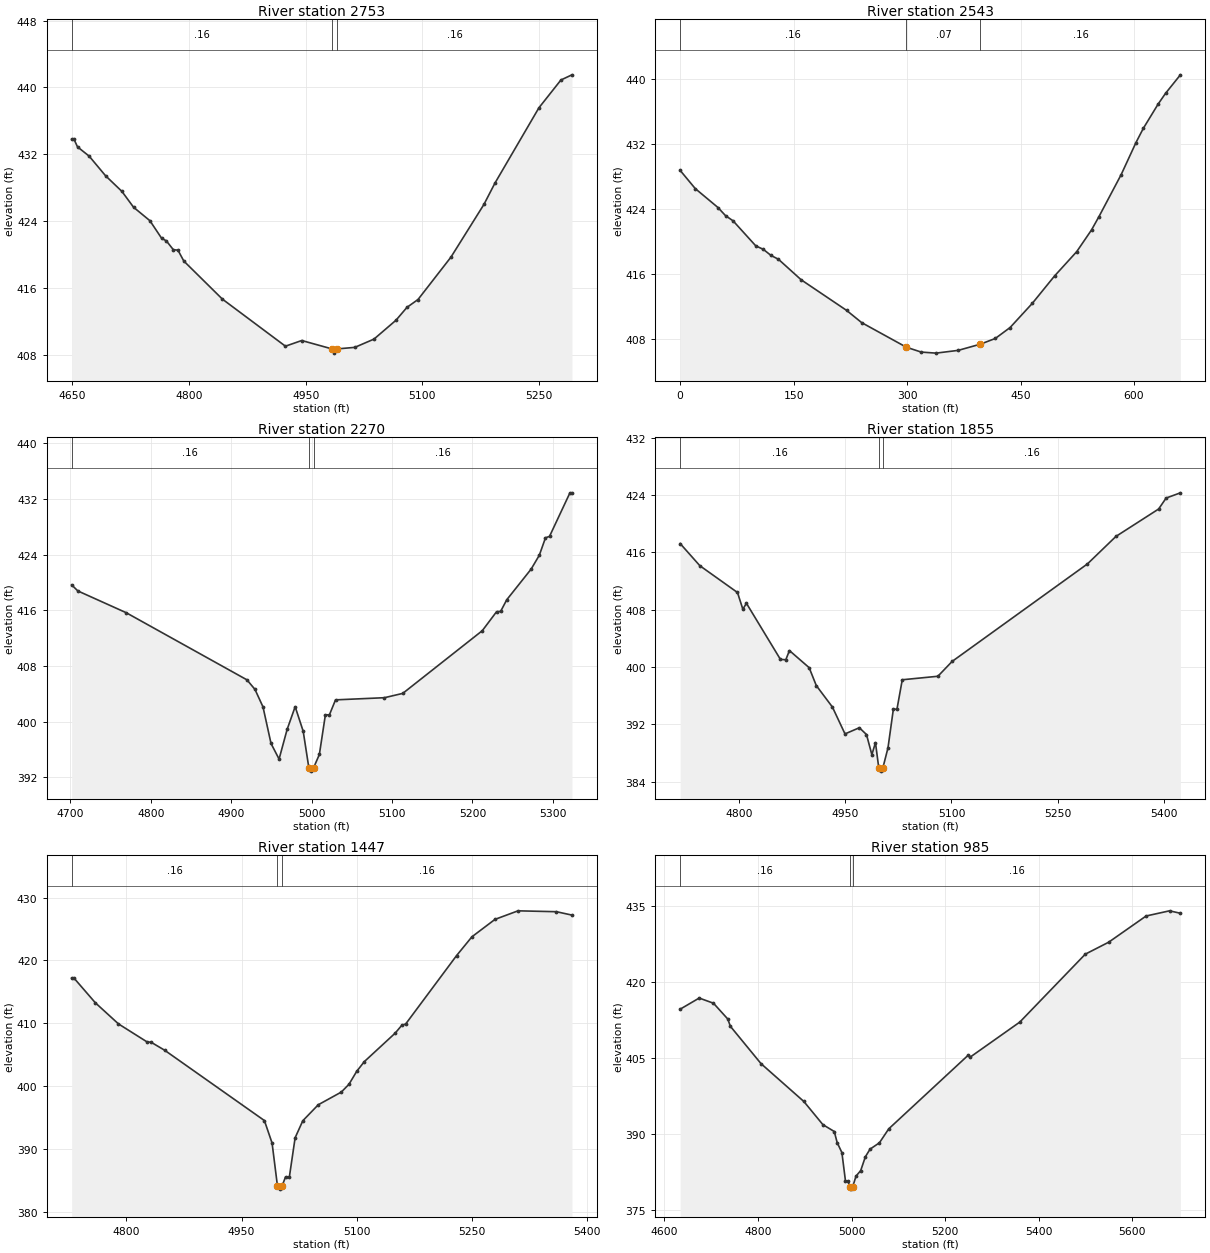
Type RM Length L Ch R = 1 ,2753    ,210,210,210
BEGIN DESCRIPTION:
DEVILS JUMP CREEK TRIBUTARY 14.1 6.0
END DESCRIPTION:
XS GIS Cut Line= 3
      3550292.08     10349441.63      3549992.11     10349241.64
      3549792.09     10349041.62
#Sta/Elev= 30
    4649  433.78    4652  433.78  4656.5  432.87  4671.5  431.76  4692.5  429.42
  4713.6  427.54  4728.6  425.64  4749.6  424.03  4764.7  421.92  4770.7  421.62
  4779.7  420.56  4785.7   420.5  4793.2   419.2  4842.8  414.64  4923.9     409
  4944.9  409.68    4984  408.67  4986.7  408.17    4990  408.67  5013.1  408.86
  5037.8  409.85  5066.1  412.11  5080.2  413.65  5094.4  414.59  5136.8  419.67
  5179.2  425.98  5193.4  428.54  5249.9  437.55  5278.2  440.88  5292.4   441.5
#Mann= 3 ,-1 , 0
    4649     .16       0    4984     .07       0    4990     .16       0
Bank Sta=4984,4990
XS Rating Curve= 0 ,0
Exp/Cntr=0.3,0.1

Type RM Length L Ch R = 1 ,2543    ,273,273,273
XS GIS Cut Line= 3
     3550363.209    10349304.538     3550199.364     10349105.97
     3549802.228     10349026.76
#Sta/Elev= 30
       0428.719719.99672426.4764 49.9918424.147659.99016423.145869.98853 422.507
 99.9836419.4264 109.982418.9949119.9803418.2554129.9787417.7726159.9738415.2497
219.9639411.4867239.9606409.9757299.1129406.9444318.6906406.3491338.2683406.2199
367.6349406.5607397.0016407.3265416.5793 408.023 436.157409.3686465.5237412.3459
494.8903415.7129524.2569418.7154543.8346421.3899553.6235423.0232582.9901428.1933
602.5679432.1413612.3567433.9041631.9344436.8909641.7233438.2094661.3011440.4806
#Mann= 3 , 0 , 0
       0     .16       0299.1129     .07       0397.0016     .16       0
Bank Sta=299.1129,397.0016
XS Rating Curve= 0 ,0
Exp/Cntr=0.3,0.1

Type RM Length L Ch R = 1 ,2270    ,415,415,415
BEGIN DESCRIPTION:
DEVILS JUMP CREEK TRIBUTARY 14.1 5.0
END DESCRIPTION:
XS GIS Cut Line= 3
      3550509.78     10348828.12      3550192.11     10348841.64
       3549892.1     10348891.64
#Sta/Elev= 30
  4701.7  419.67  4709.4   418.8  4769.4  415.68  4919.6  406.03  4929.6  404.66
  4939.6  402.14  4949.6  396.88  4959.6  394.64  4969.6   398.9  4979.6  402.17
  4989.6  398.64  4996.6  393.41  4999.4  392.91  5002.6  393.41  5009.7   395.3
  5017.2     401  5022.2     401  5029.8  403.15  5090.6  403.46  5113.4  404.08
  5212.3  413.09    5230  415.81  5235.1  415.86  5242.7  417.53  5273.1  421.95
  5283.2  423.93  5290.9  426.44  5295.9  426.64  5321.3   432.9  5323.8   432.9
#Mann= 3 ,-1 , 0
  4701.7     .16       0  4996.6     .07       0  5002.6     .16       0
Bank Sta=4996.6,5002.6
XS Rating Curve= 0 ,0
Exp/Cntr=0.3,0.1

Type RM Length L Ch R = 1 ,1855    ,408,408,408
BEGIN DESCRIPTION:
DEVILS JUMP CREEK TRIBUTARY 14.1 4.0
END DESCRIPTION:
XS GIS Cut Line= 3
      3550442.11     10348391.64      3550142.11     10348441.64
       3549741.5     10348489.58
#Sta/Elev= 30
  4716.2  417.24  4744.1  414.14  4797.3   410.4  4804.9  408.07    4810  408.89
  4858.1  401.05  4865.7  401.01  4870.8  402.29  4898.7   399.9  4908.8   397.4
  4931.6   394.4  4949.4  390.65  4969.7  391.51  4979.8  390.56  4987.4  387.75
  4992.5  389.43  4997.1  385.95  4999.8  385.45  5003.1  385.95  5010.2   388.7
  5017.8   394.1  5022.9   394.1  5030.4  398.21  5080.8   398.7  5100.9  400.77
  5292.3  414.39  5332.6  418.23    5393  422.06  5403.6  423.59  5423.8  424.32
#Mann= 3 ,-1 , 0
  4716.2     .16       0  4997.1     .07       0  5003.1     .16       0
Bank Sta=4997.1,5003.1
XS Rating Curve= 0 ,0
Exp/Cntr=0.3,0.1

Type RM Length L Ch R = 1 ,1447    ,462,462,462
BEGIN DESCRIPTION:
DEVILS JUMP CREEK TRIBUTARY 14.1 3.0
END DESCRIPTION:
XS GIS Cut Line= 3
      3550422.94     10348033.85      3550142.11     10348041.64
      3549771.94     10348029.51
#Sta/Elev= 30
  4728.9   417.2  4731.8   417.2  4759.7  413.26  4789.8   409.9  4827.2  407.02
  4832.2  406.99  4849.8  405.72  4979.8  394.52  4989.8  390.94  4996.8  384.11
  4999.6  383.61  5002.8  384.11  5007.3  385.54  5012.3  385.54  5019.8  391.78
  5029.8  394.49  5049.9  397.03  5079.9  399.05  5089.9  400.29  5099.9  402.34
  5109.9   403.9  5149.9  408.41  5158.7  409.68  5163.7  409.88    5230  420.77
    5250  423.76    5280  426.53    5310  427.89    5360  427.75  5380.2  427.21
#Mann= 3 ,-1 , 0
  4728.9     .16       0  4996.8     .07       0  5002.8     .16       0
Bank Sta=4996.8,5002.8
XS Rating Curve= 0 ,0
Exp/Cntr=0.3,0.1

Type RM Length L Ch R = 1 ,985     ,454,454,454
BEGIN DESCRIPTION:
DEVILS JUMP CREEK TRIBUTARY 14.1 2.0
END DESCRIPTION:
XS GIS Cut Line= 3
       3550592.2     10347656.24      3550242.11     10347591.64
      3549528.84     10347578.12
#Sta/Elev= 30
  4633.6  414.57  4674.4  416.77  4704.9  415.75  4735.4  412.64    4741   411.2
  4806.6  403.82  4898.1  396.36  4938.8  391.79  4963.1  390.44  4969.3  388.25
  4979.4  386.28  4987.1  380.63  4992.1  380.63  4996.6  379.57  4999.4  379.07
  5002.6  379.57  5009.6  381.64  5019.6  382.73  5029.6  385.46  5039.6  386.96
  5059.6  388.21  5079.6  390.97    5249  405.46    5254  405.14  5359.7  412.03
  5499.7  425.43  5549.7  427.79  5629.7  432.96  5679.7  433.98    5703   433.5
#Mann= 3 ,-1 , 0
  4633.6     .16       0  4996.6     .07       0  5002.6     .16       0
Bank Sta=4996.6,5002.6
XS Rating Curve= 0 ,0
Exp/Cntr=0.3,0.1

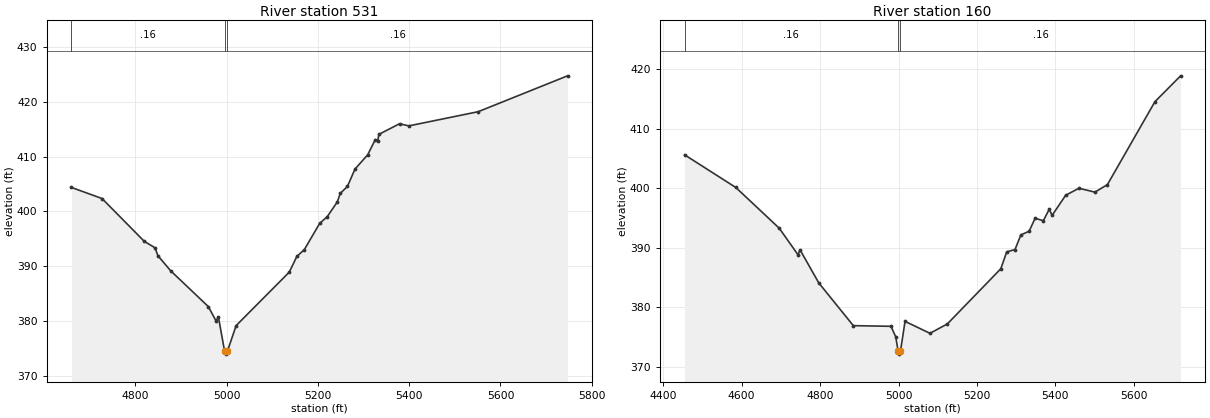
Type RM Length L Ch R = 1 ,531     ,371,371,371
BEGIN DESCRIPTION:
Mapping XS 8636a8ab
END DESCRIPTION:
XS GIS Cut Line= 4
      3550664.94     10347412.08      3550556.46     10347255.87
      3550126.77     10347034.51      3549718.78     10346969.41
#Sta/Elev= 30
  4660.2  404.38  4727.1  402.36  4819.6  394.55  4843.3  393.36  4849.4  391.93
  4877.8  389.14    4960  382.63  4976.6  380.05  4982.2   380.7  4995.7  374.45
  4998.5  373.95  5001.7  374.45  5020.9  379.16  5137.4  388.93  5153.9  391.79
  5170.3  393.03    5204  397.83  5220.4  399.04  5242.6  401.75    5249  403.29
  5264.7  404.57  5281.3  407.74  5309.1  410.34  5325.6   413.1  5331.2  412.95
  5333.6  414.07  5378.8  416.01  5399.2  415.62  5551.1  418.21  5746.9  424.76
#Mann= 3 ,-1 , 0
  4660.2     .16       0  4995.7     .07       0  5001.7     .16       0
Bank Sta=4995.7,5001.7
XS Rating Curve= 0 ,0
Exp/Cntr=0.3,0.1

Type RM Length L Ch R = 1 ,160     ,0,0,0
BEGIN DESCRIPTION:
DEVILS JUMP CREEK TRIBUTARY 14.1 1.0
END DESCRIPTION:
XS GIS Cut Line= 4
      3550732.25      10347351.4      3550680.16     10346921.67
      3550259.15     10346643.89      3549937.95     10346578.78
#Sta/Elev= 30
  4454.3  405.65  4585.1  400.15  4695.8   393.3  4743.7  388.83  4748.8  389.67
  4796.5  384.11  4884.7  376.91  4980.7   376.8  4992.9  375.03    4999  372.62
  5001.7  372.12    5005  372.62  5016.6  377.63  5080.2  375.62  5124.5   377.2
  5260.8  386.48  5275.9  389.32    5297  389.71    5312  392.18  5333.1  392.79
  5348.2  394.97  5369.2  394.56  5384.3  396.49  5391.6  395.46  5426.2  398.84
    5460  400.02  5500.8  399.37  5532.6  400.63  5653.8  414.58  5719.3  418.93
#Mann= 3 ,-1 , 0
  4454.3     .16       0    4999     .07       0    5005     .16       0
Bank Sta=4999,5005
XS Rating Curve= 0 ,0
Exp/Cntr=0.3,0.1

Chan Stop Cuts=-1
Use User Specified Reach Order=0
Composite Channel Slope=5