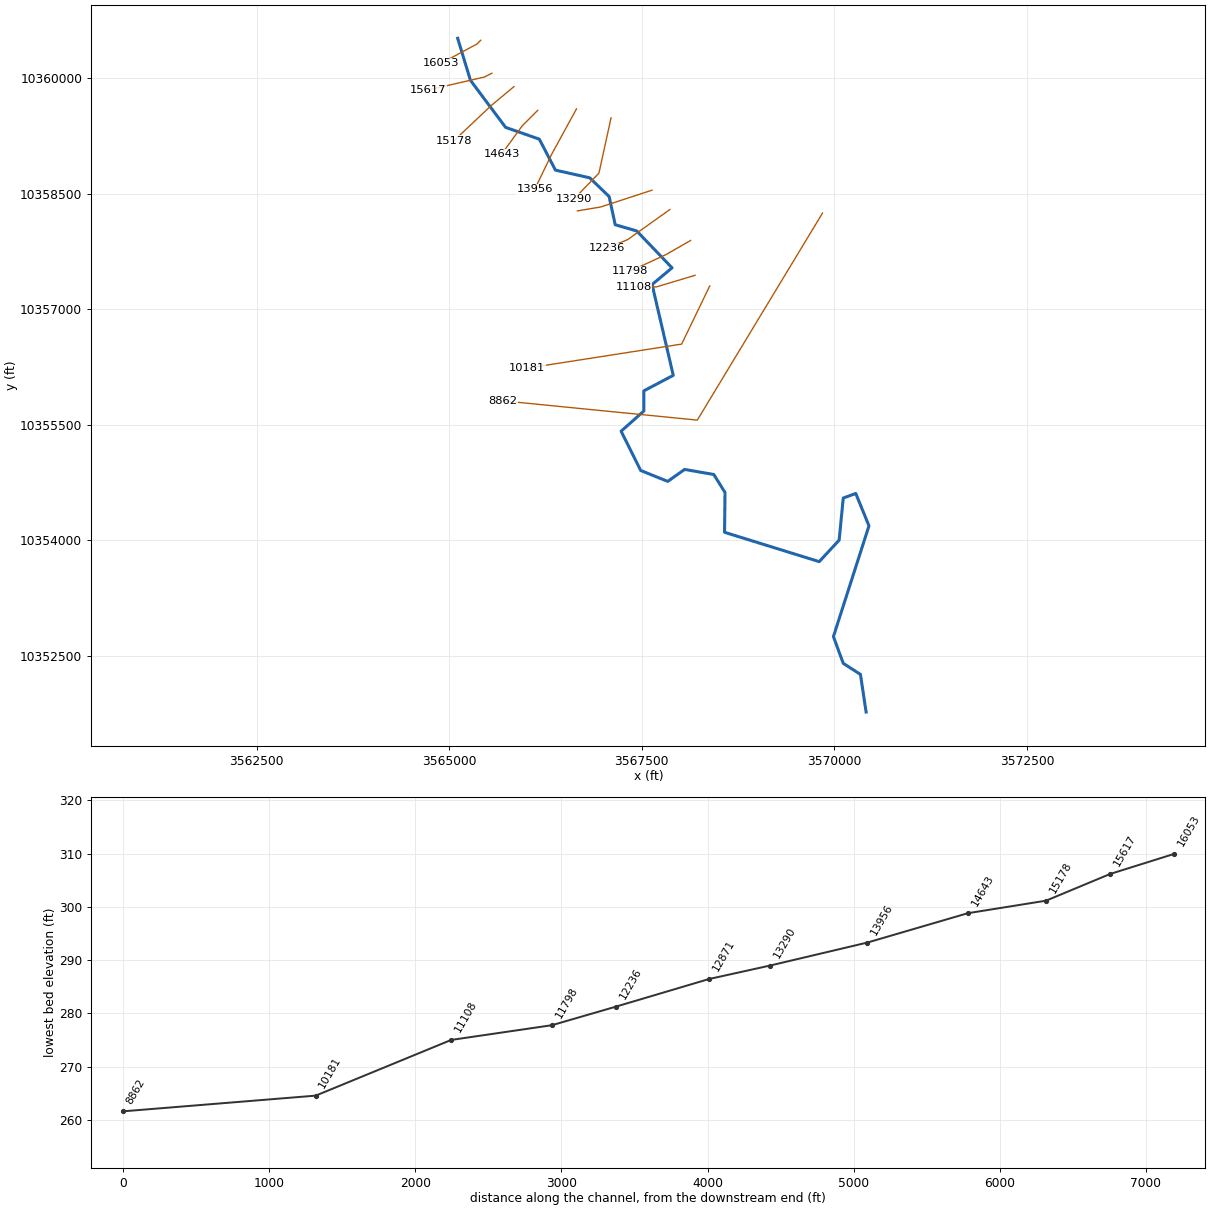
--- DEVILS JUMP CREEK TRIBUTARY 2 2.prj (project) ---

Proj Title=DEVILS JUMP CREEK TRIBUTARY 2 2 Base Level Engineering
Current Plan=p01
Default Exp/Contr=0.3,0.1
English Units
Geom File=g01
Flow File=f01
Plan File=p01
Y Axis Title=Elevation
X Axis Title(PF)=Main Channel Distance
X Axis Title(XS)=Station
BEGIN DESCRIPTION:
DEVILS JUMP CREEK TRIBUTARY 2 2
END DESCRIPTION:
DSS Export Rating Curves= 0
DSS Export Rating Curve Sorted= 0
DSS Export Volume Flow Curves= 0
DXF OffsetX= 0
DXF OffsetY= 0
DXF ScaleX= 1
DXF ScaleY= 10

--- DEVILS JUMP CREEK TRIBUTARY 2 2.p01 (plan) ---

Plan Title=Multiple Run
Short Identifier=Multiple
Geom File=g01
Flow File=f01
Subcritical Flow
K Sum by GR= 0
Std Step Tol= 0.01
Critical Tol= 0.01
Num of Std Step Trials= 20
Max Error Tol= 0.3
Flow Tol Ratio= 0.001
Split Flow NTrial= 30
Split Flow Tol= 0.02
Split Flow Ratio= 0.02
Log Output Level= 0
Friction Slope Method= 1
Unsteady Friction Slope Method= 2
Unsteady Bridges Friction Slope Method= 1
Parabolic Critical Depth
Global Vel Dist=  1 , 1 , 1
Global Log Level= 0
CheckData=True
Encroach Param= -1, 0, 0, 0
BEGIN DESCRIPTION:
Multiple Run
END DESCRIPTION:

--- DEVILS JUMP CREEK TRIBUTARY 2 2.f01 (steady flow) ---

Flow Title=Multiple
Program Version=4.10
Number of Profiles= 7
Profile Names=10-year,25-year,50-year,1pct_min,100-year,1pct_plu,500-year
River Rch & RM=DEVILS JUMP CREE,Reach-1         ,16053
     897    1234    1512    1354    1832    2477    2677
River Rch & RM=DEVILS JUMP CREE,Reach-1         ,10181
    1654    2336    2912    2644    3576    4837    5383
River Rch & RM=DEVILS JUMP CREE,Reach-1         ,8862
    1654    2336    2912    2644    3576    4837    5383
Boundary for River Rch & Prof#=DEVILS JUMP CREE,Reach-1         , 1
Up Type= 0
Dn Type= 3
Dn Slope=0.005
Boundary for River Rch & Prof#=DEVILS JUMP CREE,Reach-1         , 2
Up Type= 0
Dn Type= 3
Dn Slope=0.005
Boundary for River Rch & Prof#=DEVILS JUMP CREE,Reach-1         , 3
Up Type= 0
Dn Type= 3
Dn Slope=0.005
Boundary for River Rch & Prof#=DEVILS JUMP CREE,Reach-1         , 4
Up Type= 0
Dn Type= 3
Dn Slope=0.005
Boundary for River Rch & Prof#=DEVILS JUMP CREE,Reach-1         , 5
Up Type= 0
Dn Type= 3
Dn Slope=0.005
Boundary for River Rch & Prof#=DEVILS JUMP CREE,Reach-1         , 6
Up Type= 0
Dn Type= 3
Dn Slope=0.005
Boundary for River Rch & Prof#=DEVILS JUMP CREE,Reach-1         , 7
Up Type= 0
Dn Type= 3
Dn Slope=0.005
DSS Import GetInterval= 0
DSS Import GetPeak= 0
DSS Import FillOption= 0

--- DEVILS JUMP CREEK TRIBUTARY 2 2.g01 (geometry) ---

Geom Title=Existing Conditions
Program Version=4.10

River Reach=DEVILS JUMP CREE,Reach-1
Reach XY= 30
      3565110.54     10360518.59      3565276.12     10359973.89
      3565732.55     10359362.16      3566170.47     10359208.95
      3566379.66     10358807.12      3566824.72     10358706.93
      3567076.57     10358464.23      3567155.74     10358098.04
      3567435.04     10358017.08      3567893.29     10357538.32
      3567634.29      10357321.7      3567909.08     10356142.81
      3567527.37     10355941.44       3567526.7     10355679.41
      3567232.17     10355417.55      3567486.36     10354907.45
      3567836.76     10354766.36       3568056.6     10354921.21
      3568434.72     10354856.01      3568580.85     10354621.93
      3568574.68     10354105.41      3569803.53     10353724.44
      3570062.15     10354003.49      3570115.77     10354550.26
      3570277.94     10354609.51       3570449.5     10354189.14
      3569987.94     10352751.53      3570115.76     10352403.76
      3570338.86     10352260.22      3570412.11     10351771.64

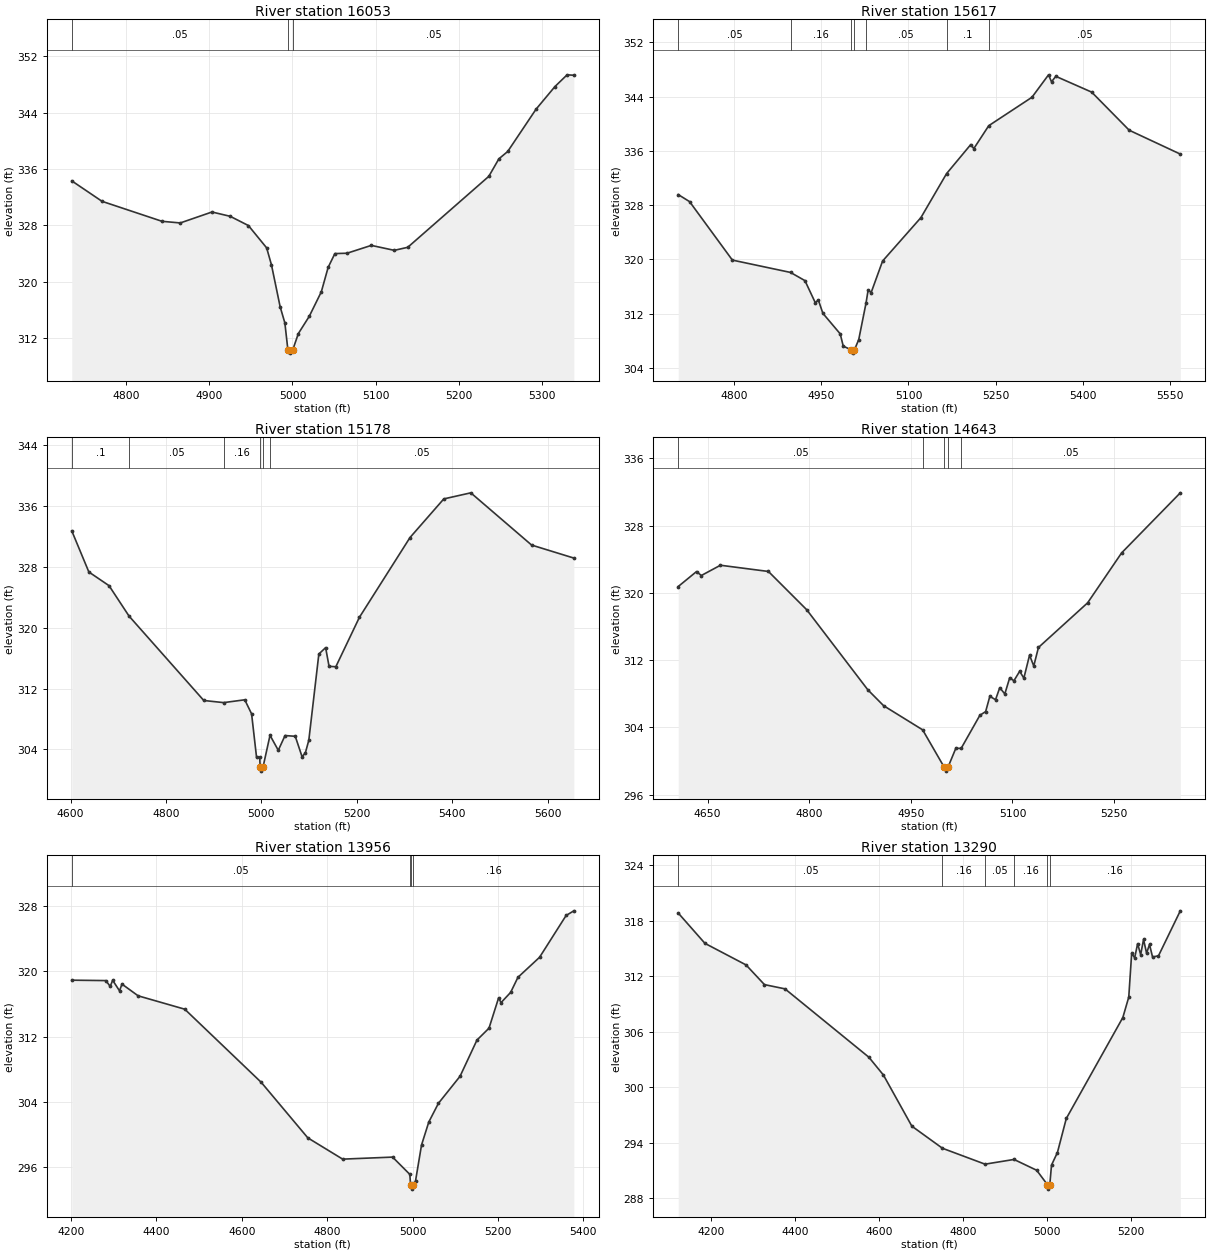
Type RM Length L Ch R = 1 ,16053   ,436,436,436
BEGIN DESCRIPTION:
DEVILS JUMP CREEK TRIBUTARY 2.2 19.0
END DESCRIPTION:
XS GIS Cut Line= 3
      3565411.15     10360494.09      3565361.18     10360444.11
      3564892.08     10360191.63
#Sta/Elev= 30
  4734.8  334.32  4771.2  331.42  4843.3  328.59  4865.2  328.36  4903.3  329.91
  4925.2   329.3  4947.1  327.99    4969  324.83  4974.8  322.42  4985.2   316.5
  4990.9   314.2  4994.5  310.42  4997.2  309.92  5000.5  310.42  5007.1  312.69
  5020.2  315.13  5034.7   318.6  5042.9  322.06    5051  324.02  5065.6  324.07
  5094.8  325.18  5122.4  324.48  5138.6  324.91    5236  334.96  5248.1  337.44
  5258.7  338.48  5292.7  344.46  5315.5  347.68  5330.1  349.34  5338.2  349.28
#Mann= 3 ,-1 , 0
  4734.8     .05       0  4994.5    .035       0  5000.5     .05       0
Bank Sta=4994.5,5000.5
XS Rating Curve= 0 ,0
Exp/Cntr=0.3,0.1

Type RM Length L Ch R = 1 ,15617   ,439,439,439
BEGIN DESCRIPTION:
DEVILS JUMP CREEK TRIBUTARY 2.2 18.0
END DESCRIPTION:
XS GIS Cut Line= 3
      3565555.33     10360064.95      3565455.35     10360014.96
      3564723.68     10359846.46
#Sta/Elev= 30
  4704.4  329.55  4723.9  328.51  4797.4  319.89  4897.3  318.07  4922.1  316.86
  4939.9   313.6  4945.1  314.01  4952.9  312.04  4982.7  309.01  4987.9   307.2
  5001.2  306.67    5004  306.17  5007.2  306.67  5014.5  308.16    5027  313.53
  5030.7   315.5  5035.8  315.09  5055.5  319.75  5121.4  326.16  5165.4  332.64
    5207  336.93  5212.2  336.33  5237.9  339.71  5312.1   343.9  5340.6  347.21
  5345.7  346.18  5353.1  346.99  5414.7  344.66  5479.2  339.04    5567  335.52
#Mann= 7 ,-1 , 0
  4704.4     .05       0  4897.3     .16       0  5001.2     .07       0
  5007.2     .16       0    5027     .05       0  5165.4      .1       0
  5237.9     .05       0
Bank Sta=5001.2,5007.2
XS Rating Curve= 0 ,0
Exp/Cntr=0.3,0.1

Type RM Length L Ch R = 1 ,15178   ,535,535,535
BEGIN DESCRIPTION:
DEVILS JUMP CREEK TRIBUTARY 2.2 17.0
END DESCRIPTION:
XS GIS Cut Line= 3
      3565842.07     10359891.62      3565542.11     10359641.64
      3565061.08     10359187.51
#Sta/Elev= 30
  4602.6  332.75  4638.4  327.34  4680.7  325.54  4722.6  321.54  4879.2  310.44
  4920.8  310.16  4965.1  310.53  4979.4  308.68  4989.8  302.95  4996.5  302.95
  4997.2  301.65  4999.9  301.15  5003.2  301.65    5018  305.86  5035.3  303.89
  5049.5  305.83  5070.9  305.73  5085.1  303.05    5092  303.54  5099.3  305.22
  5120.3  316.55  5134.5  317.39  5141.7  314.93  5155.9  314.88  5205.3  321.38
  5311.3  331.87  5382.1  336.95  5438.7  337.75  5566.1  330.88  5654.6  329.17
#Mann= 6 ,-1 , 0
  4602.6      .1       0  4722.6     .05       0  4920.8     .16       0
  4997.2     .07       0  5003.2     .16       0    5018     .05       0
Bank Sta=4997.2,5003.2
XS Rating Curve= 0 ,0
Exp/Cntr=0.3,0.1

Type RM Length L Ch R = 1 ,14643   ,687,687,687
BEGIN DESCRIPTION:
DEVILS JUMP CREEK TRIBUTARY 2.2 16.0
END DESCRIPTION:
XS GIS Cut Line= 3
      3566149.49     10359582.42      3565949.52     10359382.45
      3565679.05      10359012.6
#Sta/Elev= 30
  4606.7  320.75  4633.7  322.53  4640.8  322.06    4669  323.28  4739.8  322.54
  4796.3  317.99  4886.5  308.47  4909.8  306.58  4967.4  303.71    4999   299.3
  5001.8   298.8    5005   299.3  5016.4  301.52  5024.2   301.5  5051.9  305.44
  5060.4  305.88  5066.6   307.7    5075  307.29  5081.2  308.72  5088.7  307.98
  5095.9   309.9  5102.1  309.54  5110.6  310.67  5116.8  309.86  5125.2  312.59
  5131.4   311.3  5138.3   313.5  5210.9  318.81  5261.1  324.75  5347.7  331.89
#Mann= 5 ,-1 , 0
  4606.7     .05       0  4967.4     .16       0    4999     .07       0
    5005     .16       0  5024.2     .05       0
Bank Sta=4999,5005
XS Rating Curve= 0 ,0
Exp/Cntr=0.3,0.1

Type RM Length L Ch R = 1 ,13956   ,666,666,666
BEGIN DESCRIPTION:
DEVILS JUMP CREEK TRIBUTARY 2.2 14.0
END DESCRIPTION:
XS GIS Cut Line= 3
      3566652.65      10359601.4      3566327.97     10359007.35
      3566110.45      10358557.8
#Sta/Elev= 30
  4201.5  318.93  4281.2  318.88  4291.6  318.17  4297.3  318.92  4313.4  317.62
  4319.1  318.45    4357  317.01  4466.2  315.37  4645.5  306.39  4754.6  299.58
  4836.2  296.97  4953.2  297.22  4993.6   295.1  4995.4  293.79  4998.1  293.29
  5001.4  293.79    5007  294.31    5021   298.7    5038  301.52  5060.6  303.82
  5111.3  307.14  5150.9  311.58  5179.1  313.04  5201.7  316.77  5207.2  316.17
  5229.8  317.43  5246.9  319.28  5297.6  321.74  5359.8  326.87  5377.9  327.44
#Mann= 4 ,-1 , 0
  4201.5     .05       0  4993.6     .16       0  4995.4     .07       0
  5001.4     .16       0
Bank Sta=4995.4,5001.4
XS Rating Curve= 0 ,0
Exp/Cntr=0.3,0.1

Type RM Length L Ch R = 1 ,13290   ,419,419,419
BEGIN DESCRIPTION:
DEVILS JUMP CREEK TRIBUTARY 2.2 13.0
END DESCRIPTION:
XS GIS Cut Line= 3
      3567101.58     10359484.84      3566944.17     10358767.72
      3566624.13     10358436.04
#Sta/Elev= 30
  4122.8  318.83  4186.4  315.55  4284.2  313.22    4328  311.09  4376.9  310.63
  4576.5  303.24  4611.2  301.31  4678.9  295.78  4751.7  293.39  4853.1  291.67
  4922.1  292.18    4976  291.01  5001.3  289.47  5004.1  288.97  5007.3  289.47
  5011.3  291.57  5025.4  292.93  5046.5  296.61  5181.1  307.53  5195.2  309.74
  5202.1  314.47  5209.3  313.99  5216.3  315.52  5223.5  314.33  5230.4  315.97
  5237.6  314.49  5244.6  315.43  5251.8  314.08  5265.9   314.2  5317.9  319.07
#Mann= 6 ,-1 , 0
  4122.8     .05       0  4751.7     .16       0  4853.1     .05       0
  4922.1     .16       0  5001.3     .07       0  5007.3     .16       0
Bank Sta=5001.3,5007.3
XS Rating Curve= 0 ,0
Exp/Cntr=0.3,0.1

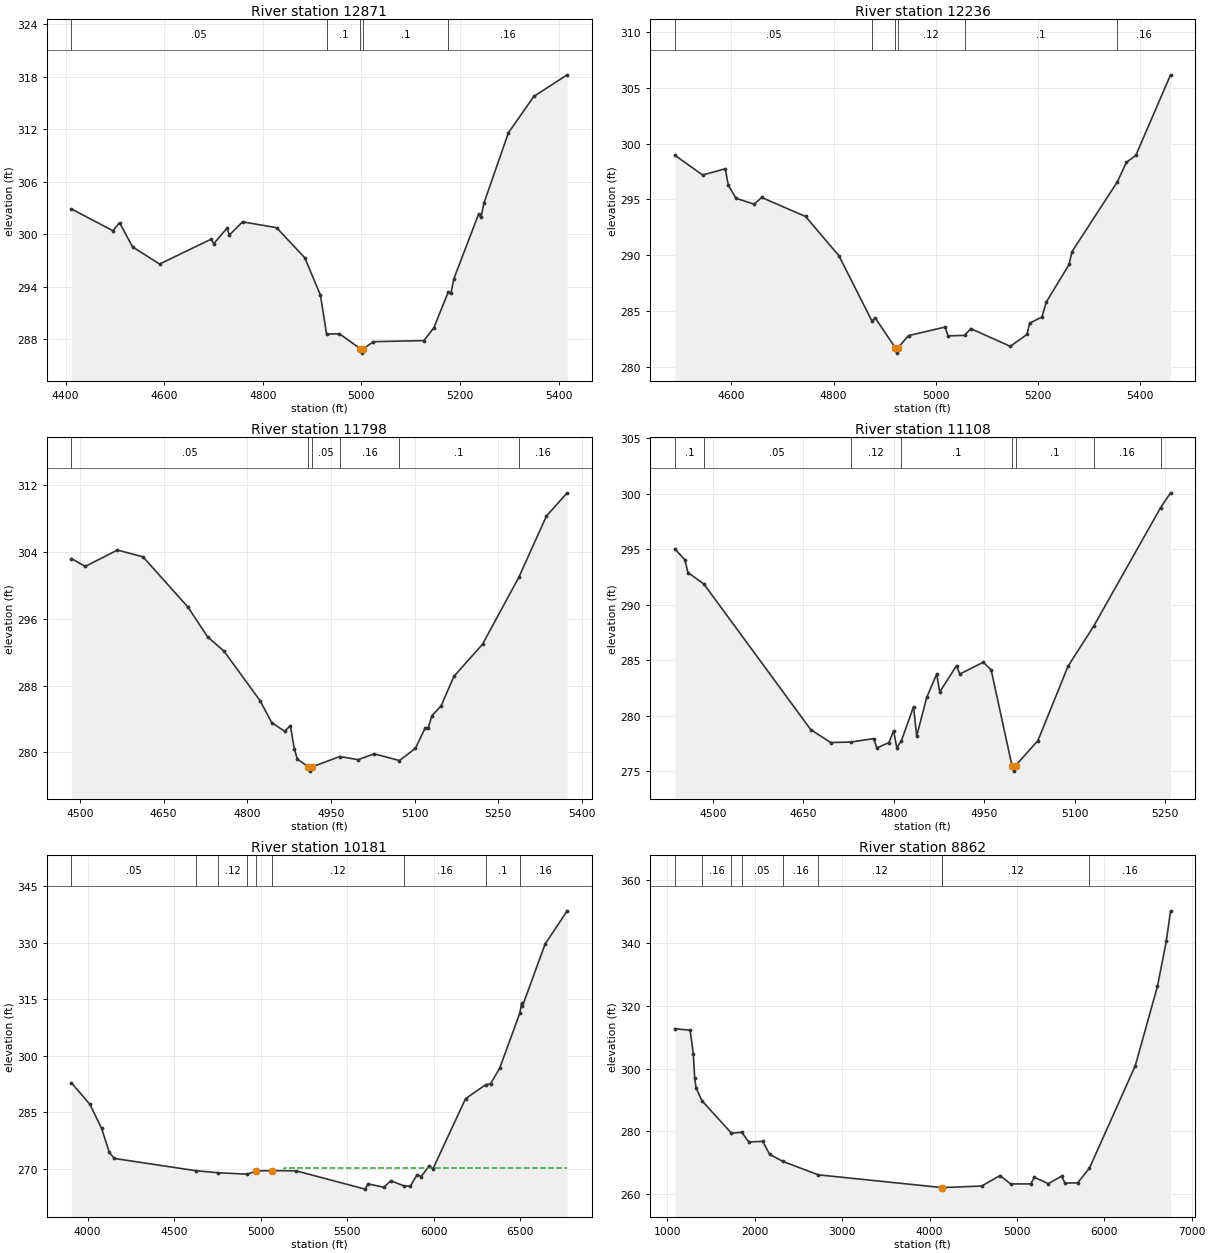
Type RM Length L Ch R = 1 ,12871   ,635,635,635
BEGIN DESCRIPTION:
DEVILS JUMP CREEK TRIBUTARY 2.2 12.0
END DESCRIPTION:
XS GIS Cut Line= 3
      3567632.14     10358546.19      3566963.84     10358327.51
      3566665.43     10358277.78
#Sta/Elev= 30
  4411.8  302.89    4496   300.4  4509.3  301.33  4535.9  298.55  4590.7   296.6
  4695.2  299.44  4700.5  298.92  4727.1  300.68  4732.3  299.92  4758.9  301.42
  4827.9  300.75  4885.3  297.31  4916.9  293.05  4929.4   288.6  4955.3  288.64
  4998.1  286.93  5000.8  286.43  5004.1  286.93  5024.3  287.74  5126.9  287.86
  5147.1  289.34  5176.3  293.41  5181.9  293.32  5187.7  294.94  5237.6  302.27
  5242.7  301.93  5248.5  303.54  5298.4   311.6  5349.9  315.74  5417.5   318.2
#Mann= 5 ,-1 , 0
  4411.8     .05       0  4929.4      .1       0  4998.1     .07       0
  5004.1      .1       0  5176.3     .16       0
Bank Sta=4998.1,5004.1
XS Rating Curve= 0 ,0
Exp/Cntr=0.3,0.1

Type RM Length L Ch R = 1 ,12236   ,438,438,438
BEGIN DESCRIPTION:
DEVILS JUMP CREEK TRIBUTARY 2.2 11.0
END DESCRIPTION:
XS GIS Cut Line= 3
      3567865.28     10358295.46      3567317.29     10357904.87
      3567042.11     10357791.65
#Sta/Elev= 30
  4489.1  298.96  4543.5  297.19  4587.8  297.75  4593.9  296.27  4608.7  295.11
  4644.3  294.58  4659.1  295.18  4745.1  293.48  4810.3  289.97  4874.8  284.15
  4881.6   284.4  4920.4  281.76  4923.1  281.26  4926.4  281.76  4946.7  282.83
    5018  283.59  5024.2   282.8  5056.2  282.85  5068.4  283.45  5145.9  281.87
  5178.4  282.93  5183.8  283.94  5207.7  284.49  5216.3  285.83    5261  289.19
  5266.4  290.32  5355.7   296.6  5373.1  298.32  5391.6  298.95  5459.6  306.15
#Mann= 6 ,-1 , 0
  4489.1     .05       0  4874.8     .12       0  4920.4     .07       0
  4926.4     .12       0  5056.2      .1       0  5355.7     .16       0
Bank Sta=4920.4,4926.4
XS Rating Curve= 0 ,0
Exp/Cntr=0.3,0.1

Type RM Length L Ch R = 1 ,11798   ,690,690,690
BEGIN DESCRIPTION:
DEVILS JUMP CREEK TRIBUTARY 2.2 9.0
END DESCRIPTION:
XS GIS Cut Line= 3
      3568133.53     10357893.23      3567818.68     10357712.48
      3567342.11     10357491.64
#Sta/Elev= 30
    4485  303.21  4509.7  302.27  4567.4  304.23  4613.2  303.42  4693.8   297.4
  4728.8  293.85  4758.5  292.12  4823.2  286.18  4843.9  283.56  4866.9  282.55
  4877.3  283.21  4884.3  280.45  4889.8  279.21  4909.7  278.27  4912.5  277.77
  4915.7  278.27  4965.9  279.52  4998.6  279.14  5027.3  279.84  5072.8  279.04
  5101.5  280.51  5118.9  282.96  5124.4  282.97  5130.8  284.39  5147.4  285.58
  5170.3  289.11  5221.6  292.96  5286.7  300.98  5336.2  308.31  5373.3  311.08
#Mann= 6 ,-1 , 0
    4485     .05       0  4909.7     .07       0  4915.7     .05       0
  4965.9     .16       0  5072.8      .1       0  5286.7     .16       0
Bank Sta=4909.7,4915.7
XS Rating Curve= 0 ,0
Exp/Cntr=0.3,0.1

Type RM Length L Ch R = 1 ,11108   ,927,927,927
BEGIN DESCRIPTION:
DEVILS JUMP CREEK TRIBUTARY 2.2 8.0
END DESCRIPTION:
XS GIS Cut Line= 3
      3568192.15     10357441.65      3567692.11     10357291.64
      3567392.06     10357291.64
#Sta/Elev= 30
  4436.9  295.04  4453.5  294.05  4458.7   292.9  4485.1  291.87  4662.3  278.74
  4695.3  277.58  4728.5  277.62  4766.7  277.93  4771.9  277.09  4791.9  277.57
  4799.7  278.64    4805  277.11  4812.8  277.76  4832.8  280.81    4838  278.17
  4854.6  281.64  4871.1  283.75  4876.3  282.14  4904.1  284.51  4909.4  283.75
  4948.5  284.82  4961.5  284.12    4996   275.5  4998.7     275    5002   275.5
    5039  277.75    5089  284.46  5131.5  288.07  5242.4  298.75    5259  300.09
#Mann= 8 ,-1 , 0
  4436.9      .1       0  4485.1     .05       0  4728.5     .12       0
  4812.8      .1       0    4996     .07       0    5002      .1       0
  5131.5     .16       0  5242.4      .1       0
Bank Sta=4996,5002
XS Rating Curve= 0 ,0
Exp/Cntr=0.3,0.1

Type RM Length L Ch R = 1 ,10181   ,1319,1319,1319
BEGIN DESCRIPTION:
DEVILS JUMP CREEK TRIBUTARY 2.2 6.0
END DESCRIPTION:
XS GIS Cut Line= 3
      3568382.64     10357303.81      3568018.07     10356548.63
      3566014.53     10356236.39
#Sta/Elev= 30
  3906.4  292.77  4012.7  287.08  4080.5   280.7  4125.7  274.27  4153.9  272.69
  4626.1  269.43  4755.7  268.89  4923.5  268.51  4973.7  269.37  5064.8  269.46
  5206.4  269.39  5603.9  264.54  5621.4  265.92  5712.5  265.05    5753  266.75
  5830.2  265.38  5865.6  265.31  5904.8  268.36  5928.4  267.89  5975.6  270.76
  5996.3  269.91  6184.8  288.55  6300.8  292.26  6329.8   292.5  6383.5  296.79
  6499.5  311.38  6509.1  313.87  6514.2  313.19  6644.9   329.6  6772.7  338.46
#Mann= 9 ,-1 , 0
  3906.4     .05       0  4626.1     .16       0  4755.7     .12       0
  4923.5     .16       0  4973.7     .07       0  5064.8     .12       0
  5830.2     .16       0  6300.8      .1       0  6499.5     .16       0
#XS Ineff= 2 , 0
                         5132.67          270.21
Permanent Ineff=
       F       F
#Block Obstruct= 2 , 0
                         5021.31          268.81
Bank Sta=4973.7,5064.8
XS Rating Curve= 0 ,0
Exp/Cntr=0.3,0.1

Type RM Length L Ch R = 1 ,8862    ,0,0,0
BEGIN DESCRIPTION:
DEVILS JUMP CREEK TRIBUTARY 2.2 1.0
END DESCRIPTION:
XS GIS Cut Line= 3
      3569846.18     10358249.13       3568221.2     10355561.65
      3565700.33     10355811.65
#Sta/Elev= 30
  1084.7   312.7  1259.9  312.25  1296.7  304.52  1312.2  296.95  1327.2  293.96
  1394.5  289.79  1733.1  279.41  1850.6  279.72  1931.1  276.63  2090.2  276.81
  2169.8  272.69  2320.8  270.43  2726.3  266.15  4140.5  262.09  4143.2  261.59
  4146.5  262.09  4596.2  262.57  4807.2  265.92  4927.8  263.25  5158.9  263.25
  5199.1  265.37  5359.9  263.32  5510.6  265.73  5550.8  263.49  5695.5   263.6
  5830.2  268.29  6354.7  300.92  6608.7  326.24  6709.6  340.61  6758.5  350.28
#Mann= 9 ,-1 , 0
  1084.7     .05       0  1394.5     .16       0  1733.1      .1       0
  1850.6     .05       0  2320.8     .16       0  2726.3     .12       0
  4140.5     .07       0  4146.5     .12       0  5830.2     .16       0
Bank Sta=4140.5,4146.5
XS Rating Curve= 0 ,0
Exp/Cntr=0.3,0.1

Chan Stop Cuts=-1
Use User Specified Reach Order=0
Composite Channel Slope=5