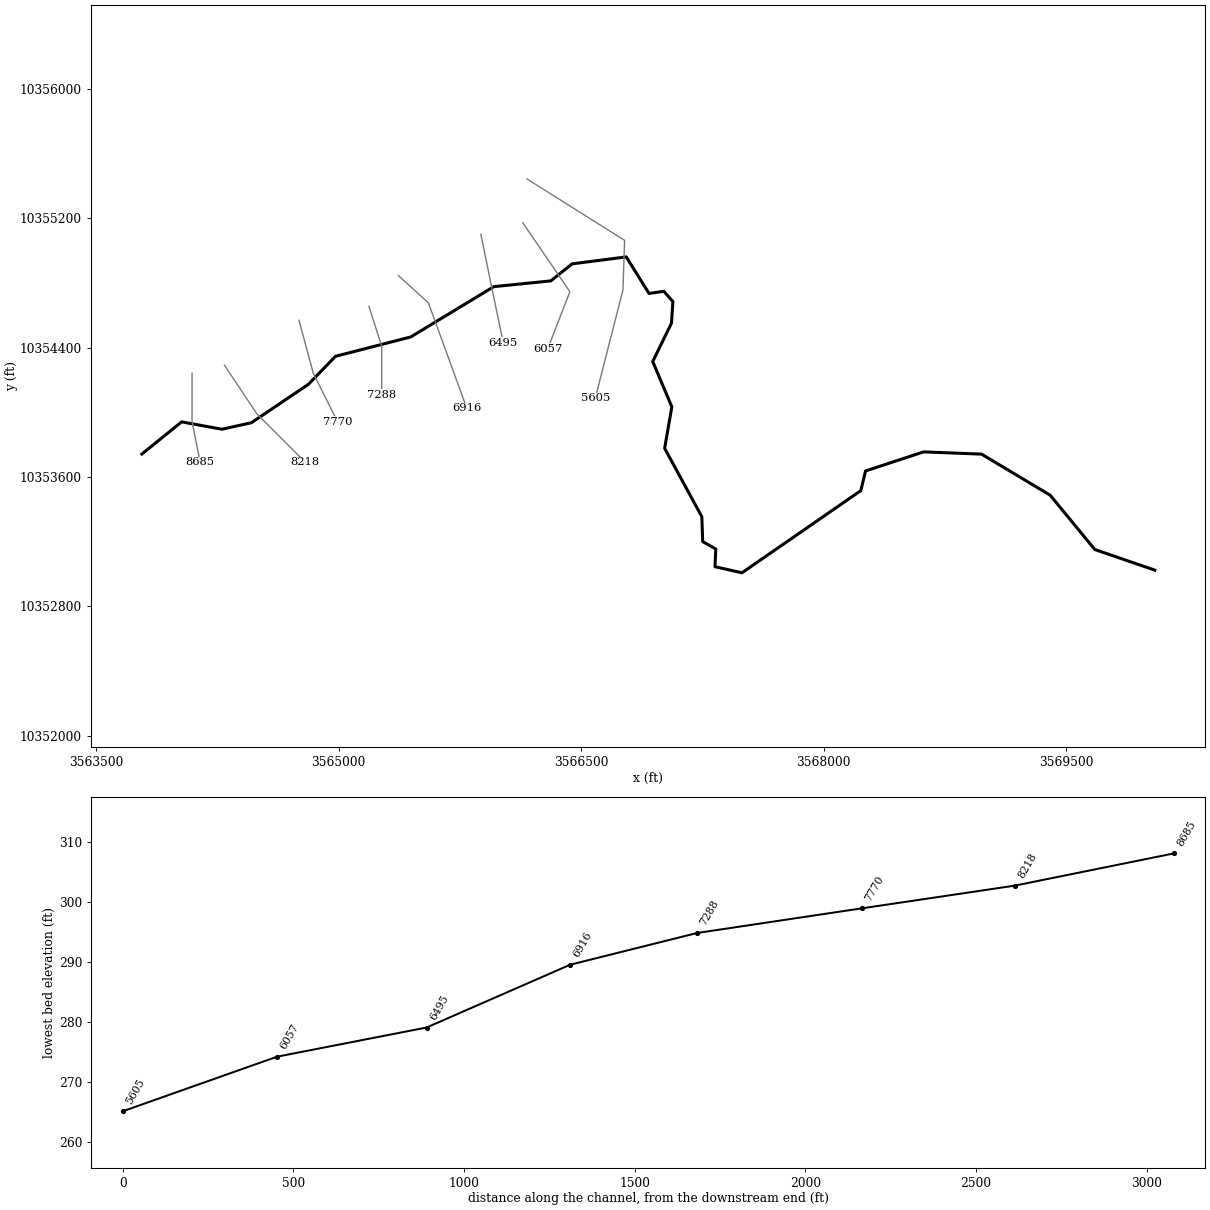
--- DEVILS JUMP CREEK TRIBUTARY 2 3.prj (project) ---

Proj Title=DEVILS JUMP CREEK TRIBUTARY 2 3 Base Level Engineering
Current Plan=p01
Default Exp/Contr=0.3,0.1
English Units
Geom File=g01
Flow File=f01
Plan File=p01
BEGIN DESCRIPTION:
DEVILS JUMP CREEK TRIBUTARY 2 3
END DESCRIPTION:

--- DEVILS JUMP CREEK TRIBUTARY 2 3.p01 (plan) ---

Plan Title=Multiple Run
Short Identifier=Multiple
Geom File=g01
Flow File=f01
Subcritical Flow
K Sum by GR= 0
Std Step Tol= 0.01
Critical Tol= 0.01
Num of Std Step Trials= 20
Max Error Tol= 0.3
Flow Tol Ratio= 0.001
Split Flow NTrial= 30
Split Flow Tol= 0.02
Split Flow Ratio= 0.02
Log Output Level= 0
Friction Slope Method= 1
Unsteady Friction Slope Method= 2
Unsteady Bridges Friction Slope Method= 1
Parabolic Critical Depth
Global Vel Dist=  1 , 1 , 1
Global Log Level= 0
CheckData=True
Encroach Param= -1, 0, 0, 0
BEGIN DESCRIPTION:
Multiple Run
END DESCRIPTION:

--- DEVILS JUMP CREEK TRIBUTARY 2 3.f01 (steady flow) ---

Flow Title=Multiple
Number of Profiles=7
Profile Names=10-year,25-year,50-year,1pct_min,100-year,1pct_plu,500-year
River Rch & RM= DEVILS JUMP CREE,Reach-1,8685
     890    1224    1501    1344    1818    2458    2658
Boundary for River Rch & Prof#=DEVILS JUMP CREE,Reach-1,1
Up Type=0
Dn Type=3
Dn Slope=0.005
Boundary for River Rch & Prof#=DEVILS JUMP CREE,Reach-1,2
Up Type=0
Dn Type=3
Dn Slope=0.005
Boundary for River Rch & Prof#=DEVILS JUMP CREE,Reach-1,3
Up Type=0
Dn Type=3
Dn Slope=0.005
Boundary for River Rch & Prof#=DEVILS JUMP CREE,Reach-1,4
Up Type=0
Dn Type=3
Dn Slope=0.005
Boundary for River Rch & Prof#=DEVILS JUMP CREE,Reach-1,5
Up Type=0
Dn Type=3
Dn Slope=0.005
Boundary for River Rch & Prof#=DEVILS JUMP CREE,Reach-1,6
Up Type=0
Dn Type=3
Dn Slope=0.005
Boundary for River Rch & Prof#=DEVILS JUMP CREE,Reach-1,7
Up Type=0
Dn Type=3
Dn Slope=0.005

--- DEVILS JUMP CREEK TRIBUTARY 2 3.g01 (geometry) ---

Geom Title=Existing Conditions

River Reach=DEVILS JUMP CREE,Reach-1
Reach XY= 30
      3563782.11     10353741.64      3564027.64     10353940.59
      3564277.10     10353895.05      3564458.89     10353935.04
      3564811.77     10354172.68      3564979.67     10354346.30
      3565445.08     10354465.85      3565959.28     10354777.23
      3566311.71     10354812.71      3566443.57     10354918.11
      3566778.34     10354961.17      3566919.46     10354734.90
      3567010.59     10354748.42      3567066.93     10354684.96
      3567058.18     10354551.35      3566942.08     10354313.72
      3567060.35     10354033.56      3567015.90     10353776.99
      3567245.96     10353353.74      3567251.38     10353199.66
      3567332.20     10353154.31      3567327.34     10353044.49
      3567494.33     10353006.97      3568229.39     10353515.12
      3568258.79     10353636.90      3568618.16     10353754.96
      3568976.47     10353740.95      3569400.95     10353486.87
      3569676.99     10353150.93      3570048.09     10353023.31

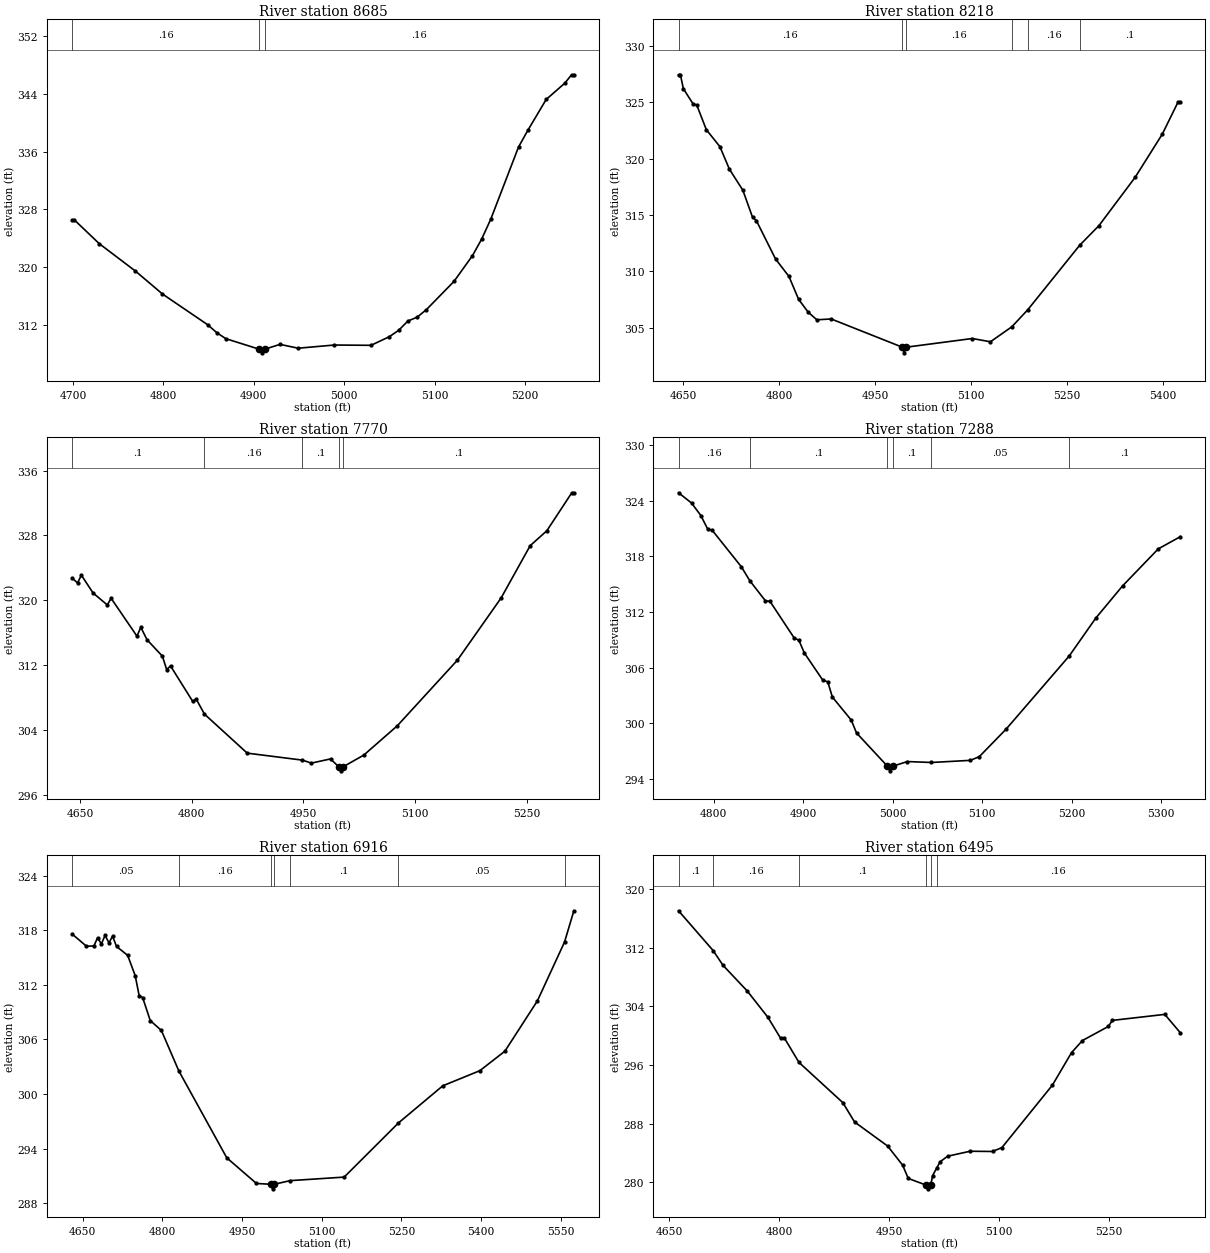
Type RM Length L Ch R = 1,8685,467,467,467
BEGIN DESCRIPTION:
DEVILS JUMP CREEK TRIBUTARY 2.3 12.0
END DESCRIPTION:
XS GIS Cut Line= 3
      3564092.11     10354241.61      3564092.11     10353941.64
      3564142.10     10353691.66
#Sta/Elev= 30
  4699.0  326.55  4701.5  326.55  4729.0  323.27  4769.0  319.48  4799.0  316.30
  4849.0  312.05  4859.0  310.96  4869.0  310.13  4906.0  308.67  4908.7  308.17
  4912.0  308.67  4929.0  309.34  4949.0  308.81  4989.0  309.25  5029.6  309.21
  5050.0  310.41  5060.2  311.29  5070.4  312.57  5080.6  313.10  5090.8  314.14
  5121.3  318.04  5141.7  321.59  5151.9  323.88  5162.1  326.67  5192.7  336.62
  5202.9  338.91  5223.3  343.20  5243.7  345.43  5251.4  346.61  5253.9  346.61
#Mann=3,-1,0
  4699.0    0.16       0  4906.0    0.07       0  4912.0    0.16       0
Bank Sta=4906,4912
Exp/Cntr=0.3,0.1

Type RM Length L Ch R = 1,8218,448,448,448
BEGIN DESCRIPTION:
DEVILS JUMP CREEK TRIBUTARY 2.3 11.0
END DESCRIPTION:
XS GIS Cut Line= 3
      3564292.12     10354291.62      3564492.11     10353991.64
      3564792.11     10353691.64
#Sta/Elev= 30
  4642.3  327.42  4645.3  327.42  4649.8  326.19  4664.8  324.86  4670.8  324.74
  4685.8  322.55  4706.9  321.06  4721.9  319.05  4742.9  317.19  4758.0  314.80
  4764.0  314.50  4794.0  311.10  4815.0  309.55  4830.1  307.52  4845.1  306.38
  4858.6  305.71  4881.1  305.78  4992.3  303.28  4995.1  302.78  4998.3  303.28
  5101.8  304.05  5130.1  303.76  5163.6  305.09  5188.4  306.59  5269.8  312.32
  5299.8  314.05  5356.4  318.33  5398.8  322.15  5423.6  325.01  5427.1  325.01
#Mann=6,-1,0
  4642.3    0.16       0  4992.3    0.07       0  4998.3    0.16       0
  5163.6     0.1       0  5188.4    0.16       0  5269.8     0.1       0
Bank Sta=4992.3,4998.3
Exp/Cntr=0.3,0.1

Type RM Length L Ch R = 1,7770,482,482,482
BEGIN DESCRIPTION:
DEVILS JUMP CREEK TRIBUTARY 2.3 10.0
END DESCRIPTION:
XS GIS Cut Line= 3
      3564753.87     10354568.88      3564842.11     10354241.64
      3564992.09     10353941.67
#Sta/Elev= 30
  4639.3  322.75  4646.7  322.15  4651.8  323.11  4667.5  320.91  4686.6  319.44
  4691.8  320.25  4726.5  315.59  4731.7  316.68  4740.0  315.15  4760.7  313.12
  4766.4  311.47  4771.6  311.92  4801.2  307.58  4806.4  307.79  4817.2  305.98
  4874.7  301.17  4948.9  300.31  4960.9  299.94  4986.6  300.46  4997.6  299.49
  5000.3  298.99  5003.6  299.49  5031.3  300.93  5076.1  304.52  5157.1  312.63
  5215.8  320.29  5254.9  326.74  5277.3  328.58  5310.8  333.26  5313.6  333.26
#Mann=5,-1,0
  4639.3     0.1       0  4817.2    0.16       0  4948.9     0.1       0
  4997.6    0.07       0  5003.6     0.1       0
Bank Sta=4997.6,5003.6
Exp/Cntr=0.3,0.1

Type RM Length L Ch R = 1,7288,372,372,372
BEGIN DESCRIPTION:
DEVILS JUMP CREEK TRIBUTARY 2.3 9.0
END DESCRIPTION:
XS GIS Cut Line= 3
      3565186.54     10354655.48      3565265.66     10354407.03
      3565265.66     10354107.08
#Sta/Elev= 30
  4760.7  324.84  4775.2  323.74  4785.7  322.38  4793.2  320.94  4798.5  320.78
  4830.7  316.89  4840.6  315.33  4857.7  313.21  4862.9  313.14  4889.9  309.20
  4895.2  308.95  4901.2  307.59  4922.1  304.62  4927.4  304.48  4932.6  302.83
  4953.6  300.36  4959.6  298.96  4994.1  295.38  4996.8  294.88  5000.1  295.38
  5016.4  295.88  5043.3  295.78  5086.8  296.01  5096.8  296.41  5126.8  299.38
  5197.2  307.25  5226.8  311.32  5256.8  314.80  5296.8  318.80  5321.4  320.11
#Mann=6,-1,0
  4760.7    0.16       0  4840.6     0.1       0  4994.1    0.07       0
  5000.1     0.1       0  5043.3    0.05       0  5197.2     0.1       0
Bank Sta=4994.1,5000.1
Exp/Cntr=0.3,0.1

Type RM Length L Ch R = 1,6916,421,421,421
BEGIN DESCRIPTION:
DEVILS JUMP CREEK TRIBUTARY 2.3 8.0
END DESCRIPTION:
XS GIS Cut Line= 3
      3565368.30     10354845.80      3565554.32     10354677.09
      3565791.76     10354025.21
#Sta/Elev= 30
  4629.9  317.58  4656.9  316.24  4671.0  316.26  4677.8  317.15  4685.2  316.50
  4692.0  317.42  4699.4  316.61  4706.2  317.34  4713.6  316.21  4734.6  315.23
  4748.8  313.00  4756.2  310.82  4762.9  310.58  4777.1  308.07  4798.1  306.98
  4830.9  302.54  4921.2  292.99  4977.1  290.17  5004.6  290.08  5007.4  289.58
  5010.6  290.08  5040.4  290.48  5142.3  290.87  5244.5  296.82  5328.0  300.90
  5397.7  302.56  5444.9  304.70  5506.1  310.23  5557.2  316.69  5574.8  320.13
#Mann=7,-1,0
  4629.9    0.05       0  4830.9    0.16       0  5004.6    0.07       0
  5010.6    0.16       0  5040.4     0.1       0  5244.5    0.05       0
  5557.2     0.1       0
Bank Sta=5004.6,5010.6
Exp/Cntr=0.3,0.1

Type RM Length L Ch R = 1,6495,438,438,438
BEGIN DESCRIPTION:
DEVILS JUMP CREEK TRIBUTARY 2.3 7.0
END DESCRIPTION:
XS GIS Cut Line= 3
      3565878.84     10355101.07      3565942.11     10354791.64
      3566017.20     10354430.90
#Sta/Elev= 30
  4663.0  317.04  4710.2  311.61  4723.7  309.59  4756.8  306.08  4784.9  302.50
  4802.2  299.64  4807.3  299.68  4827.2  296.35  4887.0  290.86  4903.1  288.21
  4948.2  284.93  4968.6  282.32  4976.3  280.51  5000.9  279.59  5003.6  279.09
  5006.9  279.59  5009.5  280.90  5014.8  281.88  5019.7  282.78  5029.9  283.54
  5060.5  284.22  5091.2  284.19  5104.0  284.72  5172.9  293.25  5199.0  297.69
  5213.8  299.33  5249.1  301.25  5254.6  302.08  5326.1  302.90  5347.3  300.39
#Mann=6,-1,0
  4663.0     0.1       0  4710.2    0.16       0  4827.2     0.1       0
  5000.9    0.07       0  5006.9     0.1       0  5014.8    0.16       0
Bank Sta=5000.9,5006.9
Exp/Cntr=0.3,0.1

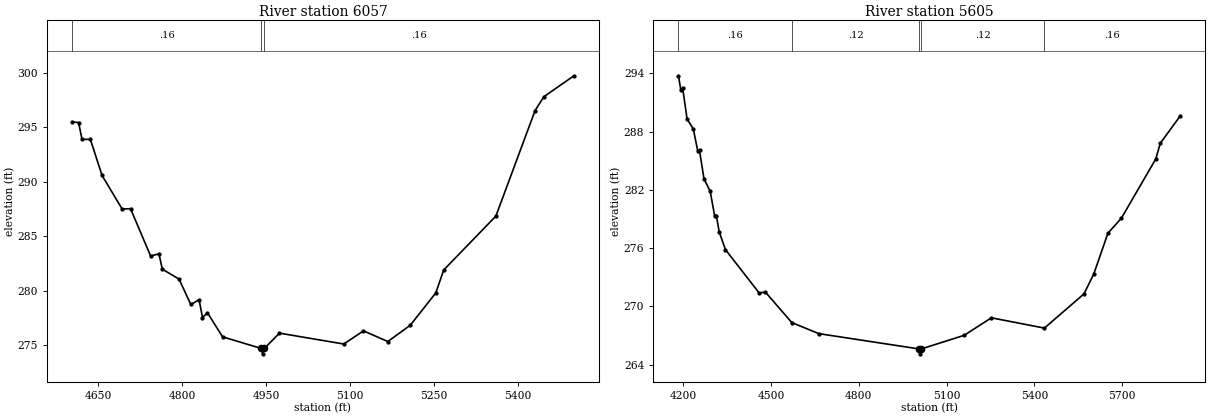
Type RM Length L Ch R = 1,6057,452,452,452
BEGIN DESCRIPTION:
DEVILS JUMP CREEK TRIBUTARY 2.3 6.0
END DESCRIPTION:
XS GIS Cut Line= 3
      3566138.05     10355172.70      3566429.73     10354745.60
      3566292.09     10354391.61
#Sta/Elev= 30
  4602.8  295.52  4614.5  295.44  4620.6  293.90  4635.5  293.91  4656.4  290.59
  4692.3  287.51  4707.3  287.54  4743.2  283.20  4758.1  283.40  4764.1  281.99
  4794.0  281.08  4815.0  278.75  4829.9  279.18  4835.9  277.55  4844.8  277.99
  4871.8  275.78  4940.6  274.72  4943.4  274.22  4946.6  274.72  4973.5  276.12
  5088.5  275.12  5123.6  276.33  5167.2  275.35  5207.4  276.85  5253.0  279.82
  5267.1  281.92  5360.3  286.86  5430.4  296.55  5446.1  297.82  5499.8  299.74
#Mann=3,-1,0
  4602.8    0.16       0  4940.6    0.07       0  4946.6    0.16       0
Bank Sta=4940.6,4946.6
Exp/Cntr=0.3,0.1

Type RM Length L Ch R = 1,5605,0,0,0
BEGIN DESCRIPTION:
DEVILS JUMP CREEK TRIBUTARY 2.3 1.0
END DESCRIPTION:
XS GIS Cut Line= 4
      3566164.13     10355443.50      3566768.27     10355063.31
      3566757.85     10354756.02      3566586.30     10354085.40
#Sta/Elev= 30
  4184.5  293.74  4192.7  292.24  4198.6  292.52  4213.9  289.28  4235.1  288.28
  4250.4  285.97  4256.3  286.05  4271.6  283.13  4292.8  281.85  4308.1  279.31
  4314.0  279.30  4323.4  277.69  4344.6  275.85  4460.0  271.38  4481.2  271.47
  4571.4  268.33  4663.7  267.19  5007.0  265.61  5009.8  265.11  5013.0  265.61
  5160.1  267.02  5252.9  268.82  5433.9  267.76  5569.2  271.29  5602.5  273.33
  5650.8  277.53  5696.8  279.08  5814.1  285.17  5829.6  286.79  5898.0  289.62
#Mann=5,-1,0
  4184.5    0.16       0  4571.4    0.12       0  5007.0    0.07       0
  5013.0    0.12       0  5433.9    0.16       0
Bank Sta=5007,5013
Exp/Cntr=0.3,0.1

Chan Stop Cuts=-1