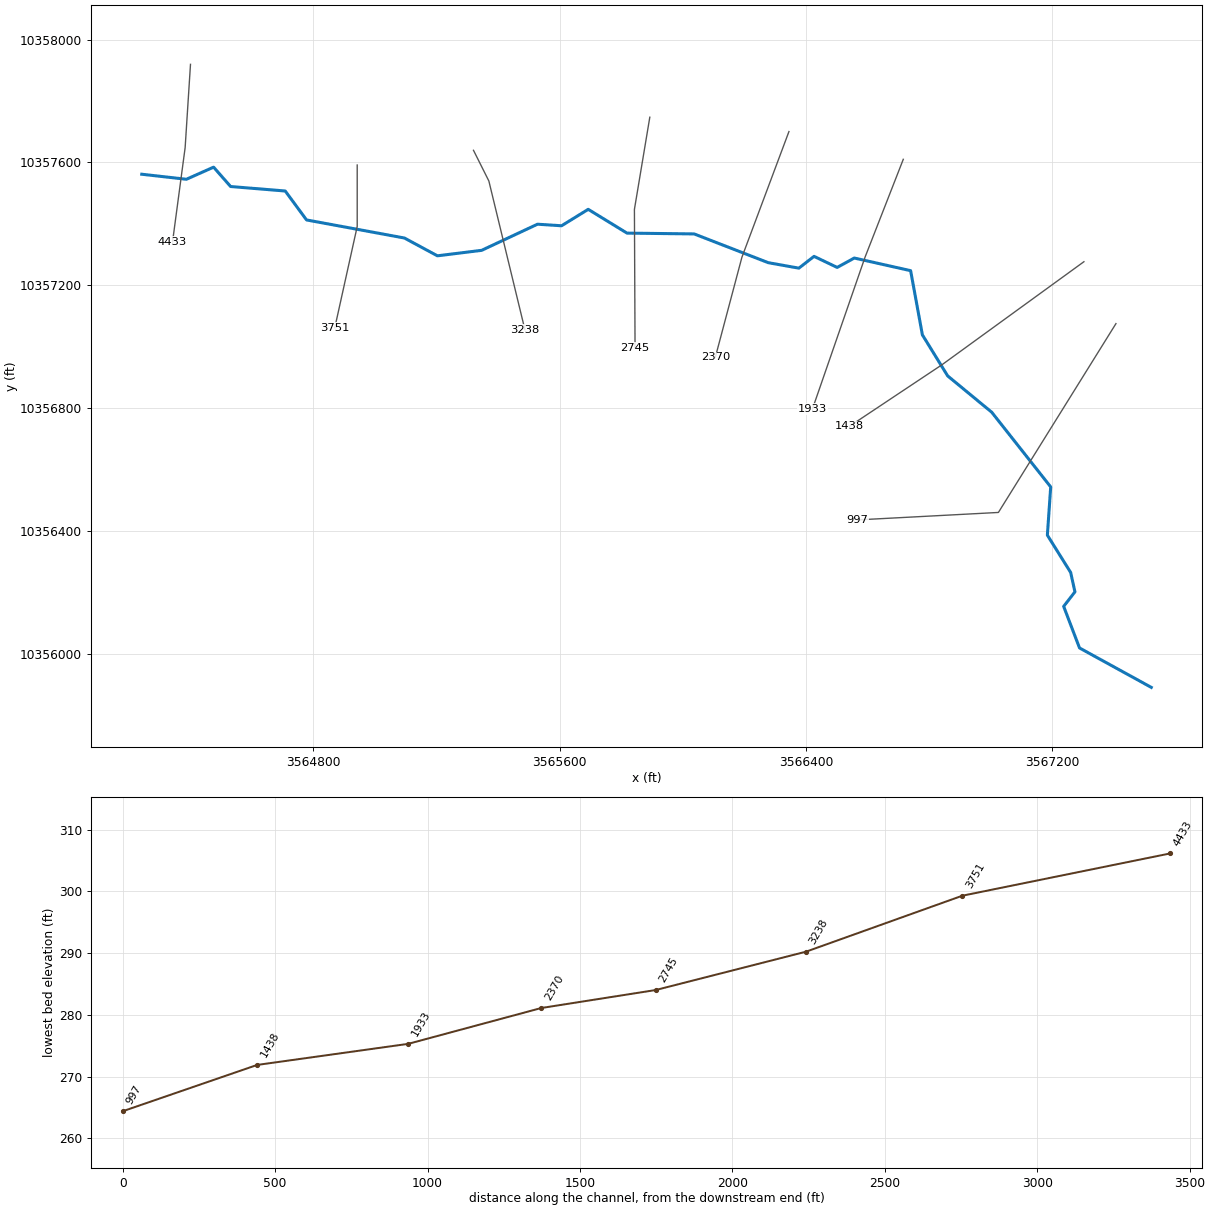
--- DEVILS JUMP CREEK TRIBUTARY 2.prj (project) ---

Proj Title=DEVILS JUMP CREEK TRIBUTARY 2 Base Level Engineering
Current Plan=p01
Default Exp/Contr=0.3,0.1
English Units
Geom File=g01
Flow File=f01
Plan File=p01
BEGIN DESCRIPTION:
DEVILS JUMP CREEK TRIBUTARY 2
END DESCRIPTION:

--- DEVILS JUMP CREEK TRIBUTARY 2.p01 (plan) ---

Plan Title=Multiple Run
Short Identifier=Multiple
Geom File=g01
Flow File=f01
Subcritical Flow
K Sum by GR= 0
Std Step Tol= 0.01
Critical Tol= 0.01
Num of Std Step Trials= 20
Max Error Tol= 0.3
Flow Tol Ratio= 0.001
Split Flow NTrial= 30
Split Flow Tol= 0.02
Split Flow Ratio= 0.02
Log Output Level= 0
Friction Slope Method= 1
Unsteady Friction Slope Method= 2
Unsteady Bridges Friction Slope Method= 1
Parabolic Critical Depth
Global Vel Dist=  1 , 1 , 1
Global Log Level= 0
CheckData=True
Encroach Param= -1, 0, 0, 0
BEGIN DESCRIPTION:
Multiple Run
END DESCRIPTION:

--- DEVILS JUMP CREEK TRIBUTARY 2.f01 (steady flow) ---

Flow Title=Multiple
Number of Profiles=7
Profile Names=10-year,25-year,50-year,1pct_min,100-year,1pct_plu,500-year
River Rch & RM= DEVILS JUMP CREE,Reach-1,4433
     996    1391    1723    1561    2111    2854    3156
Boundary for River Rch & Prof#=DEVILS JUMP CREE,Reach-1,1
Up Type=0
Dn Type=3
Dn Slope=0.005
Boundary for River Rch & Prof#=DEVILS JUMP CREE,Reach-1,2
Up Type=0
Dn Type=3
Dn Slope=0.005
Boundary for River Rch & Prof#=DEVILS JUMP CREE,Reach-1,3
Up Type=0
Dn Type=3
Dn Slope=0.005
Boundary for River Rch & Prof#=DEVILS JUMP CREE,Reach-1,4
Up Type=0
Dn Type=3
Dn Slope=0.005
Boundary for River Rch & Prof#=DEVILS JUMP CREE,Reach-1,5
Up Type=0
Dn Type=3
Dn Slope=0.005
Boundary for River Rch & Prof#=DEVILS JUMP CREE,Reach-1,6
Up Type=0
Dn Type=3
Dn Slope=0.005
Boundary for River Rch & Prof#=DEVILS JUMP CREE,Reach-1,7
Up Type=0
Dn Type=3
Dn Slope=0.005

--- DEVILS JUMP CREEK TRIBUTARY 2.g01 (geometry) ---

Geom Title=Existing Conditions

River Reach=DEVILS JUMP CREE,Reach-1
Reach XY= 30
      3564242.11     10357561.64      3564387.10     10357545.24
      3564475.54     10357584.66      3564530.73     10357521.65
      3564708.26     10357507.06      3564777.43     10357412.89
      3565095.42     10357354.06      3565202.68     10357296.13
      3565346.38     10357313.94      3565527.91     10357399.01
      3565606.10     10357393.92      3565692.66     10357447.40
      3565818.68     10357369.98      3566036.92     10357367.39
      3566277.59     10357273.81      3566377.11     10357255.95
      3566426.42     10357294.36      3566501.61     10357258.31
      3566557.18     10357288.91      3566740.24     10357247.77
      3566778.42     10357038.86      3566860.47     10356905.41
      3567003.71     10356787.11      3567195.36     10356544.01
      3567184.50     10356386.97      3567260.18     10356265.57
      3567274.12     10356202.49      3567237.44     10356155.20
      3567288.98     10356019.86      3567522.11     10355891.64

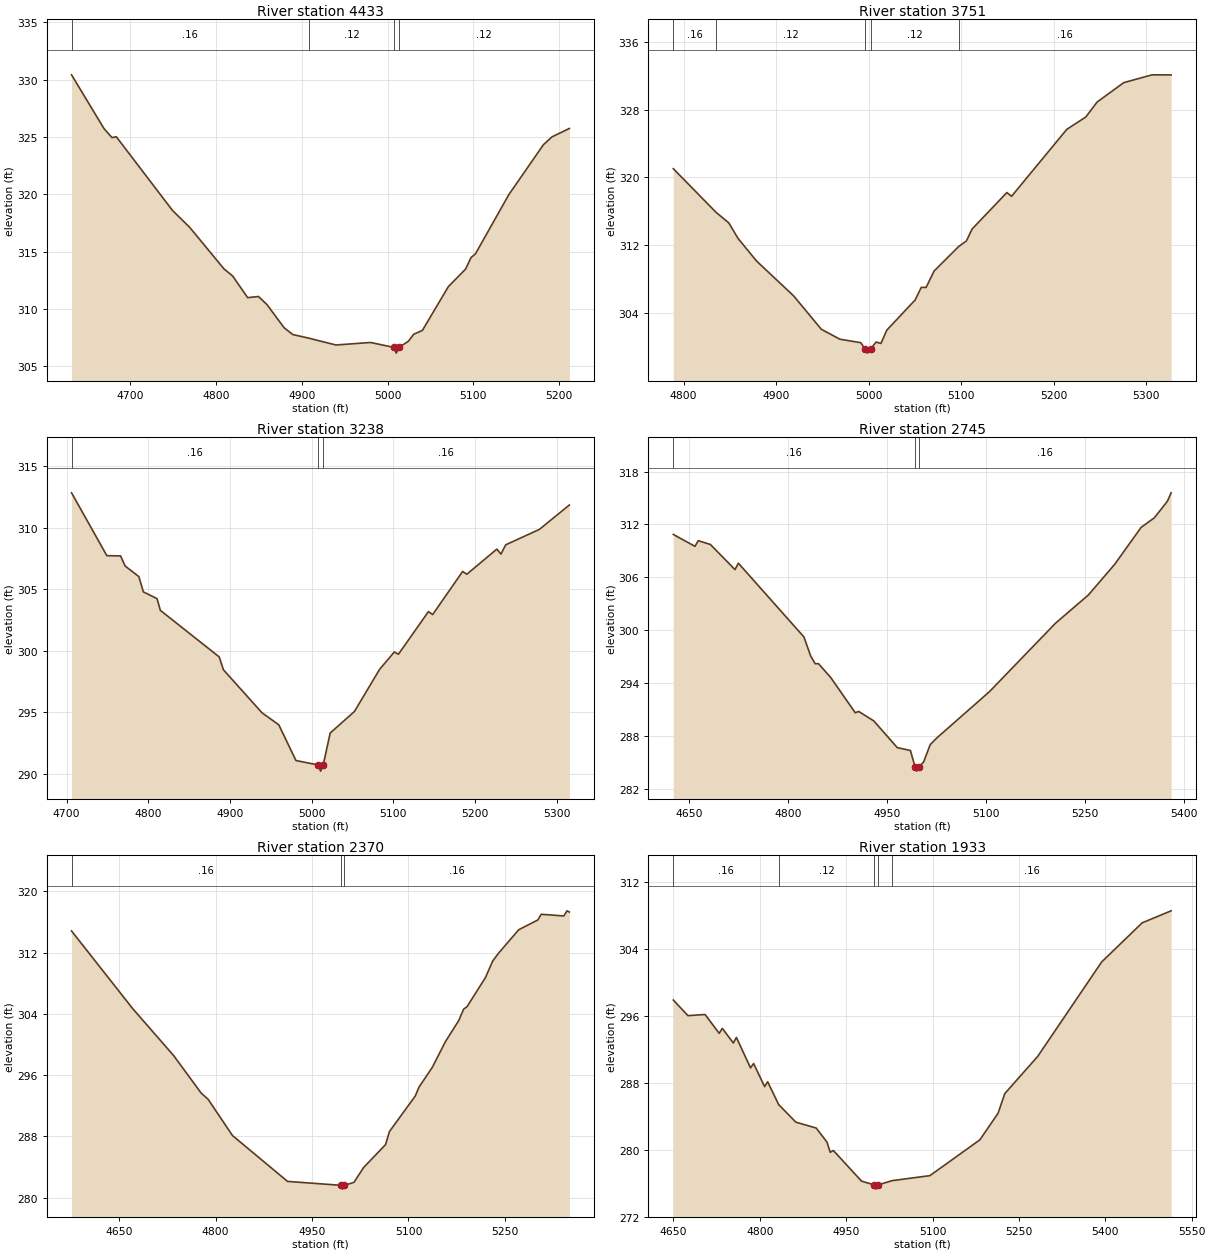
Type RM Length L Ch R = 1,4433,682,682,682
BEGIN DESCRIPTION:
DEVILS JUMP CREEK TRIBUTARY 2 8.0
END DESCRIPTION:
XS GIS Cut Line= 3
      3564400.41     10357919.28      3564383.05     10357648.42
      3564342.11     10357341.65
#Sta/Elev= 30
  4631.3  330.43  4669.0  325.76  4678.5  324.95  4683.5  325.03  4749.2  318.59
  4769.2  317.12  4809.3  313.49  4819.3  312.88  4836.8  310.99  4849.4  311.09
  4859.4  310.38  4879.4  308.36  4889.5  307.77  4908.5  307.45  4939.8  306.86
  4980.2  307.08  5007.4  306.65  5010.2  306.15  5013.4  306.65  5024.4  307.19
  5030.6  307.80  5040.7  308.13  5071.0  311.95  5091.1  313.48  5097.5  314.49
  5102.6  314.81  5141.6  319.98  5181.9  324.33  5192.0  325.02  5212.2  325.75
#Mann=4,-1,0
  4631.3    0.16       0  4908.5    0.12       0  5007.4    0.07       0
  5013.4    0.12       0
Bank Sta=5007.4,5013.4
Exp/Cntr=0.3,0.1

Type RM Length L Ch R = 1,3751,513,513,513
BEGIN DESCRIPTION:
DEVILS JUMP CREEK TRIBUTARY 2 7.0
END DESCRIPTION:
XS GIS Cut Line= 3
      3564942.11     10357591.64      3564942.11     10357391.64
      3564869.16     10357061.60
#Sta/Elev= 30
  4788.8  321.03  4834.9  315.90  4848.8  314.64  4858.8  312.81  4878.8  310.15
  4918.8  306.05  4948.8  302.11  4968.8  300.94  4991.4  300.53  4996.0  299.80
  4998.8  299.30  5002.0  299.80  5008.1  300.61  5013.2  300.44  5019.5  302.00
  5050.2  305.57  5056.8  307.05  5062.0  307.04  5070.7  308.98  5097.2  311.86
  5105.6  312.52  5111.7  313.92  5149.3  318.22  5154.4  317.78  5214.1  325.67
  5234.6  327.12  5246.8  328.88  5275.6  331.17  5306.3  332.09  5326.8  332.08
#Mann=5,-1,0
  4788.8    0.16       0  4834.9    0.12       0  4996.0    0.07       0
  5002.0    0.12       0  5097.2    0.16       0
Bank Sta=4996,5002
Exp/Cntr=0.3,0.1

Type RM Length L Ch R = 1,3238,493,493,493
BEGIN DESCRIPTION:
DEVILS JUMP CREEK TRIBUTARY 2 6.0
END DESCRIPTION:
XS GIS Cut Line= 3
      3565319.89     10357639.54      3565369.88     10357539.56
      3565486.92     10357055.89
#Sta/Elev= 30
  4706.0  312.82  4749.2  307.72  4766.0  307.70  4771.6  306.88  4788.4  306.02
  4793.9  304.78  4810.7  304.23  4814.7  303.28  4886.8  299.50  4891.9  298.46
  4939.1  294.97  4959.7  293.99  4980.7  291.09  5008.1  290.73  5010.9  290.23
  5014.1  290.73  5022.6  293.32  5052.3  295.07  5083.1  298.49  5101.1  299.90
  5106.2  299.72  5142.9  303.18  5148.1  302.94  5184.8  306.44  5189.9  306.21
  5226.6  308.25  5231.7  307.85  5237.5  308.60  5278.7  309.85  5315.4  311.83
#Mann=3,-1,0
  4706.0    0.16       0  5008.1    0.07       0  5014.1    0.16       0
Bank Sta=5008.1,5014.1
Exp/Cntr=0.3,0.1

Type RM Length L Ch R = 1,2745,375,375,375
BEGIN DESCRIPTION:
DEVILS JUMP CREEK TRIBUTARY 2 5.0
END DESCRIPTION:
XS GIS Cut Line= 3
      3565892.80     10357747.18      3565842.80     10357447.20
      3565844.85     10356996.13
#Sta/Elev= 30
  4626.0  310.87  4658.8  309.52  4663.9  310.16  4682.3  309.73  4719.6  306.88
  4724.7  307.61  4824.2  299.24  4834.4  297.08  4841.3  296.20  4846.3  296.21
  4864.8  294.64  4902.1  290.64  4907.2  290.79  4930.1  289.72  4965.7  286.69
  4985.7  286.36  4992.7  284.52  4995.4  284.02  4998.7  284.52  5005.7  285.05
  5015.7  287.02  5025.7  287.78  5105.7  293.04  5205.7  300.79  5255.7  304.00
  5295.7  307.49  5335.7  311.67  5355.7  312.75  5375.7  314.65  5381.2  315.59
#Mann=3,-1,0
  4626.0    0.16       0  4992.7    0.07       0  4998.7    0.16       0
Bank Sta=4992.7,4998.7
Exp/Cntr=0.3,0.1

Type RM Length L Ch R = 1,2370,437,437,437
BEGIN DESCRIPTION:
DEVILS JUMP CREEK TRIBUTARY 2 4.0
END DESCRIPTION:
XS GIS Cut Line= 3
      3566344.87     10357700.54      3566192.11     10357291.64
      3566105.57     10356965.53
#Sta/Elev= 30
  4576.2  314.84  4671.1  304.71  4735.1  298.54  4777.8  293.65  4788.5  292.85
  4826.4  288.11  4912.0  282.12  4994.5  281.61  4997.3  281.11  5000.5  281.61
  5015.3  282.00  5030.2  283.93  5064.4  286.93  5070.4  288.63  5110.6  293.28
  5116.2  294.42  5136.9  297.00  5157.5  300.39  5178.2  303.14  5185.8  304.63
  5191.0  304.94  5219.6  308.74  5231.1  310.93  5240.3  311.96  5271.4  315.00
  5301.2  316.28  5306.3  317.02  5341.4  316.80  5346.5  317.47  5350.1  317.31
#Mann=3,-1,0
  4576.2    0.16       0  4994.5    0.07       0  5000.5    0.16       0
Bank Sta=4994.5,5000.5
Exp/Cntr=0.3,0.1

Type RM Length L Ch R = 1,1933,495,495,495
BEGIN DESCRIPTION:
DEVILS JUMP CREEK TRIBUTARY 2 3.0
END DESCRIPTION:
XS GIS Cut Line= 3
      3566716.37     10357610.19      3566592.11     10357291.64
      3566421.23     10356797.69
#Sta/Elev= 30
  4649.7  297.87  4675.1  296.00  4704.9  296.14  4729.4  293.89  4734.8  294.48
  4753.9  292.74  4759.3  293.40  4783.8  289.77  4789.2  290.29  4808.3  287.53
  4813.6  288.11  4832.7  285.39  4862.6  283.29  4897.9  282.59  4916.5  280.92
  4922.3  279.69  4927.7  279.91  4976.7  276.25  4998.9  275.80  5001.7  275.30
  5004.9  275.80  5029.7  276.31  5095.4  276.91  5182.1  281.18  5213.8  284.36
  5225.4  286.70  5282.4  291.12  5393.7  302.41  5464.1  307.08  5514.3  308.51
#Mann=5,-1,0
  4649.7    0.16       0  4832.7    0.12       0  4998.9    0.07       0
  5004.9    0.12       0  5029.7    0.16       0
Bank Sta=4998.9,5004.9
Exp/Cntr=0.3,0.1

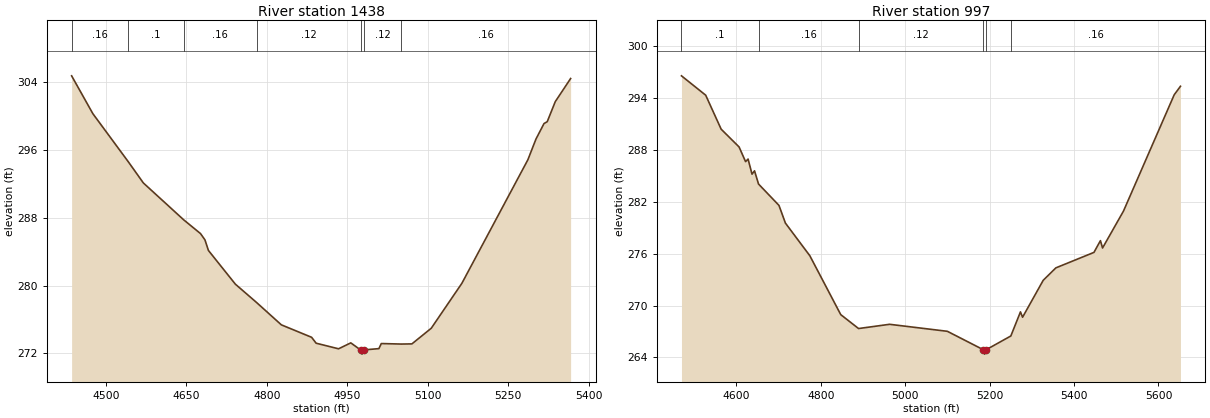
Type RM Length L Ch R = 1,1438,441,441,441
BEGIN DESCRIPTION:
DEVILS JUMP CREEK TRIBUTARY 2 2.0
END DESCRIPTION:
XS GIS Cut Line= 3
      3567303.22     10357276.91      3566842.11     10356941.64
      3566542.08     10356741.63
#Sta/Elev= 30
  4435.8  304.78  4475.4  300.31  4541.8  294.60  4569.6  292.12  4644.9  287.76
  4676.3  286.13  4684.5  285.39  4691.0  284.14  4741.2  280.16  4780.8  277.99
  4827.0  275.35  4883.4  273.88  4891.9  273.18  4933.7  272.52  4956.5  273.22
  4974.7  272.39  4977.5  271.89  4980.7  272.39  5008.9  272.54  5013.4  273.14
  5051.0  273.08  5070.5  273.10  5106.6  274.95  5163.7  280.26  5286.8  294.86
  5301.9  297.31  5316.9  299.14  5322.9  299.36  5337.9  301.73  5366.5  304.46
#Mann=7,-1,0
  4435.8    0.16       0  4541.8     0.1       0  4644.9    0.16       0
  4780.8    0.12       0  4974.7    0.07       0  4980.7    0.12       0
  5051.0    0.16       0
Bank Sta=4974.7,4980.7
Exp/Cntr=0.3,0.1

Type RM Length L Ch R = 1,997,0,0,0
BEGIN DESCRIPTION:
DEVILS JUMP CREEK TRIBUTARY 2 1.0
END DESCRIPTION:
XS GIS Cut Line= 3
      3567407.35     10357075.50      3567025.41     10356460.92
      3566567.34     10356436.63
#Sta/Elev= 30
  4469.8  296.59  4527.2  294.35  4563.8  290.42  4606.3  288.36  4621.7  286.66
  4627.6  286.96  4637.0  285.21  4642.9  285.60  4652.4  284.07  4700.8  281.60
  4716.1  279.55  4774.0  275.77  4847.2  268.96  4889.4  267.35  4962.9  267.84
  5099.8  267.03  5185.4  264.89  5188.2  264.39  5191.4  264.89  5250.2  266.49
  5273.0  269.28  5278.0  268.66  5326.9  272.93  5356.9  274.37  5447.1  276.16
  5462.5  277.52  5467.5  276.67  5517.1  280.94  5637.3  294.40  5652.1  295.38
#Mann=6,-1,0
  4469.8     0.1       0  4652.4    0.16       0  4889.4    0.12       0
  5185.4    0.07       0  5191.4    0.12       0  5250.2    0.16       0
Bank Sta=5185.4,5191.4
Exp/Cntr=0.3,0.1

Chan Stop Cuts=-1