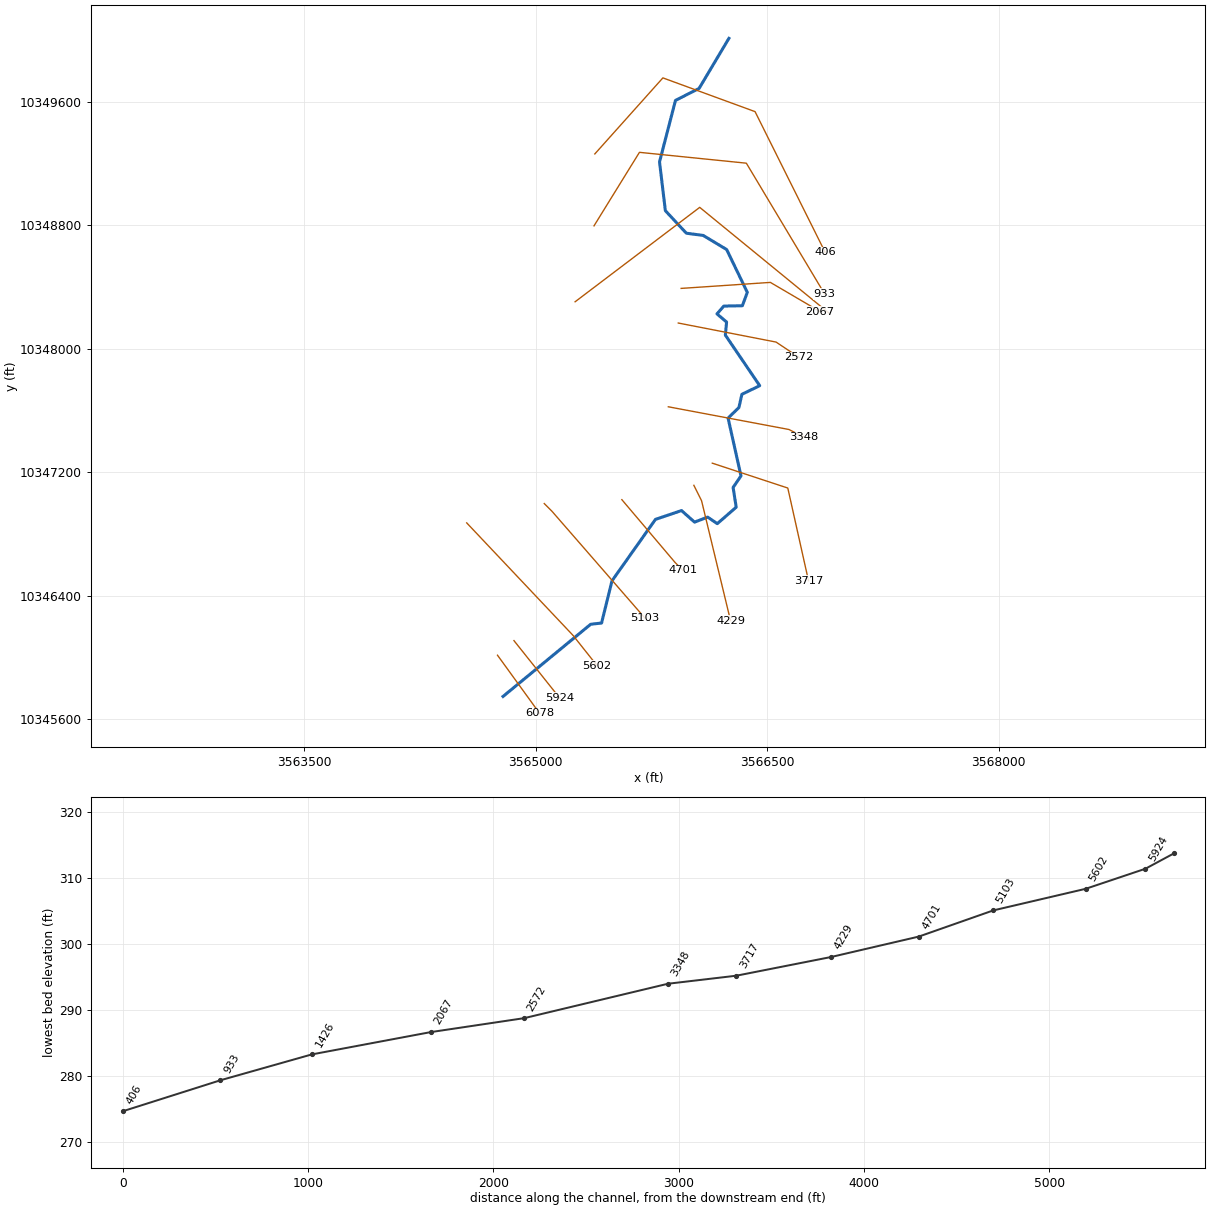
--- DEVILS JUMP CREEK TRIBUTARY 3.prj (project) ---

Proj Title=DEVILS JUMP CREEK TRIBUTARY 3 Base Level Engineering
Current Plan=p01
Default Exp/Contr=0.3,0.1
English Units
Geom File=g01
Flow File=f01
Plan File=p01
Y Axis Title=Elevation
X Axis Title(PF)=Main Channel Distance
X Axis Title(XS)=Station
BEGIN DESCRIPTION:
DEVILS JUMP CREEK TRIBUTARY 3
END DESCRIPTION:
DSS Export Rating Curves= 0
DSS Export Rating Curve Sorted= 0
DSS Export Volume Flow Curves= 0
DXF OffsetX= 0
DXF OffsetY= 0
DXF ScaleX= 1
DXF ScaleY= 10

--- DEVILS JUMP CREEK TRIBUTARY 3.p01 (plan) ---

Plan Title=Multiple Run
Short Identifier=Multiple
Geom File=g01
Flow File=f01
Subcritical Flow
K Sum by GR= 0
Std Step Tol= 0.01
Critical Tol= 0.01
Num of Std Step Trials= 20
Max Error Tol= 0.3
Flow Tol Ratio= 0.001
Split Flow NTrial= 30
Split Flow Tol= 0.02
Split Flow Ratio= 0.02
Log Output Level= 0
Friction Slope Method= 1
Unsteady Friction Slope Method= 2
Unsteady Bridges Friction Slope Method= 1
Parabolic Critical Depth
Global Vel Dist=  1 , 1 , 1
Global Log Level= 0
CheckData=True
Encroach Param= -1, 0, 0, 0
BEGIN DESCRIPTION:
Multiple Run
END DESCRIPTION:

--- DEVILS JUMP CREEK TRIBUTARY 3.f01 (steady flow) ---

Flow Title=Multiple
Number of Profiles=7
Profile Names=10-year,25-year,50-year,1pct_min,100-year,1pct_plu,500-year
River Rch & RM= DEVILS JUMP CREE,Reach-1,6078
     375     498     597     526     712     963    1012
Boundary for River Rch & Prof#=DEVILS JUMP CREE,Reach-1,1
Up Type=0
Dn Type=3
Dn Slope=0.005
Boundary for River Rch & Prof#=DEVILS JUMP CREE,Reach-1,2
Up Type=0
Dn Type=3
Dn Slope=0.005
Boundary for River Rch & Prof#=DEVILS JUMP CREE,Reach-1,3
Up Type=0
Dn Type=3
Dn Slope=0.005
Boundary for River Rch & Prof#=DEVILS JUMP CREE,Reach-1,4
Up Type=0
Dn Type=3
Dn Slope=0.005
Boundary for River Rch & Prof#=DEVILS JUMP CREE,Reach-1,5
Up Type=0
Dn Type=3
Dn Slope=0.005
Boundary for River Rch & Prof#=DEVILS JUMP CREE,Reach-1,6
Up Type=0
Dn Type=3
Dn Slope=0.005
Boundary for River Rch & Prof#=DEVILS JUMP CREE,Reach-1,7
Up Type=0
Dn Type=3
Dn Slope=0.005

--- DEVILS JUMP CREEK TRIBUTARY 3.g01 (geometry) ---

Geom Title=Existing Conditions
Program Version=4.10

River Reach=DEVILS JUMP CREE,Reach-1
Reach XY= 30
      3564788.08     10345746.34        3565356.     10346214.26
      3565426.53     10346222.35      3565494.02     10346495.85
      3565775.56     10346894.19       3565944.5     10346951.38
      3566028.84      10346876.5      3566113.85     10346909.11
      3566176.16     10346866.46      3566298.83     10346973.16
      3566278.69     10347101.31      3566329.82     10347176.08
      3566246.11     10347551.08      3566316.38     10347619.17
      3566335.62     10347705.14      3566451.15     10347761.01
      3566228.51     10348088.86      3566236.48     10348173.75
      3566174.06     10348226.35      3566218.65     10348277.13
      3566338.76     10348279.24       3566370.7     10348366.08
        3566237.     10348643.56      3566084.96     10348735.05
       3565975.8     10348749.49      3565839.87     10348895.44
      3565802.01     10349211.71      3565905.41     10349610.45
      3566058.44     10349688.24       3566251.6     10350012.85

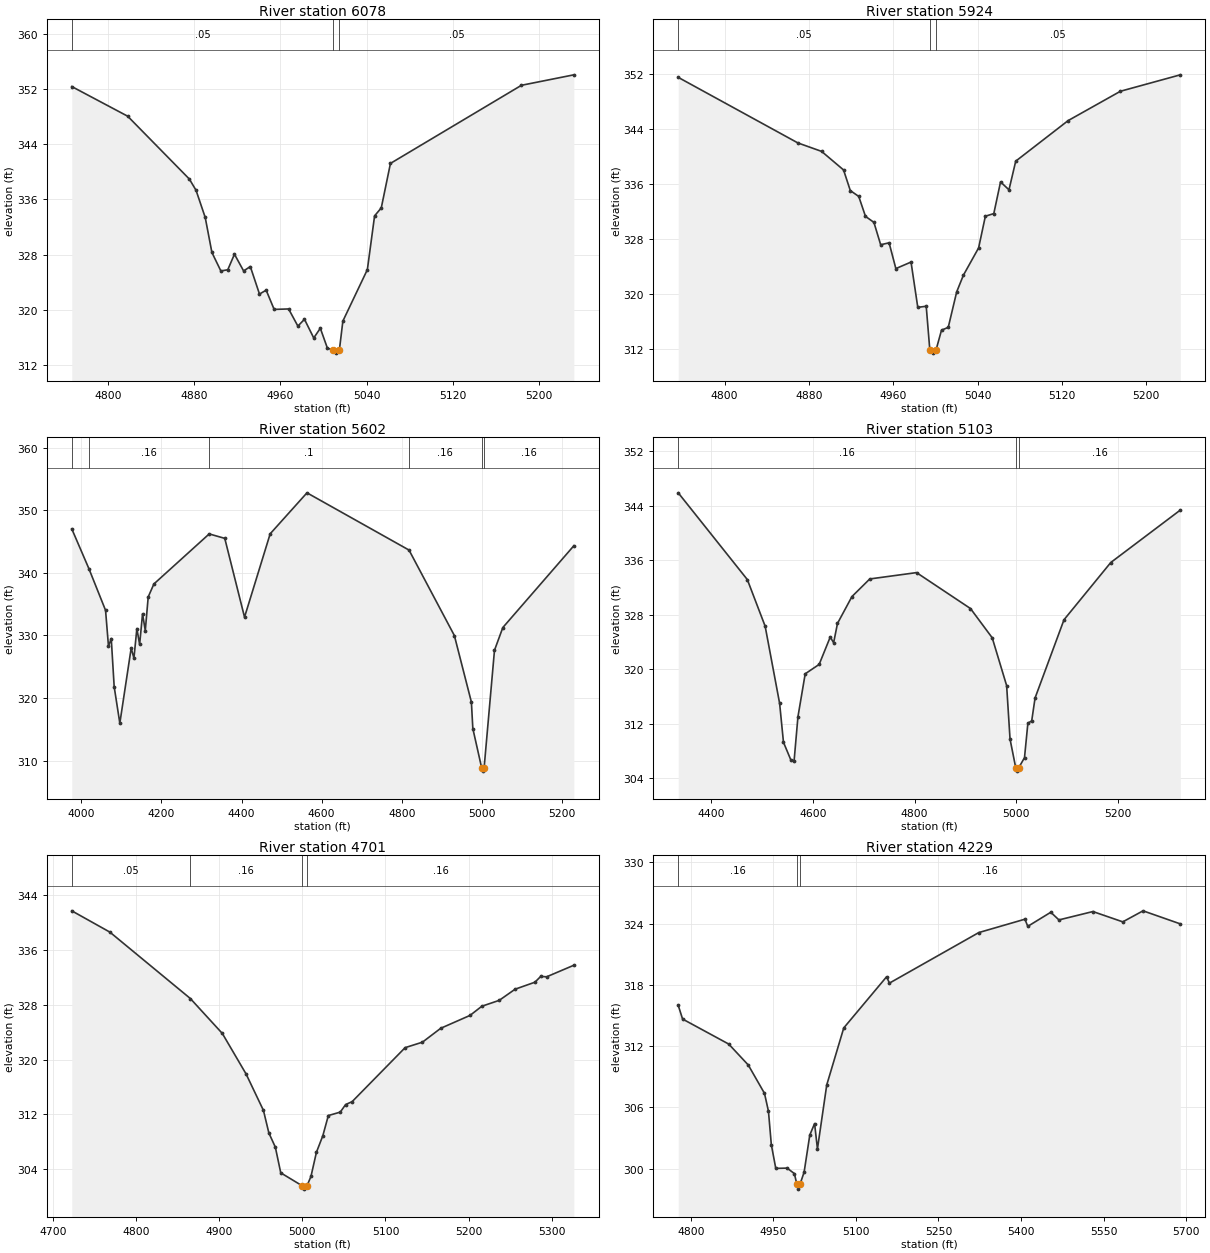
Type RM Length L Ch R = 1 ,6078    ,154,154,154
BEGIN DESCRIPTION:
DEVILS JUMP CREEK TRIBUTARY 3 11.0
END DESCRIPTION:
XS GIS Cut Line= 2
      3564752.23     10346013.63      3565025.09     10345636.62
#Sta/Elev= 30
  4766.7  352.38  4818.5  348.08  4875.7  338.96  4881.9  337.33  4890.4  333.39
  4896.6  328.31  4904.9  325.63  4911.3   325.8  4917.5  328.06    4926  325.63
  4932.2  326.27  4940.7  322.28  4946.9  322.84  4954.3  320.05  4967.7  320.12
  4976.3  317.63  4982.4  318.62    4991  315.91  4997.1  317.32  5003.7  314.41
  5008.8  314.21  5011.6  313.71  5014.8  314.21    5018  318.36  5040.7  325.82
  5047.4  333.62  5053.6  334.78  5062.1  341.23  5183.5  352.56  5232.1  354.08
#Mann= 3 ,-1 , 0
  4766.7     .05       0  5008.8     .04       0  5014.8     .05       0
Bank Sta=5008.8,5014.8
XS Rating Curve= 0 ,0
Exp/Cntr=0.3,0.1

Type RM Length L Ch R = 1 ,5924    ,322,322,322
BEGIN DESCRIPTION:
Mapping XS 6dcab88e
END DESCRIPTION:
XS GIS Cut Line= 2
      3564858.75      10346108.4      3565155.44     10345735.92
#Sta/Elev= 30
    4756   351.5  4869.5  341.96    4892  340.73  4912.8  338.03  4919.2  335.03
  4927.2  334.18  4933.6  331.28  4941.6   330.4    4948  327.15    4956  327.43
  4962.4  323.68  4976.8  324.63  4983.2  318.04  4991.2   318.2  4994.6  311.88
  4997.4  311.38  5000.6  311.88  5005.7  314.72  5012.1  315.13  5020.1  320.29
  5026.5  322.73  5040.9  326.69  5047.3   331.3  5055.3  331.68  5061.7  336.29
  5069.7  335.14  5076.1  339.31  5125.8  345.21  5175.4  349.48  5232.2  351.87
#Mann= 3 ,-1 , 0
    4756     .05       0  4994.6     .04       0  5000.6     .05       0
Bank Sta=4994.6,5000.6
XS Rating Curve= 0 ,0
Exp/Cntr=0.3,0.1

Type RM Length L Ch R = 1 ,5602    ,499,499,499
BEGIN DESCRIPTION:
DEVILS JUMP CREEK TRIBUTARY 3 10.0
END DESCRIPTION:
XS GIS Cut Line= 3
      3564552.64     10346871.59      3565242.11     10346141.64
      3565396.61     10345946.99
#Sta/Elev= 30
  3976.5  347.02  4019.2  340.67  4060.8  334.01  4068.1  328.28    4075  329.51
  4082.3  321.82  4096.4  315.99  4124.7  327.97  4131.6  326.37  4138.9   331.1
  4145.8  328.57  4153.1  333.47  4159.9  330.77  4167.2  336.15  4181.4  338.22
  4319.4  346.21  4358.2   345.5  4407.5  332.92  4471.5  346.23  4563.3  352.77
  4817.9  343.63    4931  329.99  4973.5  319.36  4977.1  315.14  4999.2  308.84
    5002  308.34  5005.2  308.84  5031.1  327.63  5051.9  331.26  5229.1  344.32
#Mann= 6 ,-1 , 0
  3976.5     .05       0  4019.2     .16       0  4319.4      .1       0
  4817.9     .16       0  4999.2     .07       0  5005.2     .16       0
Bank Sta=4999.2,5005.2
XS Rating Curve= 0 ,0
Exp/Cntr=0.3,0.1

Type RM Length L Ch R = 1 ,5103    ,402,402,402
BEGIN DESCRIPTION:
DEVILS JUMP CREEK TRIBUTARY 3 9.0
END DESCRIPTION:
XS GIS Cut Line= 3
      3565055.05     10346996.97      3565105.04     10346946.98
      3565707.76     10346254.15
#Sta/Elev= 30
  4334.6  345.87  4470.7  333.15  4505.8  326.31  4534.3     315  4541.9  309.29
  4556.2  306.74  4562.8  306.54  4570.4  313.03  4584.7  319.33  4612.2  320.71
    4634  324.72  4640.7  323.89  4648.3  326.72  4676.8  330.66  4711.9  333.24
    4804  334.17  4910.3   328.9  4953.1  324.61  4981.5   317.6  4988.2  309.75
  4999.4  305.56  5002.2  305.06  5005.4  305.56  5016.7  307.04  5023.3  312.07
  5030.9  312.44  5037.5  315.79  5094.5  327.26  5186.6  335.65  5323.6  343.34
#Mann= 3 ,-1 , 0
  4334.6     .16       0  4999.4     .07       0  5005.4     .16       0
Bank Sta=4999.4,5005.4
XS Rating Curve= 0 ,0
Exp/Cntr=0.3,0.1

Type RM Length L Ch R = 1 ,4701    ,472,472,472
BEGIN DESCRIPTION:
DEVILS JUMP CREEK TRIBUTARY 3 8.0
END DESCRIPTION:
XS GIS Cut Line= 3
      3565557.93     10347022.11      3565903.38     10346614.24
      3565952.17     10346565.45
#Sta/Elev= 30
  4722.9  341.75  4768.7  338.64  4865.4  328.94  4903.9  323.83  4932.4  317.92
  4953.3  312.59  4959.8   309.3  4967.6  307.22  4974.1  303.47  4999.7  301.59
  5002.4  301.09  5005.7  301.59  5010.4  302.94    5017  306.48  5024.7   308.9
  5031.3  311.84  5045.6  312.34  5052.1  313.45  5059.9  313.87  5123.6  321.76
  5144.4  322.56  5166.4  324.59  5201.6  326.47  5215.8  327.81  5236.7  328.67
  5255.8   330.3  5279.6  331.32  5286.6  332.17  5293.7  332.11  5326.4   333.8
#Mann= 4 ,-1 , 0
  4722.9     .05       0  4865.4     .16       0  4999.7     .07       0
  5005.7     .16       0
Bank Sta=4999.7,5005.7
XS Rating Curve= 0 ,0
Exp/Cntr=0.3,0.1

Type RM Length L Ch R = 1 ,4229    ,512,512,512
BEGIN DESCRIPTION:
DEVILS JUMP CREEK TRIBUTARY 3 7.0
END DESCRIPTION:
XS GIS Cut Line= 3
      3566024.38     10347115.25      3566074.36     10347015.29
      3566262.15     10346237.29
#Sta/Elev= 30
  4777.2     316  4785.1  314.66  4868.9  312.21  4904.4  310.16  4933.9  307.38
  4941.1  305.63  4946.3  302.36  4954.4  300.03    4975  300.06  4988.2  299.52
  4992.6   298.5  4995.3     298  4998.6   298.5  5005.9  299.67  5016.2   303.3
  5024.9  304.42  5030.1  301.94    5047  308.21  5077.9  313.79  5155.7   318.8
  5160.9  318.18  5323.2  323.13    5407  324.44  5412.2  323.74    5454  325.12
  5468.8  324.37  5530.5  325.19  5584.8  324.18  5621.6  325.26  5689.3  323.98
#Mann= 3 ,-1 , 0
  4777.2     .16       0  4992.6     .07       0  4998.6     .16       0
Bank Sta=4992.6,4998.6
XS Rating Curve= 0 ,0
Exp/Cntr=0.3,0.1

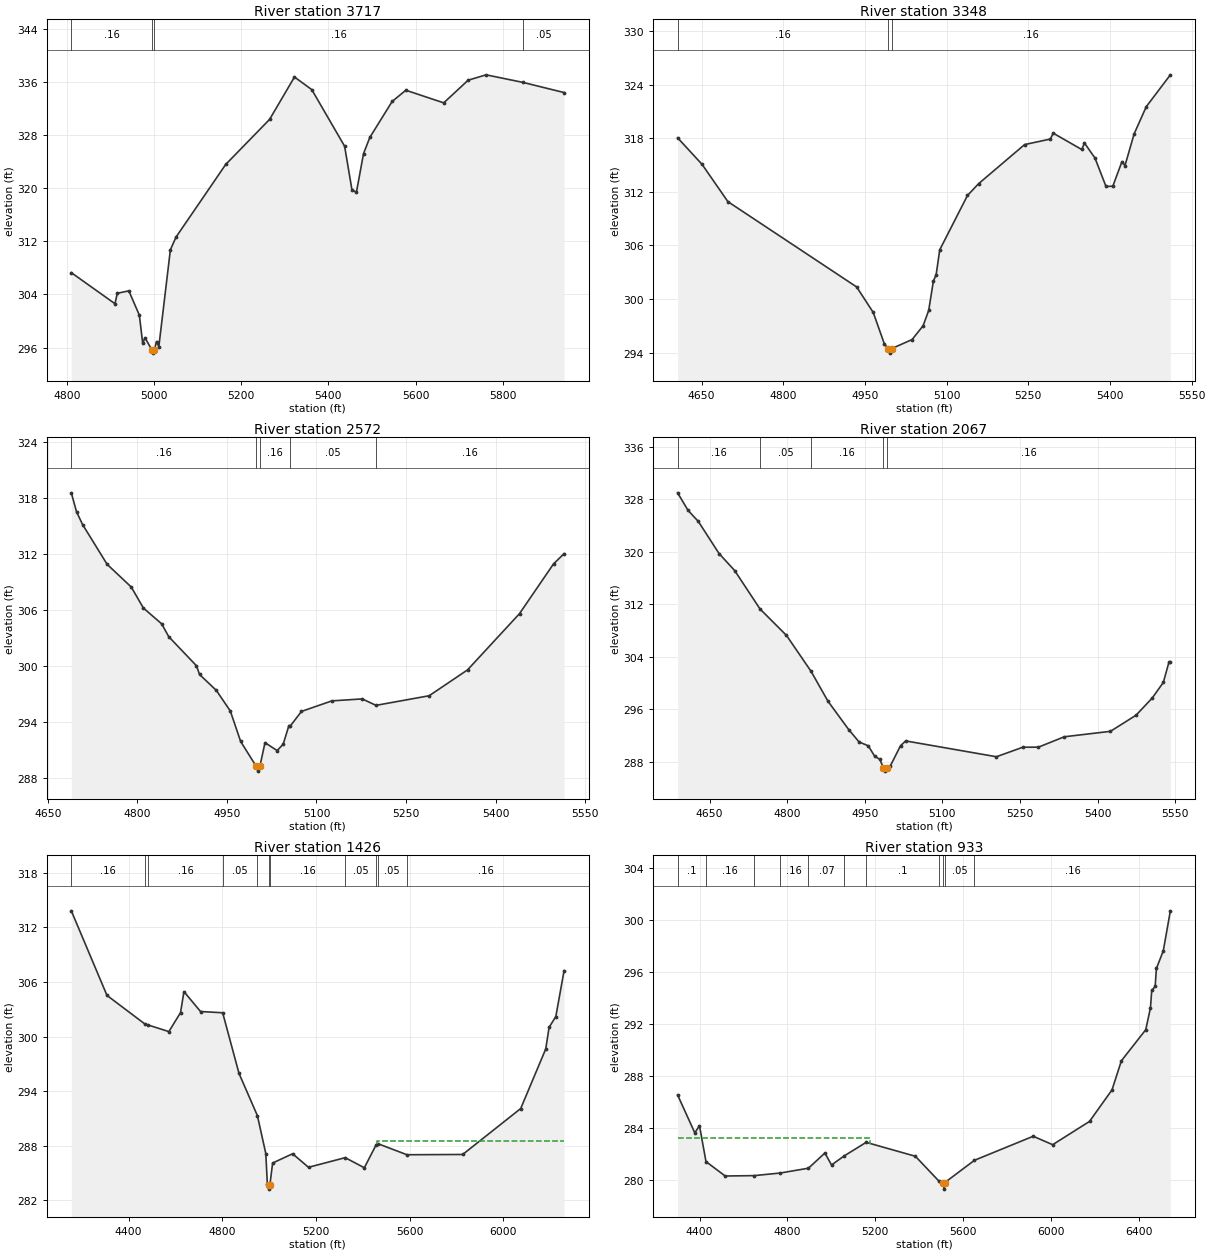
Type RM Length L Ch R = 1 ,3717    ,369,369,369
BEGIN DESCRIPTION:
DEVILS JUMP CREEK TRIBUTARY 3 6.0
END DESCRIPTION:
XS GIS Cut Line= 3
      3566143.89     10347258.68      3566633.09      10347097.4
      3566767.16     10346496.78
#Sta/Elev= 30
  4810.1  307.28  4910.3   302.6  4915.6  304.17  4942.1  304.54  4966.2  300.88
  4973.9  296.64  4979.1  297.48  4994.8  295.66  4997.5  295.16  5000.8  295.66
  5005.6  296.91  5010.9  296.13  5037.4  310.72  5050.4  312.64  5164.4  323.58
    5265  330.36  5322.1  336.74  5361.8  334.84  5437.1  326.32  5454.1   319.7
  5464.3  319.41  5480.5   325.2    5495  327.65  5546.3  333.07  5577.6  334.75
  5664.5  332.85  5720.5  336.26  5761.7  337.07  5846.9  335.92  5940.6   334.4
#Mann= 4 ,-1 , 0
  4810.1     .16       0  4994.8     .07       0  5000.8     .16       0
  5846.9     .05       0
Bank Sta=4994.8,5000.8
XS Rating Curve= 0 ,0
Exp/Cntr=0.3,0.1

Type RM Length L Ch R = 1 ,3348    ,776,776,776
BEGIN DESCRIPTION:
DEVILS JUMP CREEK TRIBUTARY 3 5.0
END DESCRIPTION:
XS GIS Cut Line= 3
      3565858.98     10347624.24      3566639.92     10347477.13
      3566738.51     10347427.84
#Sta/Elev= 30
    4606  318.05    4651  315.07  4698.4   310.9  4934.8  301.35  4965.3  298.49
  4985.7  294.97  4992.9  294.44  4995.6  293.94  4998.9  294.44  5036.6  295.46
  5056.9  297.01  5067.1  298.72  5075.7     302  5080.8  302.72  5087.4  305.51
  5138.3  311.59  5158.7  312.91  5243.2  317.29  5290.6  317.91  5295.7  318.57
  5348.1  316.74  5353.2  317.46  5372.4  315.79  5392.7   312.6  5405.2  312.63
    5422  315.38  5427.6  314.94  5444.4   318.5  5466.7  321.54  5510.9   325.1
#Mann= 3 ,-1 , 0
    4606     .16       0  4992.9     .07       0  4998.9     .16       0
Bank Sta=4992.9,4998.9
XS Rating Curve= 0 ,0
Exp/Cntr=0.3,0.1

Type RM Length L Ch R = 1 ,2572    ,505,505,505
BEGIN DESCRIPTION:
DEVILS JUMP CREEK TRIBUTARY 3 4.0
END DESCRIPTION:
XS GIS Cut Line= 3
      3565923.51      10348167.2      3566557.14     10348043.78
      3566707.13      10347943.8
#Sta/Elev= 30
  4689.1  318.55  4697.9  316.51    4708  315.15  4749.1  310.89  4789.6  308.45
  4809.9   306.2  4840.5  304.51  4852.4  303.13  4898.9  300.01    4904  299.08
  4932.2  297.37  4955.6  295.16  4972.9   291.9  4999.1  289.22  5001.9  288.72
  5005.1  289.22  5013.7  291.77  5034.1  290.92  5044.2  291.61  5053.8  293.61
  5055.9  293.54  5074.8  295.12  5125.8  296.25  5176.7  296.46  5199.7  295.77
  5288.8   296.8  5353.1  299.57  5440.2   305.6  5497.3  310.94  5514.9  312.03
#Mann= 5 ,-1 , 0
  4689.1     .16       0  4999.1     .07       0  5005.1     .16       0
  5055.9     .05       0  5199.7     .16       0
Bank Sta=4999.1,5005.1
XS Rating Curve= 0 ,0
Exp/Cntr=0.3,0.1

Type RM Length L Ch R = 1 ,2067    ,641,641,641
BEGIN DESCRIPTION:
DEVILS JUMP CREEK TRIBUTARY 3 2.0
END DESCRIPTION:
XS GIS Cut Line= 3
      3565942.07     10348391.64       3566520.2     10348430.62
      3566842.08     10348241.66
#Sta/Elev= 30
  4588.1  328.98  4608.2  326.32  4628.2  324.62  4668.3  319.73  4698.4  317.15
  4747.4   311.3  4798.6  307.27  4846.1   301.8  4878.8  297.25  4918.9  292.93
  4938.9  291.05  4956.8  290.45    4969  288.88    4979   288.4    4986   287.1
  4988.8   286.6    4992   287.1  4999.1  287.35  5019.1  290.47  5029.1   291.2
  5204.5  288.79  5255.6  290.24  5285.7  290.25  5335.7  291.83  5424.9  292.66
  5474.4  295.11  5505.7  297.73  5527.2  300.11  5537.9  303.15  5540.8  303.15
#Mann= 5 ,-1 , 0
  4588.1     .16       0  4747.4     .05       0  4846.1     .16       0
    4986     .07       0    4992     .16       0
Bank Sta=4986,4992
XS Rating Curve= 0 ,0
Exp/Cntr=0.3,0.1

Type RM Length L Ch R = 1 ,1426    ,493,493,493
BEGIN DESCRIPTION:
Mapping XS dc2f0208
END DESCRIPTION:
XS GIS Cut Line= 3
      3565255.19     10348305.08      3566062.46     10348917.04
      3566906.58     10348226.17
#Sta/Elev= 30
  4155.8  313.82  4308.1  304.52  4468.8   301.4  4484.5  301.26  4572.3  300.54
  4622.2  302.63  4636.7  304.94  4707.5  302.75    4802  302.61  4871.8  295.94
  4950.3   291.3  4986.2  287.13  4992.7  283.83  4997.8  283.72  5000.5  283.22
  5003.8  283.72  5015.3  286.09  5100.6  287.11  5168.5  285.62  5325.1  286.68
  5406.8  285.57  5457.8  288.12  5463.3  288.23  5588.9     287  5826.7  287.03
  6074.4  292.08  6181.3  298.63  6195.7  301.01  6224.4   302.2  6259.6  307.24
#Mann= 11 ,-1 , 0
  4155.8     .16       0  4468.8     .05       0  4484.5     .16       0
    4802     .05       0  4950.3     .16       0  4997.8     .07       0
  5003.8     .16       0  5325.1     .05       0  5457.8     .16       0
  5463.3     .05       0  5588.9     .16       0
#XS Ineff= 2 , 0
                         5461.65          288.54
Permanent Ineff=
       F       F
Bank Sta=4997.8,5003.8
XS Rating Curve= 0 ,0
Exp/Cntr=0.3,0.1

Type RM Length L Ch R = 1 ,933     ,527,527,527
BEGIN DESCRIPTION:
Mapping XS f1fad64e
END DESCRIPTION:
XS GIS Cut Line= 4
      3565377.57     10348797.25      3565671.84     10349273.81
      3566364.55      10349203.5      3566871.74     10348355.58
#Sta/Elev= 30
  4299.6  286.55    4378  283.63  4399.3  284.18  4428.9  281.42  4516.3  280.31
    4649  280.34  4767.3  280.54  4895.5  280.91  4970.5  282.08  5000.7  281.16
  5058.7  281.86  5158.4   282.9  5382.6  281.83  5489.7  279.92  5510.3   279.8
  5513.1   279.3  5516.3   279.8  5651.7  281.52  5919.4  283.37  6007.9  282.72
  6175.7  284.51  6278.2  286.94    6321  289.18  6431.9  291.57  6453.3  293.25
  6459.1  294.59  6474.7   294.9  6480.5  296.29  6511.6  297.63    6544  300.72
#Mann= 11 ,-1 , 0
  4299.6      .1       0  4428.9     .16       0    4649     .05       0
  4767.3     .16       0  4895.5     .07       0  5058.7     .12       0
  5158.4      .1       0  5489.7     .05       0  5510.3     .07       0
  5516.3     .05       0  5651.7     .16       0
#XS Ineff= 2 , 0
         5177.84  283.26
Permanent Ineff=
       F       F
Bank Sta=5510.3,5516.3
XS Rating Curve= 0 ,0
Exp/Cntr=0.3,0.1

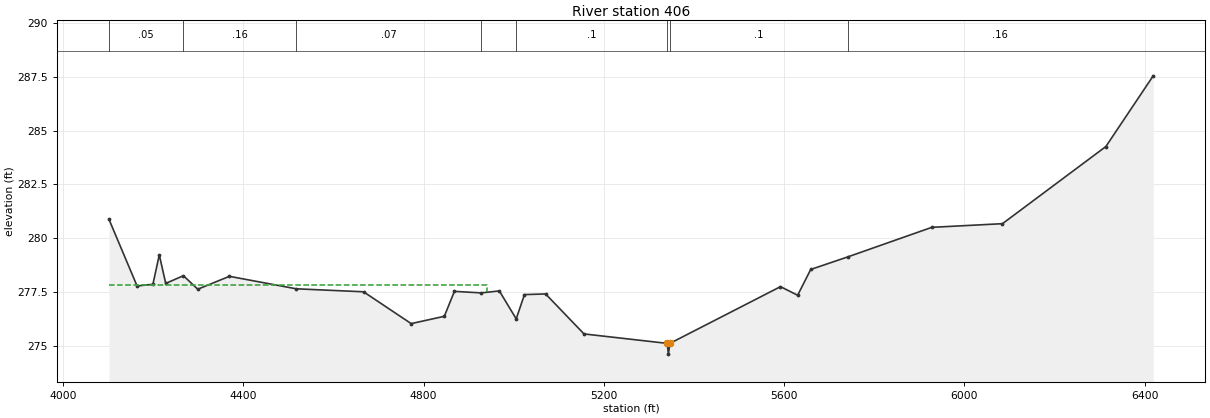
Type RM Length L Ch R = 1 ,406     ,0,0,0
BEGIN DESCRIPTION:
DEVILS JUMP CREEK TRIBUTARY 3 1.0
END DESCRIPTION:
XS GIS Cut Line= 4
      3565382.75     10349263.37      3565823.75     10349756.45
      3566420.97      10349537.7      3566875.32     10348625.54
#Sta/Elev= 30
  4102.1  280.87  4164.4  277.77  4199.5  277.85  4213.7  279.22  4227.9  277.89
  4267.2  278.25    4299  277.62  4369.2  278.22  4517.5  277.64  4666.8   277.5
  4772.5  276.02    4846  276.36  4868.4  277.52  4927.5  277.45  4968.1  277.54
  5005.5  276.24  5023.8  277.37  5070.7   277.4  5155.9  275.54  5340.4   275.1
  5343.2   274.6  5346.4   275.1  5591.8  277.74  5629.9  277.34  5658.9  278.54
  5740.5  279.12  5927.6   280.5  6084.3  280.67  6313.7  284.26  6418.7  287.55
#Mann= 8 ,-1 , 0
  4102.1     .05       0  4267.2     .16       0  4517.5     .07       0
  4927.5     .12       0  5005.5      .1       0  5340.4     .07       0
  5346.4      .1       0  5740.5     .16       0
#XS Ineff= 2 , 0
         4940.34   277.8
Permanent Ineff=
       F       F
Bank Sta=5340.4,5346.4
XS Rating Curve= 0 ,0
Exp/Cntr=0.3,0.1

Chan Stop Cuts=-1
Use User Specified Reach Order=0
Composite Channel Slope=5