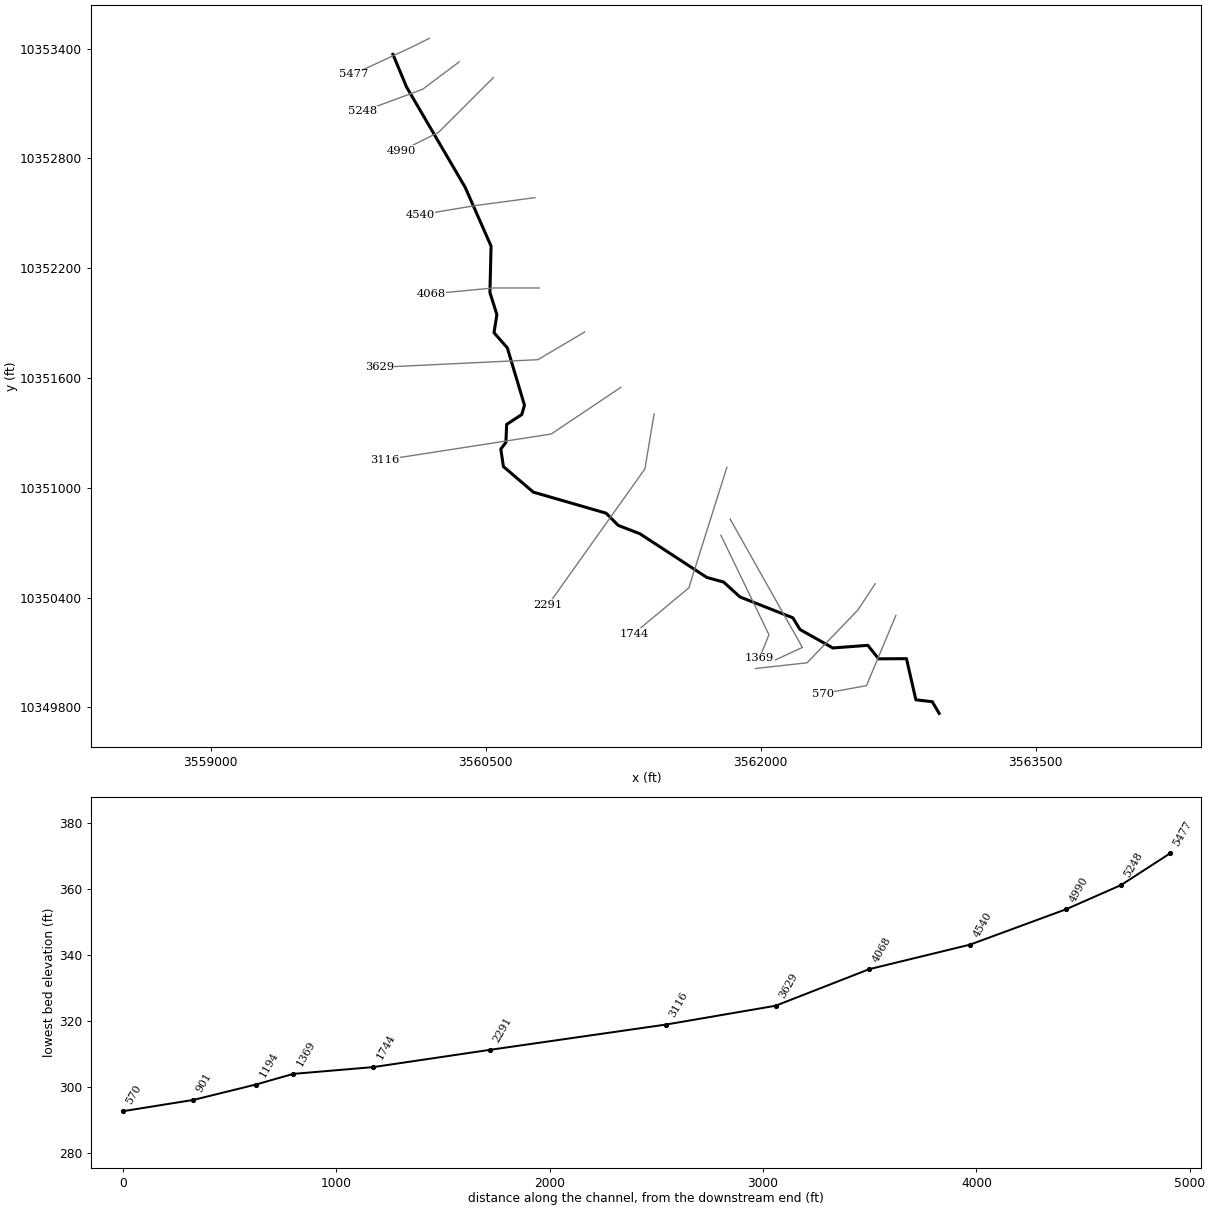
--- DEVILS JUMP CREEK TRIBUTARY 6.prj (project) ---

Proj Title=DEVILS JUMP CREEK TRIBUTARY 6 Base Level Engineering
Current Plan=p01
Default Exp/Contr=0.3,0.1
English Units
Geom File=g01
Flow File=f01
Plan File=p01
Y Axis Title=Elevation
X Axis Title(PF)=Main Channel Distance
X Axis Title(XS)=Station
BEGIN DESCRIPTION:
DEVILS JUMP CREEK TRIBUTARY 6
END DESCRIPTION:
DSS Export Rating Curves= 0
DSS Export Rating Curve Sorted= 0
DSS Export Volume Flow Curves= 0
DXF OffsetX= 0
DXF OffsetY= 0
DXF ScaleX= 1
DXF ScaleY= 10

--- DEVILS JUMP CREEK TRIBUTARY 6.p01 (plan) ---

Plan Title=Multiple Run
Short Identifier=Multiple
Geom File=g01
Flow File=f01
Subcritical Flow
K Sum by GR= 0
Std Step Tol= 0.01
Critical Tol= 0.01
Num of Std Step Trials= 20
Max Error Tol= 0.3
Flow Tol Ratio= 0.001
Split Flow NTrial= 30
Split Flow Tol= 0.02
Split Flow Ratio= 0.02
Log Output Level= 0
Friction Slope Method= 1
Unsteady Friction Slope Method= 2
Unsteady Bridges Friction Slope Method= 1
Parabolic Critical Depth
Global Vel Dist=  1 , 1 , 1
Global Log Level= 0
CheckData=True
Encroach Param= -1, 0, 0, 0
BEGIN DESCRIPTION:
Multiple Run
END DESCRIPTION:

--- DEVILS JUMP CREEK TRIBUTARY 6.f01 (steady flow) ---

Flow Title=Multiple
Program Version=4.10
Number of Profiles= 7
Profile Names=10-year,25-year,50-year,1pct_min,100-year,1pct_plu,500-year
River Rch & RM=DEVILS JUMP CREE,Reach-1         ,5477
     654     886    1075     955    1291    1746    1856
Boundary for River Rch & Prof#=DEVILS JUMP CREE,Reach-1         , 1
Up Type= 0
Dn Type= 3
Dn Slope=0.016
Boundary for River Rch & Prof#=DEVILS JUMP CREE,Reach-1         , 2
Up Type= 0
Dn Type= 3
Dn Slope=0.016
Boundary for River Rch & Prof#=DEVILS JUMP CREE,Reach-1         , 3
Up Type= 0
Dn Type= 3
Dn Slope=0.016
Boundary for River Rch & Prof#=DEVILS JUMP CREE,Reach-1         , 4
Up Type= 0
Dn Type= 3
Dn Slope=0.016
Boundary for River Rch & Prof#=DEVILS JUMP CREE,Reach-1         , 5
Up Type= 0
Dn Type= 3
Dn Slope=0.016
Boundary for River Rch & Prof#=DEVILS JUMP CREE,Reach-1         , 6
Up Type= 0
Dn Type= 3
Dn Slope=0.016
Boundary for River Rch & Prof#=DEVILS JUMP CREE,Reach-1         , 7
Up Type= 0
Dn Type= 3
Dn Slope=0.016
DSS Import GetInterval= 0
DSS Import GetPeak= 0
DSS Import FillOption= 0

--- DEVILS JUMP CREEK TRIBUTARY 6.g01 (geometry) ---

Geom Title=Existing Conditions
Program Version=4.10

River Reach=DEVILS JUMP CREE,Reach-1
Reach XY= 30
      3559993.67     10353367.96      3560067.98     10353189.49
      3560388.11     10352640.88      3560528.84     10352320.66
      3560522.71     10352066.88      3560560.66     10351946.07
      3560544.96     10351847.24      3560617.56     10351764.52
      3560711.27     10351450.92      3560696.41     10351400.04
      3560613.84     10351346.14      3560609.89     10351247.61
      3560582.11     10351211.64      3560596.28     10351115.79
      3560759.27     10350976.19      3561156.53     10350861.13
      3561223.08     10350794.13       3561340.4     10350748.99
      3561706.45      10350509.8       3561797.6     10350484.84
      3561886.57     10350403.46       3562175.2     10350289.53
      3562214.27     10350225.51       3562393.3      10350124.6
      3562584.24     10350139.07      3562643.27     10350065.28
      3562795.18     10350066.15       3562846.4     10349841.32
      3562935.81     10349830.91      3562973.42     10349767.21

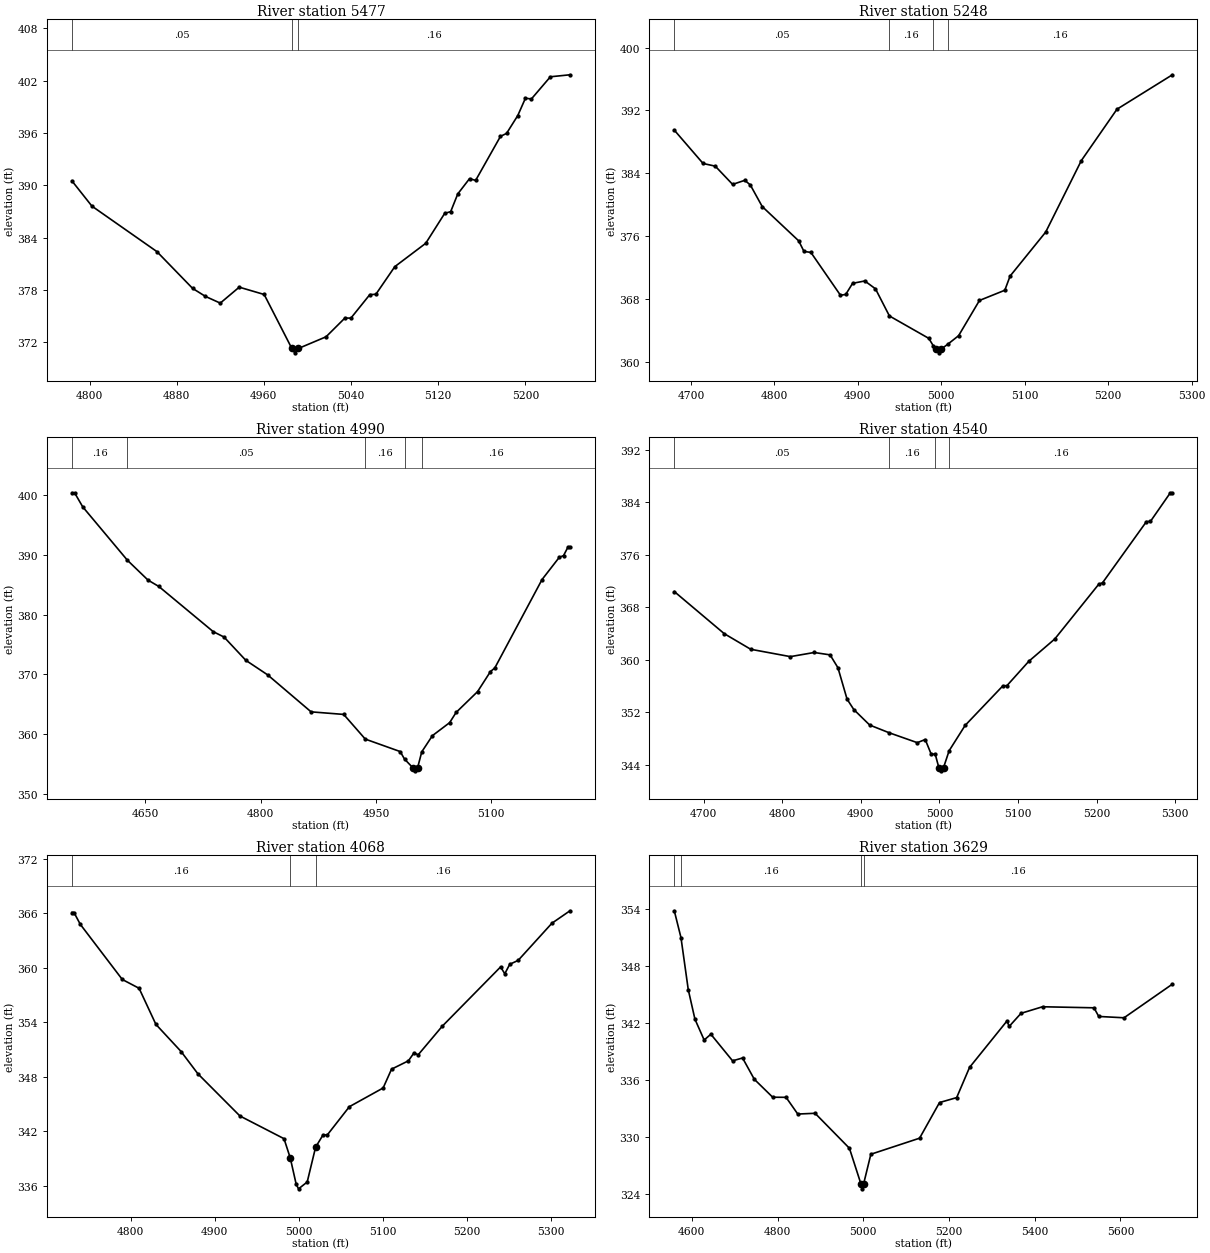
Type RM Length L Ch R = 1 ,5477    ,229,229,229
BEGIN DESCRIPTION:
DEVILS JUMP CREEK TRIBUTARY 6 12.0
END DESCRIPTION:
XS GIS Cut Line= 3
      3560191.86     10353455.71      3560091.85      10353405.7
      3559778.69     10353260.03
#Sta/Elev= 30
  4783.8   390.5  4802.2   387.6  4861.8  382.39  4894.6  378.17  4906.4  377.25
    4920  376.48  4937.4  378.31  4960.3  377.47  4985.7  371.28  4988.4  370.78
  4991.7  371.28  5017.1  372.62  5034.4  374.77  5039.9  374.76  5057.3  377.46
  5062.8  377.49  5080.2  380.66  5108.6  383.34    5126  386.77  5131.5  386.97
    5138     389  5148.8  390.75  5154.4  390.55  5177.2   395.6  5182.8  395.94
  5193.1  397.99  5200.1  399.97  5205.6  399.89    5223  402.43    5241  402.66
#Mann= 3 ,-1 , 0
  4783.8     .05       0  4985.7     .07       0  4991.7     .16       0
Bank Sta=4985.7,4991.7
XS Rating Curve= 0 ,0
Exp/Cntr=0.3,0.1

Type RM Length L Ch R = 1 ,5248    ,258,258,258
BEGIN DESCRIPTION:
DEVILS JUMP CREEK TRIBUTARY 6 11.0
END DESCRIPTION:
XS GIS Cut Line= 3
      3560355.02     10353327.13      3560155.01     10353177.12
      3559829.81     10353056.39
#Sta/Elev= 30
    4680   389.5  4714.5  385.26  4729.1  384.92  4749.9   382.6  4764.5  383.12
  4771.1  382.53  4785.4  379.78  4829.1  375.42  4835.4  374.08  4843.7  373.95
  4879.1  368.51  4885.4   368.6  4893.7  370.02  4908.3  370.32  4921.1  369.32
  4937.8  365.87    4985  363.02  4990.3  362.09  4994.1  361.68  4996.9  361.18
  5000.1  361.68  5007.8  362.28  5020.7  363.36  5045.7  367.84  5076.1  369.14
  5082.4  370.94  5125.1  376.54  5167.8  385.63  5210.5  392.16  5276.9  396.54
#Mann= 4 ,-1 , 0
    4680     .05       0  4937.8     .16       0  4990.3     .07       0
  5007.8     .16       0
Bank Sta=4994.1,5000.1
XS Rating Curve= 0 ,0
Exp/Cntr=0.3,0.1

Type RM Length L Ch R = 1 ,4990    ,450,450,450
BEGIN DESCRIPTION:
DEVILS JUMP CREEK TRIBUTARY 6 10.0
END DESCRIPTION:
XS GIS Cut Line= 3
      3560542.07     10353241.61      3560242.11     10352941.64
      3560042.13     10352841.65
#Sta/Elev= 30
  4554.6  400.45  4558.1  400.45  4568.7  398.09  4626.8  389.14  4653.6  385.81
  4667.7  384.74  4738.4  377.17  4752.5  376.26  4780.8  372.36  4809.1  369.93
  4865.7  363.72  4908.1  363.29  4936.2  359.15  4981.6  357.06  4987.2   355.8
  4998.2  354.33  5000.9  353.83  5004.2  354.33  5009.6  357.01  5023.5  359.73
  5045.9  361.91  5054.3  363.62  5082.2  367.11    5099  370.48  5104.6  371.07
  5166.1  385.91  5188.5  389.63    5194  389.91  5199.6   391.3  5202.4   391.3
#Mann= 5 ,-1 , 0
  4554.6     .16       0  4626.8     .05       0  4936.2     .16       0
  4987.2     .07       0  5009.6     .16       0
Bank Sta=4998.2,5004.2
XS Rating Curve= 0 ,0
Exp/Cntr=0.3,0.1

Type RM Length L Ch R = 1 ,4540    ,472,472,472
BEGIN DESCRIPTION:
DEVILS JUMP CREEK TRIBUTARY 6 9.0
END DESCRIPTION:
XS GIS Cut Line= 3
      3560768.42     10352585.27      3560442.11     10352541.64
      3560142.06     10352491.63
#Sta/Elev= 30
  4662.8   370.4  4726.3  363.99    4760  361.61  4810.4  360.49  4840.7  361.12
  4860.9  360.76  4870.9   358.8  4882.5  354.02  4891.1  352.43  4911.3  350.07
    4936   348.9  4971.8  347.39  4981.9  347.87  4989.5  345.64  4994.6  345.64
  4999.2   343.6  5001.9   343.1  5005.2   343.6  5012.3  346.16  5032.6  350.01
  5080.7  356.05  5085.8  356.07  5113.7  359.79  5146.6  363.17  5202.4  371.49
  5207.4  371.74  5263.2  381.05  5268.3  381.08  5293.6  385.44  5296.2  385.44
#Mann= 4 ,-1 , 0
  4662.8     .05       0    4936     .16       0  4994.6     .07       0
  5012.3     .16       0
Bank Sta=4999.2,5005.2
XS Rating Curve= 0 ,0
Exp/Cntr=0.3,0.1

Type RM Length L Ch R = 1 ,4068    ,439,439,439
BEGIN DESCRIPTION:
DEVILS JUMP CREEK TRIBUTARY 6 8.0
END DESCRIPTION:
XS GIS Cut Line= 3
      3560792.06     10352091.64      3560542.11     10352091.64
       3560200.7     10352059.23
#Sta/Elev= 30
  4729.8  366.07  4732.3  366.07  4739.8  364.77  4789.8   358.7  4809.8  357.73
  4829.8  353.76  4859.8  350.77  4879.8  348.32  4929.8  343.68  4982.3  341.18
  4989.8  339.04  4996.8  336.16  4999.6  335.66  5009.9  336.41  5019.9  340.24
  5028.8   341.6  5033.8  341.59  5060.1   344.7  5100.3  346.76  5110.3  348.83
  5130.4  349.75    5137  350.62    5142  350.41  5170.6  353.55  5240.1  360.08
  5245.1  359.33    5251  360.37    5261   360.8  5301.2  364.89  5322.7  366.26
#Mann= 3 , 0 , 0
  4729.8     .16       0  4989.8     .07       0  5019.9     .16       0
Bank Sta=4989.8,5019.9
XS Rating Curve= 0 ,0
Exp/Cntr=0.3,0.1

Type RM Length L Ch R = 1 ,3629    ,513,513,513
BEGIN DESCRIPTION:
DEVILS JUMP CREEK TRIBUTARY 6 7.0
END DESCRIPTION:
XS GIS Cut Line= 3
      3561039.19     10351850.87      3560784.01     10351699.85
      3559919.43     10351658.19
#Sta/Elev= 30
  4559.1  353.82  4574.7     351  4591.7  345.52  4607.3  342.41  4628.8  340.22
  4644.4  340.83  4695.1  338.03  4718.4  338.33  4745.8  336.09  4788.7   334.2
  4819.9  334.19  4847.2  332.43  4887.6  332.51  4967.7  328.83  4994.7  325.06
  4997.4  324.56  5000.7  325.06  5017.7   328.2  5131.4  329.89  5177.9  333.64
  5217.9  334.16    5248  337.34  5335.4  342.23  5340.4  341.65  5368.1  343.03
  5418.2  343.72  5538.3  343.61  5549.4   342.7  5608.4  342.56  5721.2   346.1
#Mann= 4 ,-1 , 0
  4559.1     .05       0  4574.7     .16       0  4994.7     .07       0
  5000.7     .16       0
Bank Sta=4994.7,5000.7
XS Rating Curve= 0 ,0
Exp/Cntr=0.3,0.1

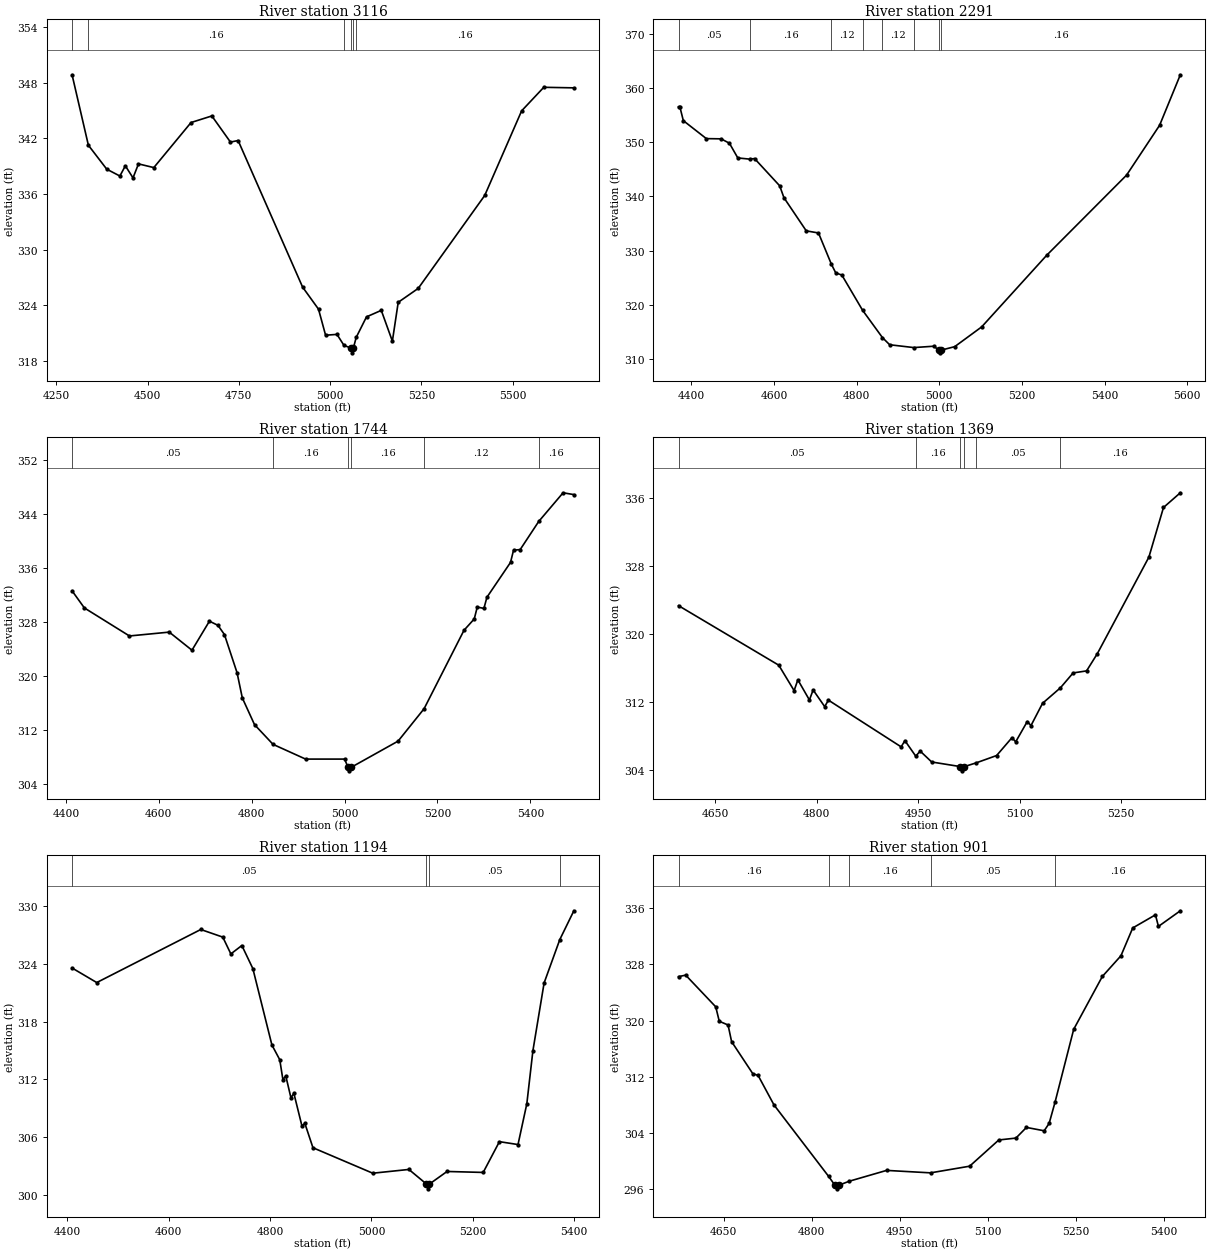
Type RM Length L Ch R = 1 ,3116    ,825,825,825
BEGIN DESCRIPTION:
DEVILS JUMP CREEK TRIBUTARY 6 6.0
END DESCRIPTION:
XS GIS Cut Line= 3
       3561237.1     10351548.79      3560856.93      10351293.6
      3559950.65     10351152.97
#Sta/Elev= 30
    4293  348.85  4337.7  341.25    4388  338.67    4424  337.93    4439  339.03
    4460  337.73    4475  339.24    4517  338.84    4619   343.7    4676  344.41
    4727  341.59    4748  341.76  4924.7  325.95  4968.3  323.57  4987.7  320.76
  5018.9  320.85    5038  319.67  5057.8  319.36  5060.5  318.86  5063.8  319.36
  5071.5  320.52  5099.8  322.74  5140.3  323.44  5170.7  320.12  5186.7  324.31
  5241.5  325.81  5423.7  335.83  5524.9  344.96  5585.6   347.5    5668  347.44
#Mann= 6 ,-1 , 0
    4293     .05       0  4337.7     .16       0    5038     .12       0
  5057.8     .07       0  5063.8     .12       0  5071.5     .16       0
Bank Sta=5057.8,5063.8
XS Rating Curve= 0 ,0
Exp/Cntr=0.3,0.1

Type RM Length L Ch R = 1 ,2291    ,547,547,547
BEGIN DESCRIPTION:
DEVILS JUMP CREEK TRIBUTARY 6 5.0
END DESCRIPTION:
XS GIS Cut Line= 3
      3561418.15     10351403.13      3561368.15      10351103.1
      3560841.31     10350361.32
#Sta/Elev= 30
  4369.1  356.51  4372.3  356.51  4380.7  353.96  4436.4  350.65    4472  350.61
  4492.2   349.8  4512.5  347.09  4541.7  346.87    4553  346.98  4613.8  341.96
  4624.1  339.77  4678.1  333.66  4707.7  333.27  4739.1  327.48  4749.5  325.91
  4764.2  325.52  4814.3  319.04  4862.4     314  4879.9  312.68  4938.2  312.16
  4986.9  312.41  4998.6  311.69  5001.4  311.19  5004.6  311.69  5037.3  312.33
  5102.5  315.97  5259.9  329.17  5453.1  343.93    5533  353.11  5583.1  362.41
#Mann= 8 ,-1 , 0
  4369.1     .05       0  4541.7     .16       0  4739.1     .12       0
  4814.3     .16       0  4862.4     .12       0  4938.2     .16       0
  4998.6     .07       0  5004.6     .16       0
Bank Sta=4998.6,5004.6
XS Rating Curve= 0 ,0
Exp/Cntr=0.3,0.1

Type RM Length L Ch R = 1 ,1744    ,375,375,375
BEGIN DESCRIPTION:
DEVILS JUMP CREEK TRIBUTARY 6 3.0
END DESCRIPTION:
XS GIS Cut Line= 3
      3561815.25     10351111.27      3561607.73      10350453.1
      3561307.75     10350203.12
#Sta/Elev= 30
  4413.1   332.6  4439.6  330.07  4536.6  325.92  4622.4  326.49  4671.3  323.81
  4708.9  328.11  4727.3  327.49  4741.2  326.13  4768.4  320.48  4779.7  316.75
    4806  312.79  4845.9  309.87    4916  307.69  4999.9  307.69  5007.6  306.45
  5010.3  305.95  5013.6  306.45  5115.2  310.35  5171.2  315.15  5257.1  326.76
  5279.2  328.44  5285.7   330.2    5300     330  5306.5  331.65  5357.3  336.81
  5363.8  338.62  5378.1  338.71    5418  342.87  5470.5  347.12  5493.7  346.85
#Mann= 6 ,-1 , 0
  4413.1     .05       0  4845.9     .16       0  5007.6     .07       0
  5013.6     .16       0  5171.2     .12       0    5418     .16       0
Bank Sta=5007.6,5013.6
XS Rating Curve= 0 ,0
Exp/Cntr=0.3,0.1

Type RM Length L Ch R = 1 ,1369    ,175,175,175
BEGIN DESCRIPTION:
DEVILS JUMP CREEK TRIBUTARY 6 2.0
END DESCRIPTION:
XS GIS Cut Line= 3
      3561782.79     10350740.38      3562044.93       10350197.
      3561992.86     10350068.56
#Sta/Elev= 30
  4595.6  323.31  4743.8  316.31  4766.5  313.32    4772  314.59  4789.1  312.22
  4794.6   313.4  4811.7  311.44  4817.2   312.2  4924.7  306.71  4930.3  307.44
  4946.3  305.62  4952.9  306.21  4969.9  304.93  5012.2  304.39  5014.9  303.89
  5018.2  304.39  5035.8  304.83  5065.9  305.69  5088.6  307.79  5094.1   307.3
  5111.2  309.69  5116.7  309.21  5133.8  311.83  5160.2  313.65    5179   315.4
  5198.9  315.64  5214.9  317.68    5291  329.01  5312.6  334.85  5337.5  336.58
#Mann= 6 ,-1 , 0
  4595.6     .05       0  4946.3     .16       0  5012.2     .07       0
  5018.2     .16       0  5035.8     .05       0  5160.2     .16       0
Bank Sta=5012.2,5018.2
XS Rating Curve= 0 ,0
Exp/Cntr=0.3,0.1

Type RM Length L Ch R = 1 ,1194    ,293,293,293
BEGIN DESCRIPTION:
Mapping XS 0ad07767
END DESCRIPTION:
XS GIS Cut Line= 3
      3561833.14     10350828.91      3562227.22     10350127.56
      3562058.84     10350049.45
#Sta/Elev= 30
  4409.2  323.55  4457.9  322.04  4663.2  327.54  4706.6  326.75  4722.5  325.01
  4744.2  325.88  4765.9  323.49  4803.5  315.57    4819  314.04  4825.2  311.98
  4830.9  312.36  4841.1  310.09  4846.8  310.57  4862.8  307.17  4868.5  307.45
  4884.5  304.92  5002.5  302.28  5073.8  302.67  5108.4  301.16  5111.2  300.66
  5114.4  301.16  5149.1  302.46  5220.4  302.36  5252.4  305.55  5289.1  305.25
  5306.5  309.48  5318.5  314.98  5340.6     322  5371.6   326.5  5399.3  329.48
#Mann= 4 ,-1 , 0
  4409.2     .05       0  5108.4     .04       0  5114.4     .05       0
  5371.6     .16       0
Bank Sta=5108.4,5114.4
XS Rating Curve= 0 ,0
Exp/Cntr=0.3,0.1

Type RM Length L Ch R = 1 ,901     ,331,331,331
BEGIN DESCRIPTION:
DEVILS JUMP CREEK TRIBUTARY 6 1.0
END DESCRIPTION:
XS GIS Cut Line= 4
      3562624.59     10350475.62       3562529.3      10350331.2
      3562252.76      10350043.6       3561971.5     10350012.35
#Sta/Elev= 30
    4573  326.26  4585.2  326.47  4636.4  321.95  4642.4  319.89  4657.4  319.36
  4663.4  316.99  4699.5  312.42  4708.6  312.16  4735.7  307.95  4828.7  297.77
  4839.6  296.49  4842.4  295.99  4845.6  296.49    4864  297.08  4927.5  298.62
  5002.4  298.27    5069  299.22  5118.7  302.96  5147.9  303.23  5165.8  304.75
    5196  304.27  5204.5  305.33  5214.4  308.31  5246.3  318.74  5295.1  326.28
  5326.8  329.23  5346.9   333.2  5385.6  335.07  5390.7  333.42    5428  335.65
#Mann= 5 ,-1 , 0
    4573     .16       0  4828.7     .07       0    4864     .16       0
  5002.4     .05       0  5214.4     .16       0
Bank Sta=4839.6,4845.6
XS Rating Curve= 0 ,0
Exp/Cntr=0.3,0.1

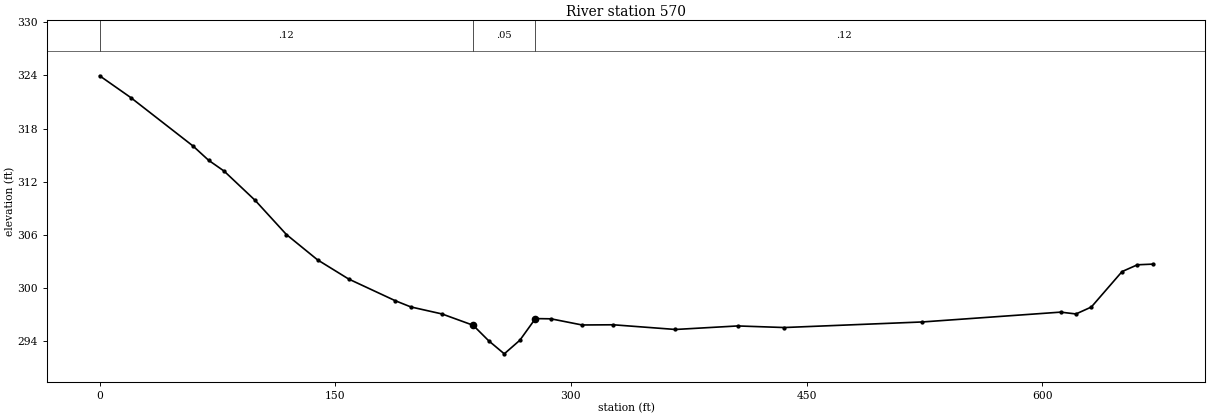
Type RM Length L Ch R = 1 ,570     ,0,0,0
XS GIS Cut Line= 3
     3562737.457    10350302.729     3562576.867    10349918.614
     3562338.151    10349875.211
#Sta/Elev= 30
       0323.964719.81472321.503659.44417316.032469.35153314.4242 79.2589313.1954
99.07362309.8802118.8883306.0365138.7031303.1762158.5178301.0092188.2399298.5552
198.1472297.8548 217.962297.0634237.7767 295.786247.6841294.0313257.5914292.5587
267.4988294.0933277.4061296.5399287.3135296.5138307.1282295.8184326.9429295.8408
366.5724295.3112406.2018295.7093435.7921  295.53523.7721296.1602611.7521297.2691
621.5276297.0633631.3032297.8466650.8543301.8489660.6299302.6162670.4054302.6918
#Mann= 3 , 0 , 0
       0     .12       0237.7767     .05       0277.4061     .12       0
Bank Sta=237.7767,277.4061
XS Rating Curve= 0 ,0
Exp/Cntr=0.3,0.1

Chan Stop Cuts=-1
Use User Specified Reach Order=0
Composite Channel Slope=5