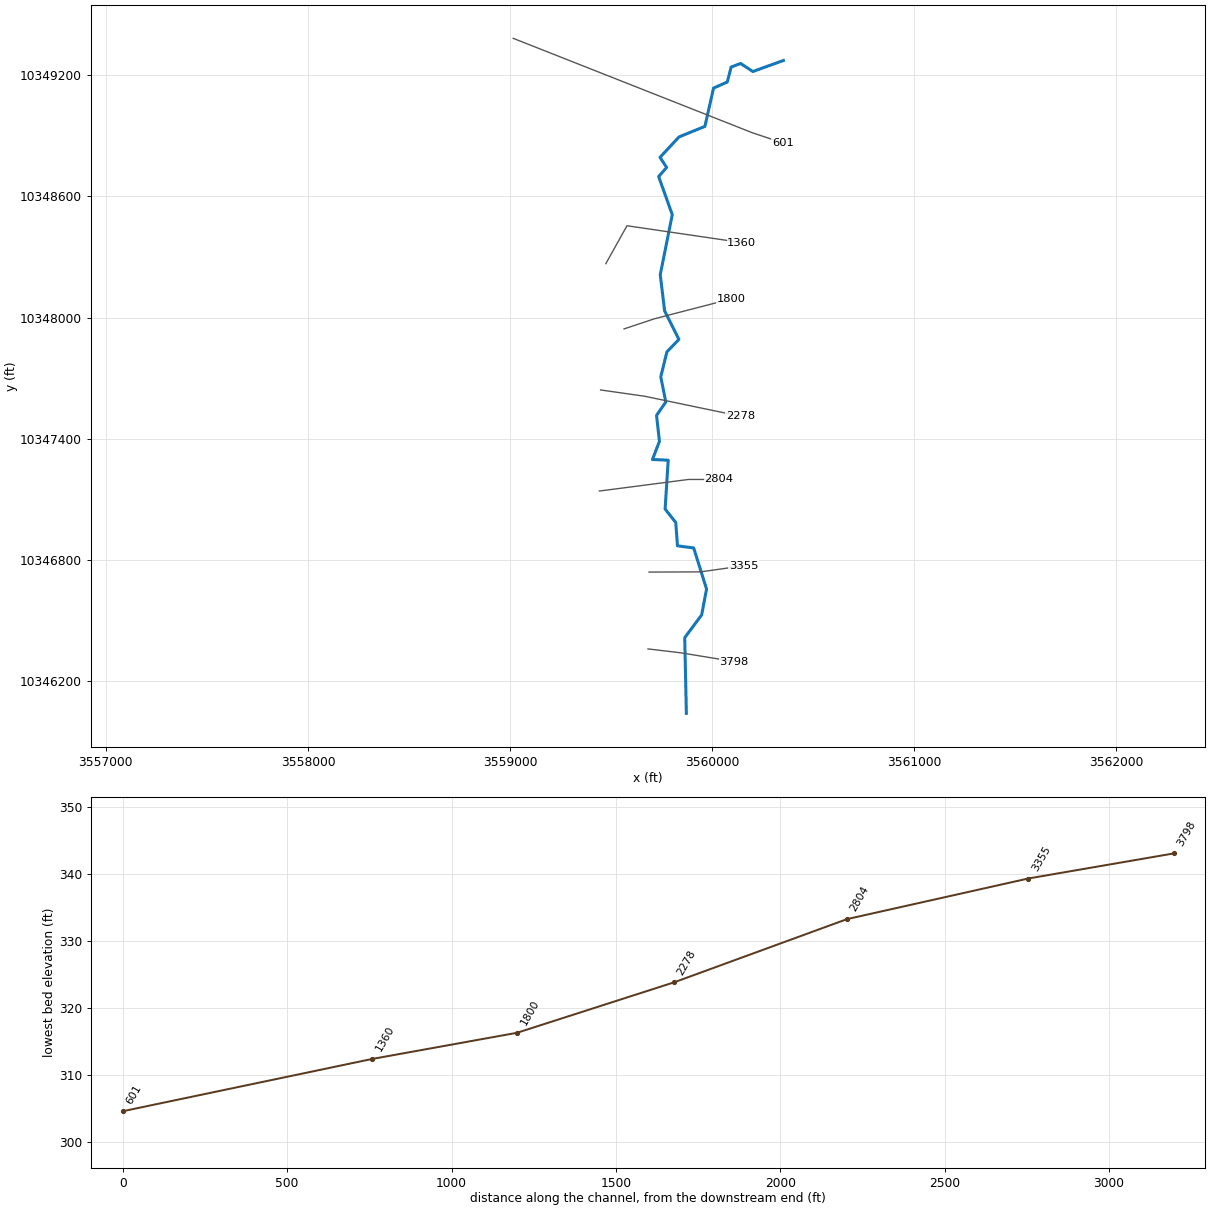
--- DEVILS JUMP CREEK TRIBUTARY 9.prj (project) ---

Proj Title=DEVILS JUMP CREEK TRIBUTARY 9 Base Level Engineering
Current Plan=p01
Default Exp/Contr=0.3,0.1
English Units
Geom File=g01
Flow File=f01
Plan File=p01
BEGIN DESCRIPTION:
DEVILS JUMP CREEK TRIBUTARY 9
END DESCRIPTION:

--- DEVILS JUMP CREEK TRIBUTARY 9.p01 (plan) ---

Plan Title=Multiple Run
Short Identifier=Multiple
Geom File=g01
Flow File=f01
Subcritical Flow
K Sum by GR= 0
Std Step Tol= 0.01
Critical Tol= 0.01
Num of Std Step Trials= 20
Max Error Tol= 0.3
Flow Tol Ratio= 0.001
Split Flow NTrial= 30
Split Flow Tol= 0.02
Split Flow Ratio= 0.02
Log Output Level= 0
Friction Slope Method= 1
Unsteady Friction Slope Method= 2
Unsteady Bridges Friction Slope Method= 1
Parabolic Critical Depth
Global Vel Dist=  1 , 1 , 1
Global Log Level= 0
CheckData=True
Encroach Param= -1, 0, 0, 0
BEGIN DESCRIPTION:
Multiple Run
END DESCRIPTION:

--- DEVILS JUMP CREEK TRIBUTARY 9.f01 (steady flow) ---

Flow Title=Multiple
Number of Profiles=7
Profile Names=10-year,25-year,50-year,1pct_min,100-year,1pct_plu,500-year
River Rch & RM= DEVILS JUMP CREE,Reach-1,3798
     217     278     325     281     380     513     517
River Rch & RM= DEVILS JUMP CREE,Reach-1,601
     591     810     993     894    1209    1635    1793
Boundary for River Rch & Prof#=DEVILS JUMP CREE,Reach-1,1
Up Type=0
Dn Type=3
Dn Slope=0.005
Boundary for River Rch & Prof#=DEVILS JUMP CREE,Reach-1,2
Up Type=0
Dn Type=3
Dn Slope=0.005
Boundary for River Rch & Prof#=DEVILS JUMP CREE,Reach-1,3
Up Type=0
Dn Type=3
Dn Slope=0.005
Boundary for River Rch & Prof#=DEVILS JUMP CREE,Reach-1,4
Up Type=0
Dn Type=3
Dn Slope=0.005
Boundary for River Rch & Prof#=DEVILS JUMP CREE,Reach-1,5
Up Type=0
Dn Type=3
Dn Slope=0.005
Boundary for River Rch & Prof#=DEVILS JUMP CREE,Reach-1,6
Up Type=0
Dn Type=3
Dn Slope=0.005
Boundary for River Rch & Prof#=DEVILS JUMP CREE,Reach-1,7
Up Type=0
Dn Type=3
Dn Slope=0.005

--- DEVILS JUMP CREEK TRIBUTARY 9.g01 (geometry) ---

Geom Title=Existing Conditions

River Reach=DEVILS JUMP CREE,Reach-1
Reach XY= 30
      3559872.23     10346041.63      3559864.17     10346415.95
      3559947.85     10346528.69      3559972.17     10346656.55
      3559908.43     10346860.18      3559828.29     10346870.46
      3559819.80     10346985.89      3559767.13     10347052.66
      3559782.48     10347294.24      3559704.35     10347297.71
      3559739.16     10347387.02      3559724.73     10347515.71
      3559770.36     10347582.05      3559745.71     10347706.83
      3559775.95     10347830.02      3559835.42     10347891.78
      3559764.69     10348032.74      3559743.05     10348212.15
      3559802.54     10348508.98      3559735.18     10348697.48
      3559774.57     10348742.31      3559742.00     10348792.63
      3559835.73     10348893.49      3559964.09     10348945.72
      3560006.63     10349134.99      3560074.53     10349165.07
      3560093.83     10349239.30      3560140.75     10349256.88
      3560200.97     10349217.06      3560352.11     10349271.64

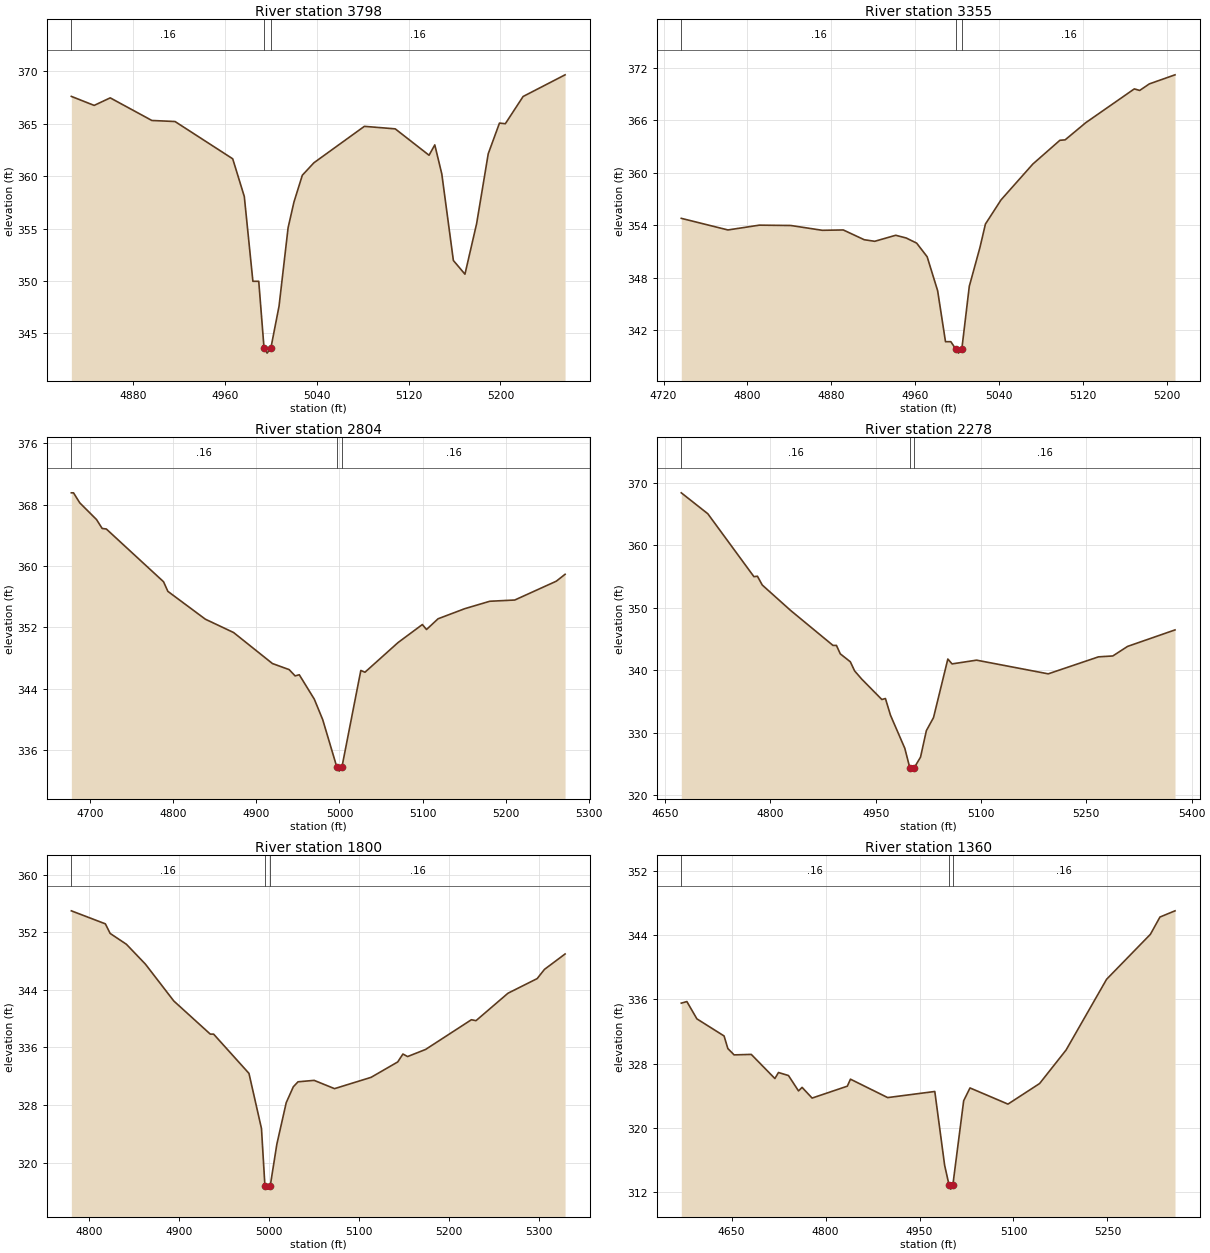
Type RM Length L Ch R = 1,3798,443,443,443
BEGIN DESCRIPTION:
DEVILS JUMP CREEK TRIBUTARY 9 6.0
END DESCRIPTION:
XS GIS Cut Line= 3
      3559682.36     10346360.49      3559842.11     10346341.64
      3560108.22     10346298.18
#Sta/Elev= 30
  4825.9  367.62  4845.8  366.76  4859.8  367.48  4896.1  365.32  4916.3  365.22
  4966.6  361.66  4976.7  358.06  4984.2  349.96  4989.3  349.96  4993.9  343.60
  4996.6  343.10  4999.9  343.60  5007.0  347.59  5014.9  355.08  5020.0  357.53
  5027.3  360.09  5037.4  361.28  5081.4  364.76  5108.3  364.52  5137.8  362.00
  5142.8  362.99  5148.9  360.22  5159.0  351.95  5169.1  350.64  5179.3  355.48
  5189.4  362.14  5199.2  365.07  5204.3  365.01  5219.8  367.61  5256.4  369.68
#Mann=3,-1,0
  4825.9    0.16       0  4993.9    0.07       0  4999.9    0.16       0
Bank Sta=4993.9,4999.9
Exp/Cntr=0.3,0.1

Type RM Length L Ch R = 1,3355,551,551,551
BEGIN DESCRIPTION:
DEVILS JUMP CREEK TRIBUTARY 9 5.0
END DESCRIPTION:
XS GIS Cut Line= 3
      3559687.56     10346740.70      3559942.11     10346741.64
      3560156.33     10346771.95
#Sta/Elev= 30
  4736.9  354.79  4781.4  353.46  4811.4  354.01  4841.4  353.97  4871.4  353.42
  4891.4  353.46  4911.4  352.34  4921.4  352.16  4941.4  352.85  4951.4  352.54
  4961.4  351.95  4971.4  350.39  4981.4  346.50  4988.9  340.66  4994.0  340.66
  4998.5  339.85  5001.3  339.35  5004.5  339.85  5011.6  347.01  5021.7  351.43
  5027.0  354.14  5041.9  356.91  5072.2  361.01  5098.0  363.73  5103.0  363.78
  5122.7  365.75  5169.0  369.62  5174.1  369.44  5183.3  370.19  5207.8  371.23
#Mann=3,-1,0
  4736.9    0.16       0  4998.5    0.07       0  5004.5    0.16       0
Bank Sta=4998.5,5004.5
Exp/Cntr=0.3,0.1

Type RM Length L Ch R = 1,2804,526,526,526
BEGIN DESCRIPTION:
DEVILS JUMP CREEK TRIBUTARY 9 4.0
END DESCRIPTION:
XS GIS Cut Line= 3
      3559442.06     10347141.64      3559882.73     10347198.93
      3560032.75     10347198.93
#Sta/Elev= 30
  4677.2  369.53  4679.8  369.53  4687.3  368.23  4707.5  366.05  4714.3  364.89
  4719.3  364.82  4788.2  357.95  4793.4  356.70  4838.6  353.07  4872.5  351.34
  4919.3  347.30  4939.4  346.51  4946.6  345.69  4951.6  345.84  4969.7  342.66
  4979.8  340.00  4996.9  333.79  4999.7  333.29  5002.9  333.79  5025.7  346.40
  5030.7  346.17  5070.5  350.03  5099.8  352.38  5104.8  351.73  5118.7  353.13
  5151.0  354.45  5181.0  355.41  5211.0  355.57  5261.0  358.02  5271.6  358.92
#Mann=3,-1,0
  4677.2    0.16       0  4996.9    0.07       0  5002.9    0.16       0
Bank Sta=4996.9,5002.9
Exp/Cntr=0.3,0.1

Type RM Length L Ch R = 1,2278,478,478,478
BEGIN DESCRIPTION:
DEVILS JUMP CREEK TRIBUTARY 9 3.0
END DESCRIPTION:
XS GIS Cut Line= 3
      3559447.95     10347641.74      3559666.70     10347610.49
      3560138.85     10347511.91
#Sta/Elev= 30
  4673.0  368.39  4710.8  365.04  4776.5  354.97  4781.5  355.04  4788.3  353.64
  4828.7  349.57  4889.1  343.97  4894.0  343.97  4899.5  342.62  4913.8  341.35
  4919.9  339.89  4930.1  338.57  4958.7  335.31  4963.8  335.47  4971.0  332.80
  4991.4  327.50  4998.6  324.35  5001.4  323.85  5004.6  324.35  5013.8  326.09
  5022.1  330.33  5032.3  332.42  5052.7  341.79  5058.7  341.01  5093.6  341.61
  5195.7  339.42  5267.3  342.14  5287.7  342.28  5308.7  343.81  5376.3  346.45
#Mann=3,-1,0
  4673.0    0.16       0  4998.6    0.07       0  5004.6    0.16       0
Bank Sta=4998.6,5004.6
Exp/Cntr=0.3,0.1

Type RM Length L Ch R = 1,1800,440,440,440
BEGIN DESCRIPTION:
DEVILS JUMP CREEK TRIBUTARY 9 2.0
END DESCRIPTION:
XS GIS Cut Line= 3
      3559564.03     10347943.74      3559713.98     10347993.73
      3560092.14     10348091.65
#Sta/Elev= 30
  4780.7  355.00  4818.5  353.19  4823.8  351.86  4841.9  350.35  4863.0  347.59
  4894.6  342.46  4935.1  337.86  4938.8  337.86  4978.1  332.40  4992.0  324.73
  4995.8  316.81  4998.6  316.31  5001.8  316.81  5009.1  322.57  5019.5  328.33
  5027.4  330.54  5032.6  331.23  5050.5  331.43  5073.2  330.28  5113.8  331.85
  5143.4  333.99  5149.2  335.09  5154.4  334.74  5174.4  335.73  5225.3  339.86
  5230.4  339.73  5265.9  343.54  5298.4  345.58  5306.5  346.86  5329.4  349.00
#Mann=3,-1,0
  4780.7    0.16       0  4995.8    0.07       0  5001.8    0.16       0
Bank Sta=4995.8,5001.8
Exp/Cntr=0.3,0.1

Type RM Length L Ch R = 1,1360,759,759,759
BEGIN DESCRIPTION:
DEVILS JUMP CREEK TRIBUTARY 9 1.0
END DESCRIPTION:
XS GIS Cut Line= 3
      3559473.98     10348266.73      3559578.56     10348454.14
      3560145.87     10348370.91
#Sta/Elev= 30
  4569.8  335.53  4578.7  335.73  4594.7  333.58  4638.1  331.45  4644.1  329.89
  4654.1  329.10  4681.5  329.16  4719.2  326.16  4724.9  326.91  4740.9  326.53
  4756.9  324.62  4762.6  325.06  4778.6  323.73  4834.8  325.21  4839.8  326.08
  4899.2  323.79  4974.4  324.55  4990.1  315.38  4997.2  312.91  5000.0  312.41
  5003.2  312.91  5020.5  323.40  5030.6  324.99  5091.2  322.98  5141.7  325.54
  5183.9  329.70  5248.6  338.50  5318.5  344.09  5333.8  346.24  5357.8  347.01
#Mann=3,-1,0
  4569.8    0.16       0  4997.2    0.07       0  5003.2    0.16       0
Bank Sta=4997.2,5003.2
Exp/Cntr=0.3,0.1

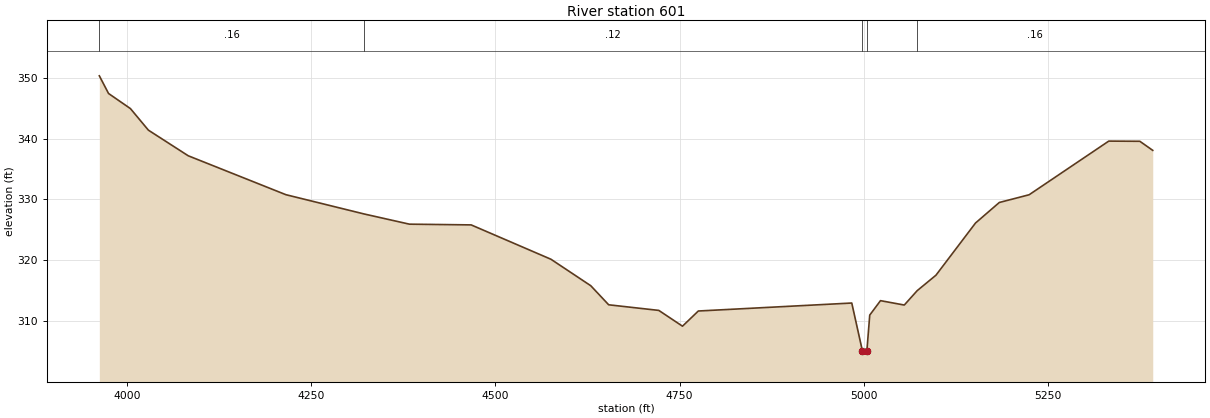
Type RM Length L Ch R = 1,601,0,0,0
BEGIN DESCRIPTION:
DEVILS JUMP CREEK TRIBUTARY 10 1.0
END DESCRIPTION:
XS GIS Cut Line= 3
      3559015.69     10349381.31      3560200.44     10348913.52
      3560348.75     10348864.08
#Sta/Elev= 30
  3962.3  350.30  3974.8  347.40  4004.5  344.92  4028.9  341.38  4083.0  337.17
  4215.6  330.78  4321.6  327.62  4383.3  325.94  4467.1  325.82  4575.4  320.18
  4629.5  315.83  4653.8  312.70  4721.8  311.78  4754.0  309.19  4775.5  311.68
  4983.8  312.99  4998.3  305.10  5001.1  304.60  5004.3  305.10  5008.2  311.01
  5022.8  313.38  5055.1  312.66  5072.6  315.02  5098.1  317.56  5151.8  326.13
  5184.1  329.50  5224.6  330.77  5332.7  339.58  5374.9  339.55  5392.4  338.06
#Mann=5,-1,0
  3962.3    0.16       0  4321.6    0.12       0  4998.3    0.07       0
  5004.3    0.12       0  5072.6    0.16       0
Bank Sta=4998.3,5004.3
Exp/Cntr=0.3,0.1

Chan Stop Cuts=-1