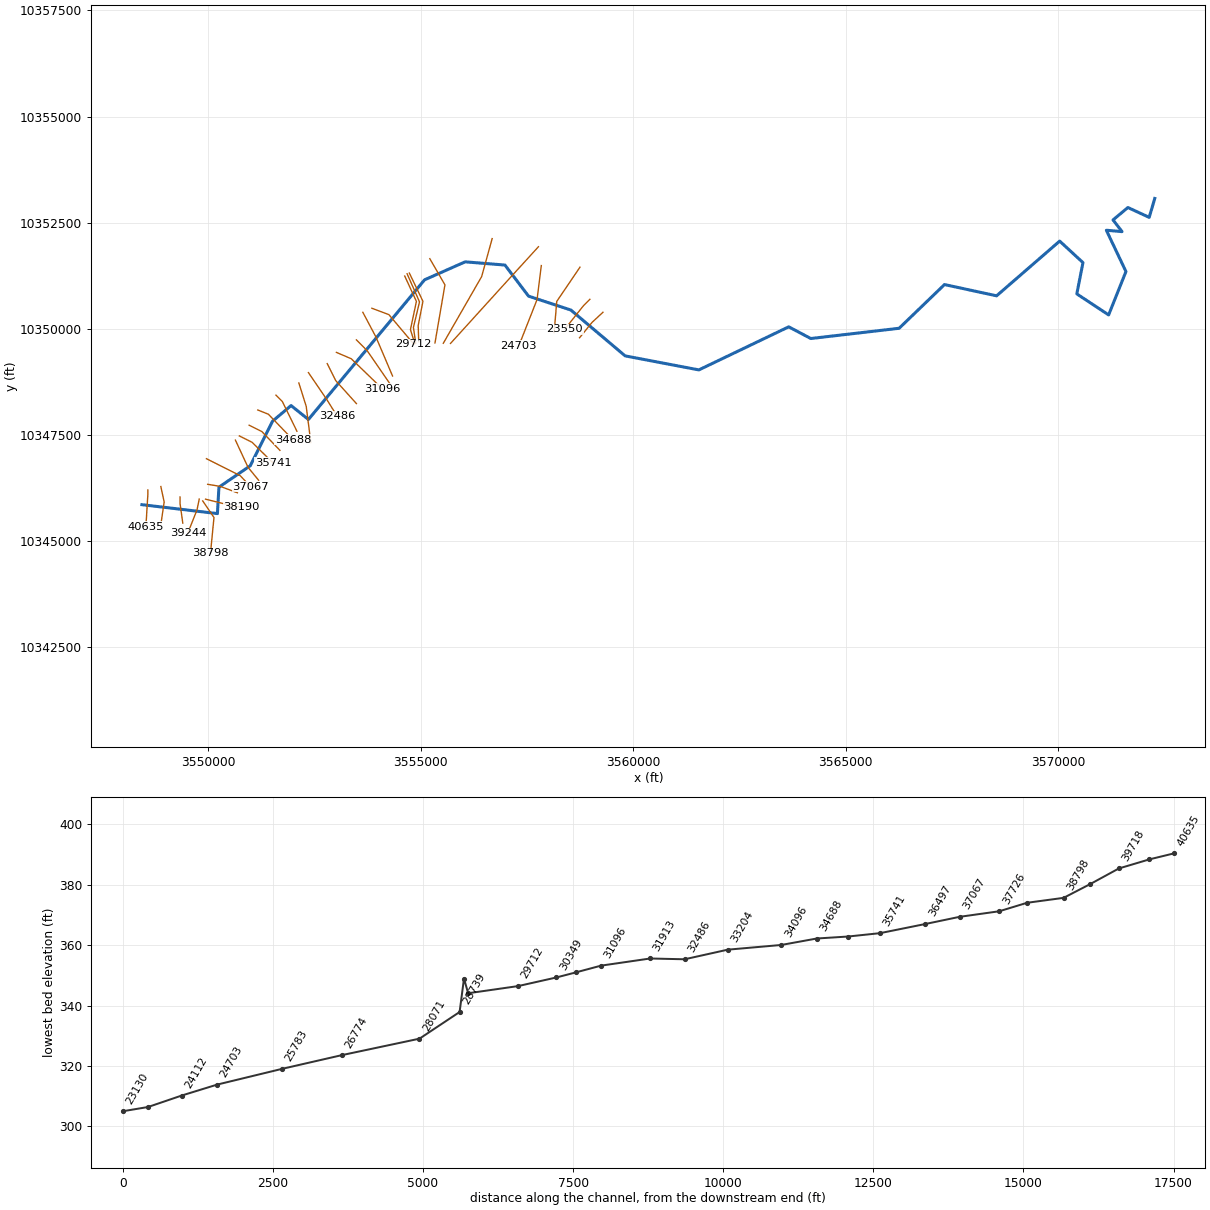
--- DEVILS JUMP CREEK.prj (project) ---

Proj Title=DEVILS JUMP CREEK Base Level Engineering
Current Plan=p01
Default Exp/Contr=0.3,0.1
English Units
Geom File=g01
Flow File=f01
Plan File=p01
Y Axis Title=Elevation
X Axis Title(PF)=Main Channel Distance
X Axis Title(XS)=Station
BEGIN DESCRIPTION:
DEVILS JUMP CREEK
END DESCRIPTION:
DSS Export Rating Curves= 0
DSS Export Rating Curve Sorted= 0
DSS Export Volume Flow Curves= 0
DXF OffsetX= 0
DXF OffsetY= 0
DXF ScaleX= 1
DXF ScaleY= 10

--- DEVILS JUMP CREEK.p01 (plan) ---

Plan Title=Multiple Run
Short Identifier=Multiple
Geom File=g01
Flow File=f01
Subcritical Flow
K Sum by GR= 0
Std Step Tol= 0.01
Critical Tol= 0.01
Num of Std Step Trials= 20
Max Error Tol= 0.3
Flow Tol Ratio= 0.001
Split Flow NTrial= 30
Split Flow Tol= 0.02
Split Flow Ratio= 0.02
Log Output Level= 0
Friction Slope Method= 1
Unsteady Friction Slope Method= 2
Unsteady Bridges Friction Slope Method= 1
Parabolic Critical Depth
Global Vel Dist=  1 , 1 , 1
Global Log Level= 0
CheckData=True
Encroach Param= -1, 0, 0, 0
BEGIN DESCRIPTION:
Multiple Run
END DESCRIPTION:

--- DEVILS JUMP CREEK.f01 (steady flow) ---

Flow Title=Multiple
Program Version=4.10
Number of Profiles= 7
Profile Names=10-year,25-year,50-year,1pct_min,100-year,1pct_plu,500-year
River Rch & RM=DEVILS JUMP CREE,Reach-1         ,40635
     679     937    1151    1038    1403    1898    2090
River Rch & RM=DEVILS JUMP CREE,Reach-1         ,36497
    1143    1610    2007    1831    2476    3348    3776
River Rch & RM=DEVILS JUMP CREE,Reach-1         ,26774
    1680    2405    3029    2785    3766    5093    5834
River Rch & RM=DEVILS JUMP CREE,Reach-1         ,24703
    1893    2722    3438    3169    4286    5796    6673
River Rch & RM=DEVILS JUMP CREE,Reach-1         ,21690
    2207    3197    4059    3759    5084    6876    7997
River Rch & RM=DEVILS JUMP CREE,Reach-1         ,20798
    2207    3197    4059    3759    5084    6876    7997
River Rch & RM=DEVILS JUMP CREE,Reach-1         ,18595
    2518    3660    4658    4321    5844    7903    9220
River Rch & RM=DEVILS JUMP CREE,Reach-1         ,17446
    2518    3660    4658    4321    5844    7903    9220
River Rch & RM=DEVILS JUMP CREE,Reach-1         ,14504
    2629    3825    4870    4521    6114    8268    9654
River Rch & RM=DEVILS JUMP CREE,Reach-1         ,13863
    2629    3825    4870    4521    6114    8268    9654
River Rch & RM=DEVILS JUMP CREE,Reach-1         ,10761
    2781    4049    5157    4787    6474    8755   10222
Boundary for River Rch & Prof#=DEVILS JUMP CREE,Reach-1         , 1
Up Type= 0
Dn Type= 3
Dn Slope=0.00285
Boundary for River Rch & Prof#=DEVILS JUMP CREE,Reach-1         , 2
Up Type= 0
Dn Type= 3
Dn Slope=0.00285
Boundary for River Rch & Prof#=DEVILS JUMP CREE,Reach-1         , 3
Up Type= 0
Dn Type= 3
Dn Slope=0.00285
Boundary for River Rch & Prof#=DEVILS JUMP CREE,Reach-1         , 4
Up Type= 0
Dn Type= 3
Dn Slope=0.00285
Boundary for River Rch & Prof#=DEVILS JUMP CREE,Reach-1         , 5
Up Type= 0
Dn Type= 3
Dn Slope=0.00285
Boundary for River Rch & Prof#=DEVILS JUMP CREE,Reach-1         , 6
Up Type= 0
Dn Type= 3
Dn Slope=0.00285
Boundary for River Rch & Prof#=DEVILS JUMP CREE,Reach-1         , 7
Up Type= 0
Dn Type= 3
Dn Slope=0.00285
DSS Import GetInterval= 0
DSS Import GetPeak= 0
DSS Import FillOption= 0

--- DEVILS JUMP CREEK.g01 (geometry) ---

Geom Title=Existing Conditions
Program Version=4.10

River Reach=DEVILS JUMP CREE,Reach-1
Reach XY= 30
       3548445.8     10345861.83      3550221.47     10345651.66
      3550257.54     10346274.11      3550993.16     10346776.58
       3551519.3     10347827.94      3551954.35     10348195.38
      3552362.85     10347867.74      3555095.39     10351155.96
      3556050.59     10351579.42      3556986.81     10351503.64
      3557541.29     10350772.14       3558538.6     10350443.95
      3559813.98     10349365.09       3561549.1     10349034.92
      3563663.35     10350049.03      3564182.03     10349773.83
      3566260.65     10350015.15      3567328.05     10351044.19
      3568553.74     10350779.43      3570037.82     10352067.73
      3570585.88     10351561.32      3570441.07     10350824.57
      3571189.86     10350329.74      3571596.95     10351351.13
      3571136.01     10352323.36      3571506.39     10352290.27
       3571293.1     10352566.08      3571643.32     10352858.43
      3572143.93     10352626.51      3572275.28     10353071.87

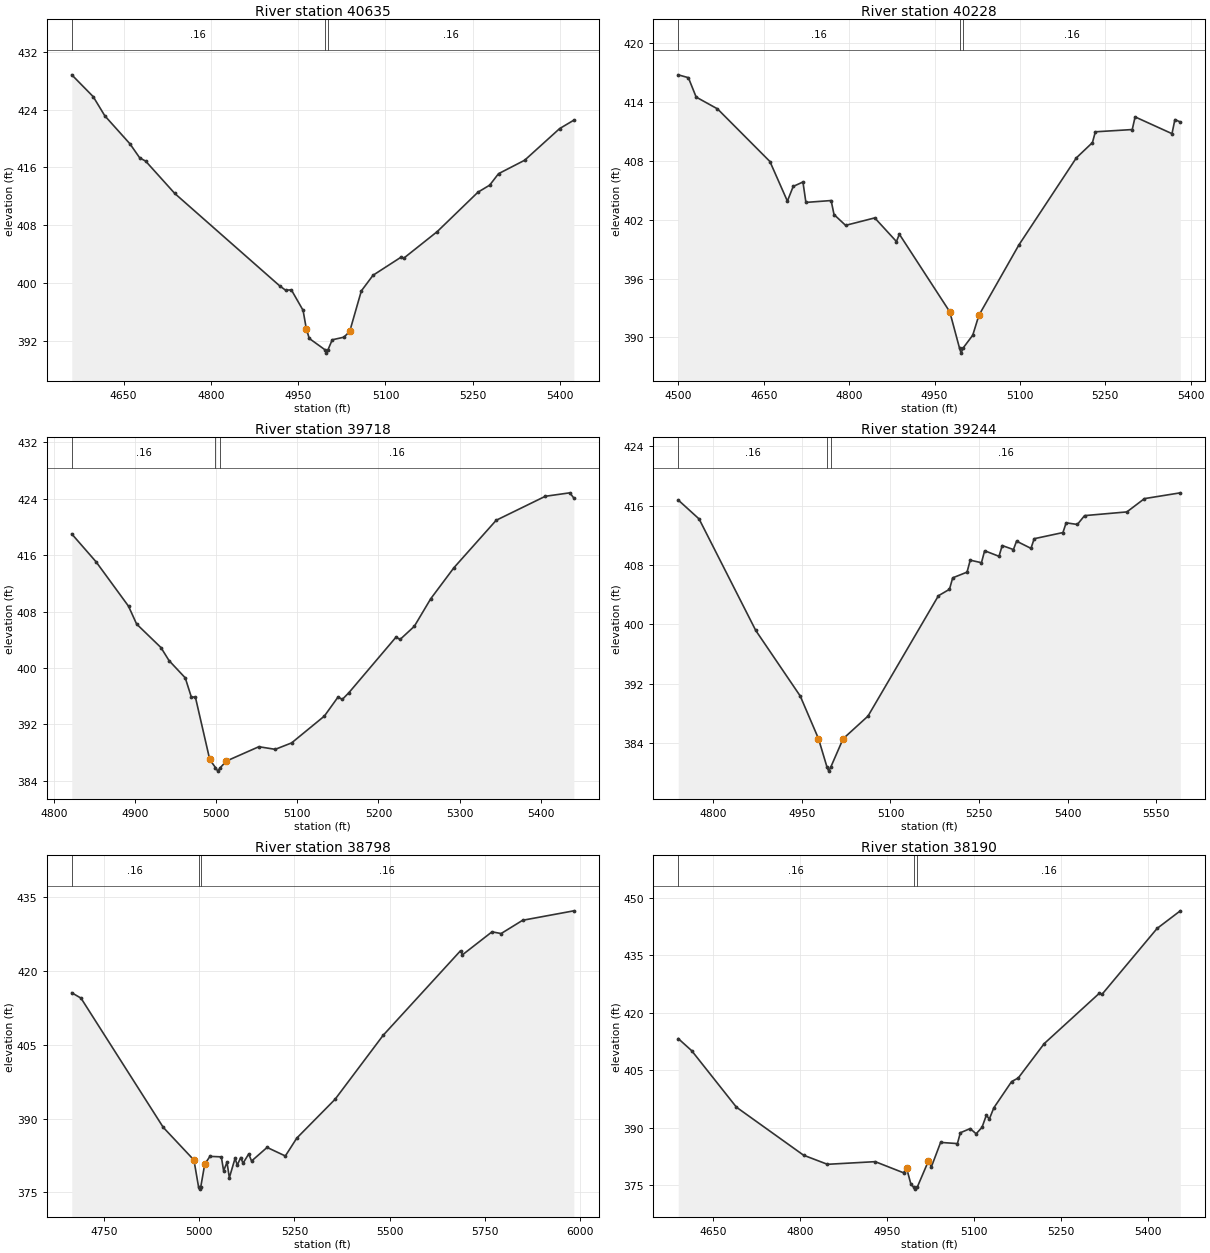
Type RM Length L Ch R = 1 ,40635   ,407,407,407
BEGIN DESCRIPTION:
DEVILS JUMP CREEK 54.0
END DESCRIPTION:
XS GIS Cut Line= 3
      3548585.51     10346208.46      3548585.51     10346108.48
      3548539.27     10345347.26
#Sta/Elev= 30
    4561  428.79  4597.8  425.78  4617.8  423.13    4661  419.26  4677.8  417.32
  4687.9  416.88    4738  412.41  4918.3  399.65  4928.3  399.06  4938.3   399.1
  4958.4  396.28  4963.9  393.76    4969   392.4  4995.4  390.87  4998.2  390.37
  5001.4  390.87  5008.5  392.21  5028.5  392.57  5038.5  393.36  5058.5  398.96
  5078.6  401.12  5126.6  403.61  5131.6  403.49  5188.8  407.14  5258.9  412.59
    5279  413.56  5294.2  415.14  5339.1     417  5399.2  421.37  5423.6  422.53
#Mann= 3 ,-1 , 0
    4561     .16       0  4995.4     .07       0  5001.4     .16       0
Bank Sta=4963.9,5038.5
XS Rating Curve= 0 ,0
Exp/Cntr=0.3,0.1

Type RM Length L Ch R = 1 ,40228   ,510,510,510
BEGIN DESCRIPTION:
DEVILS JUMP CREEK 53.0
END DESCRIPTION:
XS GIS Cut Line= 3
      3548890.83     10346289.06      3548968.96     10345924.47
      3548895.18     10345421.01
#Sta/Elev= 30
  4499.9  416.78  4517.7  416.49  4531.4  414.51  4568.8  413.31  4660.9  407.94
  4691.6   403.9  4701.8   405.4  4718.9  405.85  4724.1  403.77  4768.4  403.96
  4773.5  402.53  4793.8  401.43    4845  402.19  4883.1  399.78  4888.2  400.53
  4976.7  392.62  4993.9   388.9  4996.7   388.4  4999.9   388.9  5017.1  390.23
  5027.9  392.26    5098  399.42    5199  408.31  5227.3  409.87  5232.4  410.97
  5297.2   411.2  5302.2  412.49    5367  410.78  5372.1  412.22  5381.6  411.97
#Mann= 3 ,-1 , 0
  4499.9     .16       0  4993.9     .07       0  4999.9     .16       0
Bank Sta=4976.7,5027.9
XS Rating Curve= 0 ,0
Exp/Cntr=0.3,0.1

Type RM Length L Ch R = 1 ,39718   ,474,474,474
BEGIN DESCRIPTION:
DEVILS JUMP CREEK 52.0
END DESCRIPTION:
XS GIS Cut Line= 3
      3549342.11     10346041.66      3549342.11     10345891.64
      3549407.12     10345426.79
#Sta/Elev= 30
  4821.6     419  4851.6  415.05  4891.6  408.76  4901.6  406.23  4931.6   402.9
  4941.6  401.05  4961.6   398.6  4969.1  395.88  4974.1  395.88  4991.8  387.03
  4998.9  385.88  5001.7  385.38  5004.9  385.88  5012.4  386.81  5052.4  388.84
  5072.6  388.47  5092.8  389.38  5133.2  393.18  5150.2   395.9  5155.3  395.54
  5163.5   396.5  5221.6  404.37  5226.7  404.05  5244.2  405.91  5264.4  409.81
  5293.1  414.22  5345.2  420.94  5405.8  424.34    5436  424.83    5441  424.09
#Mann= 3 ,-1 , 0
  4821.6     .16       0  4998.9     .07       0  5004.9     .16       0
Bank Sta=4991.8,5012.4
XS Rating Curve= 0 ,0
Exp/Cntr=0.3,0.1

Type RM Length L Ch R = 1 ,39244   ,446,446,446
BEGIN DESCRIPTION:
DEVILS JUMP CREEK 51.0
END DESCRIPTION:
XS GIS Cut Line= 3
      3549793.61     10345993.92      3549742.11     10345741.64
      3549524.51     10345190.96
#Sta/Elev= 30
  4740.9  416.75  4776.2   414.2  4872.1  399.18  4947.3  390.36  4978.2  384.62
  4992.8  380.74  4995.6  380.24  4998.8  380.74  5019.9   384.6    5062  387.65
  5181.2  403.86  5199.9  404.73  5205.3  406.27  5229.6  407.04    5235  408.65
    5254  408.31  5259.4  409.92  5283.7  409.17  5289.1  410.62  5308.1  410.08
  5313.4  411.21  5337.8  410.24  5343.2  411.54  5391.9  412.37  5397.3  413.68
  5416.3  413.46  5428.5  414.65  5500.1  415.15  5529.8  416.94  5590.5  417.72
#Mann= 3 ,-1 , 0
  4740.9     .16       0  4992.8     .07       0  4998.8     .16       0
Bank Sta=4978.2,5019.9
XS Rating Curve= 0 ,0
Exp/Cntr=0.3,0.1

Type RM Length L Ch R = 1 ,38798   ,608,608,608
BEGIN DESCRIPTION:
DEVILS JUMP CREEK 50.0
END DESCRIPTION:
XS GIS Cut Line= 3
      3549876.08     10345950.51      3550140.83     10345559.89
      3550058.37      10344717.9
#Sta/Elev= 30
  4665.5  415.57  4689.7  414.48  4905.7   388.2  4986.2  381.56  4998.2  376.15
  5000.9  375.65  5004.2  376.15  5014.5  380.71  5028.2  382.31  5058.1  382.21
  5064.1  379.37    5073  381.12  5079.1  377.95    5094  381.88  5100.1  380.56
    5109  382.08    5115  380.92    5130   382.8  5137.4  381.36  5178.2  384.13
  5226.1  382.39  5256.2  386.03  5356.7  393.92  5482.8  406.92  5685.9  424.11
  5690.9  423.28  5768.6  427.96  5792.5  427.61    5849  430.31  5983.4  432.23
#Mann= 3 ,-1 , 0
  4665.5     .16       0  4998.2     .07       0  5004.2     .16       0
Bank Sta=4986.2,5014.5
XS Rating Curve= 0 ,0
Exp/Cntr=0.3,0.1

Type RM Length L Ch R = 1 ,38190   ,464,464,464
BEGIN DESCRIPTION:
DEVILS JUMP CREEK 49.0
END DESCRIPTION:
XS GIS Cut Line= 3
      3549942.09     10345991.65      3550342.11     10345891.64
      3550787.37     10345798.64
#Sta/Elev= 30
  4589.3  413.26  4612.5  410.11  4689.8  395.38  4805.8  382.86    4847  380.49
  4929.5  381.18  4978.4  378.28  4983.6  379.55  4991.3  375.24  4996.1  374.52
  4998.8  374.02  5002.1  374.52  5021.5  381.37  5026.6  379.85  5042.5   386.2
  5071.5  385.89  5076.6  388.72  5093.6   389.8  5103.8  388.44    5114  390.13
  5121.5  393.29  5126.6  392.29  5134.4  395.21  5165.1  402.05  5176.6  402.99
  5221.5  411.96  5316.4  425.04  5321.5  424.84  5416.4  441.97  5456.5  446.56
#Mann= 3 ,-1 , 0
  4589.3     .16       0  4996.1     .07       0  5002.1     .16       0
Bank Sta=4983.6,5021.5
XS Rating Curve= 0 ,0
Exp/Cntr=0.3,0.1

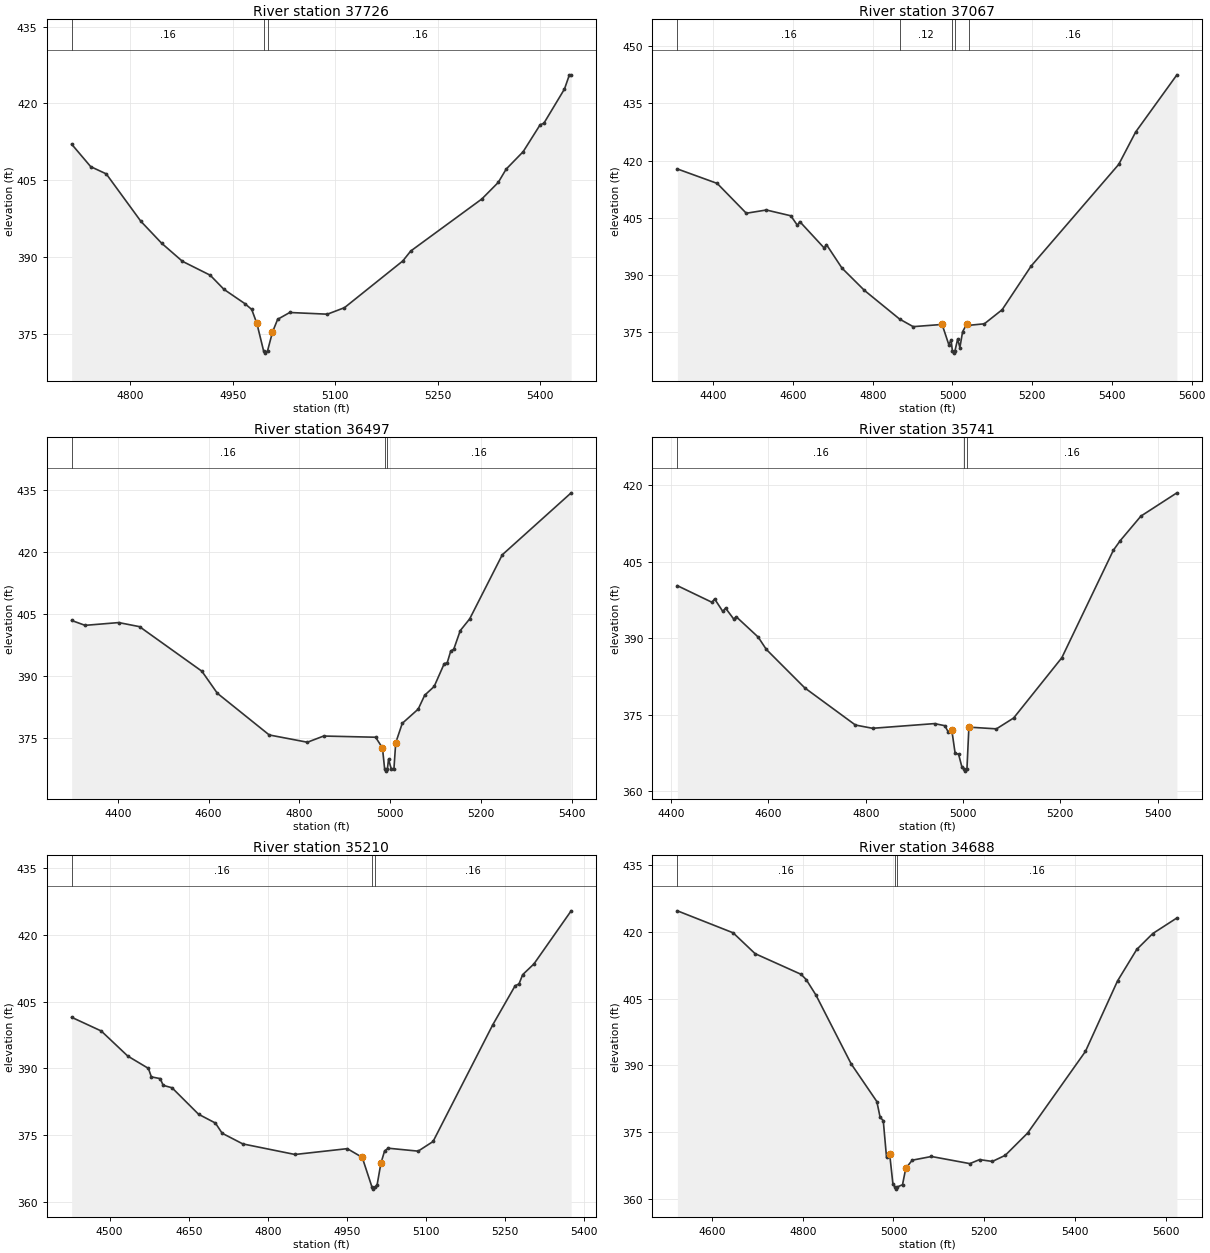
Type RM Length L Ch R = 1 ,37726   ,659,659,659
BEGIN DESCRIPTION:
DEVILS JUMP CREEK 48.0
END DESCRIPTION:
XS GIS Cut Line= 3
      3549992.11     10346341.64      3550292.11     10346291.64
      3550692.07     10346141.65
#Sta/Elev= 30
  4713.9  412.04  4741.8  407.65  4764.6  406.23  4815.3  396.96  4845.7  392.68
  4876.1  389.15  4916.7  386.44  4936.9  383.67  4967.3   380.9  4977.5  379.75
  4985.1     377  4994.8  371.71  4997.5  371.21  5000.8  371.71  5007.9  375.31
  5015.5  377.82  5033.2  379.15  5088.3  378.82  5113.3  380.09  5198.7  389.22
  5210.3  391.16  5314.4  401.33  5338.4  404.56    5350  407.16  5374.9  410.57
  5399.8  415.84  5405.2  416.12  5435.4  422.82  5442.6  425.59  5445.2  425.59
#Mann= 3 ,-1 , 0
  4713.9     .16       0  4994.8     .07       0  5000.8     .16       0
Bank Sta=4985.1,5007.9
XS Rating Curve= 0 ,0
Exp/Cntr=0.3,0.1

Type RM Length L Ch R = 1 ,37067   ,570,570,570
BEGIN DESCRIPTION:
DEVILS JUMP CREEK 47.0
END DESCRIPTION:
XS GIS Cut Line= 3
      3549962.85     10346944.45      3550757.15     10346545.13
      3551008.02     10346281.29
#Sta/Elev= 30
    4310  417.78  4409.9  413.98  4482.9  406.14  4533.2  406.99  4594.6  405.47
  4611.3  402.93  4616.9  403.96  4678.3     397  4683.9  397.91  4722.9  391.72
  4779.2  385.86  4867.5  378.32  4901.5  376.33  4974.1  376.91  4990.8  371.63
  4996.4  372.76  5000.1  369.87  5002.9  369.37  5006.1  369.87  5013.1  373.08
  5018.7  370.83  5025.5     375  5035.5  376.93  5040.3  376.67  5080.1  377.08
  5124.7  380.78  5197.3  392.24  5417.2  418.99  5459.6  427.49  5563.1  442.52
#Mann= 5 ,-1 , 0
    4310     .16       0  4867.5     .12       0  5000.1     .07       0
  5006.1     .12       0  5040.3     .16       0
Bank Sta=4974.1,5035.5
XS Rating Curve= 0 ,0
Exp/Cntr=0.3,0.1

Type RM Length L Ch R = 1 ,36497   ,756,756,756
BEGIN DESCRIPTION:
DEVILS JUMP CREEK 46.0
END DESCRIPTION:
XS GIS Cut Line= 3
      3550644.32     10347382.78      3550942.11     10346741.64
      3551191.17     10346436.64
#Sta/Elev= 30
  4298.2  403.45  4327.8  402.27    4402  402.94  4447.8  401.95  4585.2  391.17
  4619.2  385.84  4733.6  375.75  4817.7  373.99  4853.5  375.49    4968   375.2
  4983.1   372.6  4987.9   367.5  4990.7     367  4993.9   367.5  4996.4  369.84
  5002.4   367.6  5008.4   367.6  5012.3  373.85  5026.7  378.56  5061.8     382
  5076.2  385.37    5097  387.48  5119.3  393.03  5125.7   393.2  5133.6  396.08
  5140.1  396.46  5154.5     401  5175.3  403.84  5247.1  419.34  5398.9  434.33
#Mann= 3 ,-1 , 0
  4298.2     .16       0  4987.9     .07       0  4993.9     .16       0
Bank Sta=4983.1,5012.3
XS Rating Curve= 0 ,0
Exp/Cntr=0.3,0.1

Type RM Length L Ch R = 1 ,35741   ,531,531,531
BEGIN DESCRIPTION:
DEVILS JUMP CREEK 45.0
END DESCRIPTION:
XS GIS Cut Line= 3
      3550737.79     10347480.52      3551037.77     10347330.53
      3551529.75     10346844.59
#Sta/Elev= 30
  4412.8  400.29  4483.8  397.04  4489.4  397.69  4506.2  395.24  4511.8   395.9
  4528.6  393.76  4534.1  394.18  4578.9  390.22  4595.6  387.81  4674.8  380.26
  4778.8  372.99  4814.1  372.35  4941.4  373.27  4962.6  372.86  4969.7  371.62
  4976.8  372.09  4983.8  367.44  4990.9  367.27  4997.9   364.7  5002.1  364.46
  5004.8  363.96  5008.1  364.46  5012.1  372.58  5068.7  372.24  5104.1  374.37
  5203.1  386.17  5309.1  407.24  5323.2  409.11  5365.7  413.92  5439.7  418.48
#Mann= 3 ,-1 , 0
  4412.8     .16       0  5002.1     .07       0  5008.1     .16       0
Bank Sta=4976.8,5012.1
XS Rating Curve= 0 ,0
Exp/Cntr=0.3,0.1

Type RM Length L Ch R = 1 ,35210   ,522,522,522
BEGIN DESCRIPTION:
DEVILS JUMP CREEK 44.0
END DESCRIPTION:
XS GIS Cut Line= 3
      3550968.33     10347732.44      3551268.32     10347582.44
      3551692.13     10347141.62
#Sta/Elev= 30
    4428  401.49  4484.1  398.41  4534.4  392.77  4573.5     390  4579.1  388.09
  4595.9   387.7  4601.5  386.19  4618.3  385.64  4668.6  379.69  4700.5  377.71
  4713.3  375.42  4752.4  373.02  4851.4  370.64  4950.5  371.95  4978.8  369.99
  4997.2  363.35  4999.9  362.85  5003.2  363.35  5007.1  363.84  5014.2  368.66
  5021.3  371.46  5028.2  372.05  5084.8  371.39  5113.1  373.56  5226.3  399.81
  5268.7  408.59    5276  408.98  5282.9  411.07  5304.3  413.49  5374.9  425.43
#Mann= 3 ,-1 , 0
    4428     .16       0  4997.2     .07       0  5003.2     .16       0
Bank Sta=4978.8,5014.2
XS Rating Curve= 0 ,0
Exp/Cntr=0.3,0.1

Type RM Length L Ch R = 1 ,34688   ,592,592,592
BEGIN DESCRIPTION:
DEVILS JUMP CREEK 42.0
END DESCRIPTION:
XS GIS Cut Line= 3
      3551170.97     10348091.45      3551420.92     10347991.47
      3551997.78     10347392.21
#Sta/Elev= 30
  4523.7   424.7  4646.6  419.76    4695  415.08  4796.3  410.44  4807.7  409.25
    4829   405.8  4906.7  390.33  4963.3  381.87  4970.5  378.36  4977.5  377.56
  4984.7  369.31  4991.6  370.07  4998.8  363.31  5002.8  362.69  5005.5  362.19
  5008.8  362.69  5019.9  363.18  5027.1  366.86  5041.3  368.69  5083.7  369.52
  5168.3  367.92  5189.7  368.82    5218  368.41  5246.3  369.78  5295.7  374.79
    5423  393.11  5493.8  408.95  5536.2  416.03  5571.5   419.6  5624.7   423.1
#Mann= 3 ,-1 , 0
  4523.7     .16       0  5002.8     .07       0  5008.8     .16       0
Bank Sta=4991.6,5027.1
XS Rating Curve= 0 ,0
Exp/Cntr=0.3,0.1

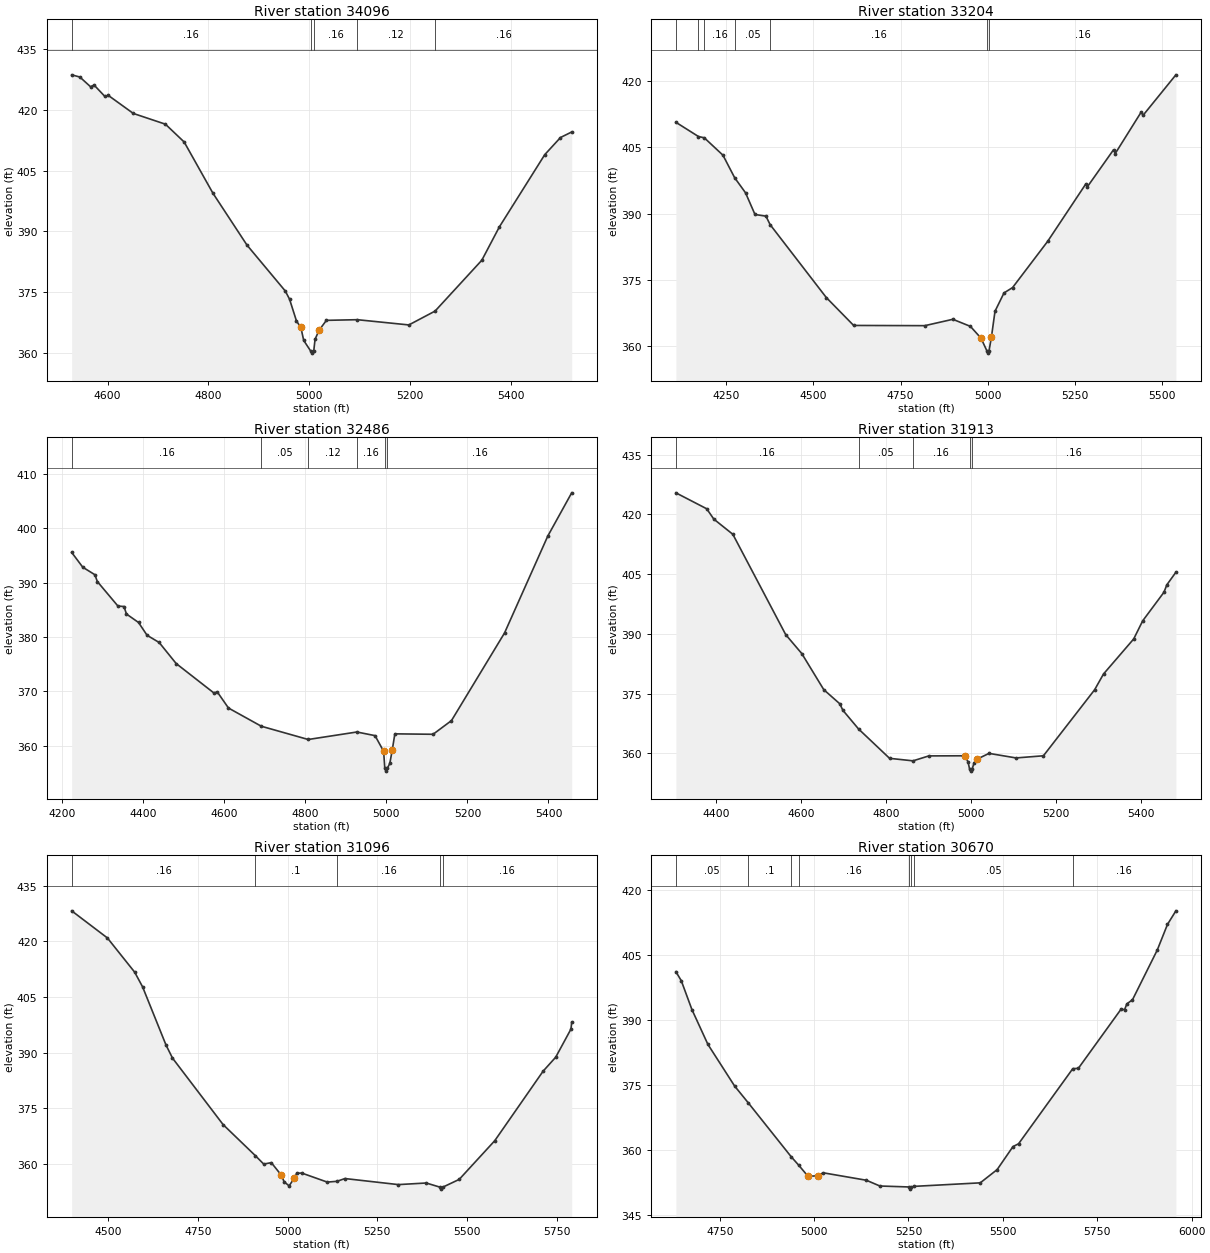
Type RM Length L Ch R = 1 ,34096   ,892,892,892
BEGIN DESCRIPTION:
DEVILS JUMP CREEK 41.0
END DESCRIPTION:
XS GIS Cut Line= 3
      3551599.04     10348441.48      3551749.05     10348291.47
      3552092.09     10347591.67
#Sta/Elev= 30
  4528.9  428.56  4545.1  428.02  4566.3  425.63  4573.4  426.04  4594.6  423.26
  4601.7  423.48  4651.2  419.05  4714.8  416.41    4752  412.02    4809  399.42
  4876.5  386.65  4952.5  375.34  4960.9  373.34  4974.7  367.95  4983.4  366.36
    4989  363.18  5002.9  360.55  5005.7  360.05  5008.9  360.55  5011.5  363.44
  5019.3  365.65    5034  368.12  5095.3  368.28  5197.5  366.99  5249.5   370.4
  5342.2  382.92    5377  391.13    5467  408.91  5498.2  413.13  5520.4  414.49
#Mann= 5 ,-1 , 0
  4528.9     .16       0  5002.9     .07       0  5008.9     .16       0
  5095.3     .12       0  5249.5     .16       0
Bank Sta=4983.4,5019.3
XS Rating Curve= 0 ,0
Exp/Cntr=0.3,0.1

Type RM Length L Ch R = 1 ,33204   ,718,718,718
BEGIN DESCRIPTION:
DEVILS JUMP CREEK 40.0
END DESCRIPTION:
XS GIS Cut Line= 3
      3552137.35     10348728.33      3552310.97     10348177.08
      3552419.46     10347326.52
#Sta/Elev= 30
    4105  410.69  4169.8  407.47  4186.6  407.18  4240.2  403.24  4273.8  398.14
  4304.9  394.75  4332.1  389.84  4363.6  389.46  4375.5  387.55  4536.8  371.06
  4615.3  364.75  4819.5   364.7  4900.1  366.14  4950.5  364.54  4980.8  361.89
  4997.9  358.99  5000.7  358.49  5003.9  358.99    5011  362.22  5021.1  367.96
  5046.9   372.1  5071.5  373.31  5172.3  383.77  5281.4   396.7  5286.5  396.13
  5361.3  404.47  5366.3  403.63  5441.1  413.04  5446.1  412.26  5540.4  421.42
#Mann= 7 ,-1 , 0
    4105     .16       0  4169.8     .05       0  4186.6     .16       0
  4273.8     .05       0  4375.5     .16       0  4997.9     .07       0
  5003.9     .16       0
Bank Sta=4980.8,5011
XS Rating Curve= 0 ,0
Exp/Cntr=0.3,0.1

Type RM Length L Ch R = 1 ,32486   ,573,573,573
BEGIN DESCRIPTION:
DEVILS JUMP CREEK 39.0
END DESCRIPTION:
XS GIS Cut Line= 3
      3552363.05     10348971.36      3552792.11     10348341.64
      3553042.11     10347941.63
#Sta/Elev= 30
  4223.6  395.56    4251  392.83  4280.9  391.45  4286.9   390.2  4337.8  385.68
  4352.7   385.6  4358.8  384.22  4388.6  382.66  4409.6  380.31  4439.5  378.98
  4481.4  375.11  4574.2  369.71  4583.1  369.86  4610.5  366.92  4691.5  363.57
  4807.2  361.13  4927.3  362.51  4972.1  361.84  4993.3  358.96  4996.2  355.81
  4998.9  355.31  5002.2  355.81  5008.6  356.74  5014.5  359.17    5021  362.17
  5115.3  362.09  5160.7  364.61  5291.6  380.73  5398.3  398.56  5457.3  406.52
#Mann= 6 ,-1 , 0
  4223.6     .16       0  4691.5     .05       0  4807.2     .12       0
  4927.3     .16       0  4996.2     .07       0  5002.2     .16       0
Bank Sta=4993.3,5014.5
XS Rating Curve= 0 ,0
Exp/Cntr=0.3,0.1

Type RM Length L Ch R = 1 ,31913   ,817,817,817
BEGIN DESCRIPTION:
DEVILS JUMP CREEK 38.0
END DESCRIPTION:
XS GIS Cut Line= 3
      3552805.28     10349182.47       3553005.3     10348782.44
      3553492.12     10348241.63
#Sta/Elev= 30
  4306.2  425.39  4378.6  421.39  4395.4  418.79  4440.1  414.98  4564.3  389.81
  4602.2  385.04  4653.7  376.01  4691.6  372.44  4698.4  370.86  4735.4  366.15
  4808.3  358.78  4863.4  358.15  4900.7  359.39  4985.2  359.42  4992.6  357.91
  4996.4  356.07  4999.1  355.57  5002.4  356.07  5006.8  357.66  5013.6  358.56
    5042  360.02  5105.5  358.88  5169.8  359.42  5290.1  375.98    5311  379.94
    5382  388.74    5403  393.27  5453.1  400.46  5459.8  402.31  5481.1  405.47
#Mann= 5 ,-1 , 0
  4306.2     .16       0  4735.4     .05       0  4863.4     .16       0
  4996.4     .07       0  5002.4     .16       0
Bank Sta=4985.2,5013.6
XS Rating Curve= 0 ,0
Exp/Cntr=0.3,0.1

Type RM Length L Ch R = 1 ,31096   ,426,426,426
BEGIN DESCRIPTION:
DEVILS JUMP CREEK 36.0
END DESCRIPTION:
XS GIS Cut Line= 3
      3553020.54     10349447.91      3553370.58     10349297.89
       3554098.1     10348594.77
#Sta/Elev= 30
  4398.6  428.22  4498.1  420.91  4574.2  411.67  4596.1  407.73  4661.4  392.04
  4679.4  388.53  4820.4   370.6  4910.4  362.21  4933.5  359.96  4954.6  360.35
  4982.9  356.93  4990.1  355.23  5004.1  354.08  5018.2   356.1  5025.4  357.48
  5039.5  357.54  5110.3  355.11  5137.4  355.31  5159.7  356.06  5308.4  354.43
  5386.1  354.86  5425.5  353.71  5428.2  353.21  5431.5  353.71  5477.9  355.83
  5576.9  366.26  5711.5  384.99  5746.7  388.77  5789.2  396.36  5791.2  398.18
#Mann= 5 ,-1 , 0
  4398.6     .16       0  4910.4      .1       0  5137.4     .16       0
  5425.5     .07       0  5431.5     .16       0
Bank Sta=4982.9,5018.2
XS Rating Curve= 0 ,0
Exp/Cntr=0.3,0.1

Type RM Length L Ch R = 1 ,30670   ,321,321,321
BEGIN DESCRIPTION:
DEVILS JUMP CREEK 35.0
END DESCRIPTION:
XS GIS Cut Line= 3
      3553492.09     10349741.66      3553742.11     10349491.64
       3554292.1     10348691.65
#Sta/Elev= 30
  4633.9  401.08  4648.1  399.02  4676.4  392.34  4718.8   384.3  4789.5  374.71
  4825.7  370.83  4939.2  358.42  4959.3  356.45  4983.9   353.9  5009.8  354.01
  5023.9  354.71  5138.3  352.99  5174.2  351.66  5251.5  351.44  5254.2  350.94
  5257.5  351.44  5265.7  351.58  5440.1  352.39  5484.8  355.44  5526.7  360.74
  5541.6   361.4  5685.1  378.71  5699.9  378.79  5813.5  392.49  5822.3   392.3
  5828.4  393.66  5843.3   394.6  5908.9  406.06    5936  411.98  5958.3  415.11
#Mann= 8 ,-1 , 0
  4633.9     .05       0  4825.7      .1       0  4939.2     .05       0
  4959.3     .16       0  5251.5     .07       0  5257.5     .16       0
  5265.7     .05       0  5685.1     .16       0
Bank Sta=4983.9,5009.8
XS Rating Curve= 0 ,0
Exp/Cntr=0.3,0.1

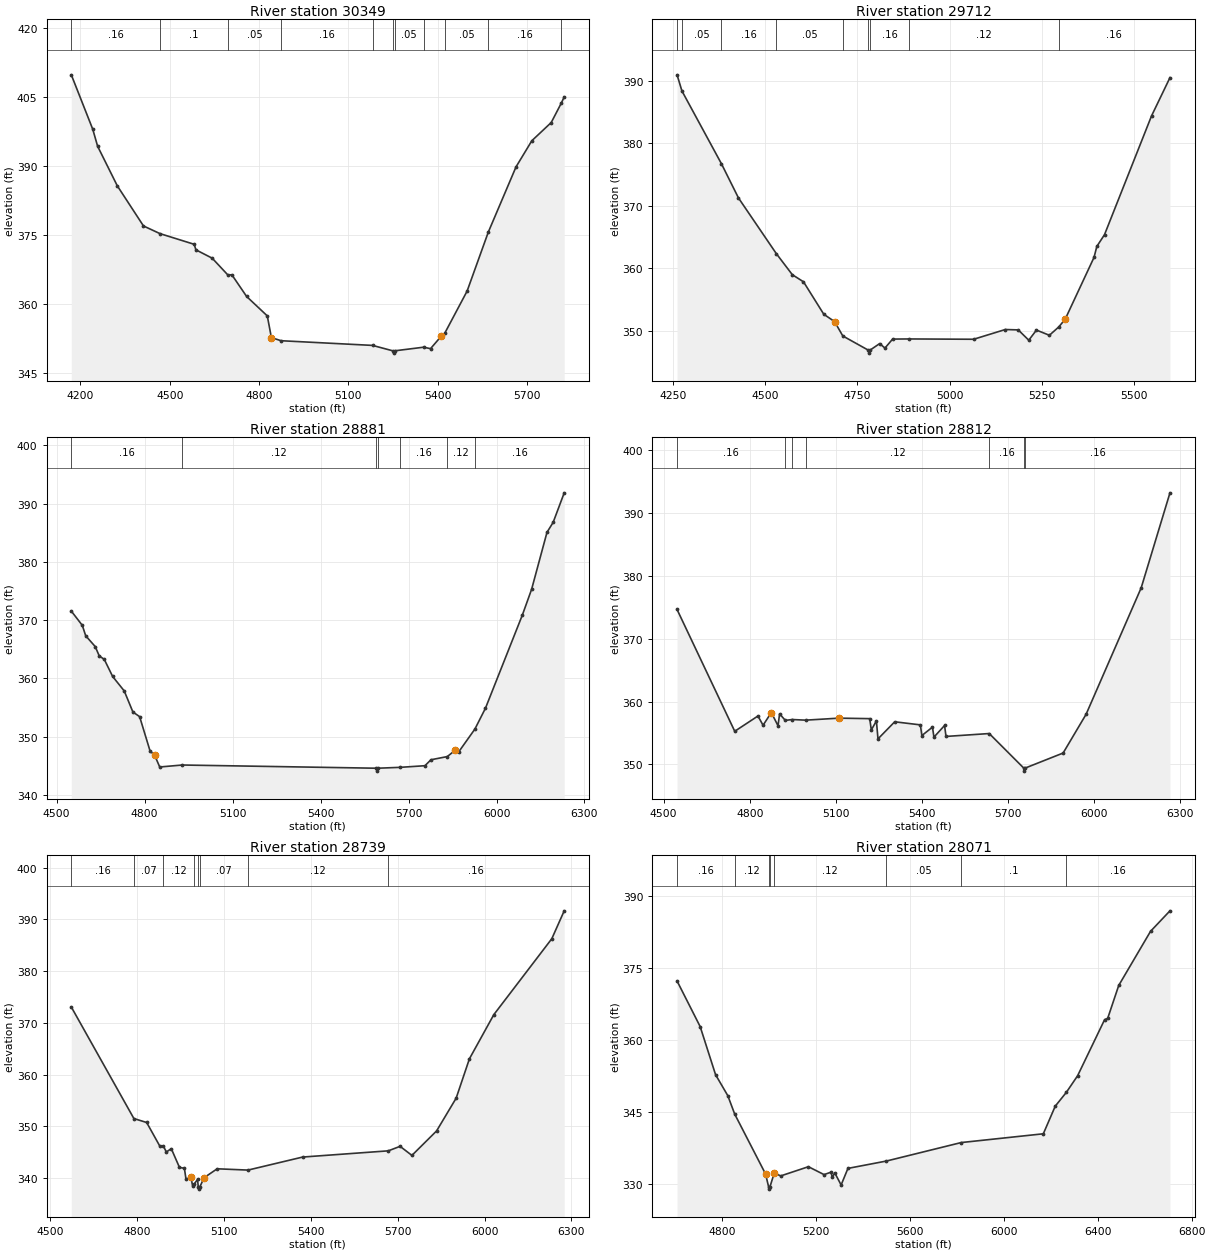
Type RM Length L Ch R = 1 ,30349   ,637,637,637
BEGIN DESCRIPTION:
DEVILS JUMP CREEK 34.0
END DESCRIPTION:
XS GIS Cut Line= 3
      3553643.46     10350390.58       3553951.6     10349809.02
      3554342.11     10348891.63
#Sta/Elev= 30
  4169.6  409.84  4241.7  397.98    4258  394.29    4324  385.69    4412  376.95
  4467.6  375.28  4582.3  372.96    4588  371.76  4642.7  369.94  4695.6  366.27
  4708.7  366.33  4758.3  361.61  4827.7  357.38  4841.5  352.66  4873.9  351.98
  5181.2  350.96  5249.3  349.78    5252  349.28  5255.3  349.78  5352.8  350.57
  5375.9  350.25  5411.8  352.96  5423.8  353.63  5498.7  362.78    5570  375.63
    5663  389.81  5716.1   395.5  5781.2  399.46  5815.1  403.69  5824.8  405.04
#Mann= 11 ,-1 , 0
  4169.6     .16       0  4467.6      .1       0  4695.6     .05       0
  4873.9     .16       0  5181.2     .05       0  5249.3     .07       0
  5255.3     .05       0  5352.8     .16       0  5423.8     .05       0
    5570     .16       0  5815.1      .1       0
Bank Sta=4841.5,5411.8
XS Rating Curve= 0 ,0
Exp/Cntr=0.3,0.1

Type RM Length L Ch R = 1 ,29712   ,831,831,831
BEGIN DESCRIPTION:
DEVILS JUMP CREEK 33.0
END DESCRIPTION:
XS GIS Cut Line= 3
      3553855.45     10350486.79      3554255.47     10350336.78
      3554842.09     10349641.66
#Sta/Elev= 30
    4261  390.99  4274.2  388.41  4381.3  376.76  4427.6  371.27  4530.1  362.37
  4573.6  358.99  4603.9  357.85    4659  352.65  4688.2  351.48  4710.5  349.18
  4778.9  346.93  4781.6  346.43  4784.9  346.93  4810.5  347.96  4824.8  347.24
  4845.6  348.68  4889.6   348.7  5065.4  348.65  5151.2  350.21  5186.3  350.15
  5214.9   348.5  5235.7  350.12  5270.8  349.29  5296.2  350.62  5313.7  351.87
  5391.8  361.75  5399.5  363.52  5420.3   365.4  5547.8  384.41  5597.8  390.54
#Mann= 9 ,-1 , 0
    4261     .16       0  4274.2     .05       0  4381.3     .16       0
  4530.1     .05       0  4710.5     .16       0  4778.9     .07       0
  4784.9     .16       0  4889.6     .12       0  5296.2     .16       0
Bank Sta=4688.2,5313.7
XS Rating Curve= 0 ,0
Exp/Cntr=0.3,0.1

Type RM Length L Ch R = 1 ,28881   ,69,69,69
BEGIN DESCRIPTION:
DEVILS JUMP CREEK 32.0
END DESCRIPTION:
XS GIS Cut Line= 4
      3554628.67     10351245.69      3554903.58     10350646.81
      3554762.96     10349982.74      3554866.79     10349655.68
#Sta/Elev= 30
    4550  371.54  4587.5  369.09  4599.1   367.3  4631.5  365.45  4645.1  363.86
  4662.5  363.24    4691  360.31  4730.5  357.83    4760  354.22    4783  353.41
  4818.5  347.53  4834.5  346.75  4851.5  344.77  4928.4  345.11  5589.4  344.56
  5592.2  344.06  5595.4  344.56  5671.3  344.71    5756  344.99  5776.4  346.01
  5832.2  346.56  5858.2  347.61  5870.6  347.33  5926.4  351.29  5962.3  354.86
  6088.3  370.88  6119.7  375.28  6172.2  385.07  6193.2  386.78  6230.9  391.85
#Mann= 7 ,-1 , 0
    4550     .16       0  4928.4     .12       0  5589.4     .07       0
  5595.4     .12       0  5671.3     .16       0  5832.2     .12       0
  5926.4     .16       0
Bank Sta=4834.5,5858.2
XS Rating Curve= 0 ,0
Exp/Cntr=0.3,0.1

Type RM Length L Ch R = 1 ,28812   ,73,73,73
BEGIN DESCRIPTION:
DEVILS JUMP CREEK 31.0
END DESCRIPTION:
XS GIS Cut Line= 4
      3554684.83     10351297.86       3554976.5     10350636.39
      3554833.27     10350034.83      3554887.96     10349662.42
#Sta/Elev= 30
  4546.7  374.66  4747.7  355.28  4828.6  357.71  4846.4  356.24  4875.2  358.26
  4898.5  356.16    4904  358.05  4924.1  357.01  4948.1  357.15  4994.8  357.05
  5110.9  357.37  5218.1  357.29  5223.6  355.49  5241.4  356.93  5246.9  354.07
  5305.2  356.79  5394.6   356.3  5399.8   354.6  5436.8  355.94  5441.9  354.35
  5478.9   356.2    5484  354.46  5634.6  354.92  5754.6  349.44  5757.4  348.94
  5760.6  349.44  5892.1  351.82  5972.1  357.98  6164.1   378.1  6264.4  393.22
#Mann= 7 ,-1 , 0
  4546.7     .16       0  4924.1     .12       0  4948.1     .07       0
  4994.8     .12       0  5634.6     .16       0  5754.6     .07       0
  5760.6     .16       0
Bank Sta=4875.2,5110.9
XS Rating Curve= 0 ,0
Exp/Cntr=0.3,0.1

Type RM Length L Ch R = 1 ,28739   ,668,668,668
BEGIN DESCRIPTION:
Mapping XS 03d087d0
END DESCRIPTION:
XS GIS Cut Line= 4
      3554736.91     10351316.09      3555057.23     10350649.41
      3554945.25      10350079.1      3554958.27     10349698.87
#Sta/Elev= 30
  4573.6  373.05  4789.6  351.49  4833.7  350.73  4878.9  346.18  4891.1  346.21
  4901.6  345.03  4918.7  345.67  4946.9  342.05  4963.9  341.87  4969.5  339.76
  4986.6  340.18  4992.1  338.51    4998  338.85  5009.2  339.72  5011.8  338.35
  5014.5  337.85  5017.8  338.35  5031.9  340.06  5077.1  341.78  5183.4  341.53
  5372.1  344.05  5667.6  345.25  5708.4  346.12  5749.2  344.37  5834.4   349.1
  5901.9  355.43  5947.8  363.05    6032  371.58  6232.1  386.25  6274.9  391.64
#Mann= 8 ,-1 , 0
  4573.6     .16       0  4789.6     .07       0  4891.1     .12       0
    4998     .07       0  5011.8     .07       0  5017.8     .07       0
  5183.4     .12       0  5667.6     .16       0
Bank Sta=4986.6,5031.9
XS Rating Curve= 0 ,0
Exp/Cntr=0.3,0.1

Type RM Length L Ch R = 1 ,28071   ,1297,1297,1297
BEGIN DESCRIPTION:
DEVILS JUMP CREEK 30.0
END DESCRIPTION:
XS GIS Cut Line= 3
      3555218.95     10351653.65      3555574.86     10351037.32
      3555340.49     10349670.18
#Sta/Elev= 30
  4608.8  372.28  4707.2   362.8  4772.8   352.8  4824.9  348.44  4854.3  344.61
  4985.7  332.16  4998.5  329.52  5001.3  329.02  5004.5  329.52  5021.4  332.16
  5023.1  332.34  5050.4  331.77  5168.1  333.68  5234.7  332.04  5264.3  332.54
  5270.1  331.45  5280.1  332.42  5307.4  329.88  5336.4  333.33  5500.5  334.86
  5818.8   338.7  6168.4  340.52  6219.1  346.26  6266.5  349.14  6314.4  352.59
  6429.4  364.25  6442.3  364.49  6489.5  371.36  6624.9   382.6  6707.6  386.86
#Mann= 8 ,-1 , 0
  4608.8     .16       0  4854.3     .12       0  4998.5     .07       0
  5004.5     .12       0  5021.4     .12       0  5500.5     .05       0
  5818.8      .1       0  6266.5     .16       0
Bank Sta=4985.7,5023.1
XS Rating Curve= 0 ,0
Exp/Cntr=0.3,0.1

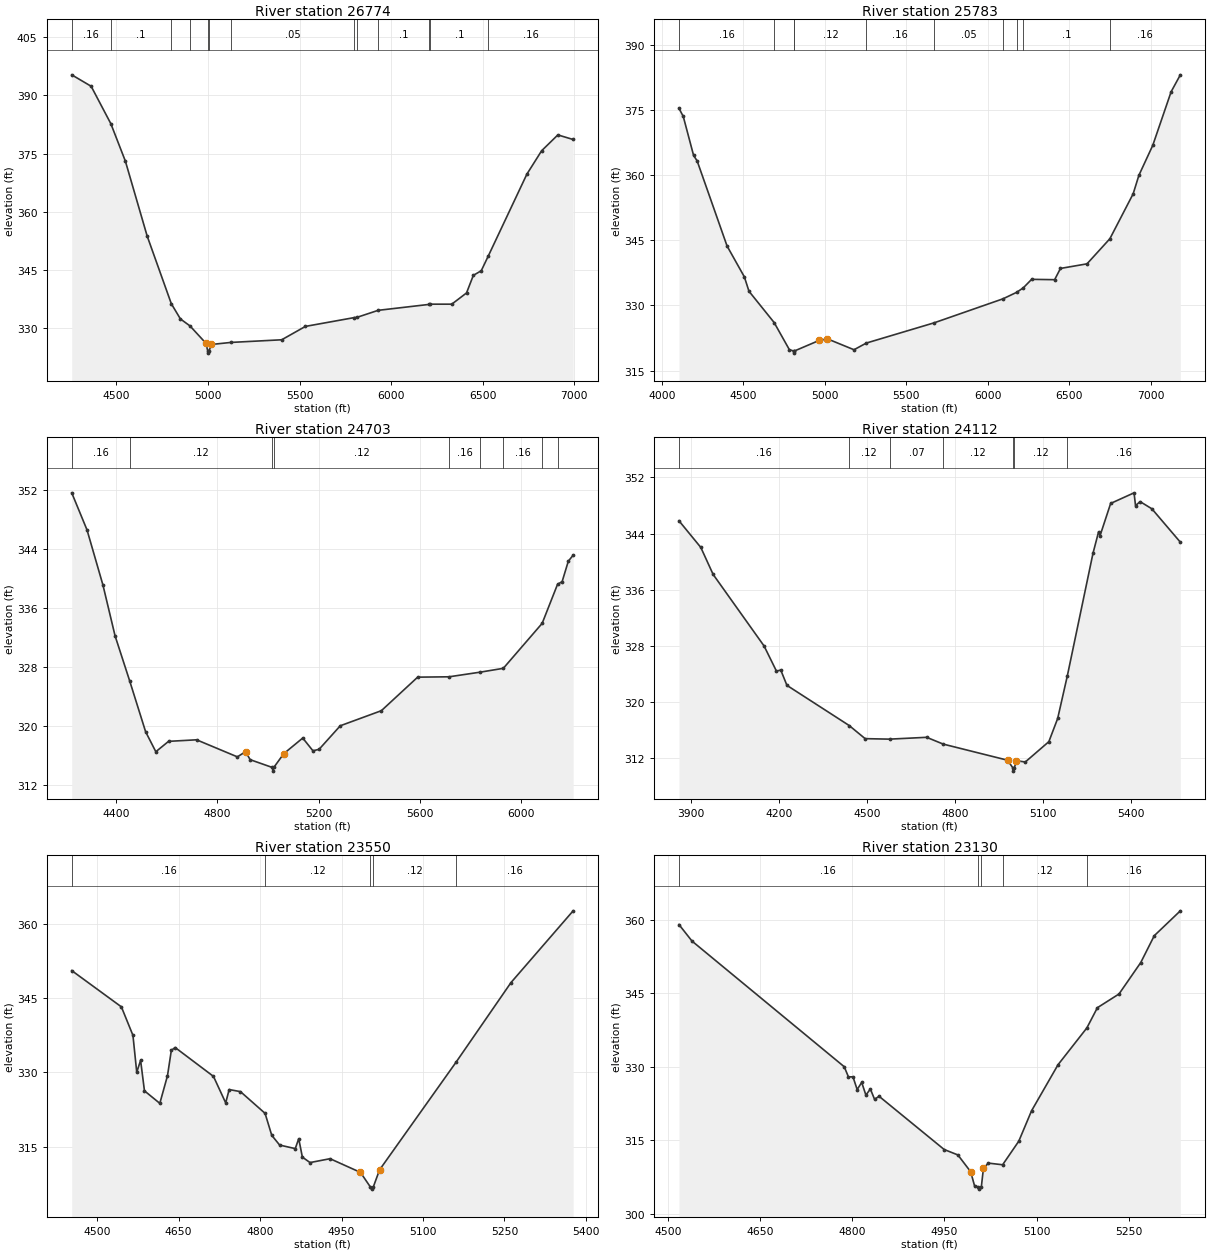
Type RM Length L Ch R = 1 ,26774   ,991,991,991
BEGIN DESCRIPTION:
DEVILS JUMP CREEK 29.0
END DESCRIPTION:
XS GIS Cut Line= 3
      3556685.96      10352126.7      3556438.58     10351232.63
      3555536.47     10349662.61
#Sta/Elev= 30
    4256  395.29    4362  392.34  4469.6  382.69  4549.1  373.02  4667.6  353.78
  4799.9  336.28  4849.6  332.36  4901.9  330.56  4987.6  326.16  4999.4  324.05
  5002.2  323.55  5005.4  324.05  5018.7  325.78  5125.6  326.31  5402.8  326.99
  5532.2  330.44  5800.2  332.72  5813.6  332.77  5929.5  334.58  6209.5  336.12
  6213.6  336.17  6331.5  336.17  6412.1  339.06  6449.4   343.6  6492.6  344.79
  6531.6  348.65  6741.8  369.69  6822.5  375.73  6910.9   379.8  6994.4  378.62
#Mann= 13 ,-1 , 0
    4256     .16       0  4469.6      .1       0  4799.9     .12       0
  4901.9     .16       0  4999.4     .07       0  5005.4     .16       0
  5125.6     .05       0  5800.2     .16       0  5813.6     .05       0
  5929.5      .1       0  6209.5     .05       0  6213.6      .1       0
  6531.6     .16       0
Bank Sta=4987.6,5018.7
XS Rating Curve= 0 ,0
Exp/Cntr=0.3,0.1

Type RM Length L Ch R = 1 ,25783   ,1080,1080,1080
BEGIN DESCRIPTION:
DEVILS JUMP CREEK 28.0
END DESCRIPTION:
XS GIS Cut Line= 3
      3557775.36     10351935.74      3557059.24     10351150.17
      3555706.06     10349658.21
#Sta/Elev= 30
  4105.3  375.41  4131.8  373.53  4195.3  364.54  4216.9   363.3  4400.7  343.69
  4506.8  336.59  4535.1  333.28  4689.6  326.07  4783.1  319.82  4808.5  319.53
  4811.2  319.03  4814.5  319.53  4966.9  321.97  5016.9  322.31  5179.7  319.81
  5255.5  321.35  5671.7  326.01  6094.4  331.54  6178.4  333.04  6219.1  334.08
  6269.8  336.02    6411  335.94  6446.8  338.53  6609.7  339.59    6750  345.37
  6892.9  355.71    6928  359.96  7013.2  366.87    7126  379.22  7182.5  383.11
#Mann= 10 ,-1 , 0
  4105.3     .16       0  4689.6     .12       0  4808.5     .07       0
  4814.5     .12       0  5255.5     .16       0  5671.7     .05       0
  6094.4      .1       0  6178.4     .05       0  6219.1      .1       0
    6750     .16       0
Bank Sta=4966.9,5016.9
XS Rating Curve= 0 ,0
Exp/Cntr=0.3,0.1

Type RM Length L Ch R = 1 ,24703   ,591,591,591
BEGIN DESCRIPTION:
DEVILS JUMP CREEK 27.0
END DESCRIPTION:
XS GIS Cut Line= 3
      3557842.11     10351491.66      3557742.11     10350691.64
      3557311.02     10349596.47
#Sta/Elev= 30
  4223.5  351.67    4284  346.62    4347  339.12  4394.8  332.23  4452.7  326.09
  4515.8  319.17  4556.1  316.46  4606.5  317.87  4717.3  318.08  4878.6  315.76
  4911.3  316.47    4929  315.38  5016.7  314.32  5019.4  313.82  5022.7  314.32
    5062  316.19  5137.2  318.32  5177.4  316.59  5201.7  316.78  5285.7  319.99
  5448.2  322.04  5591.7   326.6  5716.1  326.65    5839  327.28  5930.5   327.8
  6084.2  333.92  6144.9  339.22  6163.2   339.6  6187.6  342.37  6206.7  343.19
#Mann= 9 ,-1 , 0
  4223.5     .16       0  4452.7     .12       0  5016.7     .07       0
  5022.7     .12       0  5716.1     .16       0    5839      .1       0
  5930.5     .16       0  6084.2      .1       0  6144.9     .05       0
Bank Sta=4911.3,5062
XS Rating Curve= 0 ,0
Exp/Cntr=0.3,0.1

Type RM Length L Ch R = 1 ,24112   ,562,562,562
BEGIN DESCRIPTION:
DEVILS JUMP CREEK 26.0
END DESCRIPTION:
XS GIS Cut Line= 3
      3558751.94     10351453.98      3558205.07      10350646.7
      3558144.45     10349914.88
#Sta/Elev= 30
  3858.3  345.82  3932.9  342.02  3974.9  338.18  4148.6     328  4190.6  324.44
  4205.5  324.57  4226.5   322.4  4438.6  316.69  4493.1  314.82  4576.3  314.75
  4702.8  315.01  4759.6  314.04  4978.9  311.75    4996   310.7  4998.7   310.2
    5002   310.7    5009  311.68  5039.1   311.5  5119.4  314.39  5149.5  317.69
  5182.3  323.73  5269.9  341.19  5289.1  344.26  5294.1  343.71  5330.1  348.28
  5409.9  349.79  5414.9  347.97  5430.5  348.54  5470.6  347.52  5567.7  342.77
#Mann= 7 ,-1 , 0
  3858.3     .16       0  4438.6     .12       0  4576.3     .07       0
  4759.6     .12       0    4996     .07       0    5002     .12       0
  5182.3     .16       0
Bank Sta=4978.9,5009
XS Rating Curve= 0 ,0
Exp/Cntr=0.3,0.1

Type RM Length L Ch R = 1 ,23550   ,420,420,420
BEGIN DESCRIPTION:
DEVILS JUMP CREEK 25.0
END DESCRIPTION:
XS GIS Cut Line= 3
      3558985.17      10350697.9      3558835.16     10350547.89
      3558392.09     10349991.63
#Sta/Elev= 30
  4453.2  350.57  4544.6  343.24  4565.9  337.48  4572.9  330.01    4580  332.43
  4587.1  326.26  4615.4  323.73  4629.5  329.31  4636.6  334.44  4643.6  335.02
  4714.2  329.18  4736.7  323.83  4743.1  326.52  4763.9   326.1  4809.2  321.71
  4821.5  317.27    4836   315.3  4864.8  314.58  4871.2  316.59  4877.9  312.86
    4892  311.76  4928.9  312.54  4984.9  309.77  5002.7  306.89  5005.5  306.39
  5008.7  306.89  5020.1   310.3  5160.5  331.99    5262  348.14  5376.5  362.65
#Mann= 5 ,-1 , 0
  4453.2     .16       0  4809.2     .12       0  5002.7     .07       0
  5008.7     .12       0  5160.5     .16       0
#XS Ineff= 2 , 0
         4763.07  326.11
Permanent Ineff=
       F       F
Bank Sta=4984.9,5020.1
XS Rating Curve= 0 ,0
Exp/Cntr=0.3,0.1

Type RM Length L Ch R = 1 ,23130   ,401,401,401
BEGIN DESCRIPTION:
DEVILS JUMP CREEK 24.0
END DESCRIPTION:
XS GIS Cut Line= 3
      3559292.11     10350391.65       3559038.4     10350156.24
      3558742.11     10349791.65
#Sta/Elev= 30
  4517.9  359.09  4539.2   355.7  4786.9  330.01  4793.7  327.94  4801.1  327.95
  4807.9  325.35  4815.3  326.81  4822.1  324.22  4829.4  325.46  4836.2  323.36
  4843.6  323.97  4949.5  313.09  4971.8  311.98  4992.6  308.55  4999.1  305.59
    5004  305.49  5006.7  304.99    5010  305.49  5013.4  309.25  5021.4  310.31
  5044.6  309.97  5070.9  314.79  5091.7  321.01  5134.8  330.43  5181.7  337.95
  5198.8  342.08    5234  344.89  5269.4  351.32  5291.4  356.81  5333.8  361.89
#Mann= 5 ,-1 , 0
  4517.9     .16       0    5004     .07       0    5010     .16       0
  5044.6     .12       0  5181.7     .16       0
Bank Sta=4992.6,5013.4
XS Rating Curve= 0 ,0
Exp/Cntr=0.3,0.1