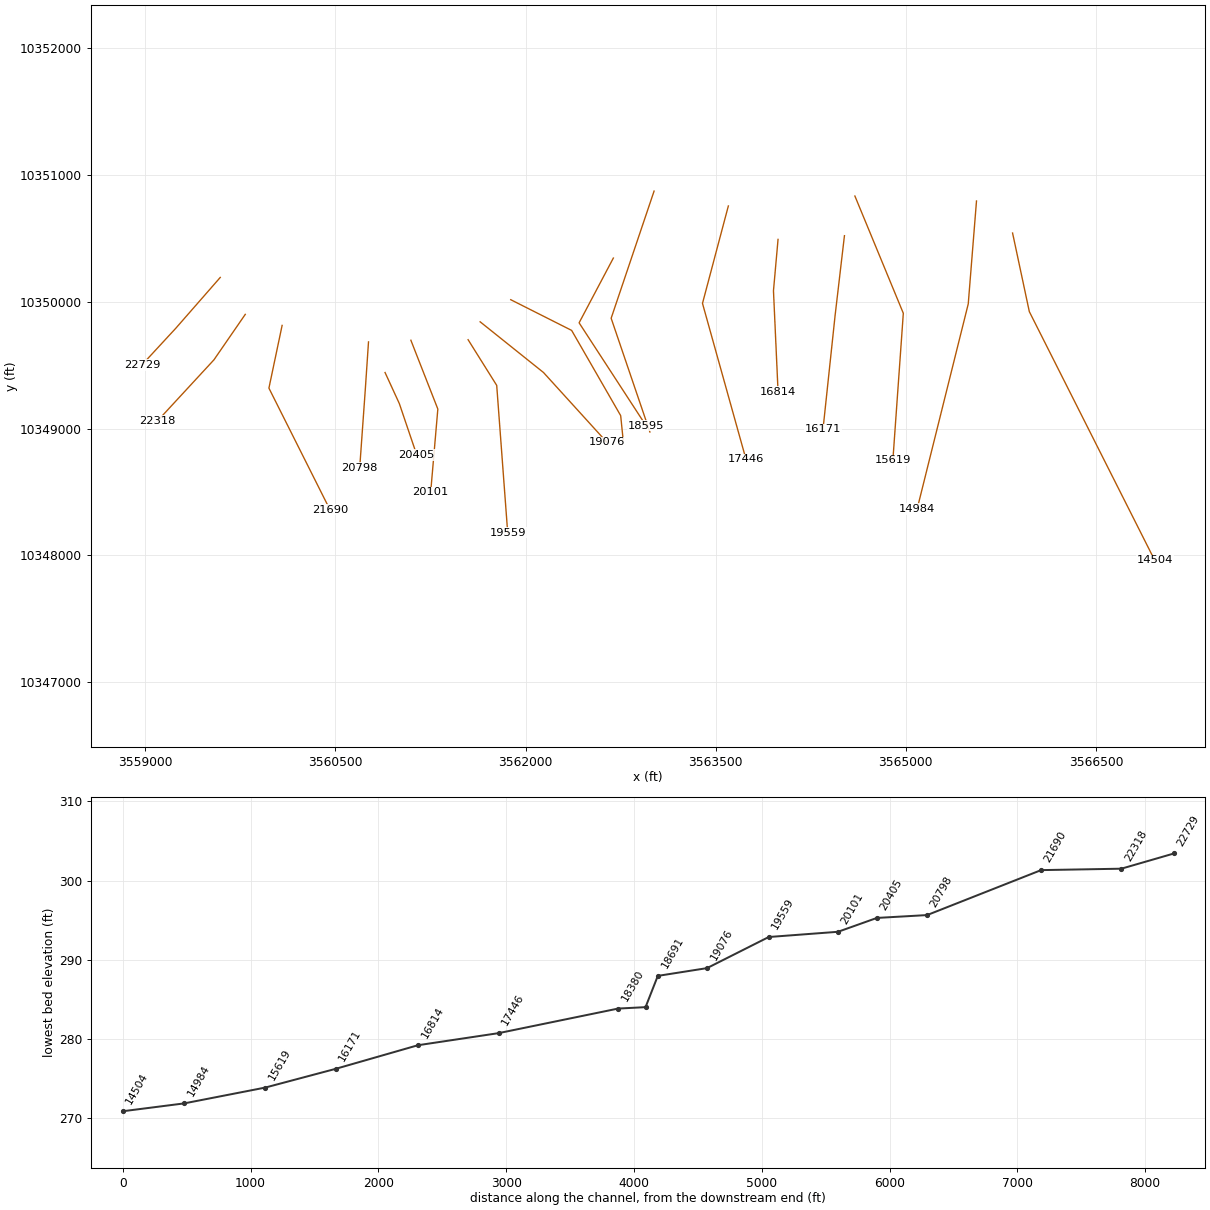
HEC-RAS study DEVILS JUMP CREEK.prj: DEVILS JUMP CREEK Base Level Engineering

--- DEVILS JUMP CREEK.g01 (geometry) --- (continued)

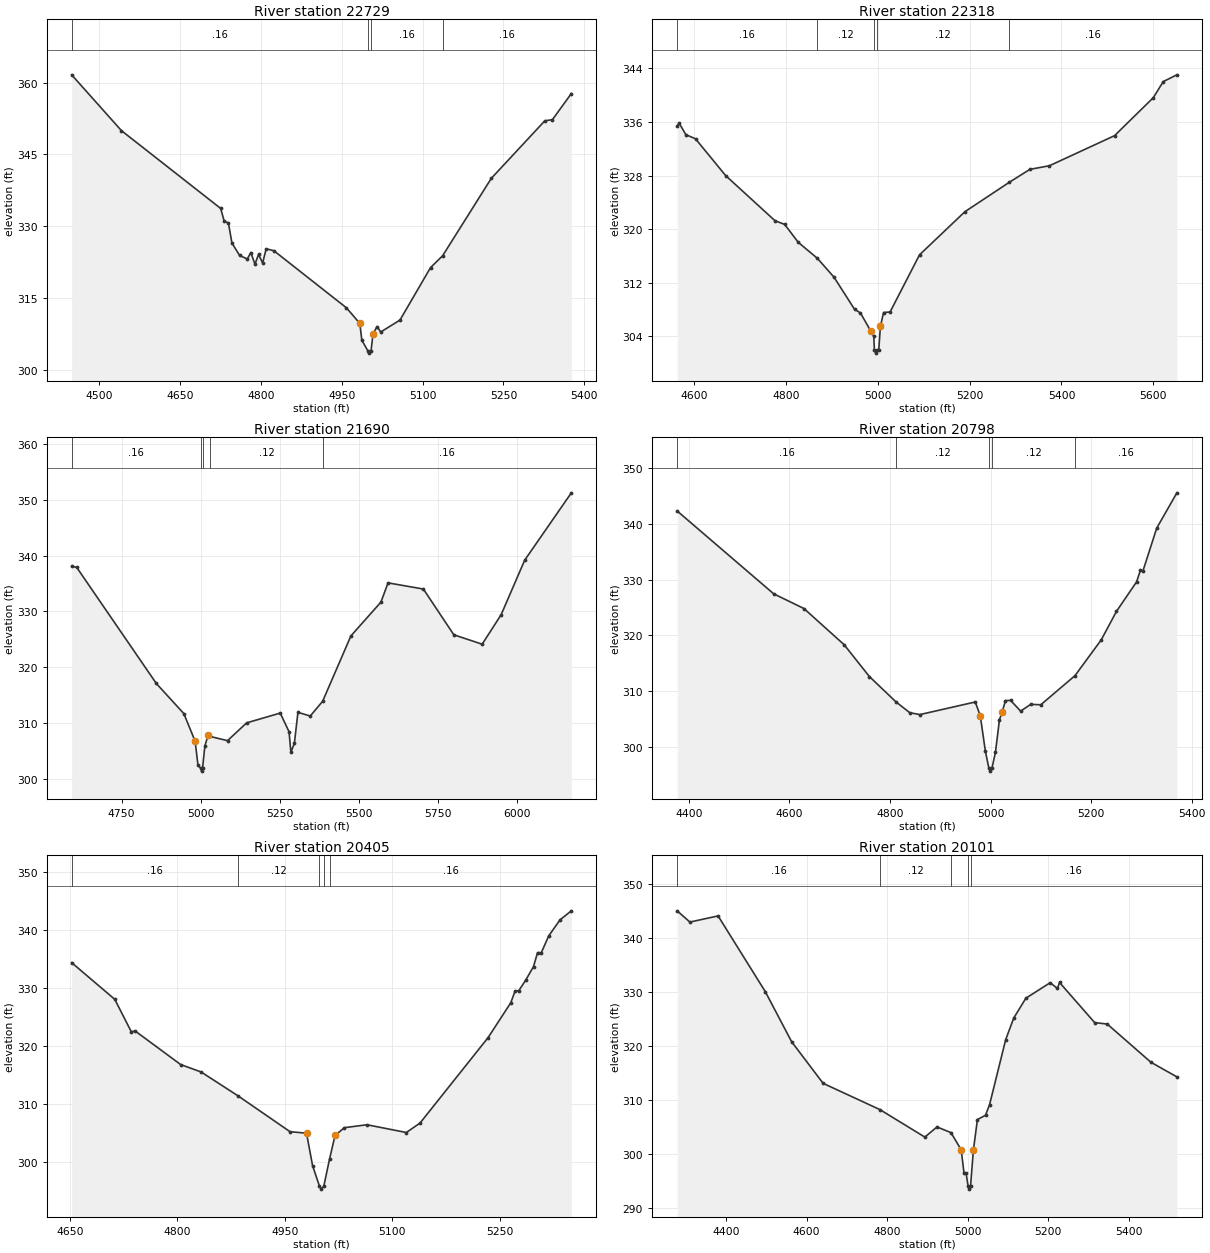
Type RM Length L Ch R = 1 ,22729   ,411,411,411
BEGIN DESCRIPTION:
DEVILS JUMP CREEK 23.0
END DESCRIPTION:
XS GIS Cut Line= 3
      3559592.08     10350191.62      3559242.11     10349791.64
      3558973.28     10349500.84
#Sta/Elev= 30
  4448.6  361.63  4541.1  349.95  4725.2  333.69  4731.9  330.97  4739.5  330.69
  4746.1  326.46  4760.4  323.85  4774.6  323.12  4781.2  324.47  4788.8  322.03
  4795.5  324.06  4803.1  322.29  4809.7  325.25  4823.9  324.85  4958.7   312.9
  4983.5  309.64  4987.2  306.14  4998.3  303.93  5001.1  303.43  5004.3  303.93
  5008.1  307.51  5015.5  308.98  5022.3  307.85    5058  310.34  5114.7  321.31
  5137.2   323.8  5227.6  339.99  5326.8  352.01    5341  352.26  5376.1  357.72
#Mann= 4 ,-1 , 0
  4448.6     .16       0  4998.3     .07       0  5004.3     .16       0
  5137.2     .16       0
Bank Sta=4983.5,5008.1
XS Rating Curve= 0 ,0
Exp/Cntr=0.3,0.1

Type RM Length L Ch R = 1 ,22318   ,628,628,628
BEGIN DESCRIPTION:
DEVILS JUMP CREEK 22.0
END DESCRIPTION:
XS GIS Cut Line= 3
      3559789.26     10349900.16      3559542.11     10349541.64
      3559099.15     10349062.47
#Sta/Elev= 30
  4563.3  335.34  4567.3  335.87  4582.2  334.12  4603.2   333.5  4668.8  328.01
  4776.3  321.27  4797.2  320.73    4827  318.04  4868.7  315.65  4904.8  312.84
  4949.4  308.06  4962.3  307.51  4985.2  304.74  4991.3  304.02  4992.7  302.01
  4995.5  301.51  4998.7  302.01  5002.2  302.01  5005.8  305.51  5012.7  307.57
  5026.8  307.65  5090.9  316.18  5189.6  322.61  5286.6  327.02  5331.3  328.94
  5373.8  329.48  5515.6  333.97  5600.1  339.65  5621.6  342.04  5651.3  343.05
#Mann= 5 ,-1 , 0
  4563.3     .16       0  4868.7     .12       0  4992.7     .07       0
  4998.7     .12       0  5286.6     .16       0
Bank Sta=4985.2,5005.8
XS Rating Curve= 0 ,0
Exp/Cntr=0.3,0.1

Type RM Length L Ch R = 1 ,21690   ,892,892,892
BEGIN DESCRIPTION:
DEVILS JUMP CREEK 21.0
END DESCRIPTION:
XS GIS Cut Line= 3
      3560080.08     10349813.39       3559975.9     10349318.57
      3560457.38     10348359.95
#Sta/Elev= 30
  4592.4  338.08  4608.2  337.91  4859.9  317.06  4946.7  311.66  4982.5  306.69
  4991.4  302.41  4999.9  301.83  5002.7  301.33  5005.9  301.83  5013.2  305.86
  5023.4  307.77    5030  307.55  5084.7   306.8  5145.1  309.99  5251.2  311.75
  5279.1   308.4  5284.9  304.73  5295.9  306.31  5307.2  311.88  5346.1  311.22
  5385.2  313.87  5474.5   325.6  5569.4  331.67  5591.8  335.12  5703.4  334.01
  5799.6   325.8  5889.1  324.11    5949   329.4  6023.4  339.19  6170.8  351.28
#Mann= 5 ,-1 , 0
  4592.4     .16       0  4999.9     .07       0  5005.9     .16       0
    5030     .12       0  5385.2     .16       0
Bank Sta=4982.5,5023.4
XS Rating Curve= 0 ,0
Exp/Cntr=0.3,0.1

Type RM Length L Ch R = 1 ,20798   ,393,393,393
BEGIN DESCRIPTION:
DEVILS JUMP CREEK 20.0
END DESCRIPTION:
XS GIS Cut Line= 3
      3560761.49     10349683.12      3560735.45     10349296.87
      3560692.11     10348691.65
#Sta/Elev= 30
  4376.8   342.3  4568.7  327.45  4628.9  324.81    4709  318.31    4759  312.62
  4812.2  308.05  4839.4  306.13  4859.4  305.79  4969.7  308.05  4979.7  305.55
  4989.7  299.27  4996.8  296.15  4999.5  295.65  5002.8  296.15  5009.8  299.02
  5017.8  304.87  5022.8  306.18  5029.8  308.29  5039.9  308.34  5059.9  306.41
    5080  307.63    5100  307.55    5168  312.77  5220.3   319.2  5250.4  324.28
  5290.5  329.59  5298.1  331.64  5303.1  331.53  5330.6  339.23  5370.7  345.56
#Mann= 5 ,-1 , 0
  4376.8     .16       0  4812.2     .12       0  4996.8     .07       0
  5002.8     .12       0    5168     .16       0
Bank Sta=4979.7,5022.8
XS Rating Curve= 0 ,0
Exp/Cntr=0.3,0.1

Type RM Length L Ch R = 1 ,20405   ,304,304,304
BEGIN DESCRIPTION:
DEVILS JUMP CREEK 19.0
END DESCRIPTION:
XS GIS Cut Line= 3
      3560892.09     10349441.68      3561004.55     10349197.04
      3561142.12      10348791.6
#Sta/Elev= 30
  4652.6  334.41  4712.8  328.07  4735.8  322.48  4741.3   322.6  4804.7  316.81
  4833.2  315.53  4884.7  311.41  4957.4  305.21  4980.4  304.95  4988.8  299.37
  4998.5  295.79  5001.2  295.29  5004.5  295.79  5012.6  300.52  5020.2  304.56
  5033.2   305.9  5064.8  306.41  5119.7  305.07  5138.8   306.7  5233.8  321.46
  5265.5  327.49  5271.4  329.49  5276.7  329.57  5286.6  331.45  5297.2  333.73
  5302.8  336.13  5308.1  336.13  5318.3  339.01  5334.2   341.8    5350  343.36
#Mann= 5 ,-1 , 0
  4652.6     .16       0  4884.7     .12       0  4998.5     .07       0
  5004.5     .12       0  5012.6     .16       0
Bank Sta=4980.4,5020.2
XS Rating Curve= 0 ,0
Exp/Cntr=0.3,0.1

Type RM Length L Ch R = 1 ,20101   ,542,542,542
BEGIN DESCRIPTION:
DEVILS JUMP CREEK 18.0
END DESCRIPTION:
XS GIS Cut Line= 3
      3561095.71     10349696.14      3561308.37     10349153.64
      3561251.95     10348498.26
#Sta/Elev= 30
  4278.8  345.03  4310.3  342.95  4380.3  344.09  4497.5  330.08  4562.9  320.81
  4641.1  313.11  4781.9  308.26  4893.6  303.17  4923.7  305.04  4958.4     304
  4983.9   300.8  4990.9  296.48  4995.9  296.57    5001  294.04  5003.8  293.54
    5007  294.04  5014.1  300.76  5024.1  306.41  5044.2  307.21  5054.2  309.15
  5094.4  321.22  5114.4  325.21  5144.5  328.87  5204.8  331.73  5222.9  330.66
  5227.9  331.78  5315.2  324.35  5346.4  324.08  5454.9  317.01  5519.3  314.31
#Mann= 5 ,-1 , 0
  4278.8     .16       0  4781.9     .12       0  4958.4     .16       0
    5001     .07       0    5007     .16       0
Bank Sta=4983.9,5014.1
XS Rating Curve= 0 ,0
Exp/Cntr=0.3,0.1

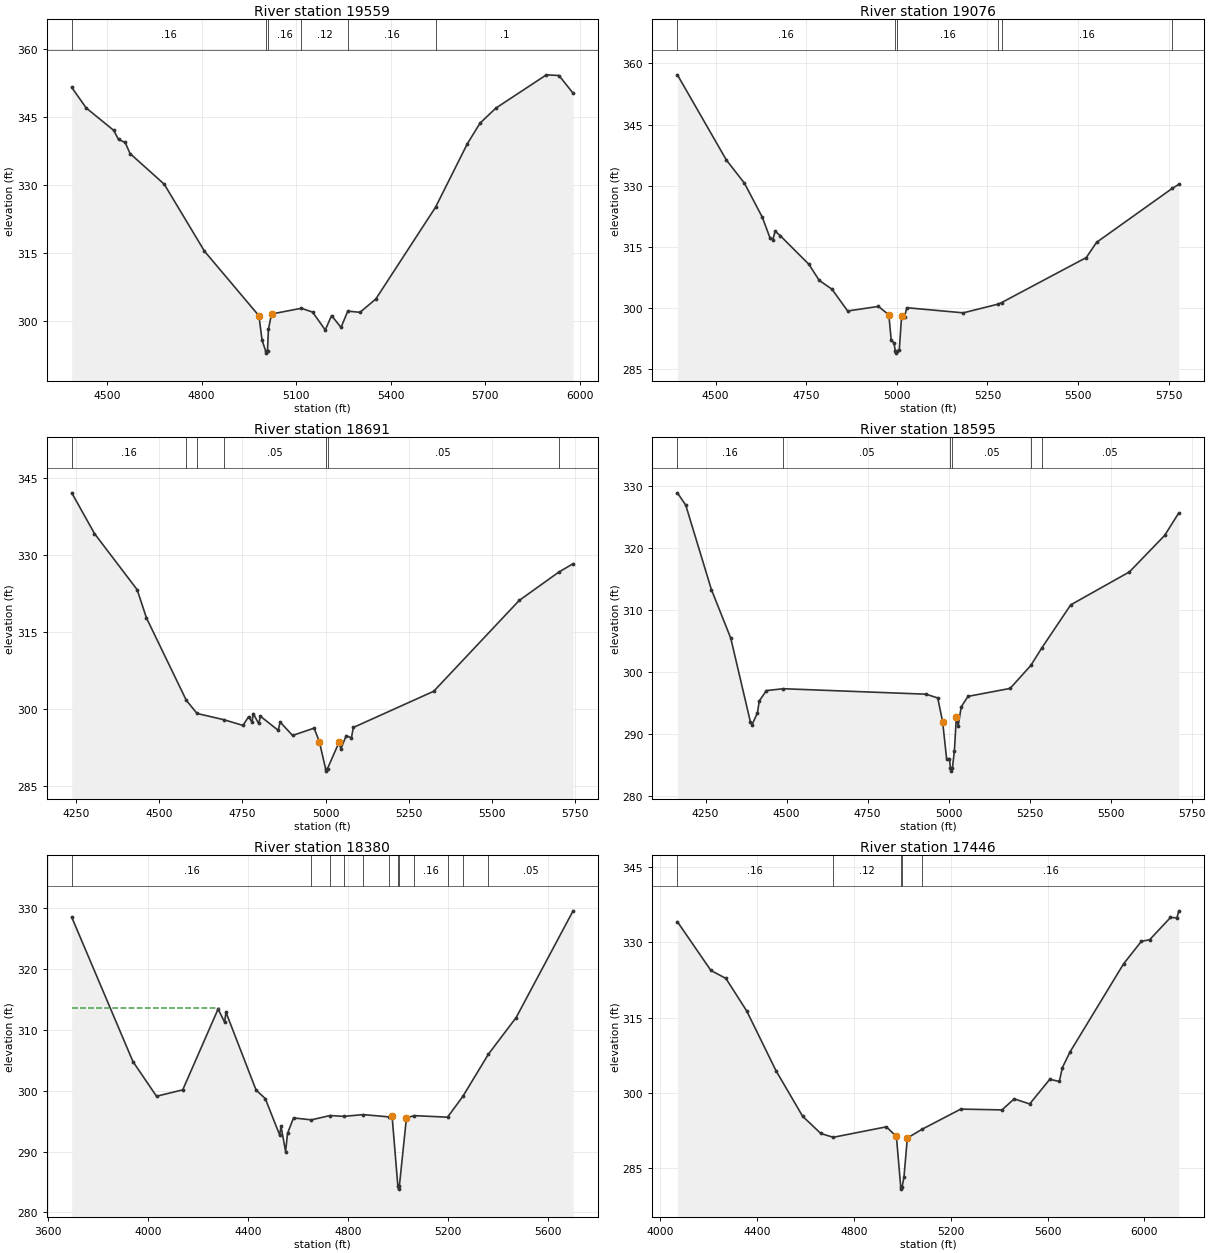
Type RM Length L Ch R = 1 ,19559   ,483,483,483
BEGIN DESCRIPTION:
DEVILS JUMP CREEK 17.0
END DESCRIPTION:
XS GIS Cut Line= 3
      3561547.07     10349700.53      3561772.78     10349340.27
      3561859.59     10348177.03
#Sta/Elev= 30
    4388  351.51  4433.9  346.97  4521.2  342.03  4536.5  340.02  4557.7  339.36
    4573  336.92  4681.7  330.15  4809.4  315.37  4982.2  301.13  4992.3  295.71
  5003.5  293.38  5006.2  292.88  5009.5  293.38  5012.3  298.11  5022.3  301.51
  5117.1  302.78  5152.7  301.93  5192.8  297.99  5212.9  301.16  5242.9  298.55
  5264.3  302.15  5303.1  301.88  5353.3  304.82  5542.9  325.07  5644.1   339.1
  5684.2  343.62  5734.3  346.93  5894.8  354.28  5934.9  354.13  5979.6  350.22
#Mann= 6 ,-1 , 0
    4388     .16       0  5003.5     .07       0  5009.5     .16       0
  5117.1     .12       0  5264.3     .16       0  5542.9      .1       0
Bank Sta=4982.2,5022.3
XS Rating Curve= 0 ,0
Exp/Cntr=0.3,0.1

Type RM Length L Ch R = 1 ,19076   ,385,385,385
BEGIN DESCRIPTION:
DEVILS JUMP CREEK 16.0
END DESCRIPTION:
XS GIS Cut Line= 3
      3561642.12     10349841.63      3562142.11     10349441.64
      3562642.11     10348891.64
#Sta/Elev= 30
  4394.5  357.18  4529.7  336.28  4579.4  330.63    4629  322.23  4650.6  317.06
  4657.8  316.74  4664.2  318.86  4678.6  317.72  4757.1  310.75  4785.9  306.78
  4821.1  304.62  4864.3  299.28  4949.2   300.4    4978  298.35  4984.4  292.23
  4992.4  291.37  4995.8  289.45  4998.5  288.95  5001.8  289.45  5006.8  289.76
  5013.2  297.99  5021.2  297.86  5027.6  300.08  5183.5  298.83  5279.1  300.95
  5289.5  301.36    5523  312.39  5551.4  316.12  5759.8  329.32  5778.1  330.32
#Mann= 6 ,-1 , 0
  4394.5     .16       0  4995.8     .07       0  5001.8     .16       0
  5279.1     .12       0  5289.5     .16       0  5759.8      .1       0
Bank Sta=4978,5013.2
XS Rating Curve= 0 ,0
Exp/Cntr=0.3,0.1

Type RM Length L Ch R = 1 ,18691   ,96,96,96
BEGIN DESCRIPTION:
Mapping XS 45323c71
END DESCRIPTION:
XS GIS Cut Line= 4
      3561883.47     10350016.02      3562363.94     10349773.83
      3562750.66     10349101.95      3562770.19     10348910.53
#Sta/Elev= 30
  4237.6  342.04  4305.9  334.13  4434.1  323.22    4462  317.74  4581.6  301.74
    4614  299.17  4694.5  297.96    4752  296.85  4768.7  298.55  4778.8  297.51
    4783  299.14  4798.8  297.23  4804.5  298.62  4857.7   295.9  4863.5  297.51
  4900.8   294.9  4965.5  296.32  4981.3   293.7  4999.8  288.47  5002.6  287.97
  5005.8  288.47  5040.2  293.55    5046  292.29  5061.8  294.85  5077.6  294.44
  5083.3  296.45  5324.8  303.49  5581.4  321.13  5700.4  326.64  5743.3  328.27
#Mann= 7 ,-1 , 0
  4237.6     .16       0  4581.6     .05       0    4614     .16       0
  4694.5     .05       0  4999.8     .04       0  5005.8     .05       0
  5700.4      .1       0
Bank Sta=4981.3,5040.2
XS Rating Curve= 0 ,0
Exp/Cntr=0.3,0.1

Type RM Length L Ch R = 1 ,18595   ,215,215,215
BEGIN DESCRIPTION:
Mapping XS ef778908
END DESCRIPTION:
XS GIS Cut Line= 3
      3562692.93     10350344.32      3562422.76      10349833.6
      3562951.62     10349021.38
#Sta/Elev= 30
  4163.3  328.87    4189  326.89  4268.1  313.29  4327.9  305.45  4388.3     292
  4393.9  291.53  4410.3  293.43  4415.9  295.33  4437.9     297  4489.9   297.3
  4930.3  296.42  4966.6  295.81  4981.7  291.95    4994  286.01  5002.8  285.92
  5005.8  284.52  5008.5  284.02  5011.8  284.52  5017.9  287.23  5023.9  292.67
  5029.9  291.37    5039  294.39  5060.1  296.07  5189.9  297.35    5254  301.06
  5287.8  303.89    5377  310.82  5558.1  316.13  5666.8  322.01  5710.3  325.63
#Mann= 6 ,-1 , 0
  4163.3     .16       0  4489.9     .05       0  5005.8     .04       0
  5011.8     .05       0    5254     .16       0  5287.8     .05       0
Bank Sta=4981.7,5023.9
XS Rating Curve= 0 ,0
Exp/Cntr=0.3,0.1

Type RM Length L Ch R = 1 ,18380   ,934,934,934
BEGIN DESCRIPTION:
DEVILS JUMP CREEK 15.0
END DESCRIPTION:
XS GIS Cut Line= 3
      3563014.11     10350872.41      3562675.56     10349869.79
      3562981.14     10348972.75
#Sta/Elev= 30
  3694.5  328.54  3939.3  304.82  4033.7  299.11  4138.6  300.16  4280.1  313.45
  4306.2  311.28  4311.5  312.92  4432.1  300.12  4468.8  298.73  4526.5  292.73
  4531.8  294.19  4550.2  290.01  4557.9  293.02  4581.9  295.54  4653.3  295.23
  4728.3  295.94  4783.3   295.8  4860.5  296.09  4962.9  295.72  4976.3  295.81
  4999.3  284.34  5002.1  283.84  5005.3  284.34  5033.7  295.57  5065.3  295.92
  5198.1  295.67  5259.2  299.08  5361.8  306.04  5472.6  312.05  5700.4  329.59
#Mann= 12 ,-1 , 0
  3694.5     .16       0  4653.3     .12       0  4728.3     .05       0
  4783.3     .12       0  4860.5     .16       0  4962.9     .12       0
  4999.3     .07       0  5005.3     .12       0  5065.3     .16       0
  5198.1     .05       0  5259.2     .16       0  5361.8     .05       0
#XS Ineff= 2 , 0
         4282.67  313.54
Permanent Ineff=
       F       F
Bank Sta=4976.3,5033.7
XS Rating Curve= 0 ,0
Exp/Cntr=0.3,0.1

Type RM Length L Ch R = 1 ,17446   ,632,632,632
BEGIN DESCRIPTION:
DEVILS JUMP CREEK 14.0
END DESCRIPTION:
XS GIS Cut Line= 3
      3563600.04     10350755.23      3563396.04     10349986.97
      3563738.91     10348758.71
#Sta/Elev= 30
  4071.6  334.13  4209.8  324.41  4271.9  322.81  4357.8  316.31  4478.8  304.38
  4588.5   295.3  4663.7  291.85  4714.9  291.09  4934.3  293.18  4975.8  291.27
  4993.6  281.24  4996.4  280.74  4999.6  281.24    5007  283.12  5020.9  290.94
    5082   292.7  5241.5  296.72  5411.9  296.56  5462.1  298.77  5526.1  297.75
  5609.1  302.67  5648.5  302.24  5661.1  305.01    5693  308.16  5913.6  325.71
  5987.2  330.22  6021.3  330.53  6107.5  334.98  6134.2  334.91  6141.7  336.31
#Mann= 5 ,-1 , 0
  4071.6     .16       0  4714.9     .12       0  4993.6     .07       0
  4999.6     .12       0    5082     .16       0
Bank Sta=4975.8,5020.9
XS Rating Curve= 0 ,0
Exp/Cntr=0.3,0.1

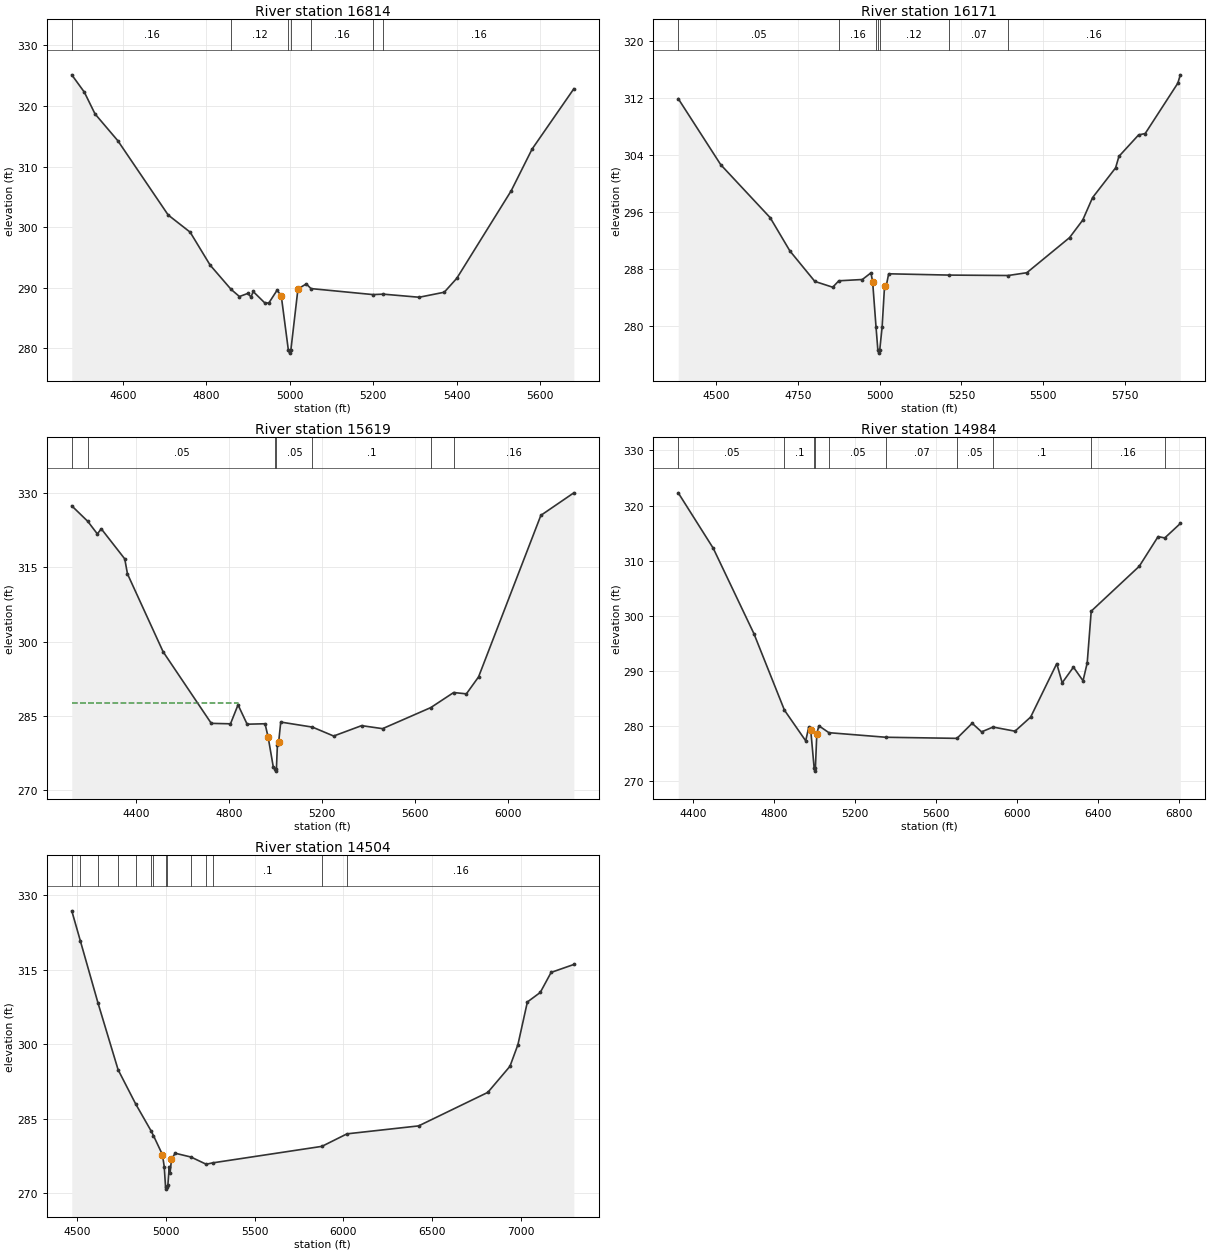
Type RM Length L Ch R = 1 ,16814   ,643,643,643
BEGIN DESCRIPTION:
DEVILS JUMP CREEK 12.0
END DESCRIPTION:
XS GIS Cut Line= 3
       3563992.1     10350491.62      3563955.94      10350086.8
      3563992.11     10349291.65
#Sta/Elev= 30
  4477.9  325.13    4508  322.27  4533.6  318.68  4588.3  314.25  4708.8     302
  4761.4  299.17  4809.2  293.74  4859.3  289.74  4879.4  288.55  4899.5  289.06
  4907.3  288.47  4912.3  289.38  4939.5  287.54  4949.6  287.46  4969.6  289.59
  4979.6  288.67  4996.6  279.71  4999.4  279.21  5002.6  279.71  5019.6  289.81
  5039.6  290.63  5050.7  289.86  5199.2  288.87  5224.1  288.94  5309.9  288.43
    5370  289.26    5400  291.56  5530.2  305.99  5580.2  312.87  5680.3  322.83
#Mann= 7 ,-1 , 0
  4477.9     .16       0  4859.3     .12       0  4996.6     .07       0
  5002.6     .12       0  5050.7     .16       0  5199.2     .07       0
  5224.1     .16       0
Bank Sta=4979.6,5019.6
XS Rating Curve= 0 ,0
Exp/Cntr=0.3,0.1

Type RM Length L Ch R = 1 ,16171   ,552,552,552
BEGIN DESCRIPTION:
DEVILS JUMP CREEK 11.0
END DESCRIPTION:
XS GIS Cut Line= 3
      3564515.83     10350520.79      3564442.11     10349891.64
      3564346.75     10348994.85
#Sta/Elev= 30
  4383.9   311.9  4513.9  302.64    4665  295.22  4725.4  290.55  4801.7  286.28
  4856.3  285.47    4875  286.37  4946.9  286.55  4973.2  287.48  4978.3  286.27
  4988.8  279.85  4994.2  276.73    4997  276.23  5000.2  276.73  5007.3  279.86
  5014.8  285.64  5019.9  285.64  5027.4  287.35  5211.4  287.17  5392.8  287.11
  5449.8   287.5  5580.5  292.42  5620.7  294.87  5650.9  298.03  5721.3   302.2
  5731.5  303.81  5791.7  306.82  5811.8  307.01  5911.6  314.07  5919.2  315.24
#Mann= 7 ,-1 , 0
  4383.9     .05       0    4875     .16       0  4988.8     .12       0
  4994.2     .07       0  5000.2     .12       0  5211.4     .07       0
  5392.8     .16       0
Bank Sta=4978.3,5014.8
XS Rating Curve= 0 ,0
Exp/Cntr=0.3,0.1

Type RM Length L Ch R = 1 ,15619   ,635,635,635
BEGIN DESCRIPTION:
DEVILS JUMP CREEK 10.0
END DESCRIPTION:
XS GIS Cut Line= 3
      3564598.28     10350833.37      3564980.24     10349908.85
      3564897.78     10348749.99
#Sta/Elev= 30
  4122.2  327.45  4191.1  324.32  4232.3  321.78  4249.3  322.81  4350.3  316.74
  4362.1   313.7  4515.5  297.98    4723  283.51  4805.7  283.42  4838.2  287.25
  4877.3  283.34  4954.5  283.43    4968  280.69  4989.7  274.78  4997.5  274.36
  5000.2  273.86  5003.5  274.36  5007.7  279.13  5013.1  279.69  5022.1  283.77
  5158.8  282.75    5250  280.95  5370.3  283.05  5460.6  282.44    5668  286.69
  5766.8  289.74  5821.5  289.47  5873.9  292.89  6142.3  325.53  6284.3  330.08
#Mann= 7 ,-1 , 0
  4122.2     .16       0  4191.1     .05       0  4997.5    .035       0
  5003.5     .05       0  5158.8      .1       0    5668     .05       0
  5766.8     .16       0
#XS Ineff= 2 , 0
         4836.65  287.61
Permanent Ineff=
       F       F
Bank Sta=4968,5013.1
XS Rating Curve= 0 ,0
Exp/Cntr=0.3,0.1

Type RM Length L Ch R = 1 ,14984   ,480,480,480
BEGIN DESCRIPTION:
DEVILS JUMP CREEK 9.0
END DESCRIPTION:
XS GIS Cut Line= 3
       3565557.5     10350794.28       3565492.4     10349982.63
      3565089.12     10348365.21
#Sta/Elev= 30
  4326.5  322.31  4499.7  312.25  4700.3   296.8  4851.4  282.91  4956.5  277.35
  4971.2  279.79  4981.2  279.35  4998.3  272.36  5001.1  271.86  5004.3  272.36
  5011.3  278.64  5021.4  280.08  5071.1  278.83  5352.5     278  5703.8   277.8
  5779.1  280.53  5825.6  278.98  5882.3  279.85  5990.7   279.1  6068.1  281.66
  6197.1  291.35  6223.9  287.87  6279.6  290.71    6327  288.24  6347.6  291.48
  6367.4  300.86  6604.7  308.99    6698  314.38  6730.8  314.13  6807.7  316.75
#Mann= 10 ,-1 , 0
  4326.5     .05       0  4851.4      .1       0  4998.3     .07       0
  5004.3      .1       0  5071.1     .05       0  5352.5     .07       0
  5703.8     .05       0  5882.3      .1       0  6367.4     .16       0
  6730.8      .1       0
Bank Sta=4981.2,5011.3
XS Rating Curve= 0 ,0
Exp/Cntr=0.3,0.1

Type RM Length L Ch R = 1 ,14504   ,641,641,641
BEGIN DESCRIPTION:
DEVILS JUMP CREEK 7.0
END DESCRIPTION:
XS GIS Cut Line= 3
      3565842.11     10350541.62      3565974.17     10349921.87
      3566963.74     10347960.08
#Sta/Elev= 30
  4468.2   326.9  4517.3  320.76  4616.3  308.32  4729.5   294.9  4829.1  287.98
  4914.2  282.67  4928.6  281.66  4979.4  277.81  4989.6  275.38  4996.8  271.37
  4999.6  270.87  5002.8  271.37  5010.1  271.69  5017.6  275.42  5022.7  274.21
  5030.5  276.86    5051   278.1  5140.4  277.33  5226.2  275.88    5263  276.16
  5878.5  279.48  6020.1     282  6423.9   283.6  6814.1  290.35  6938.9   295.6
  6983.7  299.95  7037.1  308.55  7109.6  310.46  7170.9   314.5  7299.1   316.1
#Mann= 14 ,-1 , 0
  4468.2     .05       0  4517.3      .1       0  4616.3     .05       0
  4729.5      .1       0  4829.1     .05       0  4914.2      .1       0
  4928.6     .07       0  4996.8     .07       0  5002.8     .07       0
  5140.4     .12       0  5226.2     .07       0    5263      .1       0
  5878.5     .05       0  6020.1     .16       0
Bank Sta=4979.4,5030.5
XS Rating Curve= 0 ,0
Exp/Cntr=0.3,0.1