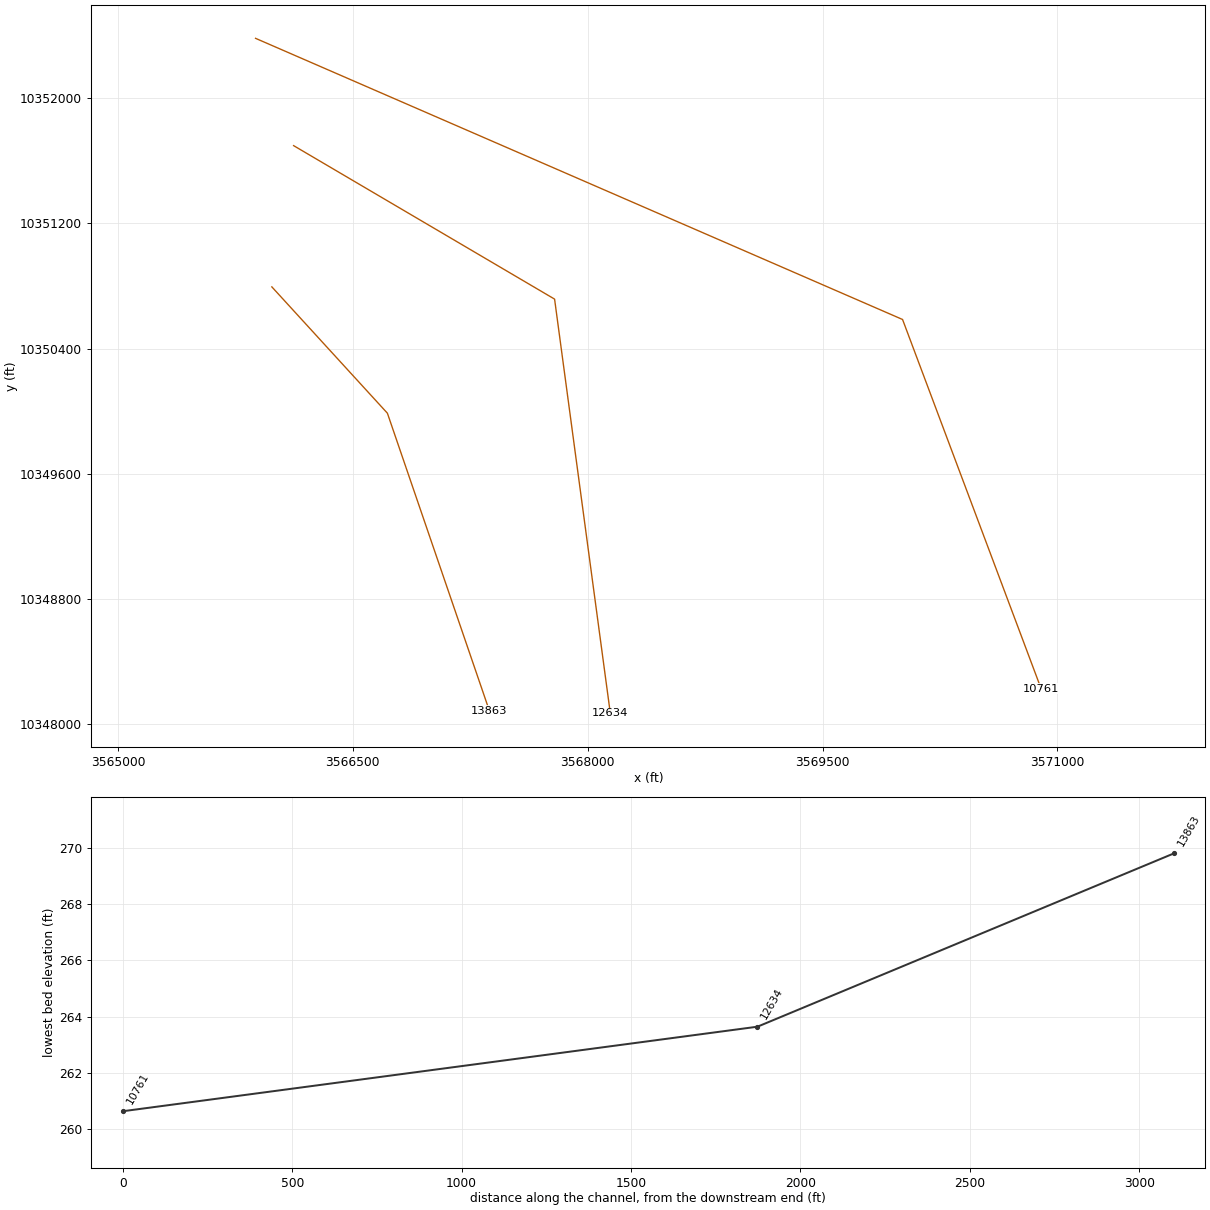
HEC-RAS study DEVILS JUMP CREEK.prj: DEVILS JUMP CREEK Base Level Engineering

--- DEVILS JUMP CREEK.g01 (geometry) --- (continued)

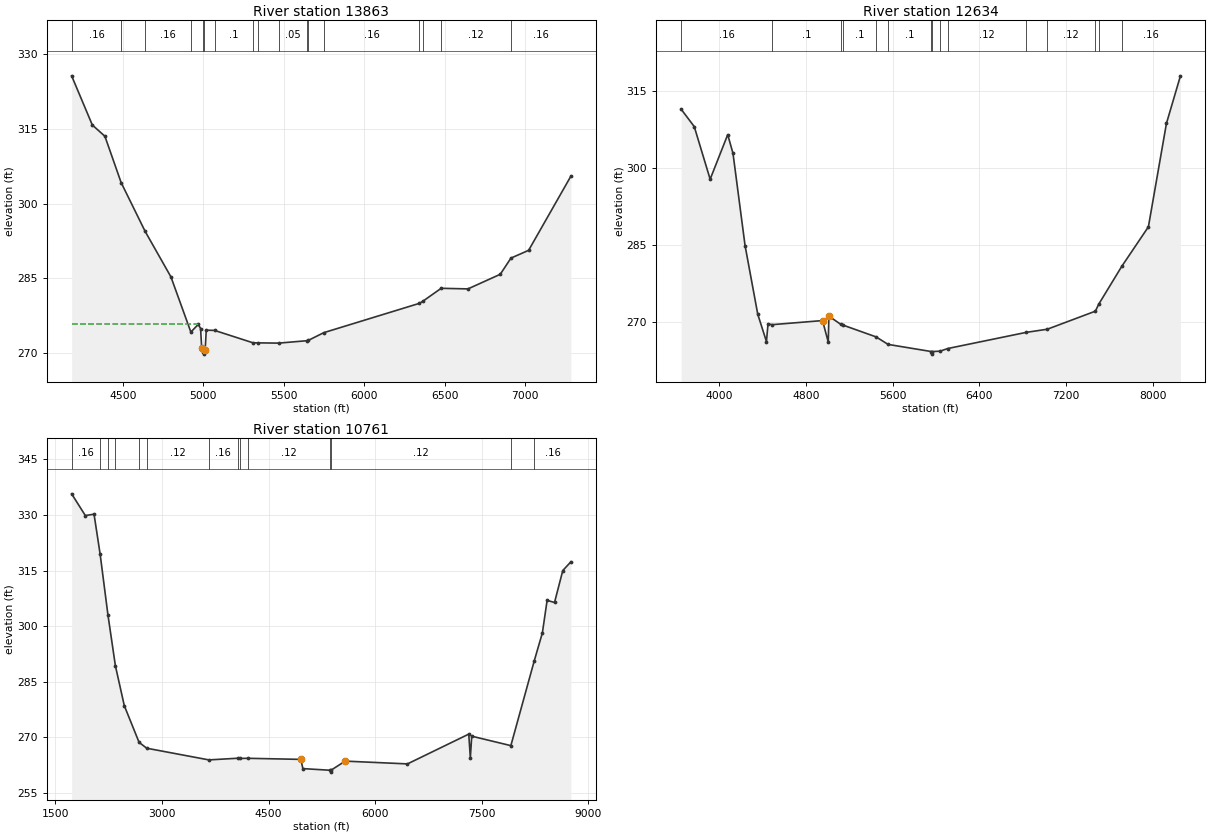
Type RM Length L Ch R = 1 ,13863   ,1229,1229,1229
BEGIN DESCRIPTION:
DEVILS JUMP CREEK 6.0
END DESCRIPTION:
XS GIS Cut Line= 3
      3565982.83     10350794.28       3566720.7     10349986.97
      3567371.63     10348086.25
#Sta/Elev= 30
  4181.7  325.66  4310.3  315.79  4388.5  313.53  4489.3  304.24  4638.6  294.44
  4798.7  285.32  4922.7  274.24  4968.9  275.78  4983.1  274.95  4989.9   271.1
  5001.1  270.31  5003.8  269.81  5007.1  270.31  5011.5   270.6  5018.3  274.62
  5070.2  274.57    5308  272.09  5339.3  272.07  5468.8  272.02  5646.5  272.51
  5652.6  272.57  5748.9  274.12  6341.8  279.99  6363.4   280.4  6478.2  283.02
  6644.6   282.9  6845.4  285.83  6911.8  289.08  7021.7  290.64  7284.5  305.53
#Mann= 17 ,-1 , 0
  4181.7     .16       0  4489.3     .05       0  4638.6     .16       0
  4922.7     .12       0  5001.1     .07       0  5007.1     .12       0
  5070.2      .1       0    5308     .05       0  5339.3      .1       0
  5468.8     .05       0  5646.5      .1       0  5652.6     .05       0
  5748.9     .16       0  6341.8     .12       0  6363.4     .16       0
  6478.2     .12       0  6911.8     .16       0
#XS Ineff= 2 , 0
         4966.48  275.86
Permanent Ineff=
       F       F
Bank Sta=4989.9,5011.5
XS Rating Curve= 0 ,0
Exp/Cntr=0.3,0.1

Type RM Length L Ch R = 1 ,12634   ,1873,1873,1873
BEGIN DESCRIPTION:
DEVILS JUMP CREEK 5.0
END DESCRIPTION:
XS GIS Cut Line= 3
      3566121.72     10351697.05       3567788.4     10350716.14
      3568144.31     10348068.57
#Sta/Elev= 30
  3648.6  311.53  3769.3  308.13  3915.9  297.84  4077.9  306.56  4126.6   302.9
  4237.9  284.87  4355.1  271.43  4435.2   266.1  4449.7  269.57  4486.6   269.4
  4952.5   270.2  5005.3     266  5011.1  271.07  5122.4  269.44  5144.5  269.29
  5446.5  267.01  5557.3  265.54  5957.4  264.14  5960.1  263.64  5963.4  264.14
    6038  264.22  6106.3  264.73  6830.2  267.89  7025.8  268.51  7469.4  272.04
  7499.9   273.4  7711.8  280.78  7958.2  288.53  8124.7  308.75  8253.9  318.06
#Mann= 15 ,-1 , 0
  3648.6     .16       0  4486.6      .1       0  5122.4     .05       0
  5144.5      .1       0  5446.5     .16       0  5557.3      .1       0
  5957.4     .07       0  5963.4      .1       0    6038     .16       0
  6106.3     .12       0  6830.2     .16       0  7025.8     .12       0
  7469.4     .16       0  7499.9     .12       0  7711.8     .16       0
Bank Sta=4952.5,5011.1
XS Rating Curve= 0 ,0
Exp/Cntr=0.3,0.1

Type RM Length L Ch R = 1 ,10761   ,0,0,0
BEGIN DESCRIPTION:
DEVILS JUMP CREEK 1.0
END DESCRIPTION:
XS GIS Cut Line= 3
      3565878.72     10352382.79      3570010.63     10350585.93
       3570895.7     10348225.73
#Sta/Elev= 30
  1728.5  335.73  1921.2  329.87  2043.9  330.23  2129.8  319.43  2239.4  303.08
  2344.4  289.33  2469.7  278.56  2677.9  268.66  2785.6  267.08    3660  263.93
  4067.8  264.38  4102.8  264.33  4208.5  264.36    4954  264.07  4982.9  261.58
  5371.4  261.13  5374.1  260.63  5377.4  261.13  5578.3   263.6  6454.9  262.85
  7317.5  270.89  7339.5  264.48  7359.1  270.33  7909.8  267.78  8239.5  290.69
  8353.4  298.21    8420  306.98  8524.3  306.41  8640.7  315.03  8754.9  317.39
#Mann= 14 ,-1 , 0
  1728.5     .16       0  2129.8     .05       0  2239.4     .16       0
  2344.4     .05       0  2677.9     .16       0  2785.6     .12       0
    3660     .16       0  4067.8     .12       0  4102.8     .16       0
  4208.5     .12       0  5371.4     .07       0  5377.4     .12       0
  7909.8     .05       0  8239.5     .16       0
Bank Sta=4954,5578.3
XS Rating Curve= 0 ,0
Exp/Cntr=0.3,0.1

Chan Stop Cuts=-1
Use User Specified Reach Order=0
Composite Channel Slope=5