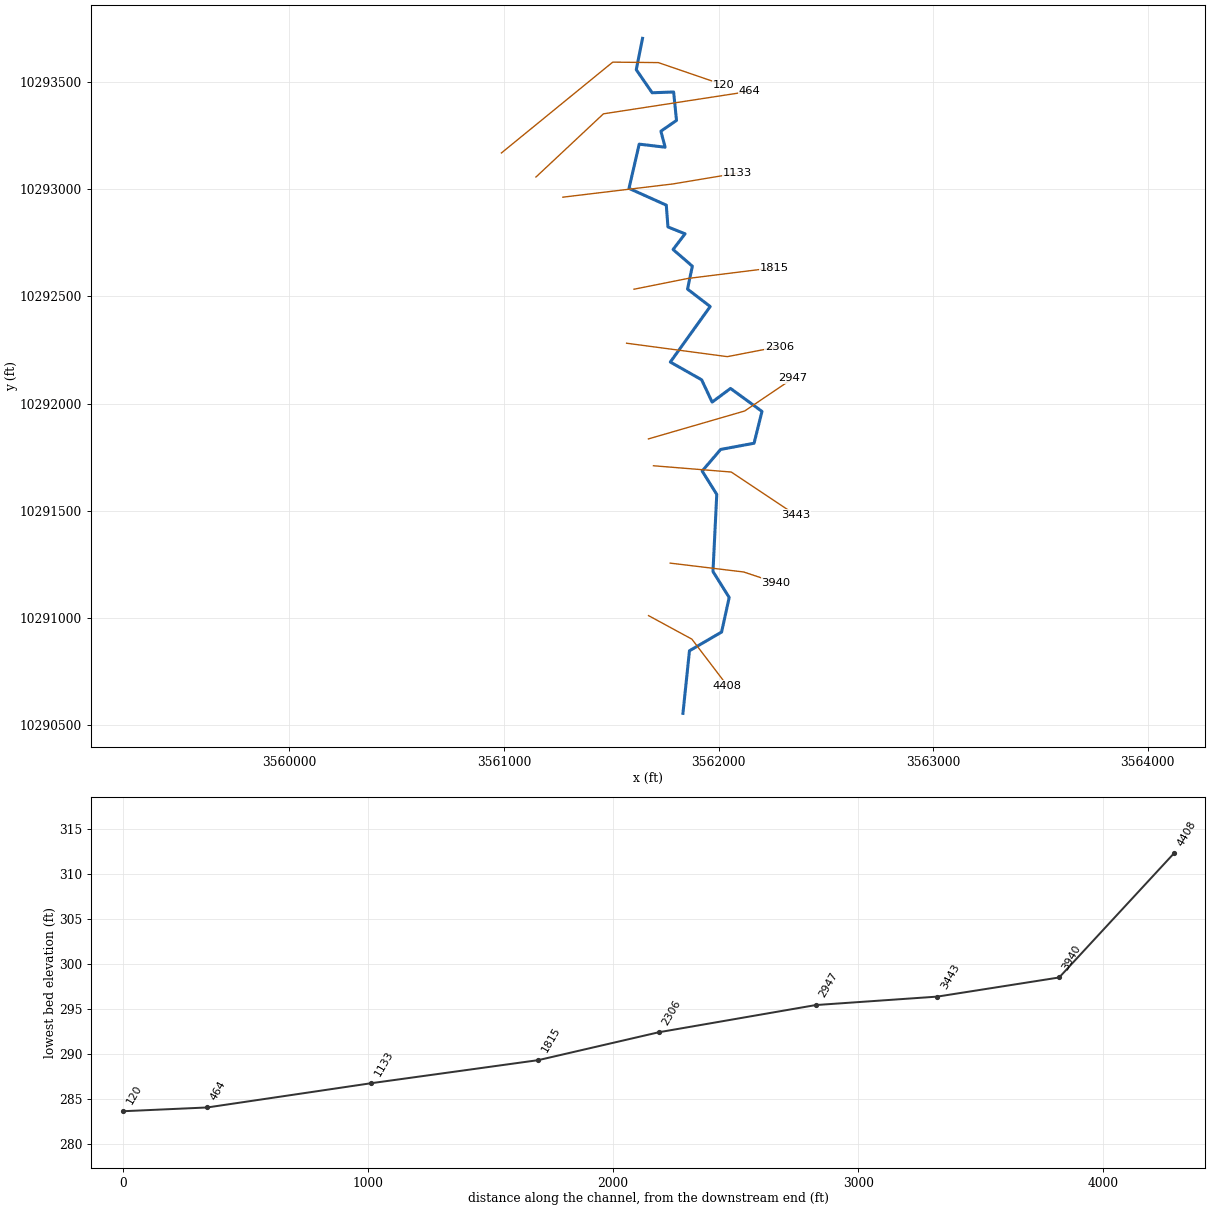
--- FERRILL BRANCH TRIBUTARY 1.prj (project) ---

Proj Title=FERRILL BRANCH TRIBUTARY 1 Base Level Engineering
Current Plan=p01
Default Exp/Contr=0.3,0.1
English Units
Geom File=g01
Flow File=f01
Plan File=p01
Y Axis Title=Elevation
X Axis Title(PF)=Main Channel Distance
X Axis Title(XS)=Station
BEGIN DESCRIPTION:
FERRILL BRANCH TRIBUTARY 1
END DESCRIPTION:
DSS Export Rating Curves= 0
DSS Export Rating Curve Sorted= 0
DSS Export Volume Flow Curves= 0
DXF OffsetX= 0
DXF OffsetY= 0
DXF ScaleX= 1
DXF ScaleY= 10

--- FERRILL BRANCH TRIBUTARY 1.p01 (plan) ---

Plan Title=Multiple Run
Short Identifier=Multiple
Geom File=g01
Flow File=f01
Subcritical Flow
K Sum by GR= 0
Std Step Tol= 0.01
Critical Tol= 0.01
Num of Std Step Trials= 20
Max Error Tol= 0.3
Flow Tol Ratio= 0.001
Split Flow NTrial= 30
Split Flow Tol= 0.02
Split Flow Ratio= 0.02
Log Output Level= 0
Friction Slope Method= 1
Unsteady Friction Slope Method= 2
Unsteady Bridges Friction Slope Method= 1
Parabolic Critical Depth
Global Vel Dist=  1 , 1 , 1
Global Log Level= 0
CheckData=True
Encroach Param= -1, 0, 0, 0
BEGIN DESCRIPTION:
Multiple Run
END DESCRIPTION:

--- FERRILL BRANCH TRIBUTARY 1.f01 (steady flow) ---

Flow Title=Multiple
Number of Profiles=7
Profile Names=10-year,25-year,50-year,1pct_min,100-year,1pct_plu,500-year
River Rch & RM= FERRILL BRANCH T,Reach-1,4408
     528     708     855     756    1023    1383    1467
River Rch & RM= FERRILL BRANCH T,Reach-1,120
    1790    2521    3139    2851    3855    5214    5835
Boundary for River Rch & Prof#=FERRILL BRANCH T,Reach-1,1
Up Type=0
Dn Type=3
Dn Slope=0.005
Boundary for River Rch & Prof#=FERRILL BRANCH T,Reach-1,2
Up Type=0
Dn Type=3
Dn Slope=0.005
Boundary for River Rch & Prof#=FERRILL BRANCH T,Reach-1,3
Up Type=0
Dn Type=3
Dn Slope=0.005
Boundary for River Rch & Prof#=FERRILL BRANCH T,Reach-1,4
Up Type=0
Dn Type=3
Dn Slope=0.005
Boundary for River Rch & Prof#=FERRILL BRANCH T,Reach-1,5
Up Type=0
Dn Type=3
Dn Slope=0.005
Boundary for River Rch & Prof#=FERRILL BRANCH T,Reach-1,6
Up Type=0
Dn Type=3
Dn Slope=0.005
Boundary for River Rch & Prof#=FERRILL BRANCH T,Reach-1,7
Up Type=0
Dn Type=3
Dn Slope=0.005

--- FERRILL BRANCH TRIBUTARY 1.g01 (geometry) ---

Geom Title=Existing Conditions
Program Version=4.10

River Reach=FERRILL BRANCH T,Reach-1
Reach XY= 30
      3561834.19     10290556.42      3561864.58     10290848.15
      3562014.23     10290935.29      3562049.65     10291096.31
      3561974.11     10291217.15      3561991.73     10291576.64
      3561923.69     10291685.47      3562009.71     10291785.96
      3562165.53     10291814.91      3562202.36      10291963.2
      3562055.88      10292070.2      3561970.16     10292006.55
      3561921.23     10292110.48      3561775.43     10292193.16
      3561961.15     10292451.86      3561855.51     10292532.93
      3561878.03     10292639.72      3561788.26     10292717.53
        3561844.     10292790.48      3561764.37     10292822.52
       3561756.6     10292924.06      3561582.89     10293002.19
      3561630.46     10293208.26       3561751.2     10293194.03
      3561731.45     10293268.48      3561804.23     10293318.92
       3561790.7     10293451.22      3561690.65     10293447.66
      3561616.73     10293555.11      3561645.96     10293701.21

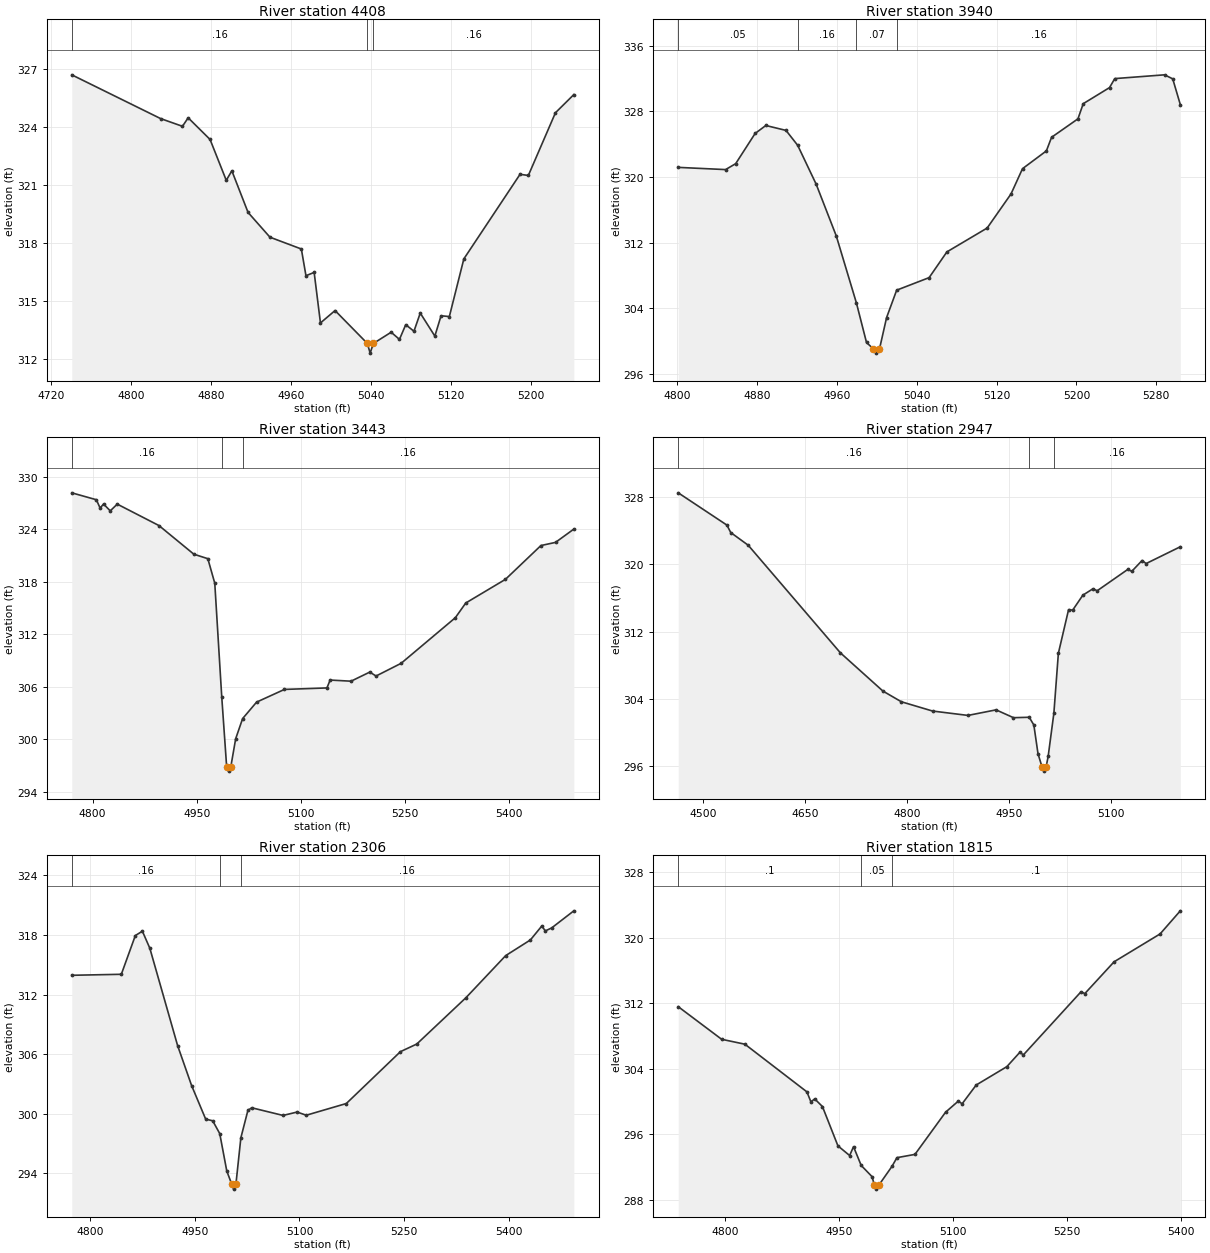
Type RM Length L Ch R = 1 ,4408    ,468,468,468
BEGIN DESCRIPTION:
FERRILL BRANCH TRIBUTARY 1 9.0
END DESCRIPTION:
XS GIS Cut Line= 3
      3561674.04     10291011.79      3561875.83     10290902.22
      3562040.87     10290685.41
#Sta/Elev= 30
  4740.4   326.7  4829.2  324.44  4851.1  324.04  4856.8  324.48  4878.7  323.36
  4894.9  321.25  4900.5  321.74  4916.7  319.59  4938.6  318.31    4970   317.7
  4974.6  316.32  4982.8  316.49  4989.1  313.88  5003.7  314.52    5036  312.82
  5038.8  312.32    5042  312.82  5059.8   313.4  5068.1  313.03  5074.4  313.79
  5082.6  313.45  5088.9  314.39  5103.5   313.2  5109.7  314.25    5118  314.21
  5132.5  317.19  5188.7  321.56    5197   321.5  5224.1  324.74  5242.5  325.68
#Mann= 3 ,-1 , 0
  4740.4     .16       0    5036     .07       0    5042     .16       0
Bank Sta=5036,5042
XS Rating Curve= 0 ,0
Exp/Cntr=0.3,0.1

Type RM Length L Ch R = 1 ,3940    ,497,497,497
BEGIN DESCRIPTION:
FERRILL BRANCH TRIBUTARY 1 8.0
END DESCRIPTION:
XS GIS Cut Line= 3
        3561775.     10291256.39      3562117.23      10291215.1
      3562267.11     10291165.14
#Sta/Elev= 30
  4801.3  321.17  4848.7   320.9  4858.8  321.62  4878.3  325.31    4889  326.28
  4909.2  325.68  4920.9  323.86  4939.4  319.12  4959.5  312.82  4979.7  304.63
  4989.8  299.81  4996.8  299.01  4999.6  298.51  5002.8  299.01  5009.9  302.84
    5020  306.19  5052.5  307.72  5070.3  310.86  5110.6  313.77  5134.5  317.93
    5146  321.01  5169.9  323.18  5175.1  324.84  5201.5  327.09  5206.8  328.94
  5233.1   330.9  5238.4     332  5288.2  332.46  5296.4  331.97    5304  328.83
#Mann= 4 ,-1 , 0
  4801.3     .05       0  4920.9     .16       0  4979.7     .07       0
    5020     .16       0
Bank Sta=4996.8,5002.8
XS Rating Curve= 0 ,0
Exp/Cntr=0.3,0.1

Type RM Length L Ch R = 1 ,3443    ,496,496,496
BEGIN DESCRIPTION:
FERRILL BRANCH TRIBUTARY 1 7.0
END DESCRIPTION:
XS GIS Cut Line= 3
      3561696.87     10291709.96      3562059.41     10291680.74
      3562358.27     10291481.51
#Sta/Elev= 30
  4770.1  328.16  4805.5  327.37  4810.9  326.42  4815.9  326.88  4825.5   326.1
  4835.6  326.87  4895.7  324.42  4945.9  321.15    4966  320.64    4976  317.84
    4986   304.9  4993.1  296.88  4995.8  296.38  4999.1  296.88  5006.1  300.08
  5016.1  302.38  5036.2  304.26  5076.3  305.71  5137.5  305.88  5142.1  306.78
  5172.2  306.65  5199.2  307.69  5208.2  307.24  5244.3  308.69  5322.4   313.9
  5337.4  315.58  5394.5  318.28  5445.6  322.14  5466.6   322.5    5493  324.02
#Mann= 3 ,-1 , 0
  4770.1     .16       0    4986     .07       0  5016.1     .16       0
Bank Sta=4993.1,4999.1
XS Rating Curve= 0 ,0
Exp/Cntr=0.3,0.1

Type RM Length L Ch R = 1 ,2947    ,641,641,641
BEGIN DESCRIPTION:
FERRILL BRANCH TRIBUTARY 1 6.0
END DESCRIPTION:
XS GIS Cut Line= 3
       3561673.4     10291835.09      3562121.72      10291965.1
      3562345.93     10292116.62
#Sta/Elev= 30
  4463.9  328.46  4535.4  324.63    4541  323.75  4566.7  322.24    4702  309.48
  4764.5  304.94  4791.6  303.67  4837.4  302.57  4889.4  302.05  4930.7  302.71
  4956.3  301.78  4979.4  301.83  4986.2  300.91  4992.3   297.5  4998.2  295.94
    5001  295.44  5004.2  295.94  5007.2  297.18  5015.6  302.31  5022.2  309.42
  5037.2   314.6  5043.2  314.54  5058.2  316.32  5073.1  317.08  5079.2  316.84
  5124.1  319.37  5130.1  319.15  5145.1  320.43  5151.1  320.07  5201.3  322.06
#Mann= 3 ,-1 , 0
  4463.9     .16       0  4979.4     .07       0  5015.6     .16       0
Bank Sta=4998.2,5004.2
XS Rating Curve= 0 ,0
Exp/Cntr=0.3,0.1

Type RM Length L Ch R = 1 ,2306    ,491,491,491
BEGIN DESCRIPTION:
FERRILL BRANCH TRIBUTARY 1 5.0
END DESCRIPTION:
XS GIS Cut Line= 3
      3561571.67     10292280.84      3562040.92     10292218.28
      3562283.32     10292265.19
#Sta/Elev= 30
  4773.3  313.94  4844.4  314.04  4864.5  317.94  4874.6  318.38  4885.3  316.66
  4925.1  306.87  4945.2  302.84  4965.4  299.46  4975.5  299.29  4985.6     298
  4995.7  294.23  5002.8  292.91  5005.5  292.41  5008.8  292.91  5015.9  297.58
    5026  300.34  5031.5   300.6  5076.4  299.83  5096.6  300.17  5109.7  299.85
  5167.2  301.03  5244.8  306.25  5268.3  307.02  5338.9  311.69  5395.8  315.92
  5431.3   317.5  5447.6   318.9  5452.7  318.41  5461.8  318.71  5493.6  320.43
#Mann= 3 ,-1 , 0
  4773.3     .16       0  4985.6     .07       0  5015.9     .16       0
Bank Sta=5002.8,5008.8
XS Rating Curve= 0 ,0
Exp/Cntr=0.3,0.1

Type RM Length L Ch R = 1 ,1815    ,682,682,682
BEGIN DESCRIPTION:
FERRILL BRANCH TRIBUTARY 1 4.0
END DESCRIPTION:
XS GIS Cut Line= 3
      3561606.08     10292532.41      3561856.08     10292582.41
      3562258.52     10292632.58
#Sta/Elev= 30
  4738.6  311.58  4795.7   307.6  4826.3     307  4907.9  301.18  4913.1  299.97
  4918.2  300.32  4928.3  299.39  4948.7  294.59  4964.1  293.41  4969.2  294.49
  4979.3   292.2  4993.6  290.83  4996.6  289.81  4999.4  289.31  5002.6  289.81
  5019.8  292.09  5026.3  293.15    5050  293.55  5090.3   298.7    5107  300.05
  5112.1  299.73  5130.6  302.02  5170.9  304.26  5187.8  305.99  5192.8  305.71
  5268.5   313.4  5273.5  313.18    5312  317.06  5372.5  320.46  5399.1  323.28
#Mann= 3 ,-1 , 0
  4738.6      .1       0  4979.3     .05       0  5019.8      .1       0
Bank Sta=4996.6,5002.6
XS Rating Curve= 0 ,0
Exp/Cntr=0.3,0.1

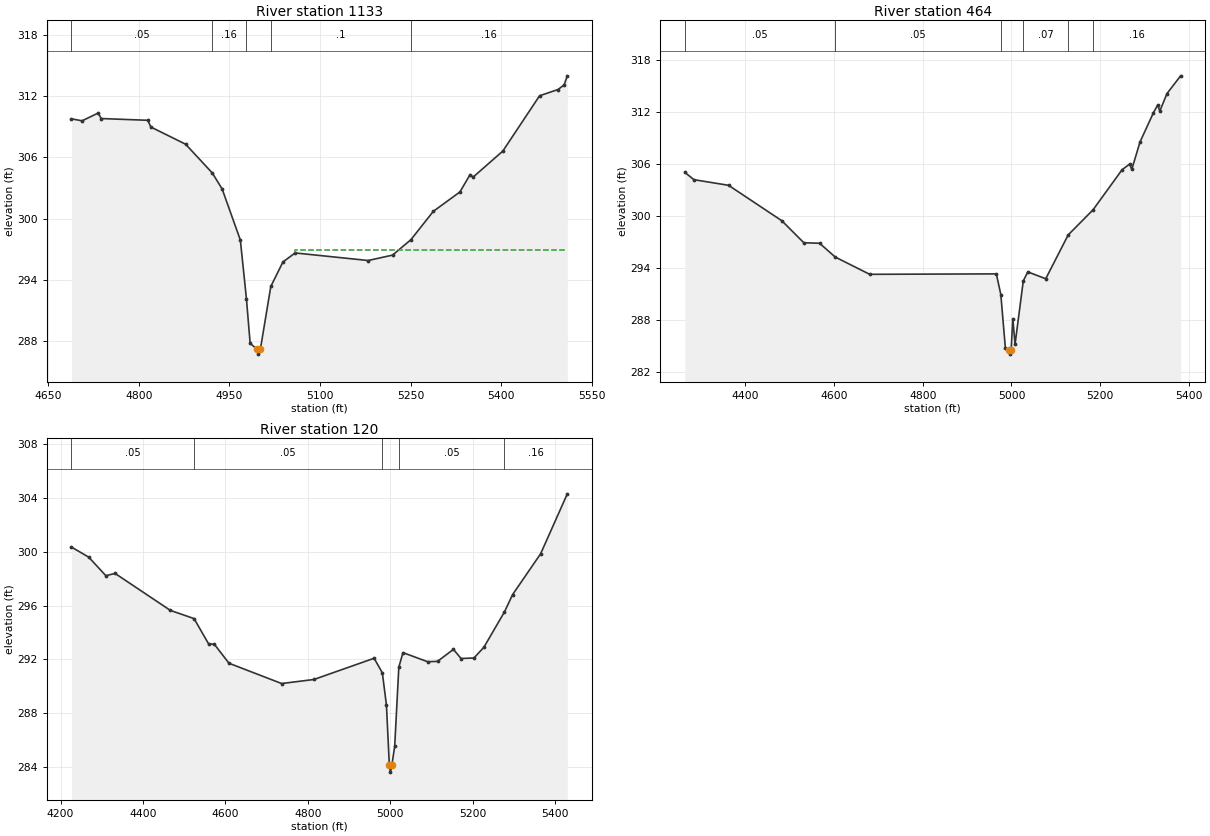
Type RM Length L Ch R = 1 ,1133    ,669,669,669
BEGIN DESCRIPTION:
FERRILL BRANCH TRIBUTARY 1 2.0
END DESCRIPTION:
XS GIS Cut Line= 3
      3561274.58      10292961.2      3561787.61     10293022.92
      3562087.34     10293072.88
#Sta/Elev= 30
  4688.5  309.76  4706.2  309.57  4732.7  310.33  4737.7  309.79  4814.8  309.62
  4819.9  308.96  4877.4  307.28  4921.5  304.47  4937.8  302.91    4968   297.9
  4978.1  292.14  4984.2   287.8  4995.2  287.24    4998  286.74  5001.2  287.24
  5018.4  293.36  5038.5  295.76  5058.7  296.64  5179.5   295.9  5219.9  296.43
  5250.3  297.94  5287.3  300.71  5331.4  302.61  5348.1   304.3  5353.2  304.06
  5402.4  306.61  5463.2  312.02  5493.7  312.63  5503.8  313.08  5509.1  313.97
#Mann= 5 ,-1 , 0
  4688.5     .05       0  4921.5     .16       0  4978.1     .04       0
  5018.4      .1       0  5250.3     .16       0
#XS Ineff= 2 , 0
                         5058.58          296.89
Permanent Ineff=
       F       F
Bank Sta=4995.2,5001.2
XS Rating Curve= 0 ,0
Exp/Cntr=0.3,0.1

Type RM Length L Ch R = 1 ,464     ,344,344,344
BEGIN DESCRIPTION:
FERRILL BRANCH TRIBUTARY 1 1.0
END DESCRIPTION:
XS GIS Cut Line= 3
      3561149.42     10293055.04      3561463.66     10293349.46
      3562142.56     10293453.87
#Sta/Elev= 30
  4263.7     305  4284.3  304.15  4362.4   303.5  4482.6  299.41    4532  296.88
  4567.6  296.82  4602.8  295.23  4680.5  293.24  4965.9  293.29    4976  290.91
  4986.2  284.76  4993.3  284.54    4996  284.04  4999.3  284.54    5003  288.13
  5008.1  285.19  5026.6  292.47  5036.7  293.52  5077.2  292.73  5127.8  297.78
  5183.9  300.68  5249.2  305.29  5266.1  305.94  5271.2  305.34  5289.7   308.5
    5320  311.87  5329.4  312.75  5334.4  312.07  5350.4  314.07  5381.2  316.12
#Mann= 6 ,-1 , 0
  4263.7     .05       0  4602.8     .05       0    4976    .035       0
  5026.6     .07       0  5127.8      .1       0  5183.9     .16       0
Bank Sta=4993.3,4999.3
XS Rating Curve= 0 ,0
Exp/Cntr=0.3,0.1

Type RM Length L Ch R = 1 ,120     ,0,0,0
BEGIN DESCRIPTION:
FERRILL BRANCH TRIBUTARY 1 1.0111
END DESCRIPTION:
XS GIS Cut Line= 4
      3560988.41     10293167.13      3561507.08     10293590.31
      3561719.75     10293588.14       3562023.6     10293483.96
#Sta/Elev= 30
  4226.4  300.36  4268.3  299.61  4309.9  298.23  4332.2   298.4  4466.4  295.65
  4523.9  295.04    4559  293.17  4573.4  293.12  4608.6  291.72  4736.4  290.21
  4814.7  290.51  4960.8  292.09  4980.8  291.01  4990.8   288.6  4997.8  284.12
  5000.6  283.62  5003.8  284.12  5010.8  285.54  5020.8  291.42  5030.8  292.51
  5090.8  291.83  5114.7  291.86  5153.3  292.75  5171.9  292.07  5203.2  292.11
  5227.3  292.91  5277.2  295.54    5297  296.83  5364.9  299.86  5429.7  304.32
#Mann= 5 ,-1 , 0
  4226.4     .05       0  4523.9     .05       0  4980.8     .03       0
  5020.8     .05       0  5277.2     .16       0
Bank Sta=4997.8,5003.8
XS Rating Curve= 0 ,0
Exp/Cntr=0.3,0.1

Chan Stop Cuts=-1
Use User Specified Reach Order=0
Composite Channel Slope=5