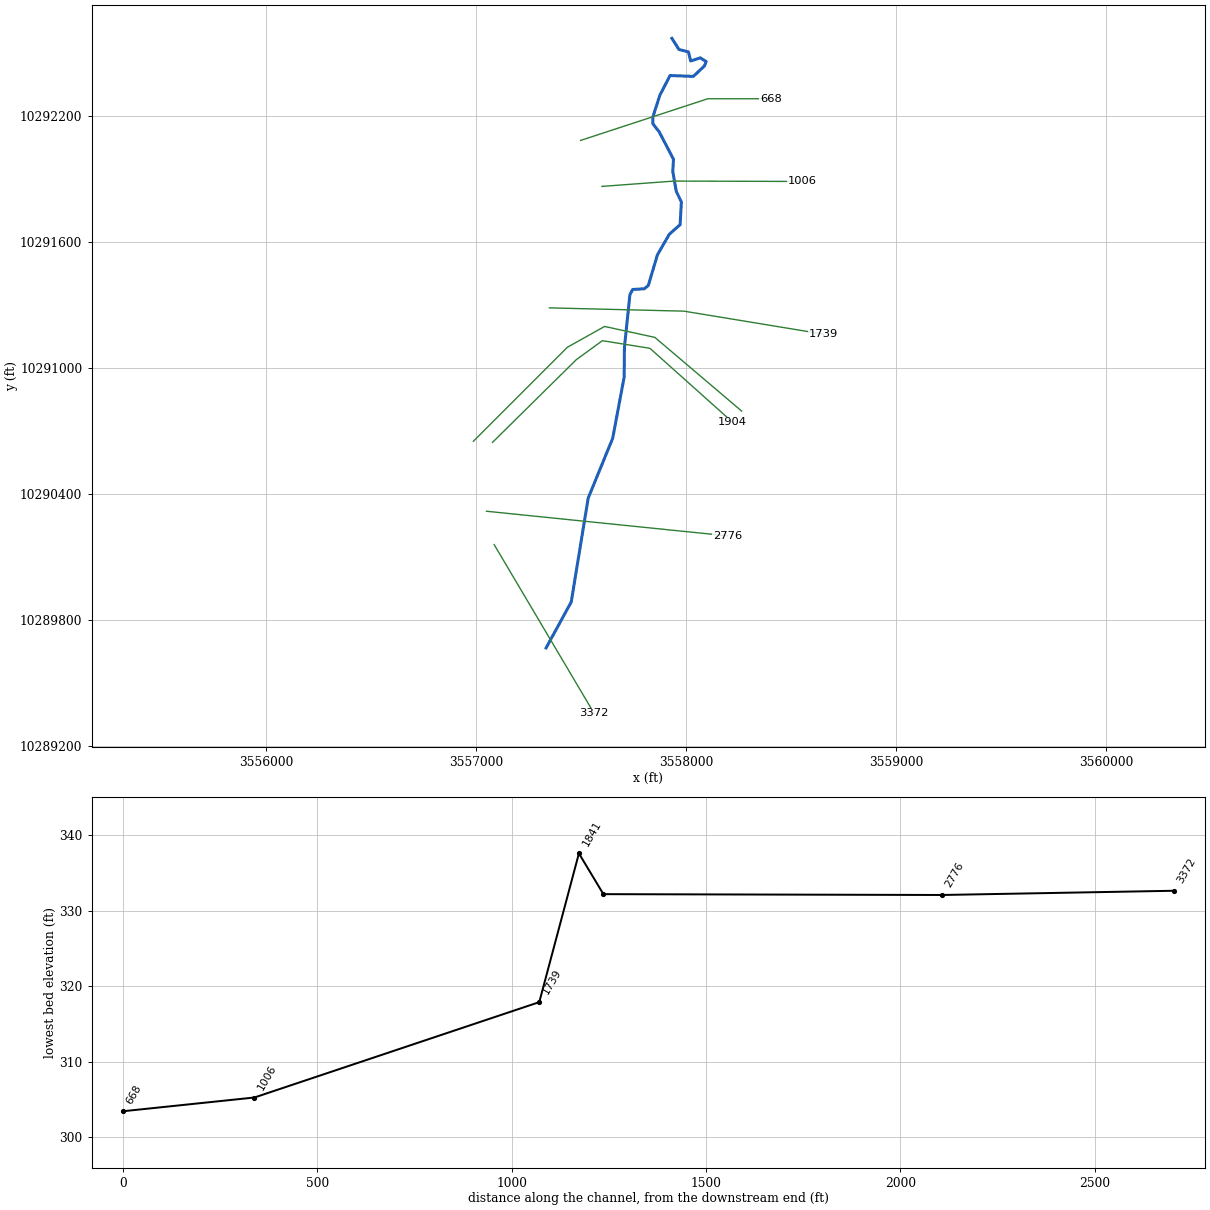
--- FERRILL BRANCH TRIBUTARY 3.prj (project) ---

Proj Title=FERRILL BRANCH TRIBUTARY 3 Base Level Engineering
Current Plan=p01
Default Exp/Contr=0.3,0.1
English Units
Geom File=g01
Flow File=f01
Plan File=p01
Y Axis Title=Elevation
X Axis Title(PF)=Main Channel Distance
X Axis Title(XS)=Station
BEGIN DESCRIPTION:
FERRILL BRANCH TRIBUTARY 3
END DESCRIPTION:
DSS Export Rating Curves= 0
DSS Export Rating Curve Sorted= 0
DSS Export Volume Flow Curves= 0
DXF OffsetX= 0
DXF OffsetY= 0
DXF ScaleX= 1
DXF ScaleY= 10

--- FERRILL BRANCH TRIBUTARY 3.p01 (plan) ---

Plan Title=Multiple Run
Short Identifier=Multiple
Geom File=g01
Flow File=f01
Subcritical Flow
K Sum by GR= 0
Std Step Tol= 0.01
Critical Tol= 0.01
Num of Std Step Trials= 20
Max Error Tol= 0.3
Flow Tol Ratio= 0.001
Split Flow NTrial= 30
Split Flow Tol= 0.02
Split Flow Ratio= 0.02
Log Output Level= 0
Friction Slope Method= 1
Unsteady Friction Slope Method= 2
Unsteady Bridges Friction Slope Method= 1
Parabolic Critical Depth
Global Vel Dist=  1 , 1 , 1
Global Log Level= 0
CheckData=True
Encroach Param= -1, 0, 0, 0
BEGIN DESCRIPTION:
Multiple Run
END DESCRIPTION:

--- FERRILL BRANCH TRIBUTARY 3.f01 (steady flow) ---

Flow Title=Multiple
Number of Profiles=7
Profile Names=10-year,25-year,50-year,1pct_min,100-year,1pct_plu,500-year
River Rch & RM= FERRILL BRANCH T,Reach-1,3372
     379     500     597     523     707     957     994
Boundary for River Rch & Prof#=FERRILL BRANCH T,Reach-1,1
Up Type=0
Dn Type=3
Dn Slope=0.005
Boundary for River Rch & Prof#=FERRILL BRANCH T,Reach-1,2
Up Type=0
Dn Type=3
Dn Slope=0.005
Boundary for River Rch & Prof#=FERRILL BRANCH T,Reach-1,3
Up Type=0
Dn Type=3
Dn Slope=0.005
Boundary for River Rch & Prof#=FERRILL BRANCH T,Reach-1,4
Up Type=0
Dn Type=3
Dn Slope=0.005
Boundary for River Rch & Prof#=FERRILL BRANCH T,Reach-1,5
Up Type=0
Dn Type=3
Dn Slope=0.005
Boundary for River Rch & Prof#=FERRILL BRANCH T,Reach-1,6
Up Type=0
Dn Type=3
Dn Slope=0.005
Boundary for River Rch & Prof#=FERRILL BRANCH T,Reach-1,7
Up Type=0
Dn Type=3
Dn Slope=0.005

--- FERRILL BRANCH TRIBUTARY 3.g01 (geometry) ---

Geom Title=Existing Conditions
Program Version=4.10

River Reach=FERRILL BRANCH T,Reach-1
Reach XY= 30
      3557332.88     10289667.84      3557452.68     10289886.59
      3557533.41     10290381.38      3557650.13     10290666.11
      3557704.81     10290957.78      3557706.12     10291099.71
      3557732.16     10291350.05      3557745.18     10291375.23
      3557800.73      10291378.7      3557819.83     10291394.32
      3557863.23     10291540.16      3557919.83     10291638.25
      3557971.39     10291684.08      3557977.33     10291792.84
      3557953.26     10291841.66      3557936.45     10291936.74
      3557939.77     10291995.57      3557871.44      10292126.5
      3557841.28     10292165.07      3557841.58     10292196.58
       3557874.8     10292300.55      3557923.41     10292394.43
      3558034.51     10292390.35      3558087.41      10292440.4
      3558095.49     10292461.12      3558067.35     10292478.68
      3558021.54     10292463.77      3558011.12       10292507.
      3557965.81     10292518.46      3557932.11     10292571.64

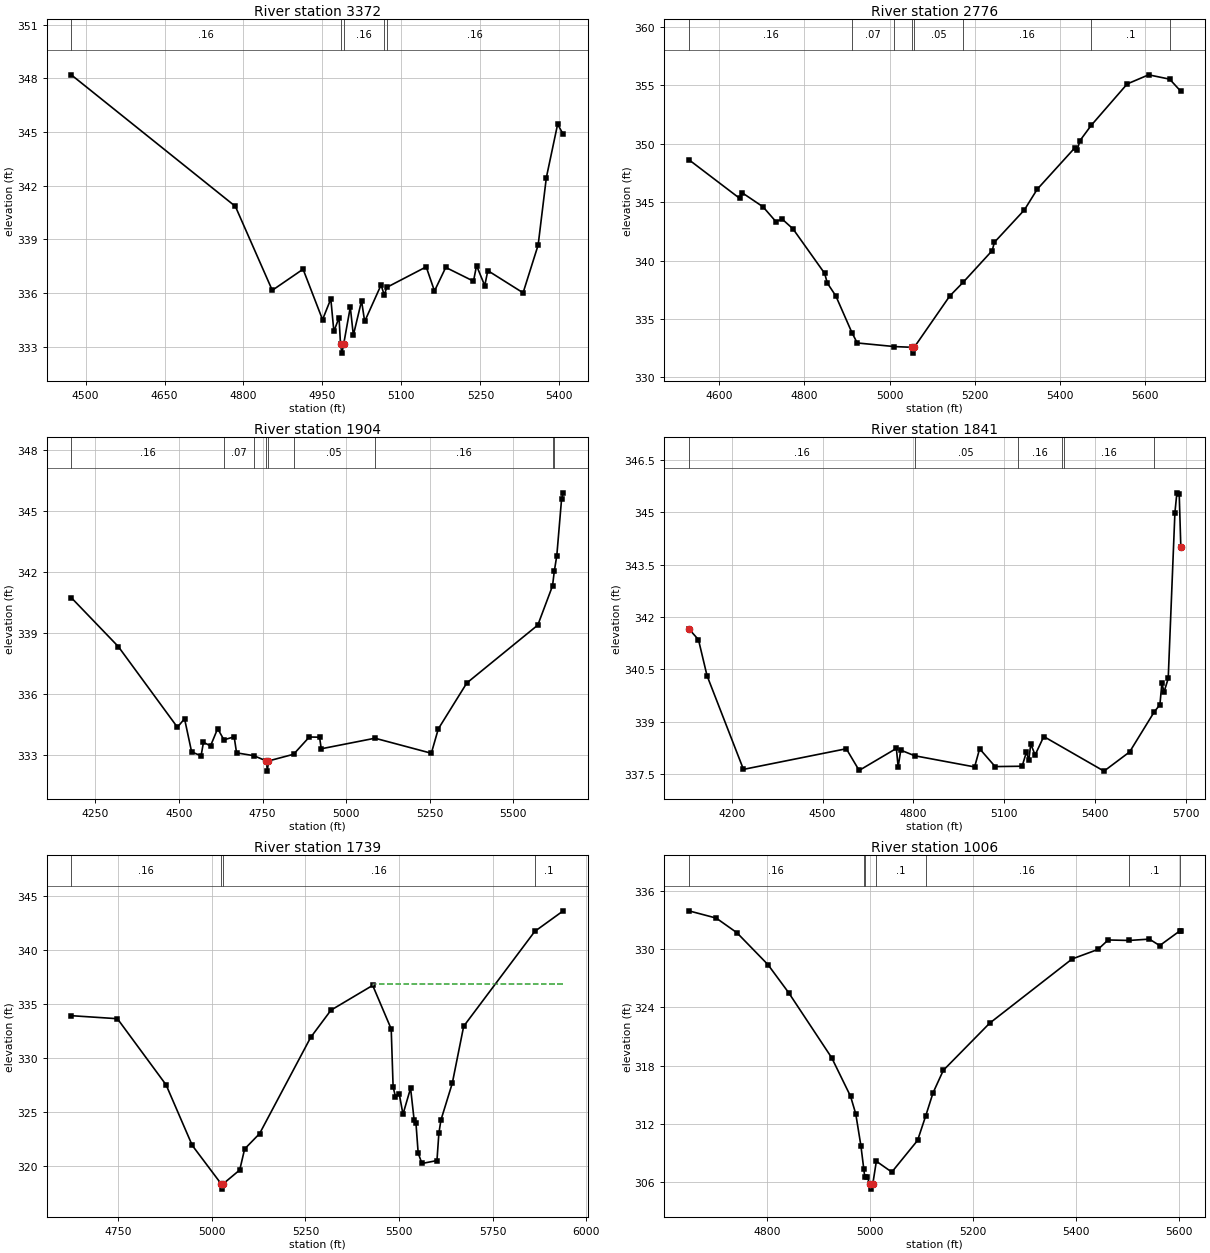
Type RM Length L Ch R = 1 ,3372    ,596,596,596
BEGIN DESCRIPTION:
FERRILL BRANCH TRIBUTARY 3 5.0
END DESCRIPTION:
XS GIS Cut Line= 2
      3557085.47     10290160.06      3557561.67     10289355.99
#Sta/Elev= 30
  4472.9  348.19  4784.6  340.84  4854.7  336.15  4913.2  337.33  4950.2  334.51
  4965.9  335.67  4971.7  333.85  4981.5  334.63  4984.3  333.14    4987  332.64
  4990.3  333.14  5002.9  335.21  5008.7  333.64  5024.3  335.56  5030.2  334.41
  5061.4  336.45  5067.5  335.87  5071.9  336.31  5147.1  337.46  5162.8  336.11
  5184.2  337.43  5236.9  336.66  5242.7  337.53  5258.3  336.41  5264.1  337.25
  5331.1  336.01  5359.7  338.68  5375.3  342.45  5396.7  345.43  5407.4  344.86
#Mann= 5 ,-1 , 0
  4472.9     .16       0  4984.3     .07       0  4990.3     .16       0
  5067.5      .1       0  5071.9     .16       0
Bank Sta=4984.3,4990.3
XS Rating Curve= 0 ,0
Exp/Cntr=0.3,0.1

Type RM Length L Ch R = 1 ,2776    ,872,872,872
BEGIN DESCRIPTION:
FERRILL BRANCH TRIBUTARY 3 5.01
END DESCRIPTION:
XS GIS Cut Line= 2
      3557049.01     10290318.88      3558197.25     10290201.72
#Sta/Elev= 30
  4529.2  348.63  4648.9  345.31  4653.9  345.81  4703.2   344.6  4733.3  343.34
  4748.4  343.54  4773.6  342.71  4847.9   338.9    4854  338.08  4874.1  336.97
    4912  333.82  4924.3  332.95  5011.7  332.64    5052  332.58  5054.8  332.08
    5058  332.58  5141.4  336.97  5172.5  338.13  5240.9  340.85    5246  341.56
  5316.4  344.33  5346.5   346.1  5434.9  349.65  5439.9  349.45    5447  350.27
  5473.5  351.58  5557.6  355.11  5607.9  355.89  5657.2  355.52  5683.4  354.48
#Mann= 8 ,-1 , 0
  4529.2     .16       0    4912     .07       0  5011.7     .05       0
    5052     .07       0    5058     .05       0  5172.5     .16       0
  5473.5      .1       0  5657.2     .16       0
Bank Sta=5052,5058
XS Rating Curve= 0 ,0
Exp/Cntr=0.3,0.1

Type RM Length L Ch R = 1 ,1904    ,63,63,63
BEGIN DESCRIPTION:
FERRILL BRANCH TRIBUTARY 3 5.01111
END DESCRIPTION:
XS GIS Cut Line= 5
      3557077.67       10290647.      3557476.11     10291040.24
      3557601.11     10291131.38      3557827.68     10291094.92
      3558220.93     10290743.34
#Sta/Elev= 30
  4177.6  340.73  4318.4  338.32  4495.1  334.35  4516.4  334.77  4537.5  333.14
  4565.8  332.94    4573  333.61  4594.1  333.43  4615.4  334.28  4634.3  333.73
  4664.8  333.88    4672  333.09  4723.6  332.95  4761.3  332.69  4764.1  332.19
  4767.3  332.69  4842.5  333.02  4889.6  333.87  4920.2  333.86  4925.3  333.29
    5086  333.81  5254.5  333.07  5275.4  334.27  5360.7  336.53    5573  339.38
    5617  341.31  5622.3  342.03  5629.8   342.8  5644.1  345.59  5649.1  345.89
#Mann= 9 ,-1 , 0
  4177.6     .16       0  4634.3     .07       0  4723.6     .16       0
  4761.3    .035       0  4767.3     .16       0  4842.5     .05       0
    5086     .16       0    5617      .1       0  5622.3     .16       0
Bank Sta=4761.3,4767.3
XS Rating Curve= 0 ,0
Exp/Cntr=0.3,0.1

Type RM Length L Ch R = 1 ,1841    ,102,102,102
BEGIN DESCRIPTION:
FERRILL BRANCH TRIBUTARY 3 5.011
END DESCRIPTION:
XS GIS Cut Line= 5
      3556986.54     10290652.22      3557434.45     10291100.13
      3557611.53     10291199.09      3557851.11     10291147.01
      3558264.45     10290796.07
#Sta/Elev= 30
  4058.7  341.66  4090.5  341.35  4118.8  340.32    4239  337.64  4578.4  338.23
  4620.8  337.61  4743.7  338.24  4749.5  337.71  4758.2  338.19    4804  338.03
  5001.9  337.71  5018.4  338.23  5069.6  337.72  5158.7  337.73    5173  338.14
  5180.7   337.9  5187.2  338.37  5201.5  338.05  5230.1  338.58  5428.9  337.59
  5513.5  338.14  5594.4  339.28  5613.4  339.49    5620  340.11  5626.9  339.85
  5640.8  340.24  5662.9  344.98  5669.4  345.55  5677.1  345.52  5682.4     344
#Mann= 6 ,-1 , 0
  4058.7     .16       0    4804     .05       0  5144.7     .16       0
  5290.8    .035       0  5296.8     .16       0  5594.4      .1       0
Bank Sta=4058.7,5682.4
XS Rating Curve= 0 ,0
Exp/Cntr=0.3,0.1

Type RM Length L Ch R = 1 ,1739    ,733,733,733
BEGIN DESCRIPTION:
FERRILL BRANCH TRIBUTARY 3 4.0
END DESCRIPTION:
XS GIS Cut Line= 3
      3557348.83     10291287.67      3557990.05     10291272.03
      3558654.78     10291162.54
#Sta/Elev= 30
    4624  333.91  4747.3  333.63  4877.4  327.52  4947.4  321.92  5024.4  318.38
  5027.1  317.88  5030.4  318.38  5074.3  319.65  5087.4  321.59  5127.4  323.01
  5263.9   331.9  5318.2  334.42  5429.7  336.71  5479.2  332.68  5484.3  327.33
  5490.5  326.44  5500.6  326.69  5510.7   324.8    5531  327.21  5540.4  324.29
  5545.4  323.97  5551.3  321.21  5561.4  320.25  5601.5  320.52  5606.6  323.03
  5612.1  324.26  5642.5  327.67  5672.9  332.93    5863   341.7  5939.1   343.6
#Mann= 4 ,-1 , 0
    4624     .16       0  5024.4     .07       0  5030.4     .16       0
    5863      .1       0
#XS Ineff= 2 , 0
                         5430.45          336.81
Permanent Ineff=
       F       F
Bank Sta=5024.4,5030.4
XS Rating Curve= 0 ,0
Exp/Cntr=0.3,0.1

Type RM Length L Ch R = 1 ,1006    ,338,338,338
BEGIN DESCRIPTION:
FERRILL BRANCH TRIBUTARY 3 2.0
END DESCRIPTION:
XS GIS Cut Line= 3
      3557599.02     10291866.36      3557942.11     10291891.64
      3558553.09     10291889.83
#Sta/Elev= 30
  4647.8  333.98    4701  333.23  4741.1  331.72  4801.3  328.43  4841.4  325.54
  4925.2   318.8  4961.7  314.83  4971.8  313.02  4981.8  309.73  4987.5  307.28
  4989.3  306.51  4994.3  306.51  4998.8  305.74  5001.6  305.24  5004.8  305.74
  5011.8  308.12  5041.8     307  5091.8  310.27  5107.3  312.75  5121.8  315.18
  5141.8  317.51  5231.8  322.38  5391.8  329.01  5441.8  329.99  5461.8  330.97
  5502.4  330.92  5541.8  331.06  5561.8  330.39  5601.2  331.92  5602.8  331.92
#Mann= 7 ,-1 , 0
  4647.8     .16       0  4987.5     .12       0  4989.3     .05       0
  5011.8      .1       0  5107.3     .16       0  5502.4      .1       0
  5601.2     .05       0
Bank Sta=4998.8,5004.8
XS Rating Curve= 0 ,0
Exp/Cntr=0.3,0.1

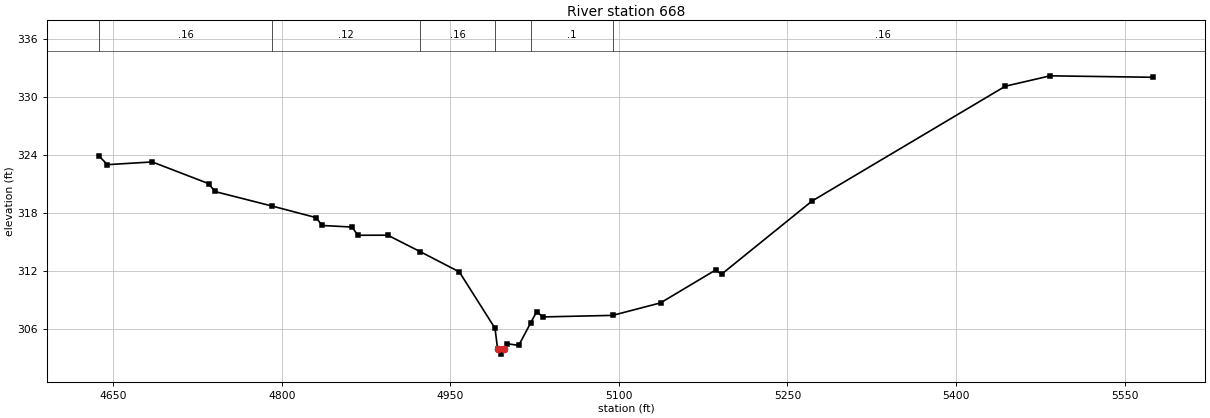
Type RM Length L Ch R = 1 ,668     ,0,0,0
BEGIN DESCRIPTION:
FERRILL BRANCH TRIBUTARY 3 1.0
END DESCRIPTION:
XS GIS Cut Line= 3
      3557497.39     10292085.34      3558103.25     10292283.82
       3558403.3     10292283.82
#Sta/Elev= 30
  4637.5  323.83  4644.7  322.98  4684.6  323.26    4735  321.01  4740.2  320.21
  4791.5   318.7  4830.5  317.51  4835.8   316.7  4862.4  316.54  4867.6  315.69
  4894.2   315.7  4922.9  314.01  4957.9  311.91  4989.7  306.08    4992  303.92
  4994.8  303.42    4998  303.92  5000.3   304.5  5010.8  304.32  5021.3  306.62
  5026.8  307.82  5032.1  307.26  5094.3  307.42    5137  308.71  5186.1  312.11
  5191.3  311.67  5271.8  319.22  5443.9  331.08  5483.9  332.15  5575.1     332
#Mann= 6 ,-1 , 0
  4637.5     .16       0  4791.5     .12       0  4922.9     .16       0
  4989.7     .05       0  5021.3      .1       0  5094.3     .16       0
Bank Sta=4992,4998
XS Rating Curve= 0 ,0
Exp/Cntr=0.3,0.1

Chan Stop Cuts=-1
Use User Specified Reach Order=0
Composite Channel Slope=5