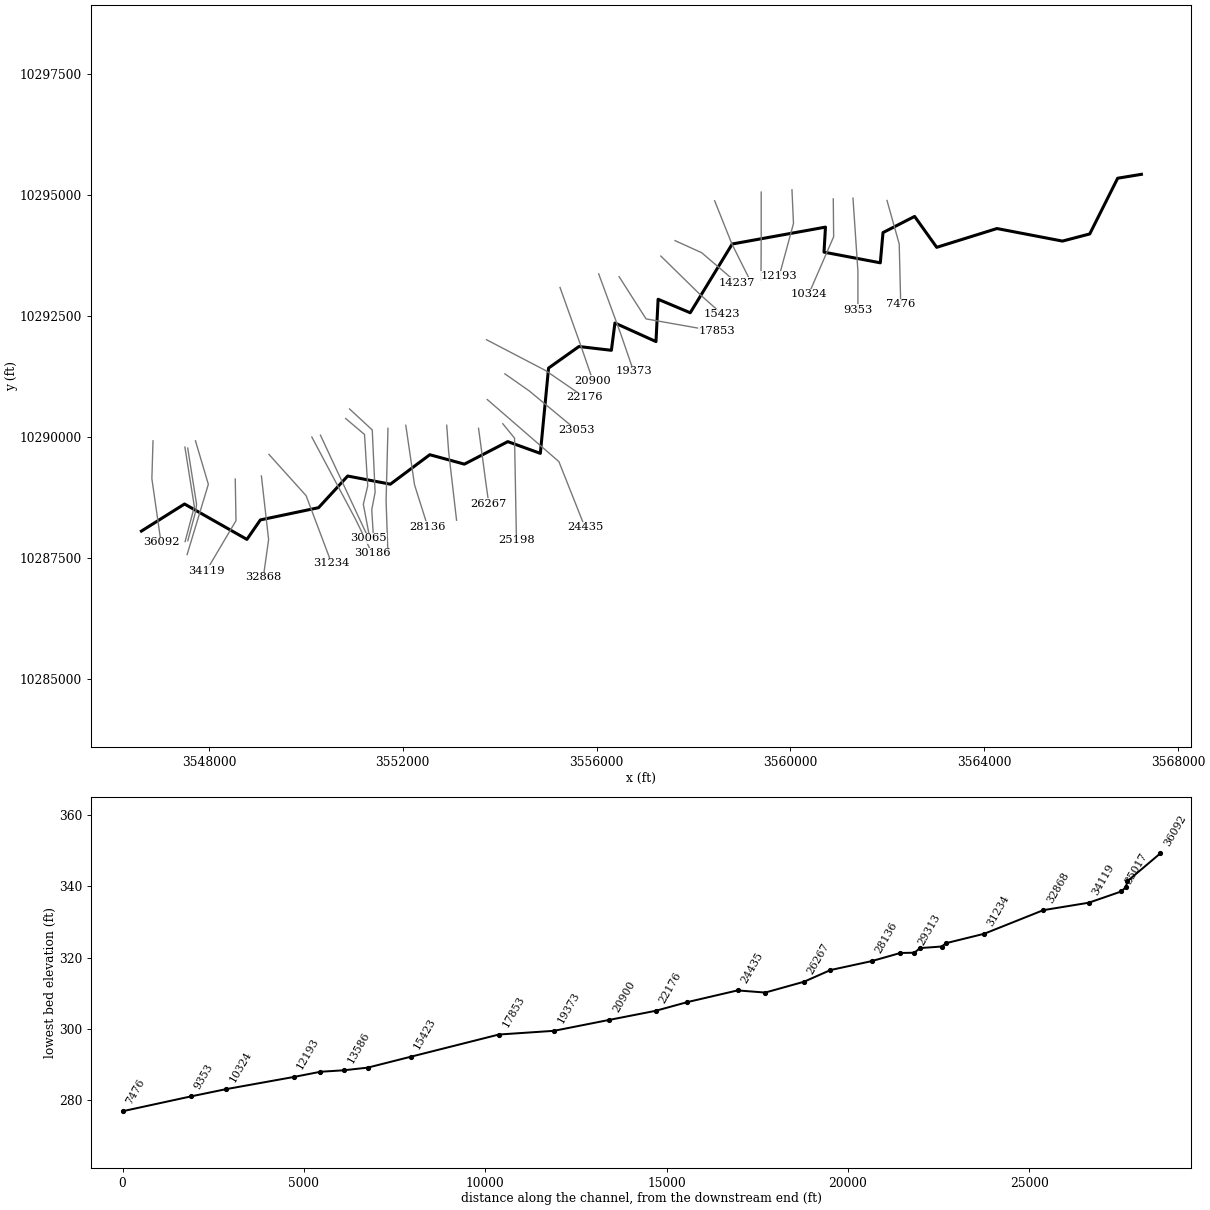
--- FERRILL BRANCH.prj (project) ---

Proj Title=FERRILL BRANCH Base Level Engineering
Current Plan=p01
Default Exp/Contr=0.3,0.1
English Units
Geom File=g01
Flow File=f01
Plan File=p01
Y Axis Title=Elevation
X Axis Title(PF)=Main Channel Distance
X Axis Title(XS)=Station
BEGIN DESCRIPTION:
FERRILL BRANCH
END DESCRIPTION:
DSS Export Rating Curves= 0
DSS Export Rating Curve Sorted= 0
DSS Export Volume Flow Curves= 0
DXF OffsetX= 0
DXF OffsetY= 0
DXF ScaleX= 1
DXF ScaleY= 10

--- FERRILL BRANCH.p01 (plan) ---

Plan Title=Multiple Run
Short Identifier=Multiple
Geom File=g01
Flow File=f01
Subcritical Flow
K Sum by GR= 0
Std Step Tol= 0.01
Critical Tol= 0.01
Num of Std Step Trials= 20
Max Error Tol= 0.3
Flow Tol Ratio= 0.001
Split Flow NTrial= 30
Split Flow Tol= 0.02
Split Flow Ratio= 0.02
Log Output Level= 0
Friction Slope Method= 1
Unsteady Friction Slope Method= 2
Unsteady Bridges Friction Slope Method= 1
Parabolic Critical Depth
Global Vel Dist=  1 , 1 , 1
Global Log Level= 0
CheckData=True
Encroach Param= -1, 0, 0, 0
BEGIN DESCRIPTION:
Multiple Run
END DESCRIPTION:

--- FERRILL BRANCH.f01 (steady flow) ---

Flow Title=Multiple
Program Version=4.10
Number of Profiles= 7
Profile Names=10-year,25-year,50-year,1pct_min,100-year,1pct_plu,500-year
River Rch & RM=FERRILL BRANCH,Reach-1         ,36092
     181     226     260     220     298     403     391
River Rch & RM=FERRILL BRANCH,Reach-1         ,35017
     664     901    1096     975    1319    1784    1917
River Rch & RM=FERRILL BRANCH,Reach-1         ,31234
     835    1148    1407    1263    1708    2309    2521
River Rch & RM=FERRILL BRANCH,Reach-1         ,28924
     987    1361    1670    1499    2027    2742    2996
River Rch & RM=FERRILL BRANCH,Reach-1         ,24435
    1139    1580    1947    1753    2371    3206    3527
River Rch & RM=FERRILL BRANCH,Reach-1         ,20900
    1284    1785    2203    1985    2685    3631    4000
River Rch & RM=FERRILL BRANCH,Reach-1         ,17853
    1469    2049    2535    2288    3094    4185    4626
River Rch & RM=FERRILL BRANCH,Reach-1         ,15423
    1469    2049    2535    2288    3094    4185    4626
River Rch & RM=FERRILL BRANCH,Reach-1         ,7476
    1790    2521    3139    2851    3855    5214    5835
Boundary for River Rch & Prof#=FERRILL BRANCH,Reach-1         , 1
Up Type= 0
Dn Type= 3
Dn Slope=0.005
Boundary for River Rch & Prof#=FERRILL BRANCH,Reach-1         , 2
Up Type= 0
Dn Type= 3
Dn Slope=0.005
Boundary for River Rch & Prof#=FERRILL BRANCH,Reach-1         , 3
Up Type= 0
Dn Type= 3
Dn Slope=0.005
Boundary for River Rch & Prof#=FERRILL BRANCH,Reach-1         , 4
Up Type= 0
Dn Type= 3
Dn Slope=0.005
Boundary for River Rch & Prof#=FERRILL BRANCH,Reach-1         , 5
Up Type= 0
Dn Type= 3
Dn Slope=0.005
Boundary for River Rch & Prof#=FERRILL BRANCH,Reach-1         , 6
Up Type= 0
Dn Type= 3
Dn Slope=0.005
Boundary for River Rch & Prof#=FERRILL BRANCH,Reach-1         , 7
Up Type= 0
Dn Type= 3
Dn Slope=0.005
DSS Import GetInterval= 0
DSS Import GetPeak= 0
DSS Import FillOption= 0

--- FERRILL BRANCH.g01 (geometry) ---

Geom Title=Existing Conditions
Program Version=4.10

River Reach=FERRILL BRANCH  ,Reach-1
Reach XY= 30
      3546606.99     10288061.72      3547496.81      10288621.2
      3548784.04     10287890.08      3549061.47     10288292.51
      3550262.51     10288545.29      3550863.19     10289198.97
      3551743.87     10289030.74      3552557.84     10289639.32
      3553271.16     10289444.81      3554167.45     10289909.67
      3554838.84     10289667.19      3555008.36     10291428.83
      3555635.48      10291874.5       3556305.2     10291796.22
      3556377.87     10292359.88      3557225.16     10291976.41
      3557269.03     10292850.71      3557932.11     10292571.64
      3558797.98      10293992.1      3560722.61     10294341.02
      3560692.28     10293823.75      3561854.04     10293603.53
      3561909.87     10294228.06      3562562.16     10294561.62
      3563017.85     10293923.38      3564261.06     10294311.71
      3565612.68     10294052.37       3566175.9     10294200.25
      3566752.13     10295351.09      3567242.11     10295431.64

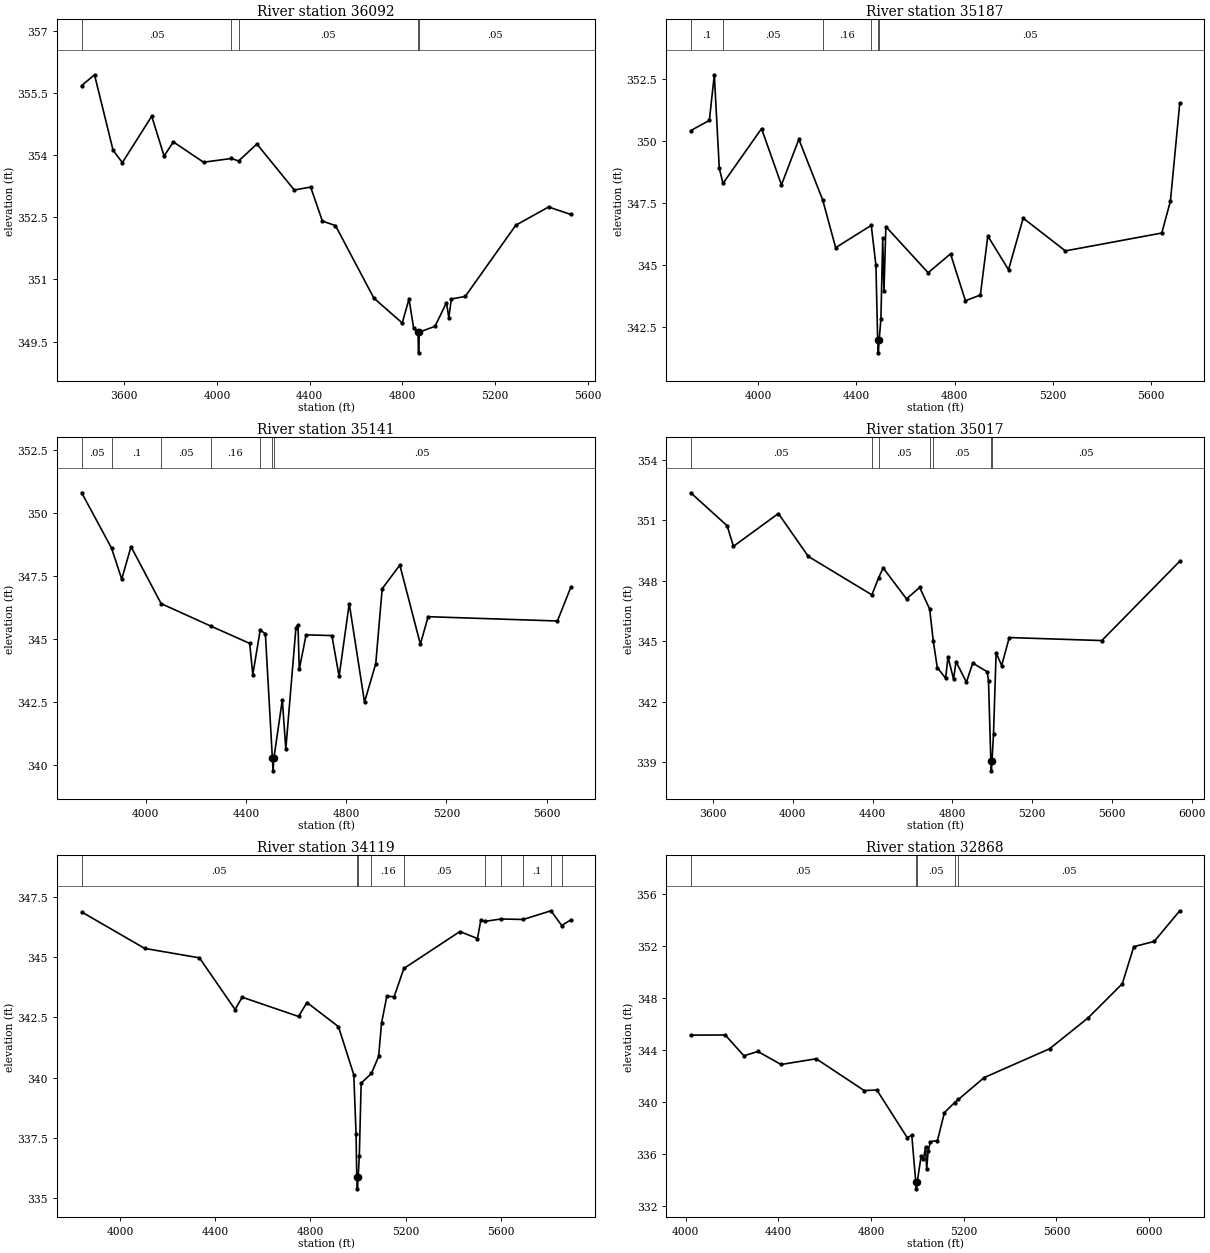
Type RM Length L Ch R = 1 ,36092   ,905,905,905
BEGIN DESCRIPTION:
FERRILL BRANCH 56.0
END DESCRIPTION:
XS GIS Cut Line= 3
      3546846.22     10289926.99      3546822.76     10289144.93
      3547010.44     10287831.18
#Sta/Elev= 30
  3416.3  355.68  3471.7  355.94  3551.7  354.12  3591.7  353.82  3718.5  354.94
  3771.8  353.98  3811.8  354.32  3941.9  353.83  4061.9  353.92  4093.3  353.86
    4172  354.27  4333.3  353.16  4404.1  353.23  4454.6  352.41  4511.2   352.3
  4676.8  350.55  4799.1  349.95  4828.3  350.53  4848.5  349.82  4866.8  349.73
  4869.6  349.23  4872.8  349.73  4940.5  349.87  4989.9  350.44    5000  350.08
  5011.2  350.53  5070.8  350.59    5289  352.31  5430.4  352.75  5525.8  352.57
#Mann= 5 ,-1 , 0
  3416.3     .05       0  4061.9      .1       0  4093.3     .05       0
  4866.8     .03       0  4872.8     .05       0
Bank Sta=4866.8,4872.8
XS Rating Curve= 0 ,0
Exp/Cntr=0.3,0.1

Type RM Length L Ch R = 1 ,35187   ,46,46,46
BEGIN DESCRIPTION:
Mapping XS 4c6237ee
END DESCRIPTION:
XS GIS Cut Line= 3
      3547503.95     10289796.49      3547699.26     10288568.23
      3547508.71       10287845.
#Sta/Elev= 30
  3725.4  350.42  3801.2  350.83  3821.4  352.67  3841.7   348.9  3856.7  348.29
  4013.8   350.5  4094.8  348.23  4165.7  350.07  4262.9  347.62  4315.6   345.7
  4460.6   346.6  4479.6  344.99  4486.7  341.96  4489.5  341.46  4492.7  341.96
  4499.9  342.83  4507.3  346.08  4512.3  343.94  4520.1  346.55  4692.2  344.69
  4783.4  345.45  4844.1  343.56  4904.9  343.79  4935.3  346.17  5019.6  344.81
  5079.3  346.89  5251.1  345.57  5643.8  346.29    5679  347.58    5717  351.53
#Mann= 6 ,-1 , 0
  3725.4      .1       0  3856.7     .05       0  4262.9     .16       0
  4460.6     .05       0  4486.7    .035       0  4492.7     .05       0
Bank Sta=4486.7,4492.7
XS Rating Curve= 0 ,0
Exp/Cntr=0.3,0.1

Type RM Length L Ch R = 1 ,35141   ,124,124,124
BEGIN DESCRIPTION:
Mapping XS 3a8e13ab
END DESCRIPTION:
XS GIS Cut Line= 4
      3547562.55     10289776.09      3547744.83     10288617.28
      3547731.81     10288491.41      3547564.44     10287862.08
#Sta/Elev= 30
    3745   350.8  3864.3   348.6  3904.7  347.37  3941.8  348.66  4061.9   346.4
  4259.5  345.51  4415.2  344.82  4427.7  343.58  4457.2  345.35  4477.8   345.2
  4505.7  340.26  4508.5  339.76  4511.7  340.26  4545.4  342.58  4559.3  340.63
  4599.8  345.45  4607.9  345.55    4613  343.79  4640.3  345.16  4743.1  345.13
  4771.9  343.51  4812.4   346.4  4873.3  342.49  4918.1  344.01  4943.8  346.99
  5014.2  347.93  5096.1  344.79  5127.1  345.88  5642.9  345.71  5695.8  347.04
#Mann= 7 ,-1 , 0
    3745     .05       0  3864.3      .1       0  4061.9     .05       0
  4259.5     .16       0  4457.2     .05       0  4505.7    .035       0
  4511.7     .05       0
Bank Sta=4505.7,4511.7
XS Rating Curve= 0 ,0
Exp/Cntr=0.3,0.1

Type RM Length L Ch R = 1 ,35017   ,898,898,898
BEGIN DESCRIPTION:
FERRILL BRANCH 55.0
END DESCRIPTION:
XS GIS Cut Line= 3
      3547722.08     10289926.96      3547987.97     10289027.62
      3547550.17     10287577.38
#Sta/Elev= 30
  3487.8  352.37  3670.6  350.73  3701.9  349.71  3927.4  351.34  4077.3  349.21
  4396.4   347.3  4430.3  348.15  4452.8  348.64    4570   347.1  4635.9  347.67
    4686   346.6  4704.4     345  4724.3  343.69  4766.1  343.16  4778.2  344.21
    4806  343.12  4818.4  343.98  4870.6  342.96  4901.9  343.91    4975  343.48
  4981.3  343.01  4992.9  339.06  4995.7  338.56  4998.9  339.06  5006.4  340.41
  5019.4  344.42  5047.2  343.79  5085.4  345.18  5549.6  345.03  5940.5  348.97
#Mann= 7 ,-1 , 0
  3487.8     .05       0  4396.4      .1       0  4430.3     .05       0
    4686     .16       0  4704.4     .05       0  4992.9    .035       0
  4998.9     .05       0
Bank Sta=4992.9,4998.9
XS Rating Curve= 0 ,0
Exp/Cntr=0.3,0.1

Type RM Length L Ch R = 1 ,34119   ,1251,1251,1251
BEGIN DESCRIPTION:
FERRILL BRANCH 54.0
END DESCRIPTION:
XS GIS Cut Line= 3
      3548543.21     10289137.13      3548558.85     10288276.88
      3547949.49     10287245.66
#Sta/Elev= 30
    3837  346.87  4102.5  345.36  4332.6  344.97  4482.6  342.83  4512.6  343.34
  4749.9  342.54    4785  343.12  4917.7  342.12  4982.2  340.13  4991.9  337.67
  4994.7   335.9  4997.4   335.4  5000.7   335.9  5005.5  336.75  5013.3  339.78
  5056.6  340.18  5086.8  340.89  5099.1  342.27  5121.6  343.39  5151.8  343.35
    5193  344.53  5428.8  346.06  5502.9  345.77  5516.6  346.52    5534  346.48
  5601.2  346.58  5695.3  346.56  5812.2  346.92  5857.3  346.31  5895.2  346.54
#Mann= 10 ,-1 , 0
    3837     .05       0  4994.7    .035       0  5000.7     .05       0
  5056.6     .16       0    5193     .05       0    5534      .1       0
  5601.2     .05       0  5695.3      .1       0  5812.2     .16       0
  5857.3      .1       0
Bank Sta=4994.7,5000.7
XS Rating Curve= 0 ,0
Exp/Cntr=0.3,0.1

Type RM Length L Ch R = 1 ,32868   ,1634,1634,1634
BEGIN DESCRIPTION:
FERRILL BRANCH 52.0
END DESCRIPTION:
XS GIS Cut Line= 3
      3549082.81     10289199.63      3549231.39     10287885.87
       3549122.1     10287105.22
#Sta/Elev= 30
  4021.9  345.15  4170.8  345.16  4251.3  343.56  4311.7  343.89  4411.7  342.89
  4563.3  343.33  4770.8  340.88    4825  340.93  4955.8  337.27  4975.9  337.43
  4993.1  333.82  4995.8  333.32  4999.1  333.82  5016.2  335.84  5026.3   335.6
  5035.1  336.52  5040.2  334.84  5046.4  336.23  5056.4  336.95  5086.6  337.04
  5116.8  339.19  5160.6  339.96  5177.1   340.2  5287.9  341.88  5570.5   344.1
  5736.3  346.47  5884.2   349.1    5934  351.96  6021.9  352.36  6132.3  354.72
#Mann= 5 ,-1 , 0
  4021.9     .05       0  4993.1    .035       0  4999.1     .05       0
  5160.6     .16       0  5177.1     .05       0
Bank Sta=4993.1,4999.1
XS Rating Curve= 0 ,0
Exp/Cntr=0.3,0.1

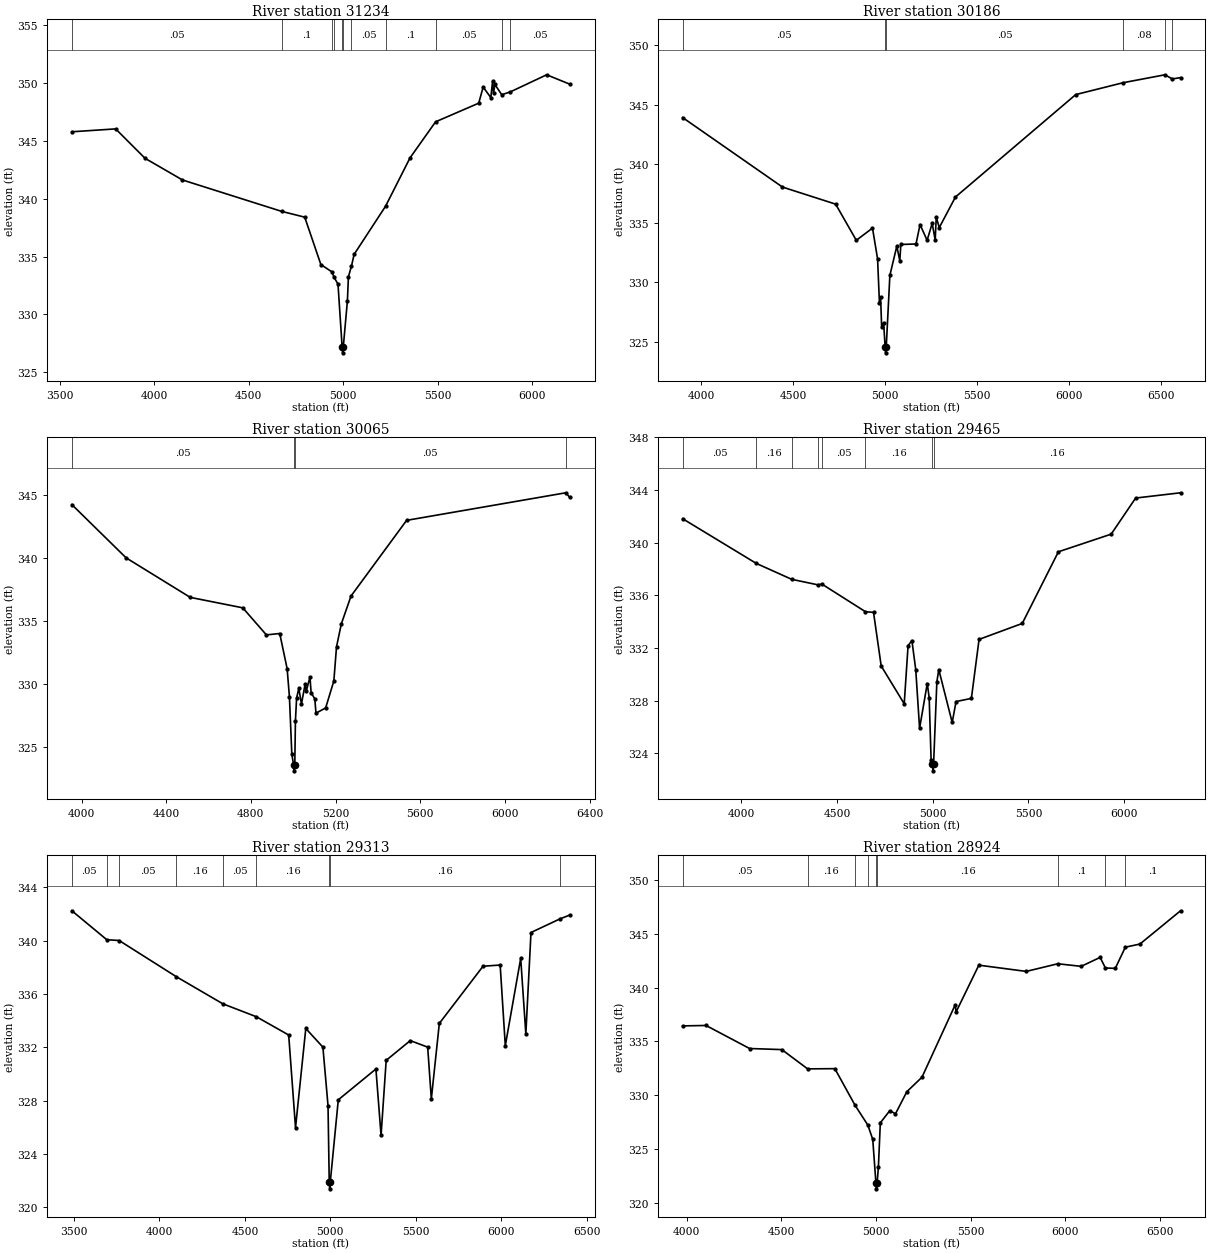
Type RM Length L Ch R = 1 ,31234   ,1048,1048,1048
BEGIN DESCRIPTION:
FERRILL BRANCH 50.0
END DESCRIPTION:
XS GIS Cut Line= 3
      3549239.18     10289645.46      3550005.59     10288793.02
      3550529.56     10287400.98
#Sta/Elev= 30
  3564.6  345.77  3796.2  346.02  3951.7  343.48  4149.8  341.61  4674.3   338.9
  4796.4   338.4  4881.8  334.31  4940.1  333.68    4952   333.2  4972.4  332.62
  4994.3  327.19  4997.1  326.69  5000.3  327.19  5022.2  331.18  5027.5  333.25
  5043.5  334.17  5057.7  335.19  5223.8  339.34  5353.5  343.52  5488.6  346.63
  5716.8  348.24  5740.3  349.63  5780.9  348.72  5790.1  350.12  5795.4   349.1
  5802.2  349.86  5838.5  348.97  5883.5  349.21  6076.2  350.69  6198.3  349.88
#Mann= 11 ,-1 , 0
  3564.6     .05       0  4674.3      .1       0  4940.1     .16       0
    4952      .1       0  4994.3     .07       0  5000.3      .1       0
  5043.5     .05       0  5223.8      .1       0  5488.6     .05       0
  5838.5      .1       0  5883.5     .05       0
Bank Sta=4994.3,5000.3
XS Rating Curve= 0 ,0
Exp/Cntr=0.3,0.1

Type RM Length L Ch R = 1 ,30186   ,121,121,121
BEGIN DESCRIPTION:
FERRILL BRANCH 48.0
END DESCRIPTION:
XS GIS Cut Line= 3
      3550122.88     10290005.17      3551033.12      10288290.9
      3551365.75     10287605.49
#Sta/Elev= 30
  3900.7   343.9  4442.6  338.04  4731.2   336.6  4843.4  333.55  4931.3  334.58
  4958.9  331.98    4969  328.27  4975.3  328.73  4980.9  326.27  4991.6  326.61
    5000  324.56  5002.7  324.06    5006  324.56  5025.6  330.59  5063.2  333.05
  5079.5  331.83  5085.2   333.2  5167.5  333.24  5189.4  334.88  5227.8  333.55
  5255.4  334.98  5271.7  333.57  5277.4  335.51  5293.7  334.62  5381.6   337.2
  6034.7  345.84  6291.7  346.84    6519  347.51  6558.5  347.16  6603.5  347.27
#Mann= 6 ,-1 , 0
  3900.7     .05       0    5000     .04       0    5006     .05       0
  6291.7     .08       0    6519     .12       0  6558.5     .08       0
Bank Sta=5000,5006
XS Rating Curve= 0 ,0
Exp/Cntr=0.3,0.1

Type RM Length L Ch R = 1 ,30065   ,600,600,600
BEGIN DESCRIPTION:
Mapping XS 5c1afc2f
END DESCRIPTION:
XS GIS Cut Line= 2
      3550300.98     10290043.46        3551294.     10287911.59
#Sta/Elev= 30
  3954.5  344.27  4210.8  340.04  4513.7   336.9  4761.8  336.07  4873.3  333.92
  4936.4  334.03  4971.4  331.23  4982.2  328.99  4993.5  324.44  5001.5  323.62
  5004.3  323.12  5007.5  323.62  5010.5  327.07  5016.1  328.91  5026.6  329.67
  5038.9  328.43  5056.3     330  5061.8  329.45  5079.2  330.58  5084.7  329.32
    5102  328.84  5107.6   327.7  5153.3  328.12    5192  330.26  5204.6  332.97
  5227.4   334.8  5273.2  337.01  5535.8  343.02  6287.9  345.21  6306.3  344.84
#Mann= 4 ,-1 , 0
  3954.5     .05       0  5001.5     .04       0  5007.5     .05       0
  6287.9     .08       0
Bank Sta=5001.5,5007.5
XS Rating Curve= 0 ,0
Exp/Cntr=0.3,0.1

Type RM Length L Ch R = 1 ,29465   ,152,152,152
BEGIN DESCRIPTION:
Mapping XS 524d1902
END DESCRIPTION:
XS GIS Cut Line= 5
      3550821.79     10290387.25      3551210.69     10290057.38
      3551276.66     10288994.88      3551186.38     10288616.41
      3551304.43     10287991.45
#Sta/Elev= 30
  3694.2  341.82  4078.4  338.43  4263.5  337.22  4400.6   336.8  4421.1  336.86
  4648.8  334.76  4690.8  334.71  4730.9  330.64  4851.1  327.77  4871.2  332.18
  4891.2  332.57  4911.3  330.36  4931.3  325.91  4971.4  329.31  4981.4  328.24
  4991.4  323.54  4998.4  323.18  5001.2  322.68  5004.4  323.18  5021.5  329.43
  5031.5  330.37  5101.6  326.35  5121.7  327.94  5201.8  328.18  5241.9  332.66
  5467.4  333.87  5656.1  339.31  5931.7  340.65  6059.5  343.39  6293.8  343.79
#Mann= 8 ,-1 , 0
  3694.2     .05       0  4078.4     .16       0  4263.5     .05       0
  4400.6     .16       0  4421.1     .05       0  4648.8     .16       0
  4998.4     .07       0  5004.4     .16       0
Bank Sta=4998.4,5004.4
XS Rating Curve= 0 ,0
Exp/Cntr=0.3,0.1

Type RM Length L Ch R = 1 ,29313   ,389,389,389
BEGIN DESCRIPTION:
Mapping XS 7d0756a8
END DESCRIPTION:
XS GIS Cut Line= 5
      3550901.64     10290585.17      3551370.41     10290151.13
      3551429.44     10288862.94      3551359.99     10288501.82
       3551398.1     10287885.23
#Sta/Elev= 30
  3487.2  342.24  3691.5  340.07  3763.8  340.01  4097.9   337.3  4370.9  335.26
  4567.2  334.29  4756.2  332.92  4796.2  325.97  4856.3  333.41  4956.4  332.01
  4986.4  327.62  4993.5  321.88  4996.2  321.38  4999.5  321.88  5046.5  328.06
  5266.7  330.37  5296.8  325.39  5326.8  331.02  5467.8   332.5  5569.7  332.01
    5591  328.12  5637.8  333.79  5893.7  338.08  5993.9  338.17    6024  332.12
  6114.1  338.67  6144.2     333  6174.3  340.61  6343.6  341.63  6401.1  341.92
#Mann= 9 ,-1 , 0
  3487.2     .05       0  3691.5     .16       0  3763.8     .05       0
  4097.9     .16       0  4370.9     .05       0  4567.2     .16       0
  4993.5     .07       0  4999.5     .16       0  6343.6     .05       0
Bank Sta=4993.5,4999.5
XS Rating Curve= 0 ,0
Exp/Cntr=0.3,0.1

Type RM Length L Ch R = 1 ,28924   ,788,788,788
BEGIN DESCRIPTION:
FERRILL BRANCH 45.0
END DESCRIPTION:
XS GIS Cut Line= 3
      3551694.76     10290185.01      3551655.66     10288691.35
      3551694.76      10287557.4
#Sta/Elev= 30
  3978.8  336.44  4102.2  336.48  4332.3  334.34  4502.4  334.24  4638.7  332.45
  4782.4  332.47  4889.7  329.05  4956.6  327.23  4982.5   325.9  4999.5  321.81
  5002.3  321.31  5005.5  321.81  5012.5  323.38  5022.5  327.44  5072.5  328.57
  5102.6  328.28  5162.6  330.33  5242.6  331.68  5417.7  338.39  5422.7  337.74
  5542.7  342.08  5792.9   341.5  5959.7  342.21    6083  341.97  6183.1   342.8
  6210.9  341.82  6263.2  341.78  6316.2  343.75  6393.2  344.04  6607.6  347.13
#Mann= 9 ,-1 , 0
  3978.8     .05       0  4638.7     .16       0  4889.7     .05       0
  4956.6     .16       0  4999.5     .07       0  5005.5     .16       0
  5959.7      .1       0  6210.9     .12       0  6316.2      .1       0
Bank Sta=4999.5,5005.5
XS Rating Curve= 0 ,0
Exp/Cntr=0.3,0.1

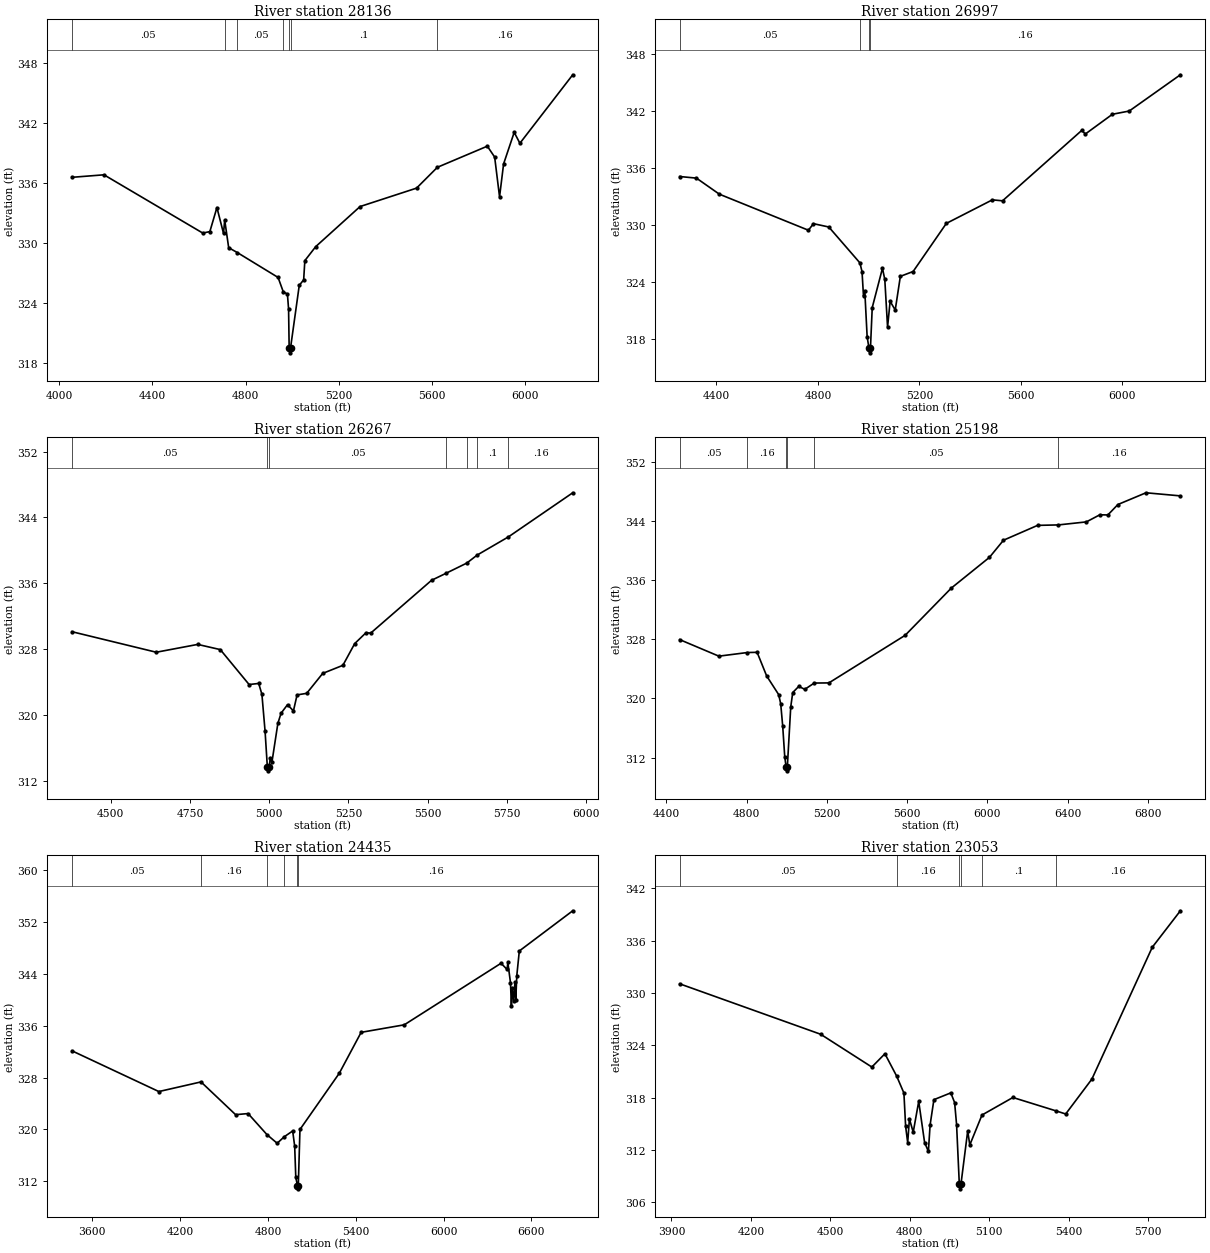
Type RM Length L Ch R = 1 ,28136   ,1139,1139,1139
BEGIN DESCRIPTION:
FERRILL BRANCH 43.0
END DESCRIPTION:
XS GIS Cut Line= 3
      3552062.32     10290247.54      3552242.18      10289019.8
      3552515.88     10288151.77
#Sta/Elev= 30
  4054.6  336.56  4191.9  336.81  4616.4  330.99  4646.7  331.14  4677.1  333.54
  4705.4  330.96  4710.5  332.29  4727.6  329.53  4765.1  329.04  4939.8  326.56
  4962.5   325.1  4979.9  324.91  4984.9  323.41  4987.4  319.53  4990.1  319.03
  4993.4  319.53  5030.8  325.77  5049.7  326.32  5054.8  328.24  5101.6  329.64
    5292  333.64  5534.7  335.48  5624.1  337.56  5838.7  339.67  5870.2  338.58
  5891.2  334.61  5908.6   337.9  5954.1  341.05  5978.6  339.96  6205.6   346.8
#Mann= 7 ,-1 , 0
  4054.6     .05       0  4710.5     .16       0  4765.1     .05       0
  4962.5      .1       0  4987.4     .07       0  4993.4      .1       0
  5624.1     .16       0
Bank Sta=4987.4,4993.4
XS Rating Curve= 0 ,0
Exp/Cntr=0.3,0.1

Type RM Length L Ch R = 1 ,26997   ,730,730,730
BEGIN DESCRIPTION:
FERRILL BRANCH 42.0
END DESCRIPTION:
XS GIS Cut Line= 3
       3552906.9     10290247.54        3552946.     10289707.98
      3553110.11     10288285.69
#Sta/Elev= 30
  4255.4   335.1  4321.5  334.93  4411.7  333.24  4762.6  329.44  4782.7  330.13
    4843  329.78  4965.5     326  4973.9  325.08  4979.7  322.48  4984.7  323.08
    4994  318.24  5001.1  317.02  5003.8  316.52  5007.1  317.02  5014.1  321.29
  5054.4  325.43  5063.6  324.25  5074.5  319.24  5084.6  321.95  5104.7  321.03
  5124.9  324.58  5175.2  325.09  5306.1  330.16  5487.3  332.64  5527.5  332.54
  5839.6  339.96  5853.8  339.58  5960.4  341.66  6026.6     342  6228.1  345.82
#Mann= 4 ,-1 , 0
  4255.4     .05       0  4965.5     .16       0  5001.1     .07       0
  5007.1     .16       0
Bank Sta=5001.1,5007.1
XS Rating Curve= 0 ,0
Exp/Cntr=0.3,0.1

Type RM Length L Ch R = 1 ,26267   ,1069,1069,1069
BEGIN DESCRIPTION:
FERRILL BRANCH 40.0
END DESCRIPTION:
XS GIS Cut Line= 3
       3553563.8     10290184.98      3553726.71     10288970.77
      3553776.72     10288620.72
#Sta/Elev= 30
  4378.4  330.13  4644.1  327.64  4774.7  328.59  4845.9  327.96  4936.7  323.72
    4967  323.85  4977.1  322.53  4987.1  318.04  4994.2  313.74    4997  313.24
  5000.2  313.74  5003.6  314.84  5008.6  314.27  5027.5  319.02  5037.6  320.24
  5057.8  321.27  5076.5  320.52    5088  322.46  5118.3  322.65  5168.8  325.07
  5232.4  326.05  5269.7  328.69  5305.3  330.01  5320.1  329.96  5511.8  336.37
  5557.3  337.22  5622.9  338.46  5655.9  339.44  5754.5  341.65  5957.1     347
#Mann= 7 ,-1 , 0
  4378.4     .05       0  4994.2    .035       0  5000.2     .05       0
  5557.3      .1       0  5622.9     .05       0  5655.9      .1       0
  5754.5     .16       0
Bank Sta=4994.2,5000.2
XS Rating Curve= 0 ,0
Exp/Cntr=0.3,0.1

Type RM Length L Ch R = 1 ,25198   ,763,763,763
BEGIN DESCRIPTION:
FERRILL BRANCH 38.0
END DESCRIPTION:
XS GIS Cut Line= 3
      3554064.29     10290278.87      3554306.72     10289981.69
      3554345.82     10287870.27
#Sta/Elev= 30
  4466.4  327.97  4661.8  325.73  4803.6  326.22  4852.4  326.25    4900  323.05
    4960  320.52    4970  319.28    4980  316.25    4990  312.15    4997  310.71
  4999.7  310.21    5003  310.71    5020  318.87    5030  320.81    5060  321.64
    5090  321.24  5137.1  322.09    5210  322.11  5590.1  328.55  5820.1  334.94
  6010.2   339.1  6080.2  341.42  6250.2  343.43  6353.6  343.49  6493.2   343.9
  6560.3  344.86  6600.3  344.84  6650.3  346.25  6790.3  347.84  6961.7  347.42
#Mann= 6 ,-1 , 0
  4466.4     .05       0  4803.6     .16       0    4997     .07       0
    5003     .16       0  5137.1     .05       0  6353.6     .16       0
Bank Sta=4997,5003
XS Rating Curve= 0 ,0
Exp/Cntr=0.3,0.1

Type RM Length L Ch R = 1 ,24435   ,1382,1382,1382
BEGIN DESCRIPTION:
FERRILL BRANCH 37.0
END DESCRIPTION:
XS GIS Cut Line= 3
      3553743.62     10290779.39      3555221.69     10289496.84
      3555761.19     10288136.34
#Sta/Elev= 30
  3461.8  332.13    4055  325.84    4343  327.33  4579.2  322.27  4664.6  322.44
  4793.4  319.19  4863.2  317.85  4911.8  318.86  4969.1  319.75  4982.8  317.41
  4990.4   312.6  5001.6  311.31  5004.4  310.81  5007.6  311.31  5018.9  319.98
  5287.6  328.67  5436.9  334.99  5731.4  336.15  6392.5  345.66  6433.7  344.71
    6439  345.78    6457  342.66  6463.4  339.06  6468.7  341.89  6478.6  339.83
  6487.7  342.76  6493.1  339.96  6500.1  343.75  6517.4  347.56  6882.3  353.77
#Mann= 6 ,-1 , 0
  3461.8     .05       0    4343     .16       0  4793.4     .05       0
  4911.8     .16       0  5001.6     .07       0  5007.6     .16       0
Bank Sta=5001.6,5007.6
XS Rating Curve= 0 ,0
Exp/Cntr=0.3,0.1

Type RM Length L Ch R = 1 ,23053   ,877,877,877
BEGIN DESCRIPTION:
FERRILL BRANCH 36.0
END DESCRIPTION:
XS GIS Cut Line= 3
      3554107.49      10291309.2       3554607.5     10290959.19
      3555592.09     10290141.65
#Sta/Elev= 30
  3931.1  331.04  4463.2  325.26  4656.5   321.5  4705.9  323.02  4750.1  320.47
  4777.6  318.52  4784.1  314.69  4791.9  312.83  4798.4  315.56  4812.7  314.03
  4833.5  317.56  4855.7  312.85    4870  311.83  4876.5  314.87  4890.8  317.76
  4954.6  318.54    4969  317.43  4976.4  314.91  4986.8  308.04  4989.5  307.54
  4992.8  308.04  5018.4  314.18  5026.3  312.57  5072.3     316    5189  318.01
  5350.2  316.49  5388.3  316.12  5487.2  320.12  5715.1  335.23  5821.2  339.41
#Mann= 6 ,-1 , 0
  3931.1     .05       0  4750.1     .16       0  4986.8     .07       0
  4992.8     .16       0  5072.3      .1       0  5350.2     .16       0
Bank Sta=4986.8,4992.8
XS Rating Curve= 0 ,0
Exp/Cntr=0.3,0.1

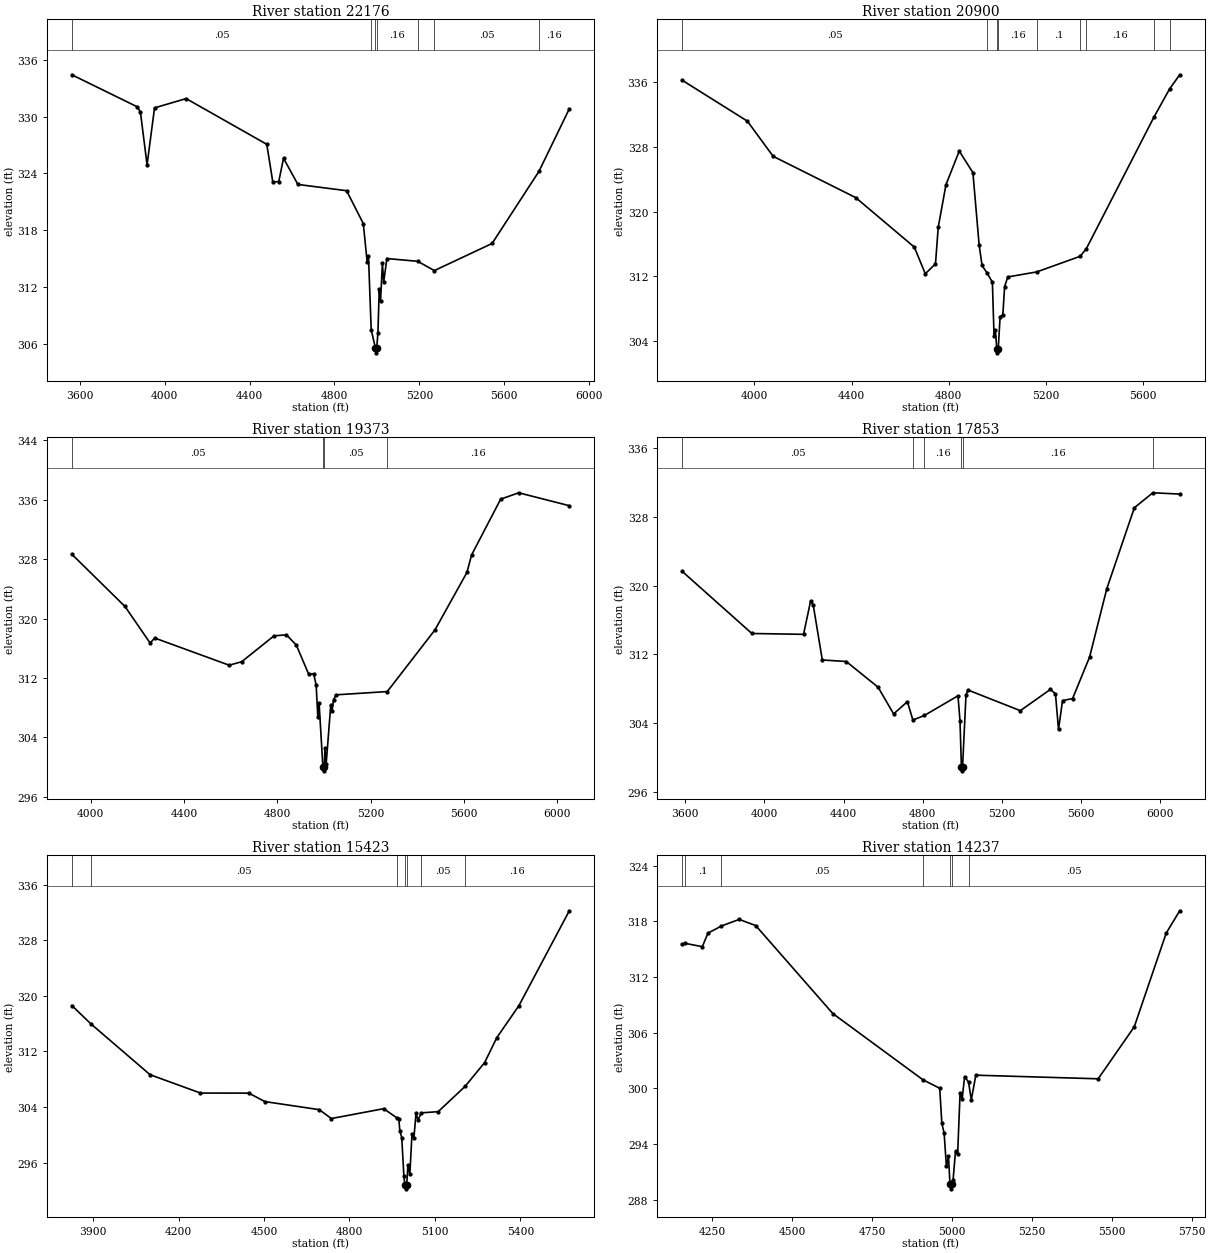
Type RM Length L Ch R = 1 ,22176   ,1276,1276,1276
BEGIN DESCRIPTION:
FERRILL BRANCH 34.0
END DESCRIPTION:
XS GIS Cut Line= 3
      3553727.98     10292014.97      3554945.18     10291379.33
      3555745.18     10290829.33
#Sta/Elev= 30
  3562.7   334.4    3872  331.01    3886  330.44  3917.1  324.91  3952.3  330.91
  4101.2  331.89  4481.2  327.07  4509.5  323.11  4537.6  323.14  4560.1   325.6
  4627.8  322.84  4857.2  322.18  4935.9  318.72  4954.3  314.65  4960.4  315.29
  4973.2  307.52  4993.2  305.59    4996  305.09  4999.2  305.59    5005  307.21
  5011.1  311.85  5017.2  310.52    5026  314.54  5032.1  312.56    5047  315.03
  5192.2  314.74  5270.9  313.76  5542.9  316.62  5763.7  324.22  5906.7  330.81
#Mann= 7 ,-1 , 0
  3562.7     .05       0  4973.2     .16       0  4993.2     .07       0
  4999.2     .16       0  5192.2      .1       0  5270.9     .05       0
  5763.7     .16       0
Bank Sta=4993.2,4999.2
XS Rating Curve= 0 ,0
Exp/Cntr=0.3,0.1

Type RM Length L Ch R = 1 ,20900   ,1527,1527,1527
BEGIN DESCRIPTION:
FERRILL BRANCH 33.0
END DESCRIPTION:
XS GIS Cut Line= 3
      3555245.14     10293094.15      3555692.11     10291841.64
      3555925.52     10291162.51
#Sta/Elev= 30
    3703  336.24  3971.1  331.19  4077.3  326.84    4417  321.74  4658.4  315.62
  4703.7  312.32  4745.6  313.56  4756.8  318.07  4788.7  323.33  4843.3  327.49
  4899.6  324.83  4925.1  315.93  4937.3  313.35  4957.3  312.44  4979.8  311.29
  4986.7  304.57    4992  305.36    4998  303.05  5000.8  302.55    5004  303.05
  5011.6  307.03  5022.8  307.23  5030.2  310.74  5043.2  311.93  5162.2  312.55
    5341  314.48  5366.4  315.41  5644.6  331.67  5709.7  335.19    5751  336.92
#Mann= 9 ,-1 , 0
    3703     .05       0  4957.3     .16       0    4998     .07       0
    5004     .16       0  5162.2      .1       0    5341     .05       0
  5366.4     .16       0  5644.6     .05       0  5709.7     .16       0
Bank Sta=4998,5004
XS Rating Curve= 0 ,0
Exp/Cntr=0.3,0.1

Type RM Length L Ch R = 1 ,19373   ,1520,1520,1520
BEGIN DESCRIPTION:
FERRILL BRANCH 30.0
END DESCRIPTION:
XS GIS Cut Line= 3
      3556042.79     10293375.71      3556496.38     10292140.07
      3556762.12      10291366.3
#Sta/Elev= 30
  3918.4  328.66  4146.4  321.62  4254.2   316.7    4274  317.37  4593.4  313.71
  4647.1  314.18  4785.6  317.66  4838.9  317.81  4881.5  316.42  4934.7  312.49
    4956  312.56  4966.7  311.01  4973.8  306.71  4979.1  308.66  4995.6  299.98
  4998.4  299.48  5001.6  299.98  5004.3  302.54  5009.6  300.41  5029.4   308.4
  5034.8  307.55  5041.2  309.03  5051.9  309.72  5271.8  310.16  5476.2  318.46
  5613.6  326.21  5633.3  328.55  5758.3  336.08  5835.7  336.94  6052.8   335.2
#Mann= 4 ,-1 , 0
  3918.4     .05       0  4995.6     .07       0  5001.6     .05       0
  5271.8     .16       0
Bank Sta=4995.6,5001.6
XS Rating Curve= 0 ,0
Exp/Cntr=0.3,0.1

Type RM Length L Ch R = 1 ,17853   ,2430,2430,2430
BEGIN DESCRIPTION:
FERRILL BRANCH 26.0
END DESCRIPTION:
XS GIS Cut Line= 3
      3556463.67     10293318.15      3557020.34     10292445.06
      3558474.87       10292187.
#Sta/Elev= 30
  3585.5  321.64  3937.2  314.42  4198.1  314.32  4233.6  318.17  4247.2  317.72
  4292.9  311.34  4413.9  311.16  4574.7  308.17  4653.2  305.06  4722.8  306.49
  4750.4  304.35  4808.4  304.88  4978.2  307.17  4988.4  304.29  4995.5  298.94
  4998.3  298.44  5001.5  298.94  5018.8  307.29    5029  307.84  5293.1  305.44
  5445.4  307.92  5470.7  307.39    5486  303.25  5506.3  306.61  5557.1  306.85
  5642.9  311.67  5729.8  319.62  5869.1  329.05  5962.5  330.79  6098.2  330.64
#Mann= 6 ,-1 , 0
  3585.5     .05       0  4750.4     .12       0  4808.4     .16       0
  4995.5     .07       0  5001.5     .16       0  5962.5     .05       0
#XS Ineff= 2 , 0
                         5446.59          307.87
Permanent Ineff=
       F       F
Bank Sta=4995.5,5001.5
XS Rating Curve= 0 ,0
Exp/Cntr=0.3,0.1

Type RM Length L Ch R = 1 ,15423   ,1186,1186,1186
BEGIN DESCRIPTION:
FERRILL BRANCH 24.0
END DESCRIPTION:
XS GIS Cut Line= 3
      3557325.36     10293743.19      3558142.11     10292941.64
      3558592.08     10292541.67
#Sta/Elev= 30
  3825.3   318.6  3891.8  315.97  4099.9  308.64  4276.7     306  4446.4  305.99
    4503  304.77  4693.8  303.61  4736.3  302.33  4920.2  303.75  4965.4  302.45
    4973  302.26  4976.8  300.59  4983.5  299.55    4991  294.02  4994.7  292.71
  4997.4  292.21  5000.7  292.71  5005.2  295.57  5011.9   294.3  5019.4  300.12
  5026.1  299.53  5033.6  303.08  5040.3  302.12  5052.4  303.15  5111.4  303.32
  5205.8  306.96  5274.5  310.39  5317.1  313.97  5394.9  318.59  5571.7  332.24
#Mann= 7 ,-1 , 0
  3825.3      .1       0  3891.8     .05       0  4965.4     .16       0
  4994.7     .07       0  5000.7     .16       0  5052.4     .05       0
  5205.8     .16       0
Bank Sta=4994.7,5000.7
XS Rating Curve= 0 ,0
Exp/Cntr=0.3,0.1

Type RM Length L Ch R = 1 ,14237   ,651,651,651
BEGIN DESCRIPTION:
FERRILL BRANCH 22.0
END DESCRIPTION:
XS GIS Cut Line= 3
      3557618.39     10294062.03       3558168.4     10293812.02
      3558892.12     10293191.63
#Sta/Elev= 30
  4155.3  315.51  4164.4  315.62  4218.2  315.26  4235.8  316.72    4278  317.49
  4333.6   318.2  4385.2  317.54  4626.8  308.05    4909  300.91  4961.4     300
    4968  296.23  4975.1  295.18  4982.3  291.59  4988.8  292.67  4993.5  289.66
  4996.3  289.16  4999.5  289.66  5003.1  290.08  5010.8  293.22  5017.4  292.87
  5025.1   299.5  5031.6  298.84  5039.3  301.26  5051.6  300.66  5060.2  298.76
  5074.5  301.41  5457.5  301.02  5570.5  306.63  5670.4  316.72  5712.7  319.13
#Mann= 7 ,-1 , 0
  4155.3     .05       0  4164.4      .1       0    4278     .05       0
    4909     .16       0  4993.5     .07       0  4999.5     .16       0
  5051.6     .05       0
Bank Sta=4993.5,4999.5
XS Rating Curve= 0 ,0
Exp/Cntr=0.3,0.1

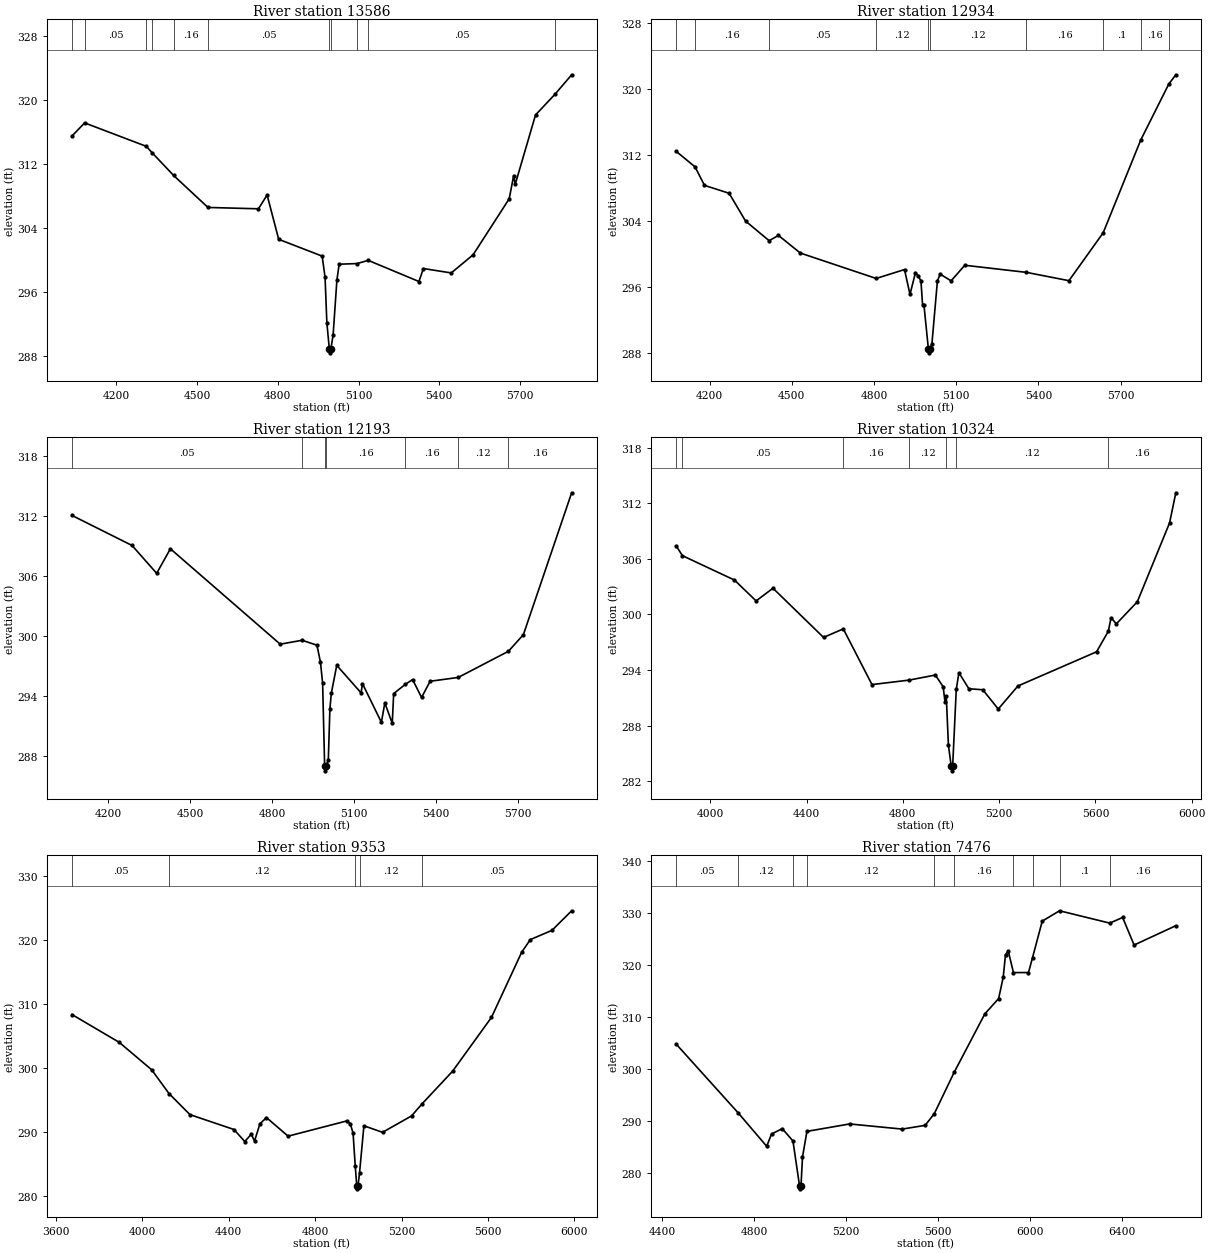
Type RM Length L Ch R = 1 ,13586   ,652,652,652
BEGIN DESCRIPTION:
FERRILL BRANCH 21.0
END DESCRIPTION:
XS GIS Cut Line= 3
      3558435.81     10294884.94      3558792.11     10293991.64
      3559192.12     10293191.61
#Sta/Elev= 30
  4035.6   315.5  4082.7  317.14  4311.9  314.21  4332.6  313.44  4413.3  310.57
  4540.8  306.58  4728.2  306.41  4760.5  308.13  4803.5   302.6    4965   300.5
  4975.8  297.85  4982.5  292.16  4991.6  288.92  4994.4  288.42  4997.6  288.92
  5005.7  290.66  5019.7  297.48  5028.1  299.49  5094.9  299.57  5136.1  299.97
  5324.4  297.33  5341.1  298.95  5444.5   298.4  5525.6  300.66  5659.8  307.66
  5676.5  310.56  5682.1  309.46  5757.6  318.13    5831  320.76  5891.8  323.15
#Mann= 11 ,-1 , 0
  4035.6     .16       0  4082.7     .05       0  4311.9     .16       0
  4332.6     .05       0  4413.3     .16       0  4540.8     .05       0
  4991.6    .035       0  4997.6     .05       0  5094.9     .16       0
  5136.1     .05       0    5831      .1       0
Bank Sta=4991.6,4997.6
XS Rating Curve= 0 ,0
Exp/Cntr=0.3,0.1

Type RM Length L Ch R = 1 ,12934   ,741,741,741
BEGIN DESCRIPTION:
FERRILL BRANCH 19.0
END DESCRIPTION:
XS GIS Cut Line= 3
       3559396.6     10295065.07       3559396.6      10294165.1
      3559392.11     10293241.68
#Sta/Elev= 30
  4077.7  312.44  4146.9  310.55  4181.1  308.31  4271.1  307.35  4331.1  303.98
  4417.1   301.6  4451.1  302.24  4531.1   300.1  4807.7  297.02  4911.1   298.1
  4931.1  295.09  4951.1  297.73  4961.1  297.32  4971.1  296.72  4976.9  293.86
  4981.9  293.86  4998.1   288.5  5000.9     288  5004.1   288.5  5011.1  289.09
  5031.1   296.7  5041.1  297.55  5081.1  296.73  5131.1  298.62  5355.8  297.76
  5511.1  296.75  5636.1  302.56    5773   313.8  5875.4  320.59  5901.1  321.72
#Mann= 10 ,-1 , 0
  4077.7     .05       0  4146.9     .16       0  4417.1     .05       0
  4807.7     .12       0  4998.1     .07       0  5004.1     .12       0
  5355.8     .16       0  5636.1      .1       0    5773     .16       0
  5875.4      .1       0
Bank Sta=4998.1,5004.1
XS Rating Curve= 0 ,0
Exp/Cntr=0.3,0.1

Type RM Length L Ch R = 1 ,12193   ,1869,1869,1869
BEGIN DESCRIPTION:
FERRILL BRANCH 18.0
END DESCRIPTION:
XS GIS Cut Line= 3
      3560031.13     10295111.73      3560062.41     10294415.76
      3559765.24     10293320.95
#Sta/Elev= 30
  4066.7  312.02    4287  309.02  4377.1  306.24  4427.4  308.69  4829.8  299.17
  4909.8  299.56  4964.5  299.07  4977.3  297.37  4985.2  295.28  4992.6  287.03
  4995.4  286.53  4998.6  287.03    5006  287.59  5011.9  292.72  5017.1  294.27
    5037  297.06  5126.2  294.31  5131.3  295.23  5200.6  291.37  5213.2  293.31
  5240.4  291.27  5245.6  294.24  5288.7  295.17  5314.9  295.64  5347.9  293.85
    5379  295.47    5482  295.85  5666.1  298.46  5720.9  300.12  5897.8  314.28
#Mann= 7 ,-1 , 0
  4066.7     .05       0  4909.8     .16       0  4992.6     .07       0
  4998.6     .16       0  5288.7     .16       0    5482     .12       0
  5666.1     .16       0
Bank Sta=4992.6,4998.6
XS Rating Curve= 0 ,0
Exp/Cntr=0.3,0.1

Type RM Length L Ch R = 1 ,10324   ,971,971,971
BEGIN DESCRIPTION:
FERRILL BRANCH 17.0
END DESCRIPTION:
XS GIS Cut Line= 3
      3560883.53     10294924.07      3560891.35     10294142.05
      3560375.91     10292954.98
#Sta/Elev= 30
    3858  307.39  3884.4  306.33  4100.4   303.7  4190.4  301.45  4260.4  302.82
  4470.5  297.51  4552.6  298.43  4671.8  292.42  4825.6   292.9  4934.9  293.45
  4967.6  292.19  4975.1  290.55  4980.5  291.17  4989.4  285.87    5001  283.61
  5003.7  283.11    5007  283.61    5022   291.9    5033   293.7  5074.3  291.97
  5132.2  291.86  5196.5  289.78  5278.3  292.27  5605.1  295.96  5653.6  298.17
  5665.3  299.64  5687.1  298.97  5774.3  301.36  5908.3  309.87  5934.2  313.12
#Mann= 7 ,-1 , 0
    3858     .16       0  3884.4     .05       0  4552.6     .16       0
  4825.6     .12       0  4980.5     .07       0    5022     .12       0
  5653.6     .16       0
Bank Sta=5001,5007
XS Rating Curve= 0 ,0
Exp/Cntr=0.3,0.1

Type RM Length L Ch R = 1 ,9353    ,1877,1877,1877
BEGIN DESCRIPTION:
FERRILL BRANCH 16.0
END DESCRIPTION:
XS GIS Cut Line= 3
      3561290.18     10294939.75      3561392.11      10293430.5
      3561392.11     10292630.49
#Sta/Elev= 30
  3674.7   308.3  3893.3  303.96  4043.6  299.67  4123.8  295.96  4220.9  292.66
  4424.5  290.34  4474.6  288.46  4504.7  289.61  4519.6  288.53  4544.8  291.24
  4574.9   292.2  4675.1   289.3  4945.7  291.67  4962.8  291.26  4975.8  289.76
  4985.8  284.61  4992.8  281.57  4995.6  281.07  4998.8  281.57  5005.8  283.61
  5025.9  290.92  5112.1   289.9  5246.2  292.46  5296.2  294.39  5436.2  299.44
  5616.2  307.85  5756.2  318.04  5796.2  320.01  5896.2  321.45  5987.4  324.51
#Mann= 5 ,-1 , 0
  3674.7     .05       0  4123.8     .12       0  4985.8     .07       0
  5005.8     .12       0  5296.2     .05       0
Bank Sta=4992.8,4998.8
XS Rating Curve= 0 ,0
Exp/Cntr=0.3,0.1

Type RM Length L Ch R = 1 ,7476    ,981,981,981
BEGIN DESCRIPTION:
FERRILL BRANCH 13.0
END DESCRIPTION:
XS GIS Cut Line= 3
      3561992.09     10294891.69      3562244.25     10293993.47
      3562275.53     10292750.01
#Sta/Elev= 30
  4459.5  304.78  4729.6  291.55  4854.2  285.11    4875  287.47  4921.9  288.51
  4968.5  286.13  4997.4  277.43  5000.2  276.93  5003.4  277.43    5010  283.03
  5029.3  287.98  5215.3  289.41  5444.3  288.42  5544.3  289.14  5584.3   291.4
  5671.1  299.37  5804.4  310.58  5864.4  313.53  5884.4  317.63  5894.4  321.98
  5906.5  322.66    5929  318.52  5994.5  318.53  6012.2  321.42  6054.5  328.42
  6129.7  330.41  6348.5  328.04  6404.6  329.12  6454.6  323.82  6636.3  327.54
#Mann= 10 ,-1 , 0
  4459.5     .05       0  4729.6     .12       0  4968.5     .07       0
  5029.3     .12       0  5584.3     .05       0  5671.1     .16       0
    5929     .05       0  6012.2     .16       0  6129.7      .1       0
  6348.5     .16       0
Bank Sta=4997.4,5003.4
XS Rating Curve= 0 ,0
Exp/Cntr=0.3,0.1