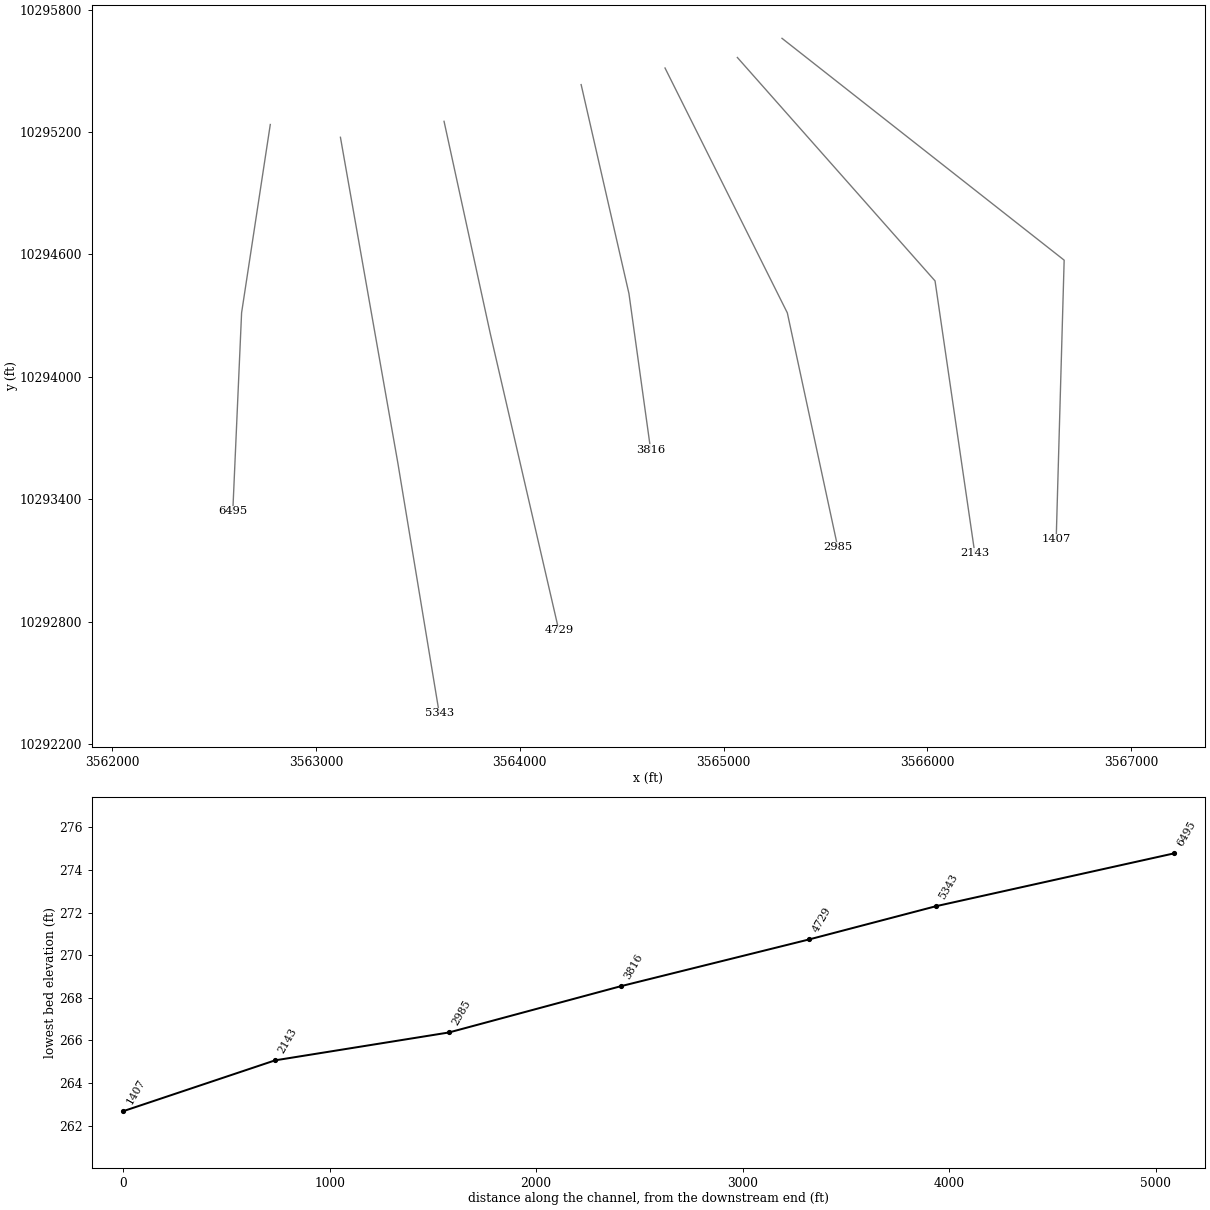
HEC-RAS study FERRILL BRANCH.prj: FERRILL BRANCH Base Level Engineering

--- FERRILL BRANCH.g01 (geometry) --- (continued)

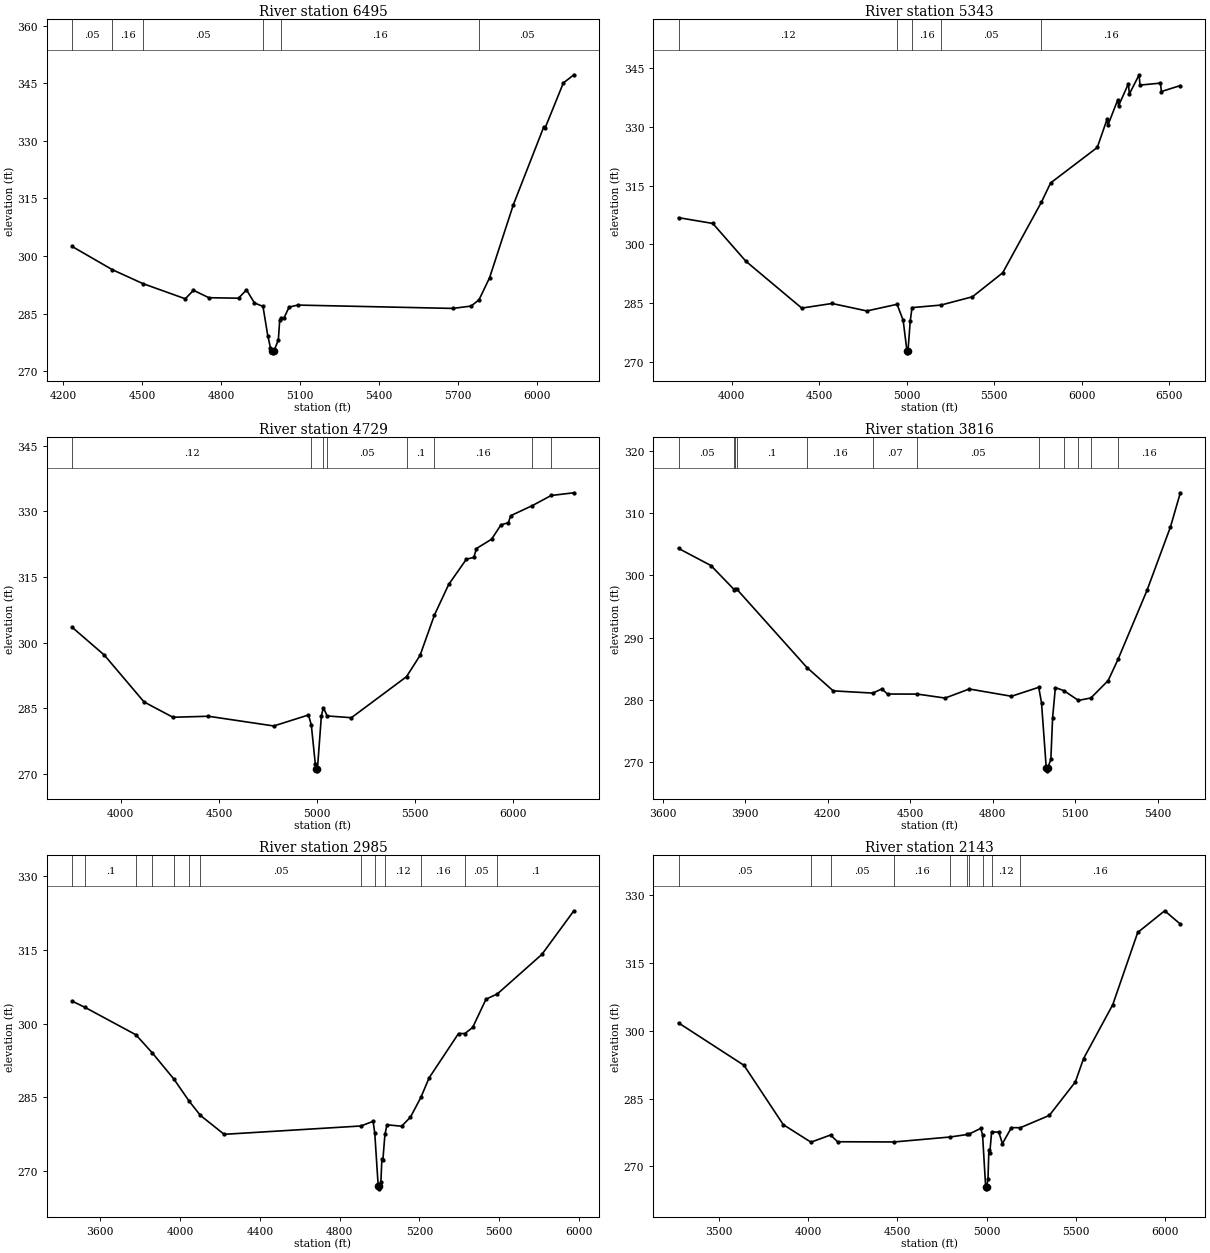
Type RM Length L Ch R = 1 ,6495    ,1152,1152,1152
BEGIN DESCRIPTION:
FERRILL BRANCH 11.0
END DESCRIPTION:
XS GIS Cut Line= 3
      3562776.03     10295236.91      3562635.26      10294314.1
      3562592.11     10293341.64
#Sta/Elev= 30
  4233.7  302.49  4387.2  296.42    4503  292.81  4663.9  288.86    4695  291.07
  4753.5  289.14  4866.2  289.01  4896.5  291.18  4926.9  287.77  4959.2  286.87
  4977.5  279.21  4987.6  276.13  4994.7  275.28  4997.5  274.78  5000.7  275.28
  5017.6  278.12  5022.7  283.27  5028.1  283.89  5038.2  283.73  5058.4  286.69
  5091.2  287.22  5680.1  286.35  5750.2  286.96  5780.2   288.6  5820.3  294.33
  5910.4  313.31  6026.7  333.69  6031.7   333.4  6100.6  345.06  6140.6   347.2
#Mann= 6 ,-1 , 0
  4233.7     .05       0  4387.2     .16       0    4503     .05       0
  4959.2     .07       0  5028.1     .16       0  5780.2     .05       0
Bank Sta=4994.7,5000.7
XS Rating Curve= 0 ,0
Exp/Cntr=0.3,0.1

Type RM Length L Ch R = 1 ,5343    ,614,614,614
BEGIN DESCRIPTION:
FERRILL BRANCH 10.0
END DESCRIPTION:
XS GIS Cut Line= 3
      3563120.12     10295174.31      3563401.64       10293579.
      3563604.98     10292351.19
#Sta/Elev= 30
  3697.6  306.86  3893.2  305.38  4082.1  295.71    4401  283.74  4573.6  284.92
  4772.6  283.01  4945.2  284.71  4979.8  280.62  5001.5   272.8  5004.2   272.3
  5007.5   272.8  5020.4  280.49  5030.6  283.86  5195.2  284.51  5375.7  286.64
    5548  292.76    5769  310.81  5821.7  315.74  6087.9   324.8  6143.8     332
  6148.9  330.51  6204.8  336.97  6209.9  335.47  6265.9  341.13  6270.9  338.45
  6326.9  343.39  6331.9  340.75  6448.9  341.26    6454  339.11  6562.1  340.63
#Mann= 5 ,-1 , 0
  3697.6     .12       0  4945.2     .07       0  5030.6     .16       0
  5195.2     .05       0    5769     .16       0
Bank Sta=5001.5,5007.5
XS Rating Curve= 0 ,0
Exp/Cntr=0.3,0.1

Type RM Length L Ch R = 1 ,4729    ,913,913,913
BEGIN DESCRIPTION:
FERRILL BRANCH 9.0
END DESCRIPTION:
XS GIS Cut Line= 3
      3563628.43     10295252.53      3563855.22     10294212.43
       3564191.5     10292757.83
#Sta/Elev= 30
  3751.5  303.55  3916.2  297.17  4118.3  286.48  4265.4  282.98  4446.3  283.21
  4779.5  280.99  4956.5   283.5  4970.8  281.22  4991.3  272.28  4996.2  271.24
    4999  270.74  5002.2  271.24  5022.1  283.28  5032.4  285.19  5051.5  283.28
  5175.3  282.88  5456.1  292.25    5525   297.1  5598.3  306.32  5670.9  313.31
  5761.5   319.1  5799.1  319.49  5812.4  321.52  5889.7  323.66  5937.5  326.93
  5975.1  327.42  5986.9  329.02  6097.8  331.34  6193.4  333.64    6309  334.26
#Mann= 8 ,-1 , 0
  3751.5     .12       0  4970.8     .05       0  5032.4     .16       0
  5051.5     .05       0  5456.1      .1       0  5598.3     .16       0
  6097.8      .1       0  6193.4     .05       0
Bank Sta=4996.2,5002.2
XS Rating Curve= 0 ,0
Exp/Cntr=0.3,0.1

Type RM Length L Ch R = 1 ,3816    ,831,831,831
BEGIN DESCRIPTION:
FERRILL BRANCH 7.0
END DESCRIPTION:
XS GIS Cut Line= 3
      3564300.96     10295432.42      3564535.58     10294407.94
      3564642.11     10293641.61
#Sta/Elev= 30
  3658.1  304.36    3776   301.6  3860.6  297.72  3864.2   297.8  3870.9  297.75
    4125  285.18  4220.6  281.42  4364.4  281.06  4397.4  281.73  4418.1  280.91
  4526.6   280.9  4627.4  280.26  4715.3  281.72  4868.7  280.55  4967.9  281.99
    4978  279.51  4995.2  269.04  4997.9  268.54  5001.2  269.04    5012  270.41
  5018.3  277.06  5028.4  281.95  5059.1  281.46  5112.3  279.88  5157.7  280.28
  5220.3  283.07  5256.3   286.5  5361.6   297.6  5446.9  307.82  5482.8  313.32
#Mann= 12 ,-1 , 0
  3658.1     .05       0  3860.6      .1       0  3864.2     .05       0
  3870.9      .1       0    4125     .16       0  4364.4     .07       0
  4526.6     .05       0  4967.9     .05       0  5059.1      .1       0
  5112.3     .16       0  5157.7      .1       0  5256.3     .16       0
Bank Sta=4995.2,5001.2
XS Rating Curve= 0 ,0
Exp/Cntr=0.3,0.1

Type RM Length L Ch R = 1 ,2985    ,842,842,842
BEGIN DESCRIPTION:
FERRILL BRANCH 5.0
END DESCRIPTION:
XS GIS Cut Line= 3
      3564712.47     10295513.73      3565312.49     10294313.69
      3565559.79     10293165.61
#Sta/Elev= 30
  3458.1  304.59  3523.1  303.32  3778.1  297.74  3860.4  294.05  3968.1  288.75
  4046.3  284.16  4101.9  281.31  4220.7  277.47  4906.4  279.17  4967.4  280.11
  4975.8  277.78  4993.2  266.87    4996  266.37  4999.2  266.87  5006.5  267.68
  5011.6  272.47  5016.7  272.32  5026.9  277.46  5037.2  279.41  5110.3  279.12
  5154.5  280.95  5207.3     285    5248  288.94  5395.9     298  5427.8  297.99
  5466.8  299.23  5533.7  304.99  5590.3  306.05  5814.2  314.12  5974.2  322.99
#Mann= 13 ,-1 , 0
  3458.1     .05       0  3523.1      .1       0  3778.1     .05       0
  3860.4      .1       0  3968.1     .05       0  4046.3      .1       0
  4101.9     .05       0  4906.4     .12       0  4975.8     .05       0
  5026.9     .12       0  5207.3     .16       0  5427.8     .05       0
  5590.3      .1       0
Bank Sta=4993.2,4999.2
XS Rating Curve= 0 ,0
Exp/Cntr=0.3,0.1

Type RM Length L Ch R = 1 ,2143    ,736,736,736
BEGIN DESCRIPTION:
FERRILL BRANCH 3.0
END DESCRIPTION:
XS GIS Cut Line= 3
      3565067.34     10295565.35      3566037.06      10294470.5
      3566232.32     10293134.95
#Sta/Elev= 30
  3272.9   301.7  3639.9  292.33  3859.8  279.24  4015.2  275.36  4124.8  276.95
  4164.3  275.46  4480.5  275.41    4793   276.5  4891.7  277.06  4898.7  277.11
  4966.7  278.41  4976.8  276.96  4994.1  265.56  4996.8  265.06  5000.1  265.56
  5007.2  267.15  5012.2  273.71  5017.3  272.92  5027.4  277.59  5067.8   277.6
    5088  275.04  5138.5  278.58  5187.8  278.55  5350.8  281.27  5496.7  288.65
  5542.8  293.82  5706.5  305.72  5846.4  321.67  5997.6  326.46  6085.2  323.52
#Mann= 10 ,-1 , 0
  3272.9     .05       0  4015.2     .16       0  4124.8     .05       0
  4480.5     .16       0    4793      .1       0  4891.7     .05       0
  4898.7     .12       0  4976.8     .03       0  5027.4     .12       0
  5187.8     .16       0
Bank Sta=4994.1,5000.1
XS Rating Curve= 0 ,0
Exp/Cntr=0.3,0.1

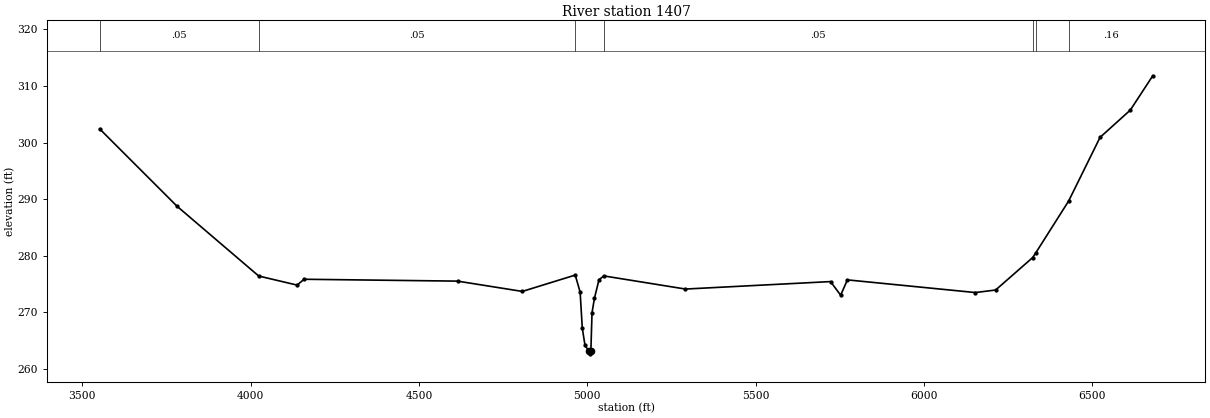
Type RM Length L Ch R = 1 ,1407    ,0,0,0
BEGIN DESCRIPTION:
FERRILL BRANCH 1.0
END DESCRIPTION:
XS GIS Cut Line= 3
      3565286.32     10295659.18       3566670.5     10294572.16
      3566631.44     10293205.11
#Sta/Elev= 30
  3551.9  302.43  3782.2  288.73  4024.4  276.42  4138.3  274.82  4159.1  275.85
  4614.7  275.52  4807.2   273.7  4964.4  276.59  4978.9  273.57  4985.3  267.21
  4993.4  264.16  5004.8  263.17  5007.6  262.67  5010.8  263.17  5014.2  269.93
  5021.5  272.53    5035  275.78  5049.4  276.44  5291.7  274.12  5722.6  275.44
  5752.6  273.03  5772.6  275.74  6152.8   273.5  6212.8  273.95  6322.8  279.68
  6331.4  280.45  6429.8  289.69  6522.9  300.92  6612.9  305.75  6679.5  311.81
#Mann= 7 ,-1 , 0
  3551.9     .05       0  4024.4     .05       0  4964.4     .03       0
  5049.4     .05       0  6322.8     .16       0  6331.4     .12       0
  6429.8     .16       0
Bank Sta=5004.8,5010.8
XS Rating Curve= 0 ,0
Exp/Cntr=0.3,0.1

Chan Stop Cuts=-1
Use User Specified Reach Order=0
Composite Channel Slope=5