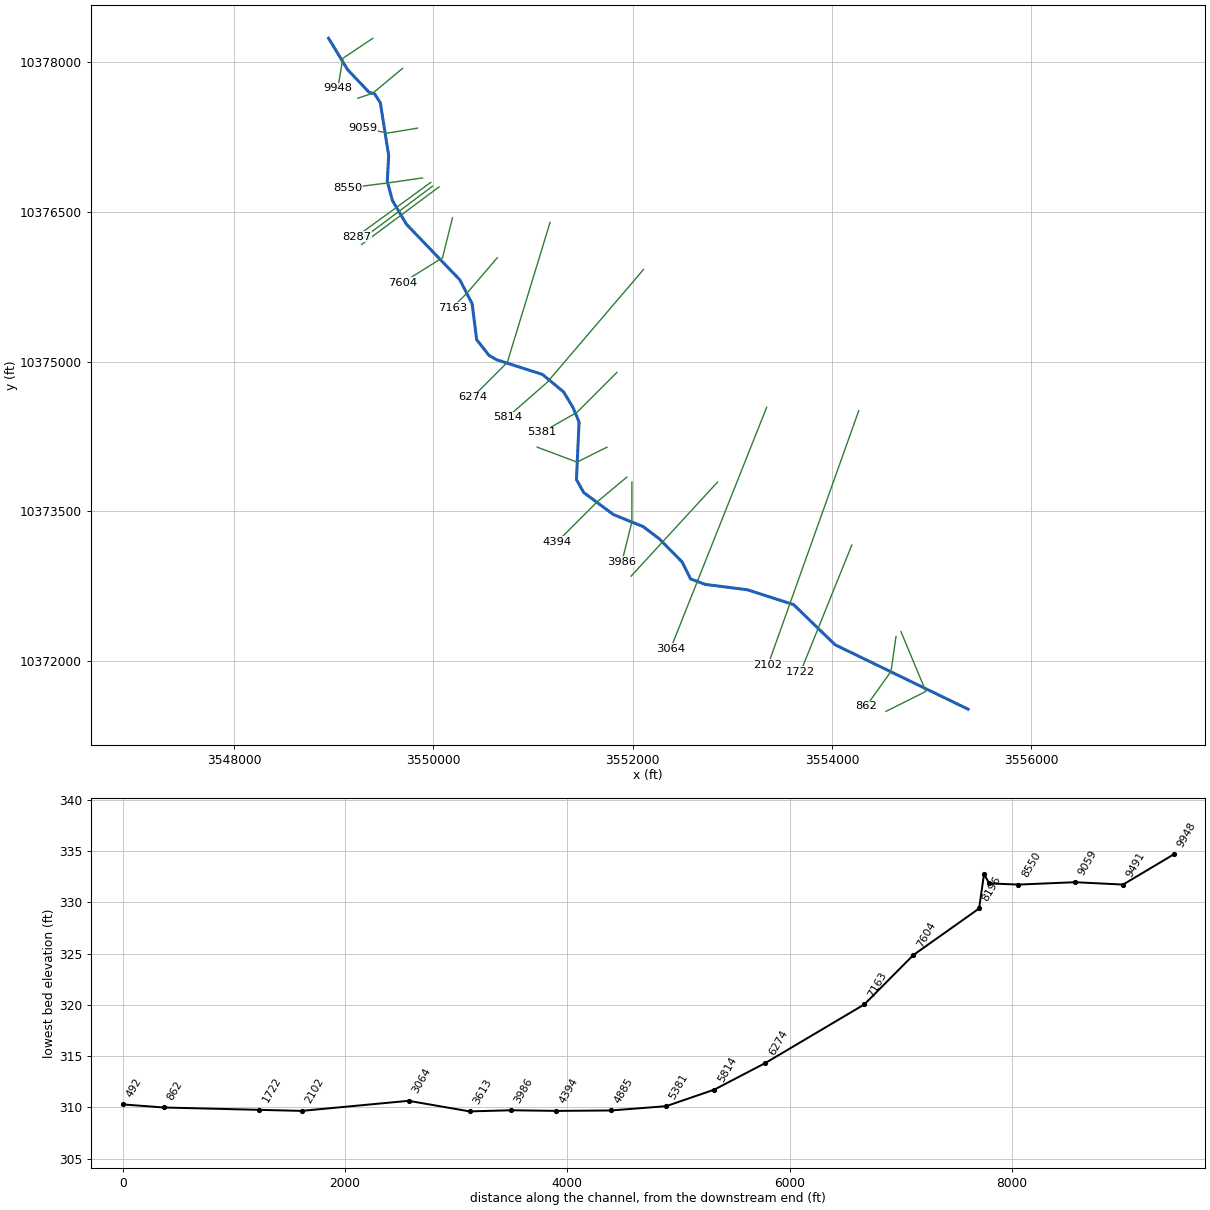
--- FLAG BRANCH.prj (project) ---

Proj Title=FLAG BRANCH Base Level Engineering
Current Plan=p01
Default Exp/Contr=0.3,0.1
English Units
Geom File=g01
Flow File=f01
Plan File=p01
BEGIN DESCRIPTION:
FLAG BRANCH
END DESCRIPTION:

--- FLAG BRANCH.p01 (plan) ---

Plan Title=Multiple Run
Short Identifier=Multiple
Geom File=g01
Flow File=f01
Subcritical Flow
K Sum by GR= 0
Std Step Tol= 0.01
Critical Tol= 0.01
Num of Std Step Trials= 20
Max Error Tol= 0.3
Flow Tol Ratio= 0.001
Split Flow NTrial= 30
Split Flow Tol= 0.02
Split Flow Ratio= 0.02
Log Output Level= 0
Friction Slope Method= 1
Unsteady Friction Slope Method= 2
Unsteady Bridges Friction Slope Method= 1
Parabolic Critical Depth
Global Vel Dist=  1 , 1 , 1
Global Log Level= 0
CheckData=True
Encroach Param= -1, 0, 0, 0
BEGIN DESCRIPTION:
Multiple Run
END DESCRIPTION:

--- FLAG BRANCH.f01 (steady flow) ---

Flow Title=Multiple
Number of Profiles=7
Profile Names=10-year,25-year,50-year,1pct_min,100-year,1pct_plu,500-year
River Rch & RM= FLAG BRANCH,Reach-1,9948
    1220    1723    2151    1962    2653    3588    4022
River Rch & RM= FLAG BRANCH,Reach-1,8550
    1584    2242    2801    2550    3448    4663    5214
Boundary for River Rch & Prof#=FLAG BRANCH,Reach-1,1
Up Type=0
Dn Type=3
Dn Slope=0.005
Boundary for River Rch & Prof#=FLAG BRANCH,Reach-1,2
Up Type=0
Dn Type=3
Dn Slope=0.005
Boundary for River Rch & Prof#=FLAG BRANCH,Reach-1,3
Up Type=0
Dn Type=3
Dn Slope=0.005
Boundary for River Rch & Prof#=FLAG BRANCH,Reach-1,4
Up Type=0
Dn Type=3
Dn Slope=0.005
Boundary for River Rch & Prof#=FLAG BRANCH,Reach-1,5
Up Type=0
Dn Type=3
Dn Slope=0.005
Boundary for River Rch & Prof#=FLAG BRANCH,Reach-1,6
Up Type=0
Dn Type=3
Dn Slope=0.005
Boundary for River Rch & Prof#=FLAG BRANCH,Reach-1,7
Up Type=0
Dn Type=3
Dn Slope=0.005

--- FLAG BRANCH.g01 (geometry) ---

Geom Title=Existing Conditions

River Reach=FLAG BRANCH,Reach-1
Reach XY= 30
      3548948.68     10378243.03      3549139.64     10377928.40
      3549354.48     10377701.62      3549410.91     10377685.35
      3549468.41     10377595.28      3549551.96     10377066.86
      3549538.08     10376807.31      3549590.16     10376613.73
      3549730.60     10376377.21      3550266.63     10375818.80
      3550389.24     10375581.17      3550434.81     10375219.84
      3550557.42     10375063.59      3550635.55     10375018.02
      3551095.18     10374870.99      3551306.12     10374696.51
      3551399.87     10374542.86      3551462.37     10374394.43
      3551436.33     10373816.30      3551509.25     10373686.09
      3551808.73     10373464.74      3552105.60     10373344.95
      3552267.06     10373222.55      3552496.66     10372989.48
      3552581.30     10372820.21      3552727.13     10372765.52
      3553152.91     10372710.83      3553615.15     10372562.40
      3554030.51     10372160.05      3555365.15     10371513.70

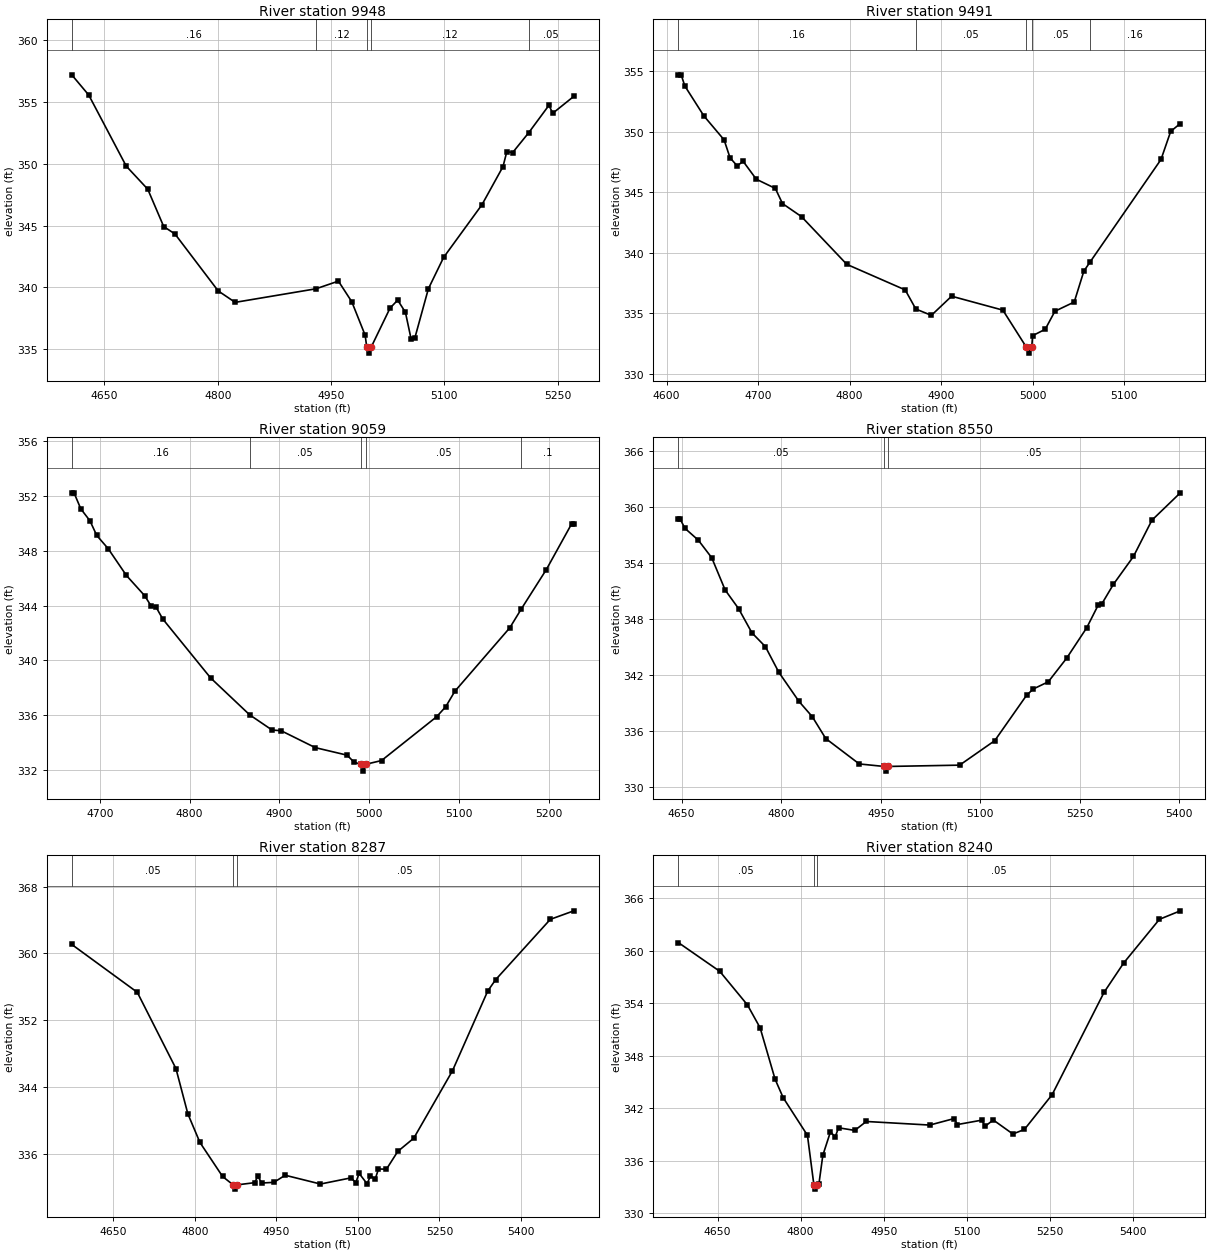
Type RM Length L Ch R = 1,9948,457,457,457
BEGIN DESCRIPTION:
FLAG BRANCH 22.0
END DESCRIPTION:
XS GIS Cut Line= 3
      3549392.10     10378241.64      3549092.11     10378041.64
      3549042.10     10377741.63
#Sta/Elev= 30
  4606.7  357.20  4629.2  355.56  4678.8  349.81  4707.3  347.94  4728.4  344.92
  4743.4  344.31  4800.5  339.71  4823.0  338.78  4930.1  339.88  4959.7  340.50
  4977.4  338.83  4995.1  336.12  4997.2  335.17  4999.9  334.67  5003.2  335.17
  5028.1  338.32  5038.2  338.96  5048.4  337.98  5056.0  335.80  5061.0  335.92
  5078.8  339.88  5099.0  342.42  5149.7  346.68  5177.6  349.77  5182.7  350.99
  5190.3  350.90  5211.6  352.51  5238.4  354.73  5243.5  354.09  5271.4  355.46
#Mann=5,-1,0
  4606.7    0.16       0  4930.1    0.12       0  4997.2    0.07       0
  5003.2    0.12       0  5211.6    0.05       0
Bank Sta=4997.2,5003.2
Exp/Cntr=0.3,0.1

Type RM Length L Ch R = 1,9491,432,432,432
BEGIN DESCRIPTION:
FLAG BRANCH 21.0
END DESCRIPTION:
XS GIS Cut Line= 3
      3549692.10     10377941.64      3549392.11     10377691.64
      3549242.12     10377641.65
#Sta/Elev= 30
  4612.8  354.70  4616.0  354.70  4620.0  353.78  4640.8  351.31  4662.9  349.33
  4669.4  347.85  4677.2  347.18  4683.7  347.56  4698.1  346.08  4718.9  345.32
  4726.7  344.07  4747.5  342.99  4797.0  339.05  4860.8  336.94  4872.4  335.36
  4889.4  334.84  4911.5  336.42  4967.5  335.27  4993.1  332.22  4995.9  331.72
  4999.1  332.22  5000.0  333.16  5013.8  333.69  5024.4  335.18  5045.5  335.94
  5056.0  338.49  5062.5  339.21  5140.3  347.71  5150.9  350.03  5161.4  350.68
#Mann=5,-1,0
  4612.8    0.16       0  4872.4    0.05       0  4993.1   0.033       0
  4999.1    0.05       0  5062.5    0.16       0
Bank Sta=4993.1,4999.1
Exp/Cntr=0.3,0.1

Type RM Length L Ch R = 1,9059,509,509,509
BEGIN DESCRIPTION:
FLAG BRANCH 20.0
END DESCRIPTION:
XS GIS Cut Line= 3
      3549842.06     10377341.63      3549542.11     10377291.64
      3549292.15     10377341.63
#Sta/Elev= 30
  4668.9  352.20  4671.4  352.20  4679.0  351.03  4689.1  350.17  4696.7  349.10
  4709.4  348.14  4729.7  346.19  4750.0  344.72  4757.6  343.93  4762.6  343.90
  4770.2  343.02  4823.5  338.73  4866.9  336.05  4891.9  334.94  4902.0  334.89
  4940.0  333.66  4975.5  333.11  4983.2  332.60  4990.4  332.45  4993.1  331.95
  4996.4  332.45  5013.8  332.72  5075.0  335.90  5085.2  336.63  5095.4  337.76
  5156.6  342.38  5169.4  343.75  5197.3  346.62  5225.4  349.94  5227.9  349.94
#Mann=5,-1,0
  4668.9    0.16       0  4866.9    0.05       0  4990.4   0.033       0
  4996.4    0.05       0  5169.4     0.1       0
Bank Sta=4990.4,4996.4
Exp/Cntr=0.3,0.1

Type RM Length L Ch R = 1,8550,263,263,263
BEGIN DESCRIPTION:
FLAG BRANCH 19.0
END DESCRIPTION:
XS GIS Cut Line= 3
      3549892.13     10376841.65      3549542.11     10376791.64
      3549142.10     10376741.64
#Sta/Elev= 30
  4644.9  358.74  4647.5  358.74  4655.0  357.71  4675.2  356.44  4695.4  354.56
  4715.6  351.11  4735.8  349.12  4756.0  346.52  4776.2  345.05  4796.5  342.30
  4826.8  339.19  4847.0  337.54  4867.2  335.21  4917.7  332.49  4955.1  332.22
  4957.8  331.72  4961.1  332.22  5069.0  332.36  5121.9  334.98  5169.8  339.83
  5179.9  340.51  5202.6  341.28  5230.3  343.81  5260.5  347.06  5278.1  349.53
  5283.2  349.61  5300.8  351.72  5331.0  354.70  5358.8  358.58  5401.6  361.51
#Mann=3,-1,0
  4644.9    0.05       0  4955.1   0.033       0  4961.1    0.05       0
Bank Sta=4955.1,4961.1
Exp/Cntr=0.3,0.1

Type RM Length L Ch R = 1,8287,47,47,47
BEGIN DESCRIPTION:
Mapping XS 35988643
END DESCRIPTION:
XS GIS Cut Line= 2
      3549974.69     10376797.47      3549228.13     10376254.04
#Sta/Elev= 30
  4573.7  361.08  4694.2  355.36  4765.3  346.24  4787.2  340.83  4809.4  337.41
  4851.1  333.34  4870.7  332.33  4873.5  331.83  4876.7  332.33  4909.8  332.60
  4916.0  333.35  4923.2  332.56  4945.4  332.64  4966.2  333.49  5031.1  332.44
  5087.5  333.18  5096.0  332.60  5102.2  333.71  5116.9  332.46  5123.1  333.44
  5131.6  332.99  5137.8  334.24  5152.4  334.21  5173.3  336.34  5202.7  337.92
  5273.8  345.97  5338.7  355.51  5353.3  356.87  5453.8  364.08  5497.1  365.10
#Mann=3,-1,0
  4573.7    0.05       0  4870.7   0.033       0  4876.7    0.05       0
Bank Sta=4870.7,4876.7
Exp/Cntr=0.3,0.1

Type RM Length L Ch R = 1,8240,44,44,44
BEGIN DESCRIPTION:
Mapping XS abb1d304
END DESCRIPTION:
XS GIS Cut Line= 2
      3549990.90     10376758.63      3549266.07     10376214.74
#Sta/Elev= 30
  4579.0  360.92  4653.9  357.63  4703.9  353.79  4726.8  351.17  4753.8  345.30
  4768.4  343.19  4812.2  338.89  4823.8  333.24  4826.5  332.74  4829.8  333.24
  4833.0  333.37  4840.0  336.61  4853.8  339.30  4862.2  338.70  4868.4  339.75
  4897.6  339.45  4918.4  340.47  5033.0  340.06  5076.7  340.80  5083.0  340.12
  5126.7  340.62  5133.0  339.93  5147.6  340.64  5183.0  339.04  5203.8  339.56
  5253.8  343.53  5347.6  355.23  5383.0  358.58  5447.5  363.57  5485.2  364.54
#Mann=3,-1,0
  4579.0    0.05       0  4823.8   0.035       0  4829.8    0.05       0
Bank Sta=4823.8,4829.8
Exp/Cntr=0.3,0.1

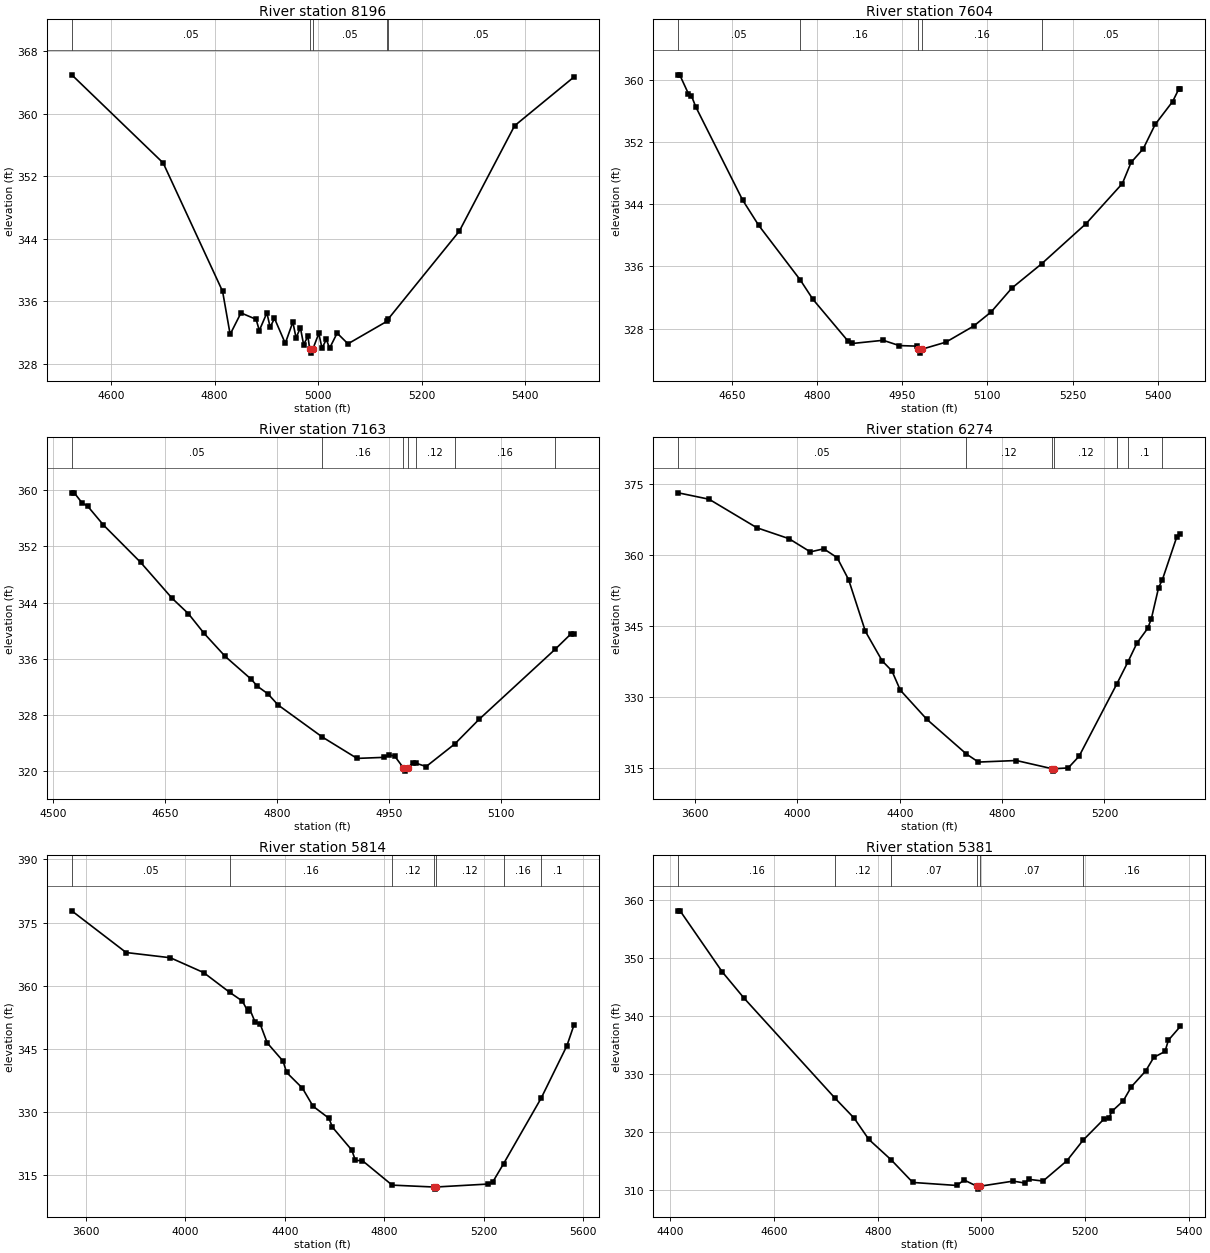
Type RM Length L Ch R = 1,8196,592,592,592
BEGIN DESCRIPTION:
FLAG BRANCH 18.0
END DESCRIPTION:
XS GIS Cut Line= 2
      3550058.03     10376752.34      3549280.26     10376174.21
#Sta/Elev= 30
  4524.4  364.95  4700.8  353.69  4815.5  337.29  4830.1  331.79  4851.0  334.53
  4880.2  333.71  4886.4  332.28  4901.0  334.53  4907.3  332.71  4915.7  333.83
  4936.5  330.64  4951.1  333.36  4957.3  331.35  4965.7  332.63  4971.9  330.49
  4980.3  331.53  4983.6  329.89  4986.3  329.39  4989.6  329.89  5001.2  331.90
  5007.4  330.03  5015.8  331.14  5022.0  330.01  5036.6  331.95  5057.5  330.58
  5132.6  333.45  5135.2  333.75  5272.3  344.96  5379.1  358.44  5493.5  364.66
#Mann=5,-1,0
  4524.4    0.05       0  4983.6   0.035       0  4989.6    0.05       0
  5132.6    0.16       0  5135.2    0.05       0
Bank Sta=4983.6,4989.6
Exp/Cntr=0.3,0.1

Type RM Length L Ch R = 1,7604,441,441,441
BEGIN DESCRIPTION:
FLAG BRANCH 17.0
END DESCRIPTION:
XS GIS Cut Line= 3
      3550192.11     10376441.65      3550092.11     10376041.64
      3549692.12     10375791.65
#Sta/Elev= 30
  4555.6  360.62  4558.2  360.62  4573.6  358.18  4578.8  357.93  4586.5  356.50
  4669.0  344.52  4697.3  341.27  4770.6  334.24  4792.7  331.77  4854.5  326.40
  4862.3  326.09  4916.4  326.50  4944.7  325.82  4975.6  325.75  4978.5  325.35
  4981.2  324.85  4984.5  325.35  5026.9  326.26  5075.8  328.33  5106.5  330.14
  5143.0  333.21  5195.4  336.33  5273.9  341.51  5337.6  346.65  5352.9  349.36
  5374.2  351.10  5395.4  354.25  5426.1  357.19  5436.7  358.76  5439.6  358.76
#Mann=5,-1,0
  4555.6    0.05       0  4770.6    0.16       0  4978.5    0.07       0
  4984.5    0.16       0  5195.4    0.05       0
Bank Sta=4978.5,4984.5
Exp/Cntr=0.3,0.1

Type RM Length L Ch R = 1,7163,889,889,889
BEGIN DESCRIPTION:
FLAG BRANCH 16.0
END DESCRIPTION:
XS GIS Cut Line= 3
      3550642.13     10376041.67      3550342.11     10375691.64
      3550192.13     10375541.67
#Sta/Elev= 30
  4524.8  359.63  4528.1  359.63  4538.5  358.21  4546.2  357.72  4567.1  355.07
  4617.0  349.75  4659.3  344.63  4681.2  342.43  4702.1  339.65  4730.6  336.35
  4765.7  333.08  4773.4  332.13  4787.7  331.04  4801.4  329.45  4860.7  324.89
  4907.3  321.85  4943.6  322.00  4950.1  322.35  4957.8  322.17  4969.1  320.54
  4971.8  320.04  4975.1  320.54  4982.5  321.18  4985.9  321.18  4999.9  320.69
  5038.4  323.92  5070.7  327.39  5172.8  337.37  5194.4  339.60  5197.9  339.60
#Mann=7,-1,0
  4524.8    0.05       0  4860.7    0.16       0  4969.1    0.07       0
  4975.1    0.16       0  4985.9    0.12       0  5038.4    0.16       0
  5172.8    0.05       0
Bank Sta=4969.1,4975.1
Exp/Cntr=0.3,0.1

Type RM Length L Ch R = 1,6274,460,460,460
BEGIN DESCRIPTION:
FLAG BRANCH 14.0
END DESCRIPTION:
XS GIS Cut Line= 3
      3551171.23     10376395.70      3550742.11     10374991.64
      3550392.14     10374641.68
#Sta/Elev= 30
  3533.8  373.05  3654.4  371.70  3841.3  365.68  3966.8  363.38  4050.4  360.59
  4102.7  361.24  4155.0  359.38  4200.0  354.73  4265.6  343.82  4331.2  337.60
  4369.2  335.49  4402.0  331.43  4505.6  325.28  4660.1  317.97  4707.6  316.25
  4855.6  316.58  4996.4  314.84  4999.1  314.34  5002.4  314.84  5058.5  315.01
  5101.0  317.47  5249.1  332.78  5292.3  337.40  5327.2  341.34  5369.7  344.49
  5383.8  346.52  5412.1  353.07  5426.7  354.71  5482.8  363.71  5496.9  364.43
#Mann=7,-1,0
  3533.8    0.05       0  4660.1    0.12       0  4996.4    0.07       0
  5002.4    0.12       0  5249.1    0.16       0  5292.3     0.1       0
  5426.7    0.05       0
Bank Sta=4996.4,5002.4
Exp/Cntr=0.3,0.1

Type RM Length L Ch R = 1,5814,433,433,433
BEGIN DESCRIPTION:
FLAG BRANCH 13.0
END DESCRIPTION:
XS GIS Cut Line= 3
      3552108.73     10375923.50      3551142.11     10374791.64
      3550742.14     10374441.67
#Sta/Elev= 30
  3542.8  377.81  3761.5  367.91  3939.4  366.67  4073.3  363.15  4177.4  358.49
  4229.2  356.38  4251.2  353.96  4257.8  354.60  4279.8  351.48  4300.6  350.96
  4329.2  346.45  4392.8  342.13  4407.1  339.44  4470.8  335.71  4513.6  331.41
  4577.3  328.57  4591.5  326.44  4669.5  321.00  4683.8  318.55  4712.3  318.49
  4831.7  312.69  5000.3  312.24  5003.0  311.74  5006.3  312.24  5215.8  312.94
  5236.7  313.46  5280.3  317.81  5431.5  333.37  5534.7  345.77  5562.7  350.62
#Mann=7,-1,0
  3542.8    0.05       0  4177.4    0.16       0  4831.7    0.12       0
  5000.3    0.07       0  5006.3    0.12       0  5280.3    0.16       0
  5431.5     0.1       0
Bank Sta=5000.3,5006.3
Exp/Cntr=0.3,0.1

Type RM Length L Ch R = 1,5381,496,496,496
BEGIN DESCRIPTION:
FLAG BRANCH 12.0
END DESCRIPTION:
XS GIS Cut Line= 3
      3551842.13     10374891.66      3551442.11     10374491.64
      3551092.13     10374291.66
#Sta/Elev= 30
  4415.1  358.06  4418.7  358.06  4500.0  347.55  4542.4  342.99  4718.0  325.76
  4754.5  322.36  4782.8  318.70  4826.0  315.17  4867.7  311.28  4952.5  310.76
  4966.7  311.70  4991.5  310.63  4994.2  310.13  4997.5  310.63  5061.4  311.51
  5084.5  311.17  5091.0  311.82  5119.0  311.52  5165.1  315.02  5196.3  318.56
  5236.4  322.18  5245.7  322.34  5252.2  323.55  5273.8  325.33  5289.6  327.78
  5317.0  330.47  5332.8  332.83  5354.4  333.84  5360.9  335.78  5383.9  338.15
#Mann=6,-1,0
  4415.1    0.16       0  4718.0    0.12       0  4826.0    0.07       0
  4991.5    0.07       0  4997.5    0.07       0  5196.3    0.16       0
Bank Sta=4991.5,4997.5
Exp/Cntr=0.3,0.1

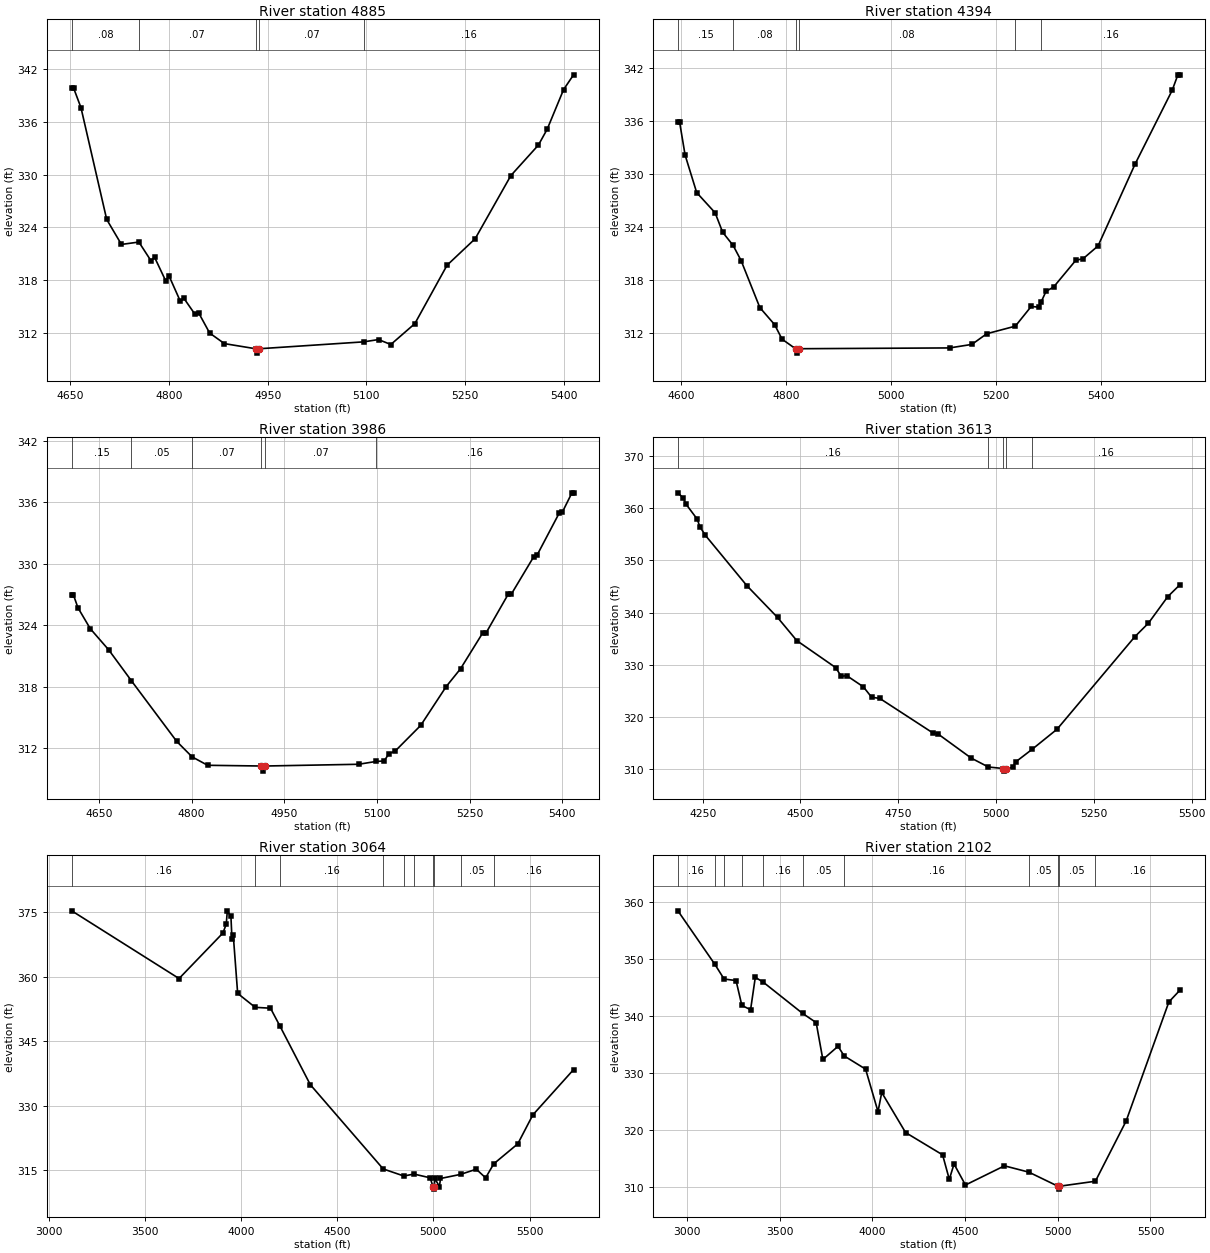
Type RM Length L Ch R = 1,4885,491,491,491
BEGIN DESCRIPTION:
FLAG BRANCH 11.0
END DESCRIPTION:
XS GIS Cut Line= 3
      3551742.11     10374141.65      3551442.11     10373991.64
      3551042.12     10374141.64
#Sta/Elev= 30
  4652.3  339.83  4655.1  339.83  4666.3  337.60  4705.4  324.90  4727.8  322.06
  4754.3  322.33  4772.5  320.23  4778.1  320.61  4794.9  317.95  4800.4  318.44
  4817.2  315.62  4822.8  315.93  4839.6  314.12  4845.2  314.28  4861.9  311.99
  4884.3  310.79  4931.6  310.21  4934.4  309.71  4937.6  310.21  5095.8  310.99
  5118.5  311.25  5137.2  310.69  5173.7  313.06  5222.7  319.70  5265.4  322.71
  5319.7  329.89  5361.5  333.35  5374.9  335.16  5399.8  339.66  5414.9  341.33
#Mann=5,-1,0
  4652.3    0.08       0  4754.3    0.07       0  4931.6    0.07       0
  4937.6    0.07       0  5095.8    0.16       0
Bank Sta=4931.6,4937.6
Exp/Cntr=0.3,0.1

Type RM Length L Ch R = 1,4394,408,408,408
BEGIN DESCRIPTION:
FLAG BRANCH 10.0
END DESCRIPTION:
XS GIS Cut Line= 3
      3551942.10     10373841.64      3551642.11     10373591.64
      3551242.10     10373191.63
#Sta/Elev= 30
  4593.3  335.89  4596.5  335.89  4607.0  332.14  4629.1  327.88  4664.2  325.59
  4678.6  323.38  4698.6  321.88  4713.7  320.17  4749.5  314.83  4777.5  312.91
  4791.8  311.25  4817.4  310.17  4820.2  309.67  4823.4  310.17  5111.1  310.26
  5153.5  310.66  5181.8  311.87  5236.3  312.73  5266.6  314.97  5280.8  314.88
  5285.7  315.51  5294.9  316.69  5309.1  317.16  5351.5  320.20  5365.6  320.39
  5393.9  321.83  5464.6  331.13  5535.3  339.50  5546.0  341.24  5549.5  341.24
#Mann=6,-1,0
  4593.3    0.15       0  4698.6    0.08       0  4817.4    0.07       0
  4823.4    0.08       0  5236.3    0.12       0  5285.7    0.16       0
Bank Sta=4817.4,4823.4
Exp/Cntr=0.3,0.1

Type RM Length L Ch R = 1,3986,373,373,373
BEGIN DESCRIPTION:
FLAG BRANCH 9.0
END DESCRIPTION:
XS GIS Cut Line= 3
      3551992.11     10373791.64      3551992.11     10373391.64
      3551892.11     10372991.65
#Sta/Elev= 30
  4606.0  326.99  4608.5  326.99  4616.0  325.70  4636.0  323.65  4666.0  321.57
  4702.7  318.55  4776.0  312.63  4800.9  311.12  4826.0  310.30  4913.0  310.23
  4915.7  309.73  4919.0  310.23  5070.4  310.40  5099.1  310.68  5111.7  310.72
  5119.4  311.43  5129.7  311.70  5170.9  314.20  5212.2  318.00  5235.3  319.73
  5271.4  323.25  5276.6  323.23  5312.7  327.04  5317.8  327.05  5353.9  330.69
  5359.0  330.81  5395.1  334.95  5400.3  335.06  5415.7  336.93  5418.3  336.93
#Mann=6,-1,0
  4606.0    0.15       0  4702.7    0.05       0  4800.9    0.07       0
  4913.0    0.07       0  4919.0    0.07       0  5099.1    0.16       0
Bank Sta=4913,4919
Exp/Cntr=0.3,0.1

Type RM Length L Ch R = 1,3613,549,549,549
BEGIN DESCRIPTION:
FLAG BRANCH 8.0
END DESCRIPTION:
XS GIS Cut Line= 2
      3552851.78     10373791.55      3551983.77     10372847.15
#Sta/Elev= 30
  4186.8  362.94  4200.4  361.95  4207.8  360.74  4236.1  357.90  4242.9  356.44
  4257.1  354.79  4363.2  345.14  4441.4  339.07  4490.8  334.62  4590.0  329.46
  4604.2  327.80  4618.4  327.91  4660.9  325.77  4681.9  323.78  4702.9  323.55
  4837.9  316.97  4852.1  316.72  4936.5  312.12  4980.4  310.41  5018.6  310.12
  5021.4  309.62  5024.6  310.12  5042.6  310.32  5050.0  311.37  5093.1  313.85
  5156.0  317.65  5354.5  335.35  5389.7  337.98  5439.0  343.05  5469.5  345.29
#Mann=5,-1,0
  4186.8    0.16       0  4980.4    0.07       0  5018.6    0.07       0
  5024.6    0.07       0  5093.1    0.16       0
Bank Sta=5018.6,5024.6
Exp/Cntr=0.3,0.1

Type RM Length L Ch R = 1,3064,962,962,962
BEGIN DESCRIPTION:
FLAG BRANCH 7.0
END DESCRIPTION:
XS GIS Cut Line= 2
      3553344.83     10374541.53      3552379.58     10372117.97
#Sta/Elev= 30
  3119.8  375.30  3677.6  359.57  3905.4  370.13  3923.0  372.19  3928.4  375.21
  3947.3  374.00  3952.7  368.76  3959.3  369.74  3982.3  356.12  4073.3  352.88
  4153.0  352.68  4202.0  348.54  4359.9  334.92  4738.8  315.34  4846.2  313.70
  4898.7  314.15  4982.8  313.28  4998.7  311.15  5001.5  310.65  5004.7  311.15
  5007.1  313.12  5031.4  311.26  5036.8  313.12  5141.6  314.08  5222.9  315.28
  5271.4  313.27  5313.7  316.53  5438.6  321.17  5516.8  327.89  5728.5  338.41
#Mann=10,-1,0
  3119.8    0.16       0  4073.3     0.1       0  4202.0    0.16       0
  4738.8     0.1       0  4846.2    0.07       0  4898.7     0.1       0
  4998.7    0.07       0  5004.7     0.1       0  5141.6    0.05       0
  5313.7    0.16       0
Bank Sta=4998.7,5004.7
Exp/Cntr=0.3,0.1

Type RM Length L Ch R = 1,2102,380,380,380
BEGIN DESCRIPTION:
FLAG BRANCH 4.0
END DESCRIPTION:
XS GIS Cut Line= 2
      3554268.47     10374506.88      3553358.75     10371958.27
#Sta/Elev= 30
  2951.4  358.40  3150.5  349.04  3200.4  346.46  3264.9  346.19  3296.2  341.84
  3343.3  341.08  3368.8  346.76  3411.9  345.90  3623.4  340.45  3697.0  338.83
  3733.1  332.37  3814.9  334.68  3848.2  332.99  3963.6  330.68  4030.5  323.24
  4050.6  326.59  4179.2  319.58  4378.9  315.67  4415.0  311.38  4440.5  314.07
  4502.1  310.39  4712.4  313.75  4844.3  312.64  5001.4  310.17  5004.2  309.67
  5007.4  310.17  5202.8  311.05  5368.7  321.60  5599.2  342.45  5657.5  344.46
#Mann=11,-1,0
  2951.4    0.16       0  3150.5    0.05       0  3200.4    0.16       0
  3296.2    0.05       0  3411.9    0.16       0  3623.4    0.05       0
  3848.2    0.16       0  4844.3    0.05       0  5001.4   0.033       0
  5007.4    0.05       0  5202.8    0.16       0
Bank Sta=5001.4,5007.4
Exp/Cntr=0.3,0.1

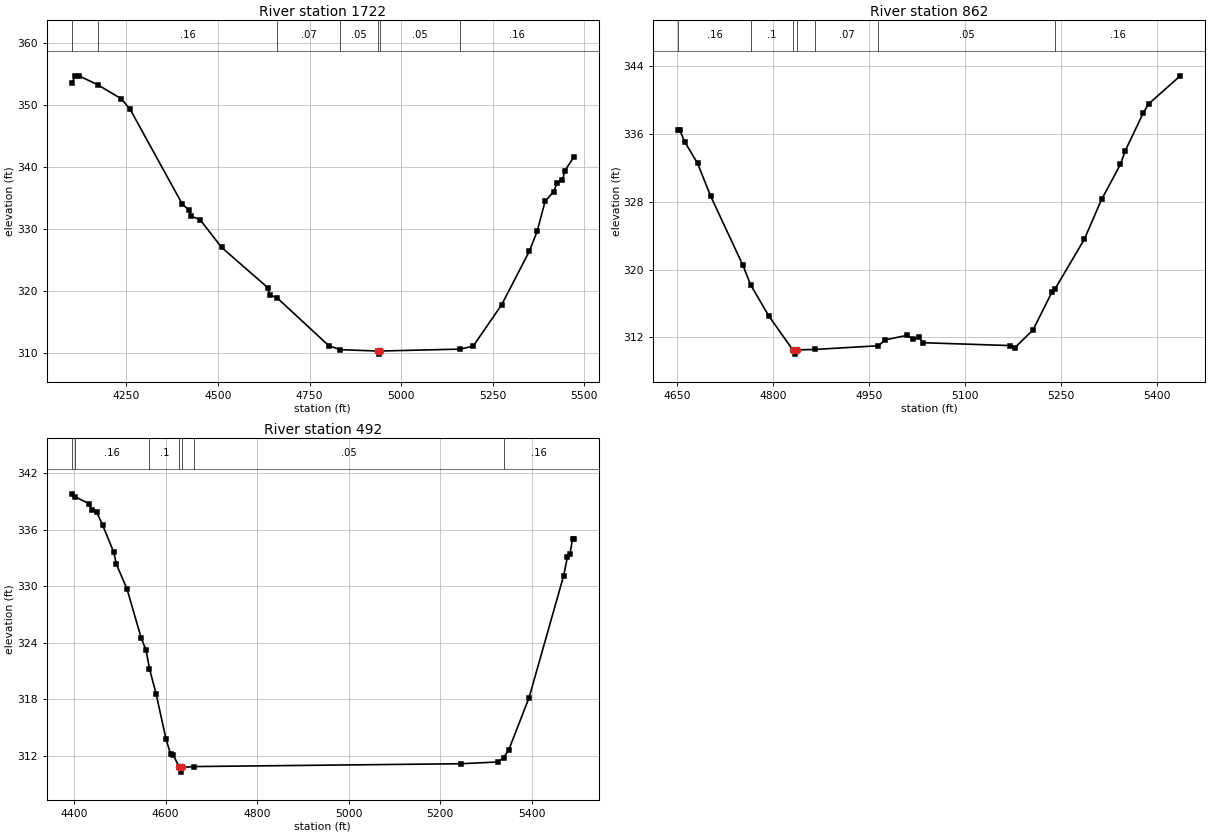
Type RM Length L Ch R = 1,1722,860,860,860
BEGIN DESCRIPTION:
FLAG BRANCH 3.0
END DESCRIPTION:
XS GIS Cut Line= 2
      3554199.01     10373159.60      3553685.12     10371888.77
#Sta/Elev= 30
  4100.6  353.54  4110.1  354.75  4120.0  354.75  4171.7  353.30  4236.1  351.03
  4260.2  349.31  4402.5  334.00  4421.2  333.03  4426.6  332.06  4450.7  331.51
  4509.7  327.02  4635.8  320.51  4641.1  319.36  4661.0  318.88  4802.1  311.14
  4833.1  310.49  4936.8  310.27  4939.5  309.77  4942.8  310.27  5160.8  310.58
  5196.3  311.04  5274.1  317.73  5349.7  326.37  5371.2  329.61  5392.8  334.45
  5416.3  336.04  5425.2  337.35  5440.4  337.89  5446.7  339.39  5471.4  341.64
#Mann=7,-1,0
  4100.6    0.05       0  4171.7    0.16       0  4661.0    0.07       0
  4833.1    0.05       0  4936.8   0.033       0  4942.8    0.05       0
  5160.8    0.16       0
Bank Sta=4936.8,4942.8
Exp/Cntr=0.3,0.1

Type RM Length L Ch R = 1,862,370,370,370
BEGIN DESCRIPTION:
FLAG BRANCH 2.0
END DESCRIPTION:
XS GIS Cut Line= 3
      3554642.11     10372241.65      3554592.11     10371891.64
      3554342.10     10371541.63
#Sta/Elev= 30
  4652.3  336.45  4654.8  336.45  4662.4  335.09  4682.6  332.53  4702.8  328.69
  4753.3  320.49  4765.3  318.19  4793.7  314.51  4831.1  310.50  4833.9  310.00
  4837.1  310.50  4865.0  310.55  4964.8  310.99  4975.6  311.69  5008.9  312.21
  5019.4  311.80  5028.0  311.98  5034.1  311.35  5170.5  311.01  5177.9  310.77
  5206.2  312.87  5235.7  317.35  5240.1  317.66  5286.1  323.56  5313.1  328.28
  5342.6  332.43  5350.0  334.03  5378.2  338.50  5386.8  339.59  5436.0  342.89
#Mann=7,-1,0
  4652.3    0.16       0  4765.3     0.1       0  4831.1   0.033       0
  4837.1     0.1       0  4865.0    0.07       0  4964.8    0.05       0
  5240.1    0.16       0
Bank Sta=4831.1,4837.1
Exp/Cntr=0.3,0.1

Type RM Length L Ch R = 1,492,0,0,0
BEGIN DESCRIPTION:
FLAG BRANCH 1.0
END DESCRIPTION:
XS GIS Cut Line= 3
      3554692.11     10372291.64      3554942.11     10371691.64
      3554542.12     10371491.65
#Sta/Elev= 30
  4395.0  339.80  4402.6  339.48  4433.5  338.74  4438.9  338.07  4449.2  337.89
  4462.7  336.45  4486.5  333.64  4492.5  332.34  4515.8  329.70  4546.7  324.52
  4557.5  323.20  4564.7  321.27  4579.2  318.62  4600.8  313.84  4611.1  312.19
  4616.5  312.13  4630.3  310.80  4633.1  310.30  4636.3  310.80  4661.9  310.89
  5246.2  311.19  5327.3  311.38  5338.7  311.85  5349.7  312.62  5394.4  318.20
  5469.9  331.12  5478.2  333.11  5483.8  333.45  5489.4  335.03  5492.2  335.03
#Mann=7,-1,0
  4395.0    0.05       0  4402.6    0.16       0  4564.7     0.1       0
  4630.3   0.033       0  4636.3     0.1       0  4661.9    0.05       0
  5338.7    0.16       0
Bank Sta=4630.3,4636.3
Exp/Cntr=0.3,0.1

Chan Stop Cuts=-1