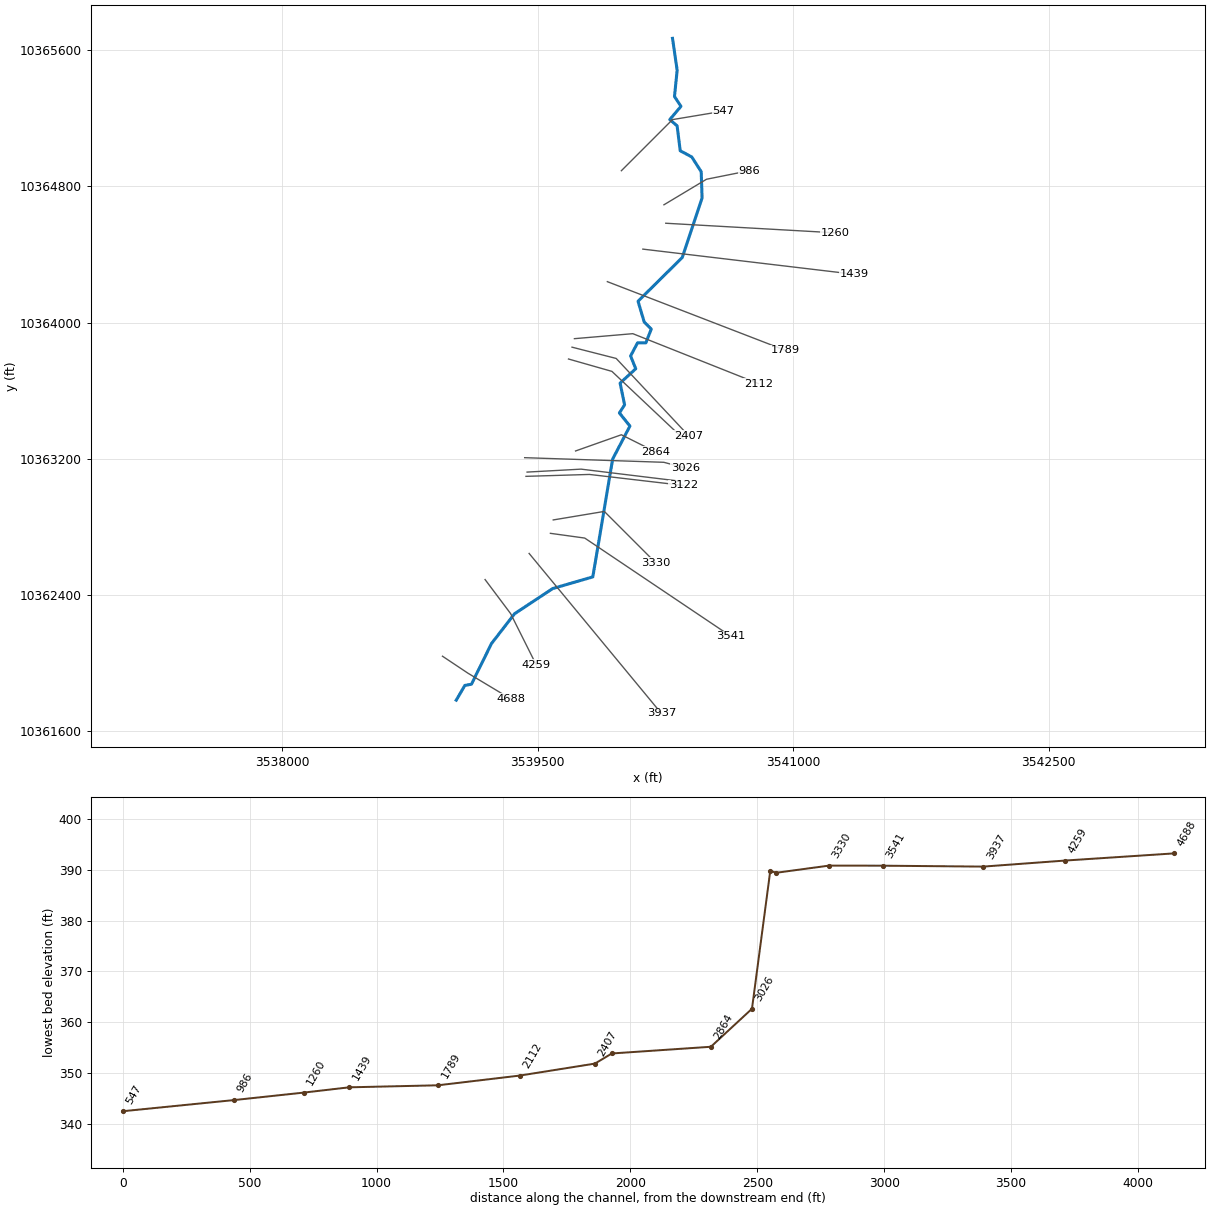
--- GOATHOUSE BRANCH.prj (project) ---

Proj Title=GOATHOUSE BRANCH Base Level Engineering
Current Plan=p01
Default Exp/Contr=0.3,0.1
English Units
Geom File=g01
Flow File=f01
Plan File=p01
BEGIN DESCRIPTION:
GOATHOUSE BRANCH
END DESCRIPTION:

--- GOATHOUSE BRANCH.p01 (plan) ---

Plan Title=Multiple Run
Short Identifier=Multiple
Geom File=g01
Flow File=f01
Subcritical Flow
K Sum by GR= 0
Std Step Tol= 0.01
Critical Tol= 0.01
Num of Std Step Trials= 20
Max Error Tol= 0.3
Flow Tol Ratio= 0.001
Split Flow NTrial= 30
Split Flow Tol= 0.02
Split Flow Ratio= 0.02
Log Output Level= 0
Friction Slope Method= 1
Unsteady Friction Slope Method= 2
Unsteady Bridges Friction Slope Method= 1
Parabolic Critical Depth
Global Vel Dist=  1 , 1 , 1
Global Log Level= 0
CheckData=True
Encroach Param= -1, 0, 0, 0
BEGIN DESCRIPTION:
Multiple Run
END DESCRIPTION:

--- GOATHOUSE BRANCH.f01 (steady flow) ---

Flow Title=Multiple
Number of Profiles=7
Profile Names=10-year,25-year,50-year,1pct_min,100-year,1pct_plu,500-year
River Rch & RM= GOATHOUSE BRANCH,Reach-1,4688
     977    1365    1691    1532    2071    2801    3098
Boundary for River Rch & Prof#=GOATHOUSE BRANCH,Reach-1,1
Up Type=0
Dn Type=3
Dn Slope=0.005
Boundary for River Rch & Prof#=GOATHOUSE BRANCH,Reach-1,2
Up Type=0
Dn Type=3
Dn Slope=0.005
Boundary for River Rch & Prof#=GOATHOUSE BRANCH,Reach-1,3
Up Type=0
Dn Type=3
Dn Slope=0.005
Boundary for River Rch & Prof#=GOATHOUSE BRANCH,Reach-1,4
Up Type=0
Dn Type=3
Dn Slope=0.005
Boundary for River Rch & Prof#=GOATHOUSE BRANCH,Reach-1,5
Up Type=0
Dn Type=3
Dn Slope=0.005
Boundary for River Rch & Prof#=GOATHOUSE BRANCH,Reach-1,6
Up Type=0
Dn Type=3
Dn Slope=0.005
Boundary for River Rch & Prof#=GOATHOUSE BRANCH,Reach-1,7
Up Type=0
Dn Type=3
Dn Slope=0.005

--- GOATHOUSE BRANCH.g01 (geometry) ---

Geom Title=Existing Conditions

River Reach=GOATHOUSE BRANCH,Reach-1
Reach XY= 30
      3539022.91     10361783.77      3539073.47     10361870.34
      3539112.09     10361877.29      3539229.72     10362116.00
      3539365.13     10362290.91      3539589.33     10362438.98
      3539824.53     10362507.32      3539940.99     10363198.99
      3540042.38     10363392.74      3539980.57     10363469.82
      3540011.13     10363517.04      3539984.74     10363644.82
      3540076.55     10363729.20      3540046.23     10363804.26
      3540087.26     10363881.36      3540135.78     10363881.28
      3540167.61     10363962.12      3540126.34     10364003.29
      3540089.94     10364125.27      3540349.74     10364382.53
      3540465.87     10364731.71      3540460.80     10364885.98
      3540405.44     10364972.28      3540337.63     10365008.99
      3540319.38     10365155.04      3540276.29     10365191.93
      3540341.88     10365269.47      3540303.89     10365327.26
      3540319.58     10365481.67      3540292.32     10365668.76

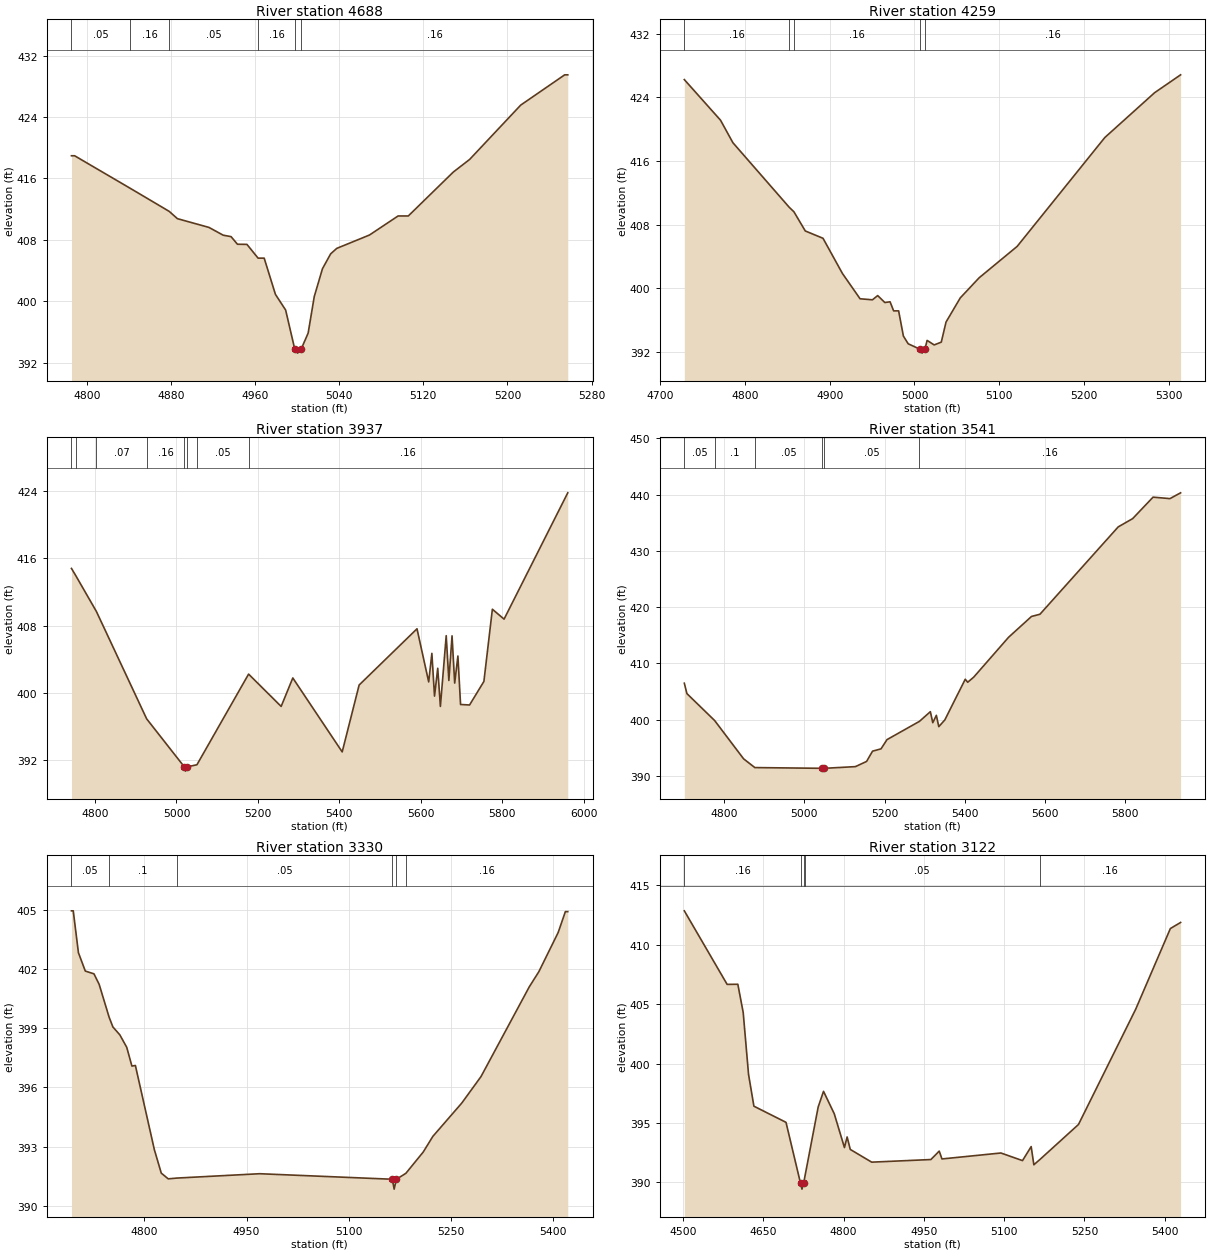
Type RM Length L Ch R = 1,4688,429,429,429
BEGIN DESCRIPTION:
GOATHOUSE BRANCH 10.0
END DESCRIPTION:
XS GIS Cut Line= 3
      3538942.09     10362041.65      3539092.11     10361941.64
      3539342.07     10361791.66
#Sta/Elev= 30
  4785.5  418.95  4788.5  418.95  4840.9  414.75  4878.4  411.71  4886.2  410.76
  4916.2  409.62  4929.7  408.61  4937.2  408.42  4943.3  407.43  4952.3  407.41
  4962.9  405.62  4968.7  405.62  4979.4  400.90  4989.1  398.86  4997.8  393.75
  5000.5  393.25  5003.8  393.75  5010.5  395.86  5016.3  400.61  5024.1  404.24
  5031.9  406.18  5037.7  406.89  5068.8  408.63  5096.0  411.11  5105.7  411.11
  5148.5  416.83  5164.0  418.47  5212.6  425.55  5254.4  429.49  5257.3  429.49
#Mann=6,-1,0
  4785.5    0.05       0  4840.9    0.16       0  4878.4    0.05       0
  4962.9    0.16       0  4997.8    0.07       0  5003.8    0.16       0
Bank Sta=4997.8,5003.8
Exp/Cntr=0.3,0.1

Type RM Length L Ch R = 1,4259,322,322,322
BEGIN DESCRIPTION:
GOATHOUSE BRANCH 9.0
END DESCRIPTION:
XS GIS Cut Line= 3
      3539192.10     10362491.65      3539342.11     10362291.64
      3539492.09     10361991.66
#Sta/Elev= 30
  4728.5  426.21  4771.2  421.11  4785.8  418.28  4852.3  410.16  4857.8  409.60
  4871.2  407.19  4892.1  406.27  4915.0  401.85  4935.8  398.67  4950.4  398.54
  4956.6  399.07  4965.0  398.20  4971.2  398.29  4975.4  397.15  4981.3  397.15
  4986.9  393.99  4992.5  393.02  5006.3  392.34  5009.0  391.84  5012.3  392.34
  5014.9  393.44  5023.2  392.87  5031.6  393.22  5037.2  395.74  5054.0  398.78
  5076.3  401.31  5121.1  405.25  5224.5  418.93  5283.2  424.56  5313.9  426.81
#Mann=5,-1,0
  4728.5    0.16       0  4852.3    0.05       0  4857.8    0.16       0
  5006.3    0.07       0  5012.3    0.16       0
Bank Sta=5006.3,5012.3
Exp/Cntr=0.3,0.1

Type RM Length L Ch R = 1,3937,396,396,396
BEGIN DESCRIPTION:
GOATHOUSE BRANCH 8.0
END DESCRIPTION:
XS GIS Cut Line= 2
      3539450.67     10362644.93      3540226.66     10361706.12
#Sta/Elev= 30
  4742.4  414.80  4753.0  413.94  4803.6  409.67  4926.9  396.88  5019.5  391.15
  5022.2  390.65  5025.5  391.15  5050.3  391.41  5177.1  402.21  5257.0  398.36
  5285.6  401.75  5406.8  392.94  5448.4  400.91  5590.4  407.61  5619.1  401.28
  5626.9  404.68  5633.4  399.59  5641.3  402.91  5647.8  398.36  5662.1  406.79
  5668.6  401.45  5676.4  406.77  5682.9  401.14  5690.8  404.37  5697.3  398.59
  5719.4  398.53  5754.6  401.34  5775.4  409.94  5804.1  408.76  5960.4  423.81
#Mann=8,-1,0
  4742.4    0.16       0  4753.0    0.05       0  4803.6    0.07       0
  4926.9    0.16       0  5019.5    0.07       0  5025.5    0.16       0
  5050.3    0.05       0  5177.1    0.16       0
Bank Sta=5019.5,5025.5
Exp/Cntr=0.3,0.1

Type RM Length L Ch R = 1,3541,211,211,211
BEGIN DESCRIPTION:
GOATHOUSE BRANCH 7.1
END DESCRIPTION:
XS GIS Cut Line= 3
      3539575.66     10362763.01      3539777.04     10362735.23
      3540634.67     10362158.85
#Sta/Elev= 30
  4701.2  406.46  4707.7  404.61  4776.7  399.83  4849.0  393.01  4877.0  391.46
  5044.3  391.33  5047.0  390.83  5050.3  391.33  5127.5  391.63  5155.3  392.55
  5170.2  394.38  5191.3  394.79  5206.2  396.43  5287.1  399.68  5314.3  401.40
  5320.3  399.44  5329.2  400.75  5335.3  398.74  5350.3  399.93  5401.2  407.17
  5407.3  406.63  5422.3  407.54  5509.2  414.63  5566.3  418.33  5587.3  418.72
  5782.3  434.25  5818.3  435.72  5869.2  439.54  5911.3  439.28  5937.8  440.31
#Mann=6,-1,0
  4701.2    0.05       0  4776.7     0.1       0  4877.0    0.05       0
  5044.3   0.033       0  5050.3    0.05       0  5287.1    0.16       0
Bank Sta=5044.3,5050.3
Exp/Cntr=0.3,0.1

Type RM Length L Ch R = 1,3330,208,208,208
BEGIN DESCRIPTION:
GOATHOUSE BRANCH 7.0
END DESCRIPTION:
XS GIS Cut Line= 3
      3539592.09     10362841.64      3539892.11     10362891.64
      3540192.09     10362591.66
#Sta/Elev= 30
  4693.0  404.94  4695.6  404.94  4703.2  402.82  4713.3  401.89  4726.0  401.75
  4733.6  401.22  4748.2  399.56  4753.8  399.06  4764.0  398.66  4774.1  398.03
  4781.7  397.08  4786.8  397.11  4814.7  392.84  4824.8  391.66  4835.0  391.37
  4847.8  391.41  4969.3  391.63  5163.9  391.35  5166.6  390.85  5169.9  391.35
  5183.8  391.65  5209.3  392.73  5223.4  393.52  5265.9  395.21  5294.1  396.55
  5364.9  401.09  5379.0  401.86  5407.3  403.84  5417.9  404.90  5421.4  404.90
#Mann=6,-1,0
  4693.0    0.05       0  4748.2     0.1       0  4847.8    0.05       0
  5163.9   0.033       0  5169.9    0.05       0  5183.8    0.16       0
Bank Sta=5163.9,5169.9
Exp/Cntr=0.3,0.1

Type RM Length L Ch R = 1,3122,24,24,24
BEGIN DESCRIPTION:
GOATHOUSE BRANCH 6.3
END DESCRIPTION:
XS GIS Cut Line= 3
      3539432.15     10363097.53      3539804.70     10363108.73
      3540355.53     10363044.36
#Sta/Elev= 30
  4502.5  412.86  4582.5  406.67  4602.5  406.68  4612.5  404.31  4622.5  399.10
  4632.5  396.42  4692.5  395.06  4719.6  389.94  4722.3  389.44  4725.6  389.94
  4727.2  390.36  4752.6  396.35  4762.6  397.67  4782.6  395.79  4801.7  392.94
  4806.7  393.83  4812.6  392.78  4852.6  391.71  4963.2  391.93  4978.8  392.64
  4983.9  391.98  5094.1  392.48  5134.4  391.84  5150.6  393.02  5155.6  391.49
  5166.6  391.92  5239.0  394.88  5345.8  404.57  5410.7  411.37  5429.8  411.88
#Mann=5,-1,0
  4502.5    0.16       0  4719.6   0.033       0  4725.6    0.16       0
  4727.2    0.05       0  5166.6    0.16       0
Bank Sta=4719.6,4725.6
Exp/Cntr=0.3,0.1

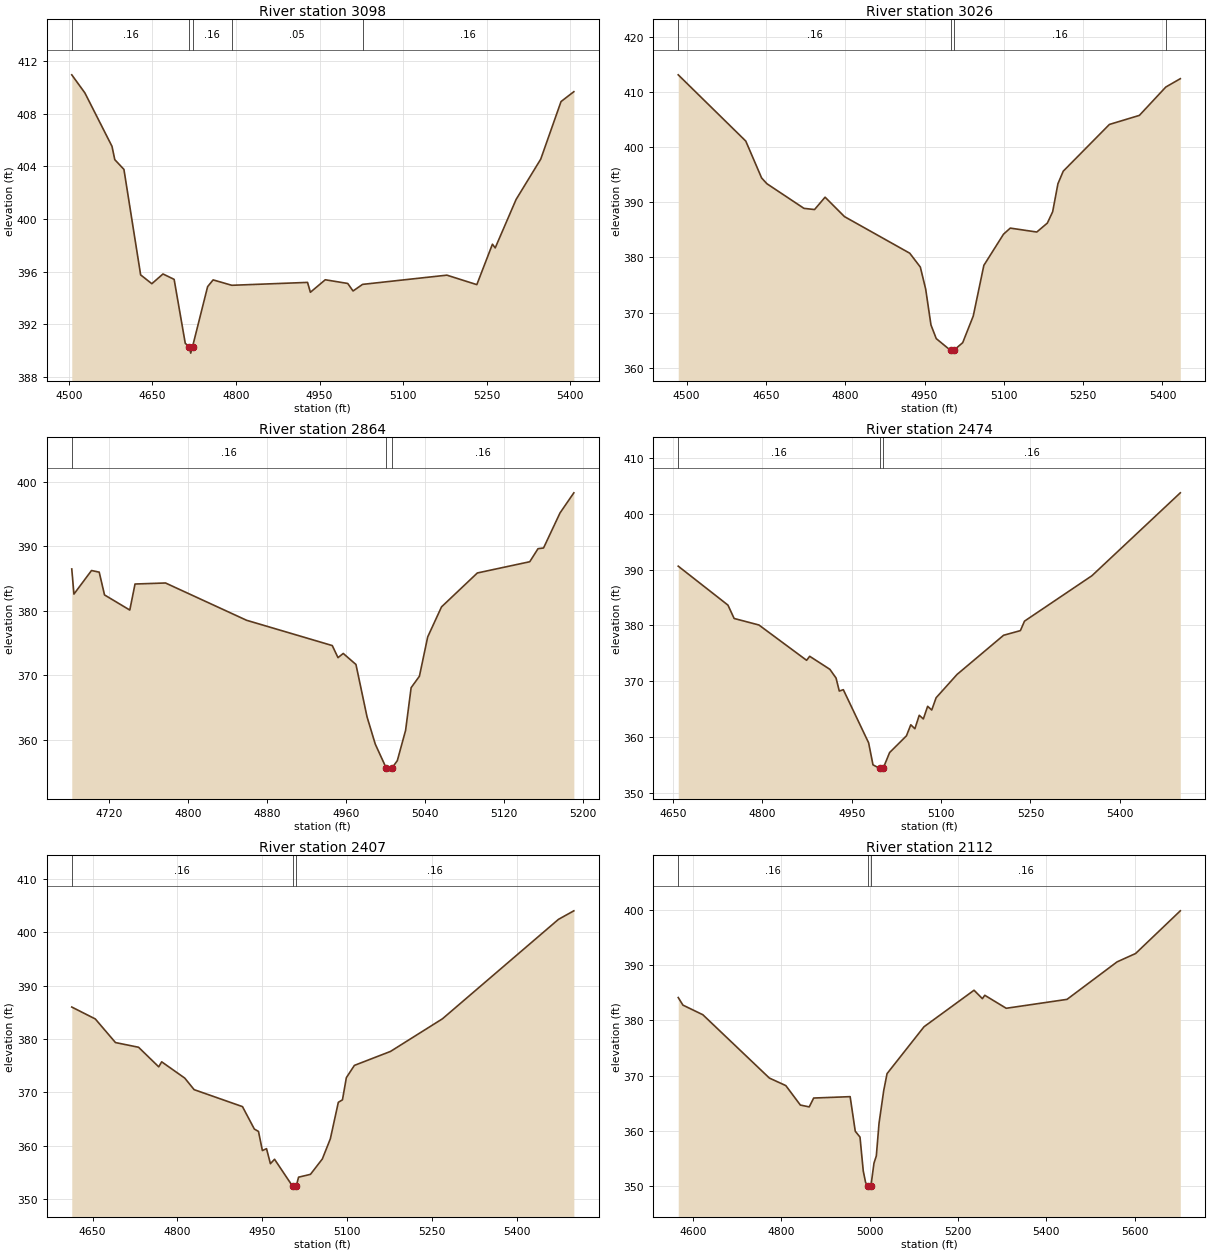
Type RM Length L Ch R = 1,3098,72,72,72
BEGIN DESCRIPTION:
GOATHOUSE BRANCH 6.2
END DESCRIPTION:
XS GIS Cut Line= 3
      3539438.66     10363122.49      3539755.48     10363139.85
      3540334.91     10363069.32
#Sta/Elev= 30
  4505.4  410.94  4528.9  409.57  4577.6  405.51  4582.6  404.50  4599.0  403.76
  4629.0  395.75  4649.1  395.08  4669.1  395.82  4689.1  395.41  4709.1  390.55
  4716.2  390.31  4718.9  389.81  4722.2  390.31  4749.2  394.86  4759.1  395.37
  4792.6  394.96  4928.5  395.18  4933.6  394.43  4960.3  395.38  5000.6  395.10
  5010.2  394.53  5027.3  395.03  5178.6  395.73  5232.3  395.01  5260.3  398.08
  5265.3  397.80  5302.8  401.48  5347.0  404.54  5383.4  408.91  5406.4  409.66
#Mann=5,-1,0
  4505.4    0.16       0  4716.2   0.033       0  4722.2    0.16       0
  4792.6    0.05       0  5027.3    0.16       0
Bank Sta=4716.2,4722.2
Exp/Cntr=0.3,0.1

Type RM Length L Ch R = 1,3026,162,162,162
BEGIN DESCRIPTION:
GOATHOUSE BRANCH 6.1
END DESCRIPTION:
XS GIS Cut Line= 3
      3539424.51     10363207.13      3540241.60     10363180.00
      3540368.94     10363145.75
#Sta/Elev= 30
  4484.3  413.07  4612.0  401.07  4642.0  394.38  4652.0  393.34  4722.0  388.88
  4742.0  388.66  4762.0  390.90  4798.7  387.38  4922.1  380.75  4942.1  378.24
  4952.2  374.25  4962.2  367.76  4972.2  365.28  4999.2  363.15  5001.9  362.65
  5005.2  363.15  5022.2  364.54  5042.2  369.38  5062.2  378.55  5099.4  384.20
  5112.2  385.30  5162.3  384.59  5182.3  386.21  5192.3  388.26  5202.3  393.34
  5212.3  395.61  5299.6  404.08  5356.3  405.72  5406.3  410.86  5433.7  412.37
#Mann=4,-1,0
  4484.3    0.16       0  4999.2    0.07       0  5005.2    0.16       0
  5406.3    0.05       0
Bank Sta=4999.2,5005.2
Exp/Cntr=0.3,0.1

Type RM Length L Ch R = 1,2864,390,390,390
BEGIN DESCRIPTION:
GOATHOUSE BRANCH 6.0
END DESCRIPTION:
XS GIS Cut Line= 3
      3539723.22     10363246.52      3539992.11     10363341.64
      3540192.09     10363241.65
#Sta/Elev= 30
  4681.9  386.46  4684.1  382.57  4701.9  386.22  4709.7  385.97  4715.1  382.44
  4740.7  380.10  4746.0  384.13  4776.9  384.29  4859.0  378.52  4945.9  374.60
  4951.7  372.73  4957.0  373.38  4969.9  371.67  4981.1  363.58  4989.5  359.33
  5000.5  355.66  5003.2  355.16  5006.5  355.66  5011.8  356.78  5020.2  361.47
  5025.8  368.08  5034.2  369.85  5042.6  375.94  5056.6  380.59  5092.9  385.84
  5146.0  387.58  5154.4  389.60  5160.0  389.71  5176.7  395.14  5190.7  398.25
#Mann=3,-1,0
  4681.9    0.16       0  5000.5    0.07       0  5006.5    0.16       0
Bank Sta=5000.5,5006.5
Exp/Cntr=0.3,0.1

Type RM Length L Ch R = 1,2474,67,67,67
BEGIN DESCRIPTION:
Mapping XS 63eae18c
END DESCRIPTION:
XS GIS Cut Line= 3
      3539681.80     10363786.36      3539936.76     10363713.67
      3540357.32     10363316.89
#Sta/Elev= 30
  4658.5  390.64  4742.0  383.65  4752.4  381.25  4794.0  380.08  4874.1  373.74
  4879.3  374.46  4913.2  372.12  4923.6  370.55  4929.0  368.22  4935.8  368.46
  4978.3  358.92  4985.6  354.97  4996.7  354.34  4999.5  353.84  5002.7  354.34
  5013.5  357.17  5041.8  360.18  5049.1  362.16  5056.0  361.45  5063.3  363.87
  5070.2  363.21  5077.4  365.48  5084.3  364.81  5091.6  367.01  5126.8  371.20
  5204.9  378.23  5233.2  379.07  5240.1  380.77  5353.4  388.93  5501.8  403.81
#Mann=3,-1,0
  4658.5    0.16       0  4996.7    0.07       0  5002.7    0.16       0
Bank Sta=4996.7,5002.7
Exp/Cntr=0.3,0.1

Type RM Length L Ch R = 1,2407,295,295,295
BEGIN DESCRIPTION:
Mapping XS 1209311b
END DESCRIPTION:
XS GIS Cut Line= 3
      3539702.43     10363855.80      3539961.72     10363789.62
      3540386.00     10363337.13
#Sta/Elev= 30
  4613.1  385.98  4654.7  383.75  4690.4  379.32  4731.2  378.44  4766.9  374.77
  4772.1  375.71  4812.9  372.66  4829.5  370.49  4915.0  367.31  4936.0  363.10
  4943.3  362.66  4950.2  359.07  4957.5  359.43  4964.4  356.61  4971.7  357.44
  5003.9  352.34  5006.6  351.84  5009.9  352.34  5014.2  354.08  5035.2  354.61
  5056.2  357.49  5070.4  361.28  5084.5  368.12  5091.8  368.58  5098.7  372.74
  5112.9  375.04  5176.8  377.66  5268.7  383.78  5473.8  402.42  5501.0  404.02
#Mann=3,-1,0
  4613.1    0.16       0  5003.9    0.07       0  5009.9    0.16       0
Bank Sta=5003.9,5009.9
Exp/Cntr=0.3,0.1

Type RM Length L Ch R = 1,2112,323,323,323
BEGIN DESCRIPTION:
GOATHOUSE BRANCH 5.0
END DESCRIPTION:
XS GIS Cut Line= 3
      3539716.50     10363905.73      3540059.37     10363935.02
      3540796.14     10363642.05
#Sta/Elev= 30
  4566.2  384.11  4576.9  382.74  4622.0  381.00  4772.6  369.56  4809.8  368.20
  4842.8  364.68  4862.9  364.35  4872.9  365.95  4955.5  366.20  4967.1  359.95
  4977.8  358.90  4985.2  352.78  4990.5  350.69  4996.4  349.99  4999.1  349.49
  5002.4  349.99  5009.5  354.19  5014.8  355.49  5020.9  361.37  5031.6  367.33
  5039.1  370.36  5122.8  378.83  5236.1  385.43  5255.0  383.91  5260.4  384.52
  5309.0  382.17  5446.6  383.78  5559.9  390.55  5602.0  392.07  5703.2  399.78
#Mann=3,-1,0
  4566.2    0.16       0  4996.4    0.07       0  5002.4    0.16       0
Bank Sta=4996.4,5002.4
Exp/Cntr=0.3,0.1

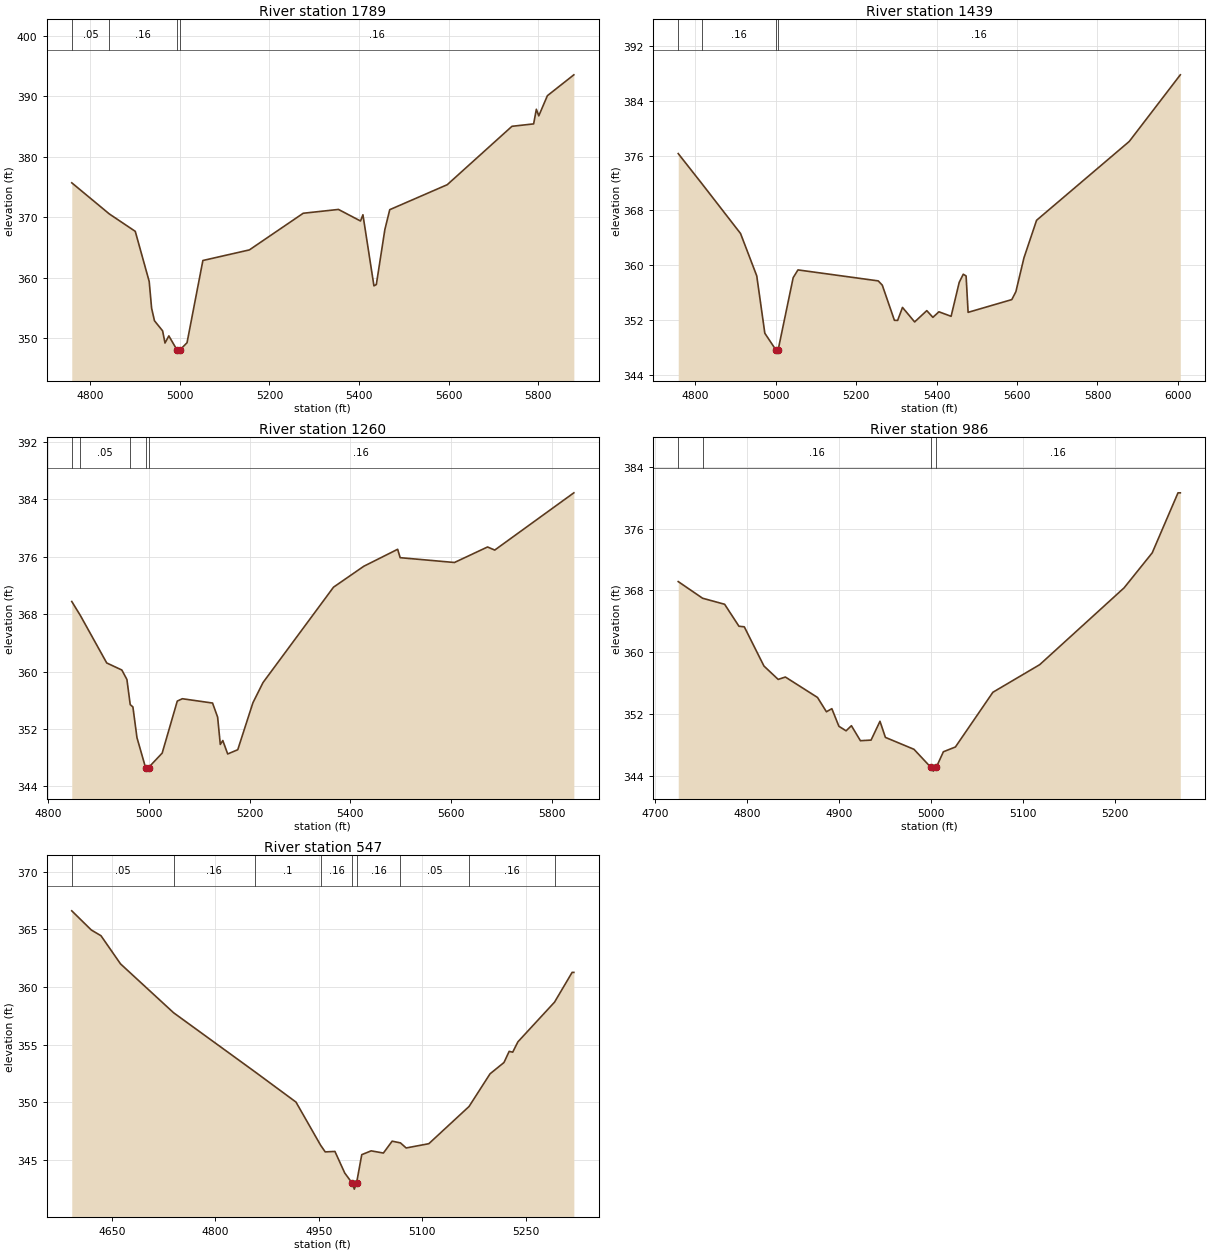
Type RM Length L Ch R = 1,1789,350,350,350
BEGIN DESCRIPTION:
GOATHOUSE BRANCH 4.0
END DESCRIPTION:
XS GIS Cut Line= 2
      3539909.83     10364240.44      3540955.85     10363836.79
#Sta/Elev= 30
  4758.7  375.72  4842.5  370.58  4900.5  367.70  4931.6  359.42  4937.0  354.99
  4943.4  352.92  4961.6  351.25  4966.9  349.24  4975.5  350.42  4993.9  348.07
  4996.7  347.57  4999.9  348.07  5016.1  349.29  5051.5  362.88  5155.3  364.63
  5275.6  370.69  5354.3  371.32  5403.5  369.41  5408.9  370.44  5433.5  358.69
  5438.8  358.90  5457.9  368.00  5468.8  371.28  5597.2  375.41  5741.7  385.06
  5790.1  385.46  5796.2  387.88  5801.6  386.79  5820.8  390.12  5879.9  393.57
#Mann=4,-1,0
  4758.7    0.05       0  4842.5    0.16       0  4993.9    0.07       0
  4999.9    0.16       0
Bank Sta=4993.9,4999.9
Exp/Cntr=0.3,0.1

Type RM Length L Ch R = 1,1439,179,179,179
BEGIN DESCRIPTION:
GOATHOUSE BRANCH 3.0
END DESCRIPTION:
XS GIS Cut Line= 2
      3540118.19     10364431.41      3541358.26     10364283.99
#Sta/Elev= 30
  4757.2  376.28  4816.5  371.86  4912.2  364.62  4952.5  358.44  4972.6  350.07
  4999.8  347.67  5002.6  347.17  5005.8  347.67  5043.1  358.18  5055.0  359.31
  5254.6  357.71  5264.7  357.09  5294.9  351.96  5302.9  351.94  5315.0  353.84
  5345.2  351.72  5375.4  353.37  5390.6  352.39  5405.6  353.20  5435.9  352.54
  5456.0  357.48  5466.1  358.68  5473.2  358.43  5478.2  353.12  5586.9  354.98
  5597.0  356.13  5617.1  361.07  5648.5  366.55  5879.0  378.05  6006.0  387.77
#Mann=4,-1,0
  4757.2     0.1       0  4816.5    0.16       0  4999.8    0.07       0
  5005.8    0.16       0
Bank Sta=4999.8,5005.8
Exp/Cntr=0.3,0.1

Type RM Length L Ch R = 1,1260,274,274,274
BEGIN DESCRIPTION:
GOATHOUSE BRANCH 2.1
END DESCRIPTION:
XS GIS Cut Line= 2
      3540252.72     10364583.32      3541249.02     10364527.01
#Sta/Elev= 30
  4846.4  369.75  4863.4  367.81  4915.9  361.19  4945.9  360.21  4956.0  358.89
  4962.6  355.39  4967.9  355.07  4976.0  350.79  4993.0  346.63  4995.8  346.13
  4999.0  346.63  5026.1  348.64  5056.1  355.88  5066.1  356.21  5126.2  355.61
  5136.3  353.65  5141.6  349.85  5146.6  350.39  5156.3  348.52  5176.3  349.11
  5206.4  355.64  5226.4  358.45  5366.6  371.74  5426.7  374.65  5494.1  377.02
  5499.1  375.85  5607.0  375.18  5672.8  377.34  5687.1  376.91  5844.3  384.88
#Mann=5,-1,0
  4846.4    0.16       0  4863.4    0.05       0  4962.6    0.16       0
  4993.0    0.07       0  4999.0    0.16       0
Bank Sta=4993,4999
Exp/Cntr=0.3,0.1

Type RM Length L Ch R = 1,986,439,439,439
BEGIN DESCRIPTION:
GOATHOUSE BRANCH 2.0
END DESCRIPTION:
XS GIS Cut Line= 3
      3540242.10     10364691.64      3540492.11     10364841.64
      3540742.10     10364891.64
#Sta/Elev= 30
  4725.1  369.15  4751.6  367.00  4775.6  366.22  4791.2  363.38  4797.0  363.31
  4818.4  358.24  4833.9  356.51  4841.7  356.82  4876.7  354.18  4886.4  352.33
  4892.3  352.73  4900.0  350.45  4907.8  349.87  4913.6  350.53  4923.4  348.59
  4935.0  348.67  4944.7  351.10  4950.6  349.02  4981.7  347.48  5000.0  345.16
  5002.8  344.66  5006.0  345.16  5013.7  347.16  5026.8  347.78  5067.6  354.85
  5118.6  358.42  5210.4  368.34  5241.0  372.86  5269.1  380.62  5271.6  380.62
#Mann=4,-1,0
  4725.1    0.05       0  4751.6    0.16       0  5000.0    0.07       0
  5006.0    0.16       0
Bank Sta=5000,5006
Exp/Cntr=0.3,0.1

Type RM Length L Ch R = 1,547,0,0,0
BEGIN DESCRIPTION:
GOATHOUSE BRANCH 1.0
END DESCRIPTION:
XS GIS Cut Line= 3
      3539992.10     10364891.64      3540292.11     10365191.64
      3540592.10     10365241.64
#Sta/Elev= 30
  4591.7  366.60  4620.0  364.94  4634.1  364.44  4662.4  362.00  4739.4  357.76
  4857.6  352.63  4917.0  350.01  4952.7  346.27  4959.4  345.69  4973.5  345.73
  4987.7  343.86  4998.8  342.96  5001.6  342.46  5004.8  342.96  5012.4  345.45
  5026.1  345.78  5043.8  345.59  5056.5  346.62  5068.6  346.47  5076.8  346.03
  5109.7  346.40  5168.1  349.63  5198.5  352.46  5218.7  353.44  5226.3  354.41
  5231.4  354.34  5239.0  355.24  5292.1  358.68  5317.6  361.26  5320.1  361.26
#Mann=9,-1,0
  4591.7    0.05       0  4739.4    0.16       0  4857.6     0.1       0
  4952.7    0.16       0  4998.8    0.07       0  5004.8    0.16       0
  5068.6    0.05       0  5168.1    0.16       0  5292.1     0.1       0
Bank Sta=4998.8,5004.8
Exp/Cntr=0.3,0.1

Chan Stop Cuts=-1