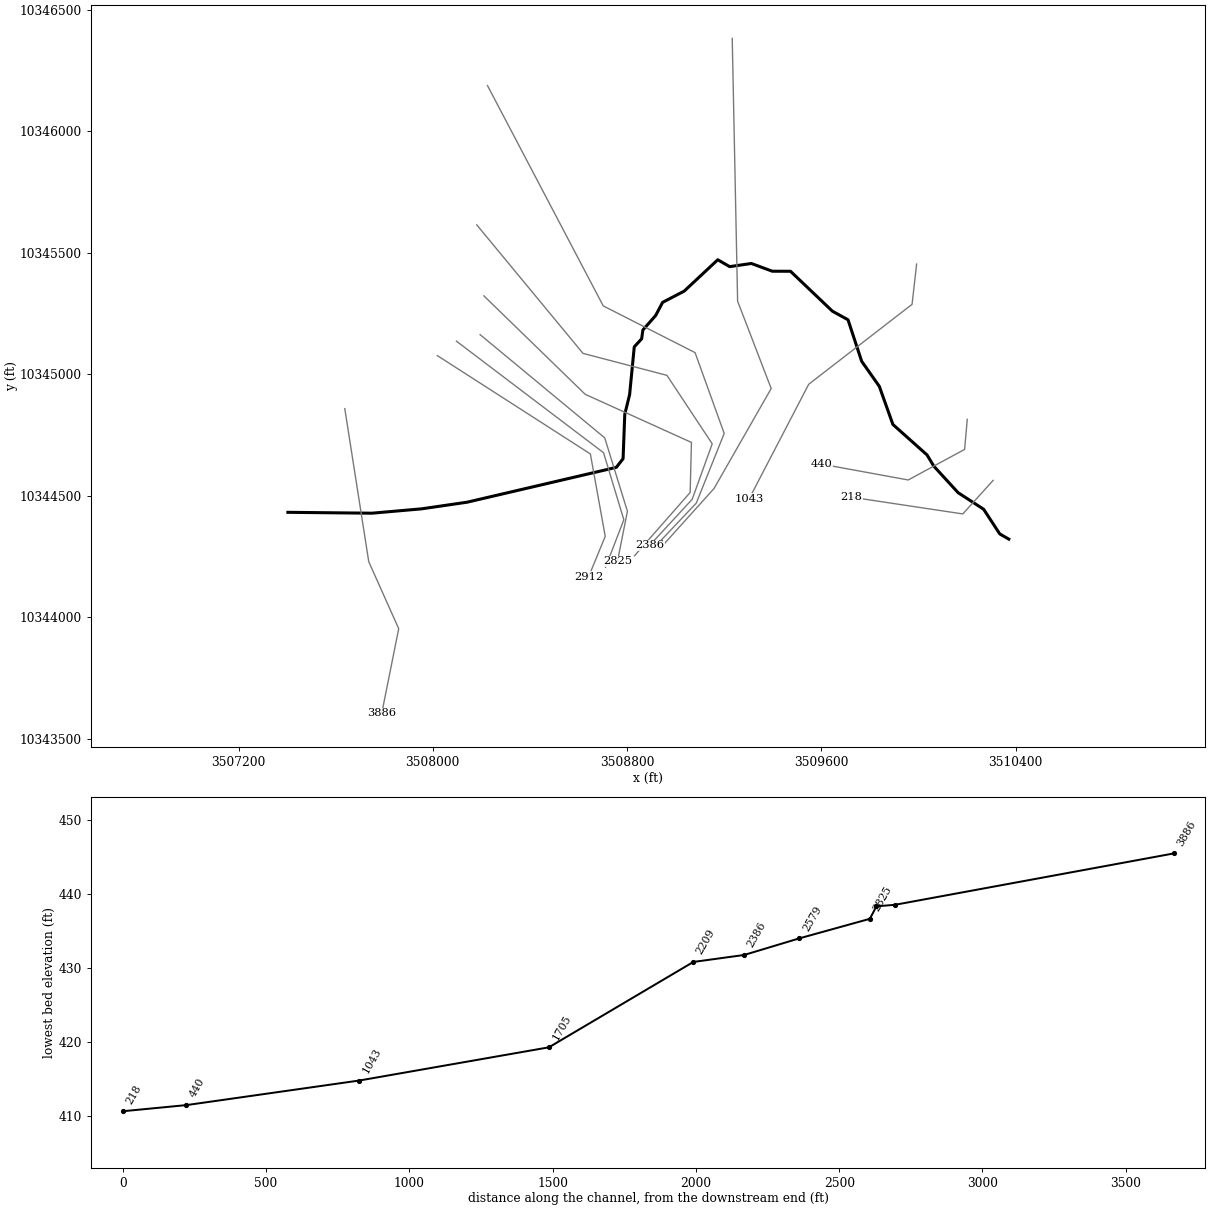
--- HARDIN BRANCH TRIBUTARY 1.prj (project) ---

Proj Title=HARDIN BRANCH TRIBUTARY 1 Base Level Engineering
Current Plan=p01
Default Exp/Contr=0.3,0.1
English Units
Geom File=g01
Flow File=f01
Plan File=p01
Y Axis Title=Elevation
X Axis Title(PF)=Main Channel Distance
X Axis Title(XS)=Station
BEGIN DESCRIPTION:
HARDIN BRANCH TRIBUTARY 1
END DESCRIPTION:
DSS Export Rating Curves= 0
DSS Export Rating Curve Sorted= 0
DSS Export Volume Flow Curves= 0
DXF OffsetX= 0
DXF OffsetY= 0
DXF ScaleX= 1
DXF ScaleY= 10

--- HARDIN BRANCH TRIBUTARY 1.p01 (plan) ---

Plan Title=Multiple Run
Short Identifier=Multiple
Geom File=g01
Flow File=f01
Subcritical Flow
K Sum by GR= 0
Std Step Tol= 0.01
Critical Tol= 0.01
Num of Std Step Trials= 20
Max Error Tol= 0.3
Flow Tol Ratio= 0.001
Split Flow NTrial= 30
Split Flow Tol= 0.02
Split Flow Ratio= 0.02
Log Output Level= 0
Friction Slope Method= 1
Unsteady Friction Slope Method= 2
Unsteady Bridges Friction Slope Method= 1
Parabolic Critical Depth
Global Vel Dist=  1 , 1 , 1
Global Log Level= 0
CheckData=True
Encroach Param= -1, 0, 0, 0
BEGIN DESCRIPTION:
Multiple Run
END DESCRIPTION:

--- HARDIN BRANCH TRIBUTARY 1.f01 (steady flow) ---

Flow Title=Multiple
Number of Profiles=7
Profile Names=10-year,25-year,50-year,1pct_min,100-year,1pct_plu,500-year
River Rch & RM= HARDIN BRANCH TR,Reach-1,3886
     542     740     904     810    1095    1481    1613
Boundary for River Rch & Prof#=HARDIN BRANCH TR,Reach-1,1
Up Type=0
Dn Type=3
Dn Slope=0.005
Boundary for River Rch & Prof#=HARDIN BRANCH TR,Reach-1,2
Up Type=0
Dn Type=3
Dn Slope=0.005
Boundary for River Rch & Prof#=HARDIN BRANCH TR,Reach-1,3
Up Type=0
Dn Type=3
Dn Slope=0.005
Boundary for River Rch & Prof#=HARDIN BRANCH TR,Reach-1,4
Up Type=0
Dn Type=3
Dn Slope=0.005
Boundary for River Rch & Prof#=HARDIN BRANCH TR,Reach-1,5
Up Type=0
Dn Type=3
Dn Slope=0.005
Boundary for River Rch & Prof#=HARDIN BRANCH TR,Reach-1,6
Up Type=0
Dn Type=3
Dn Slope=0.005
Boundary for River Rch & Prof#=HARDIN BRANCH TR,Reach-1,7
Up Type=0
Dn Type=3
Dn Slope=0.005

--- HARDIN BRANCH TRIBUTARY 1.g01 (geometry) ---

Geom Title=Existing Conditions
Program Version=4.10

River Reach=HARDIN BRANCH TR,Reach-1
Reach XY= 30
      3507403.33     10344432.02       3507749.6      10344428.4
      3507954.11     10344446.35      3508141.61     10344473.69
      3508755.88     10344616.99      3508783.66     10344652.58
       3508790.6     10344834.87      3508810.57     10344916.47
      3508829.67     10345112.65      3508860.05     10345145.64
      3508865.26     10345182.09      3508917.69     10345241.43
      3508946.33     10345295.59      3509035.39     10345341.95
      3509173.55     10345470.94      3509222.62     10345442.63
      3509312.02     10345455.59        3509398.     10345423.78
      3509472.97     10345423.62       3509645.8     10345259.26
      3509709.88     10345224.04       3509766.1      10345053.3
      3509838.77     10344950.26      3509894.76     10344793.35
      3510035.18     10344668.19      3510063.38     10344621.71
      3510163.21     10344512.84      3510268.38     10344444.65
      3510334.73      10344343.2      3510372.11     10344321.64

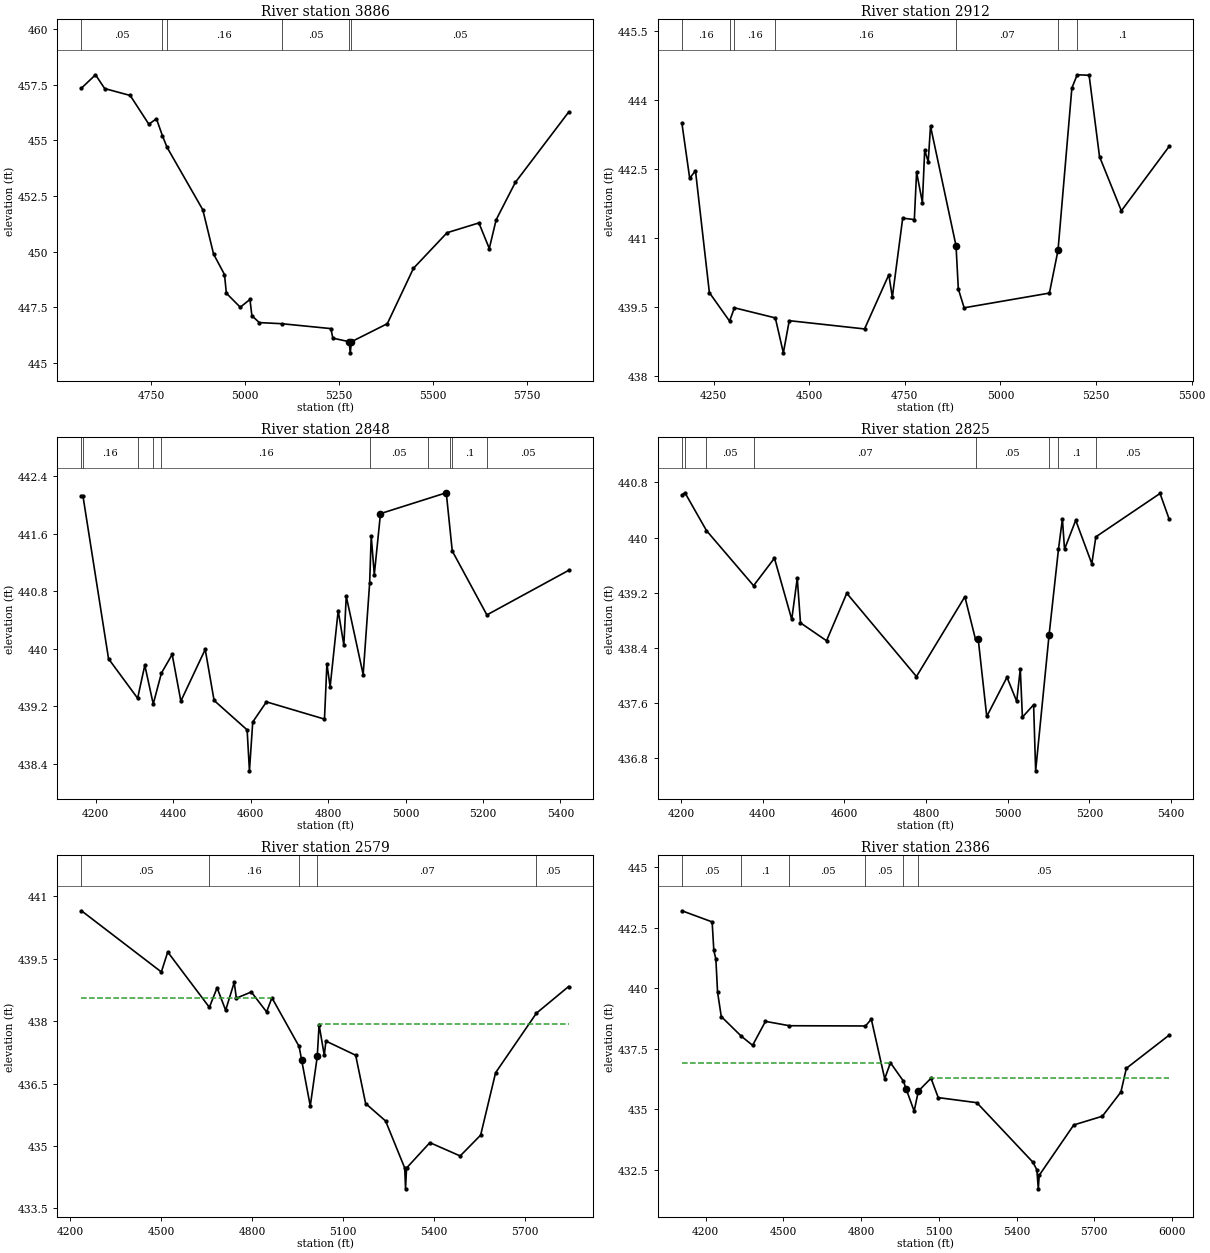
Type RM Length L Ch R = 1 ,3886    ,974,974,974
BEGIN DESCRIPTION:
HARDIN BRANCH TRIBUTARY 1 1.0
END DESCRIPTION:
XS GIS Cut Line= 4
      3507637.67     10344858.52      3507736.39     10344228.82
      3507859.73     10343953.39      3507789.76     10343604.92
#Sta/Elev= 30
  4565.1  457.35  4602.4  457.95  4626.9  457.33  4694.6  457.02  4744.1  455.73
  4764.4  455.97  4780.1  455.22  4792.5  454.69  4887.6  451.88  4916.2  449.89
  4945.2  448.97  4950.2  448.13  4987.1   447.5  5012.9  447.85    5018  447.12
  5037.7  446.81  5096.9  446.76  5227.8  446.54  5233.2  446.11  5276.6  445.95
  5279.4  445.45  5282.6  445.95  5377.9  446.76  5447.4  449.25  5536.7  450.85
  5621.3  451.29  5648.9  450.14  5667.1  451.43    5718  453.11  5859.7  456.27
#Mann= 6 ,-1 , 0
  4565.1     .05       0  4780.1      .1       0  4792.5     .16       0
  5096.9     .05       0  5276.6     .07       0  5282.6     .05       0
Bank Sta=5276.6,5282.6
XS Rating Curve= 0 ,0
Exp/Cntr=0.3,0.1

Type RM Length L Ch R = 1 ,2912    ,64,64,64
BEGIN DESCRIPTION:
HARDIN BRANCH TRIBUTARY 1 1.01
END DESCRIPTION:
XS GIS Cut Line= 4
      3508018.76     10345076.66      3508648.96     10344672.15
      3508710.15     10344333.14      3508641.55     10344166.56
#Sta/Elev= 30
  4167.5  443.49  4187.7   442.3  4202.9  442.46  4239.2  439.81    4292  439.19
  4304.7  439.48  4411.6  439.26  4432.6   438.5    4448   439.2  4644.9  439.02
  4708.3   440.2  4717.5  439.71  4744.6  441.43    4775   441.4  4780.9  442.43
  4796.1  441.77  4802.1  442.91  4811.3  442.66  4817.3  443.43    4884  440.83
    4890  439.89  4905.2  439.48  5128.1   439.8  5150.6  440.73  5186.8  444.26
  5200.7  444.55  5231.9  444.54  5259.1  442.77  5316.2  441.59    5441  442.99
#Mann= 7 ,-1 , 0
  4167.5     .16       0    4292     .05       0  4304.7     .16       0
  4411.6     .16       0    4884     .07       0  5150.6     .05       0
  5200.7      .1       0
Bank Sta=4884,5150.6
XS Rating Curve= 0 ,0
Exp/Cntr=0.3,0.1

Type RM Length L Ch R = 1 ,2848    ,23,23,23
BEGIN DESCRIPTION:
HARDIN BRANCH TRIBUTARY 1 1.10
END DESCRIPTION:
XS GIS Cut Line= 5
      3508097.54     10345135.91      3508374.94     10344925.79
      3508703.22     10344677.14      3508786.77     10344401.53
      3508711.34     10344205.66
#Sta/Elev= 30
  4163.3  442.12  4167.3  442.12  4233.2  439.86  4308.3  439.31  4326.8  439.77
  4348.6  439.23  4369.7  439.66  4397.5  439.92  4419.9  439.27  4482.8  439.99
  4505.7  439.28    4591  438.87    4597   438.3  4605.5  438.98  4640.9  439.26
  4790.7  439.02    4797  439.79  4805.3  439.47  4826.1  440.53  4840.7  440.05
  4846.9  440.73  4890.6  439.64  4907.4  440.92  4911.4  441.57  4919.3  441.03
  4935.3  441.88  5105.1  442.17  5120.6  441.36    5210  440.47    5421  441.09
#Mann= 10 ,-1 , 0
  4163.3      .1       0  4167.3     .16       0  4308.3     .05       0
  4348.6     .16       0  4369.7     .16       0  4907.4     .05       0
  5057.2      .1       0  5115.2     .05       0  5120.6      .1       0
    5210     .05       0
Bank Sta=4935.3,5105.1
XS Rating Curve= 0 ,0
Exp/Cntr=0.3,0.1

Type RM Length L Ch R = 1 ,2825    ,246,246,246
BEGIN DESCRIPTION:
HARDIN BRANCH TRIBUTARY 1 1.02
END DESCRIPTION:
XS GIS Cut Line= 4
      3508194.99     10345162.84      3508708.04     10344738.34
      3508801.52     10344436.26      3508760.43     10344229.82
#Sta/Elev= 30
  4202.7  440.62  4210.1  440.65  4262.8   440.1  4378.1   439.3  4429.1   439.7
  4471.5  438.81    4485  439.41  4492.9  438.76  4556.7   438.5  4606.2  439.19
  4776.8  437.98  4895.3  439.14  4921.4  438.52  4927.9  438.53  4948.9   437.4
  4998.4  437.97  5022.2  437.62    5031  438.09  5036.2  437.39  5063.6  437.57
  5068.6  436.61  5101.4  438.58  5124.5  439.83  5134.1  440.27  5139.3  439.83
  5166.7  440.25  5206.1  439.62    5216  440.01  5373.1  440.64  5395.3  440.27
#Mann= 8 ,-1 , 0
  4202.7     .05       0  4210.1     .16       0  4262.8     .05       0
  4378.1     .07       0  4921.4     .05       0  5101.4     .05       0
  5124.5      .1       0    5216     .05       0
Bank Sta=4927.9,5101.4
XS Rating Curve= 0 ,0
Exp/Cntr=0.3,0.1

Type RM Length L Ch R = 1 ,2579    ,193,193,193
BEGIN DESCRIPTION:
HARDIN BRANCH TRIBUTARY 1 1.03
END DESCRIPTION:
XS GIS Cut Line= 6
      3508210.34     10345322.57      3508627.63     10344917.47
      3508943.75     10344774.46      3509065.13     10344719.55
      3509059.91     10344513.68      3508830.74     10344253.26
#Sta/Elev= 30
  4237.4  440.65    4501  439.18  4522.1  439.66  4659.5  438.33  4684.9   438.8
  4713.2  438.26  4741.5  438.93  4748.5  438.55  4797.9   438.7  4848.3  438.22
  4865.9  438.56  4955.6  437.39  4963.8  437.07  4992.4  435.96  5015.5  437.15
  5021.5  437.91  5038.6  437.18  5044.1  437.52  5142.2  437.18  5175.1  436.02
    5241   435.6  5304.1  434.47  5306.8  433.97  5310.1  434.47  5387.1  435.08
  5487.1  434.76  5554.6  435.26    5604  436.76  5738.7  438.19  5844.9  438.83
#Mann= 5 ,-1 , 0
  4237.4     .05       0  4659.5     .16       0  4955.6    .035       0
  5015.5     .07       0  5738.7     .05       0
#XS Ineff= 2 , 0
       0  4867.2  438.56 5022.03       0  437.92
Permanent Ineff=
       F       T
Bank Sta=4963.8,5015.5
XS Rating Curve= 0 ,0
Exp/Cntr=0.3,0.1

Type RM Length L Ch R = 1 ,2386    ,177,177,177
BEGIN DESCRIPTION:
HARDIN BRANCH TRIBUTARY 1 1.04
END DESCRIPTION:
XS GIS Cut Line= 6
      3508181.08     10345614.48      3508618.58     10345085.84
      3508964.19     10344995.45      3509150.66     10344713.93
       3509068.2     10344485.53      3508893.74     10344296.74
#Sta/Elev= 30
  4108.1  443.21  4224.7  442.75  4231.2  441.57  4239.1  441.21  4245.6  439.85
  4259.9  438.84    4338  438.02    4381  437.65  4430.5  438.64  4523.2  438.46
  4816.8  438.45  4839.3  438.73    4891  436.27  4913.2  436.93  4963.3  436.17
  4973.7  435.85  5004.7  434.93  5020.9  435.76  5069.8  436.29  5097.7  435.49
  5246.7  435.28  5463.3  432.82  5478.4  432.51  5484.1  431.72  5487.6  432.28
    5621  434.36  5731.4  434.72    5803  435.72    5824   436.7  5989.1  438.07
#Mann= 6 ,-1 , 0
  4108.1     .05       0    4338      .1       0  4523.2     .05       0
  4816.8     .05       0  4963.3    .035       0  5020.9     .05       0
#XS Ineff= 2 , 0
       0  4914.6  436.93 5066.83       0  436.29
Permanent Ineff=
       F       T
Bank Sta=4973.7,5020.9
XS Rating Curve= 0 ,0
Exp/Cntr=0.3,0.1

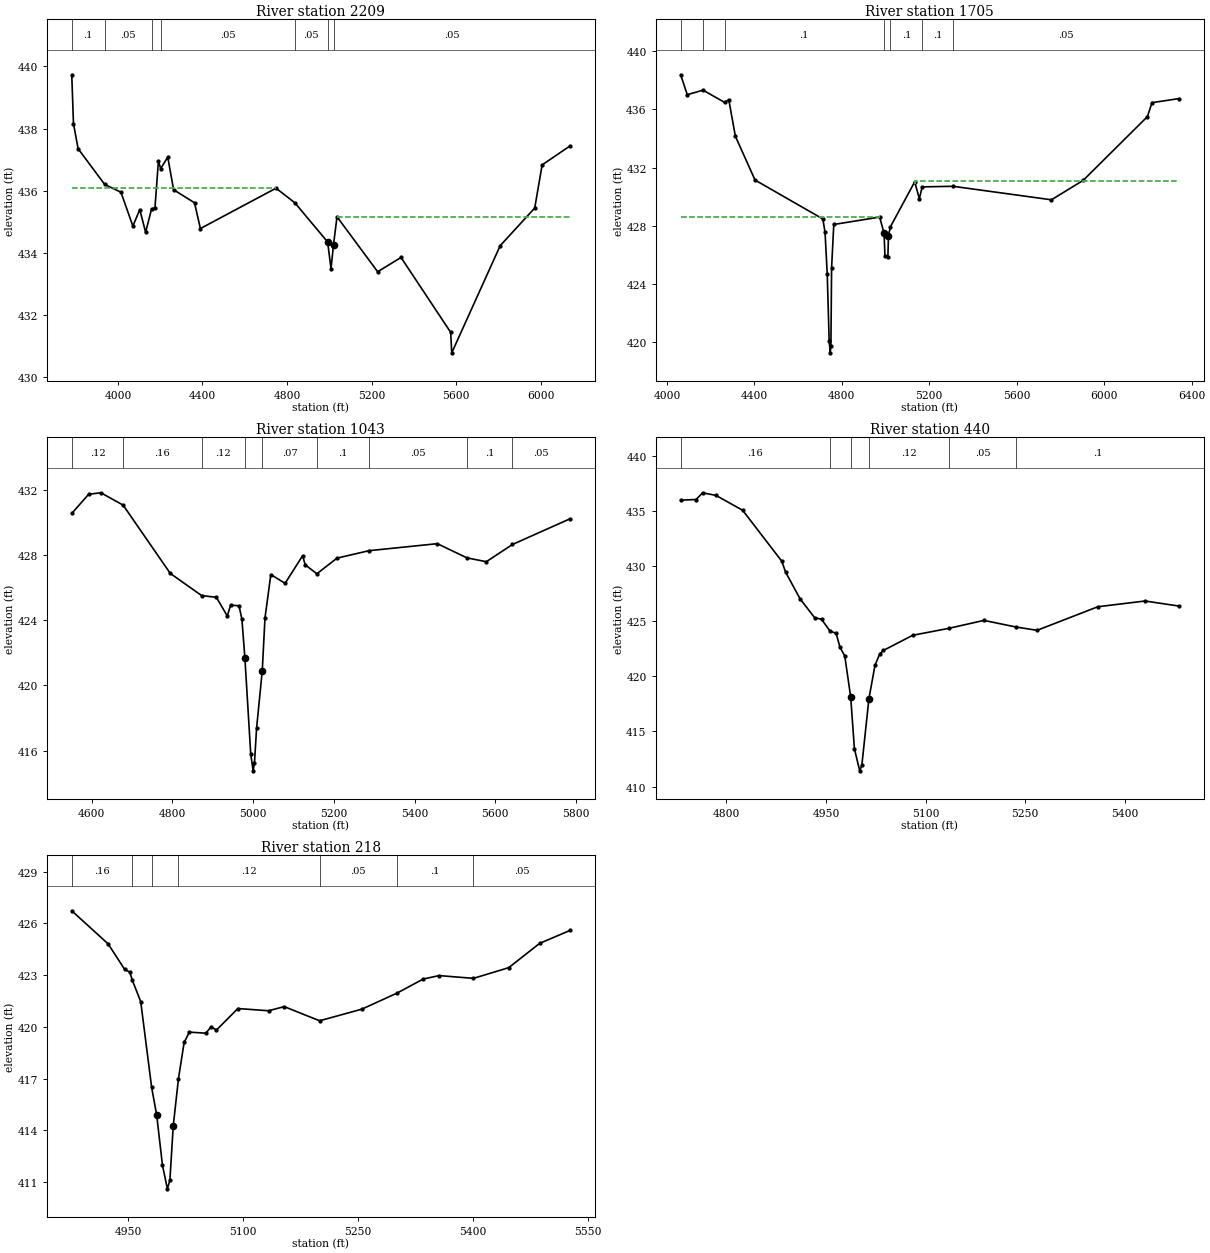
Type RM Length L Ch R = 1 ,2209    ,504,504,504
BEGIN DESCRIPTION:
HARDIN BRANCH TRIBUTARY 1 1.05
END DESCRIPTION:
XS GIS Cut Line= 6
      3508225.36     10346187.39      3508701.92     10345281.15
      3509080.14     10345088.88      3509200.02     10344756.57
      3509085.13     10344469.91      3508915.83     10344291.56
#Sta/Elev= 30
  3781.9  439.73  3789.9  438.16  3811.9  437.35  3937.7   436.2  4014.4  435.95
  4070.9  434.86  4103.5  435.39  4131.2  434.66  4159.2  435.41  4175.3  435.45
  4191.7  436.95  4202.4  436.71  4235.8  437.08  4263.5  436.03  4362.4  435.61
  4390.1  434.78  4747.8  436.08  4836.8  435.61  4991.7  434.35  5007.9  433.49
  5019.6  434.26  5036.2  435.16  5228.4  433.39  5338.9  433.85  5573.7  431.44
  5578.8  430.78  5807.9  434.23  5971.1  435.44  6006.3  436.83  6138.1  437.44
#Mann= 7 ,-1 , 0
  3781.9      .1       0  3937.7     .05       0  4159.2      .1       0
  4202.4     .05       0  4836.8     .05       0  4991.7    .035       0
  5019.6     .05       0
#XS Ineff= 2 , 0
       0 4749.43  436.08 5037.13       0  435.16
Permanent Ineff=
       F       T
Bank Sta=4991.7,5019.6
XS Rating Curve= 0 ,0
Exp/Cntr=0.3,0.1

Type RM Length L Ch R = 1 ,1705    ,662,662,662
BEGIN DESCRIPTION:
HARDIN BRANCH TRIBUTARY 1 1.06
END DESCRIPTION:
XS GIS Cut Line= 5
      3509233.11      10346381.6      3509255.27     10345300.46
      3509393.56     10344941.28      3509158.05      10344529.8
      3508931.49      10344278.5
#Sta/Elev= 30
  4063.1  438.39  4093.1  437.02  4165.4  437.33  4263.6  436.49  4283.1  436.67
  4313.1  434.16  4403.1  431.14  4713.2  428.46  4723.2  427.55  4733.2   424.7
  4742.1  420.08  4746.9  419.24  4750.1  419.74  4753.2  425.09  4763.2  428.08
  4973.2  428.59  4993.2  427.46 4997.28   425.9 5010.66  425.83  5013.3  427.32
  5022.2  427.92  5133.3  431.02  5154.4  429.86  5167.7  430.67  5308.7  430.71
  5758.7  429.78    5904  431.12  6197.6  435.51  6218.5  436.47  6341.8  436.75
#Mann= 7 ,-1 , 0
  4063.1     .05       0  4165.4      .1       0  4263.6      .1       0
  4993.2     .03       0  5022.2      .1       0  5167.7      .1       0
  5308.7     .05       0
#XS Ineff= 2 , 0
       0 4973.27  428.59 5135.52       0  431.08
Permanent Ineff=
       T       F
Bank Sta=4993.2,5013.3
XS Rating Curve= 0 ,0
Exp/Cntr=0.3,0.1

Type RM Length L Ch R = 1 ,1043    ,603,603,603
BEGIN DESCRIPTION:
HARDIN BRANCH TRIBUTARY 1 1.07
END DESCRIPTION:
XS GIS Cut Line= 4
       3509992.4     10345453.27      3509973.66     10345287.57
      3509548.04     10344958.74      3509303.32     10344488.74
#Sta/Elev= 30
  4550.8  430.58  4592.7  431.76  4622.9  431.85  4678.1  431.09  4794.9  426.89
  4872.5  425.53  4909.1  425.42  4936.2  424.27  4944.4  424.94  4965.2   424.9
  4972.3  424.08  4979.7  421.71  4994.2  415.78  5000.2  414.75  5003.5  415.25
  5008.7  417.37  5022.8  420.91  5029.5  424.15    5044  426.82  5079.3  426.28
  5122.8  427.98  5129.1  427.42  5158.1  426.87  5207.9  427.83  5287.4  428.29
  5456.5  428.72  5529.6  427.85  5577.8  427.61  5642.6  428.67  5785.3  430.25
#Mann= 9 ,-1 , 0
  4550.8     .12       0  4678.1     .16       0  4872.5     .12       0
  4979.7     .03       0  5022.8     .07       0  5158.1      .1       0
  5287.4     .05       0  5529.6      .1       0  5642.6     .05       0
Bank Sta=4979.7,5022.8
XS Rating Curve= 0 ,0
Exp/Cntr=0.3,0.1

Type RM Length L Ch R = 1 ,440     ,222,222,222
BEGIN DESCRIPTION:
HARDIN BRANCH TRIBUTARY 1 1.08
END DESCRIPTION:
XS GIS Cut Line= 4
      3510200.92     10344814.62      3510190.07     10344690.92
      3509957.86     10344565.05      3509601.96     10344630.16
#Sta/Elev= 30
  4731.4  435.99  4754.5  436.05  4764.5  436.66  4784.6  436.42  4824.7  435.07
  4883.6  430.45  4889.3  429.46  4911.2  427.03    4933  425.33  4943.5  425.18
  4956.2  424.11  4965.4  423.91  4971.1  422.66  4978.4  421.85  4987.3  418.14
  4992.9  413.44  5000.9  411.43  5004.1  411.93  5014.8  417.99  5023.9     421
    5031  422.04  5036.7  422.36  5080.7  423.73    5135  424.36  5187.9  425.08
  5236.2  424.48  5267.9  424.18  5359.4  426.32  5430.5  426.84  5481.5  426.38
#Mann= 6 ,-1 , 0
  4731.4     .16       0  4956.2     .12       0  4987.3     .03       0
  5014.8     .12       0    5135     .05       0  5236.2      .1       0
Bank Sta=4987.3,5014.8
XS Rating Curve= 0 ,0
Exp/Cntr=0.3,0.1

Type RM Length L Ch R = 1 ,218     ,0,0,0
BEGIN DESCRIPTION:
HARDIN BRANCH TRIBUTARY 1 1.09
END DESCRIPTION:
XS GIS Cut Line= 3
      3510307.52     10344563.45      3510182.51     10344425.42
      3509722.89     10344494.43
#Sta/Elev= 30
    4876  426.73  4923.5  424.81  4945.1  423.33  4951.9  423.17  4955.2  422.69
  4966.1  421.46  4980.3   416.5    4987  414.86  4994.5  411.97  5000.9   410.6
  5004.2   411.1  5008.6  414.26  5015.4  416.99  5022.8  419.09  5029.6  419.69
  5051.2  419.63    5058     420    5065  419.81    5093  421.06  5133.1  420.93
  5153.6  421.17  5199.8  420.35  5254.8  421.02  5300.3  421.94  5335.2  422.77
  5355.9  422.97  5400.8  422.81  5446.9  423.43  5487.3  424.84    5527  425.59
#Mann= 7 ,-1 , 0
    4876     .16       0  4955.2     .12       0  4980.3     .03       0
  5015.4     .12       0  5199.8     .05       0  5300.3      .1       0
  5400.8     .05       0
Bank Sta=4987,5008.6
XS Rating Curve= 0 ,0
Exp/Cntr=0.3,0.1

Chan Stop Cuts=-1
Use User Specified Reach Order=0
Composite Channel Slope=5