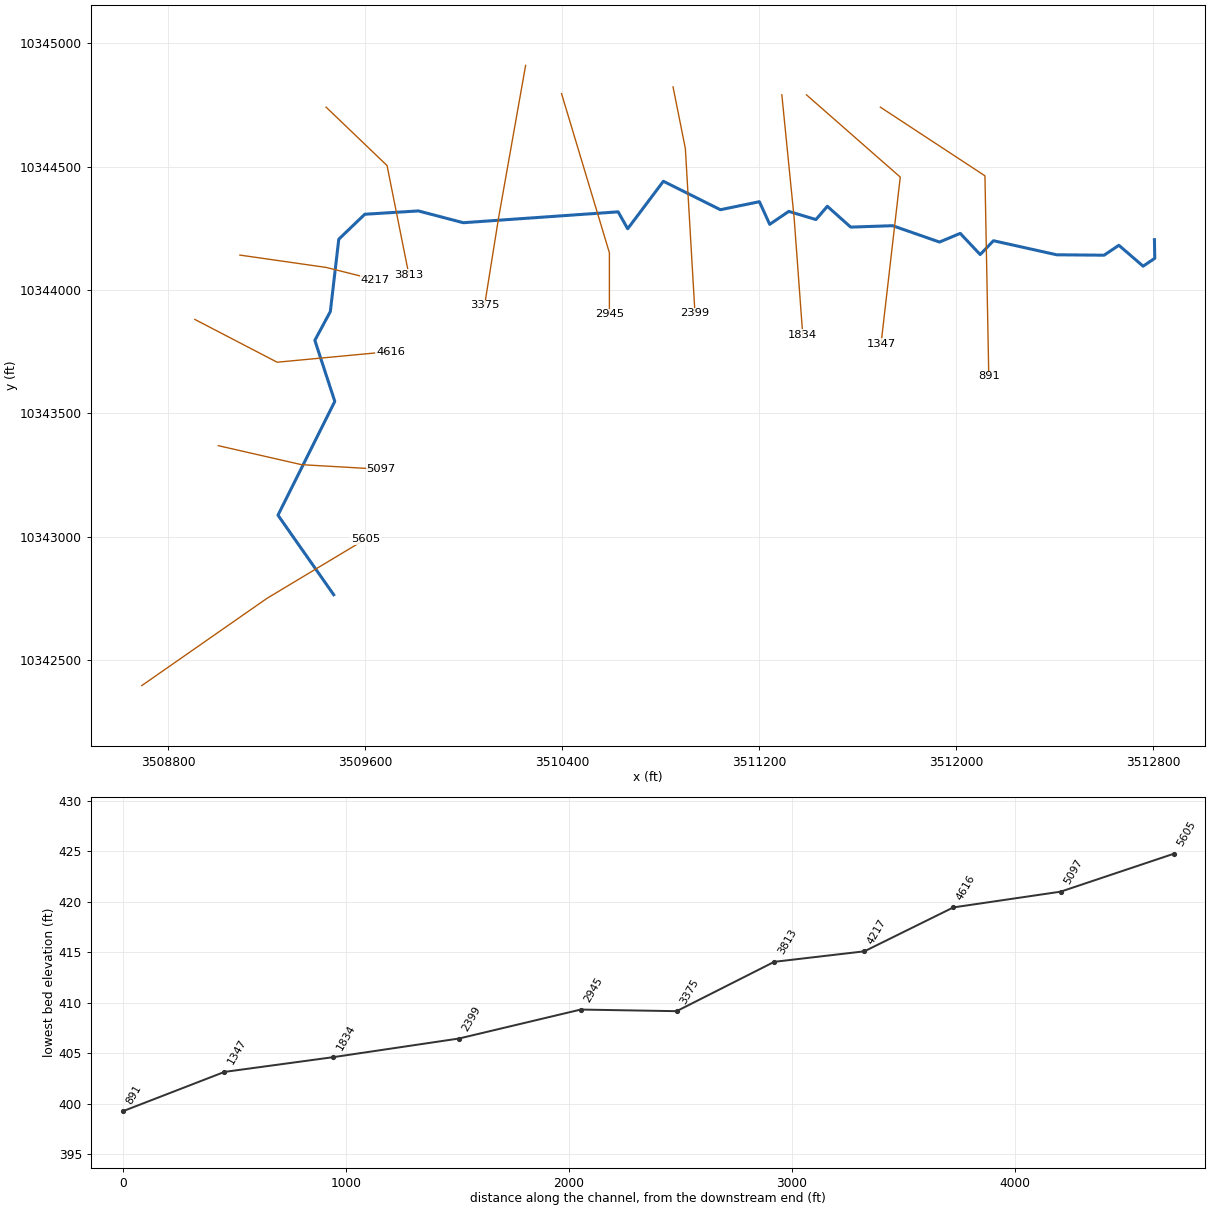
--- HARDIN BRANCH.prj (project) ---

Proj Title=HARDIN BRANCH Base Level Engineering
Current Plan=p01
Default Exp/Contr=0.3,0.1
English Units
Geom File=g01
Flow File=f01
Plan File=p01
Y Axis Title=Elevation
X Axis Title(PF)=Main Channel Distance
X Axis Title(XS)=Station
BEGIN DESCRIPTION:
HARDIN BRANCH
END DESCRIPTION:
DSS Export Rating Curves= 0
DSS Export Rating Curve Sorted= 0
DSS Export Volume Flow Curves= 0
DXF OffsetX= 0
DXF OffsetY= 0
DXF ScaleX= 1
DXF ScaleY= 10

--- HARDIN BRANCH.p01 (plan) ---

Plan Title=Multiple Run
Short Identifier=Multiple
Geom File=g01
Flow File=f01
Subcritical Flow
K Sum by GR= 0
Std Step Tol= 0.01
Critical Tol= 0.01
Num of Std Step Trials= 20
Max Error Tol= 0.3
Flow Tol Ratio= 0.001
Split Flow NTrial= 30
Split Flow Tol= 0.02
Split Flow Ratio= 0.02
Log Output Level= 0
Friction Slope Method= 1
Unsteady Friction Slope Method= 2
Unsteady Bridges Friction Slope Method= 1
Parabolic Critical Depth
Global Vel Dist=  1 , 1 , 1
Global Log Level= 0
CheckData=True
Encroach Param= -1, 0, 0, 0
BEGIN DESCRIPTION:
Multiple Run
END DESCRIPTION:

--- HARDIN BRANCH.f01 (steady flow) ---

Flow Title=Multiple
Program Version=4.10
Number of Profiles= 7
Profile Names=10-year,25-year,50-year,1pct_min,100-year,1pct_plu,500-year
River Rch & RM=HARDIN BRANCH,Reach-1         ,5605
     475     638     771     682     923    1248    1326
River Rch & RM=HARDIN BRANCH,Reach-1         ,3375
     916    1278    1581    1432    1936    2619    2913
River Rch & RM=HARDIN BRANCH,Reach-1         ,2945
     916    1278    1581    1432    1936    2619    2913
Boundary for River Rch & Prof#=HARDIN BRANCH,Reach-1         , 1
Up Type= 0
Dn Type= 3
Dn Slope=0.005
Boundary for River Rch & Prof#=HARDIN BRANCH,Reach-1         , 2
Up Type= 0
Dn Type= 3
Dn Slope=0.005
Boundary for River Rch & Prof#=HARDIN BRANCH,Reach-1         , 3
Up Type= 0
Dn Type= 3
Dn Slope=0.005
Boundary for River Rch & Prof#=HARDIN BRANCH,Reach-1         , 4
Up Type= 0
Dn Type= 3
Dn Slope=0.005
Boundary for River Rch & Prof#=HARDIN BRANCH,Reach-1         , 5
Up Type= 0
Dn Type= 3
Dn Slope=0.005
Boundary for River Rch & Prof#=HARDIN BRANCH,Reach-1         , 6
Up Type= 0
Dn Type= 3
Dn Slope=0.005
Boundary for River Rch & Prof#=HARDIN BRANCH,Reach-1         , 7
Up Type= 0
Dn Type= 3
Dn Slope=0.005
DSS Import GetInterval= 0
DSS Import GetPeak= 0
DSS Import FillOption= 0

--- HARDIN BRANCH.g01 (geometry) ---

Geom Title=Existing Conditions
Program Version=4.10

River Reach=HARDIN BRANCH   ,Reach-1
Reach XY= 30
      3509472.89     10342764.03      3509246.74     10343086.68
      3509477.43     10343548.34      3509396.42     10343795.86
      3509459.34     10343912.76      3509493.57     10344206.03
      3509599.19     10344307.29       3509816.7     10344320.79
      3509999.06     10344272.94       3510627.6     10344317.08
       3510666.3     10344248.33      3510811.25     10344441.05
      3511042.71     10344325.68      3511201.06     10344358.14
      3511242.83     10344266.32      3511320.25     10344318.89
      3511430.61     10344285.77      3511476.73     10344339.62
      3511571.52     10344255.15      3511741.76     10344260.85
      3511932.05     10344194.55      3512016.33     10344229.69
       3512097.3     10344143.83      3512151.23      10344199.9
      3512407.77     10344142.87      3512600.33      10344141.2
      3512660.17     10344181.42      3512758.78     10344096.69
        3512806.     10344128.64      3512804.61     10344204.33

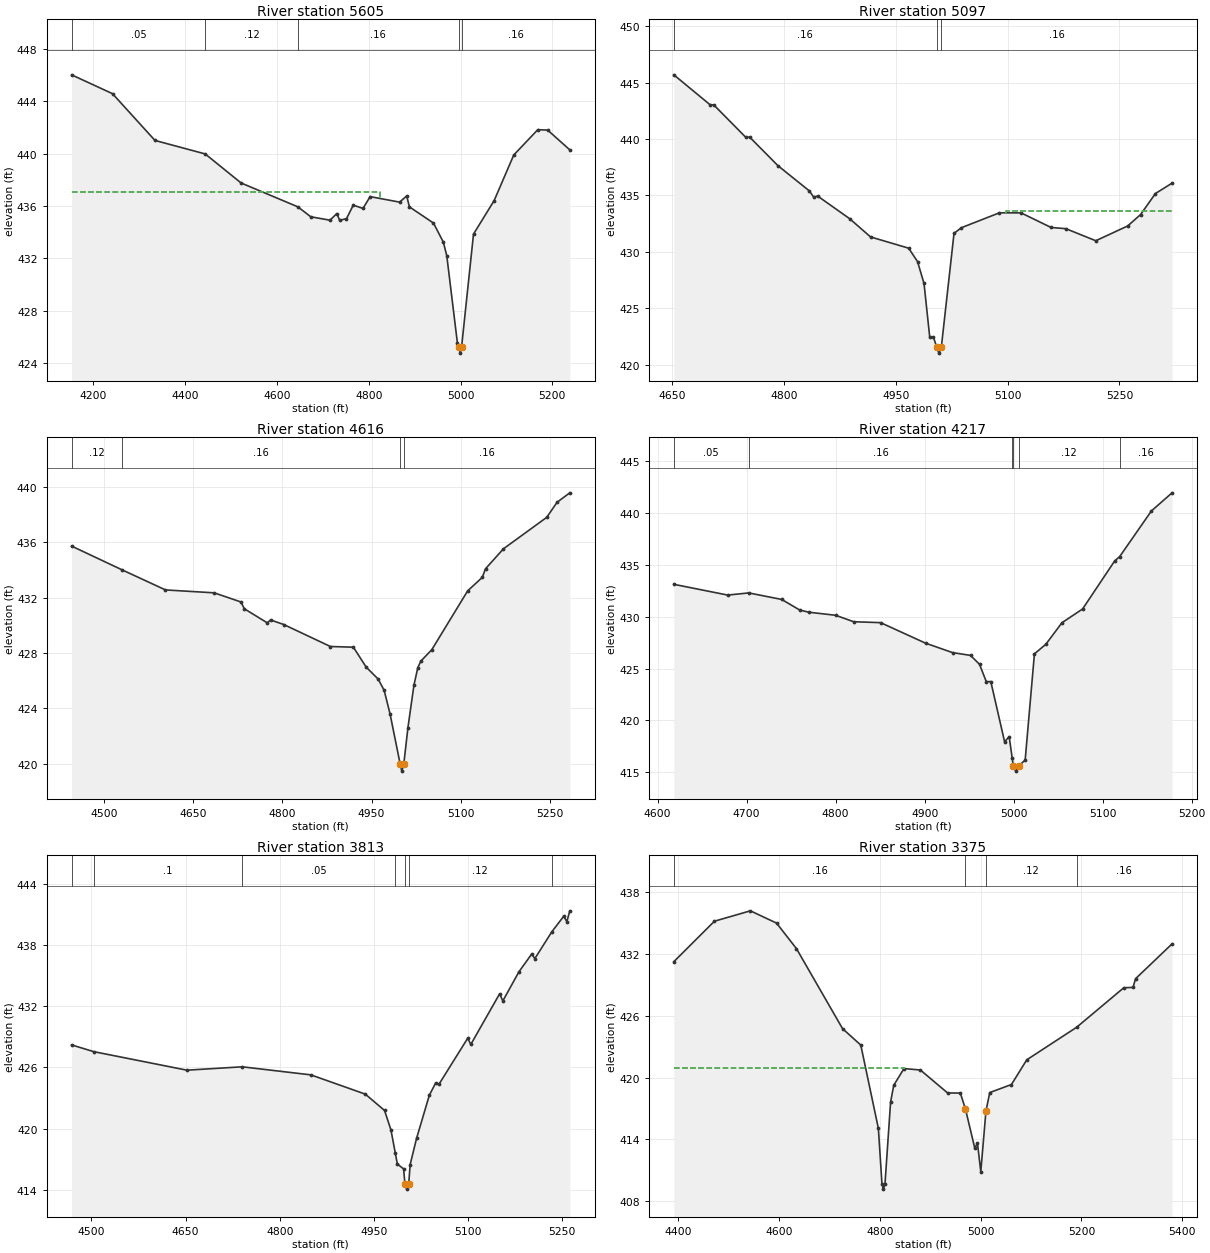
Type RM Length L Ch R = 1 ,5605    ,508,508,508
BEGIN DESCRIPTION:
HARDIN BRANCH 11.0
END DESCRIPTION:
XS GIS Cut Line= 3
      3508694.01     10342395.57      3509202.66     10342749.72
        3509602.     10342989.32
#Sta/Elev= 30
  4152.6  446.02  4241.8  444.58  4334.3  441.01  4443.7  439.98    4522  437.76
  4645.6  435.94  4673.8  435.18  4715.7  434.92  4730.5  435.43  4736.6  434.92
  4751.5  435.03  4766.3  436.07  4787.5  435.82  4803.1  436.72  4867.2   436.3
  4882.8  436.77  4888.6  435.94  4941.1   434.7  4962.5  433.25    4970  432.22
  4993.3  425.52  4996.4  425.27  4999.2  424.77  5002.4  425.27  5028.3  433.86
  5073.3  436.42    5116   439.9  5168.3  441.83  5189.9   441.8  5238.1  440.29
#Mann= 5 ,-1 , 0
  4152.6     .05       0  4443.7     .12       0  4645.6     .16       0
  4996.4     .07       0  5002.4     .16       0
#XS Ineff= 2 , 0
         4824.09  437.05
Permanent Ineff=
       F       F
Bank Sta=4996.4,5002.4
XS Rating Curve= 0 ,0
Exp/Cntr=0.3,0.1

Type RM Length L Ch R = 1 ,5097    ,481,481,481
BEGIN DESCRIPTION:
HARDIN BRANCH 10.0
END DESCRIPTION:
XS GIS Cut Line= 3
      3509004.64     10343368.57      3509342.11     10343291.64
      3509664.35     10343273.09
#Sta/Elev= 30
  4651.8   445.7  4700.4  443.05  4705.5  443.03  4748.5  440.15  4753.7  440.17
  4791.6  437.64  4833.8   435.4  4839.7  434.84  4844.8  434.95  4887.8  432.94
  4915.9  431.32  4967.1  430.32    4979  429.13  4987.7  427.19  4995.4  422.42
  5000.4  422.42  5004.9  421.51  5007.7  421.01  5010.9  421.51    5028  431.64
    5038  432.14    5089  433.46  5118.1  433.45  5158.2  432.16  5178.2  432.05
  5218.3  430.98  5261.1  432.29  5278.4   433.3  5298.4  435.17  5320.7  436.09
#Mann= 3 ,-1 , 0
  4651.8     .16       0  5004.9     .07       0  5010.9     .16       0
#XS Ineff= 2 , 0
                         5097.27          433.59
Permanent Ineff=
       F       F
Bank Sta=5004.9,5010.9
XS Rating Curve= 0 ,0
Exp/Cntr=0.3,0.1

Type RM Length L Ch R = 1 ,4616    ,399,399,399
BEGIN DESCRIPTION:
HARDIN BRANCH 9.0
END DESCRIPTION:
XS GIS Cut Line= 3
      3508909.12     10343880.74      3509243.34     10343707.12
      3509703.37     10343750.52
#Sta/Elev= 30
  4445.1  435.72  4529.2  434.02  4603.2  432.55  4685.1  432.34  4730.2  431.68
  4735.9  431.19  4774.5  430.17  4780.1  430.38  4802.2  430.05  4880.8  428.46
  4919.5  428.41    4941  426.97  4961.1  426.11  4971.2   425.3  4981.2  423.59
  4998.3  419.95    5001  419.45  5004.3  419.95  5011.3  422.59  5021.4  425.66
    5028  426.94    5033   427.4  5051.5  428.23  5111.8  432.48  5136.5  433.46
  5141.9  434.08    5172  435.52    5245   437.8  5262.4  438.89  5283.8  439.57
#Mann= 4 ,-1 , 0
  4445.1     .12       0  4529.2     .16       0  4998.3     .07       0
  5004.3     .16       0
Bank Sta=4998.3,5004.3
XS Rating Curve= 0 ,0
Exp/Cntr=0.3,0.1

Type RM Length L Ch R = 1 ,4217    ,404,404,404
BEGIN DESCRIPTION:
HARDIN BRANCH 8.0
END DESCRIPTION:
XS GIS Cut Line= 3
      3509092.14     10344141.64      3509442.11     10344091.64
      3509642.14     10344041.63
#Sta/Elev= 30
  4618.2  433.13  4678.8  432.09  4702.3   432.3  4739.4  431.67  4759.6  430.65
  4769.7  430.44    4800  430.14  4820.2  429.52  4850.5  429.43    4901  427.45
  4931.3  426.54  4951.5  426.27  4961.6  425.41  4969.2  423.74  4974.3  423.74
  4989.8  417.93  4994.9  418.43  4998.4  416.32  4999.6   415.6  5002.4   415.1
  5005.6   415.6  5012.9  416.17  5023.3  426.42  5036.1  427.34  5054.2  429.42
  5077.4  430.75  5113.4  435.38  5119.1  435.81  5154.7  440.21  5177.9  441.96
#Mann= 6 ,-1 , 0
  4618.2     .05       0  4702.3     .16       0  4998.4     .12       0
  4999.6     .07       0  5005.6     .12       0  5119.1     .16       0
Bank Sta=4999.6,5005.6
XS Rating Curve= 0 ,0
Exp/Cntr=0.3,0.1

Type RM Length L Ch R = 1 ,3813    ,438,438,438
BEGIN DESCRIPTION:
HARDIN BRANCH 7.0
END DESCRIPTION:
XS GIS Cut Line= 3
      3509442.12     10344741.62      3509689.52     10344504.86
      3509778.06     10344062.16
#Sta/Elev= 30
  4468.3   428.2  4503.3  427.54  4652.1  425.72  4740.2  426.05  4849.6  425.26
  4936.4  423.37    4967  421.77  4977.2  419.86  4984.2  417.57  4987.4  416.52
  4997.4  416.04  4999.5  414.56  5002.3  414.06  5005.5  414.56  5007.8  416.47
    5018  419.03  5038.4  423.27  5048.4  424.46  5053.5  424.32  5099.4  428.84
  5104.5  428.25  5150.4  433.21  5155.5  432.51  5181.1  435.36  5201.4   437.1
  5206.5  436.66  5233.6  439.29  5252.4   440.8  5257.5  440.29  5262.2  441.34
#Mann= 7 ,-1 , 0
  4468.3     .05       0  4503.3      .1       0  4740.2     .05       0
  4984.2     .12       0  4999.5     .07       0  5005.5     .12       0
  5233.6     .16       0
Bank Sta=4999.5,5005.5
XS Rating Curve= 0 ,0
Exp/Cntr=0.3,0.1

Type RM Length L Ch R = 1 ,3375    ,430,430,430
BEGIN DESCRIPTION:
HARDIN BRANCH 6.0
END DESCRIPTION:
XS GIS Cut Line= 3
      3510252.01     10344911.09      3510142.11     10344291.64
      3510085.35     10343937.18
#Sta/Elev= 30
  4391.5  431.26    4472  435.19  4543.3   436.2  4595.2  435.01  4634.7  432.53
  4726.1  424.76  4762.3  423.16  4797.2  415.06  4804.3  409.67  4807.1  409.17
  4810.3  409.67  4821.4  417.62  4827.7  419.26    4848  420.88  4880.5  420.74
  4934.5  418.51  4959.7   418.5  4969.8  416.97  4988.5  413.12  4993.6  413.67
  5000.3  410.86  5010.5  416.74  5018.1  418.55  5061.1  419.33  5091.5  421.73
  5190.4  424.89  5283.9  428.73  5302.2  428.76  5307.3  429.61  5379.6  432.99
#Mann= 4 ,-1 , 0
  4391.5     .16       0  4969.8     .07       0  5010.5     .12       0
  5190.4     .16       0
#XS Ineff= 2 , 0
         4847.05  420.94
Permanent Ineff=
       F       F
Bank Sta=4969.8,5010.5
XS Rating Curve= 0 ,0
Exp/Cntr=0.3,0.1

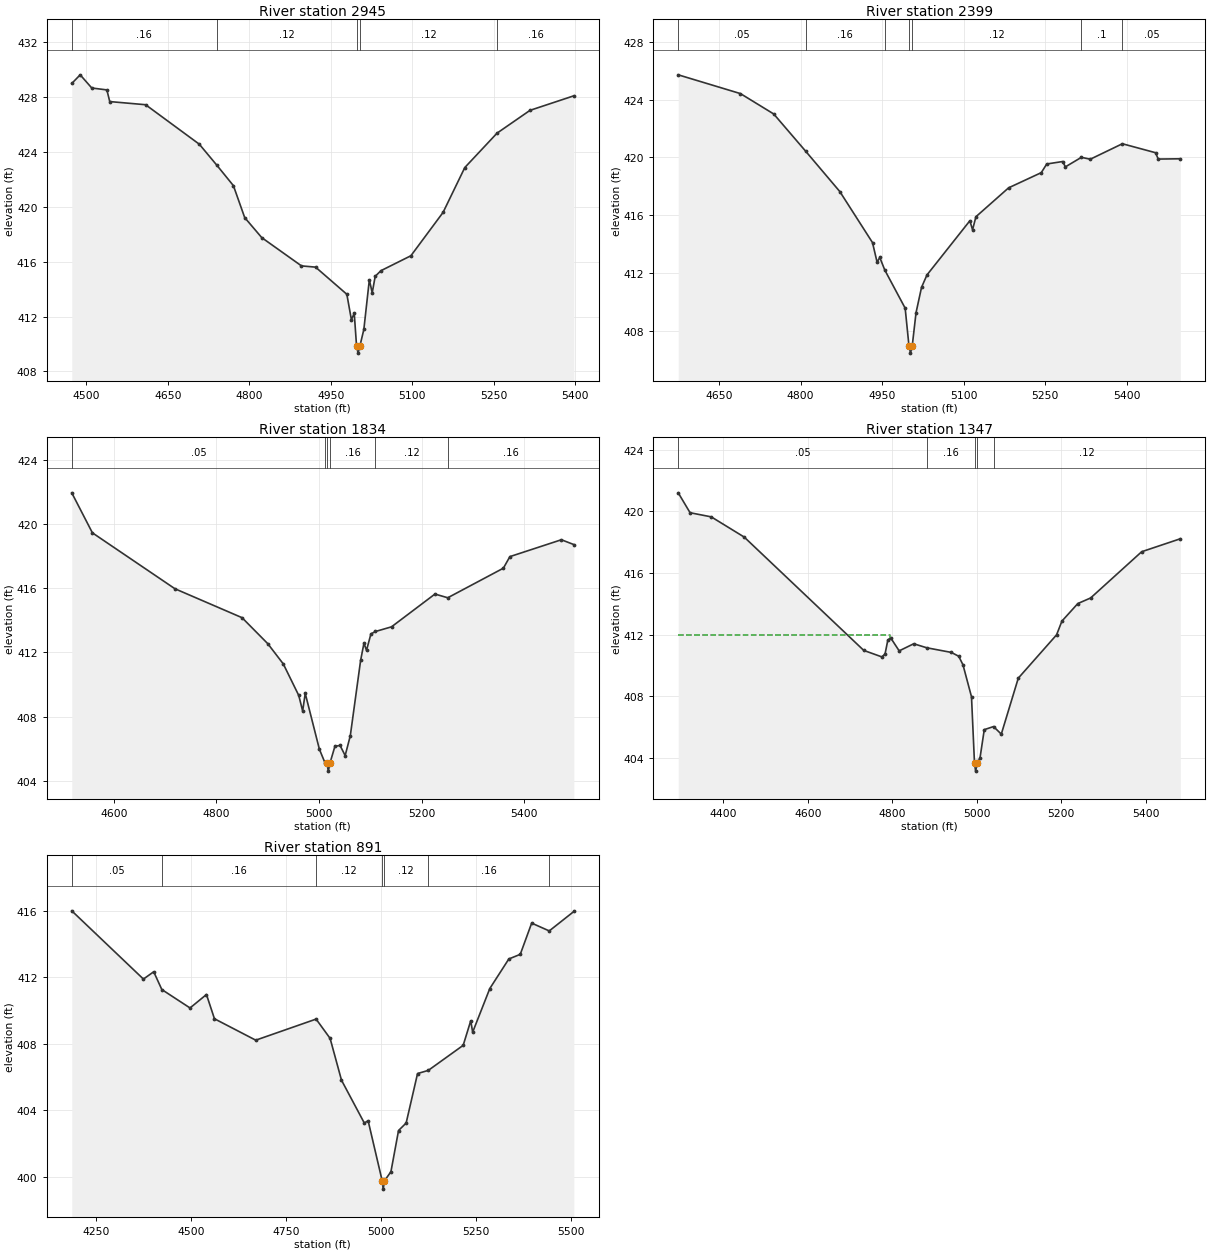
Type RM Length L Ch R = 1 ,2945    ,546,546,546
BEGIN DESCRIPTION:
HARDIN BRANCH 5.0
END DESCRIPTION:
XS GIS Cut Line= 3
      3510397.86     10344796.48      3510592.11     10344151.02
      3510592.11     10343900.97
#Sta/Elev= 30
  4473.4  428.99  4488.9  429.62  4510.2  428.66    4538  428.52  4543.3  427.67
  4609.3  427.44  4708.2  424.56  4740.2  423.04  4770.9  421.54  4791.7  419.21
  4823.1  417.75  4896.2  415.69  4922.1   415.6  4979.7  413.62  4988.1  411.76
  4993.3  412.24  4997.6  409.83  5000.4  409.33  5003.6  409.83    5011  411.06
  5021.1  414.68  5026.4  413.73  5031.9  414.93  5042.4  415.34  5097.6  416.43
  5156.8  419.59  5196.8  422.86  5256.2  425.37  5316.8  427.03  5397.5  428.09
#Mann= 5 ,-1 , 0
  4473.4     .16       0  4740.2     .12       0  4997.6     .07       0
  5003.6     .12       0  5256.2     .16       0
Bank Sta=4997.6,5003.6
XS Rating Curve= 0 ,0
Exp/Cntr=0.3,0.1

Type RM Length L Ch R = 1 ,2399    ,565,565,565
BEGIN DESCRIPTION:
HARDIN BRANCH 4.0
END DESCRIPTION:
XS GIS Cut Line= 3
      3510850.44     10344823.93      3510900.44     10344573.93
      3510939.49     10343906.32
#Sta/Elev= 30
  4574.8  425.72  4689.3  424.42  4750.5  423.01  4809.1  420.44  4872.1  417.64
  4932.2  414.11  4940.6  412.76  4945.6  413.08  4954.8  412.21  4992.3  409.57
  4999.3  406.96  5002.1  406.46  5005.3  406.96  5012.3  409.26  5022.4  411.01
  5032.4  411.87  5111.3  415.62  5116.3     415  5122.5   415.9  5182.6   417.9
  5242.7  418.95  5252.8  419.55  5282.1  419.72  5287.1  419.35  5316.5  420.01
  5332.9  419.88  5391.9  420.95  5452.9  420.33  5457.9  419.89  5498.5  419.91
#Mann= 7 ,-1 , 0
  4574.8     .05       0  4809.1     .16       0  4954.8     .12       0
  4999.3     .07       0  5005.3     .12       0  5316.5      .1       0
  5391.9     .05       0
Bank Sta=4999.3,5005.3
XS Rating Curve= 0 ,0
Exp/Cntr=0.3,0.1

Type RM Length L Ch R = 1 ,1834    ,487,487,487
BEGIN DESCRIPTION:
HARDIN BRANCH 3.0
END DESCRIPTION:
XS GIS Cut Line= 3
       3511292.1     10344791.69      3511342.11     10344291.64
      3511377.02     10343817.37
#Sta/Elev= 30
  4518.2  421.93  4558.4  419.44  4719.2  415.96  4849.9  414.16  4900.1  412.54
  4930.3  411.28  4960.4  409.32    4968  408.35    4973  409.45  5000.6  405.97
  5011.6  405.12  5015.2  405.11    5018  404.61  5021.2  405.11  5030.8  406.15
  5040.8  406.21  5050.8  405.58  5060.8  406.81  5080.9   411.5  5087.4  412.57
  5092.4  412.13    5101  413.15  5109.8   413.3  5141.1  413.59  5225.7  415.63
  5250.7   415.4    5359  417.24  5371.7  417.96    5472  419.01  5496.3  418.71
#Mann= 6 ,-1 , 0
  4518.2     .05       0  5011.6     .16       0  5015.2     .03       0
  5021.2     .16       0  5109.8     .12       0  5250.7     .16       0
Bank Sta=5015.2,5021.2
XS Rating Curve= 0 ,0
Exp/Cntr=0.3,0.1

Type RM Length L Ch R = 1 ,1347    ,456,456,456
BEGIN DESCRIPTION:
HARDIN BRANCH 2.0
END DESCRIPTION:
XS GIS Cut Line= 3
      3511392.14     10344791.61      3511772.85     10344457.99
      3511694.72     10343780.89
#Sta/Elev= 30
  4293.6   421.2  4321.6  419.91  4371.8  419.64  4449.7  418.33  4732.5  410.98
  4775.2  410.56  4782.8  410.74  4789.4  411.64    4796   411.8  4816.3  410.95
  4850.7  411.41  4881.6  411.15  4939.6  410.85  4957.2   410.6  4967.3  410.04
  4987.4  407.97  4994.5  403.65  4997.2  403.15  5000.5  403.65  5007.5     404
  5017.6  405.84  5039.5  406.04  5057.9  405.55  5098.1  409.18  5188.7  411.99
  5201.3  412.88    5239  414.02  5269.2  414.38    5390  417.38  5481.4  418.22
#Mann= 5 ,-1 , 0
  4293.6     .05       0  4881.6     .16       0  4994.5     .07       0
  5000.5     .16       0  5039.5     .12       0
#XS Ineff= 2 , 0
            4795  411.98
Permanent Ineff=
       F       F
Bank Sta=4994.5,5000.5
XS Rating Curve= 0 ,0
Exp/Cntr=0.3,0.1

Type RM Length L Ch R = 1 ,891     ,0,0,0
BEGIN DESCRIPTION:
HARDIN BRANCH 1.0
END DESCRIPTION:
XS GIS Cut Line= 3
       3511692.1     10344741.65       3512116.6     10344463.19
      3512132.22     10343650.72
#Sta/Elev= 30
  4186.7  416.01  4375.1   411.9  4402.2  412.34  4423.5  411.27  4497.7  410.16
  4540.9  410.97  4561.9  409.51  4670.5  408.22  4829.2  409.49    4866  408.33
    4896  405.81    4956  403.23    4966  403.37    5003  399.75  5005.7  399.25
    5009  399.75    5026   400.3    5046  402.78    5066  403.23    5096  406.21
  5124.2   406.4    5216  407.91  5235.9  409.39  5240.9   408.7    5286  411.33
    5336  413.11  5366.1  413.39  5396.1  415.27  5442.3   414.8    5507  415.97
#Mann= 7 ,-1 , 0
  4186.7     .05       0  4423.5     .16       0  4829.2     .12       0
    5003     .07       0    5009     .12       0  5124.2     .16       0
  5442.3     .05       0
Bank Sta=5003,5009
XS Rating Curve= 0 ,0
Exp/Cntr=0.3,0.1

Chan Stop Cuts=-1
Use User Specified Reach Order=0
Composite Channel Slope=5