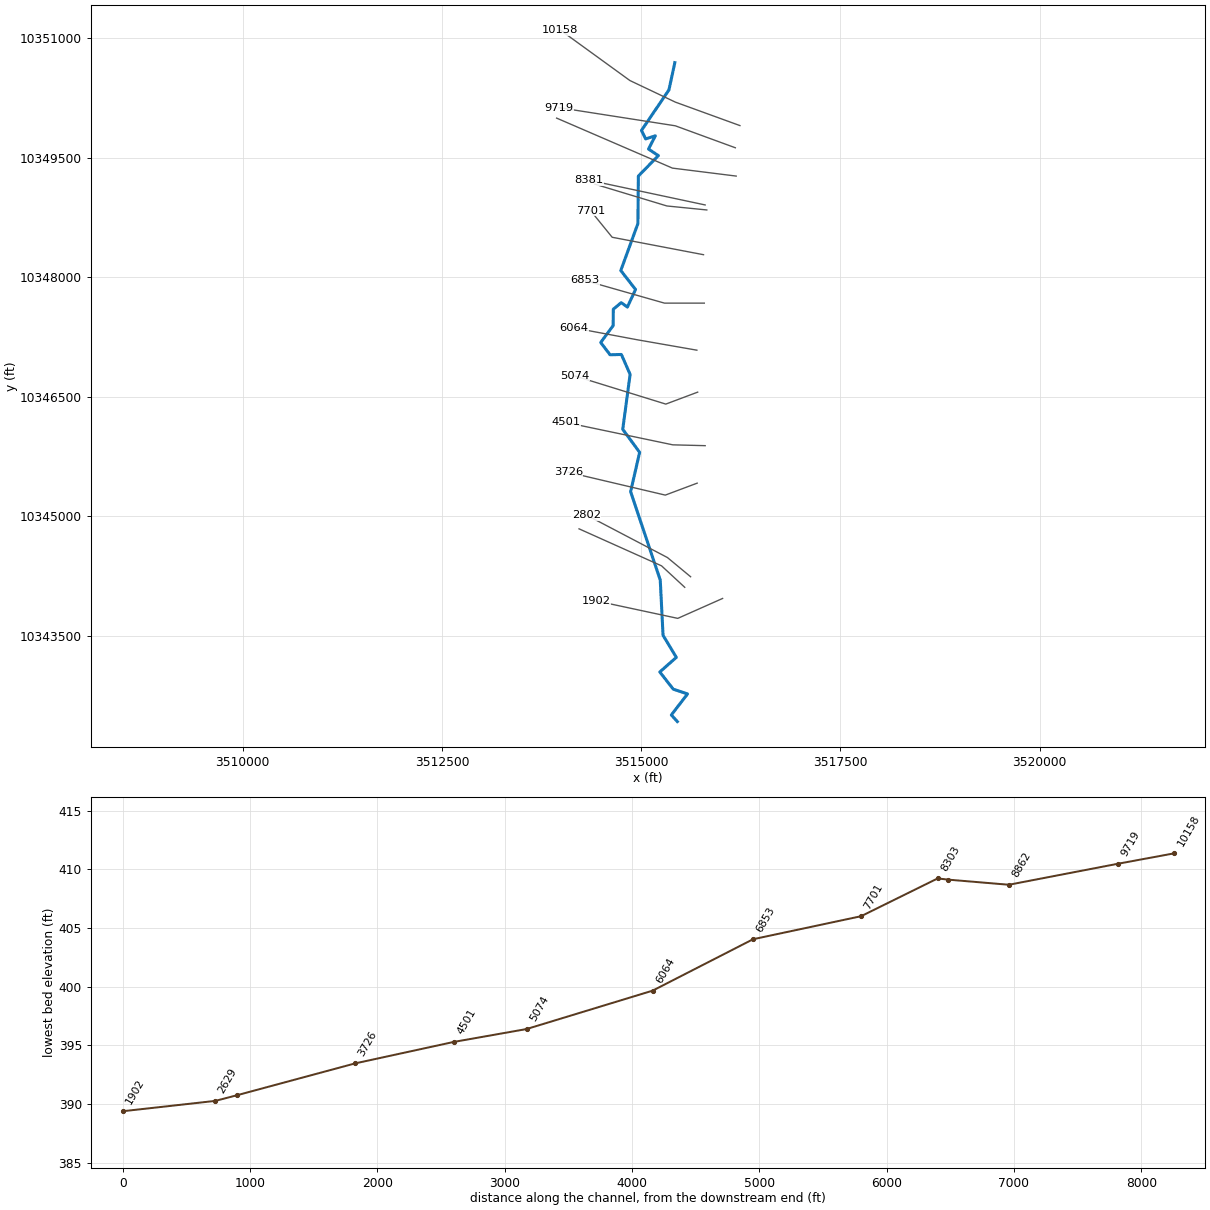
--- HAYWARD BRANCH.prj (project) ---

Proj Title=HAYWARD BRANCH Base Level Engineering
Current Plan=p01
Default Exp/Contr=0.3,0.1
English Units
Geom File=g01
Flow File=f01
Plan File=p01
BEGIN DESCRIPTION:
HAYWARD BRANCH
END DESCRIPTION:

--- HAYWARD BRANCH.p01 (plan) ---

Plan Title=Multiple Run
Short Identifier=Multiple
Geom File=g01
Flow File=f01
Subcritical Flow
K Sum by GR= 0
Std Step Tol= 0.01
Critical Tol= 0.01
Num of Std Step Trials= 20
Max Error Tol= 0.3
Flow Tol Ratio= 0.001
Split Flow NTrial= 30
Split Flow Tol= 0.02
Split Flow Ratio= 0.02
Log Output Level= 0
Friction Slope Method= 1
Unsteady Friction Slope Method= 2
Unsteady Bridges Friction Slope Method= 1
Parabolic Critical Depth
Global Vel Dist=  1 , 1 , 1
Global Log Level= 0
CheckData=True
Encroach Param= -1, 0, 0, 0
BEGIN DESCRIPTION:
Multiple Run
END DESCRIPTION:

--- HAYWARD BRANCH.f01 (steady flow) ---

Flow Title=Multiple
Number of Profiles=7
Profile Names=10-year,25-year,50-year,1pct_min,100-year,1pct_plu,500-year
River Rch & RM= HAYWARD BRANCH,Reach-1,10158
    1071    1472    1801    1606    2172    2937    3155
Boundary for River Rch & Prof#=HAYWARD BRANCH,Reach-1,1
Up Type=0
Dn Type=3
Dn Slope=0.005
Boundary for River Rch & Prof#=HAYWARD BRANCH,Reach-1,2
Up Type=0
Dn Type=3
Dn Slope=0.005
Boundary for River Rch & Prof#=HAYWARD BRANCH,Reach-1,3
Up Type=0
Dn Type=3
Dn Slope=0.005
Boundary for River Rch & Prof#=HAYWARD BRANCH,Reach-1,4
Up Type=0
Dn Type=3
Dn Slope=0.005
Boundary for River Rch & Prof#=HAYWARD BRANCH,Reach-1,5
Up Type=0
Dn Type=3
Dn Slope=0.005
Boundary for River Rch & Prof#=HAYWARD BRANCH,Reach-1,6
Up Type=0
Dn Type=3
Dn Slope=0.005
Boundary for River Rch & Prof#=HAYWARD BRANCH,Reach-1,7
Up Type=0
Dn Type=3
Dn Slope=0.005

--- HAYWARD BRANCH.g01 (geometry) ---

Geom Title=Existing Conditions

River Reach=HAYWARD BRANCH,Reach-1
Reach XY= 30
      3515422.11     10350691.64      3515348.16     10350349.64
      3515003.55     10349841.00      3515056.35     10349734.96
      3515177.88     10349773.85      3515091.77     10349607.88
      3515215.38     10349525.24      3514964.69     10349268.99
      3514958.97     10348672.79      3514744.16     10348084.01
      3514929.11     10347846.23      3514827.03     10347625.48
      3514749.23     10347680.80      3514650.29     10347598.33
      3514648.78     10347393.10      3514492.20     10347181.58
      3514609.63     10347026.95      3514751.49     10347030.80
      3514861.05     10346781.20      3514768.63     10346091.57
      3514980.43     10345803.37      3514867.58     10345309.45
      3515239.19     10344200.63      3515274.33     10343507.44
      3515441.05     10343230.99      3515233.77     10343047.80
      3515401.63     10342832.49      3515581.45     10342772.35
      3515378.17     10342508.42      3515454.07     10342425.42

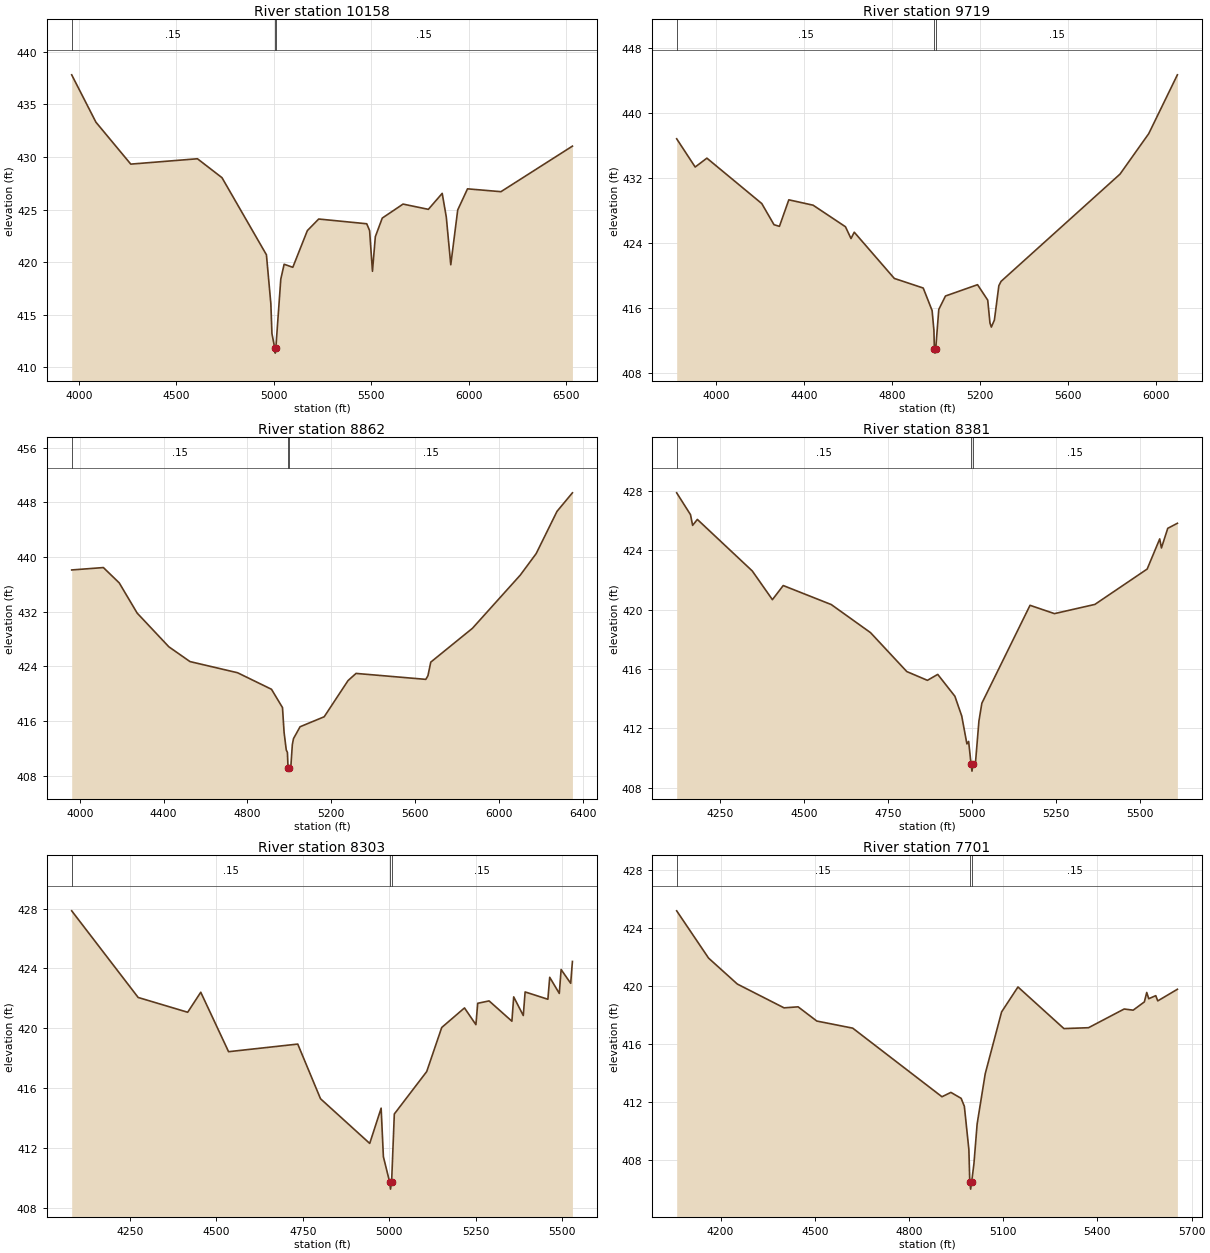
Type RM Length L Ch R = 1,10158,439,439,439
BEGIN DESCRIPTION:
HAYWARD BRANCH 11.02
END DESCRIPTION:
XS GIS Cut Line= 4
      3516238.90     10349901.95      3515429.01     10350196.22
      3514858.69     10350467.06      3513986.70     10351099.58
#Sta/Elev= 30
  3962.6  437.82  4086.9  433.32  4265.8  429.33  4608.2  429.84  4734.1  428.04
  4962.2  420.71  4984.9  416.06  4990.5  413.22  5004.6  411.86  5007.4  411.36
  5010.6  411.86  5035.9  418.39  5053.1  419.81  5097.6  419.52  5172.3  423.01
  5230.5  424.11  5477.1  423.66  5491.8  423.01  5506.5  419.14  5521.2  422.43
  5556.8  424.20  5663.5  425.53  5793.4  425.03  5864.5  426.55  5885.4  424.31
  5908.5  419.76  5944.1  424.97  5994.4  426.98  6166.0  426.71  6532.9  431.04
#Mann=3,-1,0
  3962.6    0.15       0  5004.6    0.05       0  5010.6    0.15       0
Bank Sta=5004.6,5010.6
Exp/Cntr=0.3,0.1

Type RM Length L Ch R = 1,9719,857,857,857
BEGIN DESCRIPTION:
HAYWARD BRANCH 11.01
END DESCRIPTION:
XS GIS Cut Line= 3
      3516181.19     10349623.74      3515428.14     10349899.35
      3513969.48     10350126.92
#Sta/Elev= 30
  3819.7  436.82  3903.9  433.35  3957.2  434.44  4206.9  428.86  4262.6  426.26
  4287.3  426.06  4329.9  429.32  4440.4  428.66  4587.7  426.01  4612.9  424.56
  4627.7  425.34  4809.9  419.66  4941.5  418.48  4981.9  415.71  4990.1  413.30
  4992.2  410.98  4994.9  410.48  4998.2  410.98  5012.3  415.85  5042.7  417.50
  5188.6  418.89  5235.0  416.99  5245.1  414.19  5251.4  413.68  5265.3  414.54
  5285.6  418.77  5295.7  419.30  5836.9  432.48  5967.5  437.45  6097.9  444.68
#Mann=3,-1,0
  3819.7    0.15       0  4992.2    0.05       0  4998.2    0.15       0
Bank Sta=4992.2,4998.2
Exp/Cntr=0.3,0.1

Type RM Length L Ch R = 1,8862,481,481,481
BEGIN DESCRIPTION:
HAYWARD BRANCH 11.0
END DESCRIPTION:
XS GIS Cut Line= 3
      3516192.03     10349268.53      3515392.03     10349368.53
      3513939.46     10349995.69
#Sta/Elev= 30
  3961.5  438.11  4112.6  438.46  4188.2  436.22  4273.8  431.80  4425.0  426.87
  4525.8  424.71  4752.5  423.08  4914.5  420.66  4967.0  417.98  4974.6  414.35
  4985.0  411.78  4990.5  411.42  4993.4  409.19  4996.1  408.69  4999.4  409.19
  5007.3  409.59  5014.0  412.59  5019.4  413.44  5050.8  415.18  5165.9  416.64
  5279.6  421.93  5317.8  422.98  5650.6  422.11  5660.8  422.65  5674.2  424.63
  5873.1  429.58  6101.0  437.35  6177.0  440.50  6276.4  446.68  6349.9  449.39
#Mann=3,-1,0
  3961.5    0.15       0  4993.4    0.05       0  4999.4    0.15       0
Bank Sta=4993.4,4999.4
Exp/Cntr=0.3,0.1

Type RM Length L Ch R = 1,8381,78,78,78
BEGIN DESCRIPTION:
HAYWARD BRANCH 10.011
END DESCRIPTION:
XS GIS Cut Line= 2
      3515802.40     10348906.49      3514344.04     10349217.26
#Sta/Elev= 30
  4119.8  427.86  4161.0  426.39  4167.3  425.67  4181.4  426.07  4345.0  422.60
  4404.9  420.67  4437.1  421.62  4580.2  420.34  4697.1  418.45  4805.1  415.83
  4866.5  415.24  4897.2  415.64  4948.3  414.17  4968.7  412.84  4984.1  410.96
  4989.2  411.13  4996.4  409.63  4999.2  409.13  5002.4  409.63  5009.6  409.69
  5019.9  412.50  5028.6  413.70  5172.1  420.29  5244.8  419.73  5365.2  420.35
  5520.9  422.73  5558.3  424.76  5563.4  424.15  5582.2  425.47  5610.9  425.81
#Mann=3,-1,0
  4119.8    0.15       0  4996.4    0.05       0  5002.4    0.15       0
Bank Sta=4996.4,5002.4
Exp/Cntr=0.3,0.1

Type RM Length L Ch R = 1,8303,602,602,602
BEGIN DESCRIPTION:
HAYWARD BRANCH 10.0
END DESCRIPTION:
XS GIS Cut Line= 3
      3515823.29     10348843.54      3515323.28     10348893.55
      3514419.18     10349167.14
#Sta/Elev= 30
  4082.4  427.86  4274.5  422.06  4417.6  421.07  4455.4  422.41  4535.8  418.43
  4735.7  418.94  4801.5  415.28  4943.7  412.29  4976.7  414.65  4983.2  411.40
  5001.0  409.73  5003.8  409.23  5007.0  409.73  5014.8  414.26  5108.4  417.10
  5151.8  420.05  5217.6  421.36  5250.6  420.24  5255.8  421.67  5288.7  421.83
  5354.6  420.47  5359.8  422.10  5387.5  420.85  5392.8  422.43  5458.6  421.94
  5463.9  423.41  5491.6  422.33  5496.8  423.93  5524.5  423.01  5529.5  424.47
#Mann=3,-1,0
  4082.4    0.15       0  5001.0    0.05       0  5007.0    0.15       0
Bank Sta=5001,5007
Exp/Cntr=0.3,0.1

Type RM Length L Ch R = 1,7701,848,848,848
BEGIN DESCRIPTION:
HAYWARD BRANCH 9.0
END DESCRIPTION:
XS GIS Cut Line= 3
      3515781.92     10348282.32      3514636.23     10348501.05
      3514366.26     10348833.31
#Sta/Elev= 30
  4060.2  425.20  4161.8  421.94  4253.4  420.15  4402.1  418.51  4446.9  418.58
  4506.4  417.60  4620.8  417.11  4905.0  412.38  4933.5  412.68  4966.1  412.27
  4976.3  411.72  4990.7  408.74  4993.6  406.51  4996.4  406.01  4999.6  406.51
  5006.8  407.76  5017.0  410.50  5042.8  413.97  5094.9  418.23  5147.0  419.95
  5293.4  417.08  5371.7  417.14  5485.2  418.43  5513.9  418.35  5549.5  418.92
  5557.1  419.57  5563.5  419.14  5585.8  419.35  5592.2  418.99  5654.7  419.79
#Mann=3,-1,0
  4060.2    0.15       0  4993.6    0.05       0  4999.6    0.15       0
Bank Sta=4993.6,4999.6
Exp/Cntr=0.3,0.1

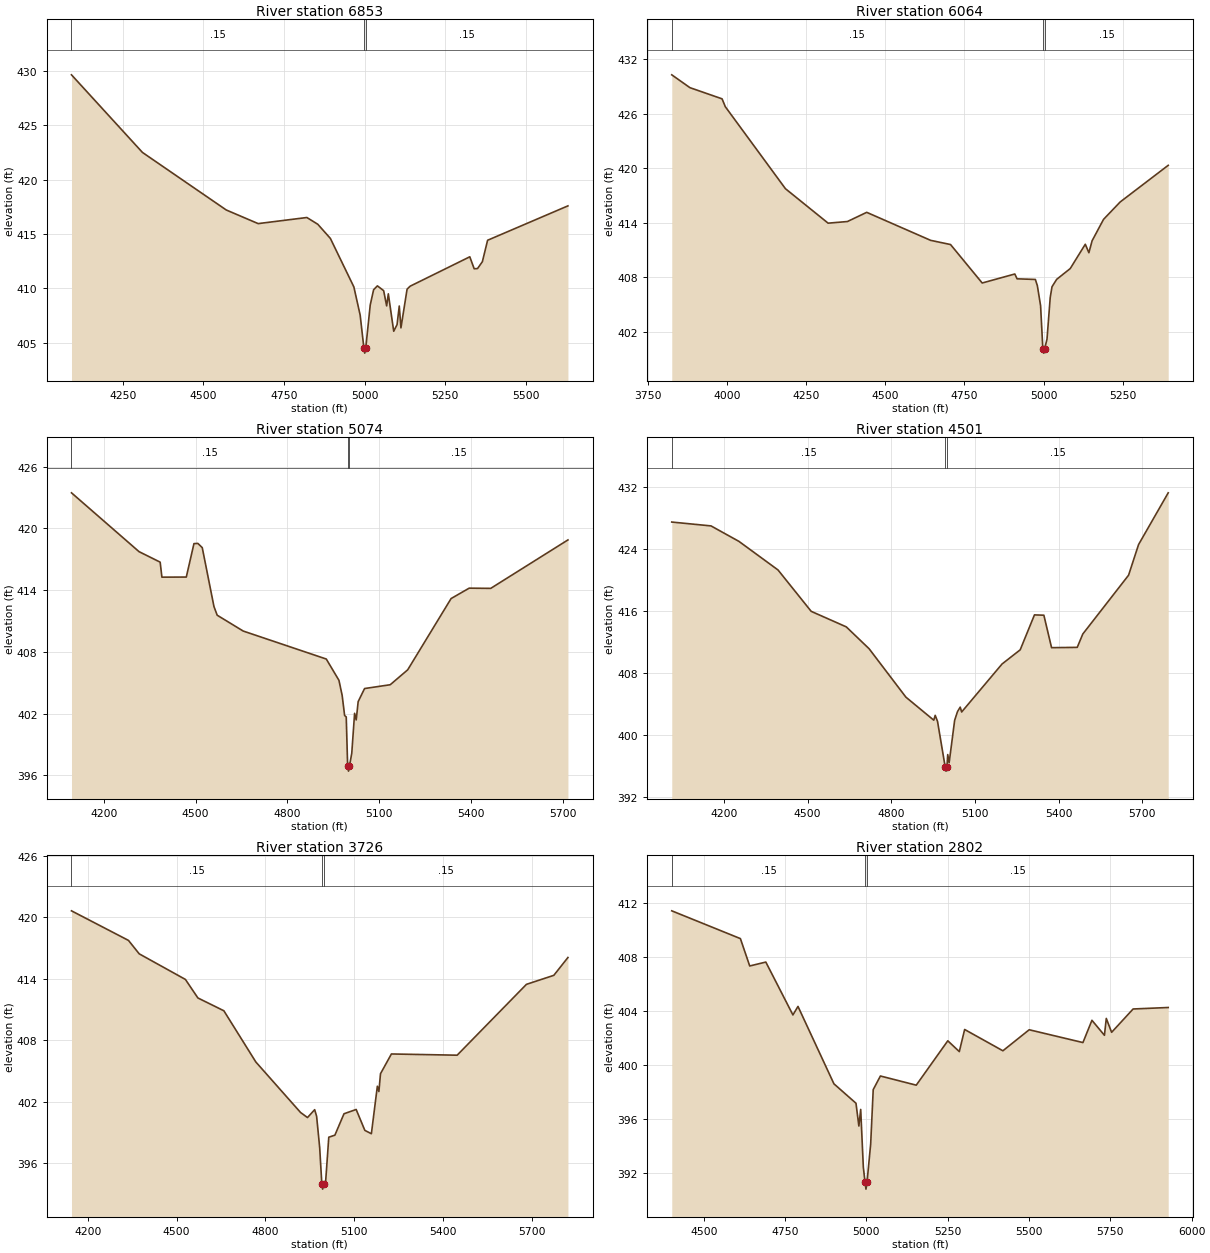
Type RM Length L Ch R = 1,6853,789,789,789
BEGIN DESCRIPTION:
HAYWARD BRANCH 8.0
END DESCRIPTION:
XS GIS Cut Line= 3
      3515792.09     10347674.84      3515292.06     10347674.84
      3514292.51     10347959.43
#Sta/Elev= 30
  4090.8  429.62  4310.8  422.49  4570.8  417.20  4669.6  415.95  4820.6  416.51
  4854.5  415.89  4893.5  414.59  4966.4  410.13  4985.9  407.54  4997.3  404.55
  5000.0  404.05  5003.3  404.55  5017.1  408.47  5027.5  409.87  5039.3  410.23
  5058.7  409.79  5068.0  408.39  5073.2  409.50  5089.9  406.06  5100.3  406.67
  5107.1  408.38  5112.3  406.37  5131.4  409.93  5140.9  410.20  5325.8  412.90
  5339.4  411.80  5349.8  411.82  5364.8  412.45  5381.0  414.42  5630.1  417.58
#Mann=3,-1,0
  4090.8    0.15       0  4997.3    0.05       0  5003.3    0.15       0
Bank Sta=4997.3,5003.3
Exp/Cntr=0.3,0.1

Type RM Length L Ch R = 1,6064,990,990,990
BEGIN DESCRIPTION:
HAYWARD BRANCH 7.0
END DESCRIPTION:
XS GIS Cut Line= 3
      3515698.59     10347084.53      3514954.60     10347214.43
      3514155.87     10347364.19
#Sta/Elev= 30
  3825.7  430.27  3883.0  428.86  3984.6  427.63  3994.7  426.77  4184.7  417.75
  4319.5  413.96  4380.5  414.14  4441.4  415.15  4643.3  412.07  4706.1  411.61
  4806.1  407.38  4909.1  408.37  4916.3  407.84  4974.0  407.77  4980.3  407.09
  4990.5  404.89  4997.6  400.17  5000.4  399.67  5003.6  400.17  5010.8  401.21
  5021.0  405.80  5026.6  406.97  5041.3  407.78  5084.2  408.97  5131.7  411.64
  5143.1  410.71  5153.2  412.02  5189.4  414.38  5241.9  416.29  5393.6  420.32
#Mann=3,-1,0
  3825.7    0.15       0  4997.6    0.05       0  5003.6    0.15       0
Bank Sta=4997.6,5003.6
Exp/Cntr=0.3,0.1

Type RM Length L Ch R = 1,5074,573,573,573
BEGIN DESCRIPTION:
HAYWARD BRANCH 6.0
END DESCRIPTION:
XS GIS Cut Line= 3
      3515708.74     10346558.22      3515308.73     10346408.22
      3514167.51     10346761.64
#Sta/Elev= 30
  4094.7  423.46  4315.4  417.74  4384.4  416.72  4390.1  415.26  4469.8  415.27
  4494.8  418.52  4507.6  418.54  4521.9  418.13  4560.2  412.40  4570.7  411.56
  4655.7  410.02  4927.1  407.30  4968.5  405.23  4979.0  403.76  4987.0  401.81
  4992.3  401.67  4996.9  396.90  4999.7  396.40  5002.9  396.90  5010.4  398.15
  5019.6  402.02  5024.9  401.38  5031.3  403.16  5052.2  404.43  5136.0  404.80
  5193.1  406.25  5334.9  413.18  5394.0  414.19  5464.4  414.17  5716.6  418.88
#Mann=3,-1,0
  4094.7    0.15       0  4996.9    0.05       0  5002.9    0.15       0
Bank Sta=4996.9,5002.9
Exp/Cntr=0.3,0.1

Type RM Length L Ch R = 1,4501,775,775,775
BEGIN DESCRIPTION:
HAYWARD BRANCH 5.0
END DESCRIPTION:
XS GIS Cut Line= 3
      3515802.75     10345886.72      3515396.57     10345897.14
      3514053.00     10346178.35
#Sta/Elev= 30
  4013.5  427.52  4154.2  427.02  4254.2  425.02  4394.3  421.32  4513.1  415.97
  4638.9  413.96  4720.7  411.13  4852.5  404.87  4952.4  401.89  4957.5  402.52
  4965.9  401.73  4993.5  395.80  4996.3  395.30  4999.5  395.80  5002.4  397.44
  5007.5  396.39  5027.2  401.87  5037.4  403.00  5047.2  403.58  5052.3  402.95
  5197.1  409.16  5262.1  410.99  5313.2  415.51  5346.9  415.47  5374.5  411.27
  5466.5  411.31  5486.5  413.04  5650.4  420.64  5686.3  424.61  5792.5  431.30
#Mann=3,-1,0
  4013.5    0.15       0  4993.5    0.05       0  4999.5    0.15       0
Bank Sta=4993.5,4999.5
Exp/Cntr=0.3,0.1

Type RM Length L Ch R = 1,3726,924,924,924
BEGIN DESCRIPTION:
HAYWARD BRANCH 4.0
END DESCRIPTION:
XS GIS Cut Line= 3
      3515702.47     10345416.57      3515302.50     10345266.58
      3514085.64     10345553.08
#Sta/Elev= 30
  4144.7  420.65  4337.3  417.76  4373.5  416.45  4529.6  413.95  4571.8  412.14
  4659.5  410.89  4767.5  405.89  4918.8  400.95  4942.1  400.46  4966.3  401.23
  4972.9  400.58  4983.2  397.55  4990.5  393.97  4993.2  393.47  4996.5  393.97
  5003.6  394.30  5014.0  398.54  5034.6  398.74  5065.4  400.83  5106.5  401.25
  5135.8  399.21  5157.9  398.88  5178.1  403.52  5183.3  403.00  5188.7  404.74
  5225.6  406.67  5447.7  406.55  5681.8  413.47  5774.3  414.35  5822.0  416.09
#Mann=3,-1,0
  4144.7    0.15       0  4990.5    0.05       0  4996.5    0.15       0
Bank Sta=4990.5,4996.5
Exp/Cntr=0.3,0.1

Type RM Length L Ch R = 1,2802,173,173,173
BEGIN DESCRIPTION:
HAYWARD BRANCH 1.03
END DESCRIPTION:
XS GIS Cut Line= 3
      3515620.07     10344242.42      3515329.26     10344483.32
      3514311.94     10345016.92
#Sta/Elev= 30
  4401.5  411.41  4612.5  409.35  4641.2  407.32  4690.7  407.61  4774.0  403.69
  4789.6  404.32  4900.1  398.58  4967.9  397.14  4976.8  395.45  4982.4  396.68
  4990.5  392.40  4995.8  391.27  4998.6  390.77  5001.8  391.27  5013.1  394.13
  5020.9  398.15  5043.0  399.16  5153.2  398.48  5250.2  401.77  5285.6  400.97
  5302.0  402.61  5419.6  401.03  5500.5  402.59  5665.7  401.64  5693.4  403.29
  5731.8  402.18  5737.5  403.43  5753.9  402.40  5820.0  404.13  5927.9  404.24
#Mann=3,-1,0
  4401.5    0.15       0  4995.8    0.05       0  5001.8    0.15       0
Bank Sta=4995.8,5001.8
Exp/Cntr=0.3,0.1

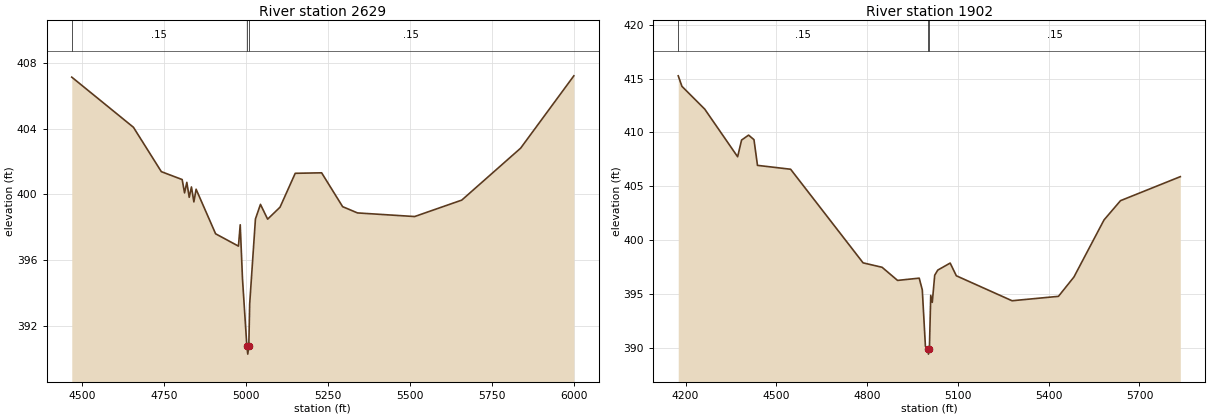
Type RM Length L Ch R = 1,2629,727,727,727
BEGIN DESCRIPTION:
HAYWARD BRANCH 1.02
END DESCRIPTION:
XS GIS Cut Line= 3
      3515546.30     10344110.03      3515255.47     10344379.15
      3514220.32     10344843.56
#Sta/Elev= 30
  4468.4  407.13  4656.4  404.08  4741.5  401.38  4805.0  400.90  4812.3  400.09
  4819.2  400.73  4826.5  399.82  4833.3  400.45  4840.7  399.54  4847.5  400.31
  4907.0  397.60  4976.6  396.85  4982.0  398.15  4988.9  394.87  5002.2  390.78
  5005.0  390.28  5008.2  390.78  5010.8  393.32  5028.4  398.50  5043.7  399.39
  5065.6  398.49  5103.4  399.22  5149.7  401.28  5230.2  401.31  5294.3  399.25
  5339.6  398.87  5513.8  398.65  5657.5  399.65  5837.0  402.81  5999.2  407.21
#Mann=3,-1,0
  4468.4    0.15       0  5002.2    0.05       0  5008.2    0.15       0
Bank Sta=5002.2,5008.2
Exp/Cntr=0.3,0.1

Type RM Length L Ch R = 1,1902,0,0,0
BEGIN DESCRIPTION:
HAYWARD BRANCH 1.0
END DESCRIPTION:
XS GIS Cut Line= 3
      3516021.46     10343970.23      3515459.06     10343720.27
      3514438.38     10343938.99
#Sta/Elev= 30
  4175.6  415.26  4187.9  414.28  4263.1  412.17  4371.9  407.74  4384.9  409.29
  4408.1  409.75  4425.9  409.33  4437.5  406.94  4547.0  406.58  4786.6  397.88
  4849.3  397.47  4900.4  396.25  4972.0  396.46  4982.2  395.37  4992.5  390.13
  4999.7  389.90  5002.5  389.40  5005.7  389.90  5010.1  394.86  5015.2  394.21
  5023.2  396.73  5033.4  397.21  5074.3  397.86  5094.7  396.68  5278.8  394.36
  5432.2  394.77  5483.4  396.57  5582.8  401.87  5637.3  403.66  5834.9  405.89
#Mann=3,-1,0
  4175.6    0.15       0  4999.7    0.05       0  5005.7    0.15       0
Bank Sta=4999.7,5005.7
Exp/Cntr=0.3,0.1

Chan Stop Cuts=-1