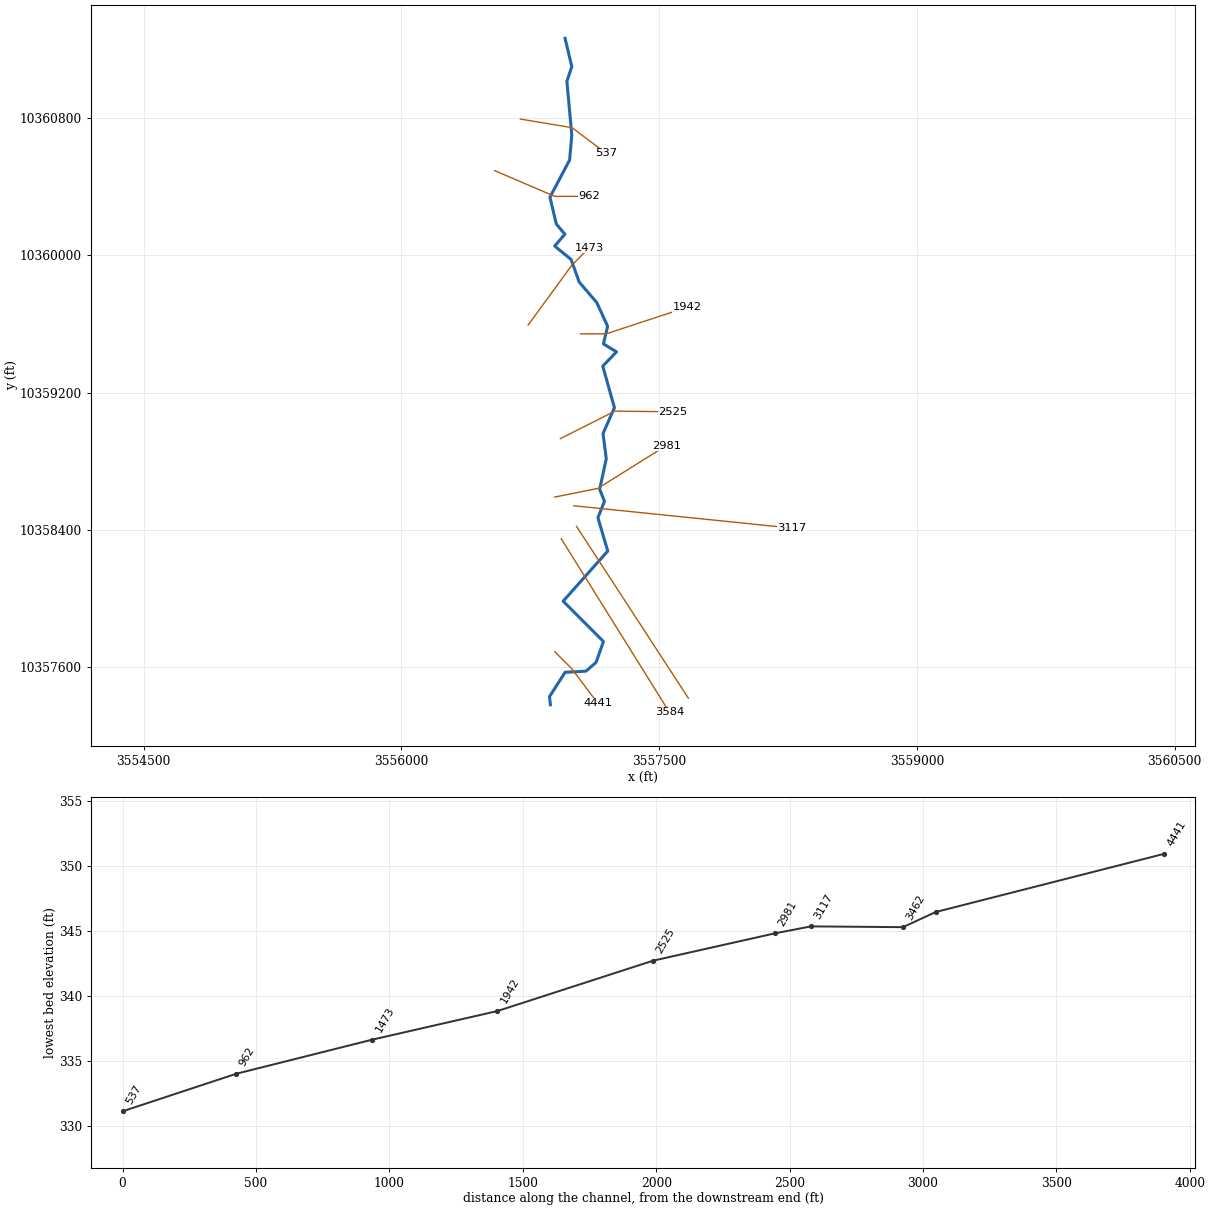
--- HUDSON BRANCH.prj (project) ---

Proj Title=HUDSON BRANCH Base Level Engineering
Current Plan=p01
Default Exp/Contr=0.3,0.1
English Units
Geom File=g01
Flow File=f01
Plan File=p01
BEGIN DESCRIPTION:
HUDSON BRANCH
END DESCRIPTION:

--- HUDSON BRANCH.p01 (plan) ---

Plan Title=Multiple Run
Short Identifier=Multiple
Geom File=g01
Flow File=f01
Subcritical Flow
K Sum by GR= 0
Std Step Tol= 0.01
Critical Tol= 0.01
Num of Std Step Trials= 20
Max Error Tol= 0.3
Flow Tol Ratio= 0.001
Split Flow NTrial= 30
Split Flow Tol= 0.02
Split Flow Ratio= 0.02
Log Output Level= 0
Friction Slope Method= 1
Unsteady Friction Slope Method= 2
Unsteady Bridges Friction Slope Method= 1
Parabolic Critical Depth
Global Vel Dist=  1 , 1 , 1
Global Log Level= 0
CheckData=True
Encroach Param= -1, 0, 0, 0
BEGIN DESCRIPTION:
Multiple Run
END DESCRIPTION:

--- HUDSON BRANCH.f01 (steady flow) ---

Flow Title=Multiple
Number of Profiles=7
Profile Names=10-year,25-year,50-year,1pct_min,100-year,1pct_plu,500-year
River Rch & RM= HUDSON BRANCH,Reach-1,4441
    1124    1571    1947    1763    2384    3224    3562
River Rch & RM= HUDSON BRANCH,Reach-1,3584
    1461    2066    2579    2349    3177    4296    4806
Boundary for River Rch & Prof#=HUDSON BRANCH,Reach-1,1
Up Type=0
Dn Type=3
Dn Slope=0.005
Boundary for River Rch & Prof#=HUDSON BRANCH,Reach-1,2
Up Type=0
Dn Type=3
Dn Slope=0.005
Boundary for River Rch & Prof#=HUDSON BRANCH,Reach-1,3
Up Type=0
Dn Type=3
Dn Slope=0.005
Boundary for River Rch & Prof#=HUDSON BRANCH,Reach-1,4
Up Type=0
Dn Type=3
Dn Slope=0.005
Boundary for River Rch & Prof#=HUDSON BRANCH,Reach-1,5
Up Type=0
Dn Type=3
Dn Slope=0.005
Boundary for River Rch & Prof#=HUDSON BRANCH,Reach-1,6
Up Type=0
Dn Type=3
Dn Slope=0.005
Boundary for River Rch & Prof#=HUDSON BRANCH,Reach-1,7
Up Type=0
Dn Type=3
Dn Slope=0.005

--- HUDSON BRANCH.g01 (geometry) ---

Geom Title=Existing Conditions

River Reach=HUDSON BRANCH,Reach-1
Reach XY= 30
      3556866.92     10357382.51      3556861.71     10357430.43
      3556952.34     10357571.57      3557074.21     10357578.52
      3557132.54     10357629.21      3557175.60     10357750.74
      3556941.01     10357985.72      3557200.63     10358277.20
      3557143.49     10358471.32      3557181.53     10358566.89
      3557153.49     10358636.69      3557191.93     10358814.07
      3557173.08     10358961.07      3557239.49     10359111.63
      3557171.77     10359353.56      3557251.40     10359436.81
      3557175.41     10359483.06      3557199.82     10359585.65
      3557136.45     10359724.01      3557034.56     10359842.66
      3556987.25     10359974.29      3556891.91     10360052.70
      3556951.16     10360121.16      3556901.36     10360180.51
      3556864.18     10360336.50      3556978.55     10360553.12
      3556991.32     10360696.98      3556962.86     10361011.72
      3556991.50     10361096.35      3556952.11     10361261.64

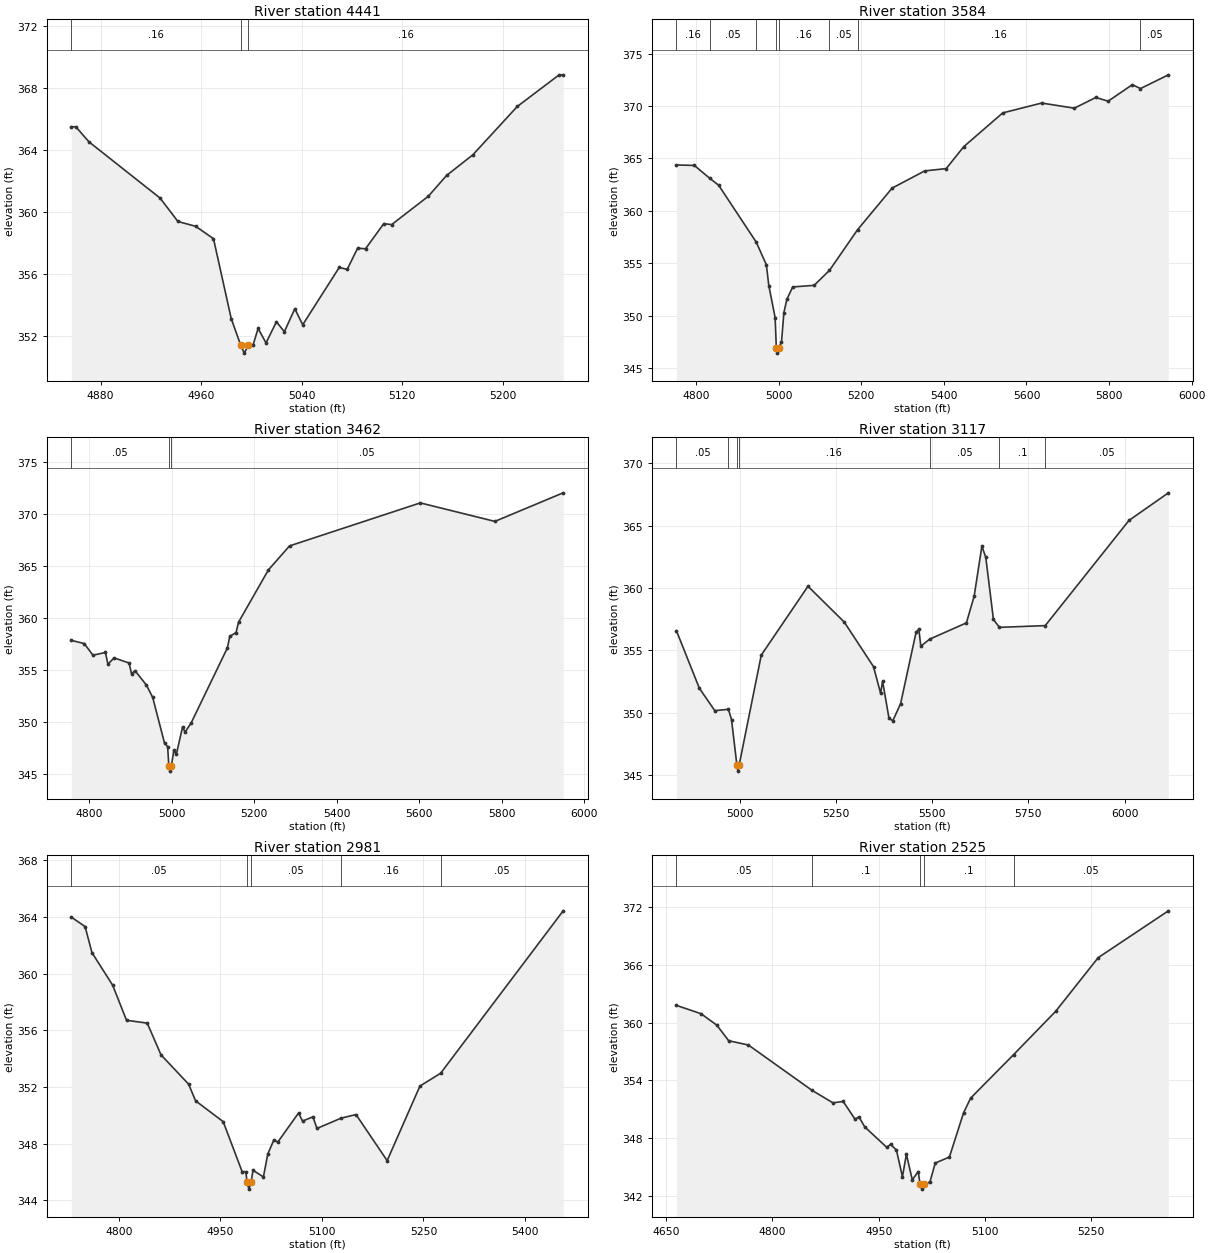
Type RM Length L Ch R = 1,4441,857,857,857
BEGIN DESCRIPTION:
HUDSON BRANCH 9.0
END DESCRIPTION:
XS GIS Cut Line= 3
      3556892.08     10357691.66      3556992.11     10357591.64
      3557142.13     10357391.60
#Sta/Elev= 30
  4856.6  365.52  4860.2  365.52  4870.8  364.54  4927.3  360.92  4941.5  359.41
  4955.6  359.10  4969.8  358.30  4983.9  353.15  4991.5  351.42  4994.3  350.92
  4997.5  351.42  5001.2  351.42  5005.3  352.51  5011.6  351.58  5019.9  352.94
  5026.2  352.30  5034.5  353.78  5040.8  352.75  5069.9  356.45  5076.2  356.32
  5084.5  357.69  5090.8  357.65  5105.3  359.27  5111.6  359.21  5140.8  361.04
  5155.3  362.38  5176.2  363.71  5211.6  366.83  5244.9  368.87  5248.1  368.87
#Mann=3,-1,0
  4856.6    0.16       0  4991.5    0.07       0  4997.5    0.16       0
Bank Sta=4991.5,4997.5
Exp/Cntr=0.3,0.1

Type RM Length L Ch R = 1,3584,122,122,122
BEGIN DESCRIPTION:
HUDSON BRANCH 8.0
END DESCRIPTION:
XS GIS Cut Line= 2
      3556930.15     10358348.35      3557560.39     10357337.88
#Sta/Elev= 30
  4752.8  364.38  4796.1  364.33  4832.9  363.12  4854.8  362.45  4945.9  357.02
  4970.4  354.86  4976.3  352.88  4991.6  349.83  4994.5  346.94  4997.3  346.44
  5000.5  346.94  5007.0  347.48  5012.8  350.30  5020.0  351.56  5034.1  352.75
  5086.0  352.90  5123.2  354.33  5191.3  358.21  5274.8  362.17  5353.8  363.81
  5405.7  364.03  5448.2  366.12  5542.6  369.34  5636.9  370.28  5716.0  369.79
  5767.9  370.81  5797.8  370.46  5856.4  372.03  5876.1  371.66  5943.7  372.97
#Mann=8,-1,0
  4752.8    0.16       0  4832.9    0.05       0  4945.9    0.16       0
  4994.5    0.07       0  5000.5    0.16       0  5123.2    0.05       0
  5191.3    0.16       0  5876.1    0.05       0
Bank Sta=4994.5,5000.5
Exp/Cntr=0.3,0.1

Type RM Length L Ch R = 1,3462,345,345,345
BEGIN DESCRIPTION:
HUDSON BRANCH 7.0
END DESCRIPTION:
XS GIS Cut Line= 2
      3557018.71     10358421.23      3557669.77     10357421.20
#Sta/Elev= 30
  4756.3  357.87  4787.8  357.56  4808.9  356.44  4839.2  356.70  4845.2  355.58
  4860.3  356.18  4896.5  355.69  4902.5  354.65  4910.9  354.95  4938.7  353.56
  4953.8  352.38  4982.5  347.98  4990.1  347.64  4993.0  345.78  4995.8  345.28
  4999.0  345.78  5005.2  347.27  5011.2  346.90  5026.3  349.53  5032.3  349.03
  5047.4  349.94  5135.0  357.14  5140.9  358.25  5156.1  358.62  5162.0  359.61
  5234.5  364.65  5285.8  366.96  5603.0  371.10  5783.9  369.32  5949.6  372.07
#Mann=3,-1,0
  4756.3    0.05       0  4993.0    0.04       0  4999.0    0.05       0
Bank Sta=4993,4999
Exp/Cntr=0.3,0.1

Type RM Length L Ch R = 1,3117,136,136,136
BEGIN DESCRIPTION:
HUDSON BRANCH 6.1
END DESCRIPTION:
XS GIS Cut Line= 2
      3557003.10     10358541.02      3558273.95     10358410.81
#Sta/Elev= 30
  4836.2  356.57  4895.5  351.98  4935.7  350.18  4971.0  350.29  4979.1  349.47
  4993.0  345.84  4995.8  345.34  4999.0  345.84  5056.4  354.63  5177.7  360.14
  5272.0  357.27  5347.9  353.70  5366.3  351.57  5371.4  352.55  5388.1  349.56
  5398.1  349.38  5418.2  350.74  5458.4  356.46  5465.6  356.69  5470.7  355.34
  5493.4  355.90  5589.1  357.21  5609.2  359.34  5629.3  363.35  5639.4  362.46
  5659.3  357.48  5675.0  356.85  5793.8  356.99  6011.3  365.41  6113.7  367.62
#Mann=7,-1,0
  4836.2    0.05       0  4971.0    0.16       0  4993.0    0.07       0
  4999.0    0.16       0  5493.4    0.05       0  5675.0     0.1       0
  5793.8    0.05       0
Bank Sta=4993,4999
Exp/Cntr=0.3,0.1

Type RM Length L Ch R = 1,2981,456,456,456
BEGIN DESCRIPTION:
HUDSON BRANCH 6.0
END DESCRIPTION:
XS GIS Cut Line= 3
      3556892.11     10358591.64      3557142.11     10358641.64
      3557542.06     10358891.62
#Sta/Elev= 30
  4729.9  363.99  4750.3  363.32  4760.5  361.48  4791.1  359.18  4811.5  356.71
  4842.1  356.51  4862.5  354.27  4903.3  352.20  4913.5  351.03  4954.3  349.56
  4982.3  346.03  4987.8  346.03  4989.5  345.30  4992.3  344.80  4995.5  345.30
  4998.4  346.13  5013.7  345.66  5020.2  347.28  5029.1  348.26  5035.0  348.12
  5065.6  350.17  5071.5  349.60  5086.9  349.90  5092.8  349.08  5128.1  349.80
  5150.5  350.06  5196.5  346.81  5244.9  352.07  5275.4  352.97  5456.5  364.43
#Mann=5,-1,0
  4729.9    0.05       0  4989.5    0.03       0  4995.5    0.05       0
  5128.1    0.16       0  5275.4    0.05       0
Bank Sta=4989.5,4995.5
Exp/Cntr=0.3,0.1

Type RM Length L Ch R = 1,2525,583,583,583
BEGIN DESCRIPTION:
HUDSON BRANCH 5.0
END DESCRIPTION:
XS GIS Cut Line= 3
      3556924.99     10358931.66      3557242.11     10359091.64
      3557581.20     10359087.90
#Sta/Elev= 30
  4664.7  361.81  4699.3  360.95  4721.6  359.76  4738.3  358.14  4766.2  357.69
  4855.9  352.98  4885.5  351.68  4900.0  351.82  4916.7  349.97  4922.3  350.21
  4930.3  349.18  4961.3  347.06  4966.9  347.35  4975.1  346.77  4983.6  343.98
  4989.2  346.33  4997.5  343.67  5005.9  344.52  5008.5  343.20  5011.3  342.70
  5014.5  343.20  5022.4  343.44  5029.9  345.41  5049.9  346.04  5069.9  350.64
  5079.9  352.17  5140.6  356.70  5199.9  361.20  5259.9  366.78  5359.0  371.65
#Mann=5,-1,0
  4664.7    0.05       0  4855.9     0.1       0  5008.5    0.07       0
  5014.5     0.1       0  5140.6    0.05       0
Bank Sta=5008.5,5014.5
Exp/Cntr=0.3,0.1

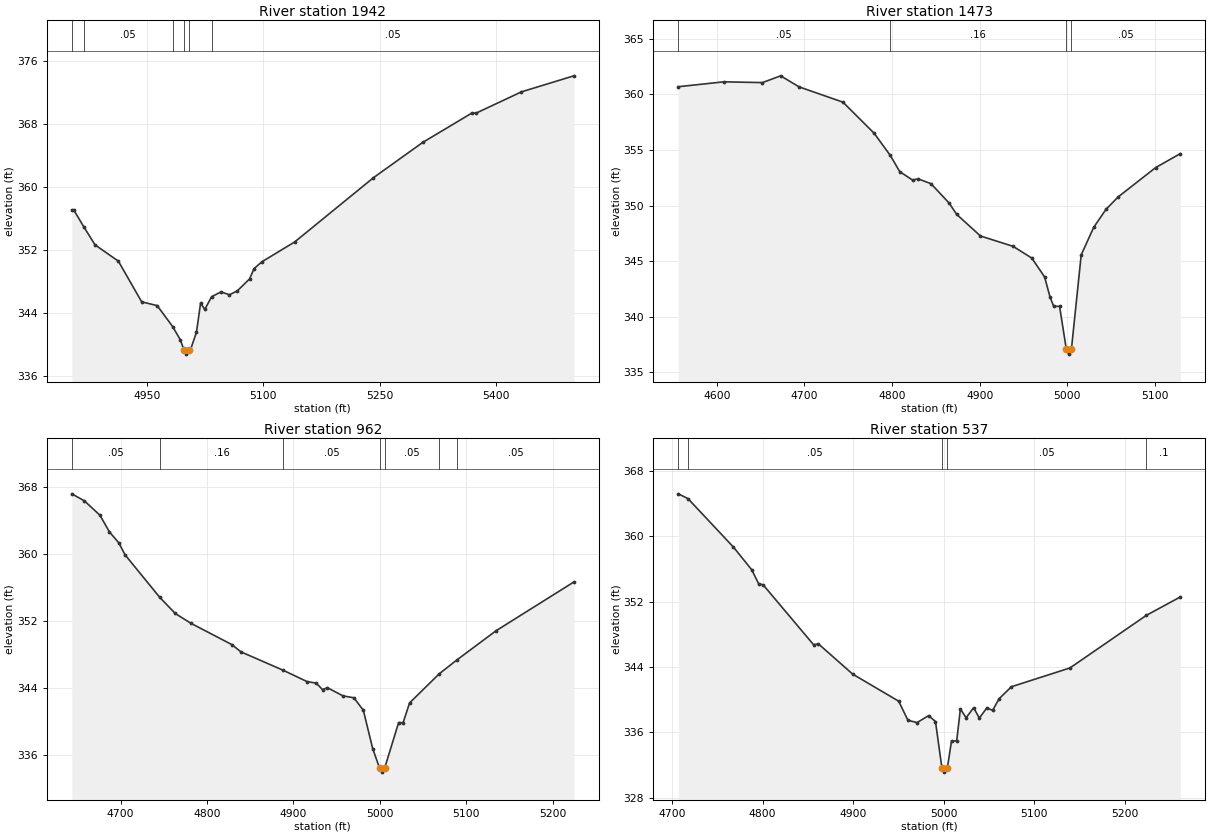
Type RM Length L Ch R = 1,1942,469,469,469
BEGIN DESCRIPTION:
HUDSON BRANCH 4.0
END DESCRIPTION:
XS GIS Cut Line= 3
      3557042.06     10359541.64      3557192.11     10359541.64
      3557663.63     10359696.97
#Sta/Elev= 30
  4853.2  357.09  4855.7  357.09  4868.6  354.96  4883.2  352.66  4913.2  350.60
  4943.2  345.45  4963.2  344.97  4983.1  342.32  4993.2  340.60  4997.7  339.33
  5000.5  338.83  5003.7  339.33  5005.9  339.33  5013.8  341.62  5019.1  345.31
  5024.4  344.48  5033.3  346.10  5045.4  346.71  5056.2  346.34  5066.4  346.84
  5082.2  348.36  5087.9  349.65  5098.0  350.52  5140.1  353.02  5241.5  361.15
  5305.1  365.63  5368.6  369.36  5373.9  369.34  5432.2  372.03  5499.7  374.06
#Mann=6,-1,0
  4853.2     0.1       0  4868.6    0.05       0  4983.1     0.1       0
  4997.7    0.07       0  5003.7     0.1       0  5033.3    0.05       0
Bank Sta=4997.7,5003.7
Exp/Cntr=0.3,0.1

Type RM Length L Ch R = 1,1473,511,511,511
BEGIN DESCRIPTION:
HUDSON BRANCH 3.0
END DESCRIPTION:
XS GIS Cut Line= 3
      3556737.47     10359593.13      3556992.11     10359941.64
      3557092.07     10360041.61
#Sta/Elev= 30
  4556.0  360.69  4608.1  361.13  4652.1  361.06  4672.9  361.67  4693.8  360.68
  4744.0  359.30  4779.5  356.51  4798.0  354.51  4808.8  353.05  4823.5  352.29
  4829.7  352.40  4844.4  351.97  4865.2  350.22  4873.7  349.21  4900.9  347.26
  4938.1  346.33  4959.4  345.28  4974.1  343.58  4980.3  341.77  4984.5  340.93
  4991.2  340.93  4998.8  337.13  5001.5  336.63  5004.8  337.13  5015.9  345.56
  5030.1  348.03  5044.2  349.66  5058.3  350.79  5100.8  353.41  5129.0  354.67
#Mann=4,-1,0
  4556.0    0.05       0  4798.0    0.16       0  4998.8    0.07       0
  5004.8    0.05       0
Bank Sta=4998.8,5004.8
Exp/Cntr=0.3,0.1

Type RM Length L Ch R = 1,962,425,425,425
BEGIN DESCRIPTION:
HUDSON BRANCH 2.0
END DESCRIPTION:
XS GIS Cut Line= 3
      3556542.11     10360491.64      3556892.11     10360341.64
      3557092.12     10360341.64
#Sta/Elev= 30
  4643.6  367.17  4658.1  366.34  4676.2  364.62  4687.1  362.64  4698.0  361.33
  4705.3  359.89  4745.3  354.84  4763.3  352.91  4781.4  351.74  4828.6  349.21
  4839.4  348.33  4888.4  346.13  4915.6  344.80  4926.5  344.60  4933.7  343.83
  4939.2  344.07  4957.3  343.09  4970.0  342.86  4980.9  341.37  4991.7  336.81
  4999.6  334.50  5002.4  334.00  5005.6  334.50  5021.7  339.90  5026.9  339.90
  5034.4  342.25  5068.8  345.73  5089.1  347.37  5134.4  350.85  5224.4  356.66
#Mann=7,-1,0
  4643.6    0.05       0  4745.3    0.16       0  4888.4    0.05       0
  4999.6    0.03       0  5005.6    0.05       0  5068.8     0.1       0
  5089.1    0.05       0
Bank Sta=4999.6,5005.6
Exp/Cntr=0.3,0.1

Type RM Length L Ch R = 1,537,0,0,0
BEGIN DESCRIPTION:
HUDSON BRANCH 1.0
END DESCRIPTION:
XS GIS Cut Line= 3
      3556692.10     10360791.64      3556992.11     10360741.64
      3557192.07     10360591.67
#Sta/Elev= 30
  4706.9  365.21  4717.6  364.63  4767.7  358.70  4788.0  355.91  4795.6  354.20
  4800.7  354.05  4856.4  346.71  4861.5  346.84  4899.5  343.12  4950.2  339.81
  4960.4  337.47  4970.5  337.19  4983.2  338.04  4990.8  337.32  4997.9  331.62
  5000.7  331.12  5003.9  331.62  5008.5  334.94  5014.2  334.94  5018.3  338.86
  5024.6  337.78  5032.9  339.01  5039.2  337.74  5047.5  338.99  5053.8  338.68
  5061.0  340.11  5074.6  341.58  5139.2  343.88  5223.6  350.33  5261.0  352.58
#Mann=5,-1,0
  4706.9     0.1       0  4717.6    0.05       0  4997.9    0.03       0
  5003.9    0.05       0  5223.6     0.1       0
Bank Sta=4997.9,5003.9
Exp/Cntr=0.3,0.1

Chan Stop Cuts=-1