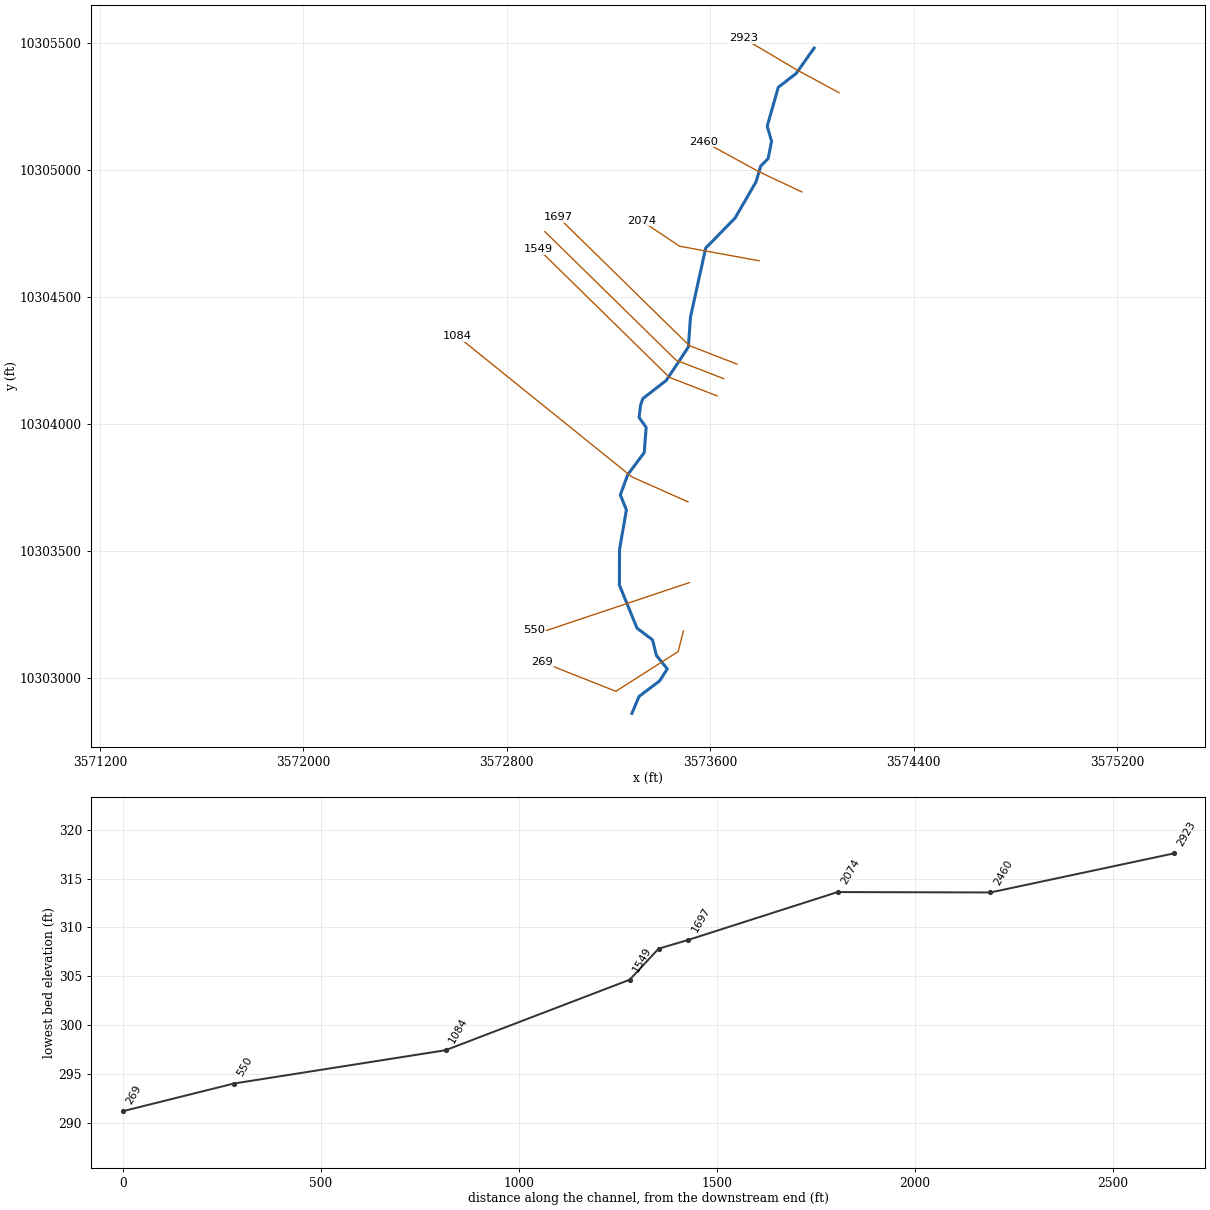
--- IRON CREEK TRIBUTARY 1.prj (project) ---

Proj Title=IRON CREEK TRIBUTARY 1 Base Level Engineering
Current Plan=p01
Default Exp/Contr=0.3,0.1
English Units
Geom File=g01
Flow File=f01
Plan File=p01
Y Axis Title=Elevation
X Axis Title(PF)=Main Channel Distance
X Axis Title(XS)=Station
BEGIN DESCRIPTION:
IRON CREEK TRIBUTARY 1
END DESCRIPTION:
DSS Export Rating Curves= 0
DSS Export Rating Curve Sorted= 0
DSS Export Volume Flow Curves= 0
DXF OffsetX= 0
DXF OffsetY= 0
DXF ScaleX= 1
DXF ScaleY= 10

--- IRON CREEK TRIBUTARY 1.p01 (plan) ---

Plan Title=Multiple Run
Short Identifier=Multiple
Geom File=g01
Flow File=f01
Subcritical Flow
K Sum by GR= 0
Std Step Tol= 0.01
Critical Tol= 0.01
Num of Std Step Trials= 20
Max Error Tol= 0.3
Flow Tol Ratio= 0.001
Split Flow NTrial= 30
Split Flow Tol= 0.02
Split Flow Ratio= 0.02
Log Output Level= 0
Friction Slope Method= 1
Unsteady Friction Slope Method= 2
Unsteady Bridges Friction Slope Method= 1
Parabolic Critical Depth
Global Vel Dist=  1 , 1 , 1
Global Log Level= 0
CheckData=True
Encroach Param= -1, 0, 0, 0
BEGIN DESCRIPTION:
Multiple Run
END DESCRIPTION:

--- IRON CREEK TRIBUTARY 1.f01 (steady flow) ---

Flow Title=Multiple
Program Version=4.10
Number of Profiles= 7
Profile Names=10-year,25-year,50-year,1pct_min,100-year,1pct_plu,500-year
River Rch & RM=IRON CREEK TRIBU,Reach-1         ,2923
     254     326     382     329     445     602     604
Boundary for River Rch & Prof#=IRON CREEK TRIBU,Reach-1         , 1
Up Type= 0
Dn Type= 3
Dn Slope=0.00775
Boundary for River Rch & Prof#=IRON CREEK TRIBU,Reach-1         , 2
Up Type= 0
Dn Type= 3
Dn Slope=0.00775
Boundary for River Rch & Prof#=IRON CREEK TRIBU,Reach-1         , 3
Up Type= 0
Dn Type= 3
Dn Slope=0.00775
Boundary for River Rch & Prof#=IRON CREEK TRIBU,Reach-1         , 4
Up Type= 0
Dn Type= 3
Dn Slope=0.00775
Boundary for River Rch & Prof#=IRON CREEK TRIBU,Reach-1         , 5
Up Type= 0
Dn Type= 3
Dn Slope=0.00775
Boundary for River Rch & Prof#=IRON CREEK TRIBU,Reach-1         , 6
Up Type= 0
Dn Type= 3
Dn Slope=0.00775
Boundary for River Rch & Prof#=IRON CREEK TRIBU,Reach-1         , 7
Up Type= 0
Dn Type= 3
Dn Slope=0.00775
DSS Import GetInterval= 0
DSS Import GetPeak= 0
DSS Import FillOption= 0

--- IRON CREEK TRIBUTARY 1.g01 (geometry) ---

Geom Title=Existing Conditions
Program Version=4.10

River Reach=IRON CREEK TRIBU,Reach-1
Reach XY= 30
       3574008.6     10305478.14      3573938.22     10305378.67
      3573867.73     10305324.14      3573824.09     10305171.16
      3573841.33     10305111.58      3573827.89     10305044.06
      3573798.41     10305013.55      3573780.23     10304952.45
      3573697.99     10304810.12        3573582.     10304691.26
      3573522.27     10304419.73      3573513.94     10304302.37
      3573427.13     10304171.12      3573334.77     10304099.59
      3573325.75     10304072.51      3573320.26     10304025.21
      3573347.98     10303986.66      3573340.39     10303887.13
      3573275.44     10303800.21      3573246.43     10303721.06
       3573270.4     10303662.12      3573243.26     10303506.33
      3573242.81     10303366.32      3573312.24     10303196.47
       3573373.1     10303150.75      3573388.35      10303089.5
      3573431.18     10303036.46      3573401.08     10302989.66
      3573319.89     10302927.99      3573292.11     10302861.64

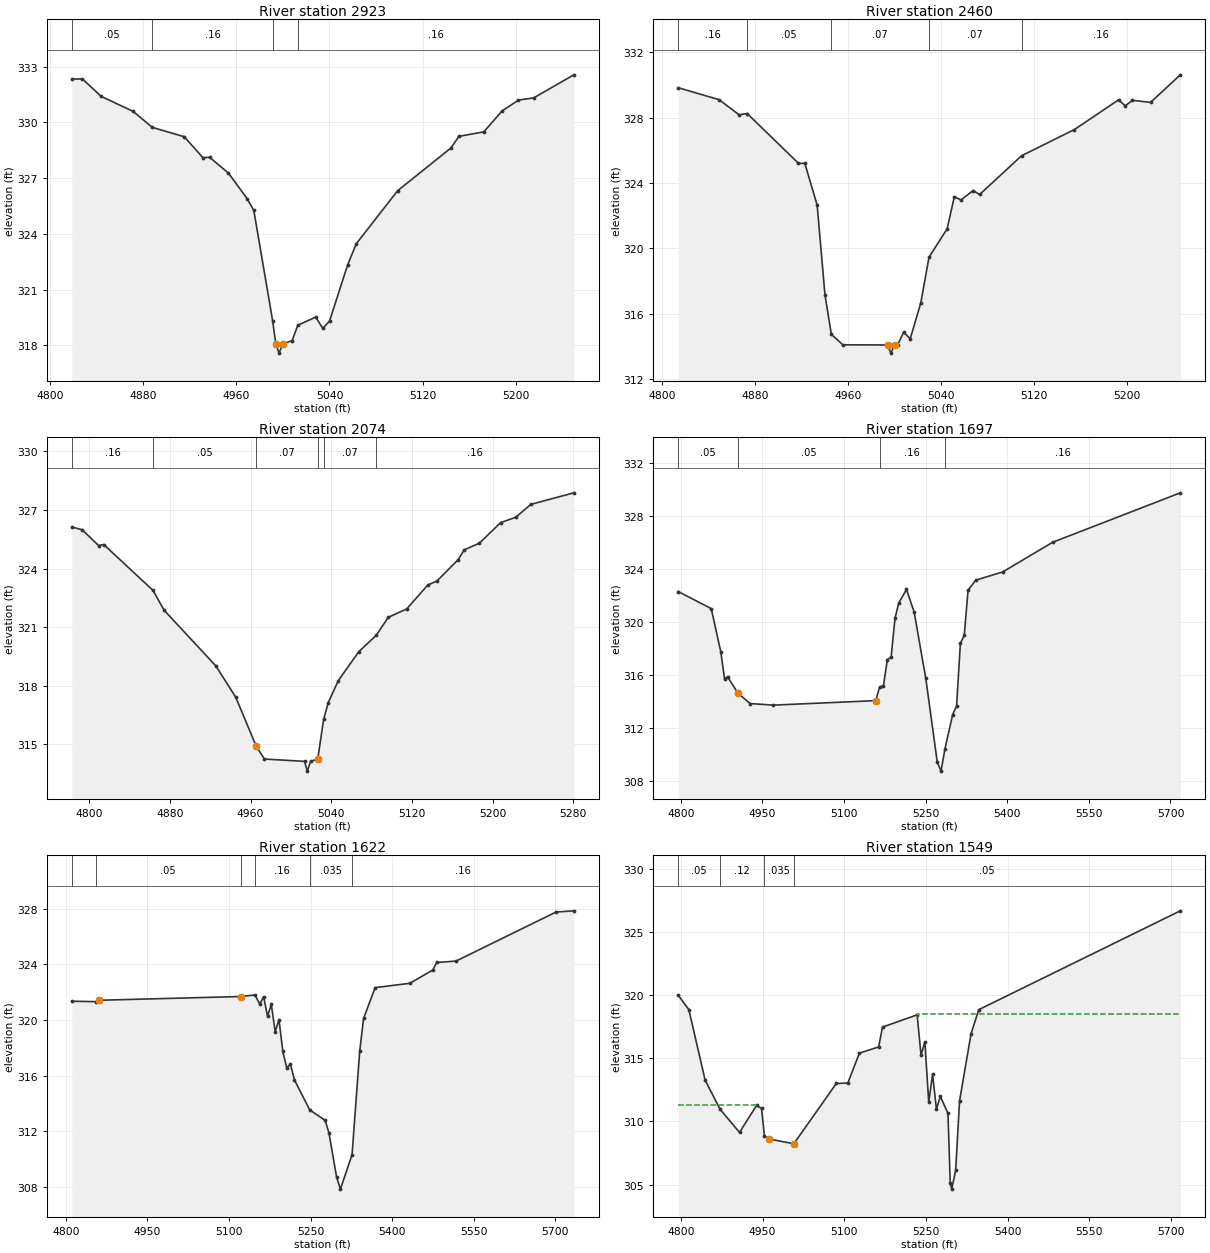
Type RM Length L Ch R = 1 ,2923    ,463,463,463
BEGIN DESCRIPTION:
IRON CREEK TRIBUTARY 1 6.0
END DESCRIPTION:
XS GIS Cut Line= 3
      3574106.16     10305302.93      3573942.11     10305391.64
      3573731.18     10305516.46
#Sta/Elev= 30
  4818.5  332.33  4827.6  332.34  4843.8   331.4  4871.3  330.59  4887.8  329.73
  4915.1  329.23  4931.3   328.1    4937  328.12  4953.2  327.27  4969.3  325.89
    4975  325.26  4991.2  319.31  4993.9  318.08  4996.7  317.58  4999.9  318.08
  5007.9  318.25  5012.8  319.08  5028.2  319.52  5034.3  318.91  5040.1  319.31
  5055.7  322.34  5063.1  323.47  5098.6  326.32  5144.4  328.62  5151.3  329.25
  5172.7  329.49  5188.3  330.61  5202.5   331.2  5215.6  331.32  5250.1  332.56
#Mann= 4 ,-1 , 0
  4818.5     .05       0  4887.8     .16       0  4991.2     .07       0
  5012.8     .16       0
Bank Sta=4993.9,4999.9
XS Rating Curve= 0 ,0
Exp/Cntr=0.3,0.1

Type RM Length L Ch R = 1 ,2460    ,386,386,386
BEGIN DESCRIPTION:
IRON CREEK TRIBUTARY 1 5.0
END DESCRIPTION:
XS GIS Cut Line= 3
       3573960.3     10304912.31      3573792.11     10304991.64
      3573575.98     10305109.63
#Sta/Elev= 30
  4814.1  329.84  4849.2  329.11  4866.5  328.18  4873.4  328.26  4917.6  325.21
  4923.1   325.2  4933.7  322.64  4940.4  317.16  4945.9  314.73  4955.8  314.09
  4994.3  314.08  4997.1  313.58  5000.3  314.08  5002.9  314.08  5008.1  314.86
  5013.8  314.46  5022.9  316.66    5030  319.46  5045.6   321.2  5051.8  323.17
  5057.5  322.96  5067.9  323.54  5073.6   323.3  5109.6  325.67  5155.2  327.28
  5193.2   329.1  5198.9  328.73  5205.1  329.07  5220.7  328.94  5246.3  330.63
#Mann= 5 ,-1 , 0
  4814.1     .16       0  4873.4     .05       0  4945.9     .07       0
    5030     .07       0  5109.6     .16       0
Bank Sta=4994.3,5000.3
XS Rating Curve= 0 ,0
Exp/Cntr=0.3,0.1

Type RM Length L Ch R = 1 ,2074    ,377,377,377
BEGIN DESCRIPTION:
IRON CREEK TRIBUTARY 1 4.0
END DESCRIPTION:
XS GIS Cut Line= 3
      3573792.14     10304641.64      3573479.61     10304698.93
      3573329.62     10304798.92
#Sta/Elev= 30
  4782.6  326.13  4792.8  325.99  4809.2  325.18  4814.3  325.23  4863.2  322.88
  4874.1  321.87  4925.7     319  4945.3   317.4  4965.6  314.89  4973.7  314.24
  5013.5  314.12  5016.2  313.62  5019.5  314.12  5026.6  314.24  5032.4  316.27
    5037  317.13    5047  318.26  5067.3  319.74  5084.6  320.58  5096.5   321.5
  5114.8  321.93  5135.8  323.16  5144.8  323.36  5165.9  324.46  5171.9  324.96
  5186.9   325.3  5207.9  326.35    5223  326.63    5238  327.29  5280.6  327.88
#Mann= 6 ,-1 , 0
  4782.6     .16       0  4863.2     .05       0  4965.6     .07       0
  5026.6     .05       0  5032.4     .07       0  5084.6     .16       0
Bank Sta=4965.6,5026.6
XS Rating Curve= 0 ,0
Exp/Cntr=0.3,0.1

Type RM Length L Ch R = 1 ,1697    ,75,75,75
BEGIN DESCRIPTION:
IRON CREEK TRIBUTARY 1 3.2
END DESCRIPTION:
XS GIS Cut Line= 3
      3573705.12     10304235.22      3573517.63     10304308.13
      3573002.04      10304813.3
#Sta/Elev= 30
  4795.1  322.27  4855.8  320.98  4873.4  317.71  4880.3  315.67  4885.7  315.84
  4904.8  314.61  4927.1  313.82    4970   313.7  5158.2  314.04  5165.3  315.07
  5172.3  315.15  5179.5  317.12  5186.5  317.33  5193.6  320.26  5200.6  321.42
  5214.7  322.43  5228.9  320.71  5250.2  315.71  5271.3   309.4  5278.2  308.72
  5285.5  310.41  5299.6  312.99  5306.8  313.63  5313.8  318.37  5320.9  318.97
  5327.9  322.37    5342  323.13  5391.6  323.75  5483.5  325.99  5718.1  329.72
#Mann= 4 ,-1 , 0
  4795.1     .05       0  4904.8     .05       0  5165.3     .16       0
  5285.5     .16       0
#Block Obstruct= 2 , 0
                         5158.14          313.79
Bank Sta=4904.8,5158.2
XS Rating Curve= 0 ,0
Exp/Cntr=0.3,0.1

Type RM Length L Ch R = 1 ,1622    ,73,73,73
BEGIN DESCRIPTION:
IRON CREEK TRIBUTARY 1 3.1
END DESCRIPTION:
XS GIS Cut Line= 3
      3573653.08     10304177.91      3573465.54     10304250.84
      3572949.91     10304756.05
#Sta/Elev= 30
    4811  321.35    4855  321.32  4861.5  321.42  5121.3  321.69  5147.8   321.8
  5156.7  321.14  5163.7  321.68  5170.9  320.28  5177.9  321.12    5185  319.15
    5192  320.02    5199  317.75  5206.1  316.57  5213.1   316.8  5220.3  315.69
  5248.6  313.52  5276.9  312.77  5283.9  311.85    5298  308.67  5304.9  307.82
  5326.3   310.3  5340.4  317.76  5347.6  320.12  5368.7  322.33  5432.5  322.64
  5474.9   323.6  5481.9  324.14  5517.3  324.24  5701.2  327.77  5734.1  327.86
#Mann= 6 ,-1 , 0
    4811     .16       0    4855     .05       0  5121.3     .07       0
  5147.8     .16       0  5248.6    .035       0  5326.3     .16       0
Bank Sta=4861.5,5121.3
XS Rating Curve= 0 ,0
Exp/Cntr=0.3,0.1

Type RM Length L Ch R = 1 ,1549    ,465,465,465
BEGIN DESCRIPTION:
IRON CREEK TRIBUTARY 1 3.0
END DESCRIPTION:
XS GIS Cut Line= 3
      3573626.97     10304110.23       3573439.5     10304183.13
      3572924.75     10304687.49
#Sta/Elev= 30
  4795.1  319.98  4814.6  318.84  4844.5  313.26  4871.9  310.96  4907.6  309.13
 4938.86  311.26    4948  311.02  4953.3  308.86  4961.3  308.61  5007.4  308.23
  5085.3     313  5106.4  313.03  5127.7   315.4    5163  315.89  5170.2  317.46
  5233.7  318.43  5240.9  315.23  5247.9   316.3    5255  311.52    5262  313.71
  5269.2  310.96  5276.2  311.98  5290.3  310.63  5294.5  305.14  5297.2  304.64
  5304.5  306.15  5311.6  311.62  5332.7  316.93  5346.9  318.84  5716.9  326.66
#Mann= 4 ,-1 , 0
  4795.1     .05       0  4871.9     .12       0  4953.3    .035       0
  5007.4     .05       0
#XS Ineff= 2 , 0
         4938.86   311.3 5234.09          318.47
Permanent Ineff=
       F       F
#Block Obstruct= 2 , 0
                         5000.29          307.26
Bank Sta=4961.3,5007.4
XS Rating Curve= 0 ,0
Exp/Cntr=0.3,0.1

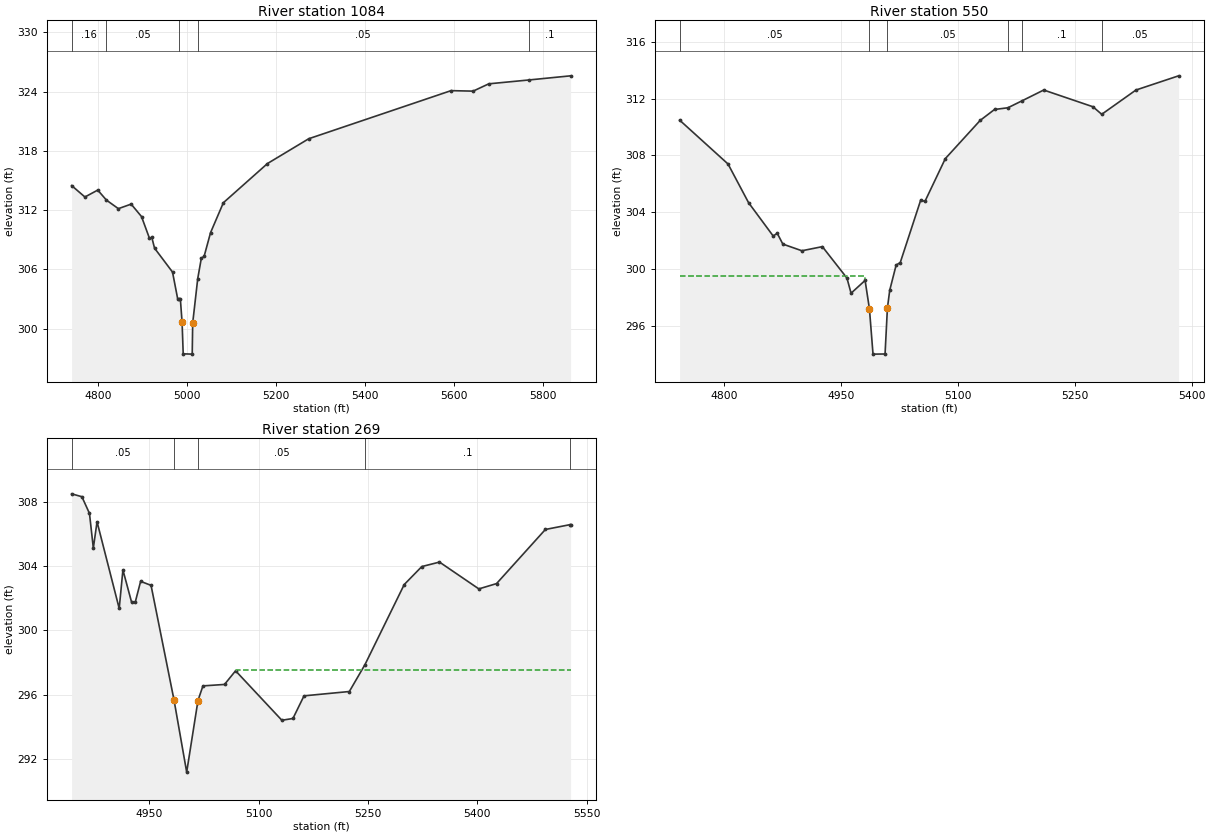
Type RM Length L Ch R = 1 ,1084    ,534,534,534
BEGIN DESCRIPTION:
IRON CREEK TRIBUTARY 1 2.0
END DESCRIPTION:
XS GIS Cut Line= 3
      3573512.41     10303693.55      3573292.11     10303791.64
      3572606.64     10304344.21
#Sta/Elev= 30
  4739.9  314.49  4769.8  313.33  4798.6  314.03  4818.3  313.01    4845  312.15
  4873.7  312.61    4897  311.35  4914.7  309.17  4920.2  309.23  4926.3  308.15
  4966.7  305.73  4978.3  303.02  4981.1  303.02  4984.3  303.02  4988.2  300.65
 4990.73  297.45 5010.99  297.42 5012.05  300.56  5023.4  305.07  5031.4  307.11
  5037.8  307.33  5052.2  309.72    5081  312.75  5180.2  316.72  5272.9  319.23
  5592.8   324.1  5642.4  324.05  5677.6  324.79  5767.6  325.18  5861.5   325.6
#Mann= 5 ,-1 , 0
  4739.9     .16       0  4818.3     .05       0  4981.1     .03       0
  5023.4     .05       0  5767.6      .1       0
Bank Sta=4988.2,5012.05
XS Rating Curve= 0 ,0
Exp/Cntr=0.3,0.1

Type RM Length L Ch R = 1 ,550     ,281,281,281
BEGIN DESCRIPTION:
IRON CREEK TRIBUTARY 1 1.0
END DESCRIPTION:
XS GIS Cut Line= 3
      3573517.65     10303375.85      3572958.25     10303188.34
      3572908.24     10303188.34
#Sta/Elev= 30
  4743.3  310.49  4805.4   307.4  4831.7  304.68  4863.3  302.33  4868.5  302.52
  4875.7  301.76  4900.1  301.29  4926.4  301.58  4957.9  299.37  4963.2   298.3
  4981.2   299.2 4986.76   297.2 4991.36  294.01  5006.8  294.02 5009.83  297.26
  5012.8  298.51    5021  300.28  5026.3  300.46  5052.6  304.87  5057.9  304.76
  5084.1  307.78  5128.8  310.47  5147.2  311.24  5164.3  311.36  5182.5  311.85
  5210.3  312.61  5273.5  311.43  5284.7   310.9  5328.6  312.61  5383.3  313.61
#Mann= 6 ,-1 , 0
  4743.3     .05       0 4986.76     .03       0 5009.83     .05       0
  5164.3     .16       0  5182.5      .1       0  5284.7     .05       0
#XS Ineff= 2 , 0
         4981.19  299.48
Permanent Ineff=
       F       F
Bank Sta=4986.76,5009.83
XS Rating Curve= 0 ,0
Exp/Cntr=0.3,0.1

Type RM Length L Ch R = 1 ,269     ,0,0,0
BEGIN DESCRIPTION:
IRON CREEK TRIBUTARY 1 1.0111
END DESCRIPTION:
XS GIS Cut Line= 4
      3573494.58     10303185.32      3573473.76     10303104.63
      3573228.97     10302948.38       3572939.9     10303062.96
#Sta/Elev= 30
  4843.2   308.5  4857.3  308.32  4867.7  307.28    4873  305.12  4878.1  306.76
  4908.5  301.36  4913.6  303.76  4925.5  301.75  4930.5  301.75  4937.9  303.05
  4952.2   302.8 4983.64  295.68  5001.1  291.17  5016.6  295.63  5023.4  296.54
    5053  296.63  5068.2  297.48  5131.7   294.4  5146.9  294.51  5162.1  295.92
  5224.3  296.19  5245.8  297.87  5299.6  302.85  5323.7  303.97    5348  304.25
    5402  302.58  5426.3  302.91  5493.3  306.28  5527.1  306.58  5527.9  306.58
#Mann= 5 ,-1 , 0
  4843.2     .05       0 4983.64    .035       0  5016.6     .05       0
  5245.8      .1       0  5527.1     .05       0
#XS Ineff= 2 , 0
                         5068.64          297.56
Permanent Ineff=
       F       F
Bank Sta=4983.64,5016.6
XS Rating Curve= 0 ,0
Exp/Cntr=0.3,0.1

Chan Stop Cuts=-1
Use User Specified Reach Order=0
Composite Channel Slope=5