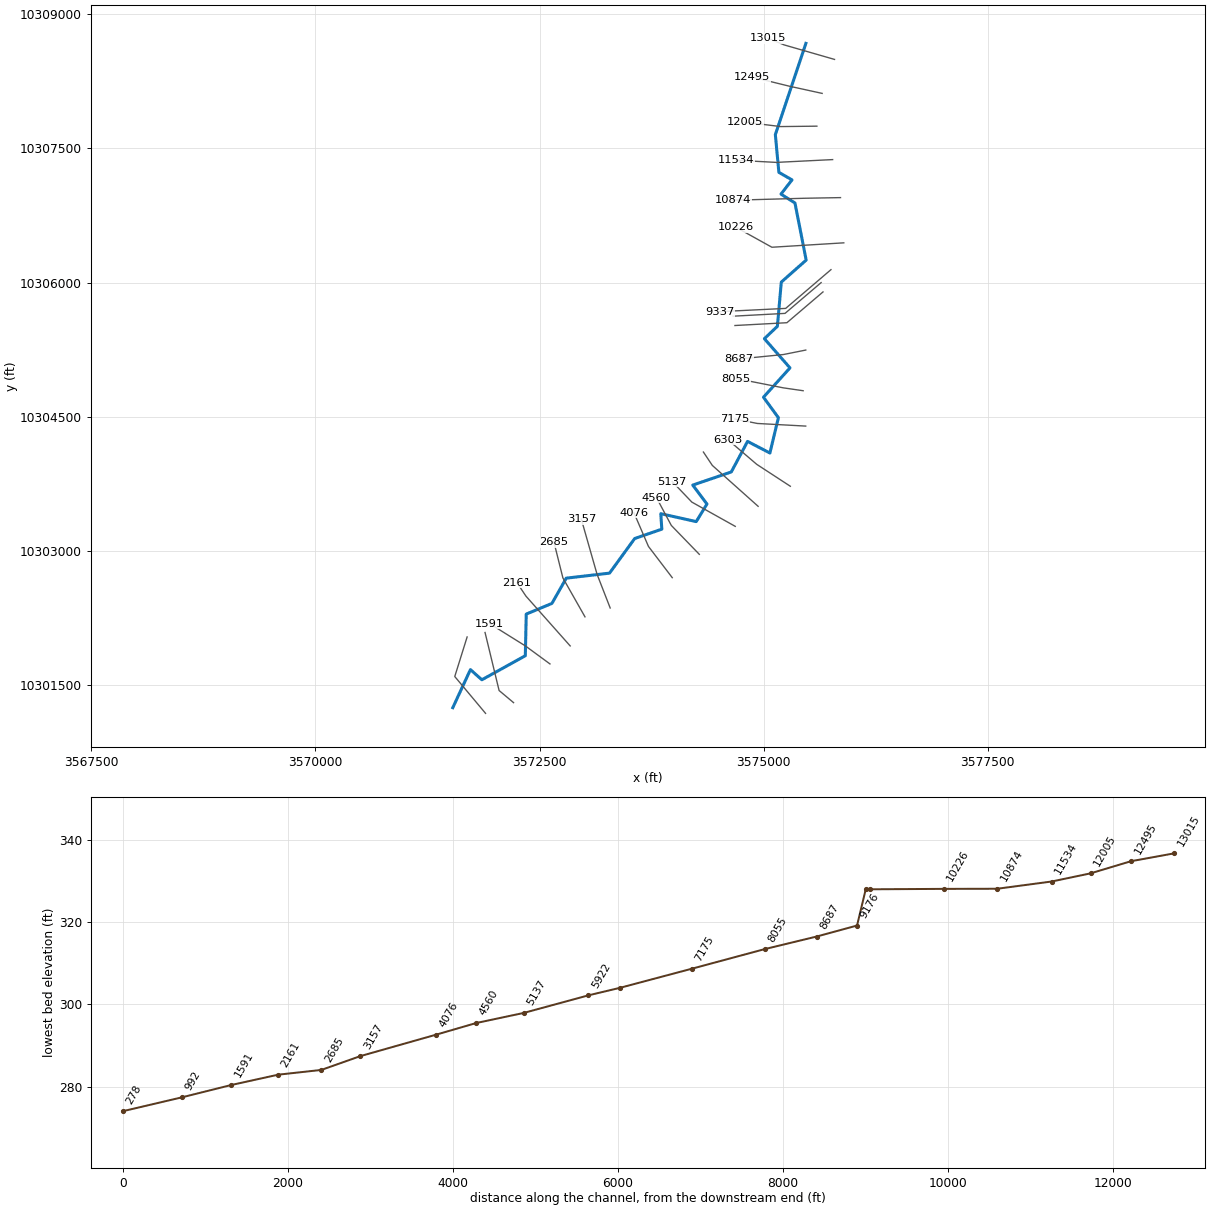
--- IRON CREEK.prj (project) ---

Proj Title=IRON CREEK Base Level Engineering
Current Plan=p01
Default Exp/Contr=0.3,0.1
English Units
Geom File=g01
Flow File=f01
Plan File=p01
BEGIN DESCRIPTION:
IRON CREEK
END DESCRIPTION:

--- IRON CREEK.p01 (plan) ---

Plan Title=Multiple Run
Short Identifier=Multiple
Geom File=g01
Flow File=f01
Subcritical Flow
K Sum by GR= 0
Std Step Tol= 0.01
Critical Tol= 0.01
Num of Std Step Trials= 20
Max Error Tol= 0.3
Flow Tol Ratio= 0.001
Split Flow NTrial= 30
Split Flow Tol= 0.02
Split Flow Ratio= 0.02
Log Output Level= 0
Friction Slope Method= 1
Unsteady Friction Slope Method= 2
Unsteady Bridges Friction Slope Method= 1
Parabolic Critical Depth
Global Vel Dist=  1 , 1 , 1
Global Log Level= 0
CheckData=True
Encroach Param= -1, 0, 0, 0
BEGIN DESCRIPTION:
Multiple Run
END DESCRIPTION:

--- IRON CREEK.f01 (steady flow) ---

Flow Title=Multiple
Number of Profiles=7
Profile Names=10-year,25-year,50-year,1pct_min,100-year,1pct_plu,500-year
River Rch & RM= IRON CREEK,Reach-1,13015
     407     535     637     557     753    1018    1052
River Rch & RM= IRON CREEK,Reach-1,3157
     596     801     967     856    1158    1566    1662
Boundary for River Rch & Prof#=IRON CREEK,Reach-1,1
Up Type=0
Dn Type=3
Dn Slope=0.005
Boundary for River Rch & Prof#=IRON CREEK,Reach-1,2
Up Type=0
Dn Type=3
Dn Slope=0.005
Boundary for River Rch & Prof#=IRON CREEK,Reach-1,3
Up Type=0
Dn Type=3
Dn Slope=0.005
Boundary for River Rch & Prof#=IRON CREEK,Reach-1,4
Up Type=0
Dn Type=3
Dn Slope=0.005
Boundary for River Rch & Prof#=IRON CREEK,Reach-1,5
Up Type=0
Dn Type=3
Dn Slope=0.005
Boundary for River Rch & Prof#=IRON CREEK,Reach-1,6
Up Type=0
Dn Type=3
Dn Slope=0.005
Boundary for River Rch & Prof#=IRON CREEK,Reach-1,7
Up Type=0
Dn Type=3
Dn Slope=0.005

--- IRON CREEK.g01 (geometry) ---

Geom Title=Existing Conditions

River Reach=IRON CREEK,Reach-1
Reach XY= 30
      3575472.58     10308670.89      3575131.66     10307651.36
      3575171.07     10307230.32      3575317.41     10307146.27
      3575194.64     10306987.48      3575350.74     10306887.93
      3575475.66     10306250.36      3575198.31     10306005.14
      3575154.33     10305510.92      3575009.37     10305372.90
      3575294.96     10305046.51      3574999.12     10304719.08
      3575165.79     10304490.61      3575070.92     10304095.94
      3574821.61     10304225.81      3574640.31     10303884.53
      3574210.08     10303737.83      3574368.49     10303526.33
      3574248.63     10303329.89      3573853.28     10303418.40
      3573864.67     10303245.61      3573562.09     10303141.06
      3573281.11     10302754.48      3572798.56     10302698.40
      3572638.36     10302416.24      3572351.87     10302297.14
      3572341.47     10301832.04      3571856.32     10301563.39
      3571729.03     10301677.22      3571532.11     10301251.64

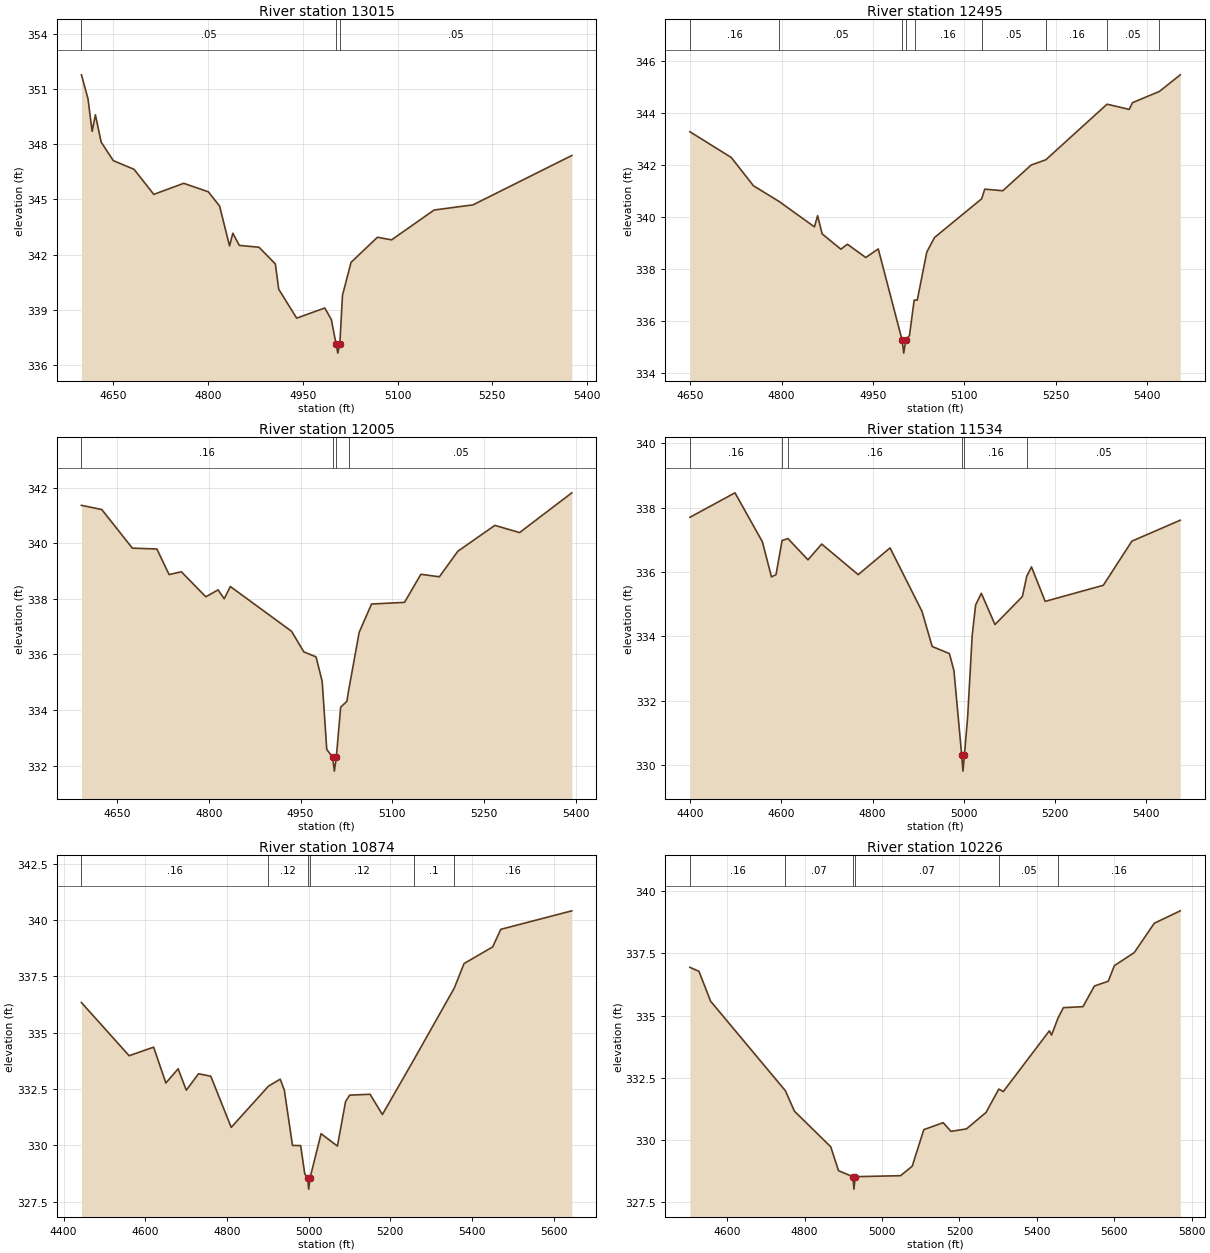
Type RM Length L Ch R = 1,13015,520,520,520
BEGIN DESCRIPTION:
IRON CREEK 24.0
END DESCRIPTION:
XS GIS Cut Line= 3
      3575792.13     10308491.64      3575229.34     10308653.93
      3575053.70     10308727.11
#Sta/Elev= 30
  4599.7  351.76  4610.1  350.46  4616.6  348.69  4621.8  349.59  4630.9  348.11
  4650.2  347.10  4683.0  346.63  4714.2  345.27  4761.6  345.87  4800.4  345.41
  4818.3  344.64  4834.1  342.47  4839.3  343.16  4849.5  342.50  4880.7  342.40
  4906.6  341.49  4911.9  340.12  4940.3  338.55  4984.8  339.10  4995.2  338.47
  5002.6  337.15  5005.4  336.65  5008.6  337.15  5012.8  339.79  5026.4  341.58
  5068.1  342.94  5090.5  342.80  5157.8  344.42  5219.4  344.70  5375.7  347.38
#Mann=3,-1,0
  4599.7    0.05       0  5002.6   0.035       0  5008.6    0.05       0
Bank Sta=5002.6,5008.6
Exp/Cntr=0.3,0.1

Type RM Length L Ch R = 1,12495,490,490,490
BEGIN DESCRIPTION:
IRON CREEK 23.0
END DESCRIPTION:
XS GIS Cut Line= 3
      3575653.93     10308112.24      3575292.11     10308191.64
      3574870.69     10308295.24
#Sta/Elev= 30
  4649.7  343.27  4717.5  342.28  4754.0  341.19  4795.8  340.59  4854.0  339.61
  4859.2  340.04  4866.6  339.34  4897.3  338.75  4908.1  338.94  4938.2  338.43
  4958.7  338.76  4997.8  335.25  5000.5  334.75  5003.8  335.25  5009.9  335.43
  5017.6  336.79  5018.8  336.79  5022.7  336.79  5038.3  338.64  5051.0  339.20
  5128.3  340.69  5133.4  341.06  5163.0  341.00  5209.6  341.99  5233.5  342.19
  5334.0  344.33  5370.3  344.13  5375.8  344.39  5419.8  344.82  5454.1  345.46
#Mann=9,-1,0
  4649.7    0.16       0  4795.8    0.05       0  4997.8   0.035       0
  5003.8    0.05       0  5018.8    0.16       0  5128.3    0.05       0
  5233.5    0.16       0  5334.0    0.05       0  5419.8    0.16       0
Bank Sta=4997.8,5003.8
Exp/Cntr=0.3,0.1

Type RM Length L Ch R = 1,12005,471,471,471
BEGIN DESCRIPTION:
IRON CREEK 22.0
END DESCRIPTION:
XS GIS Cut Line= 3
      3575595.31     10307746.25      3575192.11     10307741.64
      3574797.41     10307790.17
#Sta/Elev= 30
  4592.1  341.36  4625.3  341.21  4675.3  339.82  4715.3  339.79  4735.3  338.87
  4755.3  338.97  4795.3  338.07  4815.3  338.32  4825.3  338.00  4835.3  338.44
  4935.3  336.83  4955.3  336.09  4975.3  335.91  4985.3  335.03  4992.8  332.58
  5002.4  332.30  5005.2  331.80  5008.4  332.30  5015.5  334.10  5025.6  334.31
  5028.9  334.75  5045.7  336.79  5065.9  337.81  5119.8  337.87  5146.5  338.88
  5176.7  338.79  5206.9  339.71  5267.4  340.64  5307.7  340.38  5393.0  341.81
#Mann=4,-1,0
  4592.1    0.16       0  5002.4    0.07       0  5008.4    0.16       0
  5028.9    0.05       0
Bank Sta=5002.4,5008.4
Exp/Cntr=0.3,0.1

Type RM Length L Ch R = 1,11534,660,660,660
BEGIN DESCRIPTION:
IRON CREEK 21.0
END DESCRIPTION:
XS GIS Cut Line= 3
      3575771.00     10307372.93      3575142.11     10307341.64
      3574696.02     10307365.55
#Sta/Elev= 30
  4399.0  337.70  4498.0  338.46  4558.1  336.94  4578.1  335.85  4588.1  335.92
  4601.3  336.98  4614.2  337.04  4658.2  336.38  4688.3  336.87  4768.4  335.92
  4838.4  336.75  4908.5  334.78  4930.8  333.69  4968.6  333.47  4978.6  332.94
  4995.6  330.32  4998.4  329.82  5001.6  330.32  5008.7  331.51  5018.7  334.04
  5026.2  334.98  5038.7  335.34  5068.7  334.37  5128.8  335.24  5138.4  335.87
  5148.8  336.16  5178.9  335.09  5306.5  335.59  5369.2  336.96  5475.4  337.61
#Mann=6,-1,0
  4399.0    0.16       0  4601.3    0.12       0  4614.2    0.16       0
  4995.6    0.07       0  5001.6    0.16       0  5138.4    0.05       0
Bank Sta=4995.6,5001.6
Exp/Cntr=0.3,0.1

Type RM Length L Ch R = 1,10874,648,648,648
BEGIN DESCRIPTION:
IRON CREEK 20.0
END DESCRIPTION:
XS GIS Cut Line= 3
      3575858.87     10306948.37      3575456.26     10306941.05
      3574658.34     10306919.09
#Sta/Elev= 30
  4443.7  336.34  4560.5  333.98  4620.5  334.36  4650.5  332.77  4680.5  333.40
  4700.5  332.45  4730.5  333.18  4760.5  333.07  4810.5  330.80  4901.7  332.63
  4930.6  332.94  4940.6  332.45  4960.6  330.00  4980.6  329.99  4990.6  328.74
  4997.6  328.56  5000.3  328.06  5003.6  328.56  5030.6  330.52  5070.6  329.97
  5090.6  331.95  5100.6  332.23  5150.6  332.27  5180.7  331.37  5258.0  333.81
  5356.7  336.98  5380.7  338.07  5450.8  338.81  5470.8  339.59  5644.6  340.41
#Mann=6,-1,0
  4443.7    0.16       0  4901.7    0.12       0  4997.6    0.07       0
  5003.6    0.12       0  5258.0     0.1       0  5356.7    0.16       0
Bank Sta=4997.6,5003.6
Exp/Cntr=0.3,0.1

Type RM Length L Ch R = 1,10226,889,889,889
BEGIN DESCRIPTION:
IRON CREEK 19.0
END DESCRIPTION:
XS GIS Cut Line= 3
      3575895.51     10306443.29      3575093.23     10306394.00
      3574688.05     10306619.10
#Sta/Elev= 30
  4503.4  336.94  4526.8  336.78  4556.9  335.58  4750.3  331.98  4773.6  331.16
  4867.5  329.73  4887.5  328.77  4924.6  328.53  4927.3  328.03  4930.6  328.53
  5047.8  328.57  5077.9  328.95  5107.9  330.42  5158.0  330.70  5178.1  330.35
  5218.1  330.45  5268.7  331.11  5301.7  332.05  5313.4  331.95  5432.4  334.39
  5438.1  334.22  5454.7  334.90  5468.6  335.32  5519.3  335.36  5548.7  336.19
  5584.5  336.38  5600.5  337.01  5651.7  337.53  5703.5  338.71  5770.7  339.21
#Mann=6,-1,0
  4503.4    0.16       0  4750.3    0.07       0  4924.6    0.07       0
  4930.6    0.07       0  5301.7    0.05       0  5454.7    0.16       0
Bank Sta=4924.6,4930.6
Exp/Cntr=0.3,0.1

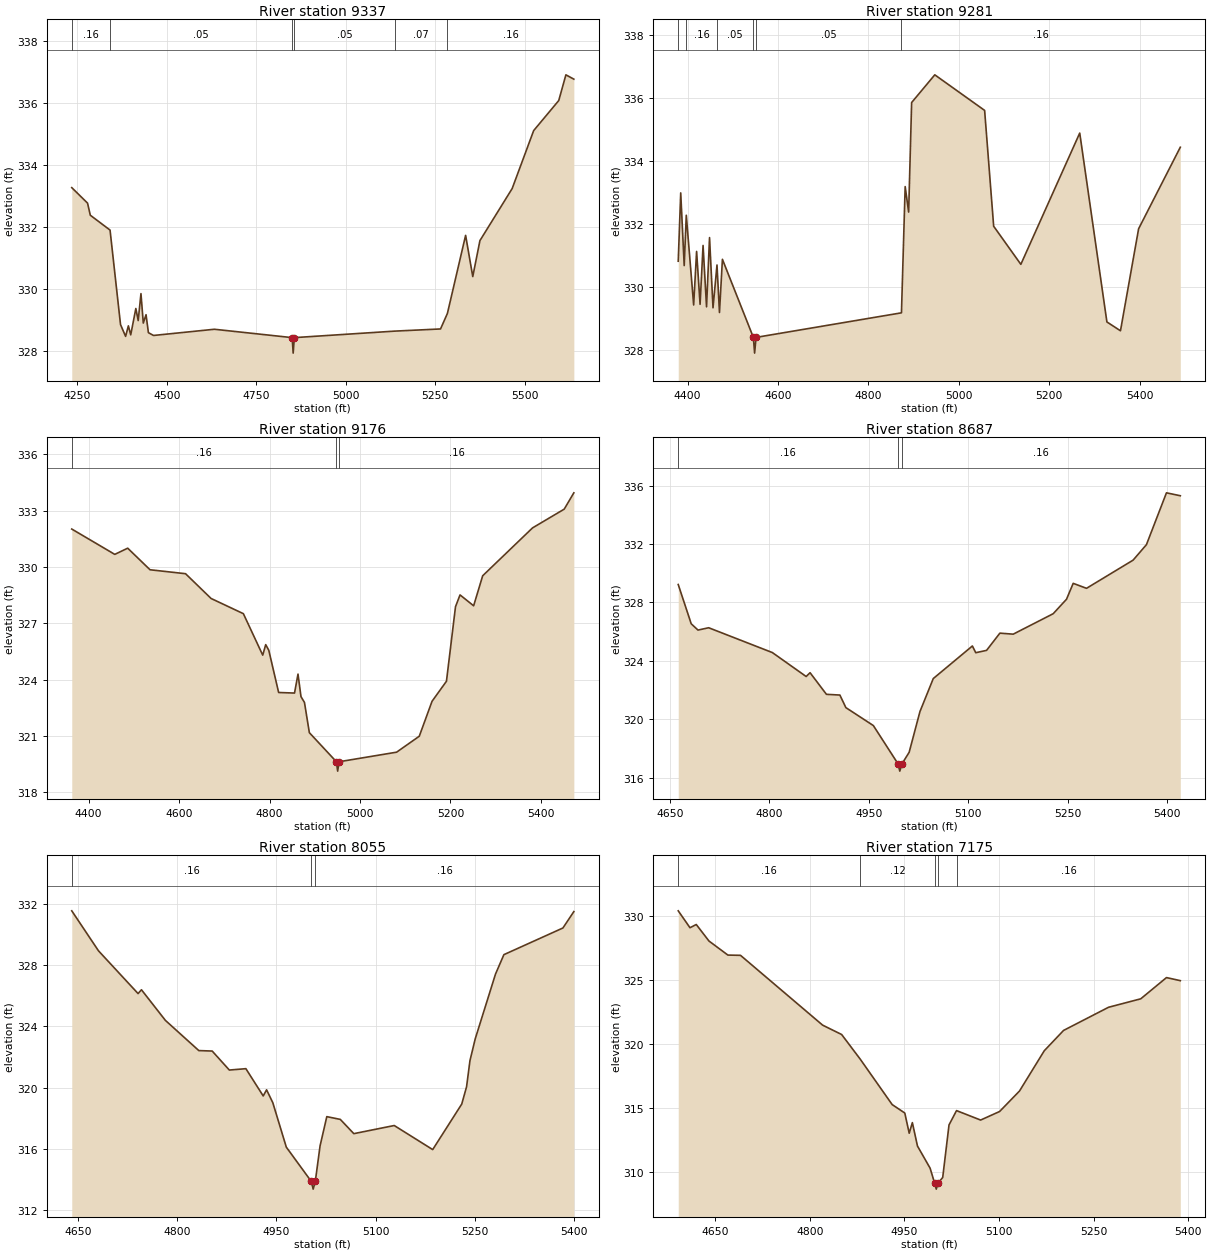
Type RM Length L Ch R = 1,9337,56,56,56
BEGIN DESCRIPTION:
IRON CREEK 17.1
END DESCRIPTION:
XS GIS Cut Line= 3
      3575752.36     10306143.78      3575246.79     10305710.91
      3574509.94     10305674.83
#Sta/Elev= 30
  4234.4  333.27  4278.5  332.77  4286.2  332.38  4341.4  331.90  4370.7  328.85
  4384.9  328.47  4392.6  328.81  4399.2  328.52  4413.5  329.37  4420.1  328.98
  4427.8  329.85  4434.3  328.90  4442.0  329.17  4448.6  328.59  4462.9  328.50
  4633.0  328.70  4850.5  328.43  4853.2  327.93  4856.5  328.43  5136.9  328.64
  5265.1  328.71  5284.3  329.21  5335.2  331.73  5355.2  330.40  5375.2  331.56
  5465.3  333.24  5525.4  335.11  5595.5  336.08  5615.5  336.91  5637.7  336.77
#Mann=6,-1,0
  4234.4    0.16       0  4341.4    0.05       0  4850.5   0.033       0
  4856.5    0.05       0  5136.9    0.07       0  5284.3    0.16       0
Bank Sta=4850.5,4856.5
Exp/Cntr=0.3,0.1

Type RM Length L Ch R = 1,9281,105,105,105
BEGIN DESCRIPTION:
IRON CREEK 17.0
END DESCRIPTION:
XS GIS Cut Line= 3
      3575642.62     10305999.10      3575239.85     10305655.35
      3574660.01     10305624.10
#Sta/Elev= 30
  4379.5  330.82  4385.0  332.99  4392.7  330.68  4397.3  332.28  4413.6  329.43
  4420.1  331.13  4427.8  329.45  4434.4  331.32  4442.1  329.37  4448.7  331.57
  4456.4  329.34  4465.2  330.70  4470.7  329.19  4477.2  330.88  4545.6  328.40
  4548.4  327.90  4551.6  328.40  4873.1  329.18  4881.3  333.19  4889.0  332.38
  4895.6  335.86  4946.8  336.74  5057.0  335.61  5077.0  331.93  5137.1  330.72
  5267.3  334.89  5327.4  328.89  5357.4  328.61  5397.5  331.85  5489.7  334.44
#Mann=6,-1,0
  4379.5    0.05       0  4397.3    0.16       0  4465.2    0.05       0
  4545.6    0.07       0  4551.6    0.05       0  4873.1    0.16       0
Bank Sta=4545.6,4551.6
Exp/Cntr=0.3,0.1

Type RM Length L Ch R = 1,9176,489,489,489
BEGIN DESCRIPTION:
IRON CREEK 16.0
END DESCRIPTION:
XS GIS Cut Line= 3
      3575663.50     10305894.97      3575260.68     10305551.19
      3574680.79     10305519.93
#Sta/Elev= 30
  4362.6  332.02  4457.7  330.67  4486.3  331.00  4535.7  329.85  4614.2  329.64
  4670.7  328.32  4742.1  327.51  4784.9  325.30  4791.5  325.86  4798.3  325.56
  4820.1  323.31  4855.2  323.28  4862.9  324.29  4869.5  323.09  4877.2  322.78
  4888.0  321.17  4947.8  319.62  4950.6  319.12  4953.8  319.62  5081.0  320.13
  5131.1  320.98  5159.3  322.84  5191.2  323.91  5211.2  327.88  5221.2  328.51
  5251.3  327.93  5271.3  329.53  5381.5  332.08  5451.6  333.08  5472.9  333.95
#Mann=3,-1,0
  4362.6    0.16       0  4947.8    0.07       0  4953.8    0.16       0
Bank Sta=4947.8,4953.8
Exp/Cntr=0.3,0.1

Type RM Length L Ch R = 1,8687,632,632,632
BEGIN DESCRIPTION:
IRON CREEK 15.0
END DESCRIPTION:
XS GIS Cut Line= 3
      3575471.31     10305245.82      3575221.27     10305195.81
      3574721.26     10305145.81
#Sta/Elev= 30
  4662.7  329.23  4682.3  326.54  4692.5  326.11  4708.6  326.27  4804.7  324.57
  4855.7  322.93  4861.6  323.19  4886.3  321.71  4906.6  321.66  4915.6  320.80
  4957.1  319.57  4994.3  316.95  4997.0  316.45  5000.3  316.95  5011.1  317.74
  5027.4  320.53  5047.5  322.79  5106.5  325.02  5111.6  324.56  5127.9  324.72
  5148.0  325.90  5168.1  325.83  5228.4  327.23  5248.5  328.22  5258.6  329.31
  5278.7  328.97  5349.0  330.90  5369.1  331.96  5399.3  335.51  5420.2  335.31
#Mann=3,-1,0
  4662.7    0.16       0  4994.3    0.07       0  5000.3    0.16       0
Bank Sta=4994.3,5000.3
Exp/Cntr=0.3,0.1

Type RM Length L Ch R = 1,8055,880,880,880
BEGIN DESCRIPTION:
IRON CREEK 14.0
END DESCRIPTION:
XS GIS Cut Line= 3
      3575442.11     10304791.64      3575220.75     10304823.76
      3574695.92     10304927.68
#Sta/Elev= 30
  4641.0  331.54  4681.4  328.93  4741.2  326.14  4746.3  326.39  4782.5  324.39
  4833.0  322.42  4853.2  322.39  4879.1  321.15  4904.1  321.24  4930.3  319.46
  4935.4  319.86  4944.8  319.02  4965.2  316.12  5003.0  313.88  5005.8  313.38
  5009.0  313.88  5016.2  316.20  5026.4  318.11  5046.8  317.93  5067.2  317.00
  5128.3  317.53  5186.4  315.96  5230.3  318.93  5237.6  320.06  5242.7  321.76
  5250.7  323.19  5281.3  327.41  5294.0  328.68  5383.2  330.42  5399.7  331.49
#Mann=3,-1,0
  4641.0    0.16       0  5003.0    0.07       0  5009.0    0.16       0
Bank Sta=5003,5009
Exp/Cntr=0.3,0.1

Type RM Length L Ch R = 1,7175,872,872,872
BEGIN DESCRIPTION:
IRON CREEK 13.0
END DESCRIPTION:
XS GIS Cut Line= 3
      3575470.71     10304396.67      3574930.65     10304426.02
      3574680.65     10304476.02
#Sta/Elev= 30
  4591.6  330.39  4610.2  329.07  4620.2  329.32  4640.3  328.03  4670.3  326.93
  4690.3  326.91  4820.5  321.45  4850.6  320.72  4880.1  318.79  4930.7  315.24
  4950.7  314.58  4957.7  313.00  4962.7  313.83  4970.8  312.00  4990.8  310.27
  4997.8  309.13  5000.6  308.63  5003.8  309.13  5010.8  309.54  5020.8  313.65
  5032.7  314.77  5070.9  314.03  5101.0  314.70  5132.5  316.30  5171.8  319.45
  5202.4  321.04  5273.7  322.85  5324.7  323.51  5365.5  325.17  5387.4  324.93
#Mann=5,-1,0
  4591.6    0.16       0  4880.1    0.12       0  4997.8    0.07       0
  5003.8    0.12       0  5032.7    0.16       0
Bank Sta=4997.8,5003.8
Exp/Cntr=0.3,0.1

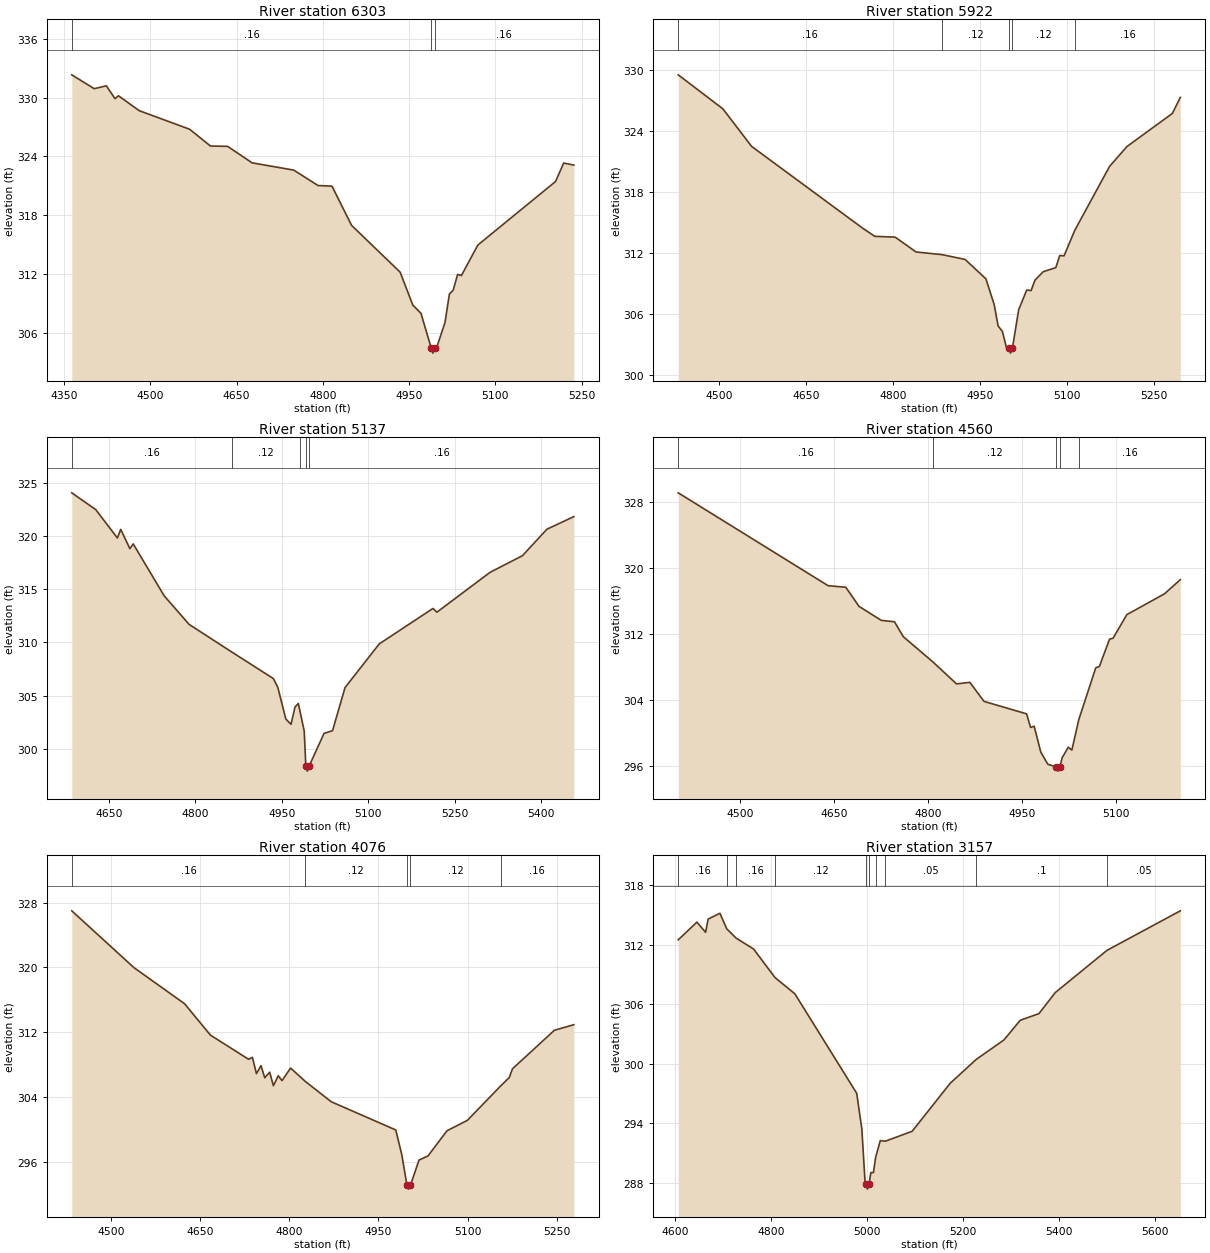
Type RM Length L Ch R = 1,6303,381,381,381
BEGIN DESCRIPTION:
IRON CREEK 12.0
END DESCRIPTION:
XS GIS Cut Line= 3
      3575298.89     10303724.79      3574923.88     10303969.59
      3574600.93     10304245.66
#Sta/Elev= 30
  4363.6  332.31  4402.6  330.90  4423.7  331.19  4438.8  329.88  4444.7  330.18
  4480.9  328.66  4568.5  326.77  4604.7  325.06  4634.4  325.03  4677.1  323.35
  4749.5  322.61  4791.7  321.04  4815.9  320.98  4849.9  316.99  4934.4  312.22
  4956.4  308.87  4970.6  308.03  4988.5  304.48  4991.2  303.98  4994.5  304.48
  4998.1  304.59  5012.3  307.09  5020.0  309.99  5026.6  310.39  5034.3  311.99
  5040.9  311.88  5069.4  314.98  5204.5  321.45  5218.7  323.33  5236.3  323.12
#Mann=3,-1,0
  4363.6    0.16       0  4988.5    0.07       0  4994.5    0.16       0
Bank Sta=4988.5,4994.5
Exp/Cntr=0.3,0.1

Type RM Length L Ch R = 1,5922,785,785,785
BEGIN DESCRIPTION:
IRON CREEK 11.0
END DESCRIPTION:
XS GIS Cut Line= 3
      3574939.52     10303500.83      3574428.56     10303957.27
      3574328.79     10304106.92
#Sta/Elev= 30
  4430.2  329.54  4507.2  326.19  4556.6  322.50  4748.0  314.45  4768.9  313.65
  4804.0  313.57  4840.0  312.11  4884.5  311.85  4924.4  311.38  4960.3  309.47
  4974.5  306.94  4981.3  304.84  4988.8  304.28  4995.5  302.73  5000.0  302.66
  5002.7  302.16  5006.0  302.66  5016.7  306.42  5030.6  308.37  5038.1  308.31
  5044.8  309.34  5059.0  310.17  5080.7  310.57  5087.4  311.76  5094.9  311.73
  5113.3  314.23  5173.4  320.54  5203.4  322.49  5281.5  325.74  5295.2  327.32
#Mann=5,-1,0
  4430.2    0.16       0  4884.5    0.12       0  5000.0    0.07       0
  5006.0    0.12       0  5113.3    0.16       0
Bank Sta=5000,5006
Exp/Cntr=0.3,0.1

Type RM Length L Ch R = 1,5137,577,577,577
BEGIN DESCRIPTION:
IRON CREEK 9.0
END DESCRIPTION:
XS GIS Cut Line= 3
      3574684.30     10303276.87      3574199.92     10303547.71
      3573981.29     10303776.76
#Sta/Elev= 30
  4585.5  324.09  4627.1  322.51  4664.7  319.84  4670.5  320.65  4686.4  318.83
  4692.2  319.28  4745.8  314.40  4789.2  311.70  4863.8  309.08  4935.4  306.60
  4943.2  305.77  4957.1  302.79  4966.1  302.29  4973.1  303.92  4978.8  304.25
  4981.2  303.64  4989.0  301.67  4991.8  298.38  4994.5  297.88  4997.8  298.38
  5023.4  301.43  5038.2  301.69  5059.9  305.75  5119.3  309.86  5212.5  313.20
  5219.4  312.85  5311.6  316.60  5367.9  318.17  5410.3  320.66  5457.1  321.85
#Mann=5,-1,0
  4585.5    0.16       0  4863.8    0.12       0  4981.2    0.16       0
  4991.8    0.07       0  4997.8    0.16       0
Bank Sta=4991.8,4997.8
Exp/Cntr=0.3,0.1

Type RM Length L Ch R = 1,4560,484,484,484
BEGIN DESCRIPTION:
IRON CREEK 8.0
END DESCRIPTION:
XS GIS Cut Line= 3
      3574283.27     10302964.36      3573970.75     10303287.30
      3573804.92     10303598.24
#Sta/Elev= 30
  4401.0  329.05  4640.3  317.83  4668.6  317.64  4689.7  315.33  4725.2  313.64
  4746.3  313.47  4760.5  311.66  4807.5  308.63  4845.4  305.96  4866.7  306.15
  4889.3  303.85  4957.3  302.34  4963.7  300.70  4969.4  300.85  4980.0  297.72
  4991.3  296.25  5004.6  295.92  5007.4  295.42  5010.6  295.92  5014.0  297.02
  5023.9  298.31  5029.6  297.96  5040.7  301.65  5067.8  307.91  5073.5  308.06
  5089.8  311.37  5095.4  311.48  5117.4  314.33  5177.6  316.85  5202.8  318.56
#Mann=5,-1,0
  4401.0    0.16       0  4807.5    0.12       0  5004.6    0.07       0
  5010.6    0.12       0  5040.7    0.16       0
Bank Sta=5004.6,5010.6
Exp/Cntr=0.3,0.1

Type RM Length L Ch R = 1,4076,919,919,919
BEGIN DESCRIPTION:
IRON CREEK 7.0
END DESCRIPTION:
XS GIS Cut Line= 3
      3573981.15     10302703.99      3573715.54     10303052.92
      3573554.36     10303427.28
#Sta/Elev= 30
  4433.1  326.99  4537.9  319.97  4623.2  315.51  4666.8  311.63  4731.2  308.64
  4737.5  308.89  4744.3  306.87  4752.0  307.86  4758.3  306.36  4766.6  307.05
  4772.9  305.38  4781.1  306.61  4787.4  306.01  4801.9  307.56  4826.5  305.92
  4870.3  303.40  4979.1  299.91  4989.3  296.84  4997.9  293.10  5000.6  292.60
  5003.9  293.10  5018.3  296.19  5033.5  296.71  5065.4  299.81  5099.8  301.10
  5156.0  305.36  5170.4  306.39  5175.8  307.47  5246.4  312.23  5279.2  312.92
#Mann=5,-1,0
  4433.1    0.16       0  4826.5    0.12       0  4997.9    0.07       0
  5003.9    0.12       0  5156.0    0.16       0
Bank Sta=4997.9,5003.9
Exp/Cntr=0.3,0.1

Type RM Length L Ch R = 1,3157,472,472,472
BEGIN DESCRIPTION:
IRON CREEK 6.0
END DESCRIPTION:
XS GIS Cut Line= 3
      3573288.46     10302365.42      3573142.11     10302741.64
      3572966.06     10303358.42
#Sta/Elev= 30
  4606.7  312.51  4645.6  314.29  4663.6  313.27  4669.0  314.60  4693.5  315.18
  4707.8  313.61  4727.2  312.68  4763.6  311.58  4808.2  308.70  4849.4  307.07
  4978.2  297.04  4988.9  293.45  4995.4  288.23  4997.8  287.88  5000.6  287.38
  5003.8  287.88  5007.7  289.05  5013.0  289.05  5017.6  290.59  5027.3  292.27
  5037.8  292.21  5093.6  293.21  5173.0  298.06  5226.9  300.45  5284.8  302.42
  5318.6  304.40  5357.6  305.07  5391.5  307.19  5499.3  311.45  5651.8  315.43
#Mann=10,-1,0
  4606.7    0.16       0  4707.8    0.12       0  4727.2    0.16       0
  4808.2    0.12       0  4997.8    0.07       0  5003.8    0.12       0
  5017.6     0.1       0  5037.8    0.05       0  5226.9     0.1       0
  5499.3    0.05       0
Bank Sta=4997.8,5003.8
Exp/Cntr=0.3,0.1

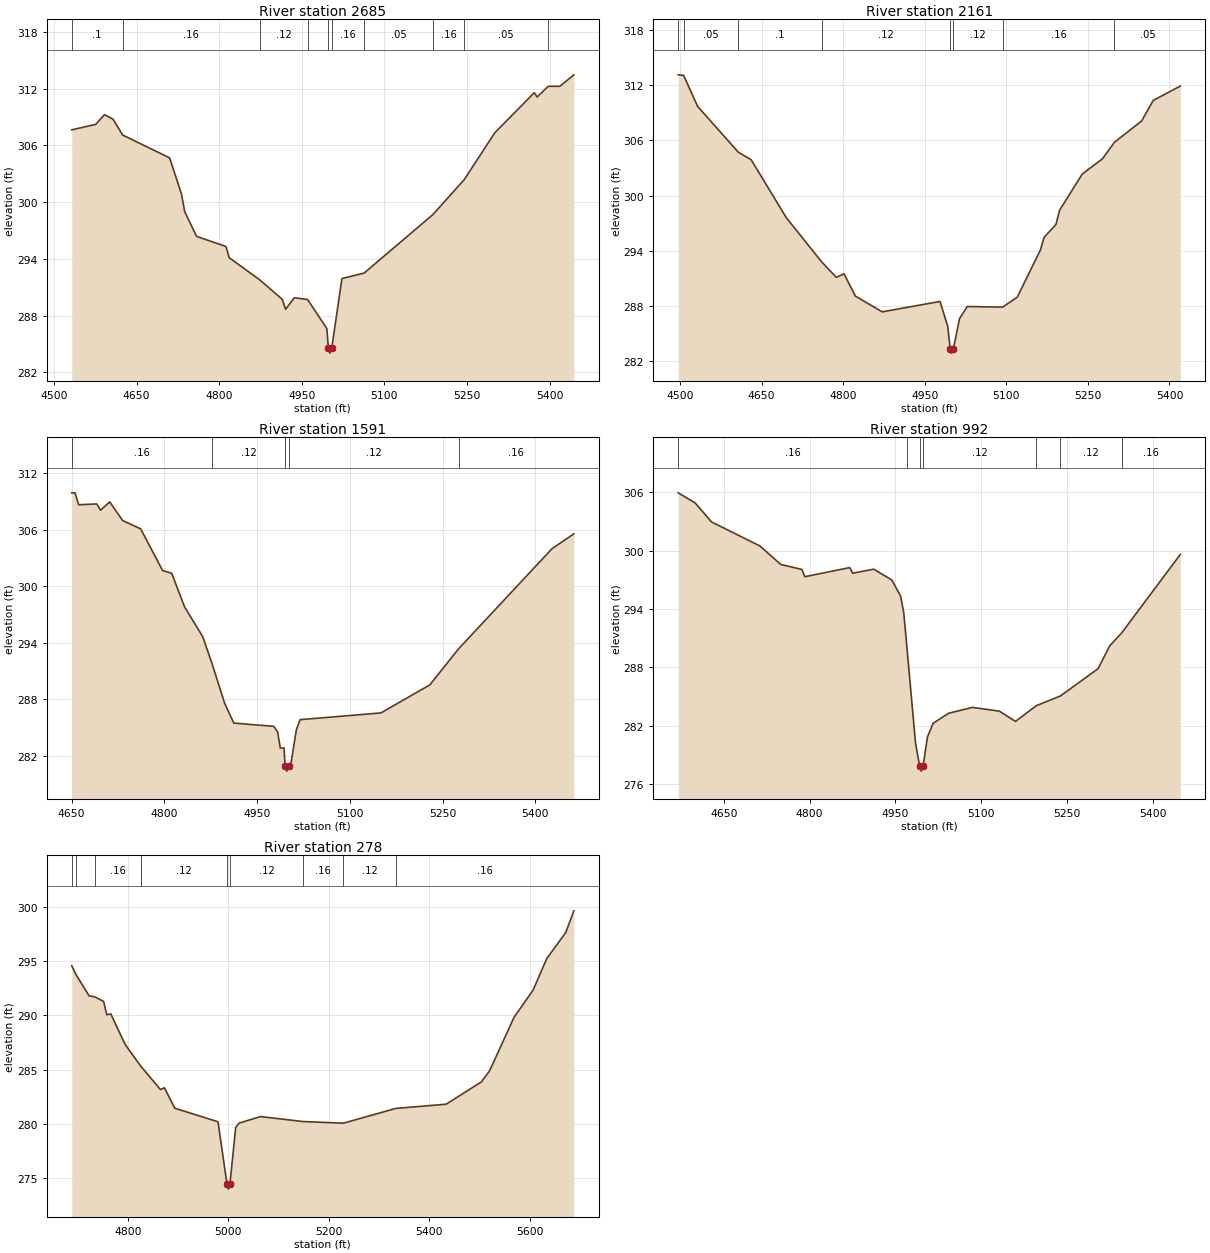
Type RM Length L Ch R = 1,2685,524,524,524
BEGIN DESCRIPTION:
IRON CREEK 5.0
END DESCRIPTION:
XS GIS Cut Line= 3
      3573007.23     10302266.43      3572760.86     10302701.02
      3572660.85     10303101.04
#Sta/Elev= 30
  4532.3  307.65  4575.8  308.23  4591.7  309.26  4607.3  308.78  4624.7  307.10
  4710.0  304.69  4731.6  300.86  4737.4  299.00  4759.0  296.38  4812.4  295.31
  4818.2  294.13  4874.2  291.76  4914.8  289.71  4920.6  288.67  4936.5  289.89
  4960.6  289.70  4995.6  286.63  4998.4  284.53  5001.1  284.03  5004.4  284.53
  5023.0  291.92  5063.3  292.50  5187.9  298.67  5245.1  302.38  5300.5  307.33
  5372.3  311.58  5377.5  311.13  5397.8  312.26  5418.7  312.26  5444.2  313.47
#Mann=10,-1,0
  4532.3     0.1       0  4624.7    0.16       0  4874.2    0.12       0
  4960.6    0.16       0  4998.4    0.07       0  5004.4    0.16       0
  5063.3    0.05       0  5187.9    0.16       0  5245.1    0.05       0
  5397.8    0.16       0
Bank Sta=4998.4,5004.4
Exp/Cntr=0.3,0.1

Type RM Length L Ch R = 1,2161,570,570,570
BEGIN DESCRIPTION:
IRON CREEK 4.0
END DESCRIPTION:
XS GIS Cut Line= 3
      3572842.12     10301941.62      3572348.36     10302497.89
      3572248.79     10302647.24
#Sta/Elev= 30
  4496.6  313.14  4506.5  313.08  4532.2  309.71  4607.0  304.73  4630.8  303.90
  4695.2  297.61  4760.3  292.80  4787.2  291.12  4801.5  291.49  4822.4  289.07
  4871.7  287.36  4978.0  288.49  4992.1  285.82  4996.7  283.37  4999.4  282.87
  5002.7  283.37  5013.9  286.62  5028.1  287.94  5093.1  287.87  5120.1  288.96
  5162.7  294.10  5169.4  295.47  5191.2  296.86  5197.9  298.41  5239.6  302.35
  5276.8  304.01  5298.7  305.80  5348.9  308.13  5370.0  310.35  5419.9  311.92
#Mann=8,-1,0
  4496.6    0.16       0  4506.5    0.05       0  4607.0     0.1       0
  4760.3    0.12       0  4996.7    0.07       0  5002.7    0.12       0
  5093.1    0.16       0  5298.7    0.05       0
Bank Sta=4996.7,5002.7
Exp/Cntr=0.3,0.1

Type RM Length L Ch R = 1,1591,599,599,599
BEGIN DESCRIPTION:
IRON CREEK 3.0
END DESCRIPTION:
XS GIS Cut Line= 3
      3572616.58     10301740.42      3572342.11     10301941.64
      3571942.13     10302191.62
#Sta/Elev= 30
  4650.4  309.94  4655.7  309.94  4661.5  308.67  4690.8  308.76  4697.0  308.09
  4711.7  308.98  4732.6  307.00  4761.9  306.10  4797.4  301.67  4812.0  301.39
  4832.9  297.80  4862.2  294.65  4877.0  291.83  4897.7  287.56  4912.4  285.46
  4977.2  285.11  4983.4  284.49  4987.6  282.81  4993.7  282.81  4995.4  280.85
  4998.1  280.35  5001.4  280.85  5004.3  280.91  5013.7  284.77  5019.6  285.82
  5150.5  286.54  5229.5  289.52  5275.9  293.35  5427.1  304.00  5462.4  305.58
#Mann=5,-1,0
  4650.4    0.16       0  4877.0    0.12       0  4995.4    0.07       0
  5001.4    0.12       0  5275.9    0.16       0
Bank Sta=4995.4,5001.4
Exp/Cntr=0.3,0.1

Type RM Length L Ch R = 1,992,714,714,714
BEGIN DESCRIPTION:
IRON CREEK 2.0
END DESCRIPTION:
XS GIS Cut Line= 3
      3572210.36     10301308.11      3572048.88     10301443.55
      3571892.12     10302091.60
#Sta/Elev= 30
  4570.4  305.94  4600.0  304.90  4628.6  302.95  4713.2  300.48  4749.6  298.58
  4786.5  298.07  4791.7  297.32  4870.2  298.26  4875.4  297.68  4912.1  298.10
  4943.8  296.98  4959.0  295.34  4964.4  293.70  4969.7  290.32  4985.0  280.30
  4992.3  277.85  4995.0  277.35  4998.3  277.85  5006.0  280.86  5015.8  282.26
  5042.7  283.29  5084.6  283.90  5131.6  283.51  5159.9  282.46  5196.1  284.07
  5238.3  285.07  5304.1  287.87  5324.5  290.22  5345.3  291.54  5447.9  299.61
#Mann=7,-1,0
  4570.4    0.16       0  4969.7    0.12       0  4992.3    0.07       0
  4998.3    0.12       0  5196.1    0.16       0  5238.3    0.12       0
  5345.3    0.16       0
Bank Sta=4992.3,4998.3
Exp/Cntr=0.3,0.1

Type RM Length L Ch R = 1,278,0,0,0
BEGIN DESCRIPTION:
IRON CREEK 1.0
END DESCRIPTION:
XS GIS Cut Line= 3
      3571897.86     10301188.31      3571554.09     10301599.80
      3571692.11     10302041.65
#Sta/Elev= 30
  4688.7  294.58  4697.5  293.74  4723.3  291.81  4734.5  291.72  4752.0  291.30
  4758.5  290.06  4766.3  290.15  4794.9  287.33  4825.8  285.34  4865.2  283.17
  4873.0  283.34  4893.8  281.45  4979.7  280.20  4997.5  274.49  5000.3  273.99
  5003.5  274.49  5014.9  279.67  5021.4  280.07  5064.3  280.68  5149.2  280.22
  5229.3  280.07  5333.4  281.43  5433.7  281.82  5503.9  283.88  5520.2  284.90
  5568.9  289.84  5606.6  292.33  5633.8  295.24  5671.6  297.64  5687.8  299.65
#Mann=9,-1,0
  4688.7    0.16       0  4697.5    0.12       0  4734.5    0.16       0
  4825.8    0.12       0  4997.5    0.07       0  5003.5    0.12       0
  5149.2    0.16       0  5229.3    0.12       0  5333.4    0.16       0
Bank Sta=4997.5,5003.5
Exp/Cntr=0.3,0.1

Chan Stop Cuts=-1