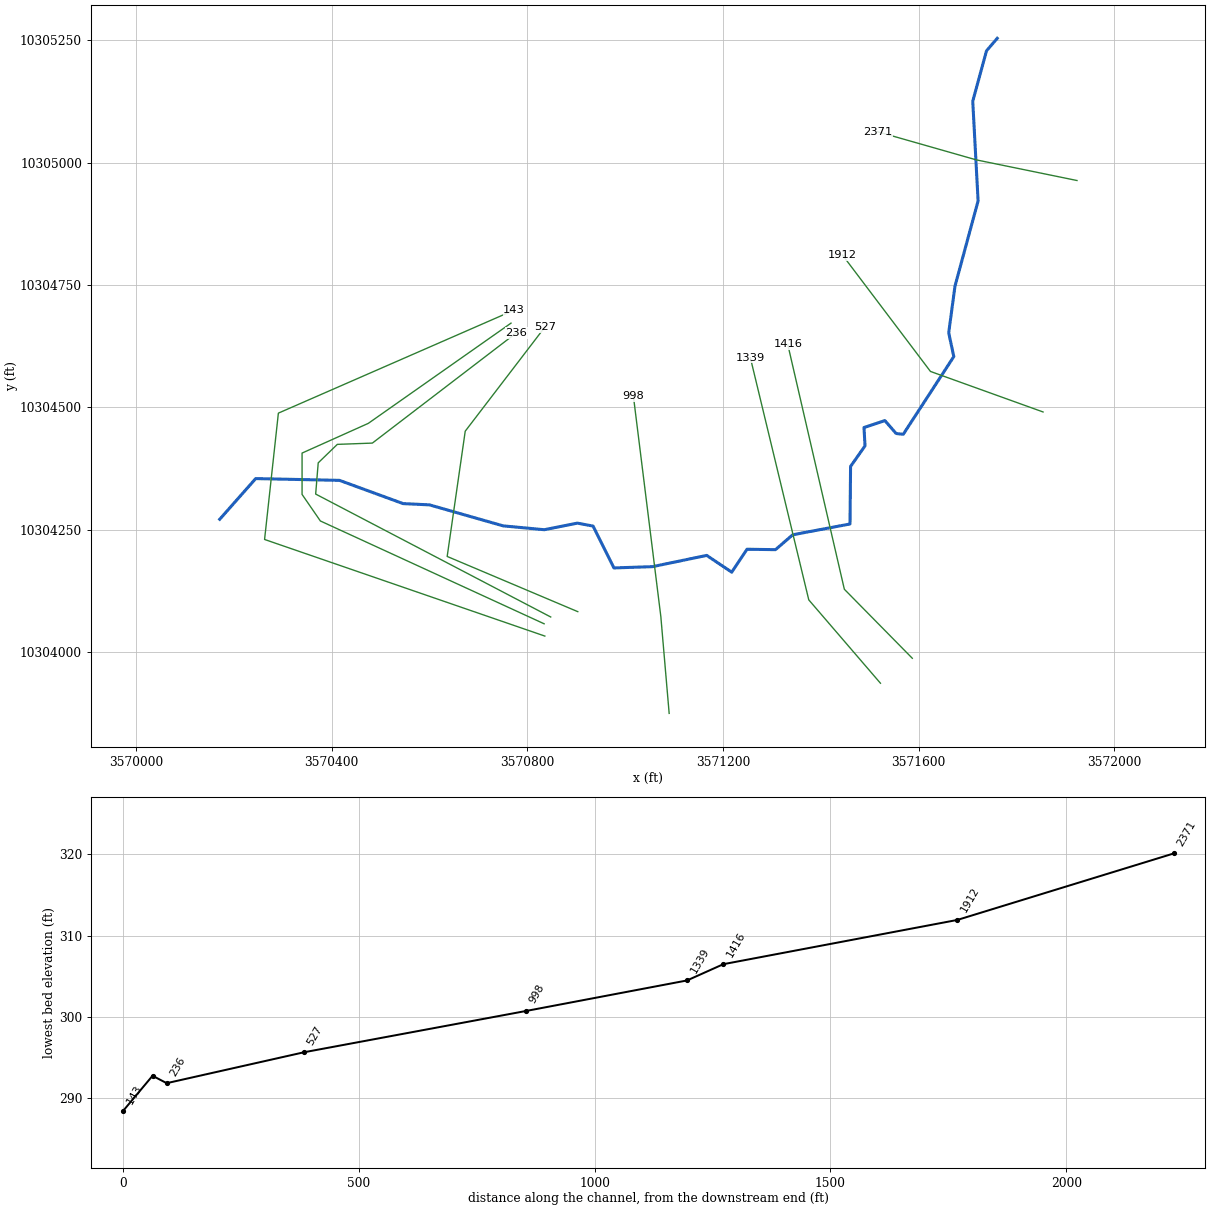
--- JACK CREEK TRIBUTARY 2.prj (project) ---

Proj Title=JACK CREEK TRIBUTARY 2 Base Level Engineering
Current Plan=p01
Default Exp/Contr=0.3,0.1
English Units
Geom File=g01
Flow File=f01
Plan File=p01
Y Axis Title=Elevation
X Axis Title(PF)=Main Channel Distance
X Axis Title(XS)=Station
BEGIN DESCRIPTION:
JACK CREEK TRIBUTARY 2
END DESCRIPTION:
DSS Export Rating Curves= 0
DSS Export Rating Curve Sorted= 0
DSS Export Volume Flow Curves= 0
DXF OffsetX= 0
DXF OffsetY= 0
DXF ScaleX= 1
DXF ScaleY= 10

--- JACK CREEK TRIBUTARY 2.p01 (plan) ---

Plan Title=Multiple Run
Short Identifier=Multiple
Geom File=g01
Flow File=f01
Subcritical Flow
K Sum by GR= 0
Std Step Tol= 0.01
Critical Tol= 0.01
Num of Std Step Trials= 20
Max Error Tol= 0.3
Flow Tol Ratio= 0.001
Split Flow NTrial= 30
Split Flow Tol= 0.02
Split Flow Ratio= 0.02
Log Output Level= 0
Friction Slope Method= 1
Unsteady Friction Slope Method= 2
Unsteady Bridges Friction Slope Method= 1
Parabolic Critical Depth
Global Vel Dist=  1 , 1 , 1
Global Log Level= 0
CheckData=True
Encroach Param= -1, 0, 0, 0
BEGIN DESCRIPTION:
Multiple Run
END DESCRIPTION:

--- JACK CREEK TRIBUTARY 2.f01 (steady flow) ---

Flow Title=Multiple
Number of Profiles=7
Profile Names=10-year,25-year,50-year,1pct_min,100-year,1pct_plu,500-year
River Rch & RM= JACK CREEK TRIBU,Reach-1,2371
      94     112     125     103     139     188     172
Boundary for River Rch & Prof#=JACK CREEK TRIBU,Reach-1,1
Up Type=0
Dn Type=3
Dn Slope=0.005
Boundary for River Rch & Prof#=JACK CREEK TRIBU,Reach-1,2
Up Type=0
Dn Type=3
Dn Slope=0.005
Boundary for River Rch & Prof#=JACK CREEK TRIBU,Reach-1,3
Up Type=0
Dn Type=3
Dn Slope=0.005
Boundary for River Rch & Prof#=JACK CREEK TRIBU,Reach-1,4
Up Type=0
Dn Type=3
Dn Slope=0.005
Boundary for River Rch & Prof#=JACK CREEK TRIBU,Reach-1,5
Up Type=0
Dn Type=3
Dn Slope=0.005
Boundary for River Rch & Prof#=JACK CREEK TRIBU,Reach-1,6
Up Type=0
Dn Type=3
Dn Slope=0.005
Boundary for River Rch & Prof#=JACK CREEK TRIBU,Reach-1,7
Up Type=0
Dn Type=3
Dn Slope=0.005

--- JACK CREEK TRIBUTARY 2.g01 (geometry) ---

Geom Title=Existing Conditions
Program Version=4.10

River Reach=JACK CREEK TRIBU,Reach-1
Reach XY= 30
      3571760.59      10305254.3      3571738.71     10305228.78
      3571710.59     10305125.65      3571721.52       10304922.
       3571674.3     10304747.87      3571661.45     10304652.39
      3571671.87     10304603.78      3571568.49     10304444.83
       3571553.9     10304446.57      3571530.99     10304472.96
      3571488.28     10304458.72      3571490.36     10304421.22
      3571460.85     10304379.21      3571459.72     10304261.59
      3571342.53     10304239.45      3571307.37     10304209.07
      3571249.21     10304209.94      3571217.96     10304163.06
      3571166.75     10304197.35      3571056.07     10304174.35
      3570977.08     10304171.74      3570934.54     10304257.25
      3570902.43     10304263.32      3570834.72     10304249.87
      3570750.95     10304257.68      3570599.91     10304300.65
      3570546.09     10304303.25      3570416.19     10304350.74
      3570244.83     10304354.38      3570171.28     10304271.18

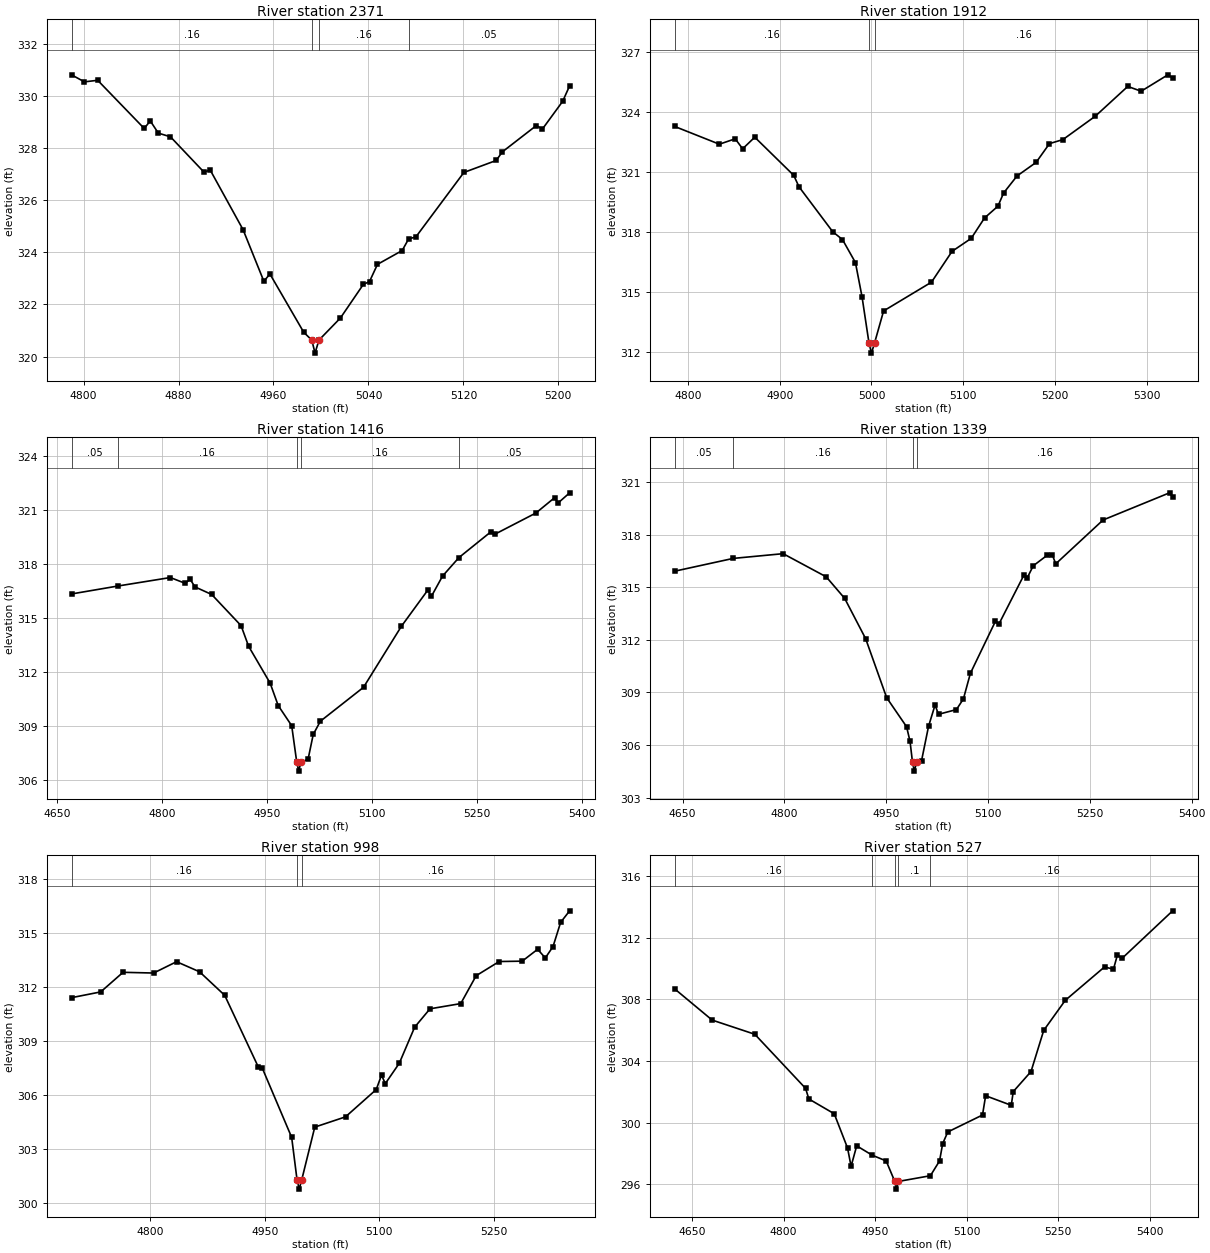
Type RM Length L Ch R = 1 ,2371    ,459,459,459
BEGIN DESCRIPTION:
JACK CREEK TRIBUTARY 2 5.0
END DESCRIPTION:
XS GIS Cut Line= 3
       3571923.7     10304963.66      3571717.88     10305005.86
       3571516.4     10305063.29
#Sta/Elev= 30
  4789.9  330.82  4800.7  330.55  4811.9  330.61  4851.1  328.76  4856.2  329.05
    4863  328.58  4873.2  328.44  4901.5  327.08  4906.6  327.17  4934.4  324.87
  4951.9  322.89    4957  323.17  4985.5  320.93  4992.3  320.63    4995  320.13
  4998.3  320.63  5016.4  321.48  5035.7  322.77  5040.9  322.88  5047.6  323.54
  5068.4  324.07  5073.9  324.52  5079.9  324.59  5120.4  327.07  5147.6  327.53
  5152.8  327.86  5181.4  328.87  5186.6  328.74  5203.6   329.8  5209.5   330.4
#Mann= 4 ,-1 , 0
  4789.9     .16       0  4992.3     .07       0  4998.3     .16       0
  5073.9     .05       0
Bank Sta=4992.3,4998.3
XS Rating Curve= 0 ,0
Exp/Cntr=0.3,0.1

Type RM Length L Ch R = 1 ,1912    ,496,496,496
BEGIN DESCRIPTION:
JACK CREEK TRIBUTARY 2 4.0
END DESCRIPTION:
XS GIS Cut Line= 3
       3571854.3     10304490.56      3571624.13     10304573.39
      3571444.35     10304811.28
#Sta/Elev= 30
  4785.4  323.29  4834.2   322.4  4851.5  322.67  4859.6  322.17  4872.8  322.75
  4915.3  320.84    4921  320.27  4957.8  318.02  4968.4  317.63  4982.5  316.48
  4989.7  314.77  4997.3  312.45    5000  311.95  5003.3  312.45  5013.2  314.06
  5065.4   315.5  5087.8  317.04  5108.7  317.69  5123.2  318.71  5137.8   319.3
    5144  319.96  5158.6  320.81  5179.4  321.49    5194  322.43  5208.6  322.63
  5243.9   323.8  5279.3  325.29  5293.9  325.05    5323  325.87  5328.2  325.72
#Mann= 3 ,-1 , 0
  4785.4     .16       0  4997.3     .07       0  5003.3     .16       0
Bank Sta=4997.3,5003.3
XS Rating Curve= 0 ,0
Exp/Cntr=0.3,0.1

Type RM Length L Ch R = 1 ,1416    ,77,77,77
BEGIN DESCRIPTION:
JACK CREEK TRIBUTARY 2 3.0
END DESCRIPTION:
XS GIS Cut Line= 3
      3571587.04     10303987.06      3571448.12     10304128.15
      3571332.47     10304628.56
#Sta/Elev= 30
  4671.2  316.34  4737.4  316.78  4812.3  317.25  4833.5  316.93  4840.6  317.15
  4847.6  316.73  4871.4  316.31  4913.4  314.58  4924.1  313.44  4954.9  311.39
  4966.4  310.15  4985.7  309.03  4992.9  307.01  4995.7  306.51  4998.9  307.01
  5009.1  307.17  5016.5  308.55  5026.7  309.28  5088.3  311.16  5142.5  314.55
  5180.1  316.55  5185.2   316.2  5201.2  317.33  5224.7  318.36  5270.7   319.8
  5275.8  319.65  5334.6  320.83  5361.3  321.68  5366.4  321.39  5382.8  321.95
#Mann= 5 ,-1 , 0
  4671.2     .05       0  4737.4     .16       0  4992.9     .07       0
  4998.9     .16       0  5224.7     .05       0
Bank Sta=4992.9,4998.9
XS Rating Curve= 0 ,0
Exp/Cntr=0.3,0.1

Type RM Length L Ch R = 1 ,1339    ,341,341,341
BEGIN DESCRIPTION:
Mapping XS 2fdf6f4f
END DESCRIPTION:
XS GIS Cut Line= 3
      3571521.93     10303936.06      3571375.42     10304106.45
      3571256.06     10304601.24
#Sta/Elev= 30
  4638.3  315.91  4724.6  316.64  4798.2  316.91  4861.7  315.59  4888.9  314.36
  4919.8  312.06  4950.7   308.7  4980.1  307.04  4985.2   306.2  4988.8  305.01
  4991.5  304.51  4994.8  305.01  5002.1   305.1  5012.4  307.06    5022  308.28
  5027.1  307.75  5053.5  308.02  5063.8  308.63  5074.1  310.09  5110.9  313.05
    5116  312.89  5152.8  315.68  5157.9  315.54  5166.7  316.22  5187.2  316.82
  5194.7  316.85  5199.8  316.33  5269.5  318.83  5367.4  320.38    5372  320.15
#Mann= 4 ,-1 , 0
  4638.3     .05       0  4724.6     .16       0  4988.8     .07       0
  4994.8     .16       0
Bank Sta=4988.8,4994.8
XS Rating Curve= 0 ,0
Exp/Cntr=0.3,0.1

Type RM Length L Ch R = 1 ,998     ,471,471,471
BEGIN DESCRIPTION:
JACK CREEK TRIBUTARY 2 2.0
END DESCRIPTION:
XS GIS Cut Line= 3
      3571090.02     10303874.43        3571073.     10304072.35
      3571016.86     10304523.32
#Sta/Elev= 30
  4696.6  311.41  4734.8  311.73  4764.1  312.82  4804.2  312.78  4834.3  313.41
  4864.4  312.85  4897.4  311.54  4941.4  307.56  4946.5  307.51  4985.2  303.64
  4992.3  301.26  4995.1  300.76  4998.3  301.26  5015.5  304.21  5055.8  304.78
  5096.1   306.3    5103   307.1    5108  306.63  5126.3  307.76  5146.5  309.77
  5166.6  310.79  5206.9  311.08  5227.1  312.63  5257.3  313.42  5287.5  313.44
  5307.7   314.1  5317.8  313.62  5327.9  314.25  5337.9   315.6  5349.7  316.24
#Mann= 3 ,-1 , 0
  4696.6     .16       0  4992.3     .07       0  4998.3     .16       0
Bank Sta=4992.3,4998.3
XS Rating Curve= 0 ,0
Exp/Cntr=0.3,0.1

Type RM Length L Ch R = 1 ,527     ,291,291,291
BEGIN DESCRIPTION:
Mapping XS 82ca0bd3
END DESCRIPTION:
XS GIS Cut Line= 4
      3570903.19     10304082.36      3570636.27     10304195.21
      3570673.16     10304451.29      3570835.91     10304663.94
#Sta/Elev= 30
  4621.4  308.68    4683  306.65  4752.9  305.73  4836.1  302.22  4841.5  301.53
  4883.1  300.57  4904.9  298.35  4910.7  297.16  4919.9  298.49  4945.4  297.88
  4968.2  297.51  4982.3  296.18    4985  295.68  4988.3  296.18  5040.7  296.55
  5055.7  297.51  5060.8  298.63  5069.2  299.39  5126.1  300.49  5131.2  301.74
  5173.2  301.12  5176.5  302.01  5205.6  303.31  5226.4  305.98  5261.7  307.93
  5326.1   310.1  5340.7  309.95    5347  310.85  5355.2  310.67  5437.7  313.74
#Mann= 5 ,-1 , 0
  4621.4     .16       0  4945.4      .1       0  4982.3     .07       0
  4988.3      .1       0  5040.7     .16       0
Bank Sta=4982.3,4988.3
XS Rating Curve= 0 ,0
Exp/Cntr=0.3,0.1

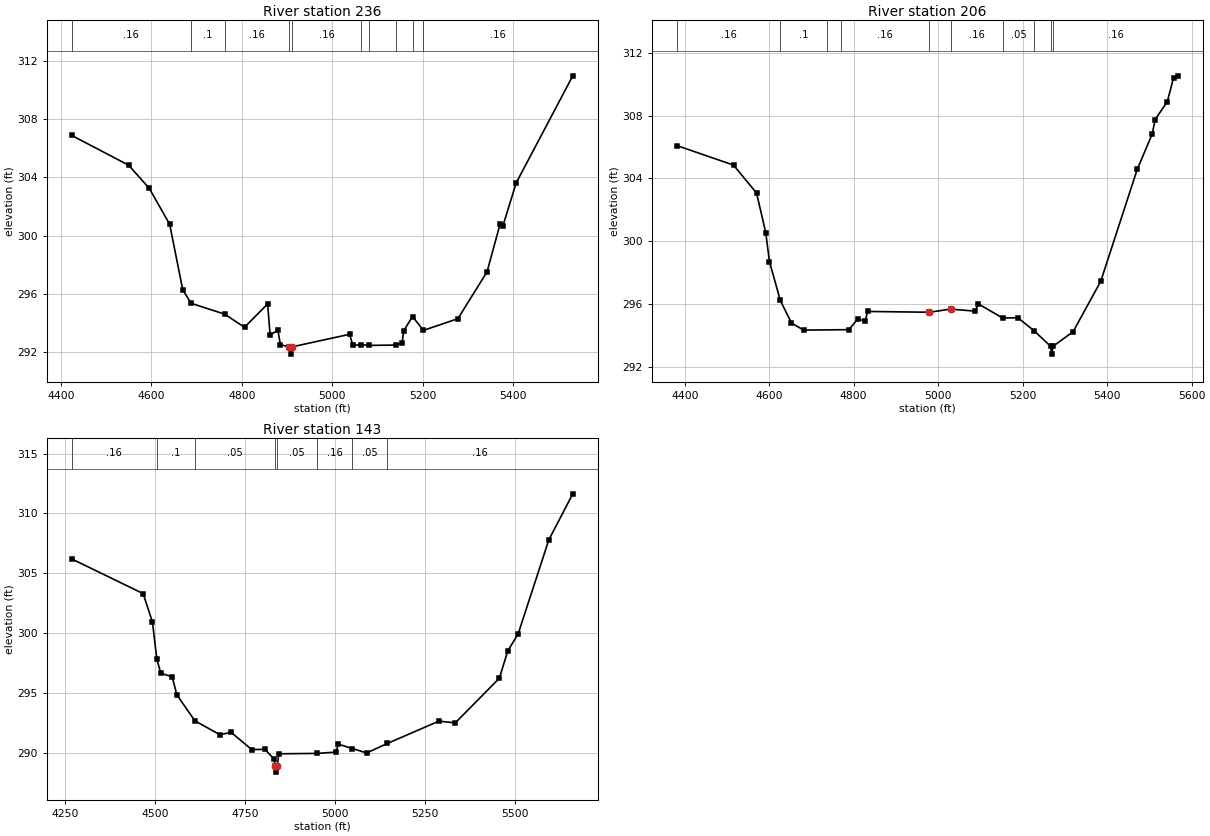
Type RM Length L Ch R = 1 ,236     ,30,30,30
BEGIN DESCRIPTION:
Mapping XS f483eefc
END DESCRIPTION:
XS GIS Cut Line= 6
      3570847.88     10304071.46      3570367.43     10304322.75
      3570372.64     10304386.55       3570411.7     10304424.31
      3570483.32     10304426.92      3570777.33     10304651.98
#Sta/Elev= 30
  4424.1  306.88  4549.9  304.84  4595.5  303.25  4640.6  300.78  4669.3  296.31
  4687.6  295.37  4762.2  294.62  4805.9  293.72  4856.9  295.32  4862.5  293.19
  4879.7  293.52  4885.2  292.52    4905  292.38  4907.7  291.88    4911  292.38
  5038.1  293.24  5045.3  292.48  5063.5  292.53  5081.7  292.48  5141.1   292.5
    5154  292.65  5157.8  293.49  5177.1  294.46  5201.3  293.51  5277.3  294.31
  5341.7  297.52  5370.8  300.83  5377.1   300.7  5406.1  303.62  5531.2  310.97
#Mann= 10 ,-1 , 0
  4424.1     .16       0  4687.6      .1       0  4762.2     .16       0
    4905     .03       0    4911     .16       0  5063.5     .16       0
  5081.7     .05       0  5141.1     .16       0  5177.1     .05       0
  5201.3     .16       0
Bank Sta=4905,4911
XS Rating Curve= 0 ,0
Exp/Cntr=0.3,0.1

Type RM Length L Ch R = 1 ,206     ,63,63,63
BEGIN DESCRIPTION:
Mapping XS 8771f1dc
END DESCRIPTION:
XS GIS Cut Line= 6
      3570834.46     10304057.55     3570377.059    10304267.717
      3570339.65    10304322.011      3570339.65    10304406.519
     3570475.069     10304467.28      3570766.74     10304672.15
#Sta/Elev= 30
  4381.9  306.08  4515.5  304.84  4570.1  303.06  4591.9  300.52  4600.6  298.69
  4626.2  296.22  4652.7  294.77  4681.6  294.32  4788.5  294.35  4810.3  295.05
  4827.2  294.87  4832.7  295.51  4979.3  295.46  5029.3  295.66    5088  295.53
  5095.1  295.99  5152.7  295.09  5188.6  295.11  5227.5  294.27    5266  293.29
  5268.8  292.79    5272  293.29  5319.4  294.22  5384.8  297.43  5471.1  304.56
  5506.8  306.83  5513.5  307.74  5542.5  308.89  5557.3  310.42    5568  310.53
#Mann= 10 ,-1 , 0
  4381.9     .16       0  4626.2      .1       0  4735.9     .05       0
  4769.9     .16       0  4979.3     .05       0  5029.3     .16       0
  5152.7     .05       0  5227.5     .16       0    5266     .03       0
    5272     .16       0
Bank Sta=4979.3,5029.3
XS Rating Curve= 0 ,0
Exp/Cntr=0.3,0.1

Type RM Length L Ch R = 1 ,143     ,0,0,0
BEGIN DESCRIPTION:
JACK CREEK TRIBUTARY 2 1.0
END DESCRIPTION:
XS GIS Cut Line= 4
      3570835.91     10304032.45        3570263.     10304229.93
      3570291.22     10304488.18      3570772.97     10304698.67
#Sta/Elev= 30
  4269.5  306.21  4467.8  303.32  4493.8  300.94  4505.7  297.88  4516.8  296.68
  4548.5  296.38  4561.5  294.87  4611.6  292.71    4681  291.55  4712.2  291.75
  4769.4  290.31  4805.9  290.33  4831.8  289.51  4834.1  288.93  4836.8  288.43
  4840.1  288.93  4844.7  289.96  4949.4  289.99  5004.1   290.1  5009.2  290.77
  5048.6   290.4  5088.5  290.03  5146.1  290.82    5289  292.68  5334.7  292.54
  5457.1  296.26  5480.5  298.54  5509.4  299.97  5594.6  307.81    5661  311.64
#Mann= 8 ,-1 , 0
  4269.5     .16       0  4505.7      .1       0  4611.6     .05       0
  4834.1     .07       0  4840.1     .05       0  4949.4     .16       0
  5048.6     .05       0  5146.1     .16       0
Bank Sta=4834.1,4840.1
XS Rating Curve= 0 ,0
Exp/Cntr=0.3,0.1

Chan Stop Cuts=-1
Use User Specified Reach Order=0
Composite Channel Slope=5