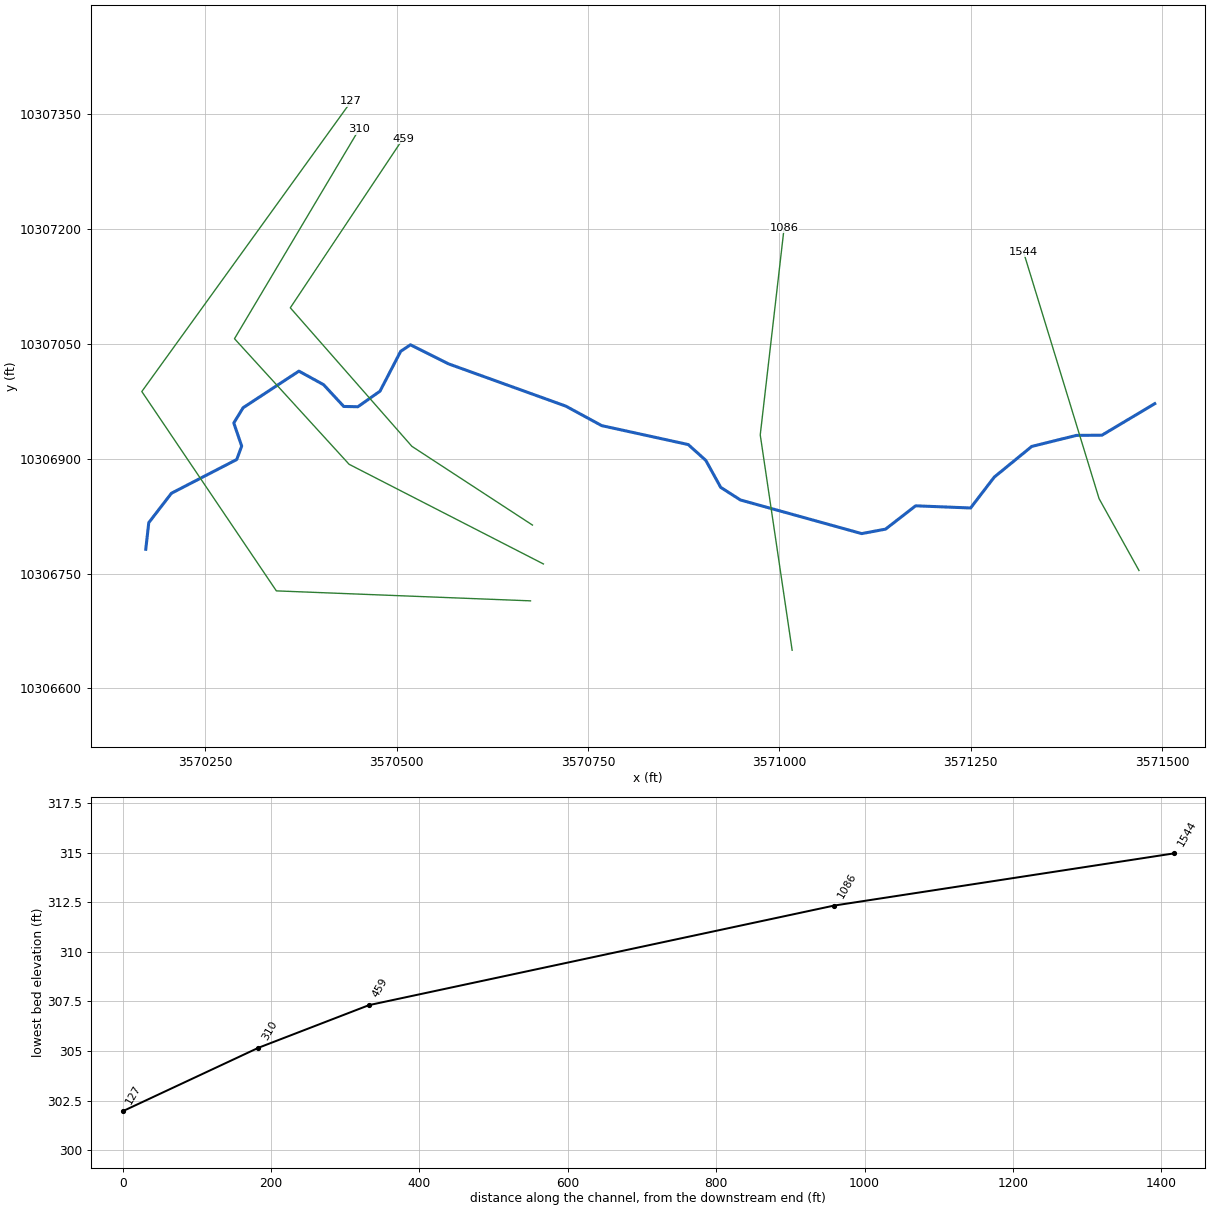
--- JACK CREEK TRIBUTARY 3.prj (project) ---

Proj Title=JACK CREEK TRIBUTARY 3 Base Level Engineering
Current Plan=p01
Default Exp/Contr=0.3,0.1
English Units
Geom File=g01
Flow File=f01
Plan File=p01
Y Axis Title=Elevation
X Axis Title(PF)=Main Channel Distance
X Axis Title(XS)=Station
BEGIN DESCRIPTION:
JACK CREEK TRIBUTARY 3
END DESCRIPTION:
DSS Export Rating Curves= 0
DSS Export Rating Curve Sorted= 0
DSS Export Volume Flow Curves= 0
DXF OffsetX= 0
DXF OffsetY= 0
DXF ScaleX= 1
DXF ScaleY= 10

--- JACK CREEK TRIBUTARY 3.p01 (plan) ---

Plan Title=Multiple Run
Short Identifier=Multiple
Geom File=g01
Flow File=f01
Subcritical Flow
K Sum by GR= 0
Std Step Tol= 0.01
Critical Tol= 0.01
Num of Std Step Trials= 20
Max Error Tol= 0.3
Flow Tol Ratio= 0.001
Split Flow NTrial= 30
Split Flow Tol= 0.02
Split Flow Ratio= 0.02
Log Output Level= 0
Friction Slope Method= 1
Unsteady Friction Slope Method= 2
Unsteady Bridges Friction Slope Method= 1
Parabolic Critical Depth
Global Vel Dist=  1 , 1 , 1
Global Log Level= 0
CheckData=True
Encroach Param= -1, 0, 0, 0
BEGIN DESCRIPTION:
Multiple Run
END DESCRIPTION:

--- JACK CREEK TRIBUTARY 3.f01 (steady flow) ---

Flow Title=Multiple
Number of Profiles=7
Profile Names=10-year,25-year,50-year,1pct_min,100-year,1pct_plu,500-year
River Rch & RM= JACK CREEK TRIBU,Reach-1,1544
     167     208     239     203     275     372     361
Boundary for River Rch & Prof#=JACK CREEK TRIBU,Reach-1,1
Up Type=0
Dn Type=3
Dn Slope=0.005
Boundary for River Rch & Prof#=JACK CREEK TRIBU,Reach-1,2
Up Type=0
Dn Type=3
Dn Slope=0.005
Boundary for River Rch & Prof#=JACK CREEK TRIBU,Reach-1,3
Up Type=0
Dn Type=3
Dn Slope=0.005
Boundary for River Rch & Prof#=JACK CREEK TRIBU,Reach-1,4
Up Type=0
Dn Type=3
Dn Slope=0.005
Boundary for River Rch & Prof#=JACK CREEK TRIBU,Reach-1,5
Up Type=0
Dn Type=3
Dn Slope=0.005
Boundary for River Rch & Prof#=JACK CREEK TRIBU,Reach-1,6
Up Type=0
Dn Type=3
Dn Slope=0.005
Boundary for River Rch & Prof#=JACK CREEK TRIBU,Reach-1,7
Up Type=0
Dn Type=3
Dn Slope=0.005

--- JACK CREEK TRIBUTARY 3.g01 (geometry) ---

Geom Title=Existing Conditions
Program Version=4.10

River Reach=JACK CREEK TRIBU,Reach-1
Reach XY= 30
       3571490.4     10306971.89      3571421.36     10306930.69
       3571388.1     10306930.46       3571329.7     10306916.03
      3571280.68     10306875.94      3571249.78     10306835.62
      3571177.96     10306838.45      3571138.68       10306808.
      3571107.51     10306802.15      3570949.07     10306846.08
      3570923.28     10306862.57      3570903.88     10306897.73
      3570880.85     10306918.47      3570767.86     10306943.19
       3570720.9     10306968.69      3570567.71     10307023.89
      3570517.96     10307048.78      3570505.17     10307040.26
      3570478.16     10306988.19      3570449.25     10306967.87
      3570430.81     10306968.24      3570404.44     10306996.68
      3570372.23     10307014.39      3570299.34     10306966.57
      3570287.12     10306946.64      3570297.46     10306916.48
      3570290.97     10306898.92      3570205.67     10306854.85
      3570176.07     10306816.46      3570172.11     10306781.64

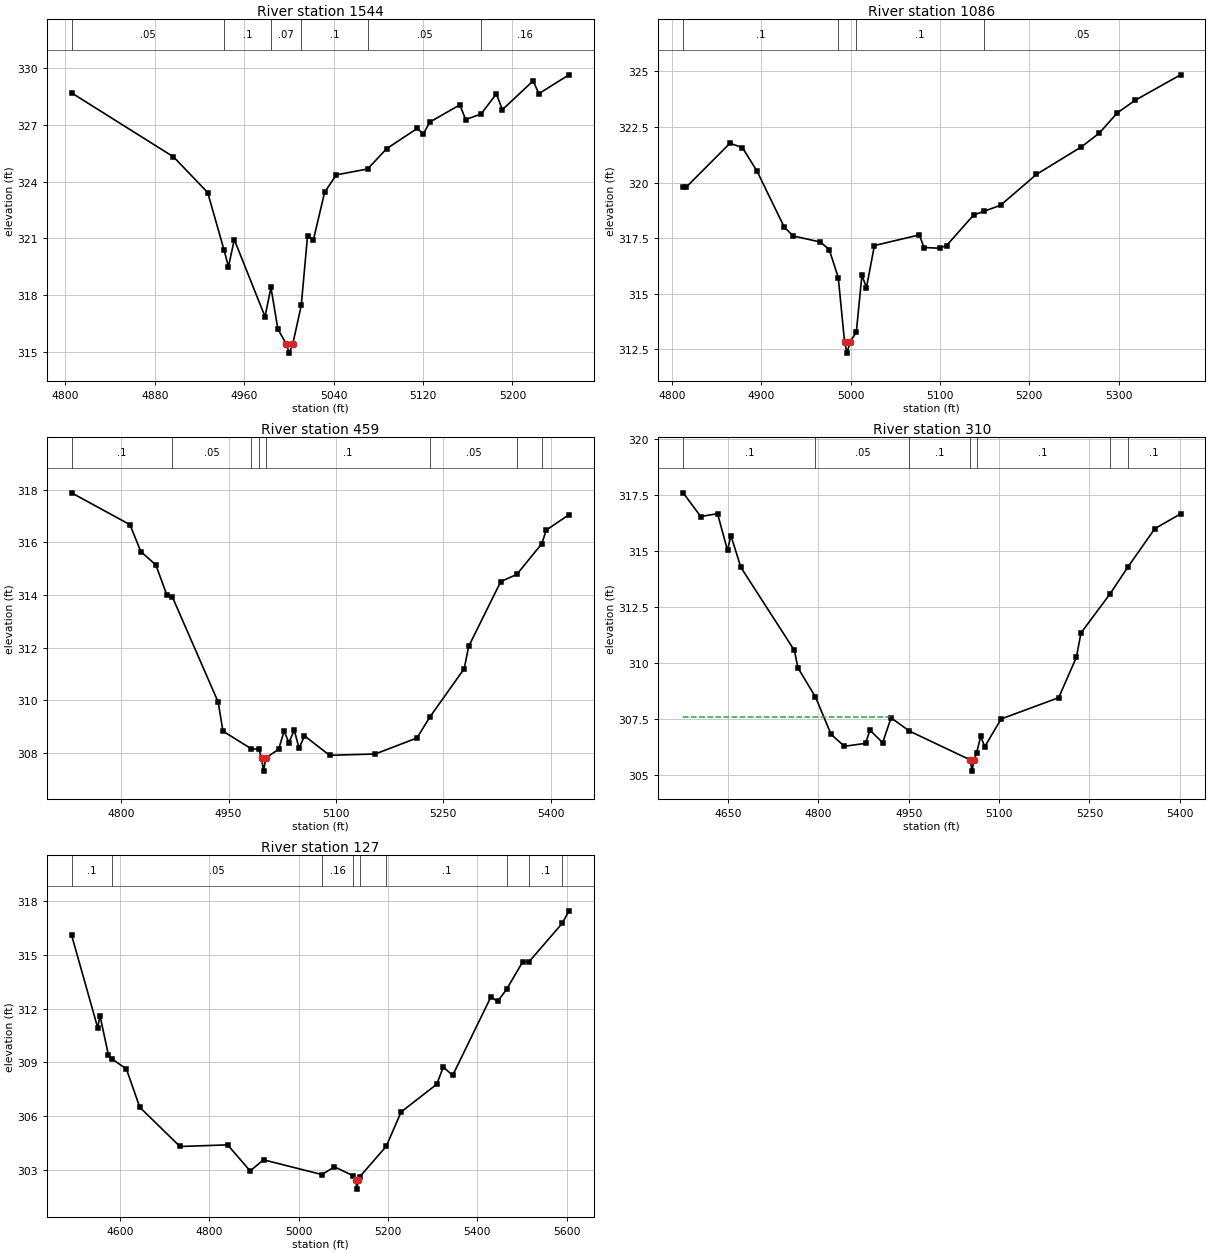
Type RM Length L Ch R = 1 ,1544    ,458,458,458
BEGIN DESCRIPTION:
JACK CREEK TRIBUTARY 3 7.0
END DESCRIPTION:
XS GIS Cut Line= 3
      3571469.76     10306753.98      3571417.66     10306847.77
       3571318.7     10307170.66
#Sta/Elev= 30
  4805.6  328.67  4896.8   325.3  4927.4  323.42    4942   320.4    4946  319.51
  4951.2  320.94  4978.7  316.88    4984  318.42  4990.2  316.22  4997.6  315.46
  5000.4  314.96  5003.6  315.46  5011.1  317.47  5016.7  321.11    5022  320.93
    5032  323.43  5042.4  324.35  5070.5  324.66  5087.5  325.73    5115   326.8
  5120.2  326.49  5126.1  327.13    5153  328.04  5158.2  327.26    5172  327.56
  5185.7  328.62    5191  327.78  5218.5   329.3  5223.7  328.63  5250.6  329.62
#Mann= 6 ,-1 , 0
  4805.6     .05       0    4942      .1       0    4984     .07       0
  5011.1      .1       0  5070.5     .05       0    5172     .16       0
Bank Sta=4997.6,5003.6
XS Rating Curve= 0 ,0
Exp/Cntr=0.3,0.1

Type RM Length L Ch R = 1 ,1086    ,627,627,627
BEGIN DESCRIPTION:
JACK CREEK TRIBUTARY 3 2.0
END DESCRIPTION:
XS GIS Cut Line= 3
      3571016.62      10306649.8      3570974.95      10306931.1
       3571006.2     10307201.94
#Sta/Elev= 30
  4812.4   319.8  4815.9   319.8  4864.8  321.77  4878.7  321.58  4895.1  320.52
  4925.5  318.01  4935.6   317.6  4965.9  317.33    4976  316.99  4986.1  315.73
  4993.2  312.83    4996  312.33  4999.2  312.83  5006.3  313.27  5012.6  315.83
  5017.7  315.28  5026.6  317.17    5077  317.65  5082.1  317.08  5099.6  317.05
  5107.4  317.17  5137.6  318.54  5149.1  318.71  5167.8  318.98    5208  320.37
  5258.4  321.61  5278.5  322.23  5298.6  323.14  5318.8  323.71  5369.4  324.85
#Mann= 4 ,-1 , 0
  4812.4      .1       0  4986.1     .07       0  5006.3      .1       0
  5149.1     .05       0
Bank Sta=4993.2,4999.2
XS Rating Curve= 0 ,0
Exp/Cntr=0.3,0.1

Type RM Length L Ch R = 1 ,459     ,149,149,149
BEGIN DESCRIPTION:
Mapping XS 6bfb347d
END DESCRIPTION:
XS GIS Cut Line= 4
      3570677.35     10306813.29      3570519.83     10306916.13
      3570360.98     10307097.12      3570508.35     10307318.17
#Sta/Elev= 30
  4730.8  317.88  4812.4  316.67  4827.5  315.65  4848.6  315.14  4863.7  314.01
  4871.7  313.92  4935.6  309.93  4942.2  308.83  4981.7  308.16  4992.5  308.14
  4996.1  307.81  4998.9  307.31  5002.1  307.81    5020  308.14  5027.6  308.83
  5034.3  308.39  5041.8  308.87  5048.5  308.18  5056.1  308.65  5091.2  307.91
  5154.8  307.96  5213.2  308.57  5231.3  309.37  5279.1   311.2  5285.4  312.05
  5330.2  314.51  5352.5  314.78  5387.6  315.95  5393.5  316.46  5425.4  317.05
#Mann= 8 ,-1 , 0
  4730.8      .1       0  4871.7     .05       0  4981.7      .1       0
  4992.5     .07       0  5002.1      .1       0  5231.3     .05       0
  5352.5      .1       0  5387.6     .05       0
Bank Sta=4996.1,5002.1
XS Rating Curve= 0 ,0
Exp/Cntr=0.3,0.1

Type RM Length L Ch R = 1 ,310     ,183,183,183
BEGIN DESCRIPTION:
Mapping XS 8841b4c4
END DESCRIPTION:
XS GIS Cut Line= 4
      3570691.67      10306762.5       3570437.8     10306892.69
      3570288.06     10307056.75       3570450.8     10307330.16
#Sta/Elev= 30
  4575.6  317.59  4604.9  316.53  4632.7  316.66  4649.3  315.02  4654.9  315.68
  4671.5  314.26  4760.3  310.55  4766.2  309.77  4795.3  308.47  4821.2   306.8
  4843.4  306.27  4878.3   306.4  4885.7  306.99  4906.7  306.43  4920.8  307.54
  4951.1  306.95  5052.3  305.66    5055  305.16  5058.3  305.66  5062.6  305.97
  5069.5  306.71  5076.2  306.25  5103.4  307.49  5198.9  308.44  5228.4  310.25
  5235.9  311.33    5284  313.07  5313.9  314.28  5358.5  315.99  5401.2  316.65
#Mann= 7 ,-1 , 0
  4575.6      .1       0  4795.3     .05       0  4951.1      .1       0
  5052.3     .07       0  5062.6      .1       0    5284     .05       0
  5313.9      .1       0
#XS Ineff= 2 , 0
         4920.64  307.58
Permanent Ineff=
       F       F
Bank Sta=5052.3,5058.3
XS Rating Curve= 0 ,0
Exp/Cntr=0.3,0.1

Type RM Length L Ch R = 1 ,127     ,0,0,0
BEGIN DESCRIPTION:
JACK CREEK TRIBUTARY 3 1.0
END DESCRIPTION:
XS GIS Cut Line= 4
      3570674.77     10306714.31      3570342.75     10306727.33
      3570166.97     10306987.74      3570440.39     10307366.63
#Sta/Elev= 30
  4491.5  316.09  4550.1  310.93  4555.1  311.61  4574.2  309.41  4582.9  309.18
  4614.3  308.64  4644.3  306.51  4734.3  304.33    4841  304.42  4891.4  302.97
  4921.3  303.59    5052  302.77  5080.2   303.2  5122.2   302.7  5127.6  302.46
  5130.3  301.96  5133.6  302.46  5137.2  302.66  5196.1  304.34  5229.4  306.25
  5309.2  307.79  5323.9  308.75  5344.8  308.28  5430.6  312.65  5445.3  312.39
  5465.4  313.06  5501.8   314.6  5516.2  314.61    5590  316.73  5605.2  317.43
#Mann= 9 ,-1 , 0
  4491.5      .1       0  4582.9     .05       0    5052     .16       0
  5122.2    .035       0  5137.2     .16       0  5196.1      .1       0
  5465.4     .05       0  5516.2      .1       0    5590     .05       0
Bank Sta=5127.6,5133.6
XS Rating Curve= 0 ,0
Exp/Cntr=0.3,0.1

Chan Stop Cuts=-1
Use User Specified Reach Order=0
Composite Channel Slope=5