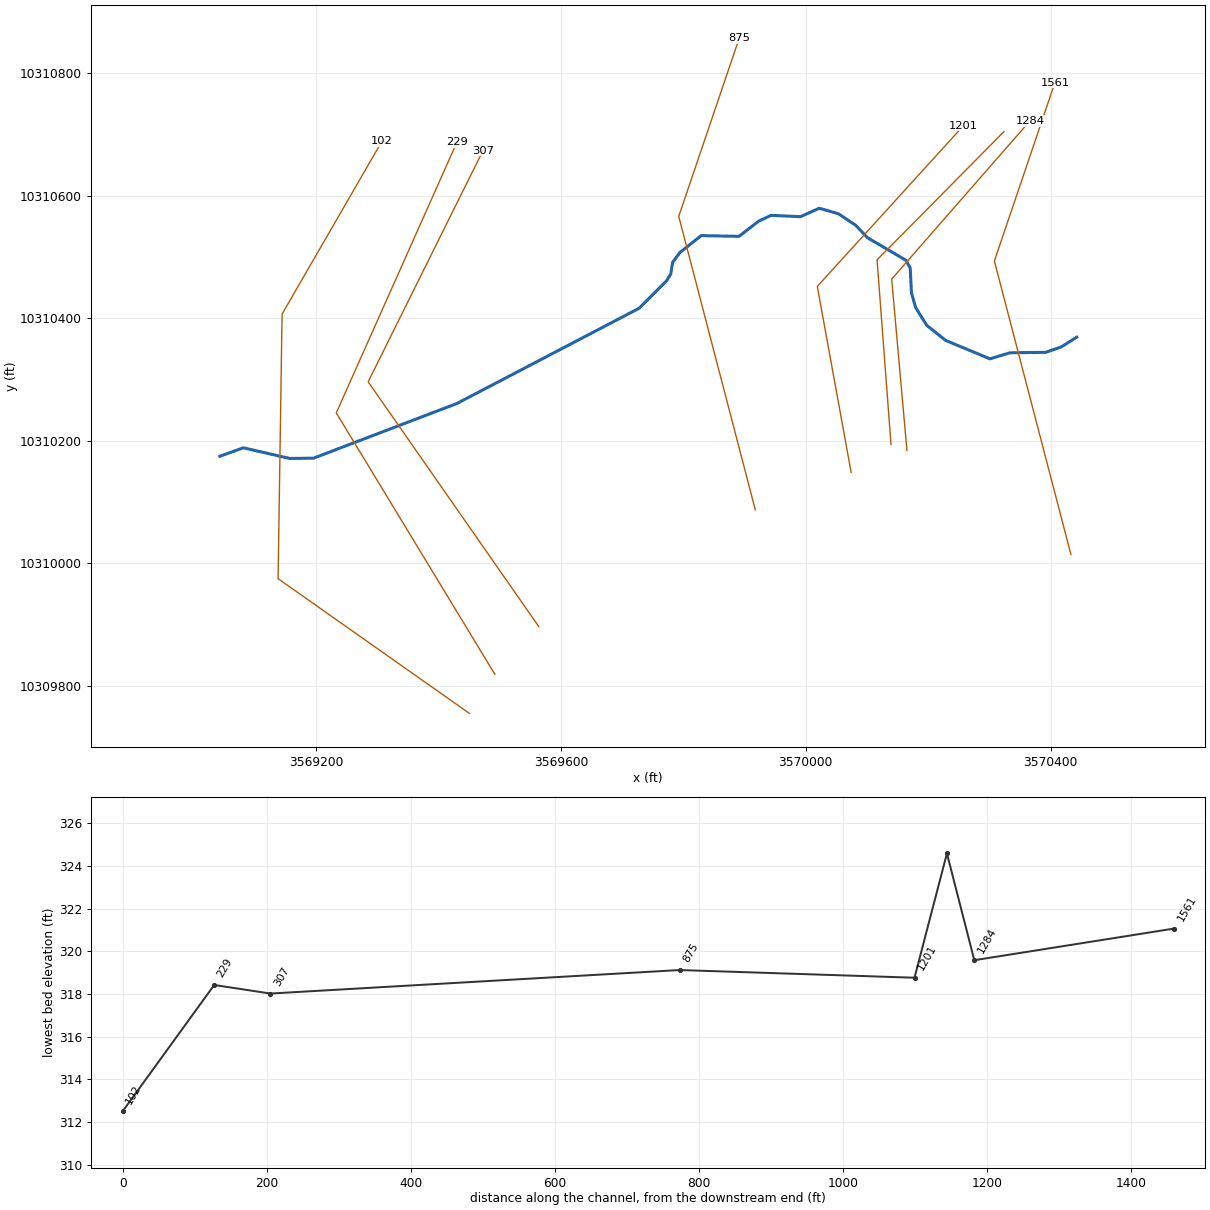
--- JACK CREEK TRIBUTARY 4.prj (project) ---

Proj Title=JACK CREEK TRIBUTARY 4 Base Level Engineering
Current Plan=p01
Default Exp/Contr=0.3,0.1
English Units
Geom File=g01
Flow File=f01
Plan File=p01
BEGIN DESCRIPTION:
JACK CREEK TRIBUTARY 4
END DESCRIPTION:

--- JACK CREEK TRIBUTARY 4.p01 (plan) ---

Plan Title=Multiple Run
Short Identifier=Multiple
Geom File=g01
Flow File=f01
Subcritical Flow
K Sum by GR= 0
Std Step Tol= 0.01
Critical Tol= 0.01
Num of Std Step Trials= 20
Max Error Tol= 0.3
Flow Tol Ratio= 0.001
Split Flow NTrial= 30
Split Flow Tol= 0.02
Split Flow Ratio= 0.02
Log Output Level= 0
Friction Slope Method= 1
Unsteady Friction Slope Method= 2
Unsteady Bridges Friction Slope Method= 1
Parabolic Critical Depth
Global Vel Dist=  1 , 1 , 1
Global Log Level= 0
CheckData=True
Encroach Param= -1, 0, 0, 0
BEGIN DESCRIPTION:
Multiple Run
END DESCRIPTION:

--- JACK CREEK TRIBUTARY 4.f01 (steady flow) ---

Flow Title=Multiple
Number of Profiles=7
Profile Names=10-year,25-year,50-year,1pct_min,100-year,1pct_plu,500-year
River Rch & RM= JACK CREEK TRIBU,Reach-1,1561
     273     351     412     355     480     649     652
Boundary for River Rch & Prof#=JACK CREEK TRIBU,Reach-1,1
Up Type=0
Dn Type=3
Dn Slope=0.005
Boundary for River Rch & Prof#=JACK CREEK TRIBU,Reach-1,2
Up Type=0
Dn Type=3
Dn Slope=0.005
Boundary for River Rch & Prof#=JACK CREEK TRIBU,Reach-1,3
Up Type=0
Dn Type=3
Dn Slope=0.005
Boundary for River Rch & Prof#=JACK CREEK TRIBU,Reach-1,4
Up Type=0
Dn Type=3
Dn Slope=0.005
Boundary for River Rch & Prof#=JACK CREEK TRIBU,Reach-1,5
Up Type=0
Dn Type=3
Dn Slope=0.005
Boundary for River Rch & Prof#=JACK CREEK TRIBU,Reach-1,6
Up Type=0
Dn Type=3
Dn Slope=0.005
Boundary for River Rch & Prof#=JACK CREEK TRIBU,Reach-1,7
Up Type=0
Dn Type=3
Dn Slope=0.005

--- JACK CREEK TRIBUTARY 4.g01 (geometry) ---

Geom Title=Existing Conditions

River Reach=JACK CREEK TRIBU,Reach-1
Reach XY= 30
      3570442.76     10310369.17      3570417.64     10310353.29
      3570392.12     10310344.44      3570333.78     10310343.70
      3570300.97     10310333.81      3570228.57     10310364.01
      3570197.84     10310388.49      3570179.62     10310417.66
      3570172.84     10310441.62      3570170.76     10310482.24
      3570163.99     10310494.74      3570100.97     10310531.72
      3570081.70     10310552.04      3570053.57     10310570.79
      3570022.22     10310579.84      3569991.55     10310566.04
      3569943.42     10310568.21      3569923.42     10310558.86
      3569891.03     10310533.87      3569829.31     10310535.14
      3569794.68     10310507.63      3569782.70     10310491.49
      3569779.57     10310472.22      3569772.28     10310460.76
      3569728.01     10310416.49      3569430.40     10310260.93
      3569196.02     10310171.52      3569156.96     10310171.09
      3569081.44     10310188.45      3569043.03     10310174.67

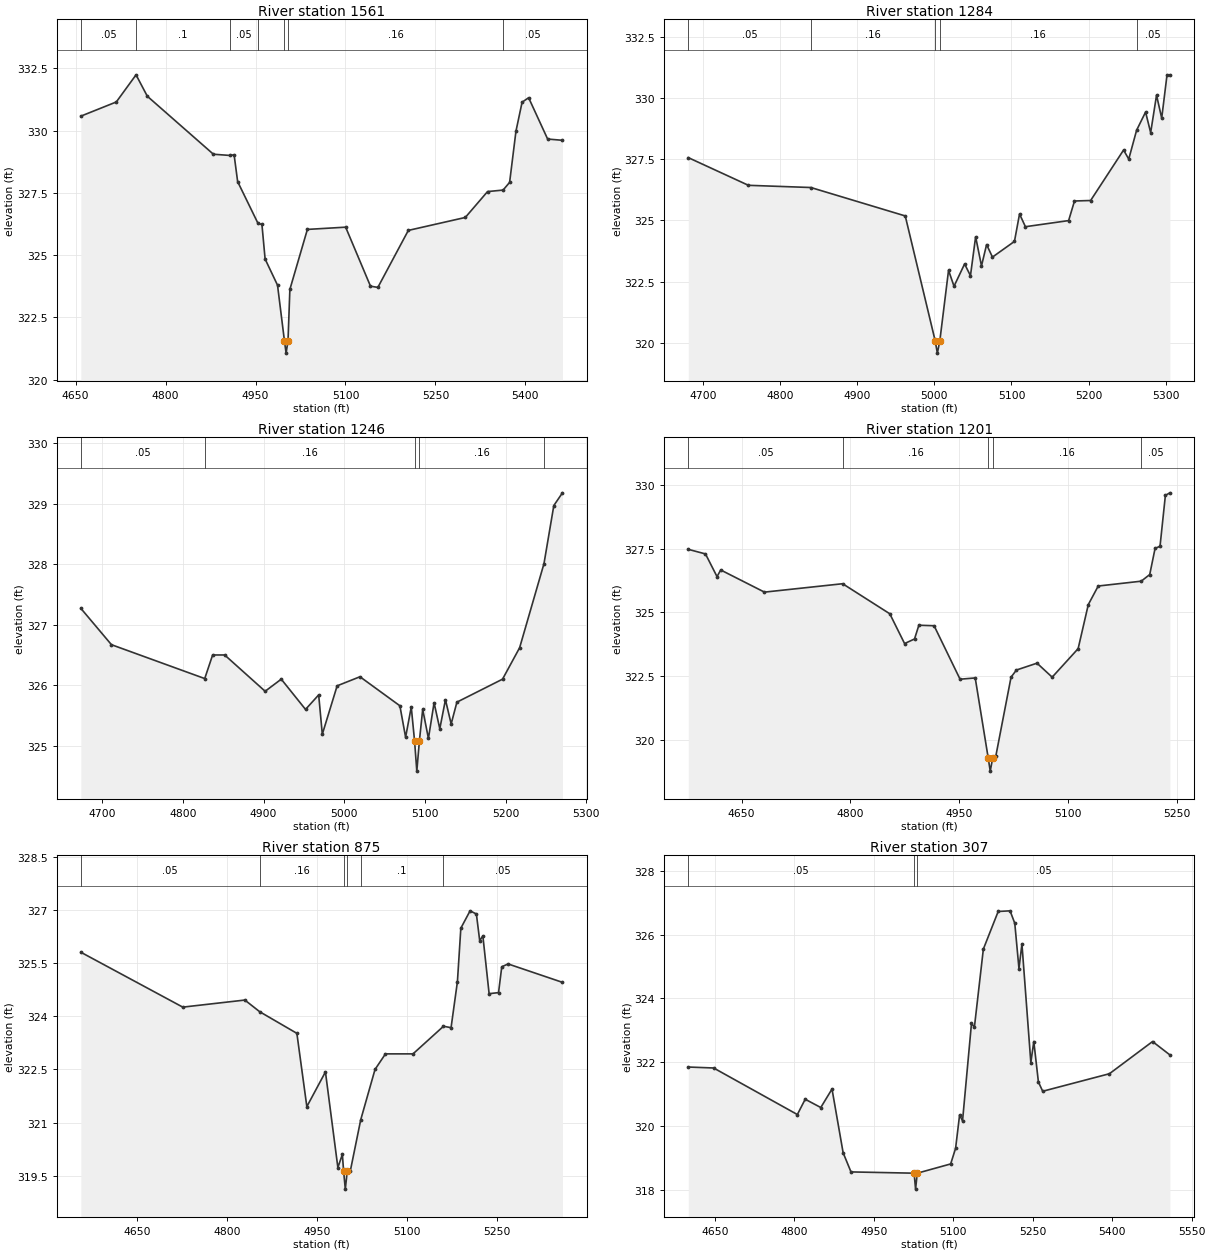
Type RM Length L Ch R = 1,1561,277,277,277
BEGIN DESCRIPTION:
JACK CREEK TRIBUTARY 4 3.0
END DESCRIPTION:
XS GIS Cut Line= 3
      3570433.29     10310014.40      3570308.28     10310493.60
      3570407.16     10310785.04
#Sta/Elev= 30
  4658.8  330.58  4717.9  331.15  4750.8  332.24  4769.6  331.38  4879.8  329.05
  4908.1  329.00  4914.3  329.03  4920.2  327.95  4954.2  326.27  4960.7  326.23
  4966.0  324.84  4986.7  323.79  4998.2  321.56  5001.0  321.06  5004.2  321.56
  5007.3  323.62  5036.5  326.03  5100.3  326.12  5141.7  323.75  5154.0  323.70
  5204.8  325.99  5299.8  326.51  5336.9  327.55  5362.8  327.61  5373.7  327.92
  5384.3  329.98  5394.5  331.14  5405.4  331.32  5437.1  329.66  5461.8  329.61
#Mann=7,-1,0
  4658.8    0.05       0  4750.8     0.1       0  4908.1    0.05       0
  4954.2    0.16       0  4998.2    0.07       0  5004.2    0.16       0
  5362.8    0.05       0
Bank Sta=4998.2,5004.2
Exp/Cntr=0.3,0.1

Type RM Length L Ch R = 1,1284,38,38,38
BEGIN DESCRIPTION:
Mapping XS 3300d7eb
END DESCRIPTION:
XS GIS Cut Line= 3
      3570165.46     10310184.09      3570140.50     10310464.03
      3570366.18     10310722.26
#Sta/Elev= 30
  4681.3  327.56  4759.2  326.43  4840.1  326.34  4962.4  325.18  5001.2  320.08
  5004.0  319.58  5007.2  320.08  5018.5  322.96  5025.6  322.31  5039.3  323.22
  5046.9  322.74  5053.6  324.33  5061.2  323.14  5067.8  324.01  5075.4  323.50
  5103.9  324.14  5110.5  325.26  5118.1  324.74  5174.1  324.99  5181.7  325.79
  5202.6  325.81  5245.3  327.87  5252.0  327.50  5262.2  328.68  5273.8  329.42
  5280.4  328.58  5288.0  330.11  5294.7  329.17  5301.6  330.94  5305.3  330.94
#Mann=5,-1,0
  4681.3    0.05       0  4840.1    0.16       0  5001.2    0.07       0
  5007.2    0.16       0  5262.2    0.05       0
Bank Sta=5001.2,5007.2
Exp/Cntr=0.3,0.1

Type RM Length L Ch R = 1,1246,45,45,45
BEGIN DESCRIPTION:
Mapping XS 26abafb9
END DESCRIPTION:
XS GIS Cut Line= 3
      3570139.42     10310193.82      3570116.63     10310495.50
      3570323.90     10310704.94
#Sta/Elev= 30
  4673.4  327.27  4711.3  326.67  4827.0  326.11  4836.8  326.50  4851.7  326.50
  4901.9  325.90  4921.9  326.10  4952.0  325.60  4968.3  325.84  4972.8  325.19
  4991.2  325.99  5019.5  326.14  5069.0  325.66  5076.1  325.14  5083.1  325.64
  5087.2  325.08  5090.0  324.58  5093.2  325.08  5097.3  325.60  5104.4  325.12
  5111.4  325.71  5118.5  325.28  5125.5  325.76  5132.6  325.36  5139.7  325.72
  5196.3  326.10  5217.5  326.62  5247.7  328.01  5259.9  328.97  5270.6  329.18
#Mann=5,-1,0
  4673.4    0.05       0  4827.0    0.16       0  5087.2    0.07       0
  5093.2    0.16       0  5247.7    0.05       0
Bank Sta=5087.2,5093.2
Exp/Cntr=0.3,0.1

Type RM Length L Ch R = 1,1201,326,326,326
BEGIN DESCRIPTION:
Mapping XS 69af8004
END DESCRIPTION:
XS GIS Cut Line= 3
      3570074.31     10310148.30      3570018.97     10310452.10
      3570257.96     10310714.87
#Sta/Elev= 30
  4576.6  327.47  4600.3  327.29  4616.2  326.40  4621.3  326.66  4681.6  325.79
  4789.4  326.12  4854.4  324.94  4874.8  323.77  4888.5  323.95  4894.5  324.49
  4915.5  324.47  4951.3  322.37  4972.2  322.42  4990.2  319.26  4992.9  318.76
  4996.2  319.26  5000.6  319.35  5021.6  322.45  5029.0  322.73  5057.4  323.00
  5078.3  322.45  5114.1  323.57  5128.1  325.30  5141.8  326.03  5201.1  326.22
  5212.8  326.48  5220.2  327.51  5227.0  327.59  5234.4  329.59  5240.6  329.69
#Mann=5,-1,0
  4576.6    0.05       0  4789.4    0.16       0  4990.2    0.07       0
  4996.2    0.16       0  5201.1    0.05       0
Bank Sta=4990.2,4996.2
Exp/Cntr=0.3,0.1

Type RM Length L Ch R = 1,875,568,568,568
BEGIN DESCRIPTION:
JACK CREEK TRIBUTARY 4 2.0
END DESCRIPTION:
XS GIS Cut Line= 3
      3569917.66     10310087.32      3569792.66     10310566.52
      3569891.35     10310857.40
#Sta/Elev= 30
  4556.1  325.81  4725.9  324.26  4829.3  324.46  4854.1  324.13  4916.0  323.52
  4932.6  321.45  4963.6  322.43  4984.3  319.73  4991.8  320.10  4993.9  319.62
  4996.7  319.12  4999.9  319.62  5005.0  319.63  5022.4  321.08  5046.2  322.50
  5063.6  322.94  5109.5  322.94  5160.3  323.72  5172.9  323.68  5183.5  324.98
  5189.2  326.49  5204.6  326.98  5215.1  326.89  5220.6  326.14  5225.9  326.27
  5236.3  324.64  5252.0  324.67  5257.4  325.40  5267.9  325.48  5358.5  324.96
#Mann=6,-1,0
  4556.1    0.05       0  4854.1    0.16       0  4993.9    0.07       0
  4999.9    0.16       0  5022.4     0.1       0  5160.3    0.05       0
Bank Sta=4993.9,4999.9
Exp/Cntr=0.3,0.1

Type RM Length L Ch R = 1,307,78,78,78
BEGIN DESCRIPTION:
Mapping XS 768f8607
END DESCRIPTION:
XS GIS Cut Line= 3
      3569563.88     10309896.56      3569285.25     10310296.28
      3569472.73     10310673.84
#Sta/Elev= 30
  4600.1  321.85  4647.9  321.82  4805.9  320.36  4820.7  320.84  4850.1  320.58
  4871.3  321.16  4892.3  319.16  4907.1  318.56  5026.2  318.52  5029.0  318.02
  5032.2  318.52  5095.2  318.81  5104.5  319.30  5112.1  320.35  5117.6  320.16
  5134.5  323.22  5140.0  323.10  5156.9  325.55  5184.9  326.73  5207.3  326.75
  5216.2  326.36  5224.1  324.94  5229.7  325.71  5246.5  321.99  5252.1  322.65
  5260.8  321.38  5268.9  321.09  5394.8  321.64  5476.2  322.65  5508.9  322.23
#Mann=3,-1,0
  4600.1    0.05       0  5026.2    0.03       0  5032.2    0.05       0
Bank Sta=5026.2,5032.2
Exp/Cntr=0.3,0.1

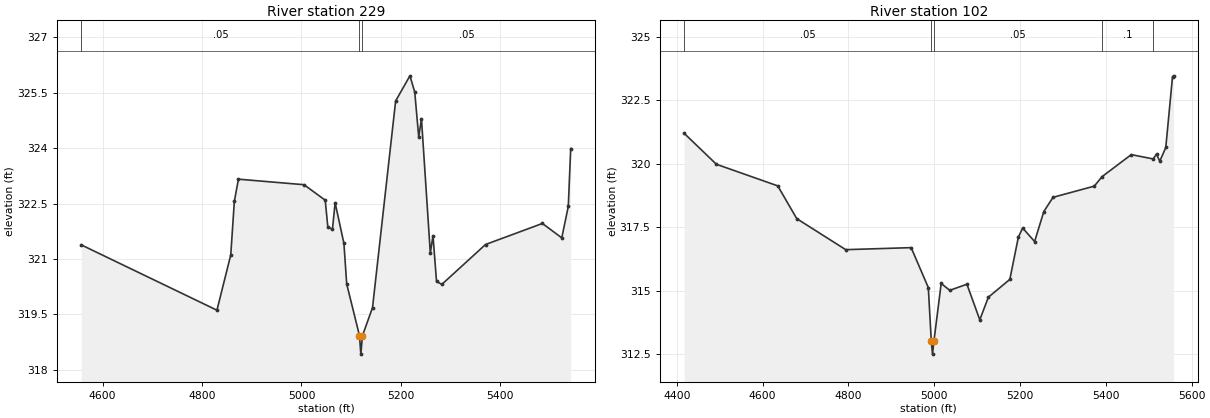
Type RM Length L Ch R = 1,229,127,127,127
BEGIN DESCRIPTION:
Mapping XS 219bd158
END DESCRIPTION:
XS GIS Cut Line= 3
      3569492.26     10309818.45      3569233.16     10310245.50
      3569430.46     10310688.11
#Sta/Elev= 30
  4557.3  321.38  4830.1  319.61  4857.9  321.11  4865.1  322.56  4873.3  323.16
  5005.2  323.01  5047.8  322.59  5053.0  321.87  5062.3  321.80  5067.7  322.52
  5085.4  321.42  5091.0  320.32  5116.7  318.92  5119.4  318.42  5122.7  318.92
  5142.9  319.68  5189.4  325.28  5218.1  325.96  5227.8  325.52  5235.8  324.30
  5241.3  324.80  5259.1  321.16  5264.5  321.63  5271.6  320.39  5282.3  320.31
  5370.1  321.39  5484.5  321.96  5523.4  321.57  5536.5  322.42  5541.4  323.99
#Mann=3,-1,0
  4557.3    0.05       0  5116.7    0.03       0  5122.7    0.05       0
Bank Sta=5116.7,5122.7
Exp/Cntr=0.3,0.1

Type RM Length L Ch R = 1,102,0,0,0
BEGIN DESCRIPTION:
JACK CREEK TRIBUTARY 4 1.0
END DESCRIPTION:
XS GIS Cut Line= 4
      3569450.62     10309754.61      3569138.11     10309974.67
      3569144.62     10310406.96      3569307.88     10310689.42
#Sta/Elev= 30
  4417.0  321.20  4492.3  319.98  4635.3  319.13  4679.6  317.84  4793.7  316.62
  4946.2  316.70  4986.2  315.13  4993.2  313.01  4996.0  312.51  4999.2  313.01
  5016.2  315.29  5036.2  315.02  5076.2  315.26  5106.2  313.86  5126.2  314.75
  5176.2  315.45  5196.2  317.12  5206.2  317.47  5234.0  316.94  5255.4  318.12
  5276.9  318.68  5373.1  319.12  5390.9  319.49  5459.3  320.36  5510.3  320.19
  5518.1  320.38  5525.7  320.10  5539.7  320.64  5555.4  323.43  5557.8  323.46
#Mann=5,-1,0
  4417.0    0.05       0  4993.2    0.03       0  4999.2    0.05       0
  5390.9     0.1       0  5510.3    0.05       0
Bank Sta=4993.2,4999.2
Exp/Cntr=0.3,0.1

Chan Stop Cuts=-1