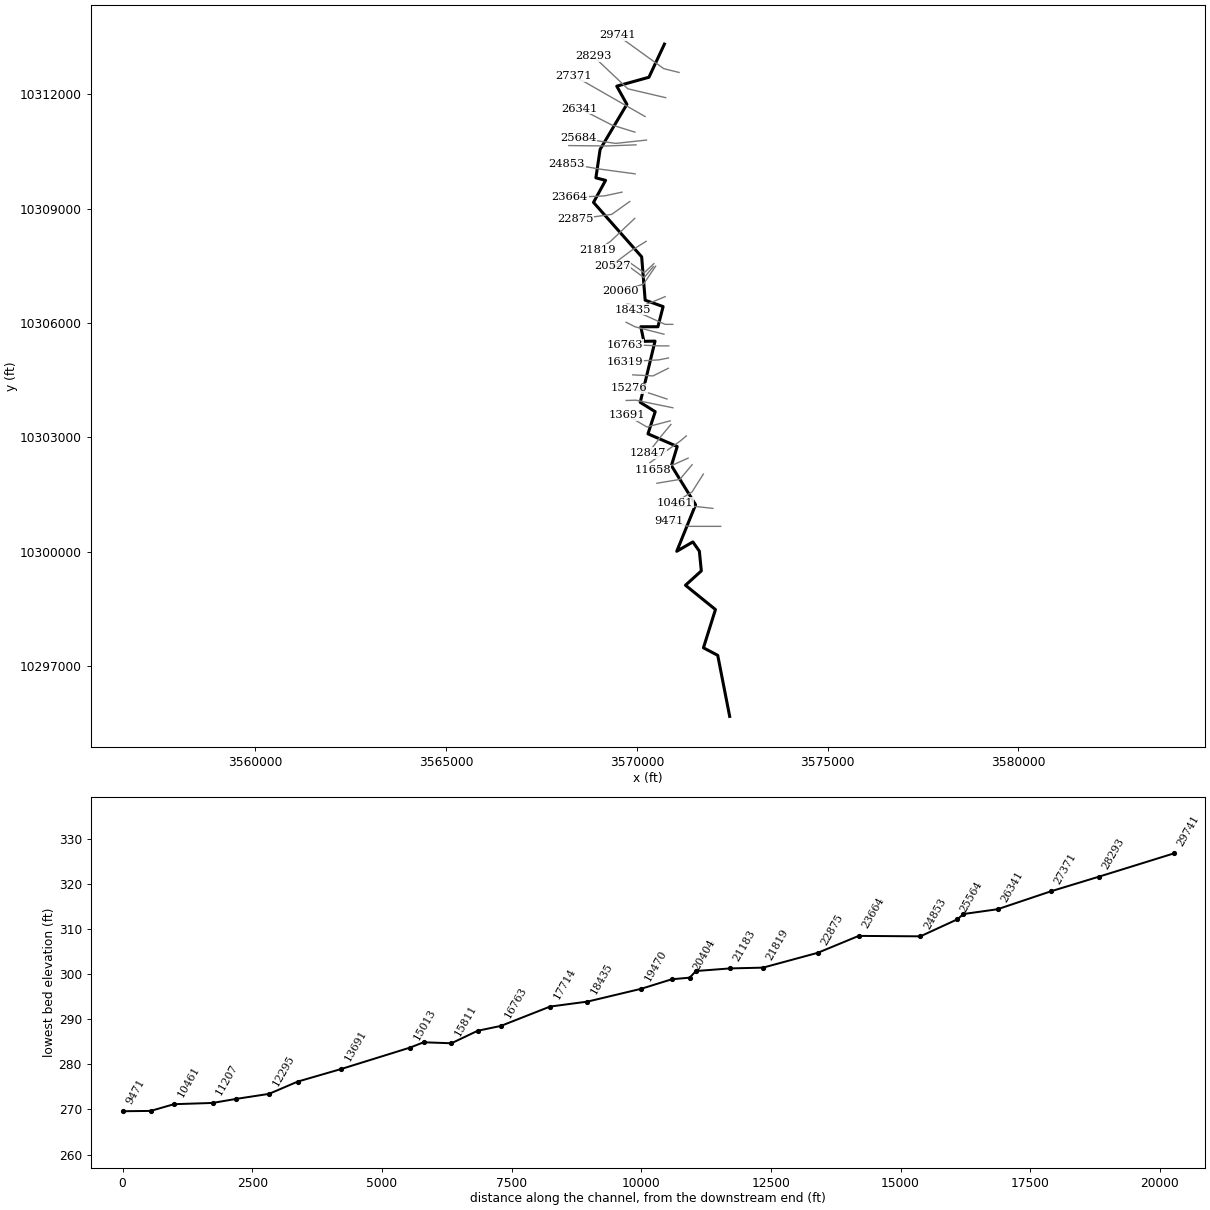
--- JACK CREEK.prj (project) ---

Proj Title=JACK CREEK Base Level Engineering
Current Plan=p01
Default Exp/Contr=0.3,0.1
English Units
Geom File=g01
Flow File=f01
Plan File=p01
BEGIN DESCRIPTION:
JACK CREEK
END DESCRIPTION:

--- JACK CREEK.p01 (plan) ---

Plan Title=Multiple Run
Short Identifier=Multiple
Geom File=g01
Flow File=f01
Subcritical Flow
K Sum by GR= 0
Std Step Tol= 0.01
Critical Tol= 0.01
Num of Std Step Trials= 20
Max Error Tol= 0.3
Flow Tol Ratio= 0.001
Split Flow NTrial= 30
Split Flow Tol= 0.02
Split Flow Ratio= 0.02
Log Output Level= 0
Friction Slope Method= 1
Unsteady Friction Slope Method= 2
Unsteady Bridges Friction Slope Method= 1
Parabolic Critical Depth
Global Vel Dist=  1 , 1 , 1
Global Log Level= 0
CheckData=True
Encroach Param= -1, 0, 0, 0
BEGIN DESCRIPTION:
Multiple Run
END DESCRIPTION:

--- JACK CREEK.f01 (steady flow) ---

Flow Title=Multiple
Number of Profiles=7
Profile Names=10-year,25-year,50-year,1pct_min,100-year,1pct_plu,500-year
River Rch & RM= JACK CREEK,Reach-1,29741
     290     371     432     370     501     678     673
River Rch & RM= JACK CREEK,Reach-1,27371
     562     749     899     790    1068    1445    1512
River Rch & RM= JACK CREEK,Reach-1,24853
     735     993    1202    1065    1441    1948    2074
River Rch & RM= JACK CREEK,Reach-1,21183
     758    1022    1237    1094    1480    2001    2124
River Rch & RM= JACK CREEK,Reach-1,19470
     857    1164    1414    1257    1699    2298    2460
River Rch & RM= JACK CREEK,Reach-1,15276
     886    1204    1465    1302    1761    2382    2553
River Rch & RM= JACK CREEK,Reach-1,12847
    1492    2087    2587    2341    3165    4281    4754
River Rch & RM= JACK CREEK,Reach-1,10013
    1724    2413    2993    2707    3661    4951    5494
Boundary for River Rch & Prof#=JACK CREEK,Reach-1,1
Up Type=0
Dn Type=3
Dn Slope=0.005
Boundary for River Rch & Prof#=JACK CREEK,Reach-1,2
Up Type=0
Dn Type=3
Dn Slope=0.005
Boundary for River Rch & Prof#=JACK CREEK,Reach-1,3
Up Type=0
Dn Type=3
Dn Slope=0.005
Boundary for River Rch & Prof#=JACK CREEK,Reach-1,4
Up Type=0
Dn Type=3
Dn Slope=0.005
Boundary for River Rch & Prof#=JACK CREEK,Reach-1,5
Up Type=0
Dn Type=3
Dn Slope=0.005
Boundary for River Rch & Prof#=JACK CREEK,Reach-1,6
Up Type=0
Dn Type=3
Dn Slope=0.005
Boundary for River Rch & Prof#=JACK CREEK,Reach-1,7
Up Type=0
Dn Type=3
Dn Slope=0.005

--- JACK CREEK.g01 (geometry) ---

Geom Title=Existing Conditions

River Reach=JACK CREEK,Reach-1
Reach XY= 30
      3570722.11     10313311.64      3570315.71     10312441.83
      3569472.47     10312208.18      3569737.91     10311732.83
      3569035.97     10310550.64      3568925.41     10309805.75
      3569179.31     10309739.77      3568862.95     10309161.96
      3570125.22     10307735.59      3570216.93     10306598.85
      3570687.53     10306430.94      3570551.14     10305902.89
      3570103.42     10305902.53      3570182.29     10305520.73
      3570475.75     10305525.80      3570087.72     10303921.43
      3570480.45     10303676.27      3570290.14     10303095.51
      3571057.05     10302764.15      3570904.95     10302262.83
      3571538.95     10301236.66      3571044.72     10300017.11
      3571467.10     10300262.71      3571637.44     10300020.85
      3571688.97     10299503.24      3571273.68     10299127.09
      3572059.14     10298490.39      3571744.57     10297487.39
      3572118.89     10297289.96      3572432.17     10295689.44

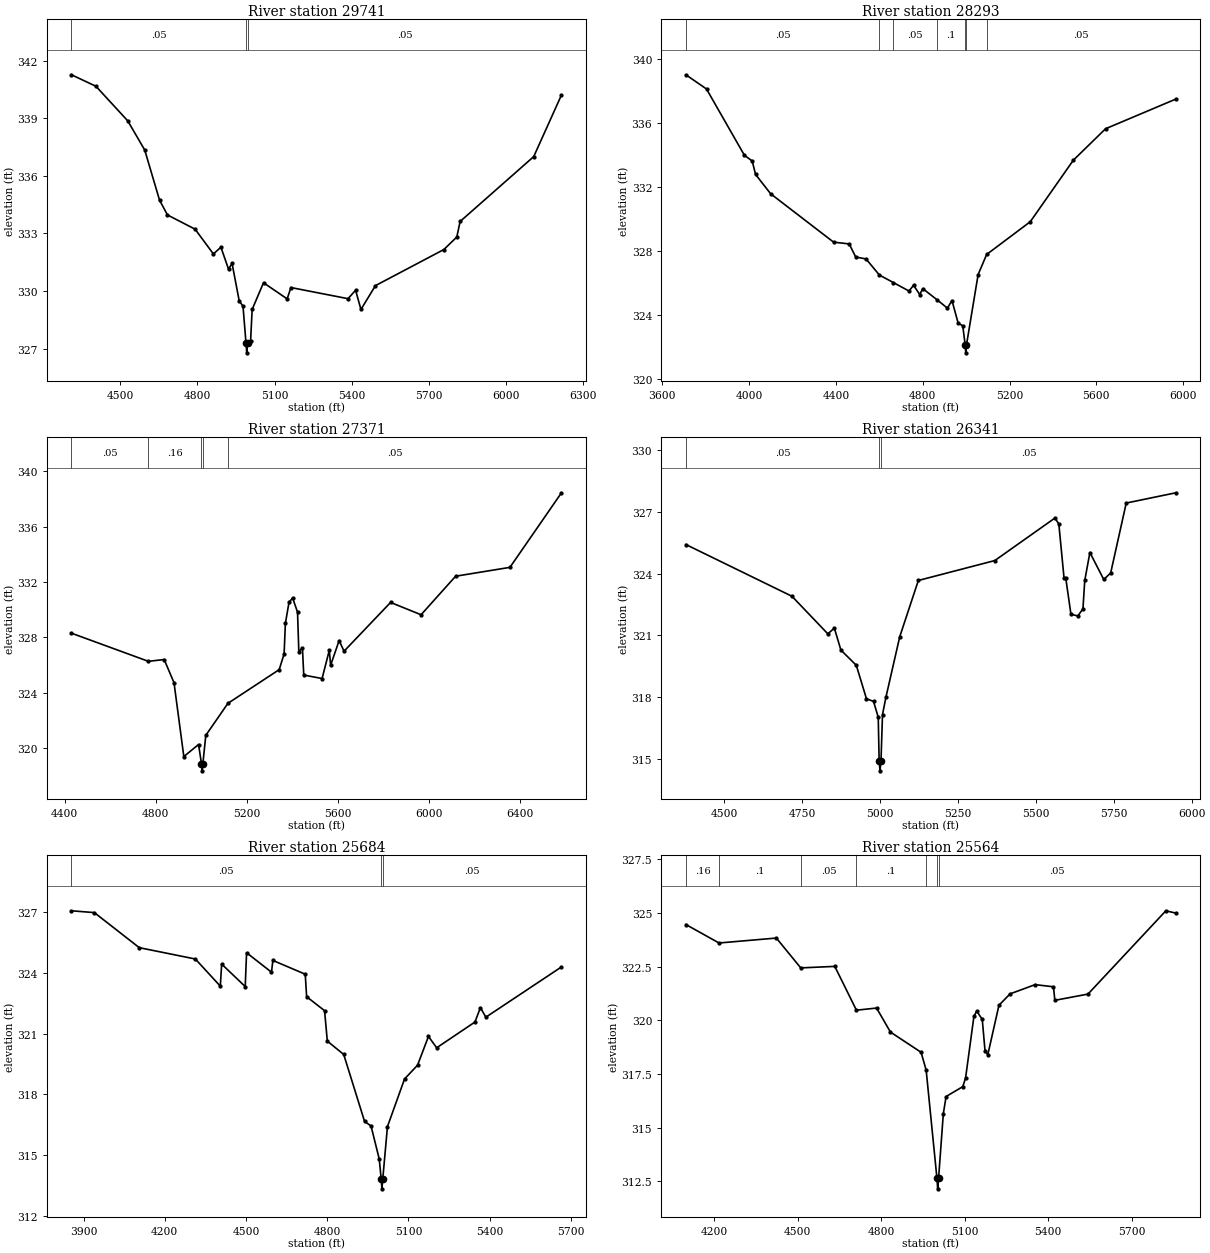
Type RM Length L Ch R = 1,29741,1448,1448,1448
BEGIN DESCRIPTION:
JACK CREEK 47.0
END DESCRIPTION:
XS GIS Cut Line= 3
      3571104.56     10312567.69      3570704.61     10312667.68
      3569492.11     10313541.64
#Sta/Elev= 30
  4309.8  341.26  4405.1  340.66  4528.8  338.86  4594.9  337.34  4652.5  334.73
  4683.4  333.96  4790.8  333.22  4862.0  331.93  4891.4  332.28  4920.9  331.14
  4934.7  331.44  4962.6  329.48  4977.3  329.21  4989.0  327.28  4991.8  326.78
  4995.0  327.28  5006.8  327.39  5012.9  329.04  5057.1  330.43  5149.1  329.59
  5163.8  330.18  5386.0  329.60  5415.4  330.04  5436.3  329.04  5492.7  330.28
  5759.0  332.16  5809.3  332.81  5822.2  333.62  6108.7  337.00  6216.7  340.21
#Mann=3,-1,0
  4309.8    0.05       0  4989.0   0.035       0  4995.0    0.05       0
Bank Sta=4989,4995
Exp/Cntr=0.3,0.1

Type RM Length L Ch R = 1,28293,922,922,922
BEGIN DESCRIPTION:
JACK CREEK 46.0
END DESCRIPTION:
XS GIS Cut Line= 3
      3570754.50     10311906.78      3569762.24     10312139.91
      3568862.26     10312989.90
#Sta/Elev= 30
  3709.2  339.02  3804.1  338.13  3978.7  333.98  4014.7  333.62  4030.1  332.78
  4099.5  331.57  4389.6  328.54  4461.5  328.43  4491.4  327.61  4538.9  327.49
  4600.7  326.48  4665.0  326.01  4736.9  325.48  4757.9  325.84  4786.3  325.26
  4800.4  325.63  4866.3  324.93  4913.7  324.41  4935.0  324.88  4963.1  323.48
  4984.5  323.30  4995.7  322.11  4998.4  321.61  5001.7  322.11  5055.3  326.51
  5094.6  327.77  5295.6  329.82  5493.8  333.67  5642.3  335.64  5966.4  337.50
#Mann=7,-1,0
  3709.2    0.05       0  4600.7     0.1       0  4665.0    0.05       0
  4866.3     0.1       0  4995.7    0.07       0  5001.7     0.1       0
  5094.6    0.05       0
Bank Sta=4995.7,5001.7
Exp/Cntr=0.3,0.1

Type RM Length L Ch R = 1,27371,1030,1030,1030
BEGIN DESCRIPTION:
JACK CREEK 44.0
END DESCRIPTION:
XS GIS Cut Line= 3
      3570216.25     10311412.01      3568639.67     10312314.56
      3568339.63     10312464.58
#Sta/Elev= 30
  4430.1  328.31  4767.9  326.28  4837.2  326.41  4880.4  324.74  4923.5  319.41
  4988.3  320.28  5001.1  318.88  5003.9  318.38  5007.1  318.88  5020.0  320.94
  5117.2  323.25  5342.3  325.68  5363.9  326.81  5369.6  329.02  5385.5  330.54
  5401.3  330.85  5422.9  329.83  5428.6  326.97  5444.5  327.25  5450.2  325.29
  5530.8  325.04  5562.5  327.08  5568.2  325.99  5605.6  327.78  5627.2  327.01
  5831.6  330.53  5965.4  329.64  6117.2  332.42  6355.8  333.06  6582.2  338.44
#Mann=5,-1,0
  4430.1    0.05       0  4767.9    0.16       0  5001.1    0.07       0
  5007.1    0.16       0  5117.2    0.05       0
Bank Sta=5001.1,5007.1
Exp/Cntr=0.3,0.1

Type RM Length L Ch R = 1,26341,657,657,657
BEGIN DESCRIPTION:
JACK CREEK 43.0
END DESCRIPTION:
XS GIS Cut Line= 3
      3569947.20     10311004.01      3569342.11     10311191.64
      3568506.68     10311620.09
#Sta/Elev= 30
  4377.1  325.42  4717.5  322.90  4832.6  321.07  4853.5  321.35  4874.5  320.28
  4923.9  319.54  4956.5  317.91  4979.2  317.78  4994.3  317.01  4997.2  314.90
  4999.9  314.40  5003.2  314.90  5008.0  317.14  5018.9  317.98  5063.3  320.93
  5123.0  323.67  5368.4  324.64  5561.3  326.71  5573.8  326.42  5590.4  323.81
  5596.0  323.79  5612.6  322.03  5634.8  321.94  5651.2  322.29  5657.0  323.67
  5673.5  325.03  5717.9  323.72  5740.1  324.03  5790.1  327.44  5949.5  327.94
#Mann=3,-1,0
  4377.1    0.05       0  4997.2   0.035       0  5003.2    0.05       0
Bank Sta=4997.2,5003.2
Exp/Cntr=0.3,0.1

Type RM Length L Ch R = 1,25684,120,120,120
BEGIN DESCRIPTION:
JACK CREEK 41.0
END DESCRIPTION:
XS GIS Cut Line= 3
      3570251.03     10310795.69      3569443.70     10310708.88
      3568455.56     10310847.56
#Sta/Elev= 30
  3855.5  327.06  3940.0  326.97  4105.9  325.24  4313.1  324.68  4405.2  323.34
  4410.2  324.43  4497.2  323.32  4502.2  324.99  4594.2  324.03  4599.3  324.61
  4718.9  323.93  4724.0  322.82  4790.3  322.13  4800.4  320.63  4861.0  319.97
  4937.9  316.67  4961.9  316.44  4992.2  314.81  4999.3  313.84  5002.1  313.34
  5005.3  313.84  5022.5  316.41  5085.6  318.76  5133.6  319.44  5174.0  320.86
  5204.3  320.30  5345.7  321.57  5365.8  322.28  5386.0  321.81  5665.3  324.29
#Mann=3,-1,0
  3855.5    0.05       0  4999.3    0.04       0  5005.3    0.05       0
Bank Sta=4999.3,5005.3
Exp/Cntr=0.3,0.1

Type RM Length L Ch R = 1,25564,711,711,711
BEGIN DESCRIPTION:
Mapping XS 2154ebc7
END DESCRIPTION:
XS GIS Cut Line= 3
      3569977.03     10310670.99      3569206.62     10310640.61
      3568215.98     10310651.45
#Sta/Elev= 30
  4097.9  324.46  4217.0  323.60  4423.1  323.83  4510.8  322.44  4633.2  322.51
  4711.0  320.47  4783.4  320.57  4833.4  319.45  4943.4  318.51  4961.7  317.68
  5000.4  312.65  5003.2  312.15  5006.4  312.65  5023.4  315.65  5033.4  316.45
  5093.4  316.91  5103.4  317.31  5133.4  320.18  5143.4  320.43  5163.4  320.04
  5173.4  318.57  5183.4  318.40  5223.4  320.70  5263.4  321.23  5353.4  321.66
  5419.4  321.56  5424.4  320.93  5543.5  321.22  5823.5  325.10  5859.6  324.99
#Mann=7,-1,0
  4097.9    0.16       0  4217.0     0.1       0  4510.8    0.05       0
  4711.0     0.1       0  4961.7    0.05       0  5000.4    0.04       0
  5006.4    0.05       0
Bank Sta=5000.4,5006.4
Exp/Cntr=0.3,0.1

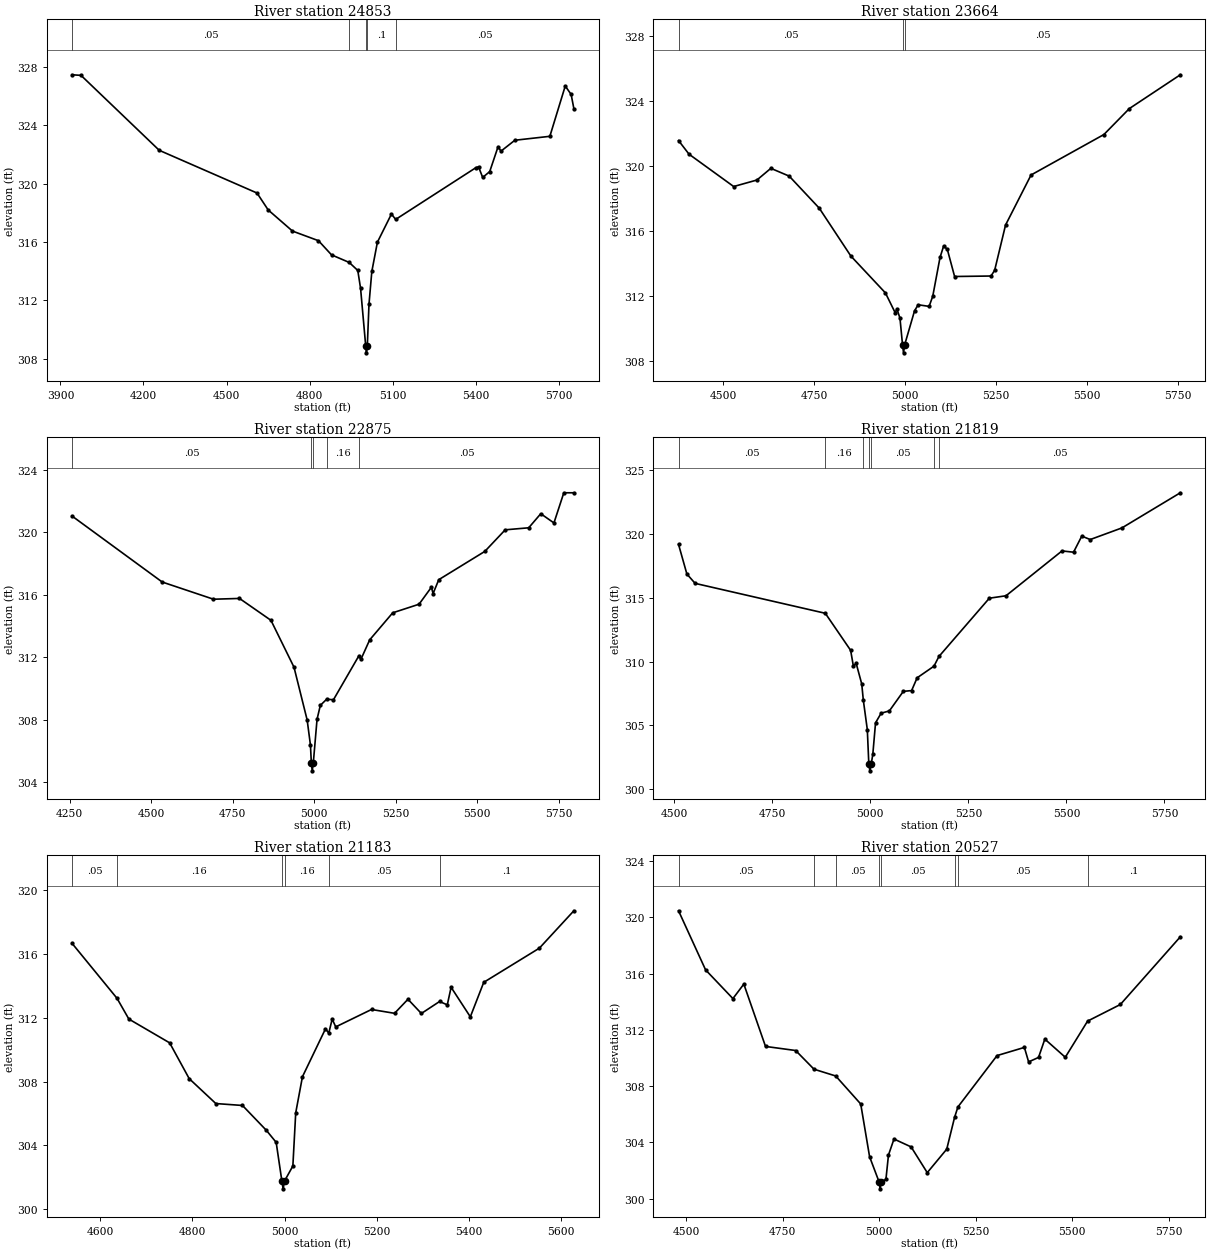
Type RM Length L Ch R = 1,24853,1189,1189,1189
BEGIN DESCRIPTION:
JACK CREEK 40.0
END DESCRIPTION:
XS GIS Cut Line= 3
      3569954.12     10309910.27      3569063.49     10310030.06
      3568162.41     10310181.11
#Sta/Elev= 30
  3942.2  327.46  3974.5  327.42  4257.0  322.28  4610.2  319.35  4650.5  318.19
  4738.3  316.74  4832.2  316.08  4879.2  315.11  4943.1  314.59  4974.1  314.04
  4984.2  312.81  5002.6  308.89  5005.4  308.39  5008.6  308.89  5014.6  311.73
  5024.8  313.97  5045.0  315.98  5095.7  317.91  5110.9  317.54  5399.9  321.08
  5410.1  321.15  5425.2  320.42  5450.6  320.82  5480.8  322.53  5491.2  322.22
  5541.4  322.97  5667.8  323.24  5723.4  326.69  5744.7  326.11  5754.5  325.14
#Mann=5,-1,0
  3942.2    0.05       0  4943.1     0.1       0  5002.6    0.07       0
  5008.6     0.1       0  5110.9    0.05       0
Bank Sta=5002.6,5008.6
Exp/Cntr=0.3,0.1

Type RM Length L Ch R = 1,23664,789,789,789
BEGIN DESCRIPTION:
JACK CREEK 38.0
END DESCRIPTION:
XS GIS Cut Line= 3
      3569610.35     10309431.09      3569146.82     10309332.14
      3568242.10     10309291.64
#Sta/Elev= 30
  4376.8  321.56  4405.7  320.72  4528.4  318.73  4592.3  319.13  4630.6  319.85
  4681.1  319.37  4763.6  317.40  4850.6  314.45  4945.6  312.18  4972.2  310.97
  4977.2  311.18  4985.6  310.63  4992.6  308.99  4995.4  308.49  4998.6  308.99
  5025.7  311.08  5035.7  311.45  5065.7  311.35  5075.7  311.97  5095.7  314.36
  5105.7  315.07  5115.8  314.86  5135.8  313.19  5235.9  313.22  5245.9  313.57
  5275.9  316.36  5346.0  319.44  5546.2  321.93  5616.3  323.53  5756.4  325.61
#Mann=3,-1,0
  4376.8    0.05       0  4992.6    0.03       0  4998.6    0.05       0
Bank Sta=4992.6,4998.6
Exp/Cntr=0.3,0.1

Type RM Length L Ch R = 1,22875,1056,1056,1056
BEGIN DESCRIPTION:
JACK CREEK 36.0
END DESCRIPTION:
XS GIS Cut Line= 3
      3569813.50     10309186.31      3569339.53     10308847.77
      3568391.59     10308717.55
#Sta/Elev= 30
  4257.5  321.04  4534.0  316.82  4691.3  315.72  4771.1  315.77  4867.6  314.37
  4938.3  311.37  4978.7  307.99  4988.8  306.38  4991.5  305.24  4994.2  304.74
  4997.5  305.24  5009.0  308.04  5019.1  308.93  5038.4  309.32  5059.4  309.29
  5137.6  312.11  5143.7  311.88  5170.5  313.12  5241.1  314.85  5321.9  315.40
  5359.9  316.49  5364.9  316.08  5382.4  316.97  5523.7  318.78  5586.2  320.16
  5658.3  320.29  5695.3  321.19  5735.7  320.60  5766.0  322.53  5796.8  322.53
#Mann=5,-1,0
  4257.5    0.05       0  4991.5    0.03       0  4997.5    0.05       0
  5038.4    0.16       0  5137.6    0.05       0
Bank Sta=4991.5,4997.5
Exp/Cntr=0.3,0.1

Type RM Length L Ch R = 1,21819,636,636,636
BEGIN DESCRIPTION:
JACK CREEK 35.0
END DESCRIPTION:
XS GIS Cut Line= 3
      3569942.12     10308741.66      3569303.56     10308136.43
      3568970.60     10307916.04
#Sta/Elev= 30
  4511.3  319.17  4532.6  316.85  4553.6  316.12  4885.4  313.78  4950.0  310.88
  4956.9  309.66  4964.2  309.85  4978.3  308.25  4982.3  306.99  4992.5  304.68
  4996.4  301.95  4999.1  301.45  5002.4  301.95  5006.6  302.77  5013.5  305.21
  5027.7  305.96  5048.7  306.14  5084.3  307.67  5105.4  307.73  5119.5  308.73
  5162.4  309.64  5175.1  310.40  5303.6  314.96  5346.0  315.15  5488.8  318.66
  5518.2  318.56  5539.2  319.82  5560.7  319.55  5641.5  320.46  5790.4  323.21
#Mann=7,-1,0
  4511.3    0.05       0  4885.4    0.16       0  4982.3    0.05       0
  4996.4    0.03       0  5002.4    0.05       0  5162.4     0.1       0
  5175.1    0.05       0
Bank Sta=4996.4,5002.4
Exp/Cntr=0.3,0.1

Type RM Length L Ch R = 1,21183,656,656,656
BEGIN DESCRIPTION:
JACK CREEK 33.0
END DESCRIPTION:
XS GIS Cut Line= 3
      3570242.10     10308141.64      3569842.11     10307891.64
      3569349.97     10307519.66
#Sta/Elev= 30
  4538.9  316.65  4636.4  313.21  4662.1  311.91  4750.6  310.42  4793.0  308.18
  4850.8  306.62  4908.6  306.50  4960.5  304.94  4981.7  304.19  4994.0  301.78
  4996.8  301.28  5000.0  301.78  5017.9  302.71  5024.1  306.04  5038.7  308.30
  5088.7  311.30  5095.8  311.03  5103.2  311.91  5110.9  311.42  5188.5  312.51
  5238.5  312.27  5267.6  313.15  5296.7  312.26  5336.2  313.01  5352.9  312.80
  5361.2  313.90  5402.9  312.05  5432.0  314.21  5552.7  316.35  5627.5  318.69
#Mann=6,-1,0
  4538.9    0.05       0  4636.4    0.16       0  4994.0    0.07       0
  5000.0    0.16       0  5095.8    0.05       0  5336.2     0.1       0
Bank Sta=4994,5000
Exp/Cntr=0.3,0.1

Type RM Length L Ch R = 1,20527,123,123,123
BEGIN DESCRIPTION:
JACK CREEK 32.0
END DESCRIPTION:
XS GIS Cut Line= 4
      3570445.79     10307556.86      3570191.86     10307318.13
      3569757.83     10307624.12      3569360.70     10307485.23
#Sta/Elev= 30
  4479.7  320.46  4549.8  316.26  4620.6  314.22  4648.9  315.25  4705.1  310.82
  4783.2  310.53  4830.8  309.20  4887.0  308.72  4951.8  306.73  4974.8  302.98
  4999.3  301.20  5002.0  300.70  5005.3  301.20  5017.1  301.37  5023.7  303.10
  5038.0  304.24  5082.4  303.68  5124.2  301.85  5174.7  303.52  5195.1  305.79
  5203.7  306.52  5305.1  310.17  5375.9  310.75  5386.9  309.72  5412.6  310.04
  5428.9  311.34  5481.9  310.05  5539.7  312.62  5624.6  313.80  5780.0  318.61
#Mann=8,-1,0
  4479.7    0.05       0  4830.8     0.1       0  4887.0    0.05       0
  4999.3    0.04       0  5005.3    0.05       0  5195.1     0.1       0
  5203.7    0.05       0  5539.7     0.1       0
Bank Sta=4999.3,5005.3
Exp/Cntr=0.3,0.1

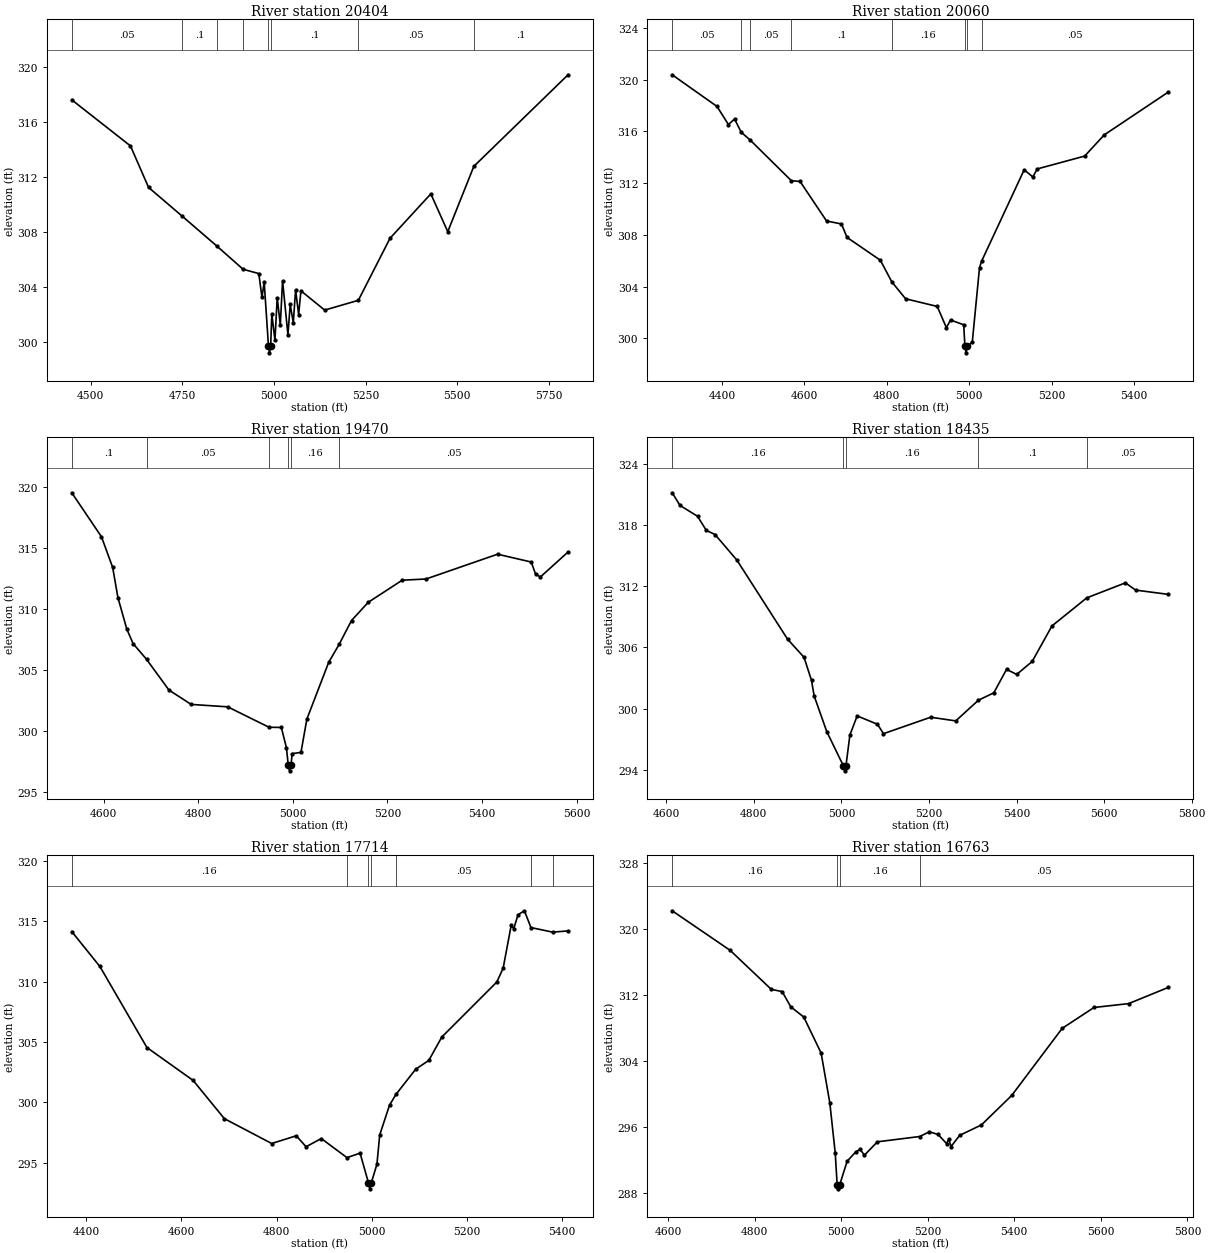
Type RM Length L Ch R = 1,20404,344,344,344
BEGIN DESCRIPTION:
Mapping XS 11691b36
END DESCRIPTION:
XS GIS Cut Line= 4
      3570430.57     10307478.71      3570187.52     10307190.09
      3569701.41     10307548.16      3569341.19     10307450.51
#Sta/Elev= 30
  4448.1  317.58  4608.2  314.24  4657.6  311.23  4749.1  309.15  4844.6  306.96
  4915.7  305.29  4958.5  304.98  4967.0  303.26  4973.2  304.35  4984.8  299.73
  4987.6  299.23  4990.8  299.73  4994.0  302.03  5002.5  300.14  5008.7  303.23
  5017.1  301.25  5023.3  304.46  5037.9  300.54  5044.2  302.74  5052.6  301.41
  5058.8  303.80  5067.2  302.01  5073.4  303.73  5138.2  302.33  5230.1  303.04
  5316.5  307.54  5427.9  310.76  5474.1  308.02  5545.3  312.76  5802.4  319.40
#Mann=8,-1,0
  4448.1    0.05       0  4749.1     0.1       0  4844.6    0.16       0
  4915.7     0.1       0  4984.8    0.07       0  4990.8     0.1       0
  5230.1    0.05       0  5545.3     0.1       0
Bank Sta=4984.8,4990.8
Exp/Cntr=0.3,0.1

Type RM Length L Ch R = 1,20060,590,590,590
BEGIN DESCRIPTION:
JACK CREEK 31.0
END DESCRIPTION:
XS GIS Cut Line= 3
      3570492.11     10307491.65      3570172.87     10307019.64
      3569568.18     10306830.19
#Sta/Elev= 30
  4279.5  320.38  4388.2  317.93  4415.9  316.53  4430.8  316.96  4446.9  315.93
  4467.7  315.36  4568.7  312.18  4589.6  312.13  4653.8  309.07  4690.0  308.84
  4703.5  307.80  4784.4  306.03  4812.3  304.35  4845.6  303.05  4922.3  302.46
  4944.4  300.82  4954.7  301.41  4986.4  301.04  4989.4  299.37  4992.1  298.87
  4995.4  299.37  5007.3  299.71  5024.8  305.46  5030.3  305.99  5133.1  313.03
  5154.0  312.48  5165.1  313.10  5279.8  314.09  5327.3  315.73  5483.0  319.05
#Mann=8,-1,0
  4279.5    0.05       0  4446.9     0.1       0  4467.7    0.05       0
  4568.7     0.1       0  4812.3    0.16       0  4989.4    0.07       0
  4995.4    0.16       0  5030.3    0.05       0
Bank Sta=4989.4,4995.4
Exp/Cntr=0.3,0.1

Type RM Length L Ch R = 1,19470,1035,1035,1035
BEGIN DESCRIPTION:
JACK CREEK 30.0
END DESCRIPTION:
XS GIS Cut Line= 3
      3570742.08     10306691.63      3570144.19     10306446.85
      3569744.16     10306496.85
#Sta/Elev= 30
  4532.7  319.53  4595.4  315.93  4619.1  313.42  4630.2  310.95  4648.8  308.39
  4662.3  307.18  4690.8  305.89  4738.0  303.38  4785.0  302.20  4862.4  302.00
  4949.6  300.33  4975.7  300.31  4986.5  298.65  4990.2  297.26  4993.0  296.76
  4996.2  297.26  4998.6  298.17  5017.2  298.27  5029.7  301.00  5076.0  305.66
  5097.8  307.11  5124.1  309.07  5159.4  310.56  5231.2  312.37  5281.6  312.47
  5432.8  314.50  5504.0  313.86  5513.4  312.85  5523.5  312.64  5581.9  314.68
#Mann=6,-1,0
  4532.7     0.1       0  4690.8    0.05       0  4949.6    0.16       0
  4990.2    0.07       0  4996.2    0.16       0  5097.8    0.05       0
Bank Sta=4990.2,4996.2
Exp/Cntr=0.3,0.1

Type RM Length L Ch R = 1,18435,721,721,721
BEGIN DESCRIPTION:
JACK CREEK 29.0
END DESCRIPTION:
XS GIS Cut Line= 3
      3570940.01     10305965.60      3570740.02     10305965.60
      3569888.00     10306347.05
#Sta/Elev= 30
  4613.5  321.15  4631.4  319.91  4671.4  318.85  4691.4  317.47  4711.4  317.06
  4761.4  314.55  4876.9  306.82  4914.6  305.04  4931.7  302.78  4937.8  301.25
  4966.5  297.77  5004.4  294.42  5007.1  293.92  5010.4  294.42  5019.4  297.43
  5036.0  299.30  5082.4  298.48  5096.1  297.56  5203.9  299.17  5261.2  298.81
  5312.8  300.83  5348.1  301.56  5377.2  303.86  5400.4  303.36  5435.7  304.63
  5480.9  308.11  5560.4  310.86  5648.7  312.33  5671.9  311.62  5747.0  311.20
#Mann=5,-1,0
  4613.5    0.16       0  5004.4    0.07       0  5010.4    0.16       0
  5312.8     0.1       0  5560.4    0.05       0
Bank Sta=5004.4,5010.4
Exp/Cntr=0.3,0.1

Type RM Length L Ch R = 1,17714,951,951,951
BEGIN DESCRIPTION:
JACK CREEK 28.0
END DESCRIPTION:
XS GIS Cut Line= 3
      3570709.33     10305707.14      3569954.12     10305901.15
      3569718.02     10306019.20
#Sta/Elev= 30
  4369.3  314.15  4428.4  311.26  4527.3  304.54  4624.5  301.81  4690.2  298.64
  4789.7  296.58  4841.4  297.22  4862.0  296.31  4894.0  296.99  4948.0  295.41
  4975.6  295.78  4993.2  293.32  4996.0  292.82  4999.2  293.32  5011.0  294.86
  5016.9  297.29  5037.5  299.76  5051.0  300.65  5092.5  302.74  5120.1  303.47
  5147.5  305.41  5263.1  309.97  5276.5  311.12  5293.3  314.66  5298.8  314.40
  5307.8  315.55  5321.2  315.88  5334.9  314.49  5380.4  314.11  5413.0  314.21
#Mann=7,-1,0
  4369.3    0.16       0  4948.0     0.1       0  4993.2    0.07       0
  4999.2     0.1       0  5051.0    0.05       0  5334.9     0.1       0
  5380.4    0.05       0
Bank Sta=4993.2,4999.2
Exp/Cntr=0.3,0.1

Type RM Length L Ch R = 1,16763,444,444,444
BEGIN DESCRIPTION:
JACK CREEK 26.0
END DESCRIPTION:
XS GIS Cut Line= 3
      3570836.07     10305401.15      3570606.89     10305401.15
      3569690.23     10305435.87
#Sta/Elev= 30
  4609.8  322.22  4743.8  317.42  4838.9  312.69  4863.8  312.43  4883.8  310.58
  4913.8  309.34  4953.9  304.97  4973.9  298.96  4986.5  292.85  4990.9  289.02
  4993.6  288.52  4996.9  289.02  5013.9  291.86  5033.9  293.00  5043.9  293.31
  5053.9  292.60  5083.9  294.22  5181.3  294.86  5204.0  295.43  5224.0  295.11
  5243.6  294.01  5248.7  294.53  5254.1  293.65  5274.1  295.01  5324.1  296.26
  5394.2  299.84  5510.8  307.97  5584.3  310.50  5664.4  310.97  5756.3  312.94
#Mann=4,-1,0
  4609.8    0.16       0  4990.9    0.07       0  4996.9    0.16       0
  5181.3    0.05       0
Bank Sta=4990.9,4996.9
Exp/Cntr=0.3,0.1

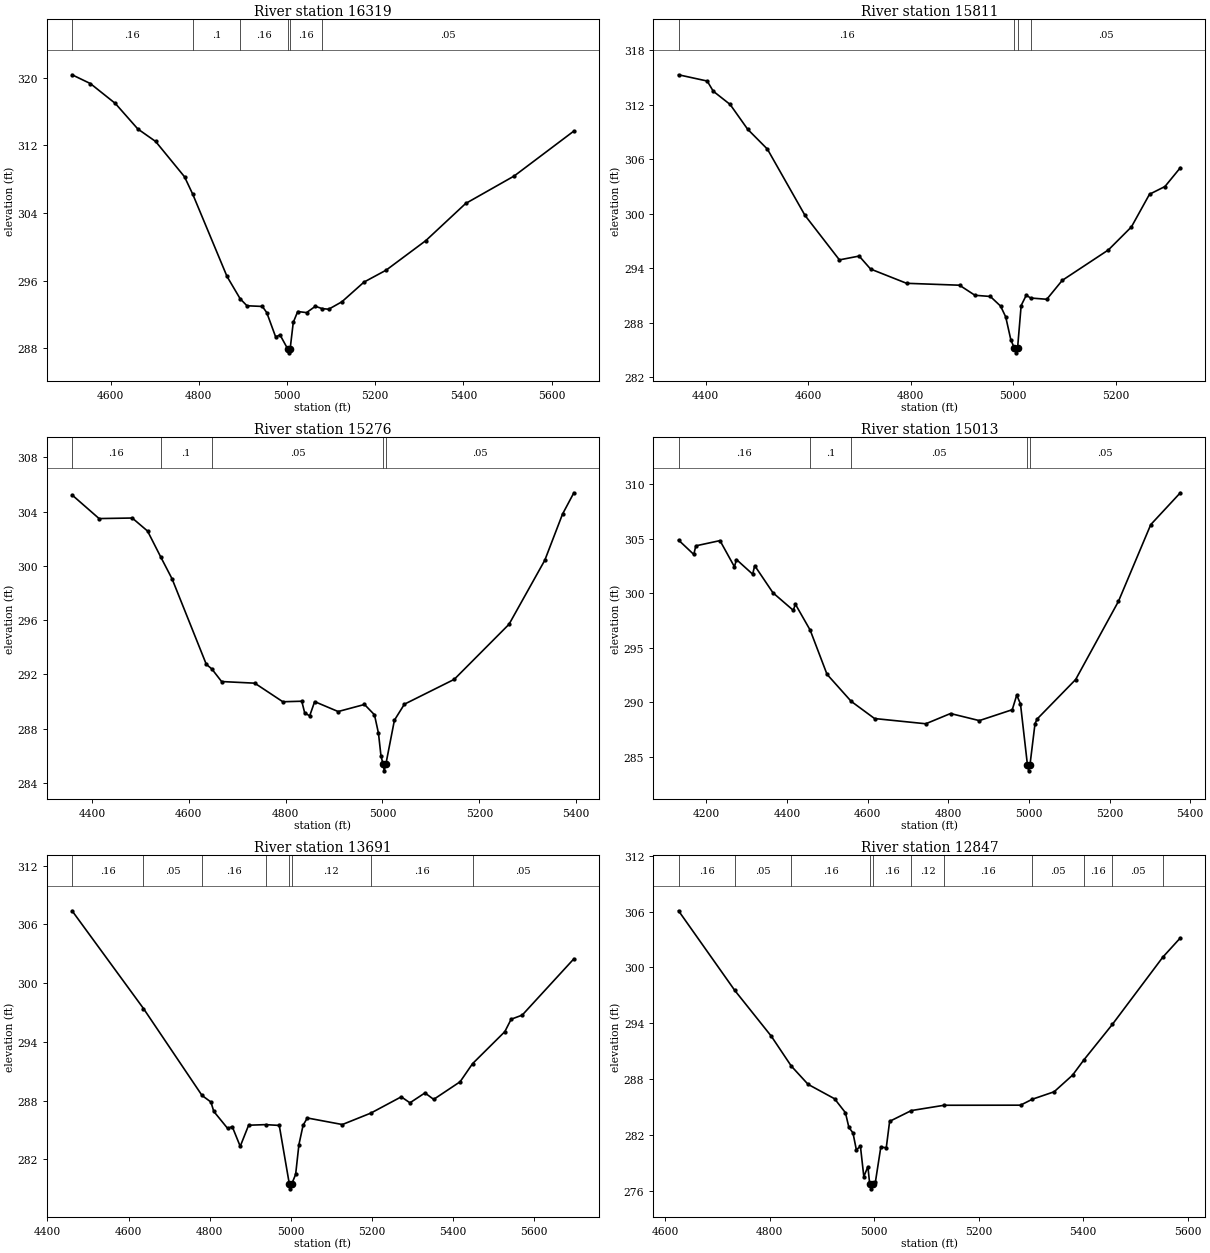
Type RM Length L Ch R = 1,16319,508,508,508
BEGIN DESCRIPTION:
JACK CREEK 25.0
END DESCRIPTION:
XS GIS Cut Line= 3
      3570828.20     10305084.69      3570578.22     10305034.70
      3569697.18     10304984.48
#Sta/Elev= 30
  4512.8  320.36  4554.3  319.32  4610.8  316.97  4661.8  313.95  4702.2  312.47
  4767.7  308.29  4786.4  306.22  4864.0  296.50  4893.8  293.86  4909.2  293.03
  4944.1  292.95  4954.1  292.22  4974.2  289.35  4984.2  289.58  5001.2  287.96
  5004.0  287.46  5007.2  287.96  5014.2  291.07  5024.3  292.35  5044.3  292.22
  5064.3  292.97  5079.1  292.70  5094.4  292.62  5124.4  293.50  5174.5  295.83
  5224.6  297.24  5314.7  300.74  5404.9  305.13  5515.1  308.39  5650.2  313.70
#Mann=6,-1,0
  4512.8    0.16       0  4786.4     0.1       0  4893.8    0.16       0
  5001.2    0.07       0  5007.2    0.16       0  5079.1    0.05       0
Bank Sta=5001.2,5007.2
Exp/Cntr=0.3,0.1

Type RM Length L Ch R = 1,15811,535,535,535
BEGIN DESCRIPTION:
JACK CREEK 24.0
END DESCRIPTION:
XS GIS Cut Line= 3
      3570822.67     10304813.87      3570422.66     10304613.86
      3569892.11     10304641.64
#Sta/Elev= 30
  4347.1  315.31  4403.0  314.62  4414.8  313.50  4447.7  312.04  4481.9  309.31
  4520.4  307.12  4593.7  299.82  4660.8  294.92  4699.3  295.34  4721.6  293.91
  4791.8  292.34  4895.0  292.13  4925.1  291.02  4955.1  290.89  4975.1  289.83
  4985.1  288.64  4995.2  286.09  5002.2  285.18  5004.9  284.68  5008.2  285.18
  5015.2  289.89  5025.2  291.03  5033.6  290.72  5065.2  290.58  5095.3  292.66
  5185.4  296.02  5230.2  298.55  5265.5  302.15  5295.6  303.00  5325.6  305.07
#Mann=4,-1,0
  4347.1    0.16       0  5002.2    0.07       0  5008.2    0.16       0
  5033.6    0.05       0
Bank Sta=5002.2,5008.2
Exp/Cntr=0.3,0.1

Type RM Length L Ch R = 1,15276,263,263,263
BEGIN DESCRIPTION:
JACK CREEK 23.0
END DESCRIPTION:
XS GIS Cut Line= 3
      3570787.97     10304008.30      3570337.94     10304158.31
      3569792.06     10304291.65
#Sta/Elev= 30
  4358.9  305.23  4414.7  303.49  4483.2  303.53  4514.8  302.57  4542.0  300.66
  4565.4  299.05  4636.1  292.75  4647.5  292.41  4667.7  291.48  4736.2  291.36
  4794.2  289.99  4833.3  290.03  4839.3  289.17  4849.6  288.95  4859.9  290.00
  4908.4  289.27  4962.8  289.79  4983.4  289.03  4991.7  287.67  4996.8  286.02
  5001.0  285.40  5003.7  284.90  5007.0  285.40  5024.6  288.63  5045.2  289.81
  5148.1  291.64  5261.3  295.70  5335.2  300.42  5371.8  303.82  5395.2  305.39
#Mann=5,-1,0
  4358.9    0.16       0  4542.0     0.1       0  4647.5    0.05       0
  5001.0   0.035       0  5007.0    0.05       0
Bank Sta=5001,5007
Exp/Cntr=0.3,0.1

Type RM Length L Ch R = 1,15013,1322,1322,1322
BEGIN DESCRIPTION:
JACK CREEK 22.0
END DESCRIPTION:
XS GIS Cut Line= 3
      3570942.79     10303778.76      3569970.61     10303978.41
      3569718.83     10303969.73
#Sta/Elev= 30
  4131.2  304.90  4169.0  303.58  4174.1  304.37  4234.0  304.85  4269.8  302.45
  4274.9  303.11  4315.0  301.77  4320.1  302.55  4365.4  300.06  4415.8  298.45
  4420.9  299.02  4457.7  296.63  4499.4  292.58  4559.3  290.10  4617.3  288.52
  4744.4  288.04  4805.7  288.98  4877.1  288.33  4958.8  289.33  4969.9  290.67
  4979.2  289.86  4996.6  284.22  4999.4  283.72  5002.6  284.22  5015.2  288.04
  5020.3  288.47  5116.0  292.10  5222.2  299.28  5302.3  306.32  5375.6  309.24
#Mann=5,-1,0
  4131.2    0.16       0  4457.7     0.1       0  4559.3    0.05       0
  4996.6   0.035       0  5002.6    0.05       0
Bank Sta=4996.6,5002.6
Exp/Cntr=0.3,0.1

Type RM Length L Ch R = 1,13691,844,844,844
BEGIN DESCRIPTION:
JACK CREEK 21.0
END DESCRIPTION:
XS GIS Cut Line= 3
      3570873.36     10303435.87      3570261.41     10303275.28
      3569740.61     10303583.42
#Sta/Elev= 30
  4460.7  307.40  4636.9  297.41  4781.3  288.53  4803.2  287.86  4810.3  286.90
  4844.5  285.16  4855.8  285.35  4875.5  283.33  4896.2  285.49  4938.1  285.55
  4971.8  285.47  4996.6  279.49  4999.4  278.99  5002.6  279.49  5012.2  280.47
  5020.3  283.51  5030.6  285.49  5041.0  286.23  5127.4  285.56  5197.8  286.73
  5272.7  288.39  5294.2  287.78  5331.2  288.79  5352.7  288.13  5417.9  289.93
  5448.6  291.78  5528.2  295.05  5543.8  296.32  5571.1  296.74  5698.5  302.49
#Mann=8,-1,0
  4460.7    0.16       0  4636.9    0.05       0  4781.3    0.16       0
  4938.1    0.12       0  4996.6    0.07       0  5002.6    0.12       0
  5197.8    0.16       0  5448.6    0.05       0
Bank Sta=4996.6,5002.6
Exp/Cntr=0.3,0.1

Type RM Length L Ch R = 1,12847,552,552,552
BEGIN DESCRIPTION:
JACK CREEK 20.0
END DESCRIPTION:
XS GIS Cut Line= 3
      3570892.09     10303341.62      3570642.11     10303041.64
      3570292.09     10302591.62
#Sta/Elev= 30
  4625.4  306.09  4733.1  297.52  4803.1  292.59  4841.2  289.39  4873.4  287.42
  4924.1  285.87  4944.9  284.37  4951.5  282.79  4959.3  282.20  4965.8  280.38
  4973.6  280.76  4980.1  277.49  4987.9  278.57  4991.4  276.68  4994.2  276.18
  4997.4  276.68  5002.2  276.89  5012.6  280.66  5023.1  280.61  5029.5  283.44
  5071.1  284.60  5133.8  285.17  5280.1  285.18  5302.7  285.82  5344.4  286.62
  5379.7  288.41  5401.5  290.06  5455.8  293.86  5552.6  301.11  5586.0  303.17
#Mann=11,-1,0
  4625.4    0.16       0  4733.1    0.05       0  4841.2    0.16       0
  4991.4    0.07       0  4997.4    0.16       0  5071.1    0.12       0
  5133.8    0.16       0  5302.7    0.05       0  5401.5    0.16       0
  5455.8    0.05       0  5552.6    0.16       0
Bank Sta=4991.4,4997.4
Exp/Cntr=0.3,0.1

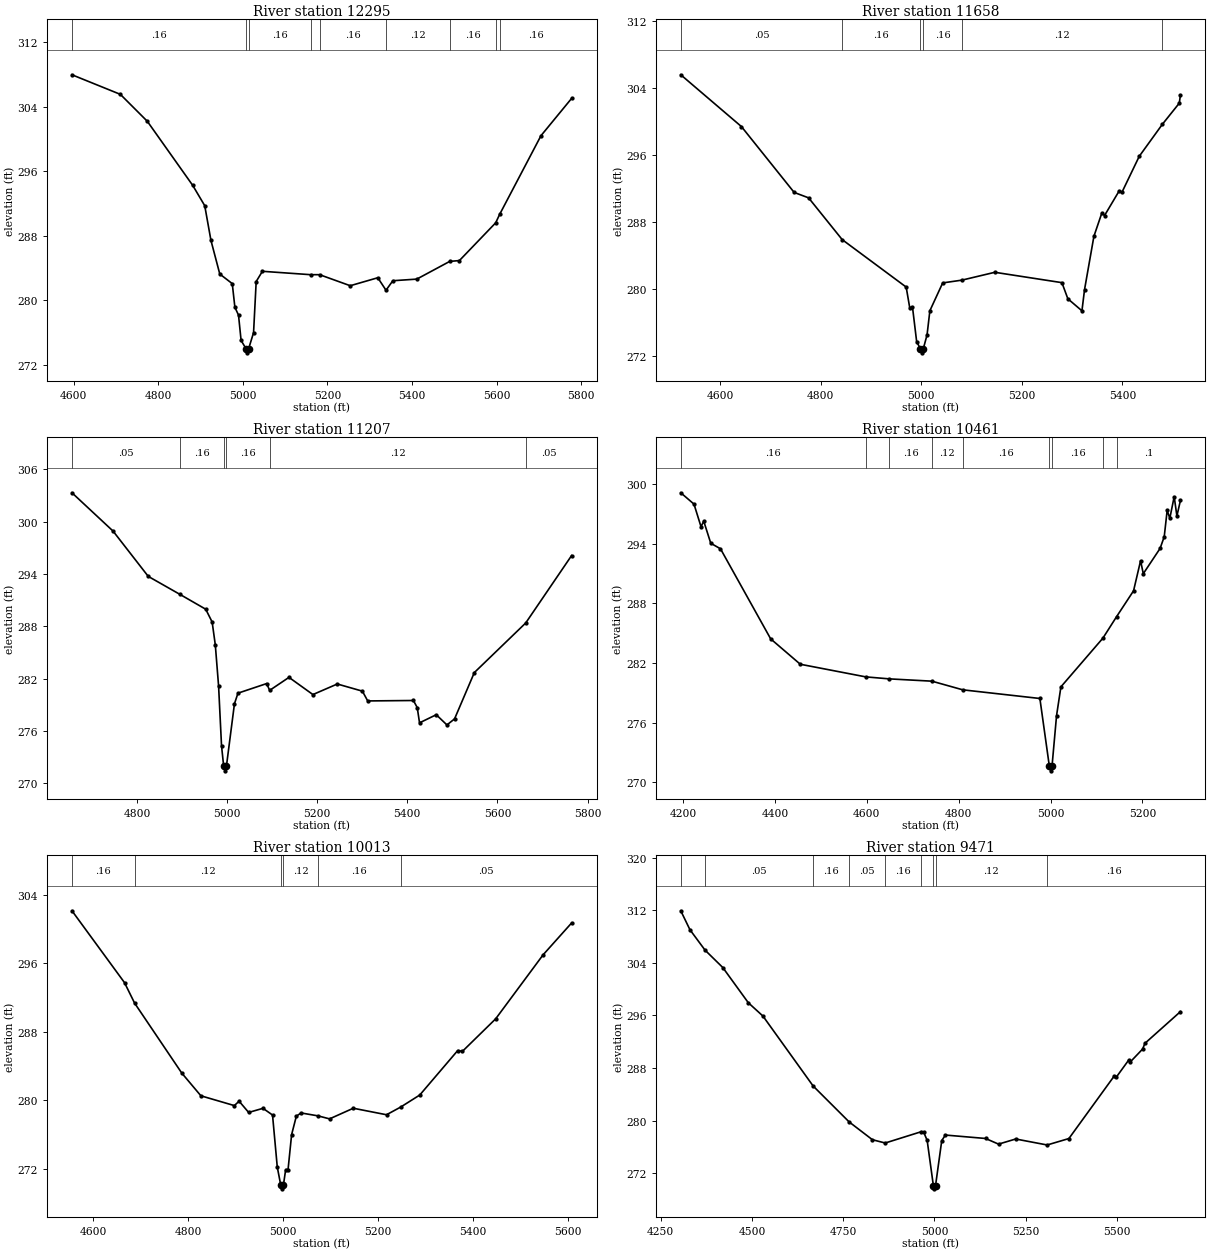
Type RM Length L Ch R = 1,12295,637,637,637
BEGIN DESCRIPTION:
JACK CREEK 19.0
END DESCRIPTION:
XS GIS Cut Line= 3
      3571294.36     10303040.88      3571146.82     10302915.04
      3570342.12     10302341.66
#Sta/Elev= 30
  4595.5  307.97  4710.0  305.54  4773.7  302.20  4881.2  294.24  4909.6  291.72
  4924.3  287.41  4945.2  283.24  4974.7  282.05  4980.9  279.12  4989.5  278.14
  4995.6  275.00  5007.4  273.96  5010.1  273.46  5013.4  273.96  5025.1  275.97
  5031.3  282.31  5046.0  283.58  5159.9  283.16  5181.3  283.16  5253.8  281.79
  5319.0  282.78  5338.4  281.23  5354.6  282.41  5411.2  282.61  5489.2  284.81
  5512.0  284.91  5597.9  289.60  5607.2  290.64  5705.0  300.41  5777.5  305.04
#Mann=9,-1,0
  4595.5    0.16       0  5007.4    0.07       0  5013.4    0.16       0
  5159.9    0.05       0  5181.3    0.16       0  5338.4    0.12       0
  5489.2    0.16       0  5597.9    0.12       0  5607.2    0.16       0
Bank Sta=5007.4,5013.4
Exp/Cntr=0.3,0.1

Type RM Length L Ch R = 1,11658,451,451,451
BEGIN DESCRIPTION:
JACK CREEK 18.0
END DESCRIPTION:
XS GIS Cut Line= 3
      3571342.12     10302459.30      3570955.13     10302285.39
      3570406.16     10302135.67
#Sta/Elev= 30
  4522.0  305.62  4642.6  299.42  4747.4  291.54  4776.1  290.89  4842.9  285.89
  4970.1  280.21  4977.4  277.65  4982.6  277.84  4990.9  273.69  4998.2  272.84
  5001.0  272.34  5004.2  272.84  5011.6  274.49  5017.2  277.38  5042.7  280.71
  5080.8  281.04  5146.3  281.98  5279.7  280.74  5291.5  278.81  5319.5  277.37
  5324.7  279.92  5343.3  286.29  5359.2  289.10  5364.4  288.77  5393.8  291.75
  5398.9  291.54  5433.5  295.87  5479.6  299.71  5513.0  302.22  5515.3  303.19
#Mann=6,-1,0
  4522.0    0.05       0  4842.9    0.16       0  4998.2    0.07       0
  5004.2    0.16       0  5080.8    0.12       0  5479.6    0.16       0
Bank Sta=4998.2,5004.2
Exp/Cntr=0.3,0.1

Type RM Length L Ch R = 1,11207,746,746,746
BEGIN DESCRIPTION:
JACK CREEK 17.0
END DESCRIPTION:
XS GIS Cut Line= 3
      3571446.32     10302285.72      3571124.57     10301900.67
      3570525.81     10301800.88
#Sta/Elev= 30
  4655.9  303.31  4747.1  298.92  4825.2  293.73  4895.1  291.68  4952.7  289.97
  4967.0  288.50  4974.0  285.88  4981.3  281.16  4987.8  274.33  4992.6  271.95
  4995.4  271.45  4998.6  271.95  5016.5  279.14  5024.3  280.35  5088.0  281.45
  5094.6  280.67  5137.5  282.16  5190.6  280.19  5244.7  281.40  5300.4  280.58
  5312.2  279.46  5413.6  279.51  5422.1  278.70  5427.2  276.95  5464.3  277.88
  5488.0  276.71  5504.9  277.40  5548.8  282.71  5662.8  288.39  5764.7  296.12
#Mann=6,-1,0
  4655.9    0.05       0  4895.1    0.16       0  4992.6    0.07       0
  4998.6    0.16       0  5094.6    0.12       0  5662.8    0.05       0
Bank Sta=4992.6,4998.6
Exp/Cntr=0.3,0.1

Type RM Length L Ch R = 1,10461,448,448,448
BEGIN DESCRIPTION:
JACK CREEK 15.0
END DESCRIPTION:
XS GIS Cut Line= 3
      3571742.11     10302041.65      3571446.30     10301573.89
      3570992.10     10301291.64
#Sta/Elev= 30
  4194.7  299.11  4223.5  297.97  4238.8  295.70  4244.7  296.26  4260.0  294.04
  4281.2  293.48  4390.5  284.43  4455.0  281.88  4597.7  280.61  4649.0  280.41
  4741.6  280.18  4808.9  279.31  4976.8  278.44  4997.3  271.67  5000.1  271.17
  5003.3  271.67  5013.1  276.72  5022.6  279.61  5114.0  284.50  5143.8  286.66
  5180.8  289.26  5196.1  292.28  5202.0  290.98  5238.6  293.52  5247.6  294.69
  5254.0  297.34  5259.8  296.55  5269.3  298.72  5275.2  296.78  5282.9  298.34
#Mann=9,-1,0
  4194.7    0.16       0  4597.7    0.12       0  4649.0    0.16       0
  4741.6    0.12       0  4808.9    0.16       0  4997.3    0.07       0
  5003.3    0.16       0  5114.0    0.05       0  5143.8     0.1       0
Bank Sta=4997.3,5003.3
Exp/Cntr=0.3,0.1

Type RM Length L Ch R = 1,10013,542,542,542
BEGIN DESCRIPTION:
JACK CREEK 14.0
END DESCRIPTION:
XS GIS Cut Line= 3
      3571992.10     10301141.64      3571542.11     10301191.64
      3570942.07     10301191.64
#Sta/Elev= 30
  4554.8  302.11  4665.5  293.73  4686.8  291.34  4786.2  283.18  4826.5  280.53
  4896.9  279.39  4907.0  279.90  4927.1  278.59  4957.3  279.07  4977.4  278.29
  4987.4  272.22  4994.5  270.18  4997.3  269.68  5000.5  270.18  5005.1  271.92
  5010.1  271.92  5017.6  276.00  5027.6  278.16  5037.6  278.53  5073.3  278.19
  5097.6  277.84  5147.6  279.08  5217.6  278.32  5247.5  279.22  5287.6  280.62
  5367.6  285.81  5377.6  285.72  5447.6  289.51  5547.6  296.98  5607.6  300.69
#Mann=6,-1,0
  4554.8    0.16       0  4686.8    0.12       0  4994.5    0.07       0
  5000.5    0.12       0  5073.3    0.16       0  5247.5    0.05       0
Bank Sta=4994.5,5000.5
Exp/Cntr=0.3,0.1

Type RM Length L Ch R = 1,9471,2110,2110,2110
BEGIN DESCRIPTION:
JACK CREEK 13.0
END DESCRIPTION:
XS GIS Cut Line= 3
      3572197.19     10300671.12      3571346.48     10300671.12
      3570848.68     10300815.78
#Sta/Elev= 30
  4304.9  311.90  4330.0  309.02  4371.3  305.92  4420.0  303.27  4490.0  297.91
  4530.0  295.89  4667.6  285.25  4766.4  279.78  4830.0  277.08  4865.1  276.58
  4963.9  278.30  4970.0  278.28  4980.0  276.99  4997.0  270.11  4999.7  269.61
  5003.0  270.11  5020.0  276.95  5030.0  277.79  5140.0  277.27  5175.6  276.41
  5222.6  277.19  5308.8  276.28  5368.4  277.26  5493.1  286.81  5498.3  286.60
  5531.8  289.16  5537.0  288.93  5570.5  290.88  5576.7  291.74  5674.0  296.56
#Mann=9,-1,0
  4304.9     0.1       0  4371.3    0.05       0  4667.6    0.16       0
  4766.4    0.05       0  4865.1    0.16       0  4963.9    0.12       0
  4997.0    0.07       0  5003.0    0.12       0  5308.8    0.16       0
Bank Sta=4997,5003
Exp/Cntr=0.3,0.1