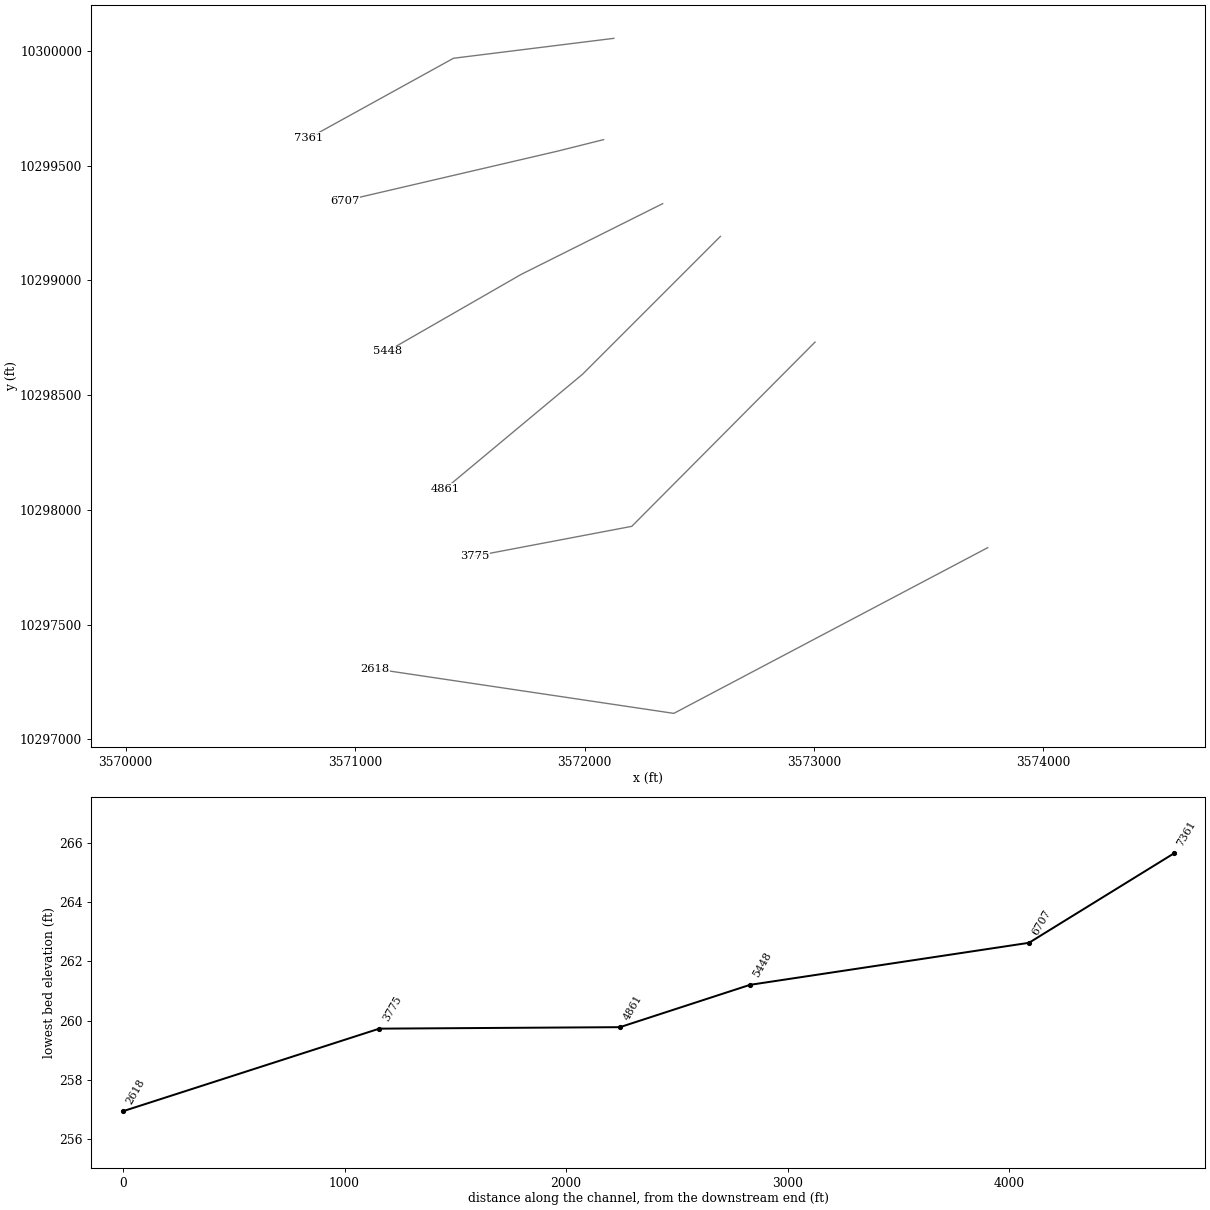
HEC-RAS study JACK CREEK.prj: JACK CREEK Base Level Engineering

--- JACK CREEK.g01 (geometry) --- (continued)

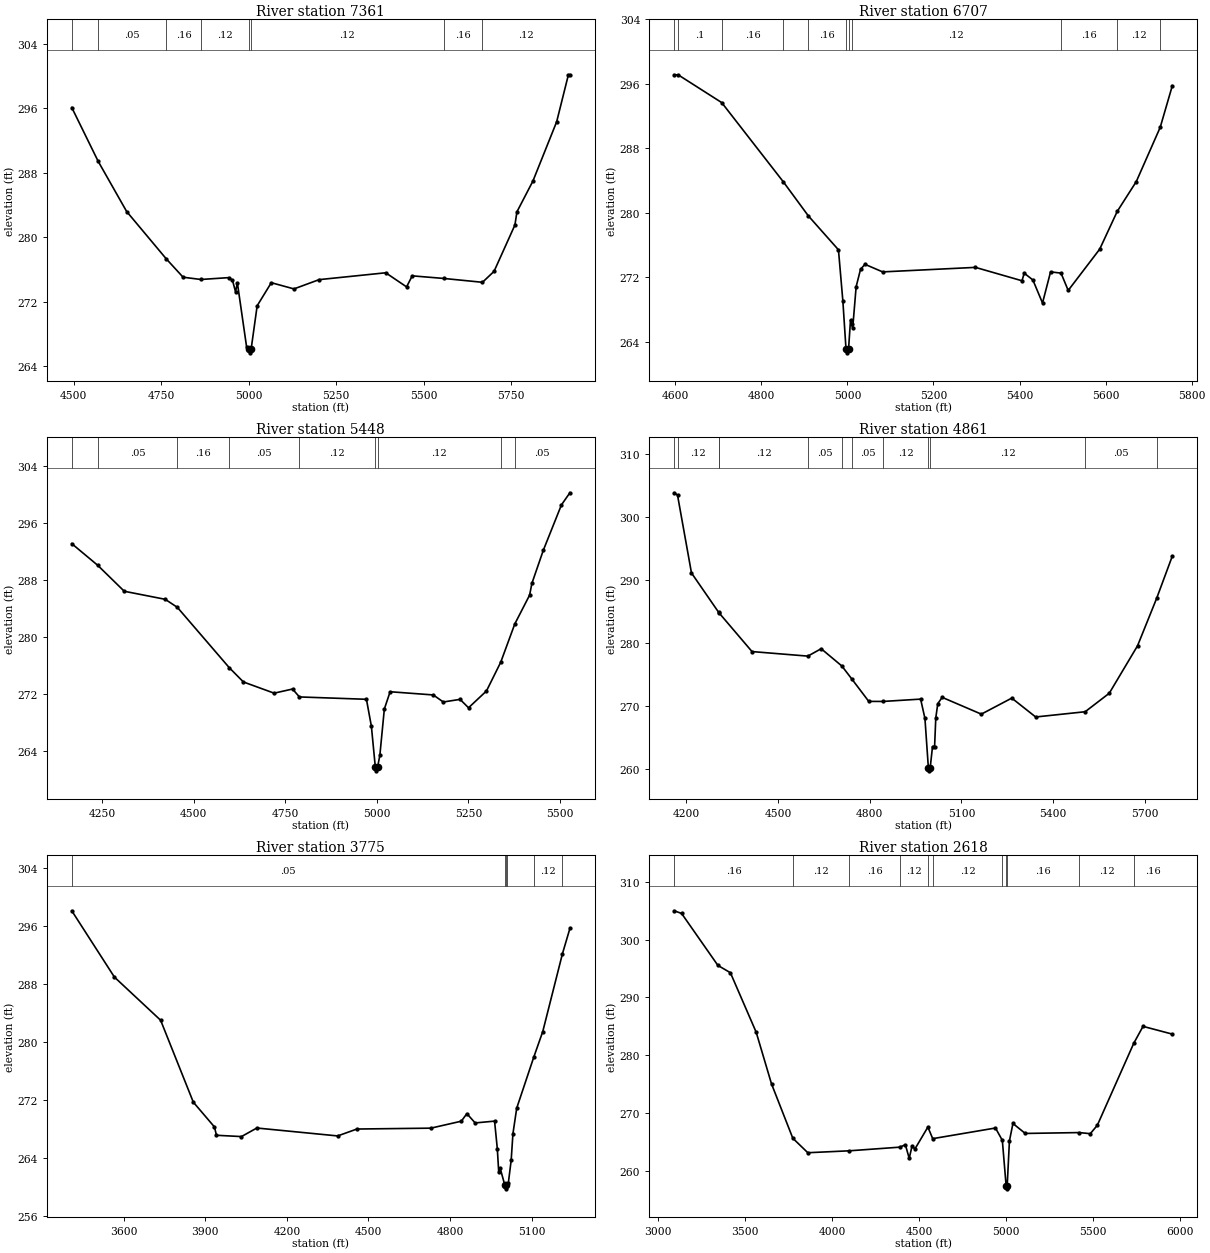
Type RM Length L Ch R = 1,7361,654,654,654
BEGIN DESCRIPTION:
JACK CREEK 11.0
END DESCRIPTION:
XS GIS Cut Line= 3
      3572127.71     10300054.79      3571428.94     10299967.99
      3570799.61     10299620.78
#Sta/Elev= 30
  4494.7  296.08  4570.2  289.40  4651.5  283.18  4764.4  277.32  4812.7  275.03
  4863.4  274.75  4943.7  274.98  4953.8  274.64  4962.6  273.22  4967.7  274.35
  4994.1  266.39  5001.2  266.15  5003.9  265.65  5007.2  266.15  5024.3  271.49
  5064.7  274.35  5129.4  273.58  5201.3  274.73  5391.5  275.58  5451.1  273.83
  5467.2  275.20  5556.6  274.88  5667.9  274.40  5701.0  275.76  5760.6  281.51
  5766.3  283.14  5812.0  286.96  5879.8  294.31  5913.3  300.14  5917.6  300.14
#Mann=8,-1,0
  4494.7    0.16       0  4570.2    0.05       0  4764.4    0.16       0
  4863.4    0.12       0  5001.2    0.07       0  5007.2    0.12       0
  5556.6    0.16       0  5667.9    0.12       0
Bank Sta=5001.2,5007.2
Exp/Cntr=0.3,0.1

Type RM Length L Ch R = 1,6707,1259,1259,1259
BEGIN DESCRIPTION:
JACK CREEK 9.0
END DESCRIPTION:
XS GIS Cut Line= 3
      3572083.08     10299613.34      3571883.08     10299563.34
      3570956.45     10299347.47
#Sta/Elev= 30
  4597.5  297.12  4607.1  297.10  4707.9  293.67  4851.4  283.82  4909.2  279.62
  4979.2  275.41  4989.5  269.02  4996.7  263.13  4999.5  262.63  5002.7  263.13
  5007.2  266.69  5009.7  266.20  5012.3  265.70  5020.3  270.83  5030.5  272.99
  5040.8  273.61  5081.9  272.67  5297.5  273.23  5405.7  271.57  5410.9  272.51
  5431.0  271.67  5453.4  268.81  5472.1  272.67  5496.4  272.52  5513.1  270.37
  5586.3  275.49  5627.0  280.17  5671.4  283.88  5726.9  290.60  5755.1  295.77
#Mann=11,-1,0
  4597.5    0.05       0  4607.1     0.1       0  4707.9    0.16       0
  4851.4    0.05       0  4909.2    0.16       0  4996.7    0.07       0
  5002.7    0.16       0  5009.7    0.12       0  5496.4    0.16       0
  5627.0    0.12       0  5726.9    0.16       0
Bank Sta=4996.7,5002.7
Exp/Cntr=0.3,0.1

Type RM Length L Ch R = 1,5448,587,587,587
BEGIN DESCRIPTION:
JACK CREEK 7.0
END DESCRIPTION:
XS GIS Cut Line= 3
      3572340.37     10299334.30      3571724.08     10299026.15
      3571142.10     10298691.64
#Sta/Elev= 30
  4166.8  293.09  4237.3  290.07  4310.2  286.41  4422.0  285.28  4455.2  284.15
  4597.0  275.68  4635.6  273.68  4719.4  272.11  4769.7  272.69  4788.5  271.58
  4971.5  271.25  4985.0  267.47  4995.8  261.71  4998.6  261.21  5001.8  261.71
  5008.1  263.37  5020.4  269.89  5036.2  272.31  5154.0  271.86  5181.4  270.87
  5227.2  271.24  5250.3  270.06  5299.3  272.42  5338.2  276.45  5376.6  281.82
  5417.1  285.87  5423.3  287.51  5454.5  292.16  5504.0  298.53  5527.1  300.23
#Mann=9,-1,0
  4166.8    0.16       0  4237.3    0.05       0  4455.2    0.16       0
  4597.0    0.05       0  4788.5    0.12       0  4995.8    0.07       0
  5001.8    0.12       0  5338.2    0.16       0  5376.6    0.05       0
Bank Sta=4995.8,5001.8
Exp/Cntr=0.3,0.1

Type RM Length L Ch R = 1,4861,1086,1086,1086
BEGIN DESCRIPTION:
JACK CREEK 6.0
END DESCRIPTION:
XS GIS Cut Line= 3
      3572592.08     10299191.62      3571992.11     10298591.64
      3571392.12     10298091.66
#Sta/Elev= 30
  4160.3  303.82  4171.1  303.46  4216.8  291.12  4305.5  284.90  4308.2  284.73
  4414.8  278.67  4597.4  277.95  4641.1  279.12  4708.6  276.39  4741.9  274.29
  4796.7  270.78  4843.0  270.77  4966.4  271.14  4980.5  268.08  4991.7  260.28
  4994.4  259.78  4997.7  260.28  5005.3  263.63  5012.1  263.63  5016.0  268.17
  5022.5  270.41  5036.8  271.42  5165.0  268.76  5264.6  271.30  5342.7  268.31
  5504.6  269.14  5583.5  272.07  5675.9  279.58  5738.7  287.13  5789.8  293.80
#Mann=12,-1,0
  4160.3    0.05       0  4171.1    0.12       0  4305.5    0.05       0
  4308.2    0.12       0  4597.4    0.05       0  4708.6    0.16       0
  4741.9    0.05       0  4843.0    0.12       0  4991.7    0.07       0
  4997.7    0.12       0  5504.6    0.05       0  5738.7    0.16       0
Bank Sta=4991.7,4997.7
Exp/Cntr=0.3,0.1

Type RM Length L Ch R = 1,3775,1157,1157,1157
BEGIN DESCRIPTION:
JACK CREEK 5.0
END DESCRIPTION:
XS GIS Cut Line= 3
      3573004.49     10298731.04      3572205.85     10297928.06
      3571520.12     10297797.86
#Sta/Elev= 30
  3409.7  298.04  3566.5  288.90  3736.2  282.96  3856.4  271.67  3934.2  268.25
  3941.3  267.11  4033.2  266.93  4089.8  268.11  4386.8  267.02  4457.5  267.97
  4729.2  268.09  4841.2  269.05  4861.6  270.09  4892.1  268.81  4963.4  269.06
  4973.5  265.26  4978.7  262.01  4983.7  262.61  5001.1  260.23  5003.8  259.73
  5007.1  260.23  5007.8  260.27  5014.2  260.59  5024.4  263.65  5030.9  267.33
  5044.8  270.85  5107.6  277.89  5140.5  281.40  5212.8  292.12  5240.2  295.60
#Mann=6,-1,0
  3409.7    0.05       0  5001.1   0.035       0  5007.1    0.05       0
  5007.8    0.16       0  5107.6    0.12       0  5212.8    0.16       0
Bank Sta=5001.1,5007.1
Exp/Cntr=0.3,0.1

Type RM Length L Ch R = 1,2618,0,0,0
BEGIN DESCRIPTION:
JACK CREEK 1.0
END DESCRIPTION:
XS GIS Cut Line= 3
      3573757.10     10297835.20      3572389.01     10297112.96
      3571085.32     10297307.12
#Sta/Elev= 30
  3091.6  304.98  3134.1  304.52  3343.0  295.54  3414.7  294.28  3563.1  284.00
  3651.3  275.07  3773.8  265.68  3860.1  263.18  4097.9  263.51  4388.9  264.14
  4421.2  264.56  4443.3  262.21  4459.6  264.34  4476.0  263.82  4550.6  267.61
  4578.5  265.61  4939.5  267.45  4978.9  265.32  5000.8  257.44  5003.5  256.94
  5006.8  257.44  5019.7  265.22  5039.9  268.23  5110.7  266.51  5421.3  266.66
  5484.8  266.47  5525.2  267.92  5735.0  282.10  5788.1  285.01  5956.7  283.67
#Mann=11,-1,0
  3091.6    0.16       0  3773.8    0.12       0  4097.9    0.16       0
  4388.9    0.12       0  4550.6    0.16       0  4578.5    0.12       0
  4978.9    0.16       0  5000.8    0.07       0  5006.8    0.16       0
  5421.3    0.12       0  5735.0    0.16       0
Bank Sta=5000.8,5006.8
Exp/Cntr=0.3,0.1

Chan Stop Cuts=-1