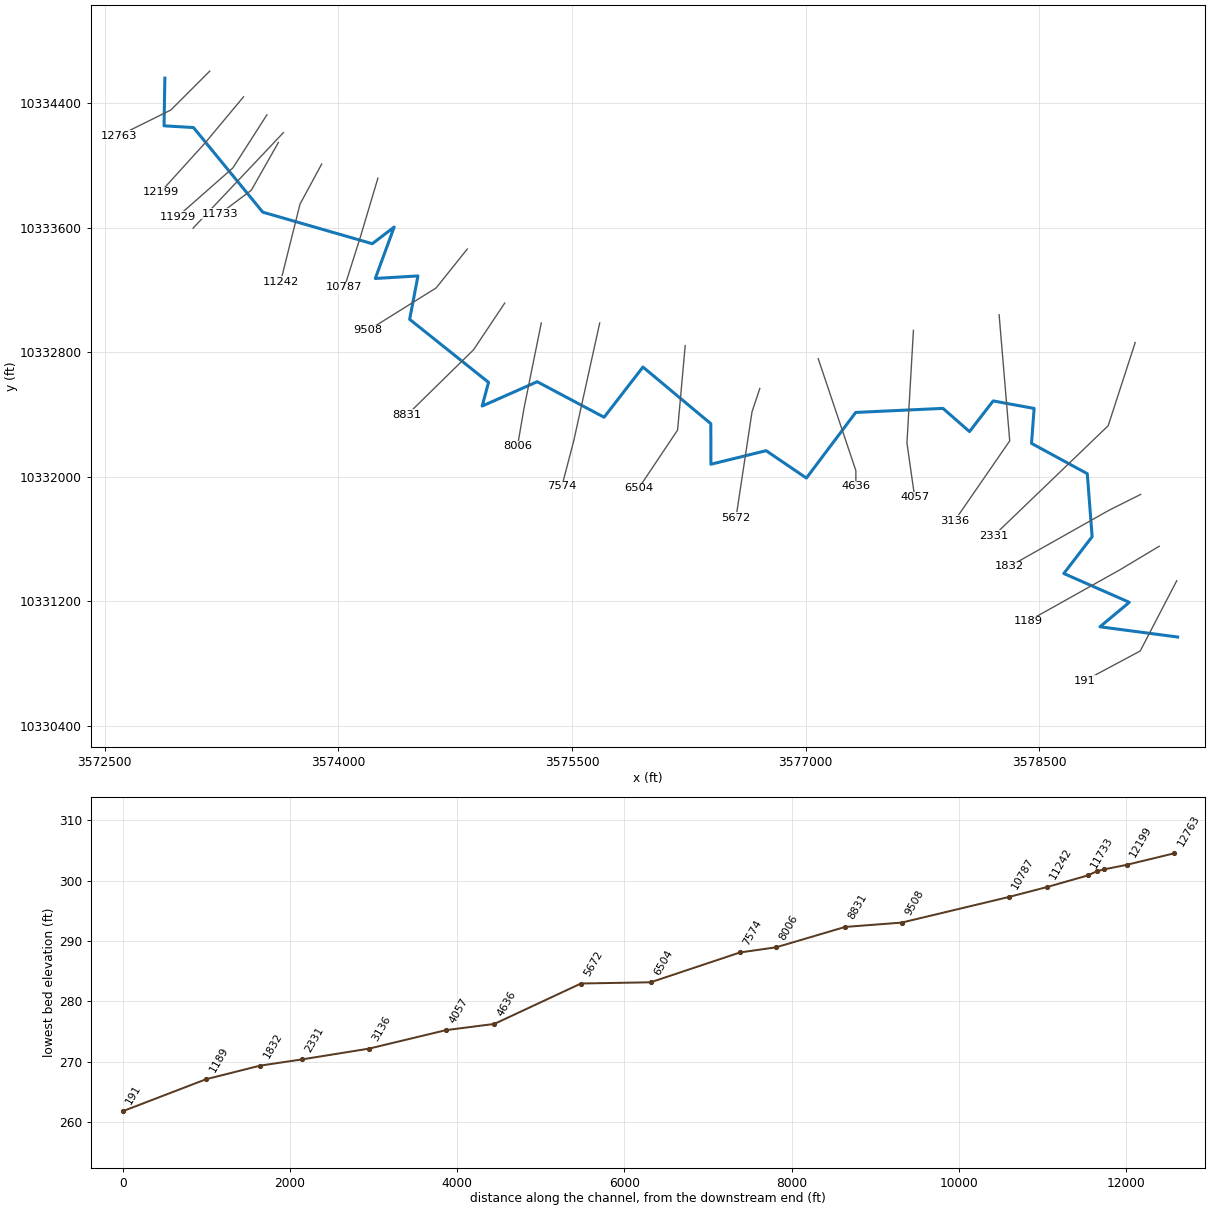
--- LITTLE CEDAR CREEK TRIBUTARY 1.prj (project) ---

Proj Title=LITTLE CEDAR CREEK TRIBUTARY 1 Base Level Engineering
Current Plan=p01
Default Exp/Contr=0.3,0.1
English Units
Geom File=g01
Flow File=f01
Plan File=p01
BEGIN DESCRIPTION:
LITTLE CEDAR CREEK TRIBUTARY 1
END DESCRIPTION:

--- LITTLE CEDAR CREEK TRIBUTARY 1.p01 (plan) ---

Plan Title=Multiple Run
Short Identifier=Multiple
Geom File=g01
Flow File=f01
Subcritical Flow
K Sum by GR= 0
Std Step Tol= 0.01
Critical Tol= 0.01
Num of Std Step Trials= 20
Max Error Tol= 0.3
Flow Tol Ratio= 0.001
Split Flow NTrial= 30
Split Flow Tol= 0.02
Split Flow Ratio= 0.02
Log Output Level= 0
Friction Slope Method= 1
Unsteady Friction Slope Method= 2
Unsteady Bridges Friction Slope Method= 1
Parabolic Critical Depth
Global Vel Dist=  1 , 1 , 1
Global Log Level= 0
CheckData=True
Encroach Param= -1, 0, 0, 0
BEGIN DESCRIPTION:
Multiple Run
END DESCRIPTION:

--- LITTLE CEDAR CREEK TRIBUTARY 1.f01 (steady flow) ---

Flow Title=Multiple
Number of Profiles=7
Profile Names=10-year,25-year,50-year,1pct_min,100-year,1pct_plu,500-year
River Rch & RM= LITTLE CEDAR CRE,Reach-1,12763
     533     712     857     756    1022    1383    1458
River Rch & RM= LITTLE CEDAR CRE,Reach-1,4057
     638     861    1043     926    1252    1693    1806
Boundary for River Rch & Prof#=LITTLE CEDAR CRE,Reach-1,1
Up Type=0
Dn Type=3
Dn Slope=0.005
Boundary for River Rch & Prof#=LITTLE CEDAR CRE,Reach-1,2
Up Type=0
Dn Type=3
Dn Slope=0.005
Boundary for River Rch & Prof#=LITTLE CEDAR CRE,Reach-1,3
Up Type=0
Dn Type=3
Dn Slope=0.005
Boundary for River Rch & Prof#=LITTLE CEDAR CRE,Reach-1,4
Up Type=0
Dn Type=3
Dn Slope=0.005
Boundary for River Rch & Prof#=LITTLE CEDAR CRE,Reach-1,5
Up Type=0
Dn Type=3
Dn Slope=0.005
Boundary for River Rch & Prof#=LITTLE CEDAR CRE,Reach-1,6
Up Type=0
Dn Type=3
Dn Slope=0.005
Boundary for River Rch & Prof#=LITTLE CEDAR CRE,Reach-1,7
Up Type=0
Dn Type=3
Dn Slope=0.005

--- LITTLE CEDAR CREEK TRIBUTARY 1.g01 (geometry) ---

Geom Title=Existing Conditions

River Reach=LITTLE CEDAR CRE,Reach-1
Reach XY= 30
      3572886.99     10334561.74      3572881.86     10334255.40
      3573070.74     10334244.29      3573515.37     10333700.79
      3574218.75     10333498.14      3574359.02     10333605.22
      3574237.83     10333274.73      3574511.62     10333291.09
      3574458.43     10333012.24      3574964.70     10332607.47
      3574923.87     10332455.31      3575277.06     10332611.60
      3575706.60     10332383.38      3575955.86     10332705.85
      3576391.49     10332341.94      3576392.25     10332081.55
      3576746.44     10332168.68      3577005.05     10331992.71
      3577321.67     10332414.32      3577881.59     10332440.41
      3578052.20     10332291.33      3578203.83     10332488.22
      3578466.81     10332439.97      3578450.14     10332215.53
      3578807.90     10332020.92      3578839.33     10331616.53
      3578657.38     10331379.64      3579077.82     10331194.67
      3578889.47     10331037.40      3579388.27     10330971.64

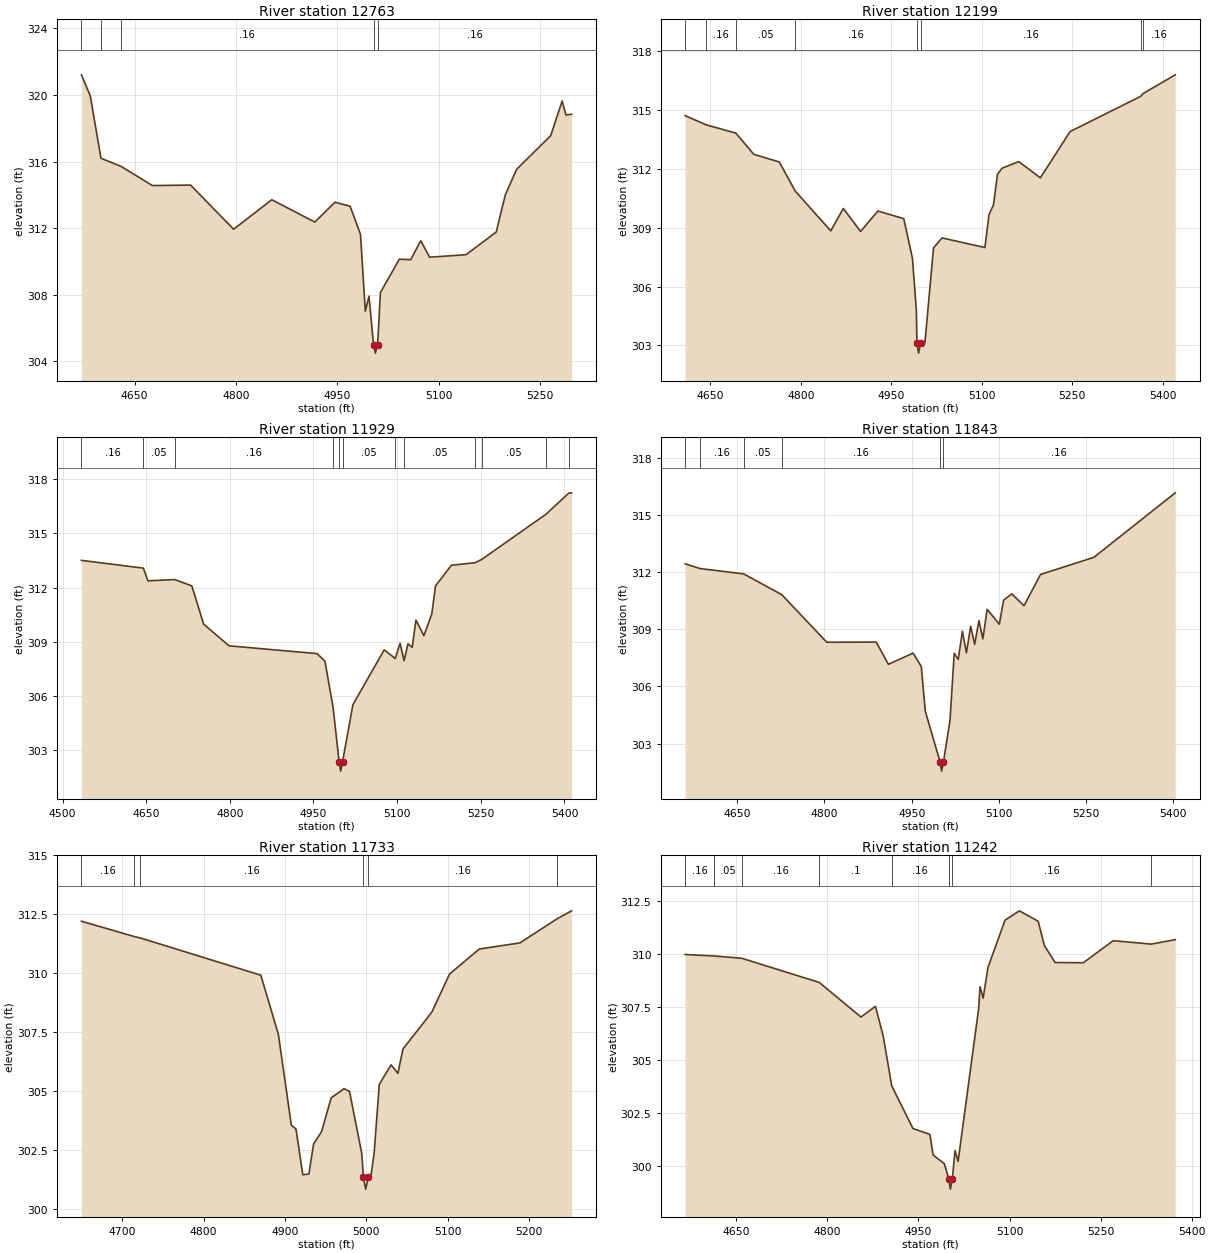
Type RM Length L Ch R = 1,12763,564,564,564
BEGIN DESCRIPTION:
LITTLE CEDAR CREEK TRIBUTARY 1 24.0
END DESCRIPTION:
XS GIS Cut Line= 3
      3573175.42     10334606.90      3572925.44     10334356.92
      3572592.09     10334191.64
#Sta/Elev= 30
  4571.4  321.21  4584.5  319.95  4600.3  316.20  4630.2  315.71  4676.5  314.56
  4733.0  314.59  4796.7  311.94  4853.2  313.71  4916.9  312.37  4946.7  313.56
  4969.1  313.32  4984.5  311.63  4991.6  307.02  4997.1  307.92  5003.8  305.00
  5006.5  304.50  5009.8  305.00  5014.0  308.14  5042.0  310.14  5058.8  310.11
  5073.7  311.25  5086.8  310.26  5140.7  310.41  5185.4  311.77  5198.9  314.01
  5215.7  315.54  5266.1  317.56  5283.0  319.64  5288.6  318.80  5297.0  318.84
#Mann=5,-1,0
  4571.4    0.16       0  4600.3    0.05       0  4630.2    0.16       0
  5003.8    0.07       0  5009.8    0.16       0
Bank Sta=5003.8,5009.8
Exp/Cntr=0.3,0.1

Type RM Length L Ch R = 1,12199,270,270,270
BEGIN DESCRIPTION:
LITTLE CEDAR CREEK TRIBUTARY 1 23.0
END DESCRIPTION:
XS GIS Cut Line= 3
      3573392.12     10334441.66      3573142.11     10334141.64
      3572858.80     10333828.91
#Sta/Elev= 30
  4608.1  314.71  4643.3  314.24  4692.3  313.82  4722.0  312.74  4764.3  312.35
  4790.6  310.87  4849.6  308.84  4870.4  309.98  4899.0  308.81  4927.7  309.85
  4970.6  309.46  4985.0  307.44  4991.5  304.77  4992.4  303.11  4995.1  302.61
  4998.4  303.11  5005.7  303.15  5019.9  307.97  5034.1  308.48  5105.1  307.99
  5111.8  309.66  5119.3  310.17  5126.0  311.73  5133.5  312.03  5161.2  312.37
  5197.0  311.54  5246.3  313.90  5363.1  315.69  5367.5  315.84  5420.6  316.79
#Mann=8,-1,0
  4608.1    0.05       0  4643.3    0.16       0  4692.3    0.05       0
  4790.6    0.16       0  4992.4    0.07       0  4998.4    0.16       0
  5363.1    0.05       0  5367.5    0.16       0
Bank Sta=4992.4,4998.4
Exp/Cntr=0.3,0.1

Type RM Length L Ch R = 1,11929,86,86,86
BEGIN DESCRIPTION:
Mapping XS c24236d9
END DESCRIPTION:
XS GIS Cut Line= 3
      3573542.16     10334325.99      3573324.07     10333985.28
      3572968.15     10333671.68
#Sta/Elev= 30
  4533.9  313.50  4644.9  313.07  4653.2  312.37  4701.2  312.44  4731.9  312.09
  4753.0  309.98  4798.6  308.78  4956.3  308.35  4970.5  307.94  4985.2  305.36
  4996.0  302.36  4998.7  301.86  5002.0  302.36  5020.7  305.53  5076.8  308.56
  5096.5  308.08  5105.2  308.92  5112.5  307.96  5119.4  308.89  5127.0  308.70
  5133.7  310.20  5147.9  309.34  5162.1  310.54  5168.8  312.09  5197.2  313.23
  5239.7  313.37  5252.0  313.56  5367.0  316.05  5407.5  317.21  5412.8  317.23
#Mann=12,-1,0
  4533.9    0.16       0  4644.9    0.05       0  4701.2    0.16       0
  4985.2    0.05       0  4996.0    0.04       0  5002.0    0.05       0
  5096.5    0.16       0  5112.5    0.05       0  5239.7    0.16       0
  5252.0    0.05       0  5367.0    0.16       0  5407.5    0.05       0
Bank Sta=4996,5002
Exp/Cntr=0.3,0.1

Type RM Length L Ch R = 1,11843,110,110,110
BEGIN DESCRIPTION:
Mapping XS 1f285812
END DESCRIPTION:
XS GIS Cut Line= 2
      3573647.42     10334210.98      3573067.96     10333597.88
#Sta/Elev= 30
  4560.1  312.44  4586.2  312.19  4661.1  311.91  4726.5  310.82  4804.0  308.32
  4889.0  308.33  4910.0  307.16  4952.5  307.75  4966.6  307.05  4973.5  304.70
  4998.8  302.05  5001.6  301.55  5004.8  302.05  5016.0  304.20  5023.3  307.74
  5030.2  307.42  5037.4  308.90  5044.3  307.77  5051.6  309.16  5058.5  308.21
  5065.8  309.46  5072.6  308.50  5079.9  310.05  5101.0  309.27  5108.2  310.53
  5122.4  310.86  5143.4  310.24  5171.8  311.88  5263.6  312.78  5403.7  316.17
#Mann=6,-1,0
  4560.1    0.05       0  4586.2    0.16       0  4661.1    0.05       0
  4726.5    0.16       0  4998.8    0.07       0  5004.8    0.16       0
Bank Sta=4998.8,5004.8
Exp/Cntr=0.3,0.1

Type RM Length L Ch R = 1,11733,491,491,491
BEGIN DESCRIPTION:
LITTLE CEDAR CREEK TRIBUTARY 1 22.0
END DESCRIPTION:
XS GIS Cut Line= 3
      3573615.78     10334148.40      3573442.11     10333841.64
      3573242.11     10333691.65
#Sta/Elev= 30
  4649.8  312.21  4714.6  311.56  4722.2  311.50  4870.3  309.92  4891.9  307.41
  4907.8  303.56  4913.5  303.40  4921.9  301.46  4929.4  301.49  4935.2  302.77
  4944.9  303.28  4956.8  304.72  4972.7  305.11  4979.3  304.99  4994.4  302.36
  4996.4  301.35  4999.2  300.85  5002.4  301.35  5005.4  301.35  5009.6  302.38
  5015.9  305.29  5030.4  306.12  5038.8  305.76  5045.0  306.79  5080.4  308.35
  5102.3  309.97  5138.8  311.03  5188.8  311.29  5234.8  312.32  5252.3  312.65
#Mann=6,-1,0
  4649.8    0.16       0  4714.6     0.1       0  4722.2    0.16       0
  4996.4    0.07       0  5002.4    0.16       0  5234.8    0.05       0
Bank Sta=4996.4,5002.4
Exp/Cntr=0.3,0.1

Type RM Length L Ch R = 1,11242,455,455,455
BEGIN DESCRIPTION:
LITTLE CEDAR CREEK TRIBUTARY 1 21.0
END DESCRIPTION:
XS GIS Cut Line= 3
      3573893.53     10334009.47      3573754.65     10333752.54
      3573629.64     10333252.49
#Sta/Elev= 30
  4565.5  309.99  4613.1  309.92  4659.1  309.81  4786.7  308.67  4855.2  307.04
  4879.1  307.54  4891.6  306.18  4906.0  303.79  4940.9  301.78  4968.9  301.50
  4974.1  300.53  4992.5  300.12  4999.8  299.42  5002.5  298.92  5005.8  299.42
  5010.2  300.74  5015.3  300.23  5049.2  307.45  5051.4  308.47  5056.5  307.93
  5064.6  309.39  5092.6  311.61  5116.2  312.05  5147.1  311.56  5157.4  310.41
  5175.1  309.61  5221.5  309.60  5270.8  310.64  5333.5  310.48  5373.0  310.69
#Mann=8,-1,0
  4565.5    0.16       0  4613.1    0.05       0  4659.1    0.16       0
  4786.7     0.1       0  4906.0    0.16       0  4999.8    0.07       0
  5005.8    0.16       0  5333.5    0.05       0
Bank Sta=4999.8,5005.8
Exp/Cntr=0.3,0.1

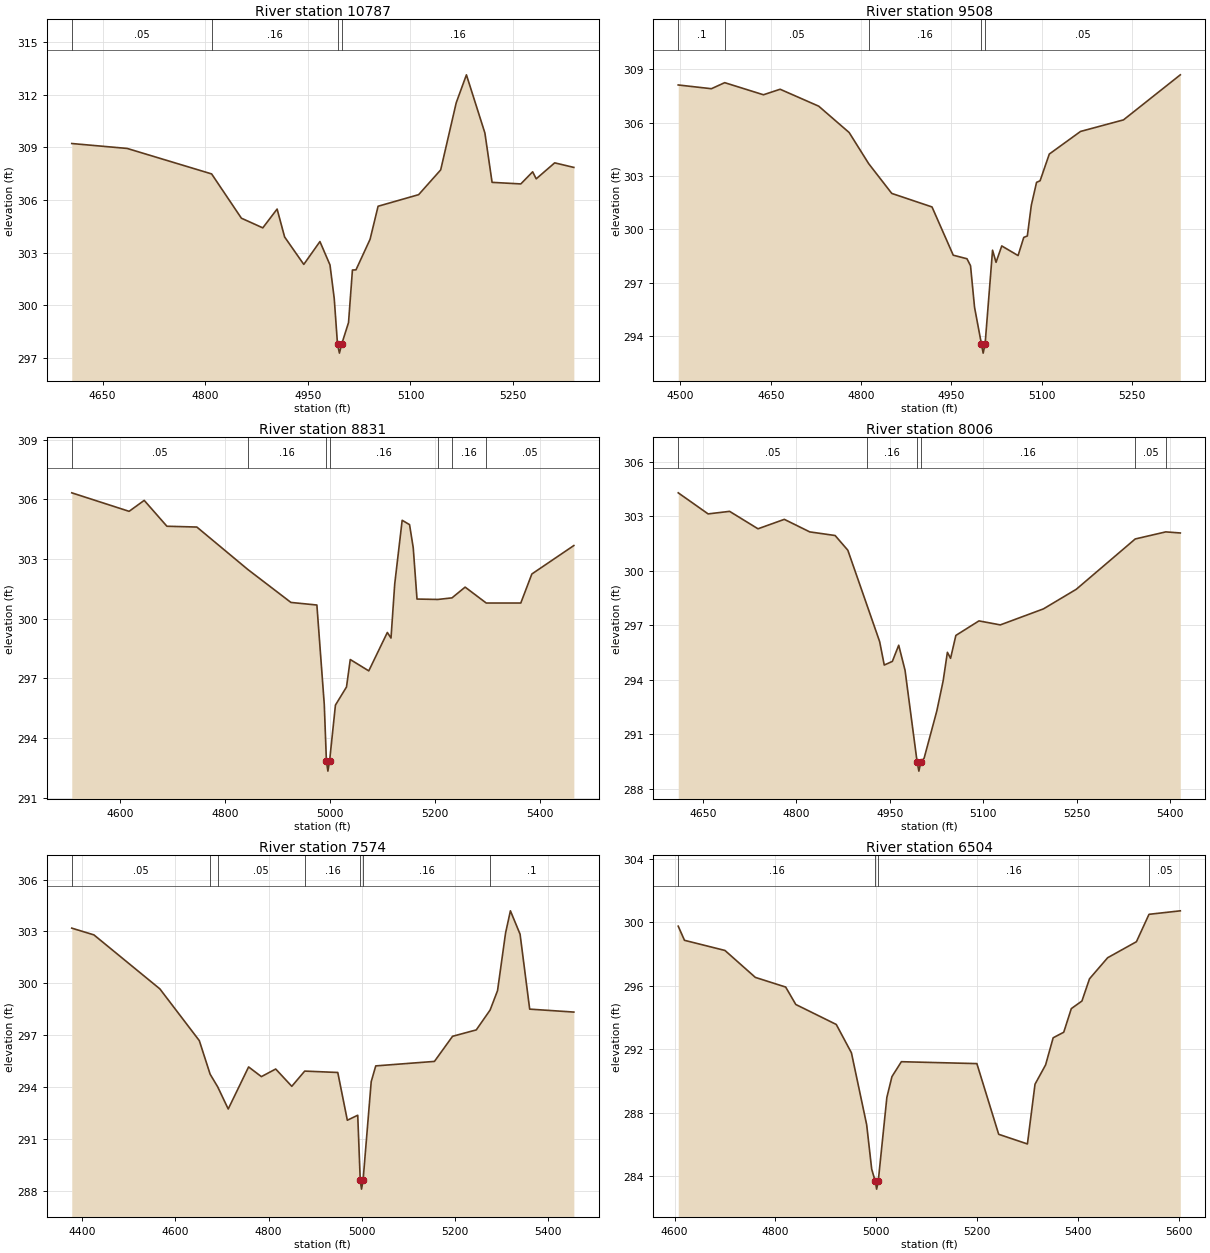
Type RM Length L Ch R = 1,10787,1279,1279,1279
BEGIN DESCRIPTION:
LITTLE CEDAR CREEK TRIBUTARY 1 20.0
END DESCRIPTION:
XS GIS Cut Line= 3
      3574254.66     10333919.24      3574142.11     10333541.64
      3574039.35     10333217.77
#Sta/Elev= 30
  4605.0  309.21  4686.0  308.93  4809.4  307.48  4852.9  304.96  4884.2  304.41
  4905.1  305.48  4916.1  303.89  4944.1  302.33  4967.7  303.63  4982.4  302.30
  4988.6  300.39  4993.4  297.78  4996.2  297.28  4999.4  297.78  5009.5  299.02
  5015.2  302.01  5020.4  302.02  5041.0  303.76  5052.7  305.64  5112.0  306.30
  5144.2  307.71  5166.9  311.53  5181.8  313.12  5208.8  309.81  5219.3  307.00
  5261.3  306.91  5278.6  307.60  5283.8  307.20  5310.8  308.11  5338.8  307.85
#Mann=4,-1,0
  4605.0    0.05       0  4809.4    0.16       0  4993.4    0.07       0
  4999.4    0.16       0
Bank Sta=4993.4,4999.4
Exp/Cntr=0.3,0.1

Type RM Length L Ch R = 1,9508,677,677,677
BEGIN DESCRIPTION:
LITTLE CEDAR CREEK TRIBUTARY 1 18.0
END DESCRIPTION:
XS GIS Cut Line= 3
      3574828.22     10333463.86      3574628.22     10333213.86
      3574192.07     10332941.62
#Sta/Elev= 30
  4496.3  308.11  4551.4  307.90  4573.5  308.24  4637.9  307.56  4665.6  307.87
  4729.7  306.92  4780.3  305.44  4812.8  303.69  4851.1  302.02  4918.0  301.26
  4953.3  298.55  4976.1  298.35  4982.0  297.96  4988.7  295.62  5000.2  293.55
  5003.0  293.05  5006.2  293.55  5018.6  298.83  5024.4  298.15  5033.9  299.07
  5061.0  298.53  5070.5  299.55  5076.4  299.63  5083.0  301.35  5091.7  302.64
  5097.6  302.73  5112.9  304.23  5164.8  305.50  5236.2  306.15  5330.6  308.68
#Mann=5,-1,0
  4496.3     0.1       0  4573.5    0.05       0  4812.8    0.16       0
  5000.2    0.07       0  5006.2    0.05       0
Bank Sta=5000.2,5006.2
Exp/Cntr=0.3,0.1

Type RM Length L Ch R = 1,8831,825,825,825
BEGIN DESCRIPTION:
LITTLE CEDAR CREEK TRIBUTARY 1 16.0
END DESCRIPTION:
XS GIS Cut Line= 3
      3575068.50     10333116.65      3574868.49     10332816.64
      3574442.16     10332398.39
#Sta/Elev= 30
  4507.1  306.32  4616.5  305.39  4645.3  305.94  4688.6  304.64  4745.7  304.60
  4842.8  302.47  4925.2  300.81  4974.7  300.68  4988.8  295.68  4992.9  292.83
  4995.7  292.33  4998.9  292.83  5010.1  295.65  5031.2  296.56  5038.4  297.94
  5073.7  297.37  5109.1  299.30  5116.1  299.02  5123.2  301.74  5137.4  304.94
  5151.5  304.72  5158.5  303.56  5165.7  300.98  5205.6  300.96  5232.5  301.04
  5257.5  301.58  5297.8  300.78  5363.7  300.78  5384.8  302.24  5464.9  303.67
#Mann=7,-1,0
  4507.1    0.05       0  4842.8    0.16       0  4992.9    0.07       0
  4998.9    0.16       0  5205.6    0.05       0  5232.5    0.16       0
  5297.8    0.05       0
Bank Sta=4992.9,4998.9
Exp/Cntr=0.3,0.1

Type RM Length L Ch R = 1,8006,432,432,432
BEGIN DESCRIPTION:
LITTLE CEDAR CREEK TRIBUTARY 1 15.0
END DESCRIPTION:
XS GIS Cut Line= 3
      3575303.26     10332988.66      3575192.15     10332440.04
      3575150.47     10332196.94
#Sta/Elev= 30
  4610.2  304.28  4658.2  303.12  4692.7  303.26  4738.3  302.30  4780.6  302.82
  4821.4  302.13  4862.2  301.93  4882.6  301.12  4913.1  298.12  4933.7  296.09
  4941.1  294.80  4954.1  295.00  4964.3  295.89  4974.5  294.51  4993.9  289.46
  4996.7  288.96  4999.9  289.46  5005.1  289.67  5025.5  292.27  5035.7  293.93
  5042.5  295.50  5047.6  295.17  5056.1  296.43  5093.2  297.23  5127.5  297.01
  5196.7  297.89  5249.5  298.97  5344.2  301.74  5393.3  302.13  5416.6  302.07
#Mann=6,-1,0
  4610.2    0.05       0  4913.1    0.16       0  4993.9    0.07       0
  4999.9    0.16       0  5344.2    0.05       0  5393.3    0.16       0
Bank Sta=4993.9,4999.9
Exp/Cntr=0.3,0.1

Type RM Length L Ch R = 1,7574,1070,1070,1070
BEGIN DESCRIPTION:
LITTLE CEDAR CREEK TRIBUTARY 1 14.0
END DESCRIPTION:
XS GIS Cut Line= 3
      3575678.27     10332988.70      3575511.59     10332231.70
      3575435.21     10331940.07
#Sta/Elev= 30
  4378.1  303.19  4425.6  302.80  4567.0  299.68  4651.6  296.69  4674.8  294.75
  4691.0  294.02  4713.6  292.74  4757.3  295.17  4784.7  294.61  4815.4  295.05
  4849.9  294.05  4877.6  294.93  4948.5  294.85  4969.0  292.09  4991.3  292.38
  4996.7  288.61  4999.4  288.11  5002.7  288.61  5020.2  294.32  5029.9  295.23
  5155.8  295.49  5194.6  296.94  5245.5  297.31  5275.2  298.46  5291.1  299.58
  5308.3  302.91  5318.7  304.19  5339.4  302.84  5360.0  298.51  5454.7  298.34
#Mann=7,-1,0
  4378.1    0.05       0  4674.8    0.16       0  4691.0    0.05       0
  4877.6    0.16       0  4996.7    0.07       0  5002.7    0.16       0
  5275.2     0.1       0
Bank Sta=4996.7,5002.7
Exp/Cntr=0.3,0.1

Type RM Length L Ch R = 1,6504,832,832,832
BEGIN DESCRIPTION:
LITTLE CEDAR CREEK TRIBUTARY 1 12.0
END DESCRIPTION:
XS GIS Cut Line= 3
      3576227.14     10332844.00      3576178.26     10332301.15
      3575927.50     10331925.98
#Sta/Elev= 30
  4607.1  299.76  4619.5  298.87  4699.8  298.23  4760.1  296.53  4820.3  295.92
  4840.4  294.82  4920.7  293.56  4950.8  291.77  4981.0  287.24  4991.0  284.43
  4998.0  283.67  5000.8  283.17  5004.0  283.67  5021.1  288.96  5031.2  290.27
  5049.9  291.21  5199.7  291.09  5243.0  286.63  5300.0  286.02  5315.1  289.79
  5336.1  291.01  5351.1  292.72  5372.1  293.07  5387.1  294.56  5408.2  295.04
  5423.2  296.44  5459.2  297.77  5516.3  298.78  5541.3  300.51  5603.4  300.73
#Mann=4,-1,0
  4607.1    0.16       0  4998.0    0.07       0  5004.0    0.16       0
  5541.3    0.05       0
Bank Sta=4998,5004
Exp/Cntr=0.3,0.1

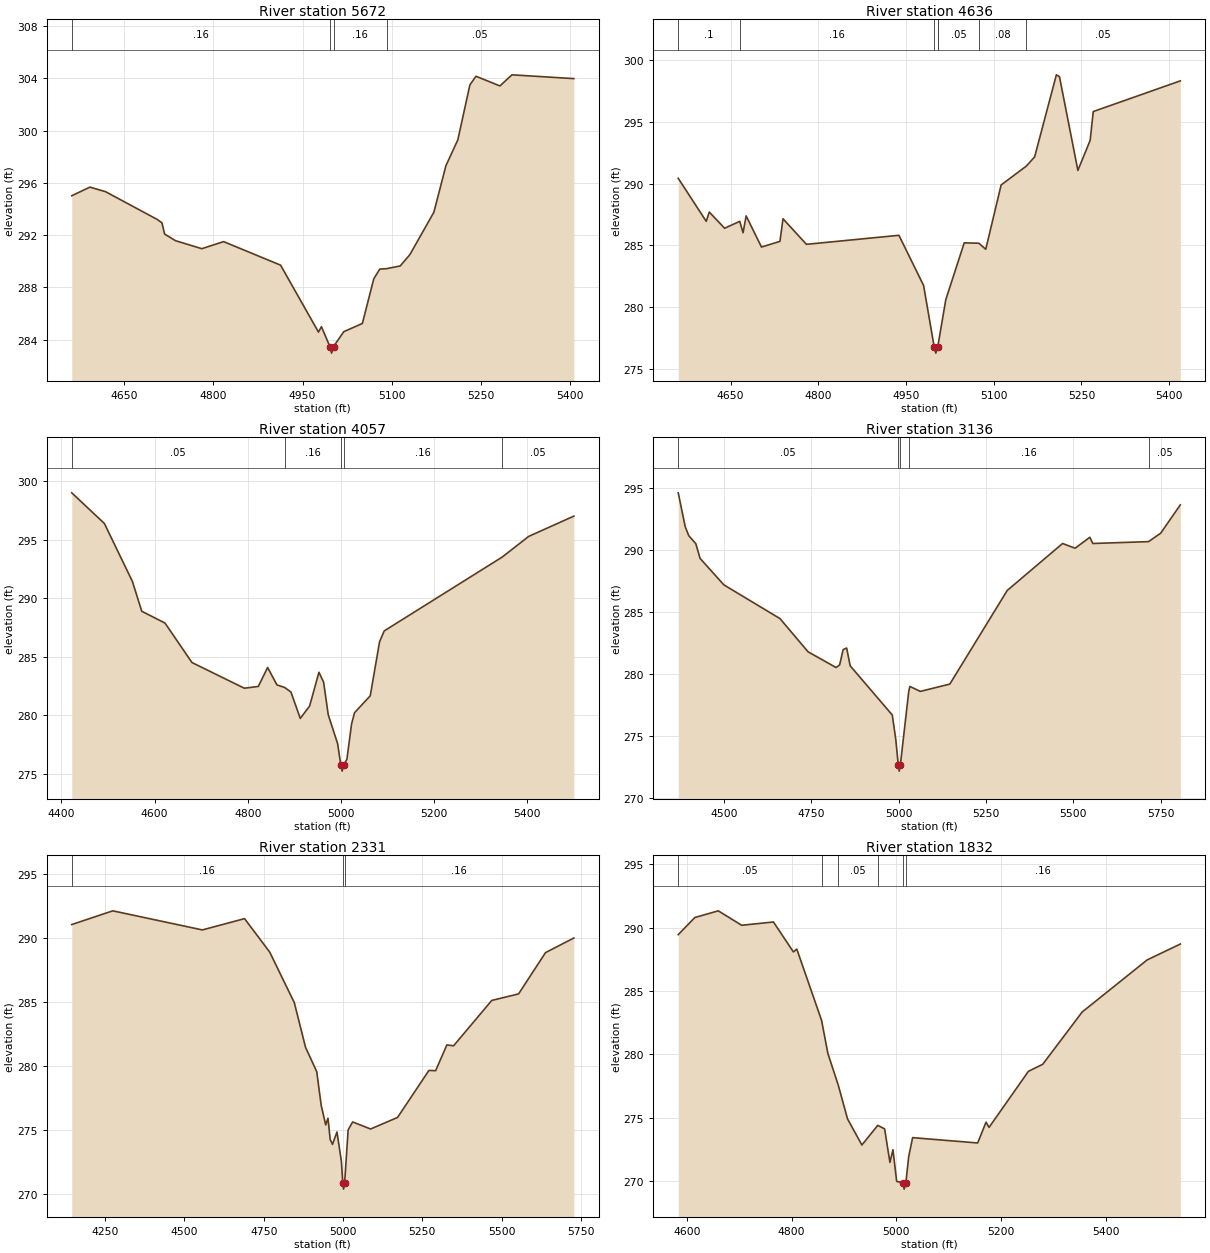
Type RM Length L Ch R = 1,5672,1036,1036,1036
BEGIN DESCRIPTION:
LITTLE CEDAR CREEK TRIBUTARY 1 11.0
END DESCRIPTION:
XS GIS Cut Line= 3
      3576705.99     10332568.01      3576655.99     10332418.03
      3576553.26     10331738.65
#Sta/Elev= 30
  4561.5  295.01  4592.1  295.67  4618.4  295.32  4705.2  293.20  4713.3  292.94
  4717.8  292.08  4736.2  291.57  4780.4  290.96  4817.1  291.50  4913.0  289.70
  4976.8  284.58  4981.8  284.99  4996.1  283.47  4998.9  282.97  5002.1  283.47
  5019.4  284.61  5050.7  285.24  5069.9  288.65  5080.0  289.40  5091.4  289.43
  5114.4  289.64  5130.6  290.50  5171.1  293.75  5191.3  297.30  5211.5  299.30
  5231.7  303.49  5241.9  304.15  5282.3  303.41  5302.5  304.26  5406.7  303.97
#Mann=4,-1,0
  4561.5    0.16       0  4996.1    0.07       0  5002.1    0.16       0
  5091.4    0.05       0
Bank Sta=4996.1,5002.1
Exp/Cntr=0.3,0.1

Type RM Length L Ch R = 1,4636,579,579,579
BEGIN DESCRIPTION:
LITTLE CEDAR CREEK TRIBUTARY 1 9.0
END DESCRIPTION:
XS GIS Cut Line= 3
      3577081.02     10332759.52      3577322.66     10332040.25
      3577322.66     10331940.22
#Sta/Elev= 30
  4560.3  290.42  4608.2  286.94  4613.4  287.69  4639.7  286.38  4665.5  286.94
  4671.2  286.02  4676.5  287.38  4702.7  284.86  4734.3  285.32  4739.5  287.15
  4779.6  285.08  4937.8  285.81  4980.0  281.75  4998.1  276.78  5000.9  276.28
  5004.1  276.78  5004.3  276.82  5018.0  280.61  5049.5  285.20  5074.5  285.17
  5086.3  284.68  5112.6  289.88  5155.5  291.40  5169.9  292.15  5207.1  298.79
  5212.4  298.64  5243.9  291.06  5264.9  293.49  5270.2  295.82  5419.1  298.30
#Mann=7,-1,0
  4560.3     0.1       0  4665.5    0.16       0  4998.1    0.07       0
  5004.1    0.16       0  5004.3    0.05       0  5074.5    0.08       0
  5155.5    0.05       0
Bank Sta=4998.1,5004.1
Exp/Cntr=0.3,0.1

Type RM Length L Ch R = 1,4057,921,921,921
BEGIN DESCRIPTION:
LITTLE CEDAR CREEK TRIBUTARY 1 8.0
END DESCRIPTION:
XS GIS Cut Line= 3
      3577692.11     10332941.66      3577650.44     10332218.03
      3577700.44     10331868.01
#Sta/Elev= 30
  4422.1  299.01  4492.2  296.39  4552.3  291.45  4572.4  288.90  4622.4  287.89
  4680.3  284.52  4792.7  282.33  4822.8  282.48  4842.8  284.10  4862.8  282.61
  4879.4  282.39  4892.9  282.00  4912.9  279.75  4933.0  280.81  4953.0  283.69
  4963.0  282.85  4973.0  280.06  4993.1  277.60  5000.1  275.75  5002.8  275.25
  5006.1  275.75  5013.1  276.27  5023.1  279.28  5029.5  280.24  5063.2  281.68
  5083.2  286.29  5093.2  287.22  5346.8  293.53  5403.5  295.29  5500.5  297.02
#Mann=5,-1,0
  4422.1    0.05       0  4879.4    0.16       0  5000.1    0.07       0
  5006.1    0.16       0  5346.8    0.05       0
Bank Sta=5000.1,5006.1
Exp/Cntr=0.3,0.1

Type RM Length L Ch R = 1,3136,805,805,805
BEGIN DESCRIPTION:
LITTLE CEDAR CREEK TRIBUTARY 1 6.0
END DESCRIPTION:
XS GIS Cut Line= 3
      3578242.10     10333041.68      3578310.20     10332231.70
      3577956.57     10331718.59
#Sta/Elev= 30
  4369.9  294.60  4390.0  291.86  4400.0  291.15  4420.1  290.51  4432.4  289.32
  4500.4  287.19  4661.0  284.47  4741.2  281.80  4821.5  280.53  4831.6  280.75
  4841.6  281.98  4851.6  282.10  4861.7  280.67  4982.1  276.71  4992.1  274.75
  4999.2  272.69  5001.9  272.19  5005.2  272.69  5029.1  278.59  5032.3  279.01
  5062.4  278.61  5146.7  279.20  5310.9  286.74  5469.2  290.52  5505.0  290.14
  5547.2  291.02  5555.7  290.52  5715.1  290.67  5749.8  291.35  5805.9  293.63
#Mann=5,-1,0
  4369.9    0.05       0  4999.2   0.035       0  5005.2    0.05       0
  5029.1    0.16       0  5715.1    0.05       0
Bank Sta=4999.2,5005.2
Exp/Cntr=0.3,0.1

Type RM Length L Ch R = 1,2331,499,499,499
BEGIN DESCRIPTION:
LITTLE CEDAR CREEK TRIBUTARY 1 5.0
END DESCRIPTION:
XS GIS Cut Line= 3
      3579115.75     10332863.64      3578942.15     10332328.93
      3578206.58     10331621.11
#Sta/Elev= 30
  4144.7  291.04  4274.0  292.11  4556.4  290.62  4689.5  291.50  4768.6  288.90
  4846.3  284.95  4881.8  281.46  4917.1  279.56  4931.2  276.92  4945.4  275.41
  4952.6  275.93  4959.5  274.27  4966.7  273.89  4980.9  274.86  4995.0  272.53
  4999.0  270.90  5001.7  270.40  5005.0  270.90  5016.1  275.02  5030.3  275.64
  5086.9  275.09  5171.8  275.99  5270.8  279.66  5291.9  279.64  5327.4  281.65
  5348.5  281.58  5468.9  285.12  5553.5  285.63  5638.4  288.85  5727.7  289.99
#Mann=3,-1,0
  4144.7    0.16       0  4999.0    0.07       0  5005.0    0.16       0
Bank Sta=4999,5005
Exp/Cntr=0.3,0.1

Type RM Length L Ch R = 1,1832,643,643,643
BEGIN DESCRIPTION:
LITTLE CEDAR CREEK TRIBUTARY 1 4.0
END DESCRIPTION:
XS GIS Cut Line= 3
      3579150.41     10331887.46      3578950.44     10331787.48
      3578310.67     10331426.41
#Sta/Elev= 30
  4583.7  289.44  4615.3  290.79  4660.1  291.32  4704.8  290.18  4765.4  290.44
  4803.5  288.08  4810.0  288.30  4857.2  282.69  4869.3  280.07  4889.2  277.56
  4906.8  274.91  4934.2  272.85  4964.5  274.40  4977.6  274.12  4987.7  271.48
  4993.5  272.48  5000.6  269.98  5012.1  269.87  5014.9  269.37  5018.1  269.87
  5023.5  271.92  5031.0  273.43  5155.2  273.01  5171.1  274.65  5176.9  274.24
  5252.0  278.66  5279.4  279.22  5354.6  283.34  5478.7  287.45  5541.9  288.70
#Mann=6,-1,0
  4583.7    0.05       0  4857.2    0.16       0  4889.2    0.05       0
  4964.5    0.16       0  5012.1    0.07       0  5018.1    0.16       0
Bank Sta=5012.1,5018.1
Exp/Cntr=0.3,0.1

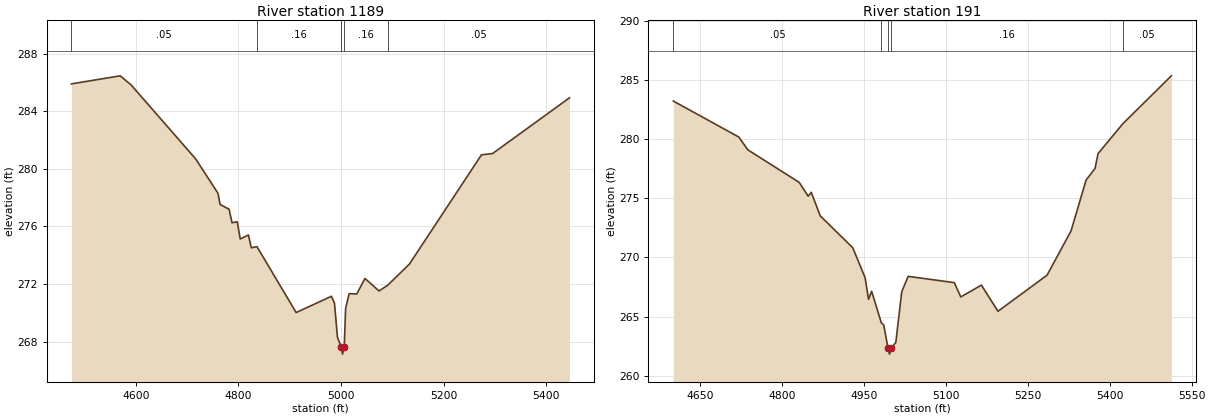
Type RM Length L Ch R = 1,1189,998,998,998
BEGIN DESCRIPTION:
LITTLE CEDAR CREEK TRIBUTARY 1 3.0
END DESCRIPTION:
XS GIS Cut Line= 3
      3579269.91     10331554.85      3579019.88     10331404.84
      3578427.43     10331072.87
#Sta/Elev= 30
  4474.4  285.91  4569.5  286.47  4590.9  285.83  4716.7  280.69  4760.0  278.31
  4764.2  277.53  4781.7  277.20  4787.4  276.26  4797.6  276.33  4803.4  275.13
  4819.3  275.41  4825.1  274.52  4836.0  274.60  4912.4  270.02  4981.2  271.15
  4987.1  270.67  4992.9  268.31  5000.1  267.63  5002.8  267.13  5006.1  267.63
  5008.8  270.30  5015.6  271.33  5030.5  271.31  5046.5  272.39  5073.9  271.52
  5090.9  271.92  5133.2  273.39  5273.6  280.98  5295.3  281.07  5445.1  284.94
#Mann=5,-1,0
  4474.4    0.05       0  4836.0    0.16       0  5000.1    0.07       0
  5006.1    0.16       0  5090.9    0.05       0
Bank Sta=5000.1,5006.1
Exp/Cntr=0.3,0.1

Type RM Length L Ch R = 1,191,0,0,0
BEGIN DESCRIPTION:
LITTLE CEDAR CREEK TRIBUTARY 1 1.0
END DESCRIPTION:
XS GIS Cut Line= 3
      3579382.26     10331333.29      3579147.88     10330881.88
      3578792.08     10330691.63
#Sta/Elev= 30
  4600.7  283.21  4720.6  280.17  4737.1  279.09  4831.2  276.34  4847.7  275.17
  4853.3  275.50  4869.8  273.51  4929.3  270.82  4951.9  268.29  4958.3  266.46
  4963.9  267.14  4981.7  264.47  4986.0  264.30  4993.9  262.33  4996.6  261.83
  4999.9  262.33  5008.2  262.83  5019.0  267.09  5030.7  268.40  5115.3  267.87
  5127.2  266.66  5164.9  267.66  5195.3  265.45  5285.2  268.50  5329.1  272.24
  5356.7  276.54  5373.0  277.51  5378.6  278.77  5423.9  281.29  5512.8  285.34
#Mann=5,-1,0
  4600.7    0.05       0  4981.7    0.16       0  4993.9    0.07       0
  4999.9    0.16       0  5423.9    0.05       0
Bank Sta=4993.9,4999.9
Exp/Cntr=0.3,0.1

Chan Stop Cuts=-1