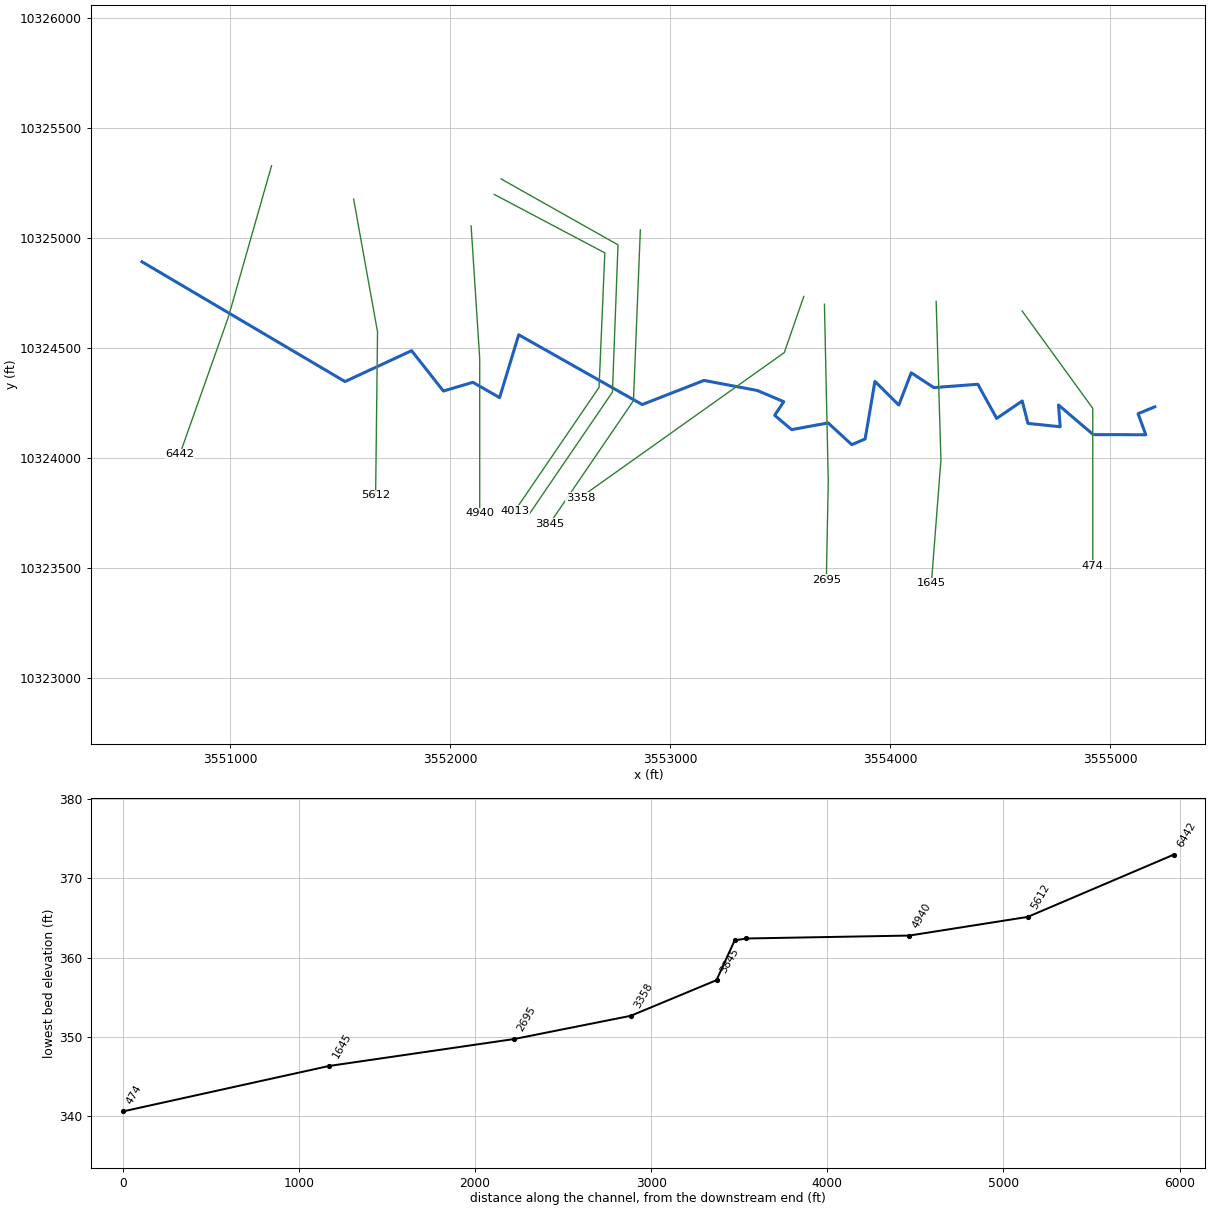
--- LITTLE CEDAR CREEK TRIBUTARY 10.prj (project) ---

Proj Title=LITTLE CEDAR CREEK TRIBUTARY 10 Base Level Engineering
Current Plan=p01
Default Exp/Contr=0.3,0.1
English Units
Geom File=g01
Flow File=f01
Plan File=p01
BEGIN DESCRIPTION:
LITTLE CEDAR CREEK TRIBUTARY 10
END DESCRIPTION:

--- LITTLE CEDAR CREEK TRIBUTARY 10.p01 (plan) ---

Plan Title=Multiple Run
Short Identifier=Multiple
Geom File=g01
Flow File=f01
Subcritical Flow
K Sum by GR= 0
Std Step Tol= 0.01
Critical Tol= 0.01
Num of Std Step Trials= 20
Max Error Tol= 0.3
Flow Tol Ratio= 0.001
Split Flow NTrial= 30
Split Flow Tol= 0.02
Split Flow Ratio= 0.02
Log Output Level= 0
Friction Slope Method= 1
Unsteady Friction Slope Method= 2
Unsteady Bridges Friction Slope Method= 1
Parabolic Critical Depth
Global Vel Dist=  1 , 1 , 1
Global Log Level= 0
CheckData=True
Encroach Param= -1, 0, 0, 0
BEGIN DESCRIPTION:
Multiple Run
END DESCRIPTION:

--- LITTLE CEDAR CREEK TRIBUTARY 10.f01 (steady flow) ---

Flow Title=Multiple
Number of Profiles=7
Profile Names=10-year,25-year,50-year,1pct_min,100-year,1pct_plu,500-year
River Rch & RM= LITTLE CEDAR CRE,Reach-1,6442
     315     409     483     419     567     767     780
Boundary for River Rch & Prof#=LITTLE CEDAR CRE,Reach-1,1
Up Type=0
Dn Type=3
Dn Slope=0.005
Boundary for River Rch & Prof#=LITTLE CEDAR CRE,Reach-1,2
Up Type=0
Dn Type=3
Dn Slope=0.005
Boundary for River Rch & Prof#=LITTLE CEDAR CRE,Reach-1,3
Up Type=0
Dn Type=3
Dn Slope=0.005
Boundary for River Rch & Prof#=LITTLE CEDAR CRE,Reach-1,4
Up Type=0
Dn Type=3
Dn Slope=0.005
Boundary for River Rch & Prof#=LITTLE CEDAR CRE,Reach-1,5
Up Type=0
Dn Type=3
Dn Slope=0.005
Boundary for River Rch & Prof#=LITTLE CEDAR CRE,Reach-1,6
Up Type=0
Dn Type=3
Dn Slope=0.005
Boundary for River Rch & Prof#=LITTLE CEDAR CRE,Reach-1,7
Up Type=0
Dn Type=3
Dn Slope=0.005

--- LITTLE CEDAR CREEK TRIBUTARY 10.g01 (geometry) ---

Geom Title=Existing Conditions

River Reach=LITTLE CEDAR CRE,Reach-1
Reach XY= 30
      3550598.57     10324891.07      3551521.49     10324346.63
      3551824.27     10324486.91      3551968.71     10324303.57
      3552102.74     10324343.16      3552224.27     10324273.71
      3552311.07     10324559.13      3552872.23     10324242.11
      3553153.26     10324351.71      3553395.23     10324306.13
      3553515.67     10324255.14      3553474.44     10324193.29
      3553551.48     10324128.18      3553717.50     10324158.56
      3553824.92     10324059.82      3553885.68     10324085.86
      3553930.17     10324347.37      3554038.68     10324239.94
      3554095.10     10324386.43      3554198.18     10324319.16
      3554397.83     10324334.35      3554483.56     10324179.18
      3554599.66     10324258.39      3554625.70     10324156.39
      3554772.18     10324141.20      3554764.59     10324239.94
      3554922.66     10324105.42      3555161.15     10324104.83
      3555126.18     10324200.69      3555202.11     10324231.64

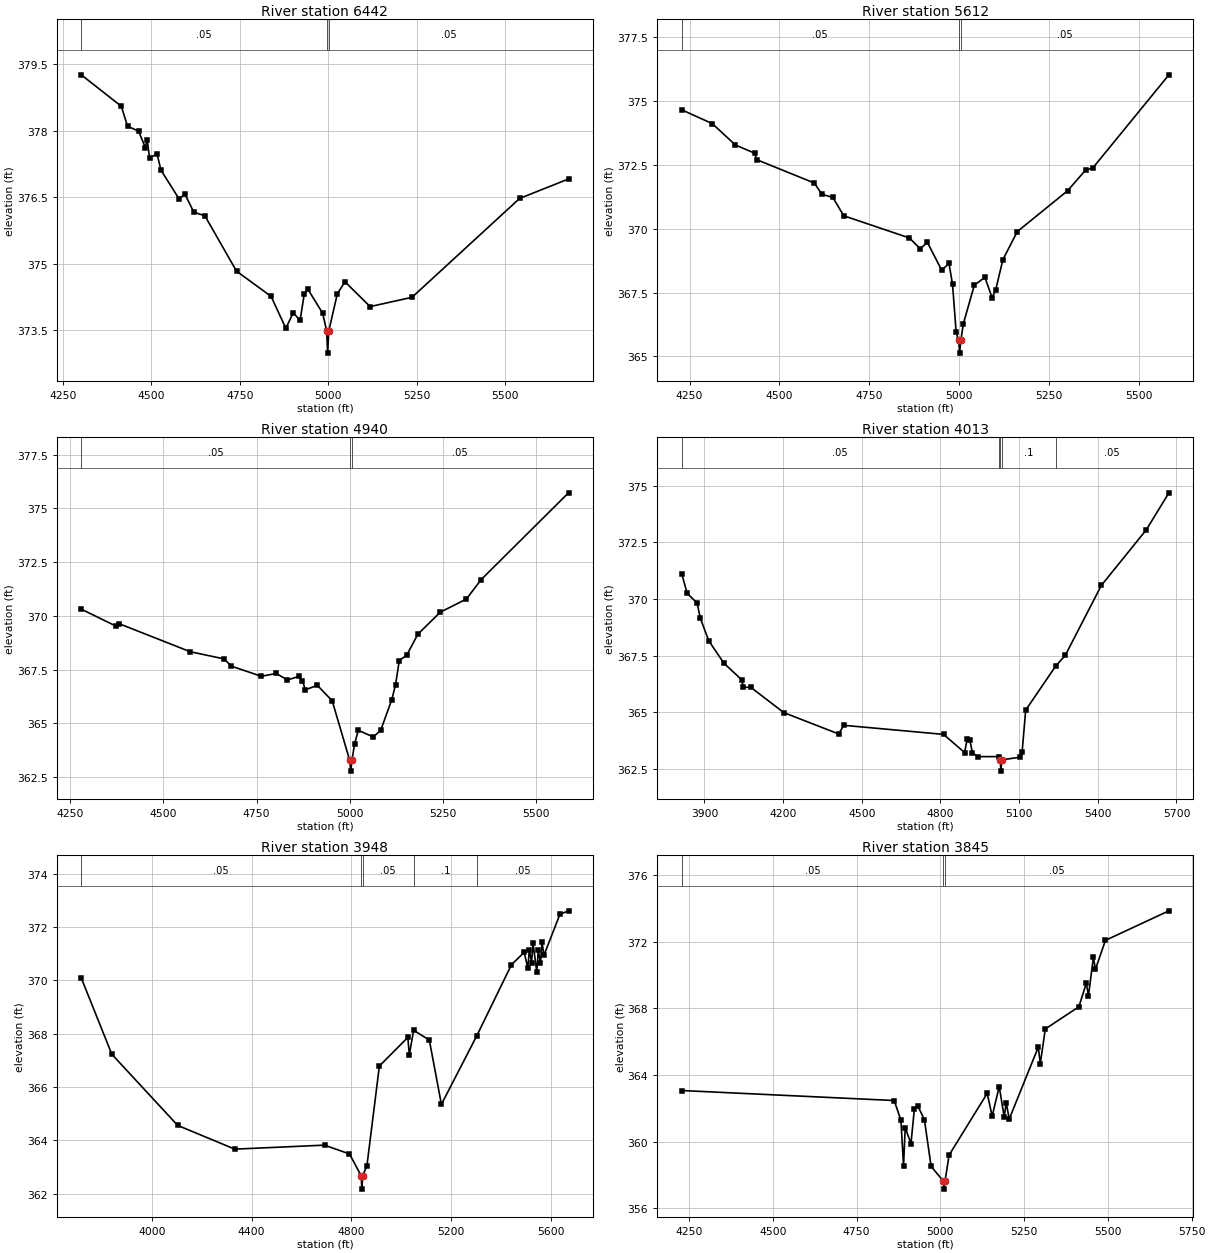
Type RM Length L Ch R = 1,6442,830,830,830
BEGIN DESCRIPTION:
LITTLE CEDAR CREEK TRIBUTARY 10 10.0
END DESCRIPTION:
XS GIS Cut Line= 3
      3551187.63     10325327.22      3550992.11     10324641.64
      3550770.98     10324016.52
#Sta/Elev= 30
  4302.3  379.26  4415.4  378.55  4432.9  378.10  4464.1  377.99  4483.1  377.62
  4488.3  377.80  4495.3  377.38  4516.1  377.48  4527.3  377.11  4578.5  376.46
  4595.0  376.57  4620.1  376.16  4651.3  376.08  4740.7  374.83  4838.4  374.26
  4880.0  373.54  4900.8  373.89  4920.2  373.72  4932.0  374.31  4942.4  374.42
  4984.0  373.88  4995.3  373.48  4998.1  372.98  5001.3  373.48  5025.4  374.32
  5047.0  374.59  5118.1  374.03  5236.4  374.24  5540.1  376.47  5678.3  376.91
#Mann=3,-1,0
  4302.3    0.05       0  4995.3    0.03       0  5001.3    0.05       0
Bank Sta=4995.3,5001.3
Exp/Cntr=0.3,0.1

Type RM Length L Ch R = 1,5612,672,672,672
BEGIN DESCRIPTION:
LITTLE CEDAR CREEK TRIBUTARY 10 8.0
END DESCRIPTION:
XS GIS Cut Line= 3
      3551560.90     10325175.34      3551669.40     10324572.04
      3551660.72     10323829.87
#Sta/Elev= 30
  4228.2  374.66  4313.2  374.12  4377.8  373.28  4431.4  372.96  4436.5  372.71
  4597.4  371.79  4618.1  371.35  4648.5  371.23  4679.0  370.51  4861.6  369.64
  4891.6  369.22  4911.6  369.47  4951.6  368.37  4971.6  368.65  4981.6  367.82
  4991.6  365.95  4998.6  365.63  5001.3  365.13  5004.6  365.63  5011.6  366.28
  5042.2  367.79  5071.6  368.10  5091.6  367.30  5101.6  367.61  5121.6  368.79
  5161.6  369.89  5301.6  371.49  5351.6  372.30  5371.6  372.38  5583.4  376.03
#Mann=3,-1,0
  4228.2    0.05       0  4998.6    0.03       0  5004.6    0.05       0
Bank Sta=4998.6,5004.6
Exp/Cntr=0.3,0.1

Type RM Length L Ch R = 1,4940,927,927,927
BEGIN DESCRIPTION:
LITTLE CEDAR CREEK TRIBUTARY 10 7.0
END DESCRIPTION:
XS GIS Cut Line= 3
      3552094.75     10325053.77      3552133.81     10324450.51
      3552133.81     10323747.43
#Sta/Elev= 30
  4279.5  370.31  4371.8  369.53  4381.8  369.63  4572.2  368.33  4662.4  368.00
  4682.5  367.66  4762.6  367.19  4802.7  367.32  4832.8  367.02  4862.8  367.18
  4872.9  366.99  4880.9  366.56  4912.9  366.77  4952.9  366.05  4999.9  363.28
  5002.6  362.78  5005.9  363.28  5012.9  364.04  5022.9  364.68  5062.9  364.37
  5082.9  364.67  5112.9  366.11  5122.9  366.80  5132.9  367.92  5152.9  368.17
  5182.9  369.15  5242.9  370.17  5312.9  370.78  5352.9  371.69  5587.1  375.72
#Mann=3,-1,0
  4279.5    0.05       0  4999.9    0.03       0  5005.9    0.05       0
Bank Sta=4999.9,5005.9
Exp/Cntr=0.3,0.1

Type RM Length L Ch R = 1,4013,65,65,65
BEGIN DESCRIPTION:
LITTLE CEDAR CREEK TRIBUTARY 10 6.2
END DESCRIPTION:
XS GIS Cut Line= 4
      3552199.93     10325197.06      3552702.50     10324931.45
      3552676.35     10324320.31      3552294.41     10323760.42
#Sta/Elev= 30
  3813.2  371.12  3834.1  370.25  3872.2  369.82  3883.7  369.17  3916.4  368.16
  3974.0  367.17  4041.9  366.44  4048.5  366.10  4076.2  366.11  4202.6  364.99
  4411.5  364.05  4431.5  364.43  4811.8  364.03  4891.9  363.23  4901.9  363.82
  4911.9  363.78  4921.9  363.22  4942.0  363.05  5021.5  363.05  5027.8  362.91
  5030.5  362.41  5033.8  362.91  5102.6  363.02  5111.5  363.27  5124.9  365.10
  5238.7  367.03  5276.1  367.52  5413.6  370.60  5584.9  373.05  5671.1  374.68
#Mann=5,-1,0
  3813.2    0.05       0  5021.5     0.1       0  5027.8    0.03       0
  5033.8     0.1       0  5238.7    0.05       0
Bank Sta=5027.8,5033.8
Exp/Cntr=0.3,0.1

Type RM Length L Ch R = 1,3948,103,103,103
BEGIN DESCRIPTION:
LITTLE CEDAR CREEK TRIBUTARY 10 6.1
END DESCRIPTION:
XS GIS Cut Line= 4
      3552231.17     10325267.37      3552762.40     10324967.91
      3552737.11     10324298.61      3552356.16     10323740.17
#Sta/Elev= 30
  3716.1  370.09  3838.7  367.23  4103.1  364.56  4332.2  363.67  4692.4  363.82
  4792.5  363.49  4839.6  362.67  4842.3  362.17  4845.6  362.67  4862.6  363.05
  4912.6  366.79  5026.7  367.86  5032.8  367.21  5050.0  368.13  5113.1  367.76
  5161.5  365.35  5303.9  367.93  5442.7  370.59  5493.5  371.05  5508.4  370.47
  5514.5  371.15  5523.3  370.67  5529.4  371.39  5544.3  370.32  5550.4  371.13
  5559.2  370.64  5565.3  371.44  5573.1  370.94  5637.1  372.48  5671.7  372.61
#Mann=5,-1,0
  3716.1    0.05       0  4839.6    0.03       0  4845.6    0.05       0
  5050.0     0.1       0  5303.9    0.05       0
Bank Sta=4839.6,4845.6
Exp/Cntr=0.3,0.1

Type RM Length L Ch R = 1,3845,487,487,487
BEGIN DESCRIPTION:
LITTLE CEDAR CREEK TRIBUTARY 10 6.0
END DESCRIPTION:
XS GIS Cut Line= 3
      3552863.96     10325035.61      3552832.60     10324259.54
      3552450.64     10323699.62
#Sta/Elev= 30
  4227.6  363.07  4862.1  362.47  4882.1  361.28  4889.9  358.55  4894.9  360.84
  4912.1  359.89  4922.1  361.94  4932.1  362.16  4952.2  361.32  4972.2  358.52
  5007.9  357.66  5010.7  357.16  5013.9  357.66  5025.9  359.20  5139.6  362.90
  5154.5  361.53  5175.5  363.31  5190.4  361.49  5196.5  362.33  5205.4  361.36
  5292.1  365.67  5298.2  364.68  5313.1  366.76  5413.3  368.09  5435.7  369.51
  5441.8  368.74  5456.7  371.06  5462.7  370.33  5492.6  372.07  5682.1  373.84
#Mann=3,-1,0
  4227.6    0.05       0  5007.9    0.03       0  5013.9    0.05       0
Bank Sta=5007.9,5013.9
Exp/Cntr=0.3,0.1

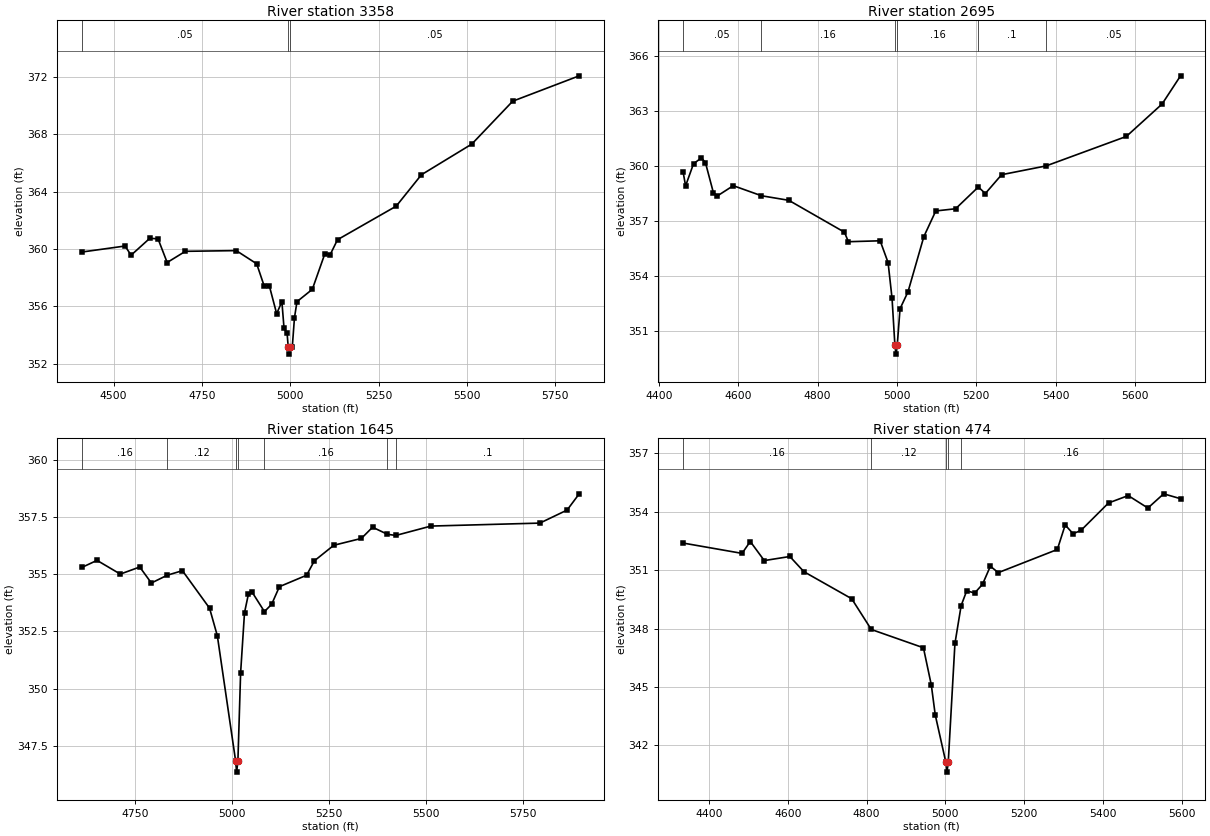
Type RM Length L Ch R = 1,3358,663,663,663
BEGIN DESCRIPTION:
LITTLE CEDAR CREEK TRIBUTARY 10 5.0
END DESCRIPTION:
XS GIS Cut Line= 3
      3553606.80     10324733.47      3553518.26     10324478.28
      3552591.15     10323819.40
#Sta/Elev= 30
  4409.9  359.79  4532.3  360.21  4549.4  359.57  4602.4  360.75  4625.7  360.71
  4651.5  359.06  4703.0  359.84  4847.0  359.89  4904.8  358.97  4925.6  357.45
  4940.4  357.45  4961.3  355.49  4976.1  356.33  4982.2  354.47  4990.8  354.14
  4994.0  353.17  4996.7  352.67  5000.0  353.17  5005.6  353.19  5011.7  355.21
  5018.8  356.33  5062.2  357.19  5097.8  359.68  5112.6  359.60  5133.5  360.65
  5299.6  362.99  5370.9  365.18  5513.5  367.32  5629.2  370.31  5817.4  372.08
#Mann=3,-1,0
  4409.9    0.05       0  4994.0    0.04       0  5000.0    0.05       0
Bank Sta=4994,5000
Exp/Cntr=0.3,0.1

Type RM Length L Ch R = 1,2695,1050,1050,1050
BEGIN DESCRIPTION:
LITTLE CEDAR CREEK TRIBUTARY 10 4.0
END DESCRIPTION:
XS GIS Cut Line= 3
      3553700.66     10324697.87      3553718.02     10323894.96
      3553709.37     10323445.14
#Sta/Elev= 30
  4461.5  359.68  4467.7  358.93  4487.7  360.14  4507.7  360.46  4517.7  360.20
  4537.7  358.56  4547.7  358.38  4587.8  358.94  4658.9  358.39  4727.8  358.14
  4867.8  356.40  4877.8  355.88  4957.8  355.93  4977.8  354.74  4987.8  352.78
  4994.9  350.24  4997.6  349.74  5000.9  350.24  5007.9  352.22  5027.9  353.14
  5067.9  356.16  5097.9  357.56  5147.9  357.68  5205.2  358.87  5222.7  358.51
  5263.8  359.54  5375.9  360.02  5578.0  361.63  5668.0  363.40  5714.5  364.94
#Mann=6,-1,0
  4461.5    0.05       0  4658.9    0.16       0  4994.9    0.07       0
  5000.9    0.16       0  5205.2     0.1       0  5375.9    0.05       0
Bank Sta=4994.9,5000.9
Exp/Cntr=0.3,0.1

Type RM Length L Ch R = 1,1645,1171,1171,1171
BEGIN DESCRIPTION:
LITTLE CEDAR CREEK TRIBUTARY 10 3.0
END DESCRIPTION:
XS GIS Cut Line= 3
      3554208.47     10324710.94      3554230.17     10323990.45
      3554186.77     10323430.55
#Sta/Elev= 30
  4611.7  355.30  4651.0  355.61  4711.0  355.01  4761.1  355.32  4791.1  354.62
  4831.9  354.96  4871.1  355.16  4941.1  353.52  4961.2  352.31  5008.2  346.85
  5010.9  346.35  5014.2  346.85  5021.2  350.70  5031.2  353.32  5041.2  354.13
  5051.2  354.21  5082.6  353.37  5101.2  353.69  5121.2  354.46  5191.3  354.96
  5211.3  355.59  5261.3  356.27  5332.5  356.57  5361.4  357.06  5399.7  356.75
  5421.3  356.70  5511.9  357.11  5792.7  357.24  5862.9  357.81  5894.1  358.52
#Mann=7,-1,0
  4611.7    0.16       0  4831.9    0.12       0  5008.2    0.07       0
  5014.2    0.12       0  5082.6    0.16       0  5399.7    0.05       0
  5421.3     0.1       0
Bank Sta=5008.2,5014.2
Exp/Cntr=0.3,0.1

Type RM Length L Ch R = 1,474,0,0,0
BEGIN DESCRIPTION:
LITTLE CEDAR CREEK TRIBUTARY 10 1.0
END DESCRIPTION:
XS GIS Cut Line= 3
      3554599.07     10324667.56      3554920.27     10324224.82
      3554920.27     10323508.70
#Sta/Elev= 30
  4334.1  352.39  4483.7  351.86  4504.6  352.47  4540.2  351.49  4605.1  351.70
  4640.7  350.92  4762.1  349.53  4811.9  347.95  4944.3  347.01  4964.3  345.10
  4974.3  343.56  5001.3  341.12  5004.0  340.62  5007.3  341.12  5024.3  347.23
  5040.1  349.18  5054.3  349.94  5074.3  349.82  5094.3  350.27  5114.3  351.20
  5134.3  350.87  5284.3  352.06  5304.3  353.32  5324.3  352.87  5344.3  353.04
  5414.3  354.45  5464.3  354.83  5514.3  354.19  5554.3  354.92  5597.2  354.67
#Mann=5,-1,0
  4334.1    0.16       0  4811.9    0.12       0  5001.3    0.07       0
  5007.3    0.12       0  5040.1    0.16       0
Bank Sta=5001.3,5007.3
Exp/Cntr=0.3,0.1

Chan Stop Cuts=-1