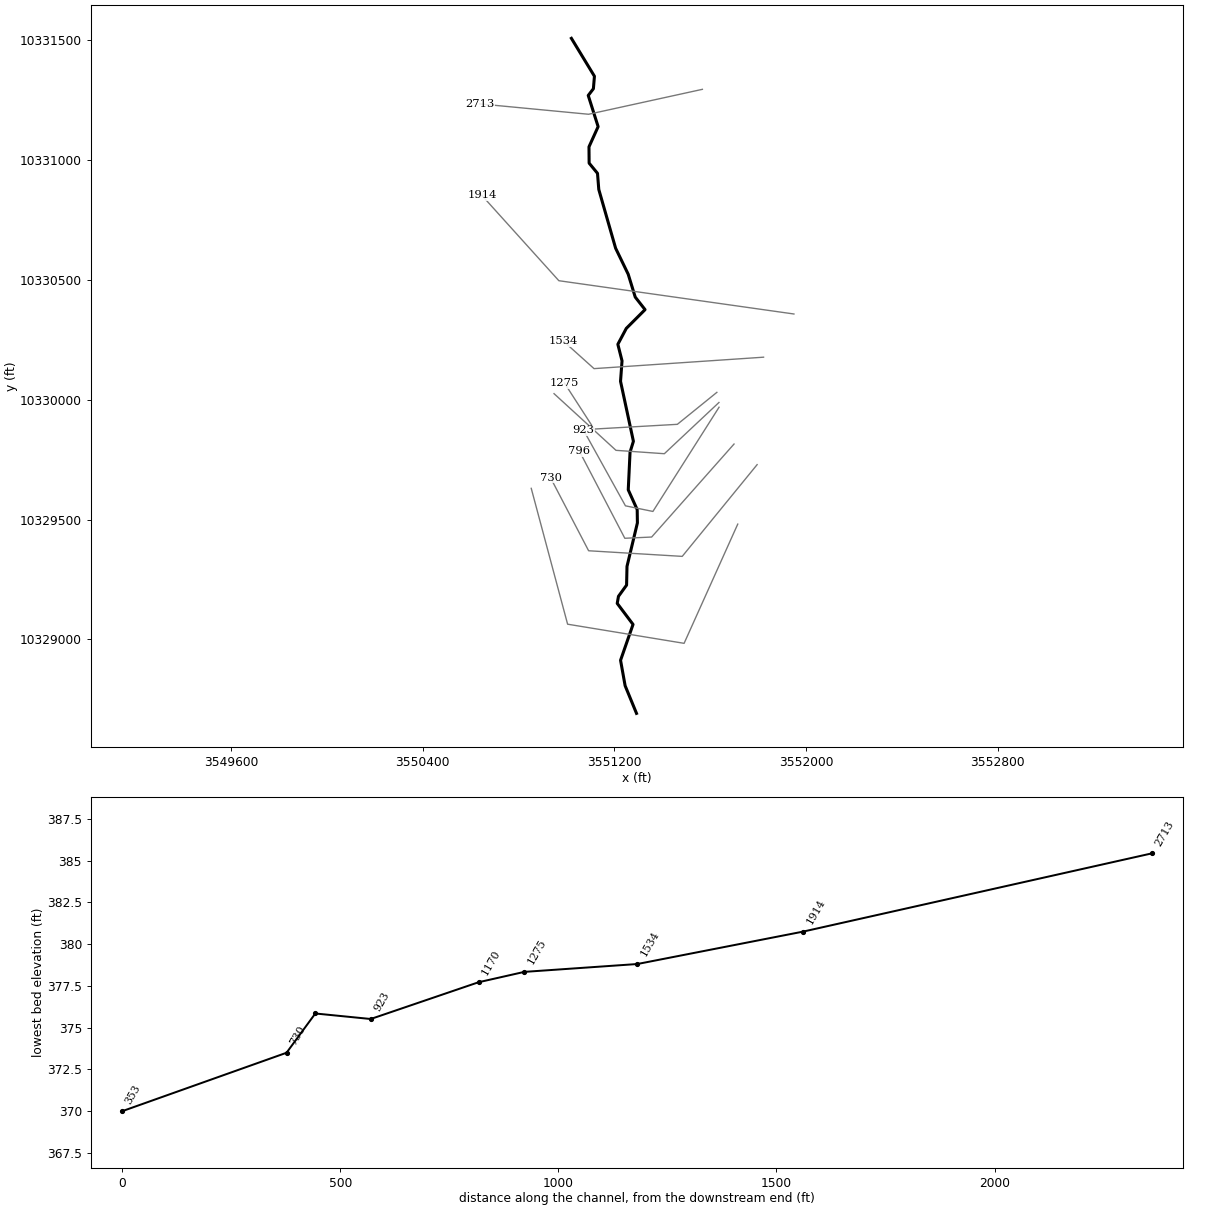
--- LITTLE CEDAR CREEK TRIBUTARY 13.prj (project) ---

Proj Title=LITTLE CEDAR CREEK TRIBUTARY 13 Base Level Engineering
Current Plan=p01
Default Exp/Contr=0.3,0.1
English Units
Geom File=g01
Flow File=f01
Plan File=p01
Y Axis Title=Elevation
X Axis Title(PF)=Main Channel Distance
X Axis Title(XS)=Station
BEGIN DESCRIPTION:
LITTLE CEDAR CREEK TRIBUTARY 13
END DESCRIPTION:
DSS Export Rating Curves= 0
DSS Export Rating Curve Sorted= 0
DSS Export Volume Flow Curves= 0
DXF OffsetX= 0
DXF OffsetY= 0
DXF ScaleX= 1
DXF ScaleY= 10

--- LITTLE CEDAR CREEK TRIBUTARY 13.p01 (plan) ---

Plan Title=Multiple Run
Short Identifier=Multiple
Geom File=g01
Flow File=f01
Subcritical Flow
K Sum by GR= 0
Std Step Tol= 0.01
Critical Tol= 0.01
Num of Std Step Trials= 20
Max Error Tol= 0.3
Flow Tol Ratio= 0.001
Split Flow NTrial= 30
Split Flow Tol= 0.02
Split Flow Ratio= 0.02
Log Output Level= 0
Friction Slope Method= 1
Unsteady Friction Slope Method= 2
Unsteady Bridges Friction Slope Method= 1
Parabolic Critical Depth
Global Vel Dist=  1 , 1 , 1
Global Log Level= 0
CheckData=True
Encroach Param= -1, 0, 0, 0
BEGIN DESCRIPTION:
Multiple Run
END DESCRIPTION:

--- LITTLE CEDAR CREEK TRIBUTARY 13.f01 (steady flow) ---

Flow Title=Multiple
Number of Profiles=7
Profile Names=10-year,25-year,50-year,1pct_min,100-year,1pct_plu,500-year
River Rch & RM= LITTLE CEDAR CRE,Reach-1,2713
     213     270     313     267     361     489     481
Boundary for River Rch & Prof#=LITTLE CEDAR CRE,Reach-1,1
Up Type=0
Dn Type=3
Dn Slope=0.005
Boundary for River Rch & Prof#=LITTLE CEDAR CRE,Reach-1,2
Up Type=0
Dn Type=3
Dn Slope=0.005
Boundary for River Rch & Prof#=LITTLE CEDAR CRE,Reach-1,3
Up Type=0
Dn Type=3
Dn Slope=0.005
Boundary for River Rch & Prof#=LITTLE CEDAR CRE,Reach-1,4
Up Type=0
Dn Type=3
Dn Slope=0.005
Boundary for River Rch & Prof#=LITTLE CEDAR CRE,Reach-1,5
Up Type=0
Dn Type=3
Dn Slope=0.005
Boundary for River Rch & Prof#=LITTLE CEDAR CRE,Reach-1,6
Up Type=0
Dn Type=3
Dn Slope=0.005
Boundary for River Rch & Prof#=LITTLE CEDAR CRE,Reach-1,7
Up Type=0
Dn Type=3
Dn Slope=0.005

--- LITTLE CEDAR CREEK TRIBUTARY 13.g01 (geometry) ---

Geom Title=Existing Conditions
Program Version=4.10

River Reach=LITTLE CEDAR CRE,Reach-1
Reach XY= 30
       3551020.4     10331508.48      3551116.53      10331350.3
      3551112.19     10331298.22      3551090.66     10331270.15
      3551131.94     10331140.05      3551093.79     10331055.77
      3551094.38     10330987.71      3551129.33     10330945.15
       3551134.7     10330877.75      3551204.87     10330632.79
      3551257.34     10330524.38      3551286.79     10330428.72
      3551327.79     10330376.38       3551249.5     10330298.12
      3551214.22     10330231.75      3551231.68     10330162.62
      3551225.45     10330077.26      3551279.16     10329827.01
      3551265.13     10329781.57      3551257.63     10329624.48
      3551294.96     10329542.01      3551295.82     10329486.45
      3551252.42     10329305.03      3551250.68     10329226.91
      3551216.83     10329180.03      3551211.62     10329150.52
      3551277.59     10329062.84      3551225.56     10328913.21
      3551244.58     10328807.15      3551292.11     10328691.64

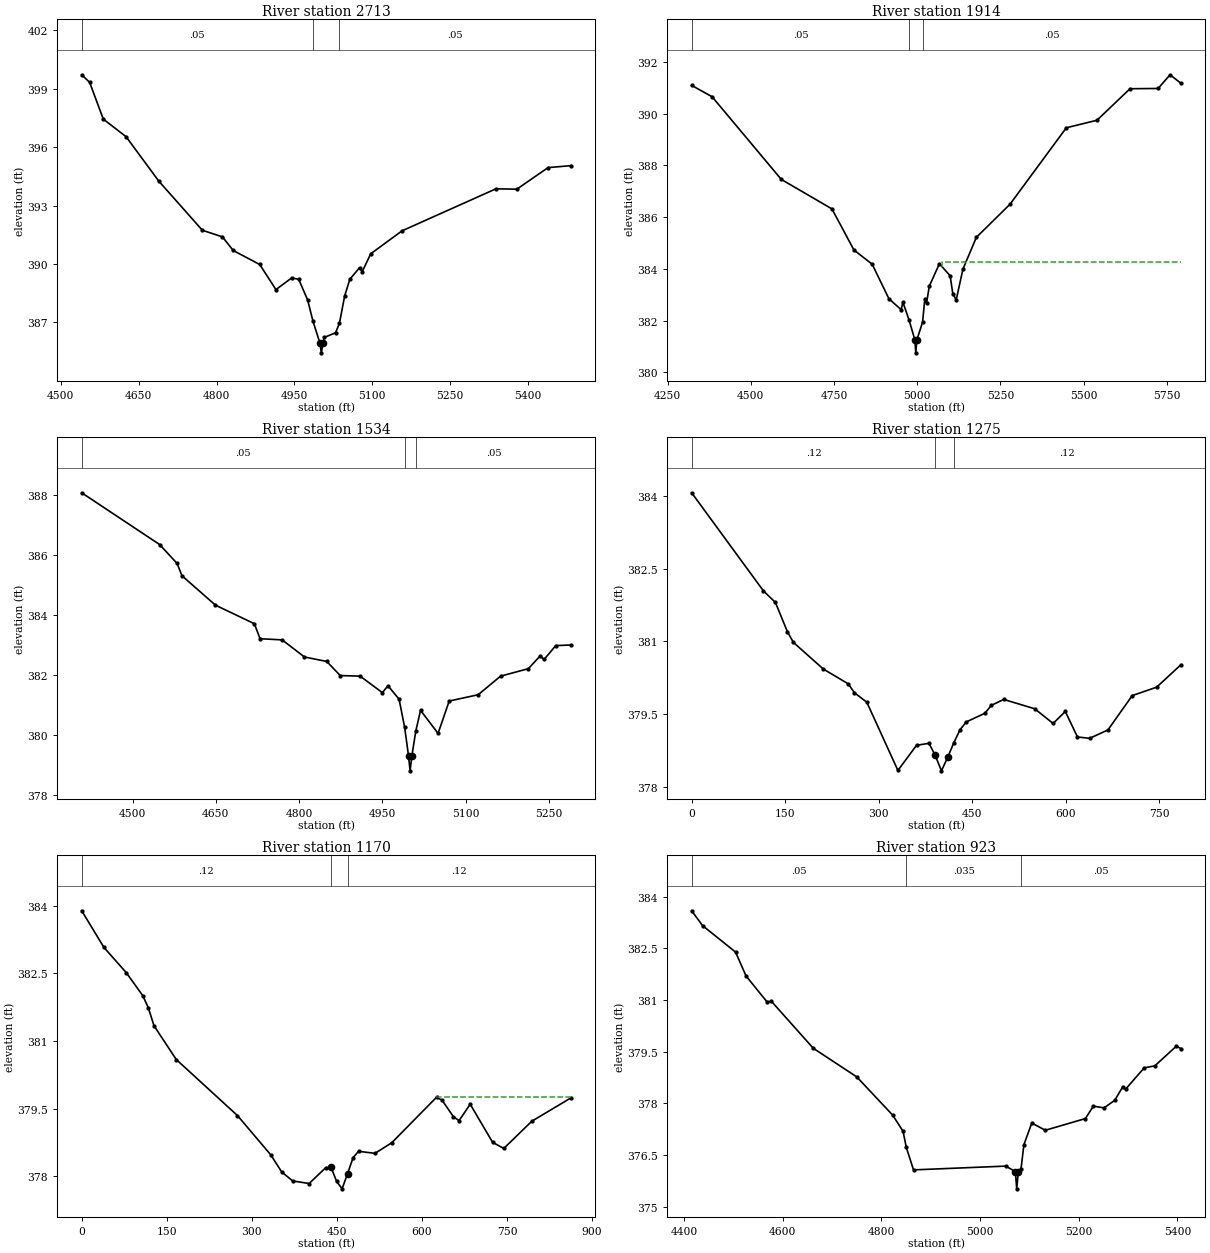
Type RM Length L Ch R = 1 ,2713    ,799,799,799
BEGIN DESCRIPTION:
LITTLE CEDAR CREEK TRIBUTARY 13 3.0
END DESCRIPTION:
XS GIS Cut Line= 3
        3551567.      10331295.7      3551092.11     10331191.64
      3550638.23     10331234.93
#Sta/Elev= 30
  4540.4  399.72  4555.7  399.33    4582  397.44  4625.8  396.54  4688.7  394.26
  4772.7  391.73  4811.4  391.39  4832.1  390.69  4883.2  389.97  4914.4  388.68
  4944.7  389.28  4958.2  389.21  4975.4  388.15  4985.6  387.07  4999.1  385.93
  5001.8  385.43  5005.1  385.93  5007.2  386.22  5029.1  386.46  5036.6  386.94
  5046.7  388.35  5056.7  389.21  5075.5  389.81  5080.5   389.6  5096.9  390.52
  5157.2   391.7    5338  393.86  5378.2  393.84  5438.4  394.95  5482.5  395.05
#Mann= 3 ,-1 , 0
  4540.4     .05       0  4985.6    .035       0  5036.6     .05       0
Bank Sta=4999.1,5005.1
XS Rating Curve= 0 ,0
Exp/Cntr=0.3,0.1

Type RM Length L Ch R = 1 ,1914    ,380,380,380
BEGIN DESCRIPTION:
LITTLE CEDAR CREEK TRIBUTARY 13 2.0
END DESCRIPTION:
XS GIS Cut Line= 3
      3551949.01     10330358.19      3550968.07     10330497.09
      3550646.97      10330852.9
#Sta/Elev= 30
  4322.5   391.1  4383.9  390.66  4591.9  387.46    4744  386.32    4810  384.73
  4864.8  384.18  4915.3  382.84    4952  382.42  4957.1  382.71  4975.9  382.01
  4993.1  381.25  4995.8  380.75  4999.1  381.25  5016.3  381.94    5023  382.84
  5028.1  382.67  5036.5  383.33  5066.8   384.2  5099.1  383.73  5107.2  383.03
  5117.3   382.8  5137.5  383.99  5177.9  385.22  5278.9   386.5  5448.2  389.46
  5540.1  389.75  5639.5  390.97  5723.9  390.98  5759.8  391.51  5792.5  391.18
#Mann= 3 ,-1 , 0
  4322.5     .05       0  4975.9     .03       0  5016.3     .05       0
#XS Ineff= 2 , 0
                         5075.45          384.27
Permanent Ineff=
       F       F
Bank Sta=4993.1,4999.1
XS Rating Curve= 0 ,0
Exp/Cntr=0.3,0.1

Type RM Length L Ch R = 1 ,1534    ,259,259,259
BEGIN DESCRIPTION:
Mapping XS 00c9cc5f
END DESCRIPTION:
XS GIS Cut Line= 3
      3551822.31     10330177.95      3551114.86     10330130.21
      3550986.95     10330245.12
#Sta/Elev= 30
  4408.5  388.09    4549  386.36  4580.3  385.73  4589.1  385.32  4649.3  384.34
  4719.4  383.72  4729.7  383.22  4769.5  383.18  4809.6  382.61  4849.7  382.46
  4874.1  381.99  4909.8  381.97  4949.9  381.42    4960  381.65    4980   381.2
    4990  380.26    4997  379.31  4999.8  378.81    5003  379.31  5010.1  380.14
  5018.6  380.83  5050.2  380.06  5070.2  381.14  5122.4  381.35  5162.7  381.97
  5212.8  382.22  5233.7  382.64  5241.2  382.53  5262.1  382.99  5289.5  383.01
#Mann= 3 ,-1 , 0
  4408.5     .05       0    4990     .03       0  5010.1     .05       0
Bank Sta=4997,5003
XS Rating Curve= 0 ,0
Exp/Cntr=0.3,0.1

Type RM Length L Ch R = 1 ,1275    ,105,105,105
BEGIN DESCRIPTION:
Mapping XS cc4fd1f0
END DESCRIPTION:
XS GIS Cut Line= 4
      3551627.45     10330031.25      3551462.52     10329897.79
     3551115.301    10329878.097     3550991.704    10330069.528
#Sta/Elev= 30
       0384.0576115.1876382.0391134.3856381.8022153.5835381.2007163.1825380.9813
211.1774380.4334251.0805380.1294261.0563379.9469281.0079  379.75330.8869378.3478
360.8143378.8654380.7659378.9052390.7417378.6563400.7175378.3395410.6933378.6165
420.6691378.9199430.6449379.1864440.6207379.3456470.5481379.5246480.5239379.6839
500.4755379.8084550.3545379.6158579.8613379.3137599.3923379.5607618.9233 379.036
638.4543379.0082667.7507379.1798706.8127379.8873745.8747380.0593784.9366380.5218
#Mann= 3 ,-1 , 0
       0     .12       0390.7417     .03       0420.6691     .12       0
Bank Sta=390.7417,410.6933
XS Rating Curve= 0 ,0
Exp/Cntr=0.3,0.1

Type RM Length L Ch R = 1 ,1170    ,247,247,247
BEGIN DESCRIPTION:
Mapping XS 80f63469
END DESCRIPTION:
XS GIS Cut Line= 4
      3551636.15     10329988.95      3551408.27     10329775.18
      3551206.44     10329789.28     3550947.954    10330025.778
#Sta/Elev= 30
       0383.884139.23966383.071278.47932 382.514107.9091381.9985 117.719381.7239
127.5289381.3343166.7686380.5861274.6776379.3431333.2794378.4741352.6414378.0938
372.0034 377.894401.0465 377.837430.0896378.1857439.7706378.1932449.4517377.8846
459.1327377.7188468.8137378.0583478.4947  378.41488.1758378.5513517.2188378.5056
 546.833378.7423625.8043379.7513635.6757379.6792655.4185379.3185665.2899379.2304
685.0327379.5948724.5183  378.75744.2612378.6145793.6182379.2177 862.718379.7364
#Mann= 3 , 0 , 0
       0     .12       0439.7706     .03       0468.8137     .12       0
#XS Ineff= 2 , 0
                          625.57          379.76
Permanent Ineff=
       F       F
Bank Sta=439.7706,468.8137
XS Rating Curve= 0 ,0
Exp/Cntr=0.3,0.1

Type RM Length L Ch R = 1 ,923     ,127,127,127
BEGIN DESCRIPTION:
Mapping XS c768ad1b
END DESCRIPTION:
XS GIS Cut Line= 4
      3551636.53     10329969.15      3551360.49     10329534.27
      3551245.91     10329557.71      3551071.45     10329872.79
#Sta/Elev= 30
  4415.1  383.59  4437.2  383.16  4504.2  382.39  4525.3   381.7  4567.7  380.95
    4577  380.96  4661.7   379.6  4749.8  378.77  4822.7  377.66  4843.8  377.19
  4850.4  376.72    4865  376.07  5052.3  376.18  5071.5  376.02  5074.3  375.52
  5077.5  376.02  5083.1  376.11  5088.8   376.8  5104.8  377.43  5132.3  377.22
  5213.6  377.56  5229.6  377.92  5251.4  377.87  5273.1  378.09  5289.2  378.48
  5294.9  378.41  5332.7  379.03  5354.4  379.09  5397.9  379.66  5407.3  379.59
#Mann= 3 ,-1 , 0
  4415.1     .05       0  4850.4    .035       0  5083.1     .05       0
Bank Sta=5071.5,5077.5
XS Rating Curve= 0 ,0
Exp/Cntr=0.3,0.1

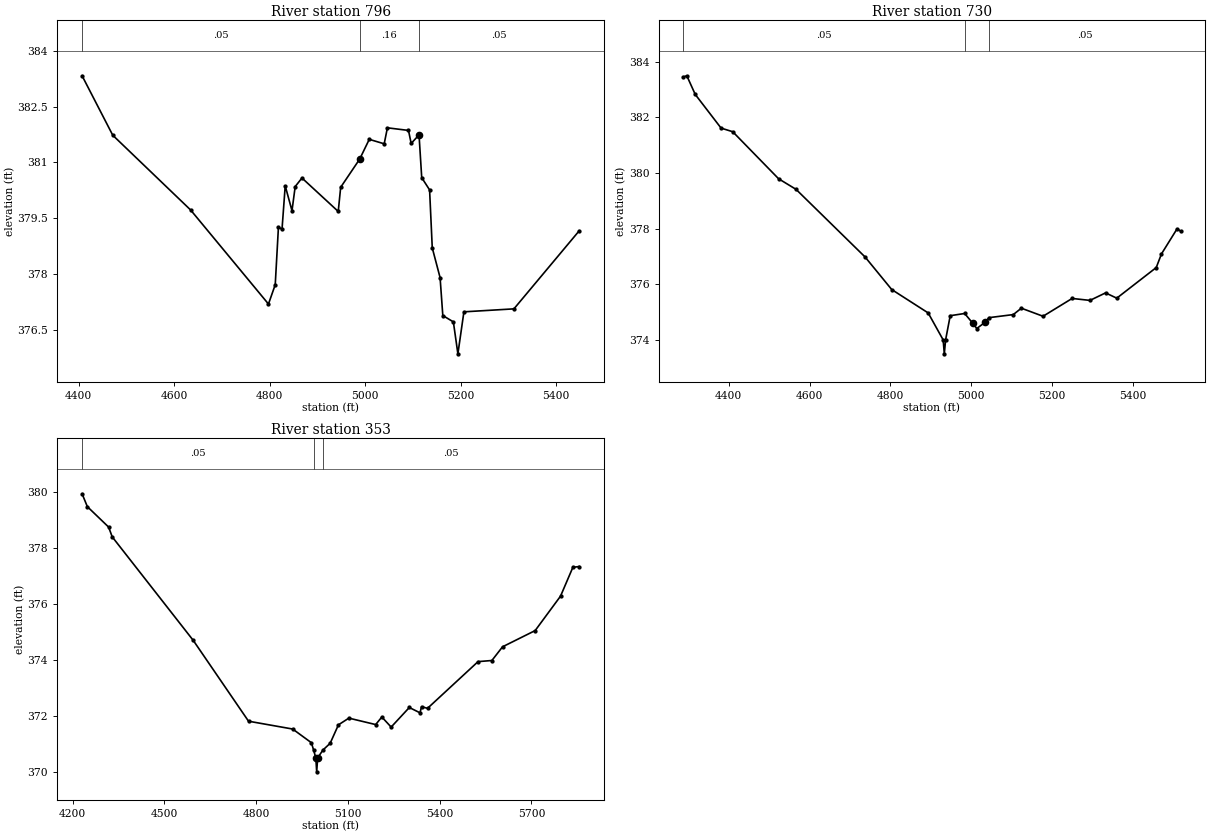
Type RM Length L Ch R = 1 ,796     ,66,66,66
BEGIN DESCRIPTION:
Mapping XS e32b455f
END DESCRIPTION:
XS GIS Cut Line= 4
      3551699.06     10329815.55      3551355.29      10329427.5
      3551243.31     10329422.29      3551053.25     10329786.79
#Sta/Elev= 30
  4407.1  383.33  4471.4  381.73  4634.5  379.72  4797.6  377.19  4811.8  377.71
  4818.5  379.26    4826   379.2  4832.7  380.37  4846.9   379.7  4853.6  380.35
  4867.8  380.58  4943.8  379.68  4948.9  380.33  4988.8  381.09  5008.8  381.62
  5040.1   381.5  5046.8  381.93    5091  381.86  5096.6  381.51  5113.1  381.74
  5118.7  380.59  5135.2  380.26  5140.8   378.7  5157.2   377.9  5162.9  376.88
    5185  376.71  5194.5  375.85  5207.1  376.98  5311.9  377.06  5448.7  379.16
#Mann= 3 , 0 , 0
  4407.1     .05       0  4988.8     .16       0  5113.1     .05       0
Bank Sta=4988.8,5113.1
XS Rating Curve= 0 ,0
Exp/Cntr=0.3,0.1

Type RM Length L Ch R = 1 ,730     ,377,377,377
BEGIN DESCRIPTION:
Mapping XS e3fd81c8
END DESCRIPTION:
XS GIS Cut Line= 4
      3551795.38     10329729.56      3551482.89     10329346.77
      3551092.27     10329370.21       3550933.4     10329674.91
#Sta/Elev= 30
  4288.1  383.45  4296.5  383.49  4317.3  382.82  4381.2  381.61    4410  381.48
  4523.4  379.79  4566.5  379.41  4737.2  376.98  4803.1  375.81  4893.2  374.97
  4930.3     374  4933.1   373.5  4936.3     374  4947.7  374.87  4983.4  374.95
  5003.4   374.6  5013.4  374.41  5033.5  374.63  5043.5   374.8  5103.6  374.91
  5123.6  375.14  5177.2  374.85  5249.1  375.49  5293.2  375.42  5331.8  375.69
  5359.5   375.5  5457.1   376.6    5470  377.09  5508.5  377.99  5517.2  377.91
#Mann= 3 ,-1 , 0
  4288.1     .05       0  4983.4     .03       0  5043.5     .05       0
Bank Sta=5003.4,5033.5
XS Rating Curve= 0 ,0
Exp/Cntr=0.3,0.1

Type RM Length L Ch R = 1 ,353     ,0,0,0
BEGIN DESCRIPTION:
LITTLE CEDAR CREEK TRIBUTARY 13 1.0
END DESCRIPTION:
XS GIS Cut Line= 4
      3551714.59     10329481.45       3551490.7     10328983.92
      3551004.59     10329063.78      3550852.82     10329630.71
#Sta/Elev= 30
  4230.9  379.94  4248.1  379.48  4317.6  378.75  4329.4   378.4  4594.2   374.7
    4775  371.81  4919.3  371.53  4980.6  371.04  4987.9  370.77    4995   370.5
  4997.8     370    5001   370.5  5018.3  370.78  5041.8  371.02  5068.9  371.68
    5103  371.92  5190.6  371.69  5210.8  371.96  5241.2   371.6  5300.6   372.3
  5335.5  372.11  5340.6  372.33  5360.1  372.27  5525.3  373.94  5570.5  373.98
  5605.4  374.47    5712  375.05  5794.9  376.28  5835.2  377.31    5856  377.34
#Mann= 3 ,-1 , 0
  4230.9     .05       0  4987.9     .03       0  5018.3     .05       0
Bank Sta=4995,5001
XS Rating Curve= 0 ,0
Exp/Cntr=0.3,0.1

Chan Stop Cuts=-1
Use User Specified Reach Order=0
Composite Channel Slope=5