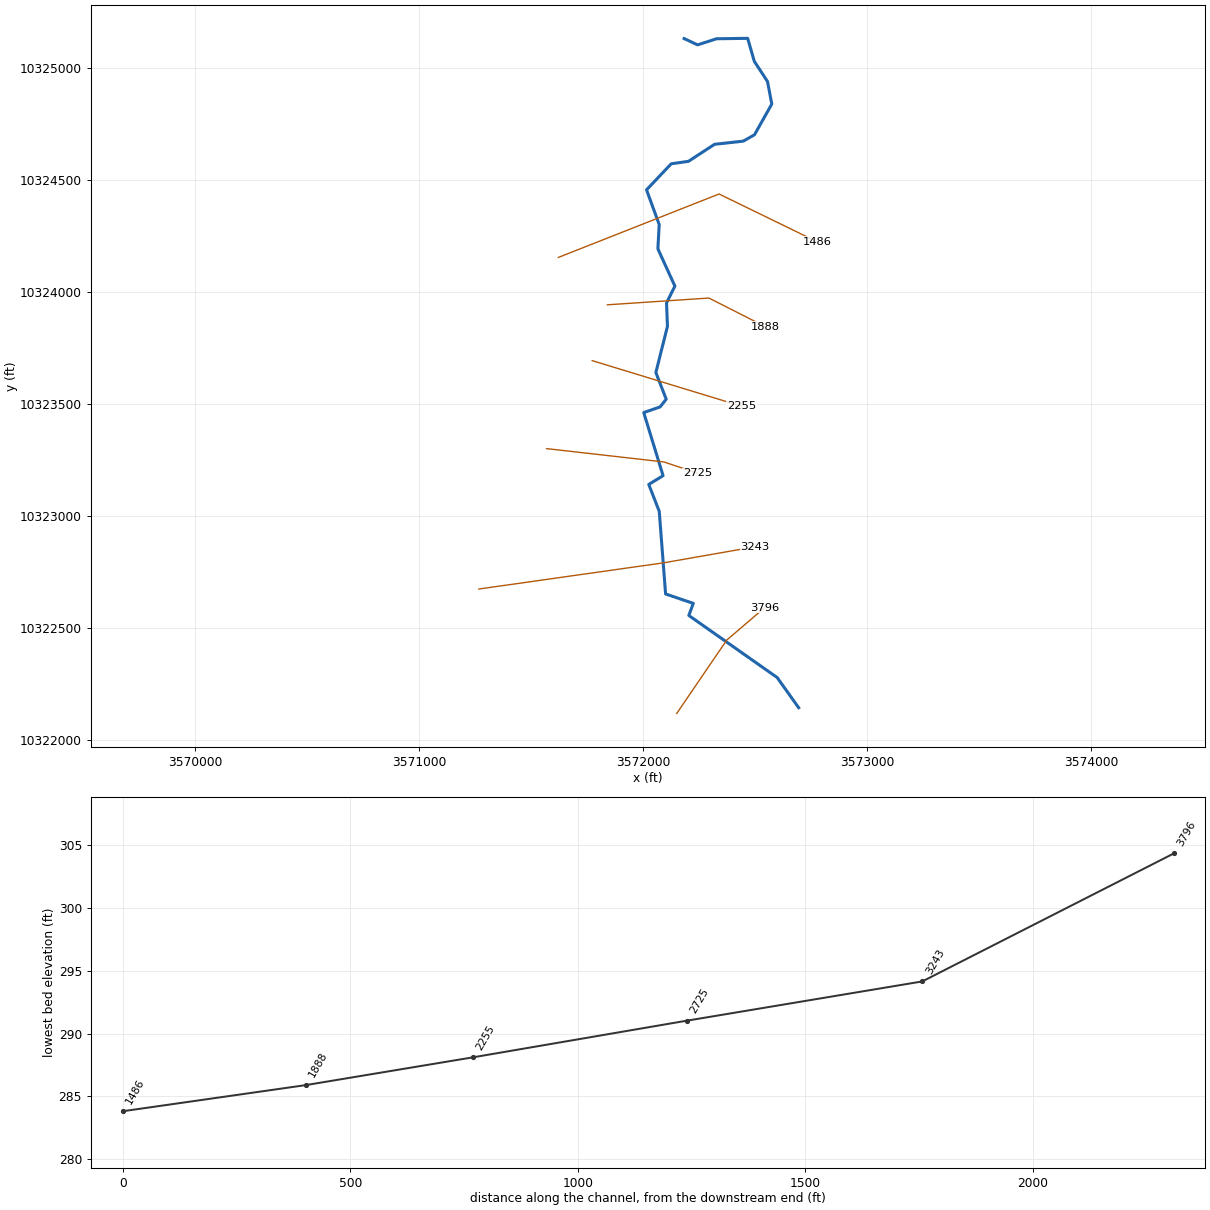
--- LITTLE CEDAR CREEK TRIBUTARY 2.prj (project) ---

Proj Title=LITTLE CEDAR CREEK TRIBUTARY 2 Base Level Engineering
Current Plan=p01
Default Exp/Contr=0.3,0.1
English Units
Geom File=g01
Flow File=f01
Plan File=p01
BEGIN DESCRIPTION:
LITTLE CEDAR CREEK TRIBUTARY 2
END DESCRIPTION:

--- LITTLE CEDAR CREEK TRIBUTARY 2.p01 (plan) ---

Plan Title=Multiple Run
Short Identifier=Multiple
Geom File=g01
Flow File=f01
Subcritical Flow
K Sum by GR= 0
Std Step Tol= 0.01
Critical Tol= 0.01
Num of Std Step Trials= 20
Max Error Tol= 0.3
Flow Tol Ratio= 0.001
Split Flow NTrial= 30
Split Flow Tol= 0.02
Split Flow Ratio= 0.02
Log Output Level= 0
Friction Slope Method= 1
Unsteady Friction Slope Method= 2
Unsteady Bridges Friction Slope Method= 1
Parabolic Critical Depth
Global Vel Dist=  1 , 1 , 1
Global Log Level= 0
CheckData=True
Encroach Param= -1, 0, 0, 0
BEGIN DESCRIPTION:
Multiple Run
END DESCRIPTION:

--- LITTLE CEDAR CREEK TRIBUTARY 2.f01 (steady flow) ---

Flow Title=Multiple
Number of Profiles=7
Profile Names=10-year,25-year,50-year,1pct_min,100-year,1pct_plu,500-year
River Rch & RM= LITTLE CEDAR CRE,Reach-1,3796
     232     295     344     295     399     540     537
Boundary for River Rch & Prof#=LITTLE CEDAR CRE,Reach-1,1
Up Type=0
Dn Type=3
Dn Slope=0.005
Boundary for River Rch & Prof#=LITTLE CEDAR CRE,Reach-1,2
Up Type=0
Dn Type=3
Dn Slope=0.005
Boundary for River Rch & Prof#=LITTLE CEDAR CRE,Reach-1,3
Up Type=0
Dn Type=3
Dn Slope=0.005
Boundary for River Rch & Prof#=LITTLE CEDAR CRE,Reach-1,4
Up Type=0
Dn Type=3
Dn Slope=0.005
Boundary for River Rch & Prof#=LITTLE CEDAR CRE,Reach-1,5
Up Type=0
Dn Type=3
Dn Slope=0.005
Boundary for River Rch & Prof#=LITTLE CEDAR CRE,Reach-1,6
Up Type=0
Dn Type=3
Dn Slope=0.005
Boundary for River Rch & Prof#=LITTLE CEDAR CRE,Reach-1,7
Up Type=0
Dn Type=3
Dn Slope=0.005

--- LITTLE CEDAR CREEK TRIBUTARY 2.g01 (geometry) ---

Geom Title=Existing Conditions

River Reach=LITTLE CEDAR CRE,Reach-1
Reach XY= 30
      3572693.30     10322144.66      3572597.46     10322279.38
      3572203.02     10322556.47      3572223.06     10322610.52
      3572099.39     10322652.39      3572071.03     10323021.21
      3572024.28     10323141.47      3572088.08     10323180.36
      3572001.82     10323462.13      3572074.83     10323487.33
      3572102.05     10323521.78      3572055.96     10323640.78
      3572107.63     10323846.81      3572103.56     10323951.51
      3572140.86     10324026.51      3572064.93     10324192.90
      3572070.74     10324301.69      3572014.33     10324456.40
      3572124.57     10324572.72      3572201.21     10324583.54
      3572317.94     10324659.62      3572446.26     10324673.74
      3572496.10     10324702.06      3572573.35     10324839.22
      3572554.26     10324939.91      3572495.23     10325030.19
      3572465.71     10325132.62      3572326.63     10325130.67
      3572242.08     10325103.48      3572182.11     10325131.64

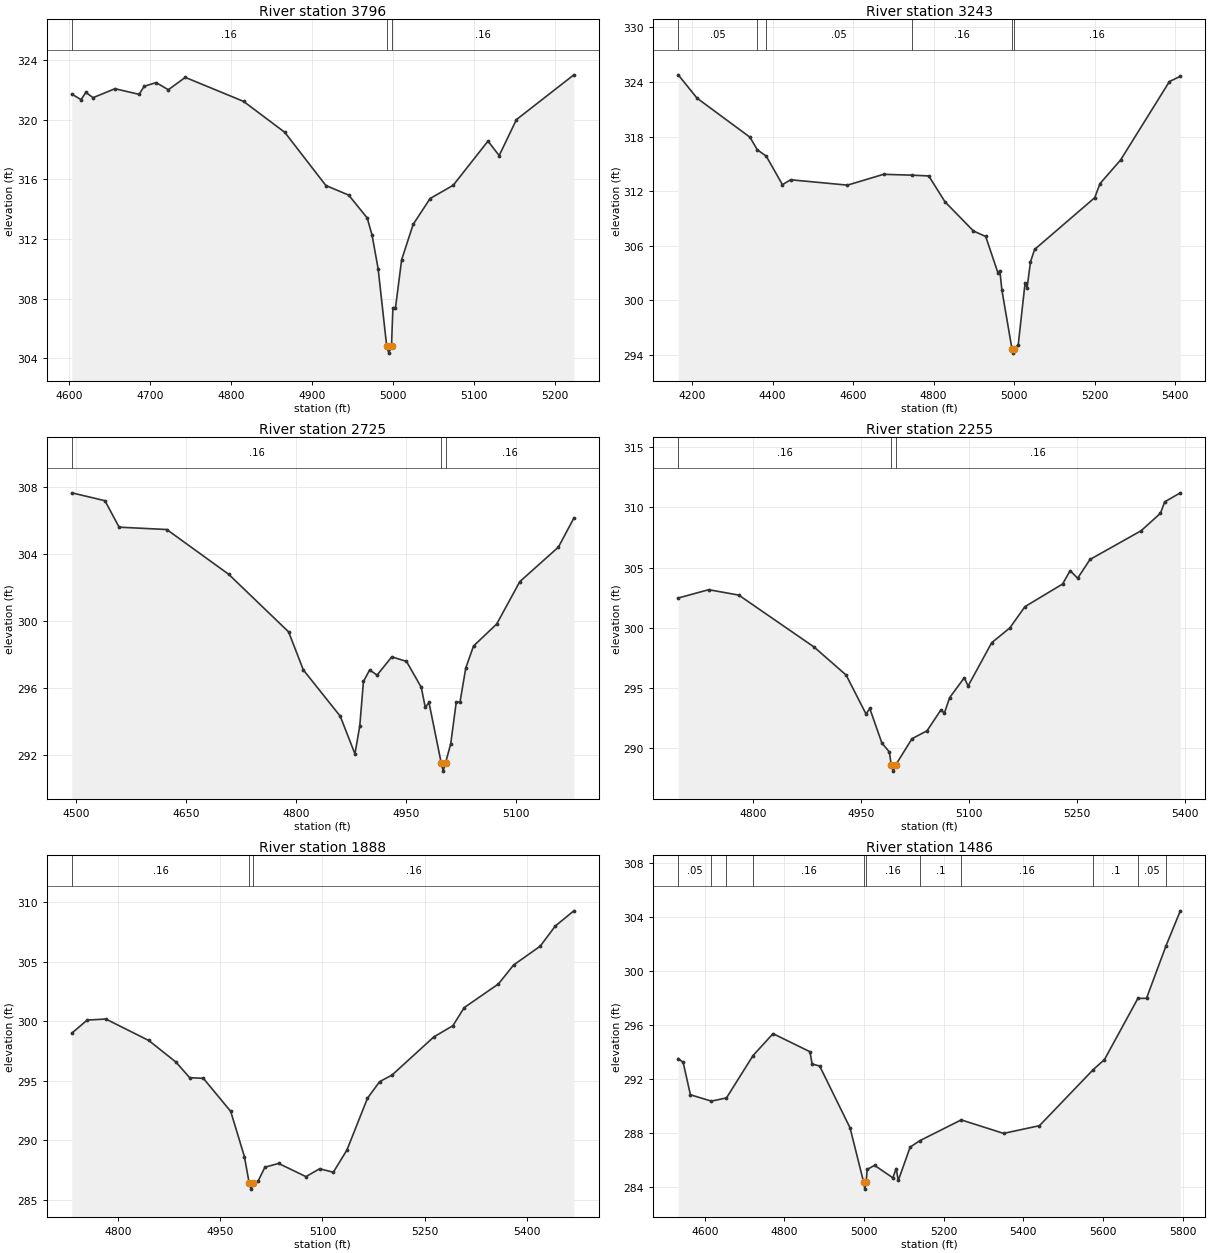
Type RM Length L Ch R = 1,3796,553,553,553
BEGIN DESCRIPTION:
LITTLE CEDAR CREEK TRIBUTARY 2 7.0
END DESCRIPTION:
XS GIS Cut Line= 3
      3572149.24     10322119.41      3572372.46     10322446.74
      3572542.11     10322591.64
#Sta/Elev= 30
  4603.8  321.72  4615.2  321.35  4621.2  321.83  4630.1  321.48  4657.1  322.08
  4687.0  321.70  4693.0  322.24  4707.9  322.49  4722.9  322.01  4743.8  322.84
  4815.7  321.23  4866.5  319.16  4917.3  315.59  4945.4  314.95  4968.2  313.42
  4974.2  312.27  4981.7  310.01  4992.2  304.86  4994.9  304.36  4998.2  304.86
  4999.9  307.40  5003.1  307.40  5010.7  310.62  5024.9  312.99  5045.8  314.72
  5074.3  315.61  5117.2  318.57  5131.0  317.60  5152.3  320.01  5223.1  323.01
#Mann=3,-1,0
  4603.8    0.16       0  4992.2    0.07       0  4998.2    0.16       0
Bank Sta=4992.2,4998.2
Exp/Cntr=0.3,0.1

Type RM Length L Ch R = 1,3243,518,518,518
BEGIN DESCRIPTION:
LITTLE CEDAR CREEK TRIBUTARY 2 6.0
END DESCRIPTION:
XS GIS Cut Line= 3
      3571265.76     10322674.49      3572092.11     10322791.64
      3572498.78     10322862.99
#Sta/Elev= 30
  4165.4  324.79  4212.2  322.22  4343.5  317.93  4361.9  316.54  4384.1  315.84
  4424.3  312.70  4444.5  313.24  4585.9  312.65  4675.6  313.84  4745.0  313.75
  4787.9  313.66  4828.3  310.81  4899.0  307.60  4929.3  307.00  4959.5  303.03
  4964.5  303.24  4969.7  301.07  4994.5  294.66  4997.2  294.16  5000.5  294.66
  5010.2  295.08  5027.2  301.88  5032.2  301.36  5040.6  304.20  5050.8  305.57
  5200.3  311.27  5213.2  312.81  5264.7  315.43  5385.8  324.05  5412.9  324.63
#Mann=6,-1,0
  4165.4    0.05       0  4361.9     0.1       0  4384.1    0.05       0
  4745.0    0.16       0  4994.5    0.07       0  5000.5    0.16       0
Bank Sta=4994.5,5000.5
Exp/Cntr=0.3,0.1

Type RM Length L Ch R = 1,2725,470,470,470
BEGIN DESCRIPTION:
LITTLE CEDAR CREEK TRIBUTARY 2 5.0
END DESCRIPTION:
XS GIS Cut Line= 3
      3571567.80     10323301.27      3572092.11     10323241.64
      3572242.10     10323191.64
#Sta/Elev= 30
  4493.6  307.64  4538.9  307.17  4558.3  305.59  4623.4  305.45  4707.9  302.78
  4789.8  299.34  4809.9  297.07  4860.3  294.31  4880.4  292.06  4887.0  293.73
  4892.0  296.38  4900.5  297.07  4910.6  296.76  4930.7  297.85  4950.8  297.58
  4971.0  296.03  4976.5  294.83  4981.5  295.13  4998.2  291.53  5000.9  291.03
  5004.2  291.53  5011.2  292.66  5018.8  295.15  5023.9  295.15  5031.8  297.19
  5042.4  298.50  5074.0  299.81  5105.6  302.34  5158.3  304.40  5179.4  306.13
#Mann=3,-1,0
  4493.6    0.16       0  4998.2    0.07       0  5004.2    0.16       0
Bank Sta=4998.2,5004.2
Exp/Cntr=0.3,0.1

Type RM Length L Ch R = 1,2255,367,367,367
BEGIN DESCRIPTION:
LITTLE CEDAR CREEK TRIBUTARY 2 4.0
END DESCRIPTION:
XS GIS Cut Line= 3
      3571771.66     10323693.97      3572144.05     10323580.31
      3572438.51     10323490.52
#Sta/Elev= 30
  4696.6  302.48  4738.9  303.17  4780.7  302.72  4885.3  298.41  4929.8  296.08
  4957.4  292.85  4962.6  293.31  4979.4  290.44  4989.8  289.70  4992.4  288.61
  4995.2  288.11  4998.4  288.61  5021.2  290.80  5042.1  291.46  5061.0  293.16
  5066.3  292.95  5073.5  294.21  5093.8  295.86  5099.1  295.18  5131.9  298.77
  5157.1  300.00  5178.0  301.76  5230.3  303.64  5240.8  304.75  5251.2  304.12
  5268.4  305.68  5339.3  308.06  5366.2  309.51  5372.1  310.46  5393.8  311.21
#Mann=3,-1,0
  4696.6    0.16       0  4992.4    0.07       0  4998.4    0.16       0
Bank Sta=4992.4,4998.4
Exp/Cntr=0.3,0.1

Type RM Length L Ch R = 1,1888,402,402,402
BEGIN DESCRIPTION:
LITTLE CEDAR CREEK TRIBUTARY 2 3.0
END DESCRIPTION:
XS GIS Cut Line= 3
      3571839.60     10323943.16      3572292.74     10323973.37
      3572544.09     10323845.83
#Sta/Elev= 30
  4732.5  299.00  4755.1  300.10  4782.4  300.19  4845.3  298.39  4885.3  296.57
  4905.4  295.26  4925.4  295.21  4965.5  292.43  4985.6  288.63  4992.6  286.40
  4995.3  285.90  4998.6  286.40  5005.6  286.57  5015.6  287.74  5035.7  288.06
  5075.8  286.95  5095.8  287.61  5115.9  287.32  5135.9  289.19  5166.0  293.54
  5183.8  294.93  5202.1  295.49  5263.3  298.69  5291.2  299.63  5307.8  301.15
  5358.0  303.14  5380.2  304.73  5419.2  306.31  5441.4  308.01  5468.5  309.28
#Mann=3,-1,0
  4732.5    0.16       0  4992.6    0.07       0  4998.6    0.16       0
Bank Sta=4992.6,4998.6
Exp/Cntr=0.3,0.1

Type RM Length L Ch R = 1,1486,0,0,0
BEGIN DESCRIPTION:
LITTLE CEDAR CREEK TRIBUTARY 2 1.0
END DESCRIPTION:
XS GIS Cut Line= 3
      3571620.63     10324154.61      3572338.05     10324437.80
      3572778.47     10324223.24
#Sta/Elev= 30
  4533.2  293.49  4545.5  293.22  4563.8  290.81  4616.6  290.34  4654.4  290.58
  4721.2  293.72  4771.3  295.34  4864.1  294.00  4869.5  293.09  4888.5  292.94
  4964.8  288.36  4999.1  284.32  5001.8  283.82  5005.1  284.32  5007.8  285.28
  5026.5  285.58  5072.3  284.66  5080.6  285.34  5086.0  284.46  5115.7  286.93
  5139.4  287.40  5244.0  288.95  5350.4  287.95  5440.5  288.52  5575.8  292.68
  5603.9  293.42  5687.8  297.95  5709.5  297.96  5758.5  301.85  5794.4  304.44
#Mann=11,-1,0
  4533.2    0.05       0  4616.6    0.16       0  4654.4     0.1       0
  4721.2    0.16       0  4999.1    0.07       0  5005.1    0.16       0
  5139.4     0.1       0  5244.0    0.16       0  5575.8     0.1       0
  5687.8    0.05       0  5758.5    0.16       0
Bank Sta=4999.1,5005.1
Exp/Cntr=0.3,0.1

Chan Stop Cuts=-1