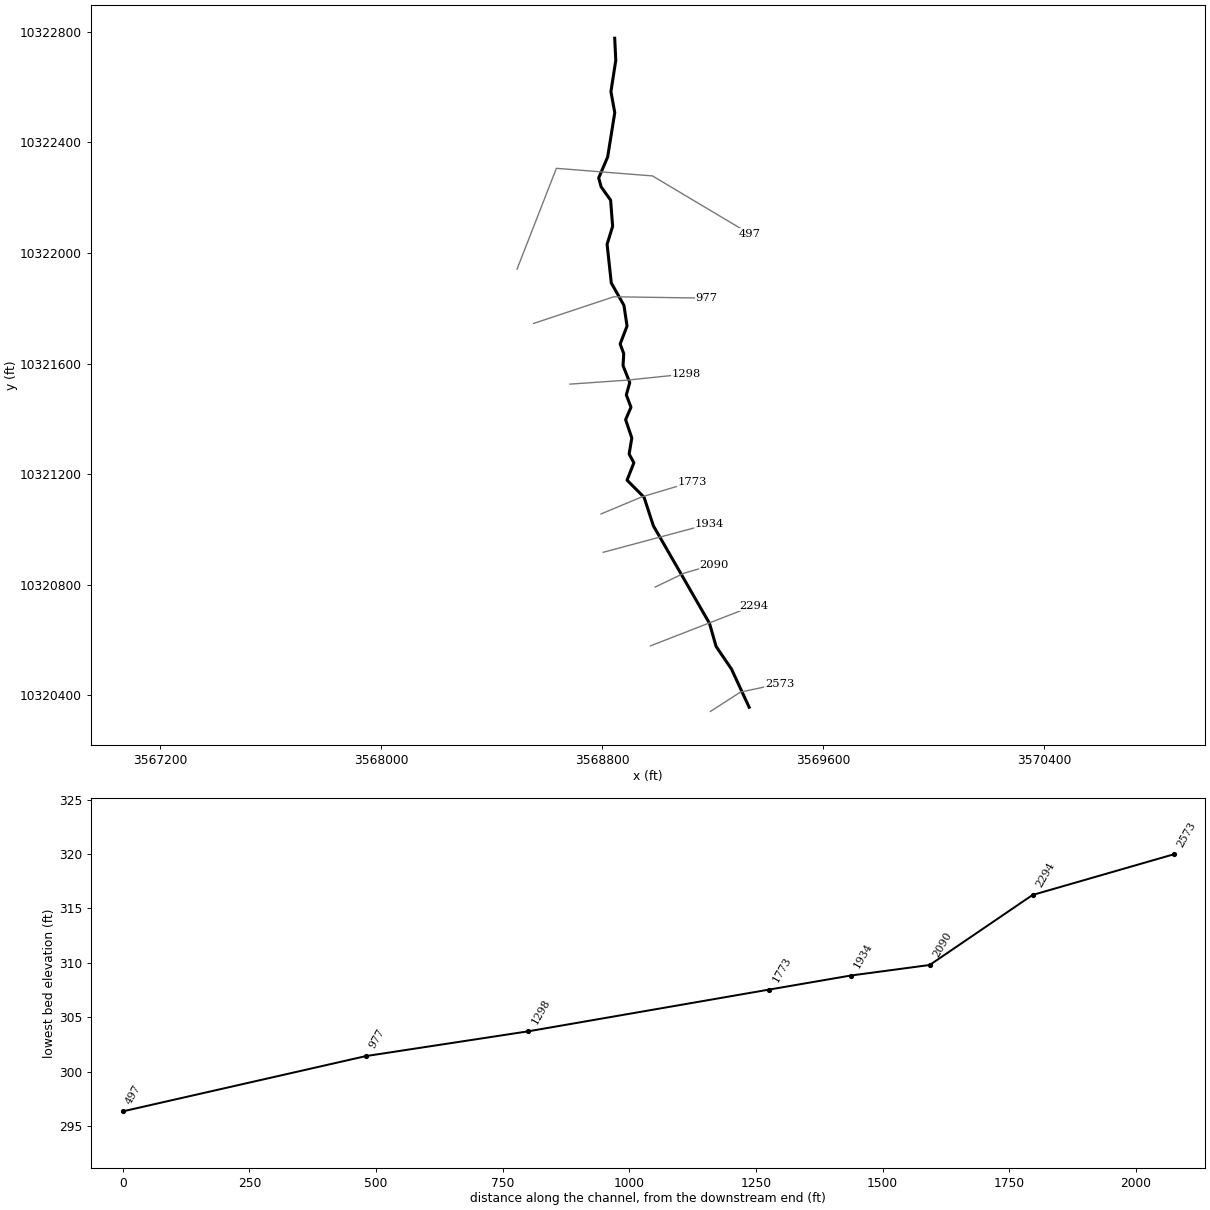
--- LITTLE CEDAR CREEK TRIBUTARY 4 1.prj (project) ---

Proj Title=LITTLE CEDAR CREEK TRIBUTARY 4 1 Base Level Engineering
Current Plan=p01
Default Exp/Contr=0.3,0.1
English Units
Geom File=g01
Flow File=f01
Plan File=p01
Y Axis Title=Elevation
X Axis Title(PF)=Main Channel Distance
X Axis Title(XS)=Station
BEGIN DESCRIPTION:
LITTLE CEDAR CREEK TRIBUTARY 4 1
END DESCRIPTION:
DSS Export Rating Curves= 0
DSS Export Rating Curve Sorted= 0
DSS Export Volume Flow Curves= 0
DXF OffsetX= 0
DXF OffsetY= 0
DXF ScaleX= 1
DXF ScaleY= 10

--- LITTLE CEDAR CREEK TRIBUTARY 4 1.p01 (plan) ---

Plan Title=Multiple Run
Short Identifier=Multiple
Geom File=g01
Flow File=f01
Subcritical Flow
K Sum by GR= 0
Std Step Tol= 0.01
Critical Tol= 0.01
Num of Std Step Trials= 20
Max Error Tol= 0.3
Flow Tol Ratio= 0.001
Split Flow NTrial= 30
Split Flow Tol= 0.02
Split Flow Ratio= 0.02
Log Output Level= 0
Friction Slope Method= 1
Unsteady Friction Slope Method= 2
Unsteady Bridges Friction Slope Method= 1
Parabolic Critical Depth
Global Vel Dist=  1 , 1 , 1
Global Log Level= 0
CheckData=True
Encroach Param= -1, 0, 0, 0
BEGIN DESCRIPTION:
Multiple Run
END DESCRIPTION:

--- LITTLE CEDAR CREEK TRIBUTARY 4 1.f01 (steady flow) ---

Flow Title=Multiple
Program Version=4.10
Number of Profiles= 7
Profile Names=10-year,25-year,50-year,1pct_min,100-year,1pct_plu,500-year
River Rch & RM=LITTLE CEDAR CRE,Reach-1         ,2573
     128     156     176     148     200     270     255
Boundary for River Rch & Prof#=LITTLE CEDAR CRE,Reach-1         , 1
Up Type= 0
Dn Type= 3
Dn Slope=0.005
Boundary for River Rch & Prof#=LITTLE CEDAR CRE,Reach-1         , 2
Up Type= 0
Dn Type= 3
Dn Slope=0.005
Boundary for River Rch & Prof#=LITTLE CEDAR CRE,Reach-1         , 3
Up Type= 0
Dn Type= 3
Dn Slope=0.005
Boundary for River Rch & Prof#=LITTLE CEDAR CRE,Reach-1         , 4
Up Type= 0
Dn Type= 3
Dn Slope=0.005
Boundary for River Rch & Prof#=LITTLE CEDAR CRE,Reach-1         , 5
Up Type= 0
Dn Type= 3
Dn Slope=0.005
Boundary for River Rch & Prof#=LITTLE CEDAR CRE,Reach-1         , 6
Up Type= 0
Dn Type= 3
Dn Slope=0.005
Boundary for River Rch & Prof#=LITTLE CEDAR CRE,Reach-1         , 7
Up Type= 0
Dn Type= 3
Dn Slope=0.005
DSS Import GetInterval= 0
DSS Import GetPeak= 0
DSS Import FillOption= 0

--- LITTLE CEDAR CREEK TRIBUTARY 4 1.g01 (geometry) ---

Geom Title=Existing Conditions
Program Version=4.10

River Reach=LITTLE CEDAR CRE,Reach-1
Reach XY= 30
      3569332.11     10320356.64      3569268.24     10320494.76
      3569212.41     10320576.77      3569188.61     10320660.19
      3568985.47     10321013.04      3568951.71     10321116.53
      3568890.21     10321178.16      3568914.94     10321241.13
      3568897.73     10321272.76      3568907.48     10321330.76
      3568884.97     10321397.17      3568904.51       10321442.
      3568887.54     10321486.56      3568900.02     10321531.13
      3568875.69     10321592.76      3568878.26     10321636.02
      3568865.25     10321670.71      3568890.15     10321735.74
      3568879.04     10321810.32      3568833.19     10321891.62
      3568818.01     10322031.69      3568838.02     10322096.61
      3568830.73     10322191.11      3568796.47      10322239.3
      3568787.61     10322271.54      3568820.05     10322347.43
      3568845.76     10322507.76      3568831.86     10322583.92
      3568849.44     10322697.23      3568845.54     10322776.92

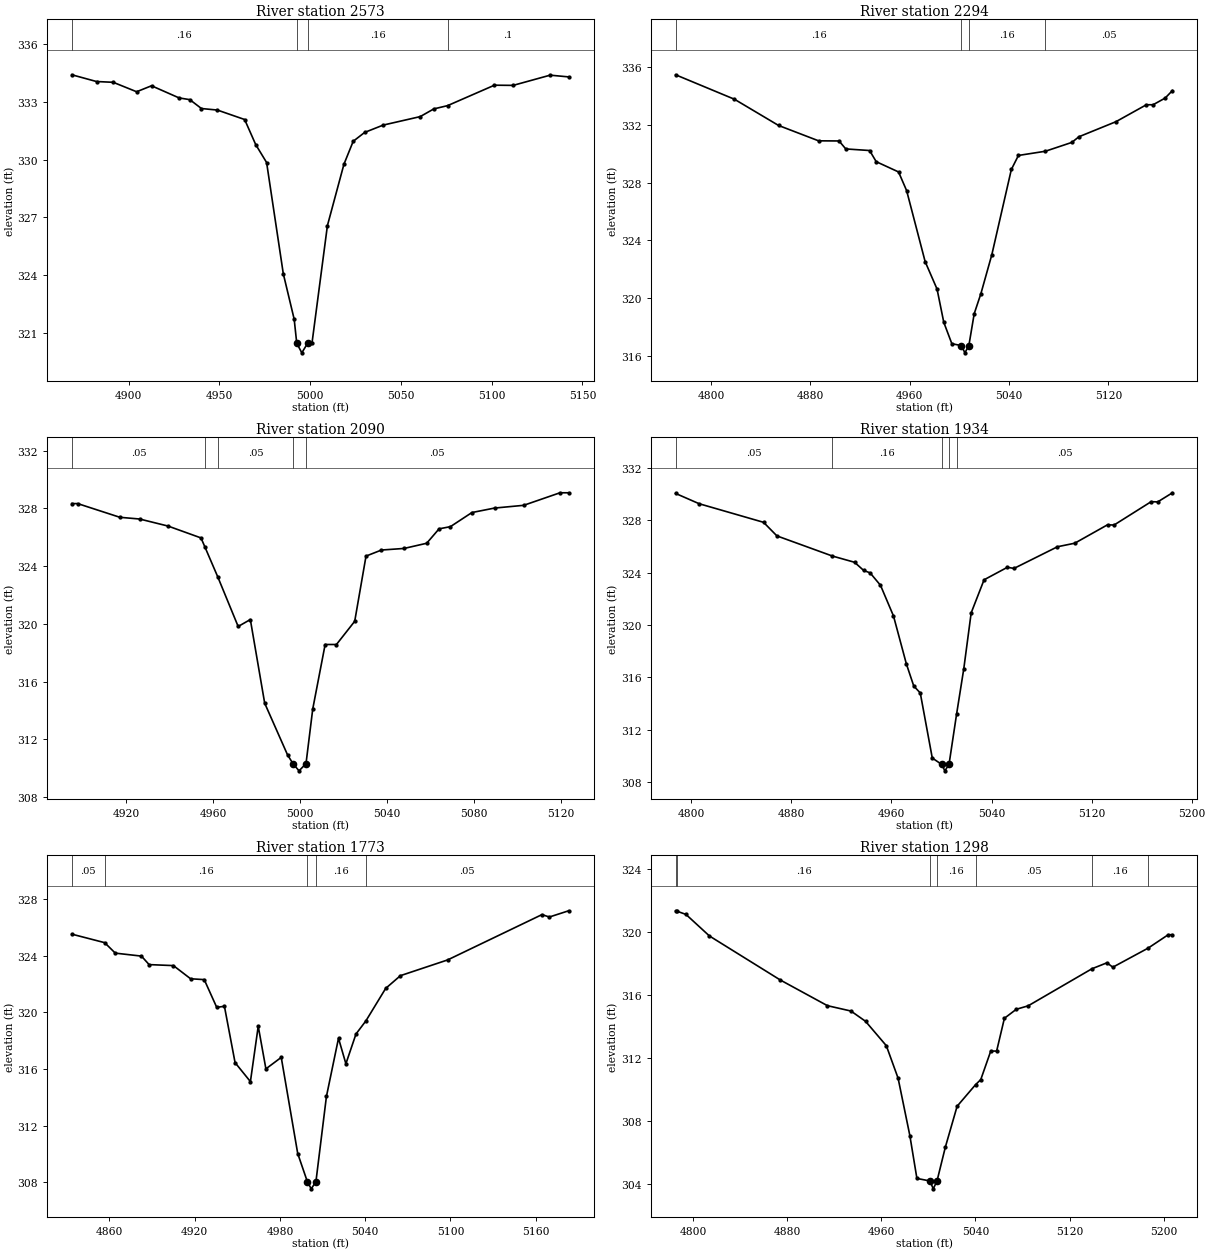
Type RM Length L Ch R = 1 ,2573    ,279,279,279
BEGIN DESCRIPTION:
LITTLE CEDAR CREEK TRIBUTARY 4.1 6.0
END DESCRIPTION:
XS GIS Cut Line= 3
      3569192.09     10320341.63      3569300.45     10320411.45
      3569442.07     10320441.63
#Sta/Elev= 30
  4868.7   334.4  4882.3  334.05  4891.5  334.01  4904.4  333.52  4912.6  333.83
  4927.8   333.2  4933.7  333.11  4940.1  332.65  4948.9  332.57  4963.9  332.08
    4970  330.78    4976  329.85  4985.2  324.08  4991.2  321.72  4992.6  320.48
  4995.4  319.98  4998.6  320.48    5001  320.48  5009.5  326.58  5018.6  329.76
  5023.7  330.95    5030  331.41  5040.2  331.79  5060.6  332.23  5068.1  332.63
  5075.7   332.8  5101.5  333.86  5111.8  333.85  5132.2  334.38  5142.4  334.29
#Mann= 4 ,-1 , 0
  4868.7     .16       0  4992.6     .07       0  4998.6     .16       0
  5075.7      .1       0
Bank Sta=4992.6,4998.6
XS Rating Curve= 0 ,0
Exp/Cntr=0.3,0.1

Type RM Length L Ch R = 1 ,2294    ,203,203,203
BEGIN DESCRIPTION:
Mapping XS 130fdf29
END DESCRIPTION:
XS GIS Cut Line= 2
      3568974.89     10320578.68      3569347.61     10320723.87
#Sta/Elev= 30
  4771.5  335.44  4818.9  333.75  4854.4  331.94  4886.6  330.88  4903.1  330.87
  4908.5  330.32  4927.7  330.21    4933  329.44    4951  328.73  4957.5  327.44
  4972.4  322.54    4982  320.64  4987.4  318.35  4993.9  316.87  5001.6  316.74
  5004.4  316.24  5007.6  316.74  5011.9  318.94  5017.3  320.33  5026.1  323.02
  5041.8   328.9  5047.5  329.87  5069.2  330.16  5090.5  330.77  5096.2  331.16
    5126   332.2  5150.5  333.37  5155.9  333.37  5165.6  333.83  5171.5  334.35
#Mann= 4 ,-1 , 0
  4771.5     .16       0  5001.6     .07       0  5007.6     .16       0
  5069.2     .05       0
Bank Sta=5001.6,5007.6
XS Rating Curve= 0 ,0
Exp/Cntr=0.3,0.1

Type RM Length L Ch R = 1 ,2090    ,156,156,156
BEGIN DESCRIPTION:
LITTLE CEDAR CREEK TRIBUTARY 4.1 5.0
END DESCRIPTION:
XS GIS Cut Line= 3
      3568992.14     10320791.66      3569097.33     10320842.01
      3569204.83       10320873.
#Sta/Elev= 30
  4895.1  328.34  4897.8  328.34  4917.2  327.39  4926.3  327.27  4939.4  326.78
  4954.5  325.96  4956.4   325.3  4962.3  323.23  4971.6  319.82  4977.2   320.3
  4983.8   314.5  4994.3  310.92  4996.8  310.31  4999.6  309.81  5002.8  310.31
  5005.9   314.1  5011.6  318.57  5016.8  318.57  5025.2  320.18  5030.4   324.7
  5037.5  325.12  5047.9  325.23  5058.3  325.59    5064  326.59  5069.2  326.74
  5079.1  327.72  5089.5  328.03  5102.9  328.22  5119.6  329.09  5123.6  329.09
#Mann= 5 ,-1 , 0
  4895.1     .05       0  4956.4     .16       0  4962.3     .05       0
  4996.8    .035       0  5002.8     .05       0
Bank Sta=4996.8,5002.8
XS Rating Curve= 0 ,0
Exp/Cntr=0.3,0.1

Type RM Length L Ch R = 1 ,1934    ,161,161,161
BEGIN DESCRIPTION:
Mapping XS a995cce6
END DESCRIPTION:
XS GIS Cut Line= 2
      3568803.87     10320917.22      3569187.55     10321019.96
#Sta/Elev= 30
  4787.4  330.07  4806.3  329.28  4857.7  327.86  4868.4  326.82  4912.7  325.28
  4930.5   324.8  4937.7  324.18  4942.9  323.99  4951.2  323.04  4961.6  320.69
  4971.9  317.02  4977.8  315.33    4983   314.8  4992.6  309.82    5000  309.34
  5002.7  308.84    5006  309.34    5012  313.16  5017.8  316.66  5023.7  320.93
    5034  323.46  5052.7  324.42  5057.9  324.33  5092.7  325.99  5106.5  326.26
  5132.7  327.67  5137.9  327.65  5167.6  329.44  5172.8  329.42  5184.6  330.12
#Mann= 5 ,-1 , 0
  4787.4     .05       0  4912.7     .16       0    5000     .07       0
    5006     .16       0    5012     .05       0
Bank Sta=5000,5006
XS Rating Curve= 0 ,0
Exp/Cntr=0.3,0.1

Type RM Length L Ch R = 1 ,1773    ,475,475,475
BEGIN DESCRIPTION:
LITTLE CEDAR CREEK TRIBUTARY 4.1 4.0
END DESCRIPTION:
XS GIS Cut Line= 3
      3568796.15     10321055.97      3568944.55     10321118.05
      3569125.55     10321171.87
#Sta/Elev= 30
  4833.5  325.53  4856.6  324.93  4864.1  324.19  4882.5  323.98  4887.9  323.38
    4905  323.31  4917.1  322.38  4926.7  322.32  4935.5  320.36  4940.9  320.44
  4948.4  316.46  4959.2  315.12  4964.7  319.03  4970.1  316.02  4980.9  316.83
  4992.5  310.04  4999.3  308.05    5002  307.55  5005.3  308.05  5012.7  314.07
  5021.2  318.18  5026.4  316.38  5033.5  318.48  5040.5  319.41  5054.4   321.7
  5064.8   322.6    5098  323.71  5164.4  326.91  5169.6  326.74  5183.2  327.18
#Mann= 5 ,-1 , 0
  4833.5     .05       0  4856.6     .16       0  4999.3     .07       0
  5005.3     .16       0  5040.5     .05       0
Bank Sta=4999.3,5005.3
XS Rating Curve= 0 ,0
Exp/Cntr=0.3,0.1

Type RM Length L Ch R = 1 ,1298    ,321,321,321
BEGIN DESCRIPTION:
LITTLE CEDAR CREEK TRIBUTARY 4.1 3.0
END DESCRIPTION:
XS GIS Cut Line= 3
      3568683.35     10321525.61        3568889.     10321539.93
       3569104.2     10321562.21
#Sta/Elev= 30
    4785  321.36  4786.3  321.33  4793.8  321.13  4813.8  319.76    4874  316.97
  4914.1  315.34  4934.1     315  4946.5  314.35  4964.2   312.8  4974.2  310.74
  4984.2   307.1  4990.2  304.38  5001.3  304.22  5004.1  303.72  5007.3  304.22
  5014.4  306.37  5024.4  308.96  5040.1  310.33  5044.5  310.65    5053  312.46
    5058  312.46  5064.6  314.54  5074.7  315.11  5084.8  315.33    5139  317.68
  5151.8  318.06  5156.8  317.78  5186.8  318.99  5203.9  319.84  5207.5  319.84
#Mann= 7 ,-1 , 0
    4785     .05       0  4786.3     .16       0  5001.3     .07       0
  5007.3     .16       0  5040.1     .05       0    5139     .16       0
  5186.8     .05       0
Bank Sta=5001.3,5007.3
XS Rating Curve= 0 ,0
Exp/Cntr=0.3,0.1

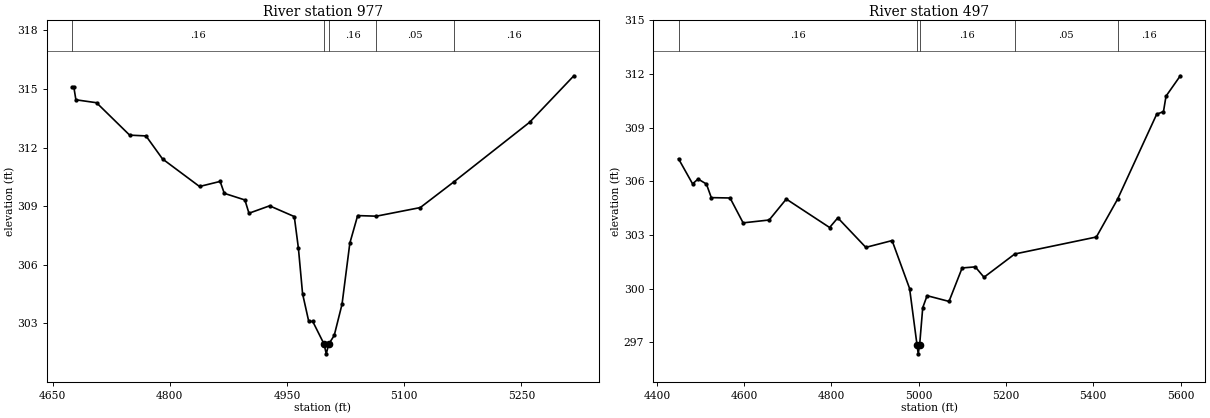
Type RM Length L Ch R = 1 ,977     ,480,480,480
BEGIN DESCRIPTION:
LITTLE CEDAR CREEK TRIBUTARY 4.1 2.0
END DESCRIPTION:
XS GIS Cut Line= 3
      3568552.19     10321745.18      3568842.11     10321841.64
      3569178.73      10321836.7
#Sta/Elev= 30
    4675  315.09  4677.3  315.09  4679.9  314.45  4706.3   314.3  4748.7  312.64
  4769.6   312.6  4790.8  311.42  4838.1  310.01  4864.5  310.27  4869.8  309.66
  4896.2  309.32  4901.4  308.64  4927.8  309.02  4959.4  308.47  4964.7  306.84
    4970  304.52  4977.9   303.1    4983   303.1  4997.5  301.94  5000.3  301.44
  5003.5  301.94  5010.5  302.38  5020.5  303.98  5030.5  307.11  5040.5  308.52
  5064.5  308.49  5120.6  308.93  5163.4  310.24  5260.6   313.3  5317.2  315.68
#Mann= 5 ,-1 , 0
    4675     .16       0  4997.5     .07       0  5003.5     .16       0
  5064.5     .05       0  5163.4     .16       0
Bank Sta=4997.5,5003.5
XS Rating Curve= 0 ,0
Exp/Cntr=0.3,0.1

Type RM Length L Ch R = 1 ,497     ,0,0,0
BEGIN DESCRIPTION:
LITTLE CEDAR CREEK TRIBUTARY 4.1 1.0
END DESCRIPTION:
XS GIS Cut Line= 4
      3568492.11     10321941.65      3568634.53     10322306.31
      3568982.19     10322278.87      3569334.13     10322069.17
#Sta/Elev= 30
  4449.7  307.26  4481.9  305.86  4494.5  306.13  4513.6  305.85  4524.8  305.09
  4567.8  305.07  4597.7  303.68  4657.4  303.84  4696.6  305.01  4795.9  303.42
  4814.7  303.96  4878.9  302.31  4939.1  302.69  4979.2  300.01  4996.2  296.86
    4999  296.36  5002.2  296.86  5009.3  298.94  5019.3  299.61  5069.5  299.29
  5099.6  301.16  5129.7  301.22  5149.7  300.64  5220.2  301.94  5407.2  302.89
  5455.7     305  5545.4  309.75    5561   309.9  5566.8  310.76  5599.6   311.9
#Mann= 5 ,-1 , 0
  4449.7     .16       0  4996.2     .07       0  5002.2     .16       0
  5220.2     .05       0  5455.7     .16       0
Bank Sta=4996.2,5002.2
XS Rating Curve= 0 ,0
Exp/Cntr=0.3,0.1
Stream Node=LITTLE CEDAR CRE,Reach-1         , 0 , 0 ,Upstream end
Stream Node=LITTLE CEDAR CRE,Reach-1         , 0 , 1 ,Downstream end

Chan Stop Cuts=-1
Use User Specified Reach Order=0
Composite Channel Slope=5