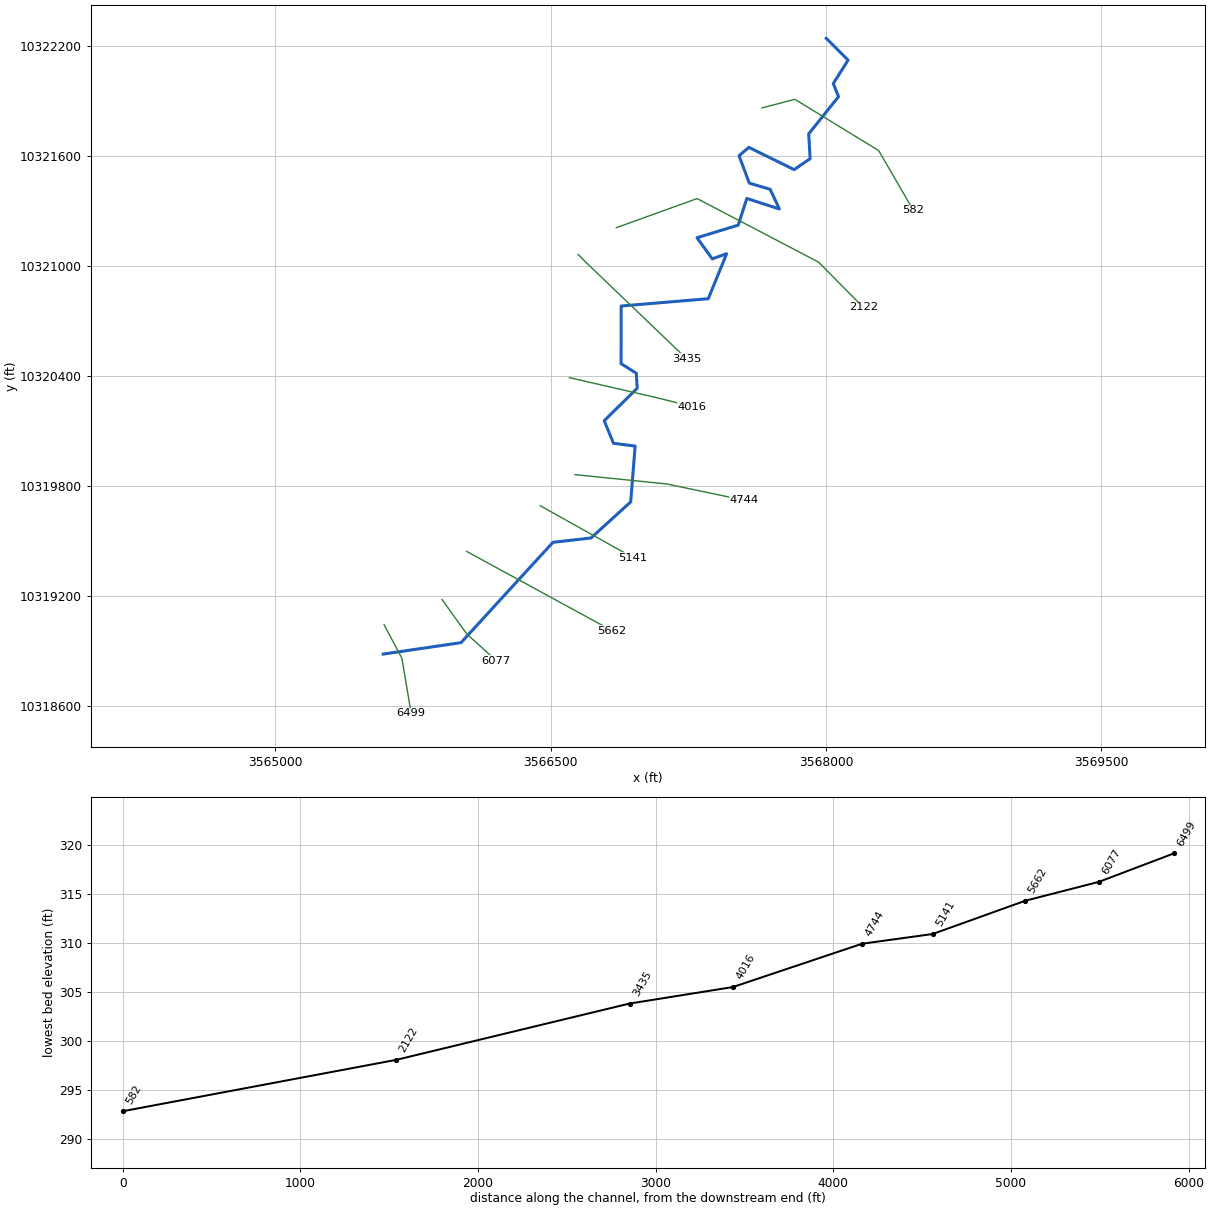
--- LITTLE CEDAR CREEK TRIBUTARY 4.prj (project) ---

Proj Title=LITTLE CEDAR CREEK TRIBUTARY 4 Base Level Engineering
Current Plan=p01
Default Exp/Contr=0.3,0.1
English Units
Geom File=g01
Flow File=f01
Plan File=p01
BEGIN DESCRIPTION:
LITTLE CEDAR CREEK TRIBUTARY 4
END DESCRIPTION:

--- LITTLE CEDAR CREEK TRIBUTARY 4.p01 (plan) ---

Plan Title=Multiple Run
Short Identifier=Multiple
Geom File=g01
Flow File=f01
Subcritical Flow
K Sum by GR= 0
Std Step Tol= 0.01
Critical Tol= 0.01
Num of Std Step Trials= 20
Max Error Tol= 0.3
Flow Tol Ratio= 0.001
Split Flow NTrial= 30
Split Flow Tol= 0.02
Split Flow Ratio= 0.02
Log Output Level= 0
Friction Slope Method= 1
Unsteady Friction Slope Method= 2
Unsteady Bridges Friction Slope Method= 1
Parabolic Critical Depth
Global Vel Dist=  1 , 1 , 1
Global Log Level= 0
CheckData=True
Encroach Param= -1, 0, 0, 0
BEGIN DESCRIPTION:
Multiple Run
END DESCRIPTION:

--- LITTLE CEDAR CREEK TRIBUTARY 4.f01 (steady flow) ---

Flow Title=Multiple
Number of Profiles=7
Profile Names=10-year,25-year,50-year,1pct_min,100-year,1pct_plu,500-year
River Rch & RM= LITTLE CEDAR CRE,Reach-1,6499
     486     650     781     689     932    1260    1328
Boundary for River Rch & Prof#=LITTLE CEDAR CRE,Reach-1,1
Up Type=0
Dn Type=3
Dn Slope=0.005
Boundary for River Rch & Prof#=LITTLE CEDAR CRE,Reach-1,2
Up Type=0
Dn Type=3
Dn Slope=0.005
Boundary for River Rch & Prof#=LITTLE CEDAR CRE,Reach-1,3
Up Type=0
Dn Type=3
Dn Slope=0.005
Boundary for River Rch & Prof#=LITTLE CEDAR CRE,Reach-1,4
Up Type=0
Dn Type=3
Dn Slope=0.005
Boundary for River Rch & Prof#=LITTLE CEDAR CRE,Reach-1,5
Up Type=0
Dn Type=3
Dn Slope=0.005
Boundary for River Rch & Prof#=LITTLE CEDAR CRE,Reach-1,6
Up Type=0
Dn Type=3
Dn Slope=0.005
Boundary for River Rch & Prof#=LITTLE CEDAR CRE,Reach-1,7
Up Type=0
Dn Type=3
Dn Slope=0.005

--- LITTLE CEDAR CREEK TRIBUTARY 4.g01 (geometry) ---

Geom Title=Existing Conditions

River Reach=LITTLE CEDAR CRE,Reach-1
Reach XY= 30
      3565587.18     10318881.38      3566011.38     10318943.88
      3566512.13     10319491.21      3566720.32     10319515.16
      3566935.98     10319711.94      3566960.31     10320016.45
      3566842.29     10320031.77      3566791.81     10320154.92
      3566971.55     10320331.92      3566966.64     10320414.04
      3566883.48     10320466.65      3566884.31     10320780.93
      3567358.82     10320820.71      3567459.10     10321066.37
      3567380.65     10321038.24      3567297.64     10321153.43
      3567522.17     10321222.21      3567568.98     10321367.81
      3567746.48     10321310.37      3567696.43     10321417.55
      3567582.55     10321451.69      3567526.63     10321600.98
      3567580.02     10321646.63      3567827.19     10321525.25
      3567914.19     10321584.88      3567906.31     10321720.26
      3568068.89     10321923.25      3568040.35     10321995.01
      3568120.92     10322122.63      3568002.11     10322241.64

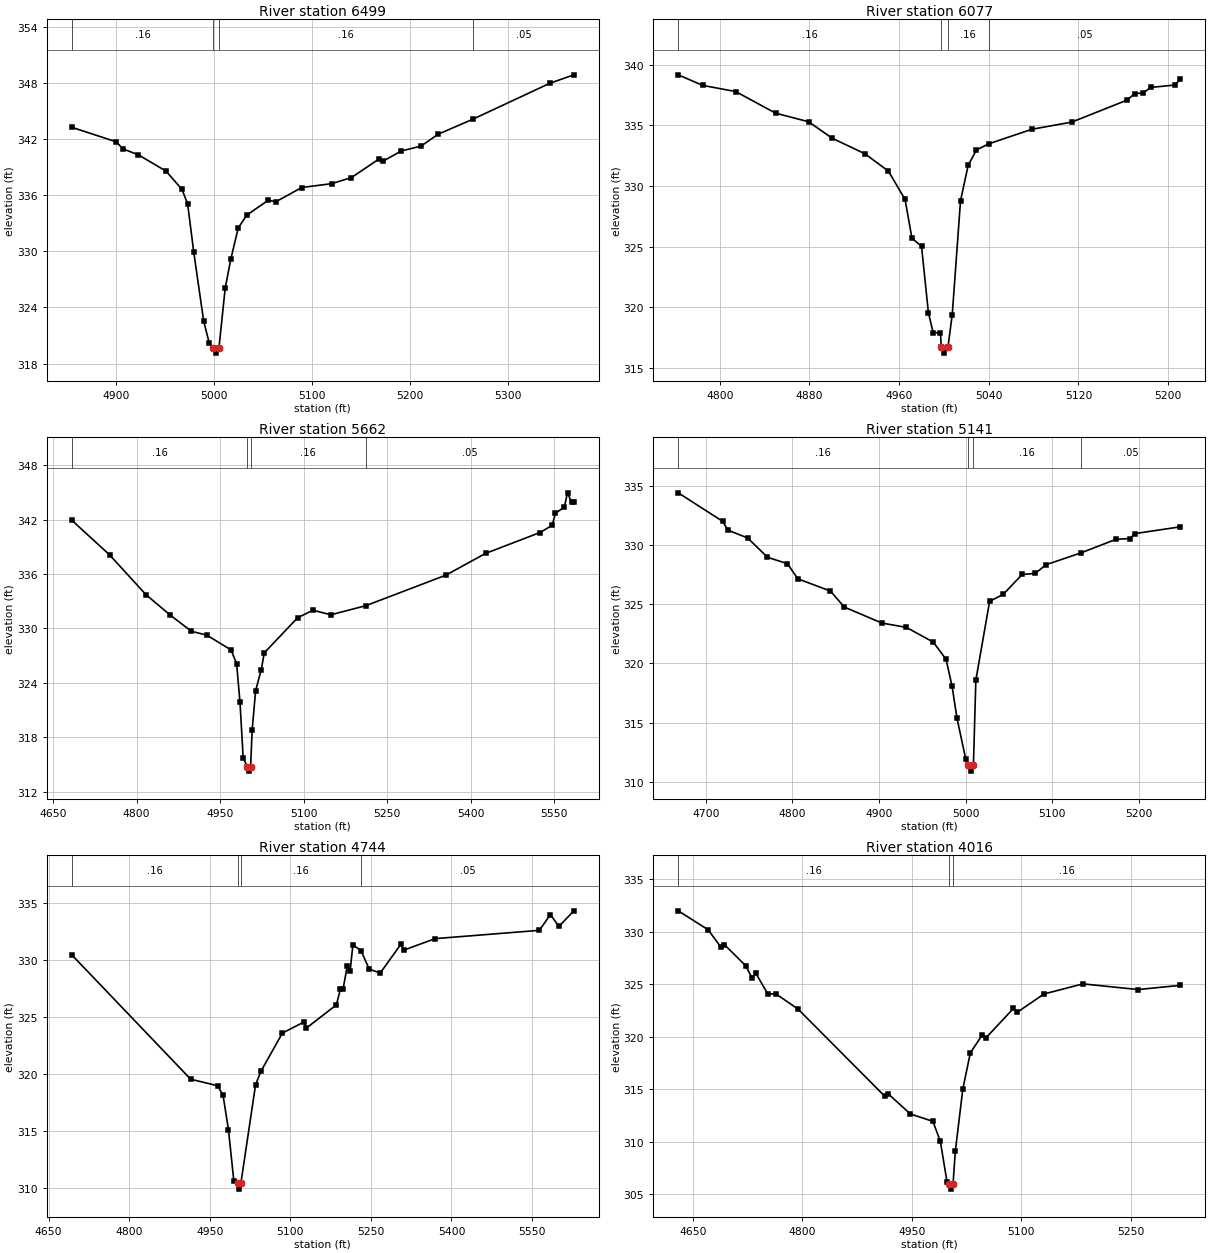
Type RM Length L Ch R = 1,6499,422,422,422
BEGIN DESCRIPTION:
LITTLE CEDAR CREEK TRIBUTARY 4 11.0
END DESCRIPTION:
XS GIS Cut Line= 3
      3565592.09     10319041.68      3565689.49     10318857.77
      3565739.48     10318557.82
#Sta/Elev= 30
  4854.7  343.27  4900.0  341.72  4906.9  340.96  4922.6  340.33  4950.9  338.58
  4967.2  336.62  4972.9  335.07  4979.2  329.89  4989.2  322.58  4994.9  320.21
  4998.8  319.62  5001.6  319.12  5004.8  319.62  5011.2  326.05  5016.9  329.15
  5024.5  332.50  5033.2  333.87  5055.2  335.48  5062.8  335.30  5089.3  336.83
  5119.7  337.24  5140.0  337.89  5167.7  339.85  5172.7  339.67  5190.7  340.73
  5211.0  341.26  5228.5  342.53  5264.0  344.14  5342.7  347.99  5366.9  348.88
#Mann=4,-1,0
  4854.7    0.16       0  4998.8    0.07       0  5004.8    0.16       0
  5264.0    0.05       0
Bank Sta=4998.8,5004.8
Exp/Cntr=0.3,0.1

Type RM Length L Ch R = 1,6077,415,415,415
BEGIN DESCRIPTION:
LITTLE CEDAR CREEK TRIBUTARY 4 10.0
END DESCRIPTION:
XS GIS Cut Line= 3
      3565907.83     10319179.14      3566042.11     10318991.64
      3566203.14     10318845.62
#Sta/Elev= 30
  4762.9  339.15  4784.7  338.28  4814.2  337.77  4849.8  335.99  4879.3  335.28
  4900.2  333.93  4929.6  332.64  4950.5  331.21  4965.3  328.88  4971.4  325.70
  4980.0  325.01  4986.1  319.56  4990.4  317.90  4996.9  317.90  4997.6  316.72
  5000.4  316.22  5003.6  316.72  5007.4  319.40  5014.8  328.79  5021.6  331.69
  5029.0  332.96  5039.8  333.46  5078.3  334.66  5114.2  335.26  5163.5  337.07
  5170.2  337.61  5177.7  337.65  5184.4  338.11  5206.1  338.31  5210.9  338.79
#Mann=4,-1,0
  4762.9    0.16       0  4997.6    0.07       0  5003.6    0.16       0
  5039.8    0.05       0
Bank Sta=4997.6,5003.6
Exp/Cntr=0.3,0.1

Type RM Length L Ch R = 1,5662,521,521,521
BEGIN DESCRIPTION:
LITTLE CEDAR CREEK TRIBUTARY 4 9.0
END DESCRIPTION:
XS GIS Cut Line= 2
      3566042.11     10319441.64      3566834.10     10319009.53
#Sta/Elev= 30
  4683.5  341.92  4751.4  338.11  4816.9  333.72  4860.5  331.47  4898.5  329.69
  4926.0  329.27  4969.7  327.64  4979.7  326.13  4985.8  321.86  4991.5  315.76
  4998.9  314.79  5001.7  314.29  5004.9  314.79  5007.6  318.77  5013.9  323.16
  5023.8  325.42  5029.5  327.32  5089.3  331.18  5116.8  332.01  5149.1  331.51
  5211.9  332.51  5355.6  335.87  5427.2  338.27  5524.9  340.57  5546.8  341.36
  5552.5  342.68  5568.6  343.37  5574.3  344.94  5581.7  343.88  5585.7  343.88
#Mann=4,-1,0
  4683.5    0.16       0  4998.9    0.07       0  5004.9    0.16       0
  5211.9    0.05       0
Bank Sta=4998.9,5004.9
Exp/Cntr=0.3,0.1

Type RM Length L Ch R = 1,5141,397,397,397
BEGIN DESCRIPTION:
LITTLE CEDAR CREEK TRIBUTARY 4 8.0
END DESCRIPTION:
XS GIS Cut Line= 2
      3566442.10     10319691.64      3566948.24     10319408.41
#Sta/Elev= 30
  4668.1  334.39  4719.5  331.98  4725.4  331.24  4748.3  330.58  4771.2  328.95
  4794.2  328.41  4806.3  327.13  4843.9  326.10  4859.9  324.75  4903.3  323.40
  4931.7  323.03  4962.7  321.79  4977.5  320.34  4984.4  318.08  4990.1  315.37
  5000.3  311.89  5003.1  311.40  5005.8  310.90  5009.1  311.40  5011.9  318.58
  5027.8  325.23  5043.7  325.83  5065.4  327.50  5080.6  327.59  5092.9  328.32
  5133.7  329.33  5173.9  330.47  5189.9  330.53  5195.6  330.95  5248.1  331.52
#Mann=4,-1,0
  4668.1    0.16       0  5003.1    0.07       0  5009.1    0.16       0
  5133.7    0.05       0
Bank Sta=5003.1,5009.1
Exp/Cntr=0.3,0.1

Type RM Length L Ch R = 1,4744,728,728,728
BEGIN DESCRIPTION:
LITTLE CEDAR CREEK TRIBUTARY 4 7.0
END DESCRIPTION:
XS GIS Cut Line= 3
      3566631.89     10319860.78      3567131.48     10319809.98
      3567554.88     10319721.06
#Sta/Elev= 30
  4693.1  330.46  4914.5  319.55  4964.7  318.98  4974.8  318.13  4984.8  315.14
  4994.9  310.60  5001.9  310.41  5004.7  309.91  5007.9  310.41  5035.3  319.06
  5045.1  320.23  5085.3  323.60  5125.0  324.56  5130.0  324.04  5185.8  326.07
  5193.1  327.43  5198.1  327.43  5206.1  329.49  5211.4  329.05  5216.5  331.33
  5231.4  330.84  5247.0  329.21  5267.4  328.86  5306.0  331.40  5311.1  330.87
  5369.6  331.88  5563.8  332.61  5584.2  333.99  5600.1  332.95  5627.9  334.32
#Mann=4,-1,0
  4693.1    0.16       0  5001.9    0.07       0  5007.9    0.16       0
  5231.4    0.05       0
Bank Sta=5001.9,5007.9
Exp/Cntr=0.3,0.1

Type RM Length L Ch R = 1,4016,581,581,581
BEGIN DESCRIPTION:
LITTLE CEDAR CREEK TRIBUTARY 4 6.0
END DESCRIPTION:
XS GIS Cut Line= 3
      3566602.21     10320390.04      3567071.55     10320282.17
      3567271.52     10320232.18
#Sta/Elev= 30
  4630.2  331.97  4671.1  330.17  4688.3  328.55  4693.4  328.76  4722.4  326.76
  4731.1  325.61  4736.3  326.05  4753.2  324.02  4763.5  324.09  4794.3  322.62
  4912.8  314.35  4917.9  314.55  4948.2  312.64  4979.0  311.94  4989.2  310.04
  4998.4  306.17  5000.6  305.99  5003.3  305.49  5006.6  305.99  5009.7  309.08
  5020.0  315.01  5030.3  318.46  5046.4  320.13  5051.5  319.87  5089.3  322.68
  5094.4  322.31  5131.2  324.06  5184.5  325.02  5260.0  324.48  5317.9  324.88
#Mann=3,-1,0
  4630.2    0.16       0  5000.6    0.07       0  5006.6    0.16       0
Bank Sta=5000.6,5006.6
Exp/Cntr=0.3,0.1

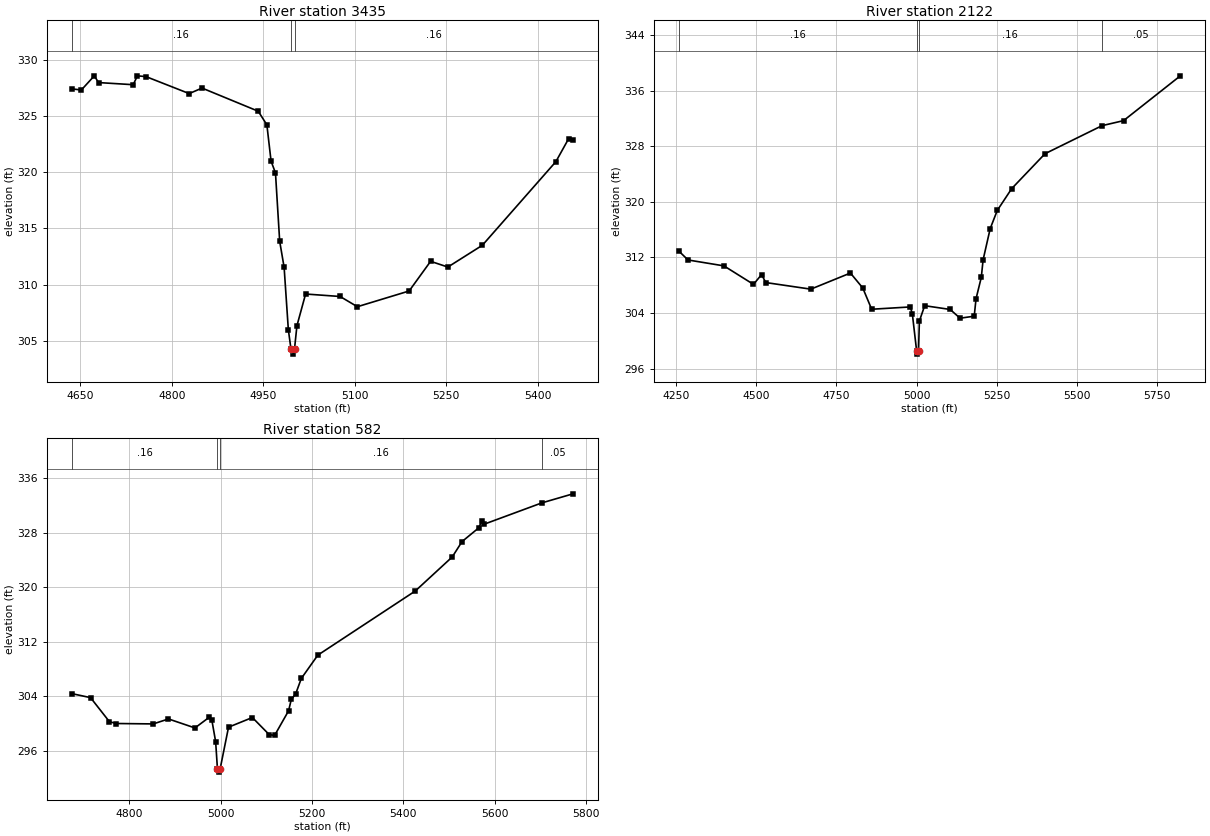
Type RM Length L Ch R = 1,3435,1313,1313,1313
BEGIN DESCRIPTION:
LITTLE CEDAR CREEK TRIBUTARY 4 4.0
END DESCRIPTION:
XS GIS Cut Line= 3
      3566649.97     10321061.80      3566699.96     10321011.81
      3567242.09     10320491.66
#Sta/Elev= 30
  4635.7  327.42  4651.5  327.32  4672.7  328.58  4679.7  327.98  4736.5  327.79
  4743.4  328.58  4757.5  328.51  4828.3  327.00  4849.4  327.49  4941.5  325.43
  4955.7  324.22  4962.6  320.98  4969.8  319.94  4976.7  313.86  4984.0  311.53
  4990.9  305.99  4995.1  304.31  4997.9  303.81  5001.1  304.31  5005.0  306.34
  5019.2  309.16  5075.8  308.94  5104.1  308.03  5189.0  309.43  5224.2  312.07
  5252.5  311.56  5309.1  313.50  5429.6  320.94  5450.7  323.00  5457.7  322.87
#Mann=3,-1,0
  4635.7    0.16       0  4995.1    0.07       0  5001.1    0.16       0
Bank Sta=4995.1,5001.1
Exp/Cntr=0.3,0.1

Type RM Length L Ch R = 1,2122,1540,1540,1540
BEGIN DESCRIPTION:
Mapping XS 8d5844cb
END DESCRIPTION:
XS GIS Cut Line= 4
      3566857.93     10321208.31      3567298.02     10321367.16
      3567959.47     10321020.80      3568204.29     10320773.38
#Sta/Elev= 30
  4259.8  312.87  4287.6  311.62  4399.6  310.77  4491.7  308.11  4517.0  309.52
  4530.0  308.37  4670.4  307.42  4793.9  309.74  4832.4  307.59  4860.1  304.53
  4980.6  304.86  4986.9  303.87  5000.2  298.57  5003.0  298.07  5006.2  298.57
  5008.9  302.84  5025.4  305.04  5104.8  304.50  5135.7  303.24  5179.8  303.53
  5185.5  306.04  5201.9  309.12  5207.5  311.64  5229.6  316.13  5251.7  318.75
  5296.7  321.89  5400.5  326.91  5578.4  330.95  5645.3  331.67  5822.4  338.12
#Mann=4,-1,0
  4259.8    0.16       0  5000.2    0.07       0  5006.2    0.16       0
  5578.4    0.05       0
Bank Sta=5000.2,5006.2
Exp/Cntr=0.3,0.1

Type RM Length L Ch R = 1,582,0,0,0
BEGIN DESCRIPTION:
LITTLE CEDAR CREEK TRIBUTARY 4 1.0
END DESCRIPTION:
XS GIS Cut Line= 4
      3567652.21     10321861.96      3567831.00     10321908.83
      3568287.60     10321629.31      3568476.85     10321302.89
#Sta/Elev= 30
  4673.9  304.36  4715.1  303.77  4756.5  300.23  4771.6  299.97  4852.4  299.91
  4885.7  300.64  4943.7  299.32  4974.6  300.87  4980.5  300.54  4989.0  297.30
  4992.9  293.33  4995.7  292.83  4998.9  293.33  5017.2  299.43  5069.4  300.85
  5106.1  298.35  5118.0  298.21  5148.7  301.84  5154.6  303.50  5164.2  304.32
  5176.6  306.59  5212.7  310.01  5426.1  319.43  5507.0  324.43  5528.5  326.69
  5564.8  328.69  5571.5  329.69  5577.3  329.25  5703.2  332.37  5771.4  333.70
#Mann=4,-1,0
  4673.9    0.16       0  4992.9    0.07       0  4998.9    0.16       0
  5703.2    0.05       0
Bank Sta=4992.9,4998.9
Exp/Cntr=0.3,0.1

Chan Stop Cuts=-1