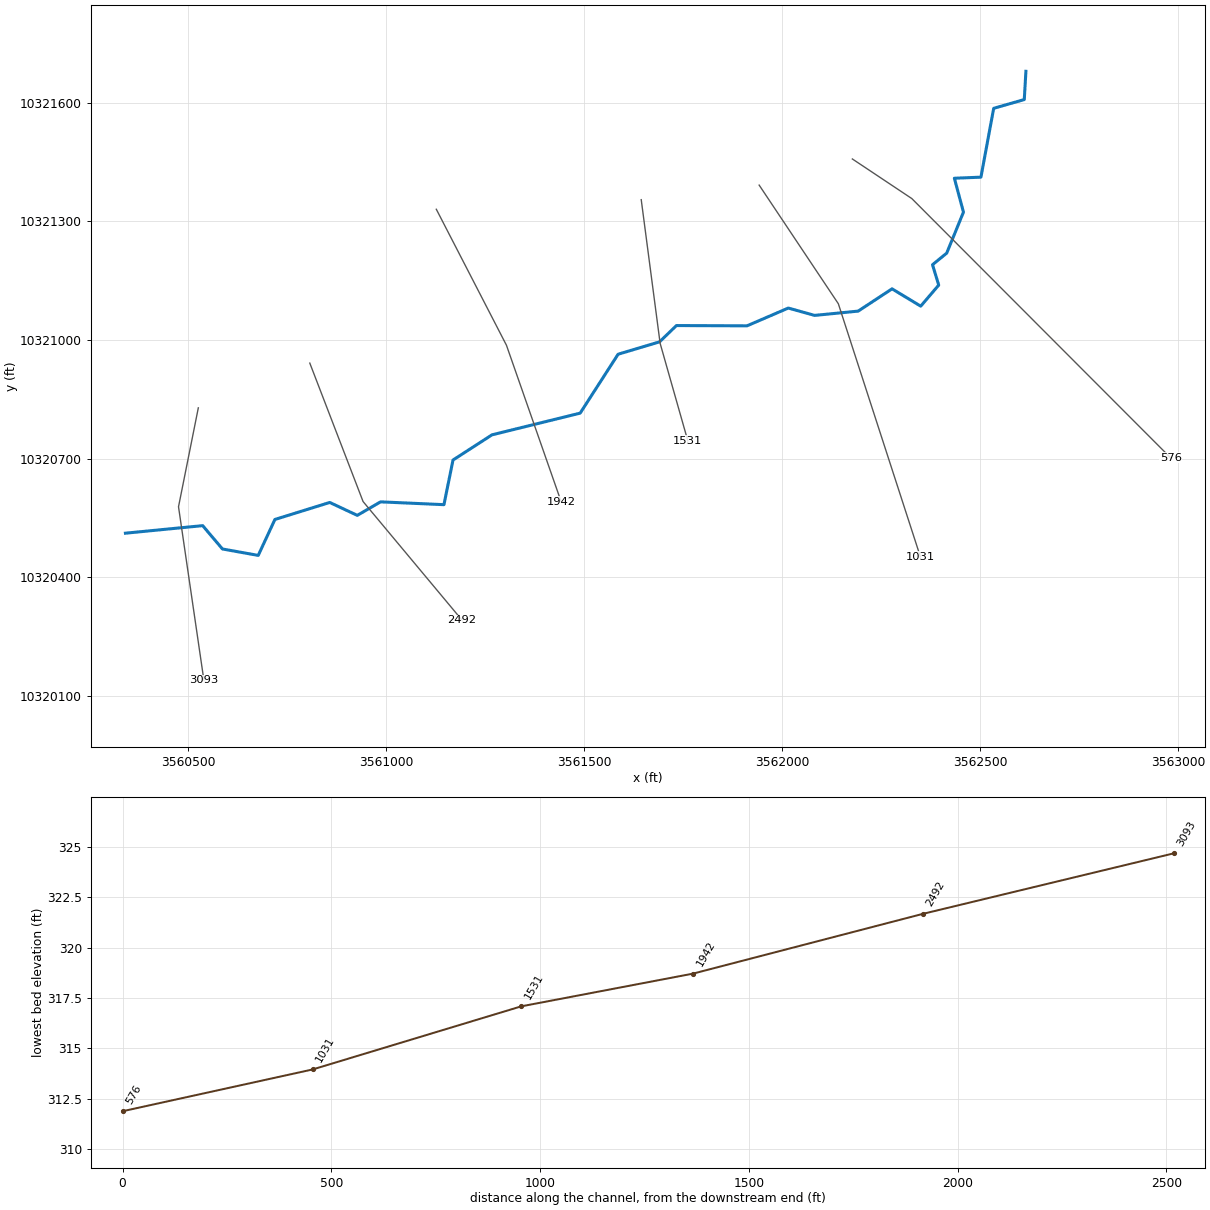
--- LITTLE CEDAR CREEK TRIBUTARY 6.prj (project) ---

Proj Title=LITTLE CEDAR CREEK TRIBUTARY 6 Base Level Engineering
Current Plan=p01
Default Exp/Contr=0.3,0.1
English Units
Geom File=g01
Flow File=f01
Plan File=p01
BEGIN DESCRIPTION:
LITTLE CEDAR CREEK TRIBUTARY 6
END DESCRIPTION:

--- LITTLE CEDAR CREEK TRIBUTARY 6.p01 (plan) ---

Plan Title=Multiple Run
Short Identifier=Multiple
Geom File=g01
Flow File=f01
Subcritical Flow
K Sum by GR= 0
Std Step Tol= 0.01
Critical Tol= 0.01
Num of Std Step Trials= 20
Max Error Tol= 0.3
Flow Tol Ratio= 0.001
Split Flow NTrial= 30
Split Flow Tol= 0.02
Split Flow Ratio= 0.02
Log Output Level= 0
Friction Slope Method= 1
Unsteady Friction Slope Method= 2
Unsteady Bridges Friction Slope Method= 1
Parabolic Critical Depth
Global Vel Dist=  1 , 1 , 1
Global Log Level= 0
CheckData=True
Encroach Param= -1, 0, 0, 0
BEGIN DESCRIPTION:
Multiple Run
END DESCRIPTION:

--- LITTLE CEDAR CREEK TRIBUTARY 6.f01 (steady flow) ---

Flow Title=Multiple
Number of Profiles=7
Profile Names=10-year,25-year,50-year,1pct_min,100-year,1pct_plu,500-year
River Rch & RM= LITTLE CEDAR CRE,Reach-1,3093
     517     693     835     738     998    1350    1428
Boundary for River Rch & Prof#=LITTLE CEDAR CRE,Reach-1,1
Up Type=0
Dn Type=3
Dn Slope=0.005
Boundary for River Rch & Prof#=LITTLE CEDAR CRE,Reach-1,2
Up Type=0
Dn Type=3
Dn Slope=0.005
Boundary for River Rch & Prof#=LITTLE CEDAR CRE,Reach-1,3
Up Type=0
Dn Type=3
Dn Slope=0.005
Boundary for River Rch & Prof#=LITTLE CEDAR CRE,Reach-1,4
Up Type=0
Dn Type=3
Dn Slope=0.005
Boundary for River Rch & Prof#=LITTLE CEDAR CRE,Reach-1,5
Up Type=0
Dn Type=3
Dn Slope=0.005
Boundary for River Rch & Prof#=LITTLE CEDAR CRE,Reach-1,6
Up Type=0
Dn Type=3
Dn Slope=0.005
Boundary for River Rch & Prof#=LITTLE CEDAR CRE,Reach-1,7
Up Type=0
Dn Type=3
Dn Slope=0.005

--- LITTLE CEDAR CREEK TRIBUTARY 6.g01 (geometry) ---

Geom Title=Existing Conditions

River Reach=LITTLE CEDAR CRE,Reach-1
Reach XY= 30
      3560342.11     10320511.64      3560537.14     10320530.71
      3560587.00     10320471.75      3560677.40     10320455.46
      3560719.51     10320546.33      3560857.91     10320589.33
      3560927.53     10320556.72      3560986.22     10320590.84
      3561146.31     10320583.76      3561169.20     10320696.61
      3561267.67     10320760.27      3561490.24     10320815.12
      3561586.07     10320964.08      3561690.59     10320995.28
      3561733.33     10321036.52      3561911.44     10321035.82
      3562015.76     10321080.76      3562082.22     10321062.20
      3562192.14     10321073.03      3562277.71     10321129.35
      3562350.08     10321085.56      3562395.52     10321138.82
      3562379.85     10321190.29      3562415.69     10321219.60
      3562458.01     10321323.23      3562435.05     10321408.95
      3562502.11     10321411.64      3562534.35     10321585.68
      3562611.55     10321607.81      3562615.69     10321679.24

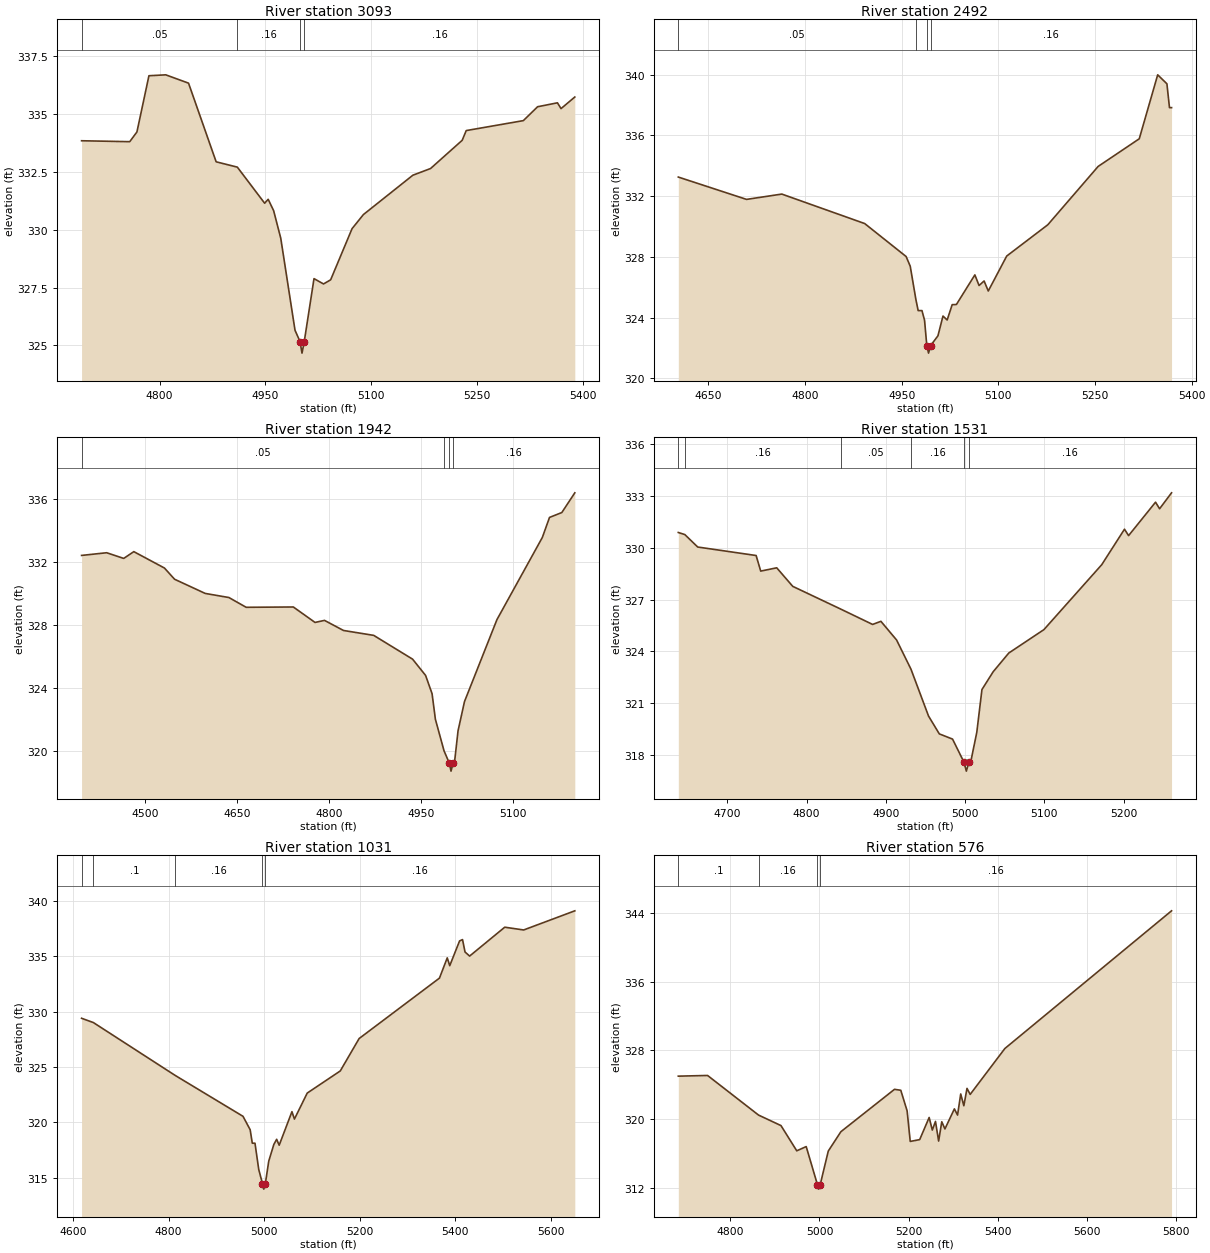
Type RM Length L Ch R = 1,3093,601,601,601
BEGIN DESCRIPTION:
LITTLE CEDAR CREEK TRIBUTARY 6 6.0
END DESCRIPTION:
XS GIS Cut Line= 3
      3560526.14     10320828.49      3560476.13     10320578.45
      3560540.25     10320139.50
#Sta/Elev= 30
  4689.6  333.85  4757.8  333.81  4768.0  334.23  4785.0  336.66  4808.8  336.70
  4841.1  336.34  4880.2  332.94  4910.2  332.71  4948.9  331.15  4953.9  331.32
  4961.6  330.83  4971.7  329.64  4991.9  325.66  4999.0  325.17  5001.8  324.67
  5005.0  325.17  5018.8  327.89  5032.3  327.66  5042.4  327.84  5072.7  330.05
  5088.8  330.66  5158.8  332.36  5183.9  332.65  5228.7  333.87  5234.4  334.29
  5315.3  334.72  5335.5  335.32  5363.6  335.49  5368.7  335.24  5388.2  335.74
#Mann=4,-1,0
  4689.6    0.05       0  4910.2    0.16       0  4999.0    0.07       0
  5005.0    0.16       0
Bank Sta=4999,5005
Exp/Cntr=0.3,0.1

Type RM Length L Ch R = 1,2492,550,550,550
BEGIN DESCRIPTION:
LITTLE CEDAR CREEK TRIBUTARY 6 5.0
END DESCRIPTION:
XS GIS Cut Line= 3
      3560807.62     10320941.58      3560942.11     10320591.64
      3561192.10     10320291.65
#Sta/Elev= 30
  4603.4  333.26  4709.3  331.79  4764.0  332.14  4892.6  330.20  4956.9  328.03
  4963.3  327.39  4972.2  325.17  4975.6  324.47  4981.5  324.47  4985.5  323.84
  4989.0  322.17  4991.7  321.67  4995.0  322.17  5006.3  322.81  5014.1  324.11
  5020.6  323.85  5028.4  324.86  5034.9  324.87  5063.6  326.82  5070.1  326.12
  5077.9  326.42  5084.4  325.76  5113.0  328.06  5176.8  330.12  5254.9  333.96
  5318.7  335.78  5347.3  339.99  5361.6  339.40  5365.6  337.83  5368.8  337.83
#Mann=4,-1,0
  4603.4    0.05       0  4972.2    0.16       0  4989.0    0.07       0
  4995.0    0.16       0
Bank Sta=4989,4995
Exp/Cntr=0.3,0.1

Type RM Length L Ch R = 1,1942,411,411,411
BEGIN DESCRIPTION:
LITTLE CEDAR CREEK TRIBUTARY 6 4.0
END DESCRIPTION:
XS GIS Cut Line= 3
      3561127.04     10321330.52      3561304.13     10320986.74
      3561442.10     10320591.65
#Sta/Elev= 30
  4395.7  332.39  4436.7  332.56  4464.5  332.20  4481.0  332.63  4531.0  331.59
  4547.5  330.88  4597.5  329.98  4636.2  329.72  4664.4  329.10  4741.4  329.12
  4776.8  328.14  4792.3  328.27  4823.3  327.63  4872.6  327.32  4936.1  325.81
  4957.3  324.78  4967.9  323.62  4973.3  322.00  4987.4  320.00  4996.1  319.21
  4998.8  318.71  5002.1  319.21  5004.4  319.23  5010.3  321.27  5020.8  323.12
  5073.8  328.32  5147.9  333.53  5159.6  334.80  5179.7  335.11  5200.9  336.36
#Mann=4,-1,0
  4395.7    0.05       0  4987.4    0.16       0  4996.1    0.07       0
  5002.1    0.16       0
Bank Sta=4996.1,5002.1
Exp/Cntr=0.3,0.1

Type RM Length L Ch R = 1,1531,500,500,500
BEGIN DESCRIPTION:
LITTLE CEDAR CREEK TRIBUTARY 6 3.0
END DESCRIPTION:
XS GIS Cut Line= 3
      3561644.41     10321354.78      3561692.11     10320991.64
      3561762.06     10320745.13
#Sta/Elev= 30
  4638.0  330.87  4646.2  330.75  4662.5  330.03  4736.2  329.54  4742.0  328.64
  4762.2  328.83  4782.4  327.76  4843.3  326.44  4883.2  325.56  4893.7  325.74
  4913.5  324.66  4931.6  322.98  4953.8  320.27  4967.4  319.24  4984.1  318.94
  4998.7  317.59  5001.5  317.09  5004.7  317.59  5006.9  317.59  5014.7  319.33
  5021.2  321.80  5035.4  322.83  5055.1  323.91  5099.4  325.26  5172.4  329.01
  5201.1  331.06  5206.3  330.69  5240.3  332.62  5245.4  332.24  5260.5  333.16
#Mann=6,-1,0
  4638.0     0.1       0  4646.2    0.16       0  4843.3    0.05       0
  4931.6    0.16       0  4998.7    0.07       0  5004.7    0.16       0
Bank Sta=4998.7,5004.7
Exp/Cntr=0.3,0.1

Type RM Length L Ch R = 1,1031,455,455,455
BEGIN DESCRIPTION:
LITTLE CEDAR CREEK TRIBUTARY 6 2.0
END DESCRIPTION:
XS GIS Cut Line= 3
      3561942.13     10321391.60      3562142.11     10321091.64
      3562349.26     10320452.06
#Sta/Elev= 30
  4617.8  329.40  4642.6  329.01  4814.0  324.23  4955.8  320.54  4970.8  319.33
  4975.3  318.11  4980.9  318.11  4988.8  315.73  4996.6  314.46  4999.3  313.96
  5002.6  314.46  5009.8  316.50  5020.4  318.00  5026.3  318.46  5031.6  317.93
  5058.3  320.96  5063.5  320.29  5090.3  322.64  5159.5  324.64  5199.0  327.57
  5367.2  333.03  5383.5  334.86  5388.7  334.15  5409.3  336.39  5415.5  336.51
  5420.7  335.39  5430.3  335.02  5503.9  337.63  5543.5  337.38  5650.6  339.11
#Mann=5,-1,0
  4617.8    0.05       0  4642.6     0.1       0  4814.0    0.16       0
  4996.6    0.07       0  5002.6    0.16       0
Bank Sta=4996.6,5002.6
Exp/Cntr=0.3,0.1

Type RM Length L Ch R = 1,576,0,0,0
BEGIN DESCRIPTION:
LITTLE CEDAR CREEK TRIBUTARY 6 1.0
END DESCRIPTION:
XS GIS Cut Line= 3
      3562177.49     10321457.64      3562327.52     10321357.61
      3562981.20     10320702.04
#Sta/Elev= 30
  4683.5  325.01  4749.1  325.09  4863.4  320.49  4913.7  319.27  4949.1  316.34
  4970.3  316.83  4995.6  312.39  4998.3  311.89  5001.6  312.39  5019.8  316.31
  5048.1  318.56  5168.3  323.48  5182.4  323.37  5196.6  320.98  5203.6  317.43
  5224.8  317.64  5246.0  320.21  5253.1  318.75  5260.2  319.75  5267.3  317.47
  5274.3  319.71  5281.4  318.88  5302.6  321.21  5309.7  320.49  5316.8  322.94
  5323.8  321.57  5330.9  323.59  5338.0  322.89  5415.8  328.22  5789.6  344.21
#Mann=4,-1,0
  4683.5     0.1       0  4863.4    0.16       0  4995.6    0.07       0
  5001.6    0.16       0
Bank Sta=4995.6,5001.6
Exp/Cntr=0.3,0.1

Chan Stop Cuts=-1