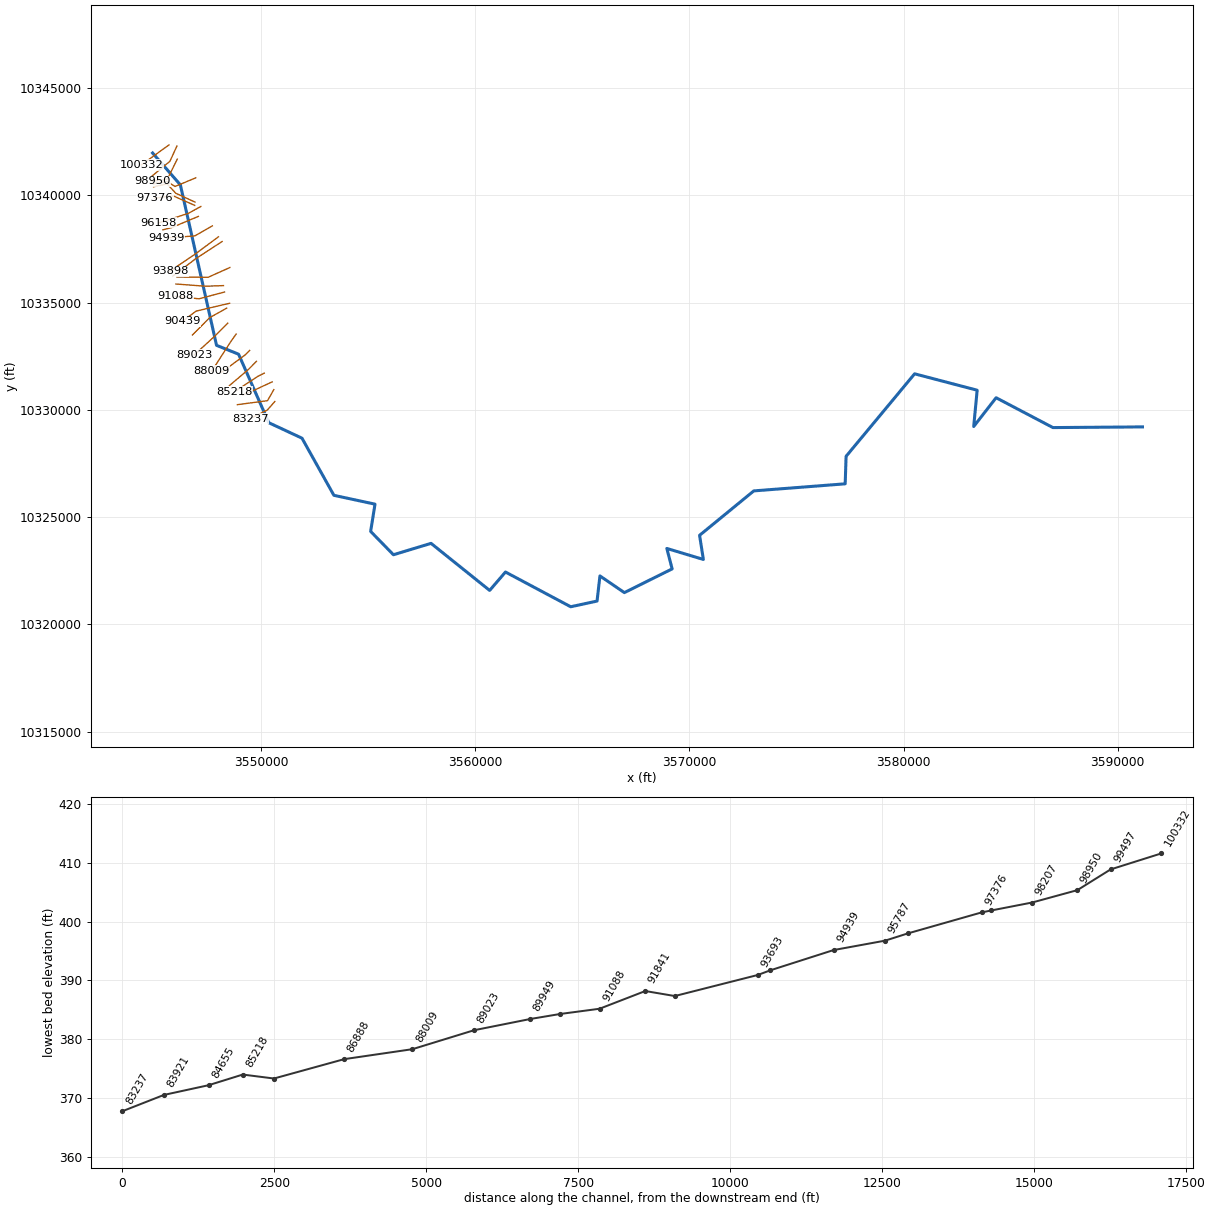
--- LITTLE CEDAR CREEK.prj (project) ---

Proj Title=LITTLE CEDAR CREEK Base Level Engineering
Current Plan=p01
Default Exp/Contr=0.3,0.1
English Units
Geom File=g01
Flow File=f01
Plan File=p01
Y Axis Title=Elevation
X Axis Title(PF)=Main Channel Distance
X Axis Title(XS)=Station
BEGIN DESCRIPTION:
LITTLE CEDAR CREEK
END DESCRIPTION:
DSS Export Rating Curves= 0
DSS Export Rating Curve Sorted= 0
DSS Export Volume Flow Curves= 0
DXF OffsetX= 0
DXF OffsetY= 0
DXF ScaleX= 1
DXF ScaleY= 10

--- LITTLE CEDAR CREEK.p01 (plan) ---

Plan Title=Multiple Run
Short Identifier=Multiple
Geom File=g01
Flow File=f01
Subcritical Flow
K Sum by GR= 0
Std Step Tol= 0.01
Critical Tol= 0.01
Num of Std Step Trials= 20
Max Error Tol= 0.3
Flow Tol Ratio= 0.001
Split Flow NTrial= 30
Split Flow Tol= 0.02
Split Flow Ratio= 0.02
Log Output Level= 0
Friction Slope Method= 1
Unsteady Friction Slope Method= 2
Unsteady Bridges Friction Slope Method= 1
Parabolic Critical Depth
Global Vel Dist=  1 , 1 , 1
Global Log Level= 0
CheckData=True
Encroach Param= -1, 0, 0, 0
BEGIN DESCRIPTION:
Multiple Run
END DESCRIPTION:

--- LITTLE CEDAR CREEK.f01 (steady flow) ---

Flow Title=Multiple
Program Version=4.10
Number of Profiles= 7
Profile Names=10-year,25-year,50-year,1pct_min,100-year,1pct_plu,500-year
River Rch & RM=LITTLE CEDAR CRE,Reach-1         ,100332
     835    1151    1413    1269    1717    2321    2542
River Rch & RM=LITTLE CEDAR CRE,Reach-1         ,95787
     835    1151    1413    1269    1717    2321    2542
River Rch & RM=LITTLE CEDAR CRE,Reach-1         ,93898
    1057    1473    1823    1649    2230    3016    3349
River Rch & RM=LITTLE CEDAR CRE,Reach-1         ,91088
    1257    1763    2188    1985    2684    3630    4053
River Rch & RM=LITTLE CEDAR CRE,Reach-1         ,85732
    1330    1866    2318    2102    2843    3845    4293
River Rch & RM=LITTLE CEDAR CRE,Reach-1         ,81075
    1535    2158    2684    2436    3294    4455    4982
River Rch & RM=LITTLE CEDAR CRE,Reach-1         ,71110
    1833    2592    3237    2948    3986    5391    6069
River Rch & RM=LITTLE CEDAR CRE,Reach-1         ,69324
    1833    2592    3237    2948    3986    5391    6069
River Rch & RM=LITTLE CEDAR CRE,Reach-1         ,58759
    2497    3562    4473    4093    5536    7487    8509
River Rch & RM=LITTLE CEDAR CRE,Reach-1         ,55855
    2497    3562    4473    4093    5536    7487    8509
River Rch & RM=LITTLE CEDAR CRE,Reach-1         ,45152
    2726    3903    4914    4507    6096    8244    9414
River Rch & RM=LITTLE CEDAR CRE,Reach-1         ,43286
    2750    3934    4951    4538    6138    8300    9467
River Rch & RM=LITTLE CEDAR CRE,Reach-1         ,39177
    2750    3934    4951    4538    6138    8300    9467
River Rch & RM=LITTLE CEDAR CRE,Reach-1         ,34970
    3404    4899    6191    5697    7704   10419   11970
River Rch & RM=LITTLE CEDAR CRE,Reach-1         ,34039
    3420    4914    6202    5698    7706   10421   11936
River Rch & RM=LITTLE CEDAR CRE,Reach-1         ,33282
    3420    4914    6202    5698    7706   10421   11936
River Rch & RM=LITTLE CEDAR CRE,Reach-1         ,28448
    4013    5795    7341    6767    9151   12376   14267
River Rch & RM=LITTLE CEDAR CRE,Reach-1         ,24215
    4013    5795    7341    6767    9151   12376   14267
River Rch & RM=LITTLE CEDAR CRE,Reach-1         ,18920
    4134    5953    7526    6923    9362   12661   14531
Boundary for River Rch & Prof#=LITTLE CEDAR CRE,Reach-1         , 1
Up Type= 0
Dn Type= 3
Dn Slope=0.00113
Boundary for River Rch & Prof#=LITTLE CEDAR CRE,Reach-1         , 2
Up Type= 0
Dn Type= 3
Dn Slope=0.00113
Boundary for River Rch & Prof#=LITTLE CEDAR CRE,Reach-1         , 3
Up Type= 0
Dn Type= 3
Dn Slope=0.00113
Boundary for River Rch & Prof#=LITTLE CEDAR CRE,Reach-1         , 4
Up Type= 0
Dn Type= 3
Dn Slope=0.00113
Boundary for River Rch & Prof#=LITTLE CEDAR CRE,Reach-1         , 5
Up Type= 0
Dn Type= 3
Dn Slope=0.00113
Boundary for River Rch & Prof#=LITTLE CEDAR CRE,Reach-1         , 6
Up Type= 0
Dn Type= 3
Dn Slope=0.00113
Boundary for River Rch & Prof#=LITTLE CEDAR CRE,Reach-1         , 7
Up Type= 0
Dn Type= 3
Dn Slope=0.00113
DSS Import GetInterval= 0
DSS Import GetPeak= 0
DSS Import FillOption= 0

--- LITTLE CEDAR CREEK.g01 (geometry) ---

Geom Title=Existing Conditions
Program Version=4.10

River Reach=LITTLE CEDAR CRE,Reach-1
Reach XY= 30
      3544932.11     10341971.64      3546229.03     10340485.57
       3547918.4     10333006.98      3548947.73     10332594.61
      3550358.06     10329400.46      3551907.59     10328680.51
      3553399.27     10326015.83      3555318.09     10325604.09
      3555115.24      10324333.3      3556179.24     10323246.52
      3557934.98     10323777.13      3560672.95     10321584.02
      3561411.52     10322440.75      3564457.81     10320821.94
      3565687.99     10321087.32      3565823.08      10322259.3
      3566963.65      10321481.4      3569194.81     10322587.15
      3568946.69     10323539.92       3570652.6     10323027.55
      3570476.38     10324151.68      3573007.04     10326221.96
      3577276.02     10326552.12      3577317.74      10327834.1
      3580517.79     10331679.54       3583439.2     10330915.28
      3583277.78      10329223.7      3584323.98     10330564.74
      3586977.86     10329173.26      3591158.71     10329205.05

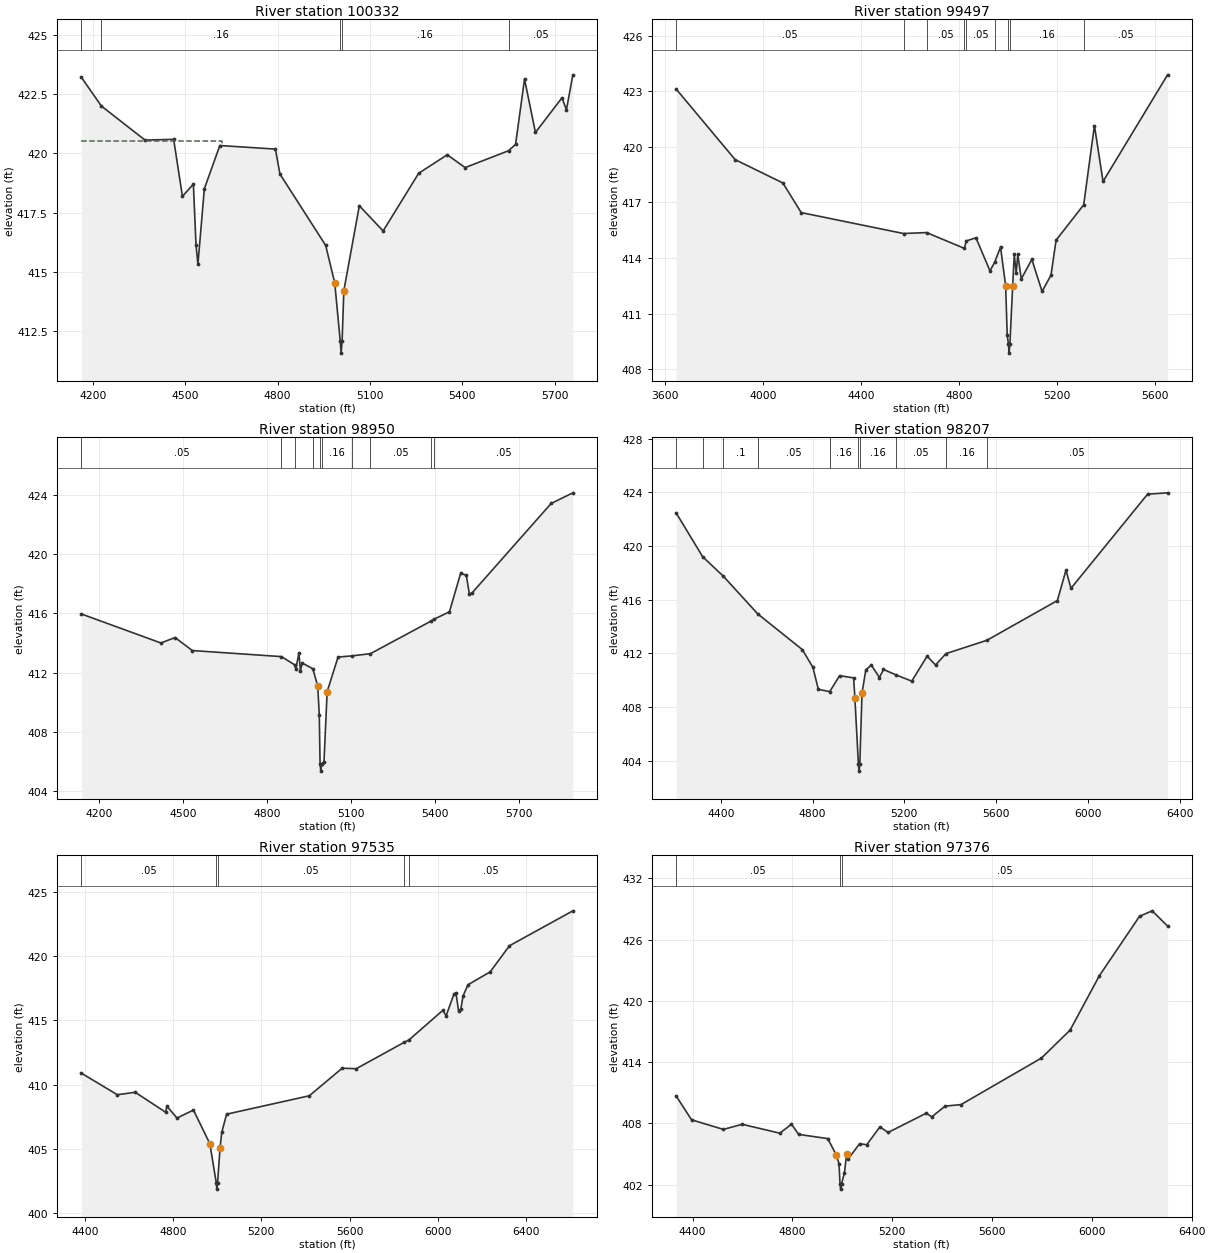
Type RM Length L Ch R = 1 ,100332  ,835,835,835
BEGIN DESCRIPTION:
Mapping XS 7bc561cb
END DESCRIPTION:
XS GIS Cut Line= 2
      3545694.78     10342346.86      3544401.37      10341413.7
#Sta/Elev= 30
  4163.6   423.2  4227.8     422  4369.7  420.56  4462.8  420.59  4491.2  418.19
  4526.8   418.7  4535.3  416.15  4541.5  415.32  4562.4  418.51  4612.7  420.33
    4793  420.18  4807.7  419.13  4956.2  416.12  4985.6  414.54  5003.5  412.08
  5006.3  411.58  5009.5  412.08  5015.1  414.21  5065.4  417.79  5142.7  416.73
    5258  419.16  5350.7  419.94  5408.9   419.4  5549.6  420.11  5572.6  420.38
  5601.6  423.13  5637.1  420.88    5723  422.34  5737.7  421.84  5758.5  423.31
#Mann= 5 ,-1 , 0
  4163.6     .05       0  4227.8     .16       0  5003.5     .07       0
  5009.5     .16       0  5549.6     .05       0
#XS Ineff= 2 , 0
          4620.8   420.5
Permanent Ineff=
       F       F
Bank Sta=4985.6,5015.1
XS Rating Curve= 0 ,0
Exp/Cntr=0.3,0.1

Type RM Length L Ch R = 1 ,99497   ,547,547,547
BEGIN DESCRIPTION:
Mapping XS 114255d8
END DESCRIPTION:
XS GIS Cut Line= 3
      3546068.05     10342294.81      3545740.04     10341584.13
      3544797.05     10340806.64
#Sta/Elev= 30
  3645.5  423.12  3886.1  419.31  4080.7  418.05  4155.6  416.45    4573  415.32
  4667.2  415.37    4821  414.52  4829.4  414.92  4868.6  415.09  4925.9   413.3
    4945  413.77  4968.9  414.59  4989.8  412.49  4996.2  409.82  5001.1  409.36
  5003.8  408.86  5007.1  409.36  5018.4  412.49  5024.9  414.19  5032.8  413.19
  5039.3  414.19  5053.6  412.87  5096.6  413.92  5138.4  412.19  5174.8  413.07
  5195.6  414.96  5308.2  416.87    5352  421.15  5387.1  418.13  5650.4  423.89
#Mann= 9 ,-1 , 0
  3645.5     .05       0    4573     .16       0  4667.2     .05       0
    4821     .16       0  4829.4     .05       0    4945     .16       0
  5001.1     .07       0  5007.1     .16       0  5308.2     .05       0
Bank Sta=4989.8,5018.4
XS Rating Curve= 0 ,0
Exp/Cntr=0.3,0.1

Type RM Length L Ch R = 1 ,98950   ,743,743,743
BEGIN DESCRIPTION:
Mapping XS acbdec4c
END DESCRIPTION:
XS GIS Cut Line= 3
       3546085.4     10341687.13      3545620.99     10340753.98
      3544915.31      10340654.4
#Sta/Elev= 30
  4138.5  415.96  4422.4     414  4472.7  414.37  4534.3  413.49  4852.8  413.08
  4899.5  412.53  4904.2  412.25    4915  413.32  4920.6  412.12  4926.5  412.65
  4964.7  412.26  4982.2  411.09  4987.8  409.16  4990.6  405.84  4993.3  405.34
  4996.6  405.84  5004.6  405.97  5015.9  410.71  5054.9  413.05  5104.9  413.13
  5170.6  413.28  5386.9  415.48  5397.1   415.6  5452.7  416.11  5492.8  418.72
    5513  418.57  5523.9  417.31  5533.2  417.38  5815.9  423.43  5893.5  424.15
#Mann= 10 ,-1 , 0
  4138.5     .05       0  4852.8     .16       0  4899.5      .1       0
  4964.7     .16       0  4990.6     .07       0  4996.6     .16       0
  5104.9      .1       0  5170.6     .05       0  5386.9      .1       0
  5397.1     .05       0
Bank Sta=4982.2,5015.9
XS Rating Curve= 0 ,0
Exp/Cntr=0.3,0.1

Type RM Length L Ch R = 1 ,98207   ,672,672,672
BEGIN DESCRIPTION:
Mapping XS 39ce580d
END DESCRIPTION:
XS GIS Cut Line= 4
      3546949.12     10340814.74      3545981.23     10340411.09
      3545603.63     10340645.47      3544966.34     10340532.75
#Sta/Elev= 30
  4206.1  422.46  4321.6   419.2  4411.6  417.75  4561.7  414.94  4755.4  412.29
  4801.5  410.97  4825.3  409.33  4874.9  409.16    4918  410.35  4979.1  410.18
  4984.5  408.68  4999.9  403.74  5002.6  403.24  5005.9  403.74  5015.5  409.04
  5032.1  410.78    5056  411.14  5091.3  410.21    5109  410.81  5164.2   410.4
  5232.2  409.94  5299.1   411.8  5335.7  411.14  5381.3  411.99  5559.5  412.98
  5866.5  415.94  5903.9   418.2  5925.7  416.85  6259.3  423.86  6346.4  423.96
#Mann= 10 ,-1 , 0
  4206.1      .1       0  4321.6     .05       0  4411.6      .1       0
  4561.7     .05       0  4874.9     .16       0  4999.9     .07       0
  5005.9     .16       0  5164.2     .05       0  5381.3     .16       0
  5559.5     .05       0
Bank Sta=4984.5,5015.5
XS Rating Curve= 0 ,0
Exp/Cntr=0.3,0.1

Type RM Length L Ch R = 1 ,97535   ,159,159,159
BEGIN DESCRIPTION:
Mapping XS 24a3ab91
END DESCRIPTION:
XS GIS Cut Line= 4
      3546909.63     10339685.57      3546016.99     10340095.56
      3545606.99     10340531.51      3544975.62     10340396.95
#Sta/Elev= 30
  4385.4  410.89  4547.7  409.22  4628.9  409.41  4766.8  407.86  4772.3  408.33
  4818.3  407.41  4892.7  408.03  4967.2  405.41  4995.9  402.39  4998.7  401.89
  5001.9  402.39  5013.2  405.08  5020.9   406.3  5042.9  407.71  5417.7  409.14
  5566.6  411.28  5630.1  411.24  5847.8  413.29  5869.4  413.48  6022.3  415.77
  6037.5  415.35  6073.4  417.06    6082  417.13  6093.8  415.74  6104.1  415.86
  6114.3   416.9  6136.6  417.76    6237  418.76  6324.6  420.79  6611.7   423.5
#Mann= 5 ,-1 , 0
  4385.4     .05       0  4995.9     .03       0  5001.9     .05       0
  5847.8     .16       0  5869.4     .05       0
Bank Sta=4967.2,5013.2
XS Rating Curve= 0 ,0
Exp/Cntr=0.3,0.1

Type RM Length L Ch R = 1 ,97376   ,1218,1218,1218
BEGIN DESCRIPTION:
Mapping XS 9bf8af6d
END DESCRIPTION:
XS GIS Cut Line= 3
      3546899.23     10339529.88      3545887.24     10339976.19
      3545030.89      10339867.2
#Sta/Elev= 30
  4334.1  410.68  4395.7  408.35  4523.3  407.41  4598.7  407.91  4749.6  407.04
  4796.2  407.92    4825  406.92  4941.6  406.51  4975.8   404.9  4986.7  404.06
  4990.7  402.06  4993.4  401.56  4996.7  402.06  5008.6  403.18    5017  404.98
  5022.5  404.48  5069.1  406.01  5097.9  405.91  5150.7  407.66  5183.4  407.11
  5336.5     409  5358.3  408.64    5412  409.69  5475.6  409.84  5798.1   414.4
  5912.9  417.14    6030  422.46  6191.3  428.29  6241.7  428.82  6303.4  427.33
#Mann= 3 ,-1 , 0
  4334.1     .05       0  4990.7     .04       0  4996.7     .05       0
Bank Sta=4975.8,5017
XS Rating Curve= 0 ,0
Exp/Cntr=0.3,0.1

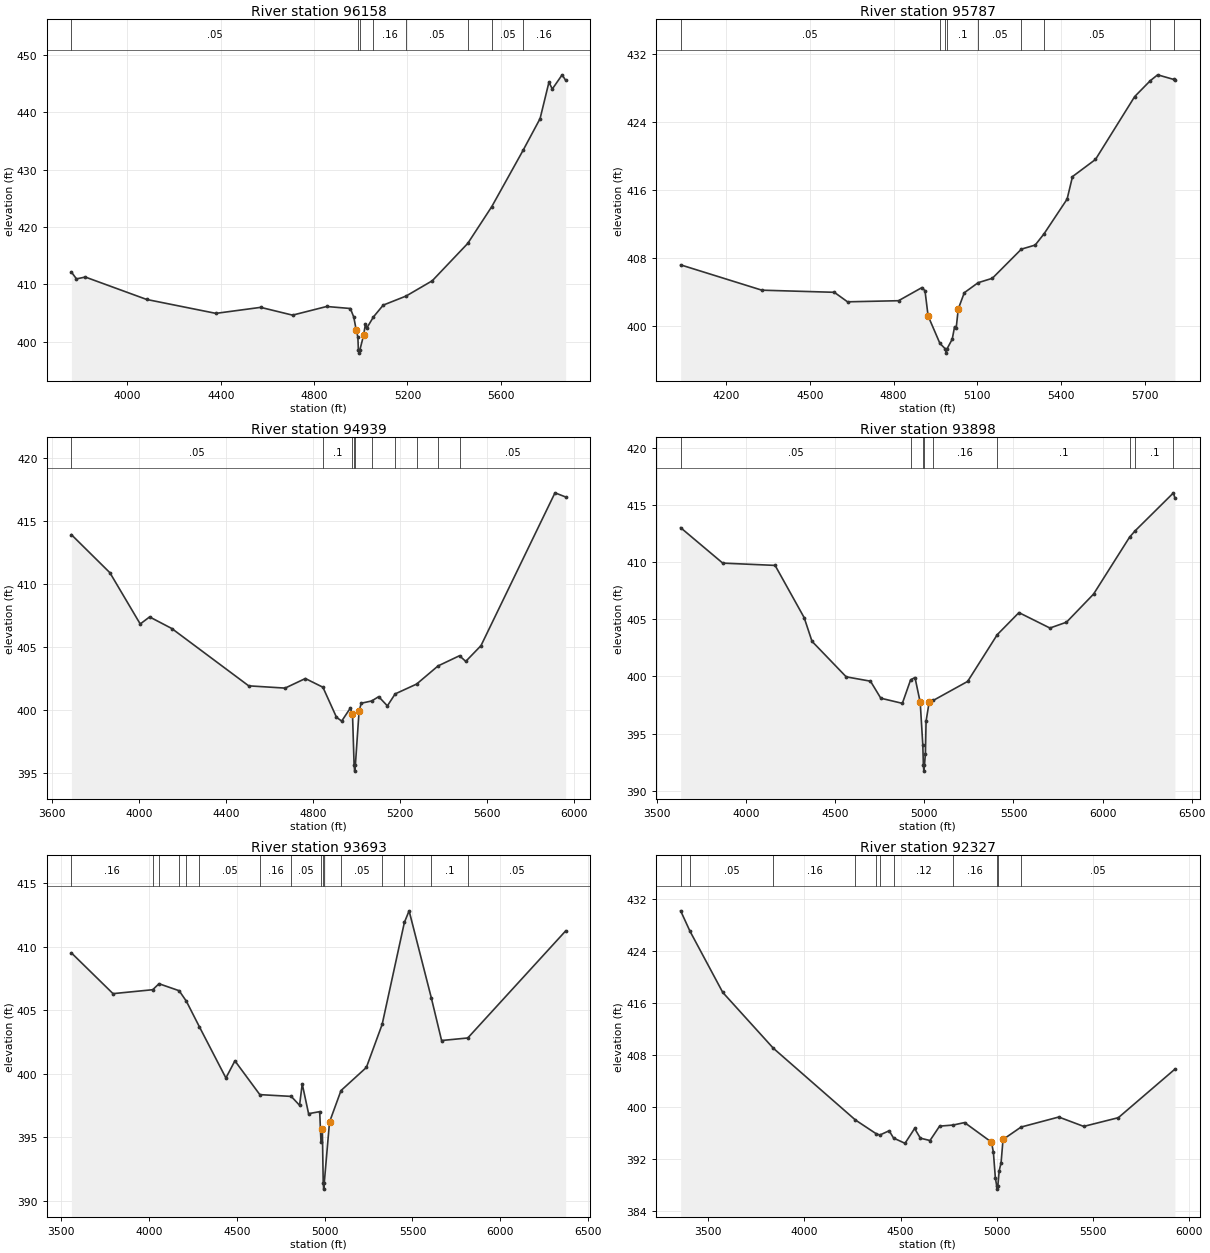
Type RM Length L Ch R = 1 ,96158   ,371,371,371
BEGIN DESCRIPTION:
Mapping XS 7bf5a0de
END DESCRIPTION:
XS GIS Cut Line= 3
      3547184.72     10339477.98      3546608.63     10339161.39
      3545217.74     10338715.06
#Sta/Elev= 30
  3759.7  412.14  3781.5  410.94  3819.4  411.26  4082.2  407.35  4378.9  404.92
  4570.9  405.97  4707.5  404.61  4853.6  406.12  4955.2  405.77    4970  404.25
  4980.5  401.97  4987.4  400.77  4989.6  398.48  4992.4  397.98  4995.6  398.48
    5012   401.1  5019.5     403  5024.7   402.3  5054.3  404.31    5096  406.36
  5193.8  407.94  5306.1  410.61  5458.2  417.13  5561.1  423.55  5695.2  433.37
  5768.2  438.92  5806.1  445.26  5820.7  444.09  5862.7  446.56  5877.8   445.6
#Mann= 8 ,-1 , 0
  3759.7     .05       0  4989.6     .03       0  4995.6     .05       0
  5054.3     .16       0  5193.8     .05       0  5458.2      .1       0
  5561.1     .05       0  5695.2     .16       0
Bank Sta=4980.5,5012
XS Rating Curve= 0 ,0
Exp/Cntr=0.3,0.1

Type RM Length L Ch R = 1 ,95787   ,848,848,848
BEGIN DESCRIPTION:
LITTLE CEDAR CREEK 101.0
END DESCRIPTION:
XS GIS Cut Line= 3
      3547070.54     10339017.07       3545814.5     10338491.64
      3545415.78     10338391.96
#Sta/Elev= 30
    4036  407.15  4327.3  404.17  4587.1  403.92  4634.5   402.8  4817.3  402.93
  4901.5  404.48  4912.3   404.1  4923.4  401.14  4965.7  397.91  4985.2  397.26
    4988  396.76  4991.2  397.26  5009.9   398.4  5018.5  399.88    5024  399.68
  5031.6  401.96  5053.2  403.87  5102.7  405.05  5153.8  405.57  5257.9     409
  5307.4  409.48  5339.3  410.81  5421.9  414.89  5441.2  417.54  5523.7  419.56
  5664.2  426.96  5720.2  428.83  5746.6  429.52    5805  428.97  5808.5  428.92
#Mann= 9 ,-1 , 0
    4036     .05       0  4965.7      .1       0  4985.2     .07       0
  4991.2      .1       0  5102.7     .05       0  5257.9      .1       0
  5339.3     .05       0  5720.2      .1       0    5805     .05       0
Bank Sta=4923.4,5031.6
XS Rating Curve= 0 ,0
Exp/Cntr=0.3,0.1

Type RM Length L Ch R = 1 ,94939   ,1041,1041,1041
BEGIN DESCRIPTION:
LITTLE CEDAR CREEK 100.0
END DESCRIPTION:
XS GIS Cut Line= 3
      3547721.53     10338574.34      3546901.23      10338105.6
      3545573.14     10338014.45
#Sta/Elev= 30
  3687.7  413.93    3865  410.91  4004.7  406.84  4047.9   407.4  4150.1  406.48
  4504.2  401.93  4671.7  401.75  4765.1  402.51  4845.9  401.82  4908.3  399.44
  4932.3  399.13  4972.4  400.17  4981.1  399.67  4982.4  399.59  4989.5  395.66
  4992.2  395.16  4995.5  395.66  5012.5  399.93  5022.5  400.55  5070.6  400.73
  5102.7  401.07  5142.8  400.34  5178.6  401.29  5277.4  402.07  5376.1  403.51
  5474.9  404.32  5503.7  403.87  5573.8  405.12  5914.6  417.25  5963.7  416.92
#Mann= 10 ,-1 , 0
  3687.7     .05       0  4845.9      .1       0  4981.1     .16       0
  4989.5     .07       0  4995.5     .16       0  5070.6     .05       0
  5178.6     .16       0  5277.4     .05       0  5376.1     .16       0
  5474.9     .05       0
Bank Sta=4981.1,5012.5
XS Rating Curve= 0 ,0
Exp/Cntr=0.3,0.1

Type RM Length L Ch R = 1 ,93898   ,205,205,205
BEGIN DESCRIPTION:
LITTLE CEDAR CREEK 99.0
END DESCRIPTION:
XS GIS Cut Line= 3
      3548007.98     10338066.52      3546901.23     10337246.22
      3545743.62     10336465.82
#Sta/Elev= 30
  3632.4  413.02  3868.7  409.92  4162.5  409.72  4325.6  405.15  4369.5  403.08
  4561.5  399.97  4697.7  399.59  4755.6   398.1  4876.6  397.65    4923  399.71
  4947.5  399.91  4976.8  397.74  4991.4     394  4994.6  392.22  4997.3  391.72
  5000.6  392.22    5006  393.26  5009.7  396.09  5027.1  397.77  5049.3   397.9
    5243  399.57  5409.1  403.66  5530.8  405.59  5704.7  404.24  5797.6  404.75
  5949.6  407.21  6151.6  412.19  6182.4  412.74  6398.1  416.07  6406.1   415.6
#Mann= 9 ,-1 , 0
  3632.4     .05       0    4923     .12       0  4994.6     .07       0
  5000.6     .12       0  5049.3     .16       0  5409.1      .1       0
  6151.6     .05       0  6182.4      .1       0  6398.1     .05       0
Bank Sta=4976.8,5027.1
XS Rating Curve= 0 ,0
Exp/Cntr=0.3,0.1

Type RM Length L Ch R = 1 ,93693   ,1366,1366,1366
BEGIN DESCRIPTION:
LITTLE CEDAR CREEK 98.0
END DESCRIPTION:
XS GIS Cut Line= 3
      3548177.26     10337845.18      3546942.11     10337041.64
      3545872.58     10336230.59
#Sta/Elev= 30
    3557  409.53  3794.2  406.32  4020.5  406.63  4056.1   407.1    4171  406.55
  4212.2  405.72  4285.9  403.72  4437.3  399.68  4488.6  401.03  4630.5  398.37
  4809.5  398.23  4856.9  397.53  4872.1  399.21  4908.3  396.87  4971.6  397.03
    4979  394.64  4986.7  395.65  4991.7  391.43  4994.5  390.93  4997.7  391.43
  5027.5  396.21    5093  398.69  5237.5  400.51  5327.4   403.9  5454.1  411.93
  5480.9  412.84  5607.3     406    5666  402.63  5815.2  402.83  6372.8  411.26
#Mann= 16 ,-1 , 0
    3557     .16       0  4020.5      .1       0  4056.1     .16       0
    4171     .05       0  4212.2     .16       0  4285.9     .05       0
  4630.5     .16       0  4809.5     .05       0    4979     .16       0
  4991.7     .07       0  4997.7     .16       0    5093     .05       0
  5327.4      .1       0  5454.1     .05       0  5607.3      .1       0
  5815.2     .05       0
Bank Sta=4986.7,5027.5
XS Rating Curve= 0 ,0
Exp/Cntr=0.3,0.1

Type RM Length L Ch R = 1 ,92327   ,486,486,486
BEGIN DESCRIPTION:
LITTLE CEDAR CREEK 95.0
END DESCRIPTION:
XS GIS Cut Line= 3
      3548541.83     10336634.23      3547526.23     10336178.51
      3546067.85     10336191.53
#Sta/Elev= 30
  3355.7  430.12  3404.1     427  3574.9  417.58  3837.7  409.01  4265.3  397.97
  4371.7  395.89  4391.8  395.66  4440.5  396.32  4463.5   395.2    4523  394.39
    4573  396.67    4603  395.18    4653  394.82    4703  397.03  4773.9   397.2
    4833  397.58    4973  394.57    4983  392.98    4993  389.12    5000  387.85
  5002.8  387.35    5006  387.85    5013  390.15    5023  391.44    5033  394.98
  5126.9  396.89    5323  398.43    5453  396.99    5633  398.33  5927.3  405.79
#Mann= 11 ,-1 , 0
  3355.7      .1       0  3404.1     .05       0  3837.7     .16       0
  4265.3     .05       0  4371.7     .16       0  4391.8     .05       0
  4463.5     .12       0  4773.9     .16       0    5000     .07       0
    5006     .16       0  5126.9     .05       0
Bank Sta=4973,5033
XS Rating Curve= 0 ,0
Exp/Cntr=0.3,0.1

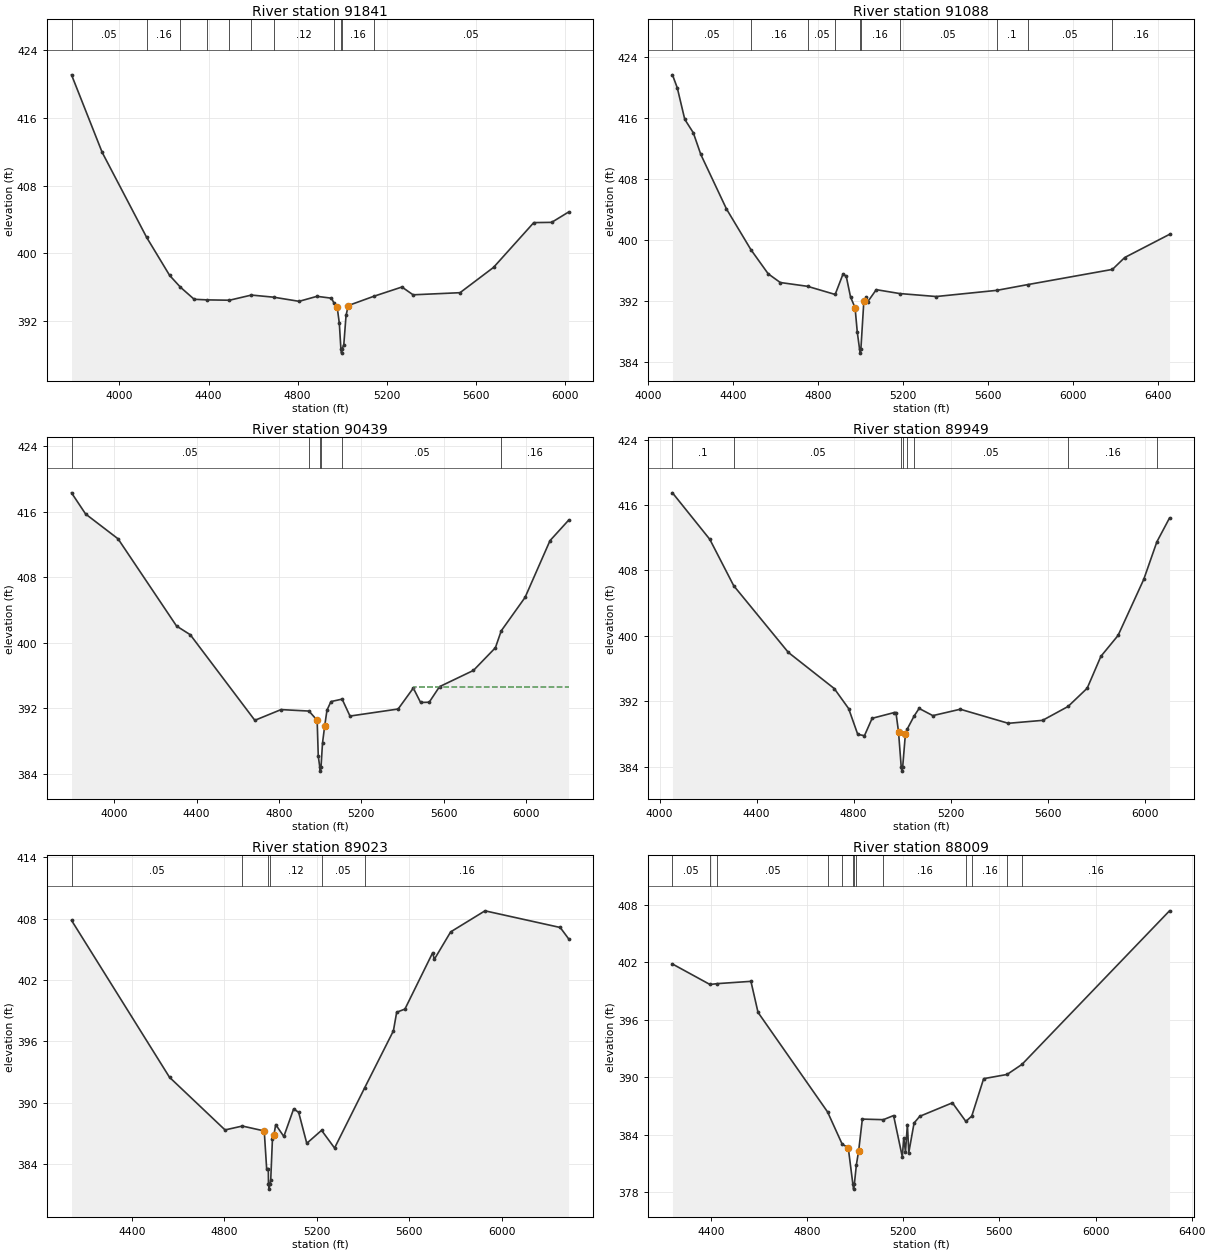
Type RM Length L Ch R = 1 ,91841   ,753,753,753
BEGIN DESCRIPTION:
LITTLE CEDAR CREEK 94.0
END DESCRIPTION:
XS GIS Cut Line= 3
      3548242.15     10335791.64      3547409.04     10335761.85
      3546016.47     10335865.96
#Sta/Elev= 30
  3785.4  421.08  3922.9  411.92  4122.6  401.87  4225.7  397.38    4274  395.99
  4335.8  394.56  4395.3  394.49    4494  394.45  4592.7  395.06  4691.9  394.81
  4806.5  394.32  4886.7  394.91  4951.8  394.69  4963.8  394.07    4977  393.69
    4987  391.72    4994   388.7  4996.8   388.2    5000   388.7  5007.1  389.21
  5017.1  392.65  5027.1  393.82  5142.2  394.92  5267.8  396.01  5317.9  395.09
  5528.5  395.34  5678.9  398.33  5859.4  403.62  5939.7  403.65  6015.5  404.87
#Mann= 11 ,-1 , 0
  3785.4     .05       0  4122.6     .16       0    4274     .12       0
  4395.3     .07       0    4494     .05       0  4592.7     .07       0
  4691.9     .12       0  4963.8     .16       0    4994     .07       0
    5000     .16       0  5142.2     .05       0
Bank Sta=4977,5027.1
XS Rating Curve= 0 ,0
Exp/Cntr=0.3,0.1

Type RM Length L Ch R = 1 ,91088   ,649,649,649
BEGIN DESCRIPTION:
LITTLE CEDAR CREEK 92.0
END DESCRIPTION:
XS GIS Cut Line= 3
      3548292.09     10335491.64      3547096.54     10335175.91
      3546002.84     10335293.09
#Sta/Elev= 30
  4115.9  421.72  4138.6  420.01  4173.7  415.88    4214  414.11  4249.1  411.27
  4369.9  404.11  4484.7  398.77    4566   395.6  4622.7  394.46  4750.8  393.96
  4880.8  392.89  4918.1   395.6    4933  395.25  4953.2  392.54  4974.3  391.16
  4984.7  387.95  4995.6  385.69  4998.4  385.19  5001.6  385.69  5015.7  392.06
  5026.1  392.54  5033.7  391.93    5074  393.52  5184.1  393.01  5355.9  392.62
  5640.5  393.43    5785  394.18  6184.1  396.18  6241.9  397.74  6452.4  400.78
#Mann= 10 ,-1 , 0
  4115.9     .05       0  4484.7     .16       0  4750.8     .05       0
  4880.8     .16       0  4995.6     .07       0  5001.6     .16       0
  5184.1     .05       0  5640.5      .1       0    5785     .05       0
  6184.1     .16       0
Bank Sta=4974.3,5015.7
XS Rating Curve= 0 ,0
Exp/Cntr=0.3,0.1

Type RM Length L Ch R = 1 ,90439   ,490,490,490
BEGIN DESCRIPTION:
LITTLE CEDAR CREEK 91.0
END DESCRIPTION:
XS GIS Cut Line= 3
      3548528.78     10334967.56      3546966.33     10334602.99
       3546316.2      10334121.9
#Sta/Elev= 30
  3793.1  418.31  3861.6  415.72    4019  412.69  4303.1  402.03  4369.6  400.97
  4683.1  390.51  4810.4  391.82    4946  391.64  4985.7  390.51  4991.1  386.13
  4998.4   384.8  5001.1   384.3  5004.4   384.8  5011.7  387.73  5021.9  389.76
  5033.4  391.75  5052.7   392.8  5106.9   393.1  5145.1  391.03  5378.8  391.89
  5452.5  394.45  5487.9  392.69  5529.6  392.72  5579.7  394.62  5744.7  396.61
  5851.1  399.38  5879.3  401.44  5995.1  405.53  6116.2  412.47  6206.3  414.96
#Mann= 6 ,-1 , 0
  3793.1     .05       0    4946     .16       0  4998.4     .07       0
  5004.4     .16       0  5106.9     .05       0  5879.3     .16       0
#XS Ineff= 2 , 0
                         5456.82          394.57
Permanent Ineff=
       F       F
Bank Sta=4985.7,5021.9
XS Rating Curve= 0 ,0
Exp/Cntr=0.3,0.1

Type RM Length L Ch R = 1 ,89949   ,926,926,926
BEGIN DESCRIPTION:
LITTLE CEDAR CREEK 90.0
END DESCRIPTION:
XS GIS Cut Line= 3
      3548392.12     10334741.65      3547592.11     10334291.64
      3546792.08     10333491.62
#Sta/Elev= 30
  4053.2  417.49  4207.2   411.8  4305.7  406.13    4531  397.97  4720.3  393.55
  4779.6   391.1  4817.2  387.94  4844.9  387.79  4876.4  389.91  4968.2  390.62
  4974.6  390.62  4985.2  388.28  4996.4  383.95  4999.1  383.45  5002.4  383.95
  5013.5  387.95  5021.1  388.59  5049.2  390.17  5070.1  391.12  5126.7  390.24
  5239.8  391.02  5437.8   389.3  5579.2  389.66  5684.4  391.36  5763.1  393.59
  5819.6  397.49  5890.3  400.04  5996.4  406.91  6050.5   411.5  6102.5  414.41
#Mann= 8 ,-1 , 0
  4053.2      .1       0  4305.7     .05       0  4996.4     .03       0
  5002.4     .05       0  5021.1     .16       0  5049.2     .05       0
  5684.4     .16       0  6050.5      .1       0
Bank Sta=4985.2,5013.5
XS Rating Curve= 0 ,0
Exp/Cntr=0.3,0.1

Type RM Length L Ch R = 1 ,89023   ,1014,1014,1014
BEGIN DESCRIPTION:
LITTLE CEDAR CREEK 88.0
END DESCRIPTION:
XS GIS Cut Line= 3
      3548442.07     10334041.61      3547842.11     10333441.64
      3546879.55     10332563.08
#Sta/Elev= 30
  4138.6  407.83  4562.8  392.48  4803.2  387.33  4878.1  387.71  4972.9  387.23
  4983.5  383.48  4990.5  383.48  4991.2  382.04  4993.9  381.54  4997.2  382.04
  5000.9   382.4  5008.4  386.46  5015.1  386.87  5022.5  387.85  5057.7  386.69
  5100.2  389.39  5121.9  389.05    5157  386.02  5221.1  387.29  5277.3  385.56
  5407.4  391.44    5532  397.02  5546.2  398.84  5581.9  399.15  5702.2  404.67
    5709  404.01  5779.9   406.7  5928.5  408.76  6254.2  407.13  6290.3  406.03
#Mann= 6 ,-1 , 0
  4138.6     .05       0  4878.1     .12       0  4991.2     .07       0
  4997.2     .12       0  5221.1     .05       0  5407.4     .16       0
Bank Sta=4972.9,5015.1
XS Rating Curve= 0 ,0
Exp/Cntr=0.3,0.1

Type RM Length L Ch R = 1 ,88009   ,1121,1121,1121
BEGIN DESCRIPTION:
LITTLE CEDAR CREEK 86.0
END DESCRIPTION:
XS GIS Cut Line= 3
      3548835.15     10333534.68      3548585.16      10333184.7
      3547696.29     10331809.08
#Sta/Elev= 30
  4239.9  401.82    4396  399.68  4426.2  399.77  4566.4  400.01  4595.9  396.77
  4885.2  386.38  4945.9  383.02  4971.3  382.64  4990.6  378.82  4993.4  378.32
  4996.6  378.82  5005.2  380.88  5014.7  382.34  5029.9  385.63  5117.4  385.57
  5159.9     386  5196.2  381.69  5202.1  383.67  5209.4  382.22  5217.3  385.06
  5223.2  382.14  5245.1  385.22  5268.7  385.92  5404.6  387.33  5460.5  385.39
  5485.1  385.94  5534.6  389.85    5632  390.29    5694  391.34  6307.8  407.37
#Mann= 13 ,-1 , 0
  4239.9     .05       0    4396      .1       0  4426.2     .05       0
  4885.2      .1       0  4945.9     .05       0  4990.6     .03       0
  4996.6     .05       0  5005.2      .1       0  5117.4     .16       0
  5460.5      .1       0  5485.1     .16       0    5632      .1       0
    5694     .16       0
Bank Sta=4971.3,5014.7
XS Rating Curve= 0 ,0
Exp/Cntr=0.3,0.1

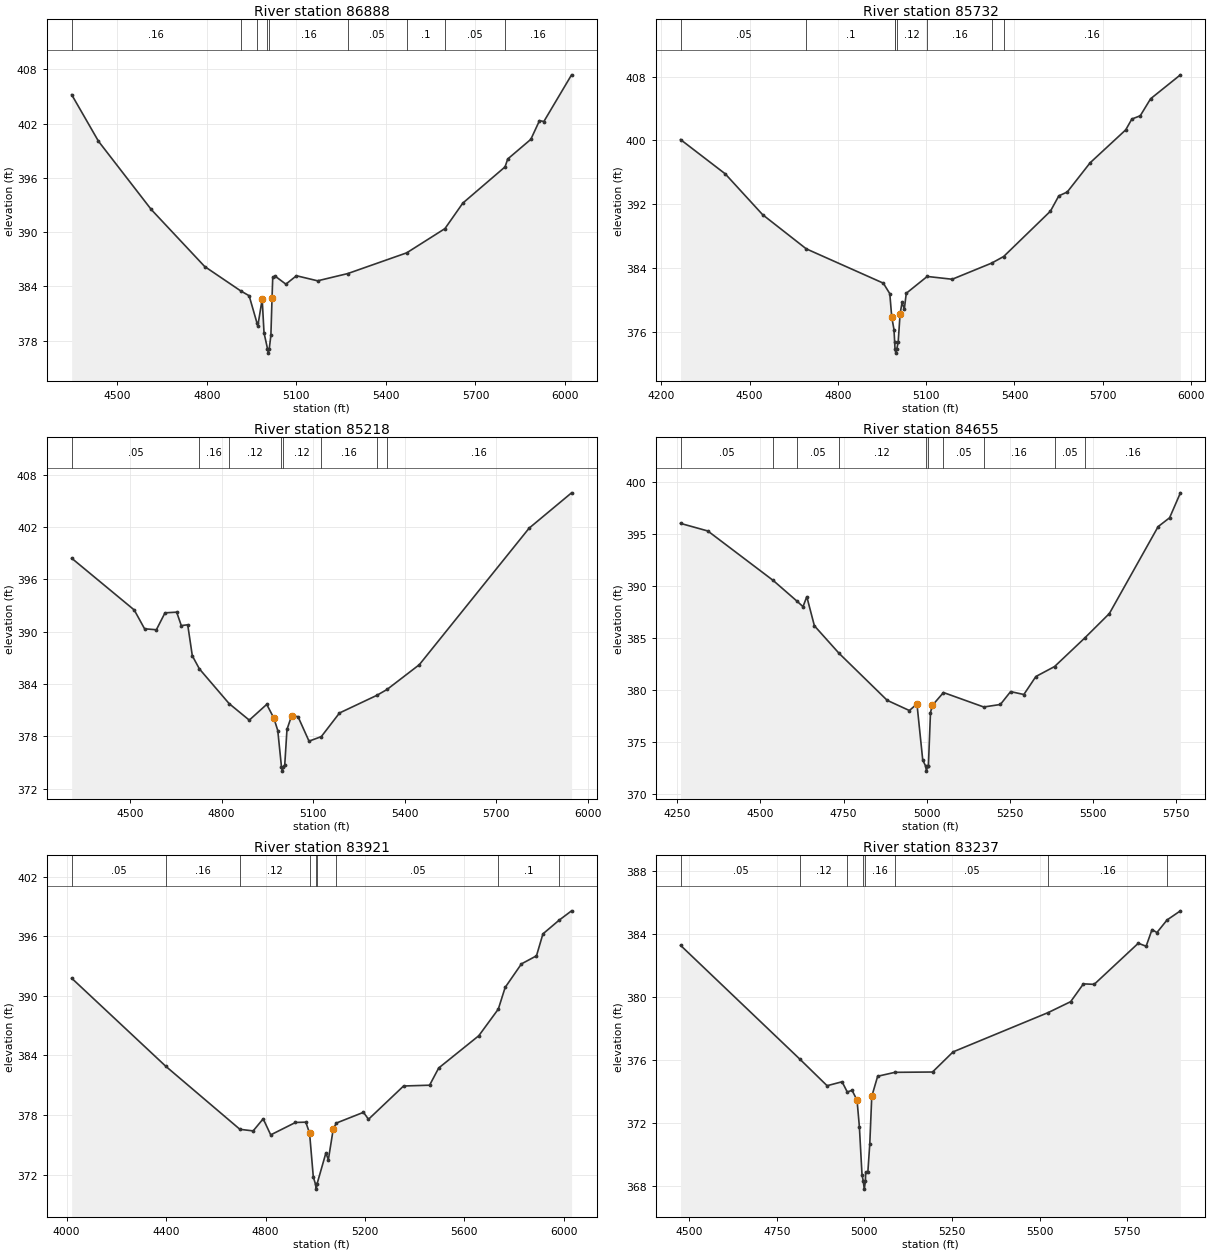
Type RM Length L Ch R = 1 ,86888   ,1156,1156,1156
BEGIN DESCRIPTION:
LITTLE CEDAR CREEK 84.0
END DESCRIPTION:
XS GIS Cut Line= 3
      3549463.27     10332767.67      3549263.29     10332567.68
      3548142.14     10331741.67
#Sta/Elev= 30
  4346.7  405.19  4436.6  400.04  4613.4   392.5  4792.5   386.2  4913.1  383.51
  4941.5  382.97  4967.7  379.97  4970.5  379.62  4985.2  382.59  4991.4  378.87
    5003  377.13  5005.8  376.63    5009  377.13  5014.4  378.59 5018.18  382.67
  5020.6  384.99  5028.5  385.14  5064.6  384.25  5100.1  385.18    5171  384.62
  5271.9  385.42  5469.5  387.71  5597.8  390.39  5657.7  393.21  5799.2  397.21
  5808.1  398.08  5885.5  400.25  5914.6  402.32  5929.2  402.22  6022.1  407.38
#Mann= 9 ,-1 , 0
  4346.7     .16       0  4913.1     .12       0  4967.7     .16       0
    5003     .07       0    5009     .16       0  5271.9     .05       0
  5469.5      .1       0  5597.8     .05       0  5799.2     .16       0
Bank Sta=4985.2,5018.18
XS Rating Curve= 0 ,0
Exp/Cntr=0.3,0.1

Type RM Length L Ch R = 1 ,85732   ,514,514,514
BEGIN DESCRIPTION:
LITTLE CEDAR CREEK 82.0
END DESCRIPTION:
XS GIS Cut Line= 3
      3549785.14      10332263.5      3549385.16     10331863.52
      3548520.16     10331130.78
#Sta/Elev= 30
  4264.9  400.11  4416.9  395.81  4544.1  390.69  4692.4  386.41  4954.3  382.11
  4976.3  380.79  4982.9  377.87  4990.6  376.28  4992.8  374.75  4994.1  373.84
  4996.9  373.34  5000.1  373.84  5004.9  374.79  5011.4  378.29    5018  379.69
  5025.7  378.86  5032.3  380.84  5103.5  382.95  5188.4   382.6    5323  384.63
  5363.4  385.45  5522.3  391.13  5550.8  393.05  5579.4  393.53  5657.4   397.2
  5778.2  401.32  5799.1  402.68  5827.7  403.09  5862.8  405.22  5964.2  408.22
#Mann= 8 ,-1 , 0
  4264.9     .05       0  4692.4      .1       0  4992.8     .12       0
  4994.1     .07       0  5000.1     .12       0  5103.5     .16       0
    5323     .05       0  5363.4     .16       0
Bank Sta=4982.9,5011.4
XS Rating Curve= 0 ,0
Exp/Cntr=0.3,0.1

Type RM Length L Ch R = 1 ,85218   ,563,563,563
BEGIN DESCRIPTION:
LITTLE CEDAR CREEK 80.0
END DESCRIPTION:
XS GIS Cut Line= 3
      3550145.93     10331710.74      3549845.92     10331560.74
      3548755.82     10330845.16
#Sta/Elev= 30
  4308.2  398.44  4513.4   392.5  4547.3  390.34    4586  390.23  4614.3  392.17
  4652.6  392.25  4667.7  390.71  4688.8   390.8  4703.9  387.24  4727.1  385.74
  4824.5  381.76  4890.7  379.86  4947.9  381.67  4971.2   380.1  4984.1  378.67
  4996.2  374.51  4998.9  374.01  5002.2  374.51    5007  374.72  5014.3  378.79
  5029.4  380.35  5050.5  380.26  5086.6  377.45  5126.9  377.97  5186.5  380.68
  5309.3  382.71  5342.5  383.38  5448.3  386.22  5808.5  401.89  5947.6  405.94
#Mann= 8 ,-1 , 0
  4308.2     .05       0  4727.1     .16       0  4824.5     .12       0
  4996.2     .07       0  5002.2     .12       0  5126.9     .16       0
  5309.3     .05       0  5342.5     .16       0
Bank Sta=4971.2,5029.4
XS Rating Curve= 0 ,0
Exp/Cntr=0.3,0.1

Type RM Length L Ch R = 1 ,84655   ,734,734,734
BEGIN DESCRIPTION:
LITTLE CEDAR CREEK 79.0
END DESCRIPTION:
XS GIS Cut Line= 3
      3550516.68     10331304.38      3549842.11     10330991.64
      3549142.13     10330691.65
#Sta/Elev= 30
  4259.2  396.03  4341.4   395.3  4538.3  390.54  4608.8  388.58    4628  388.02
  4639.4  388.98  4662.3  386.18  4736.3  383.54  4881.5  379.01  4948.2  378.03
  4971.1  378.66  4988.5  373.26    4997   372.7  4999.7   372.2    5003   372.7
  5005.5   372.7  5011.8  377.83  5017.3  378.52  5050.9  379.76  5172.1  378.37
  5222.2  378.61    5253  379.85  5292.9  379.57  5329.1   381.3  5385.4  382.26
  5475.7  384.99  5550.4  387.36  5697.2  395.72  5731.7  396.57  5764.3  398.97
#Mann= 10 ,-1 , 0
  4259.2     .05       0  4538.3     .16       0  4608.8     .05       0
  4736.3     .12       0    4997     .07       0    5003     .12       0
  5050.9     .05       0  5172.1     .16       0  5385.4     .05       0
  5475.7     .16       0
Bank Sta=4971.1,5017.3
XS Rating Curve= 0 ,0
Exp/Cntr=0.3,0.1

Type RM Length L Ch R = 1 ,83921   ,684,684,684
BEGIN DESCRIPTION:
LITTLE CEDAR CREEK 77.0
END DESCRIPTION:
XS GIS Cut Line= 3
      3550592.13     10330941.68      3550299.66     10330427.64
      3548892.11     10330241.64
#Sta/Elev= 30
  4020.1  391.78    4399  382.91    4697  376.57  4750.3  376.41  4790.6  377.63
  4820.9  376.01  4920.6  377.26  4962.1  377.29  4977.3  376.18  4992.3  371.77
  5001.1  371.05  5003.9  370.55  5007.1  371.05  5042.8  374.18  5052.9  373.52
  5072.6  376.61    5085   377.2  5194.1  378.28  5214.3  377.58  5355.5  380.93
  5460.1  381.01  5496.7  382.74  5658.1  385.99  5736.6  388.67  5764.1  390.85
  5829.6  393.22  5890.1  394.03  5916.1  396.24  5981.3  397.62  6031.3  398.56
#Mann= 9 ,-1 , 0
  4020.1     .05       0    4399     .16       0    4697     .12       0
  4977.3     .16       0  5001.1     .07       0  5007.1     .16       0
    5085     .05       0  5736.6      .1       0  5981.3     .16       0
Bank Sta=4977.3,5072.6
XS Rating Curve= 0 ,0
Exp/Cntr=0.3,0.1

Type RM Length L Ch R = 1 ,83237   ,933,933,933
BEGIN DESCRIPTION:
LITTLE CEDAR CREEK 76.0
END DESCRIPTION:
XS GIS Cut Line= 3
      3550642.11     10330391.64      3550292.11     10329991.64
      3549492.14     10329591.66
#Sta/Elev= 30
  4475.6  383.27  4816.8  376.02  4893.7  374.35  4936.4   374.6  4951.3  373.95
  4964.9  374.06  4979.1  373.43  4985.8  371.74  4993.3  368.69    4997  368.28
  4999.7  367.78    5003  368.28  5003.8  368.84  5009.9  368.84  5015.5  370.67
  5021.1  373.67  5037.9  374.95  5087.2   375.2  5194.4  375.22  5253.1   376.5
  5524.7     379  5588.5  379.69  5624.8  380.82  5655.6  380.79  5781.3   383.4
  5803.7  383.21  5820.5  384.27  5834.5  384.08  5863.4  384.88  5901.5  385.46
#Mann= 8 ,-1 , 0
  4475.6     .05       0  4816.8     .12       0  4951.3     .16       0
    4997     .07       0    5003     .16       0  5087.2     .05       0
  5524.7     .16       0  5863.4     .05       0
Bank Sta=4979.1,5021.1
XS Rating Curve= 0 ,0
Exp/Cntr=0.3,0.1