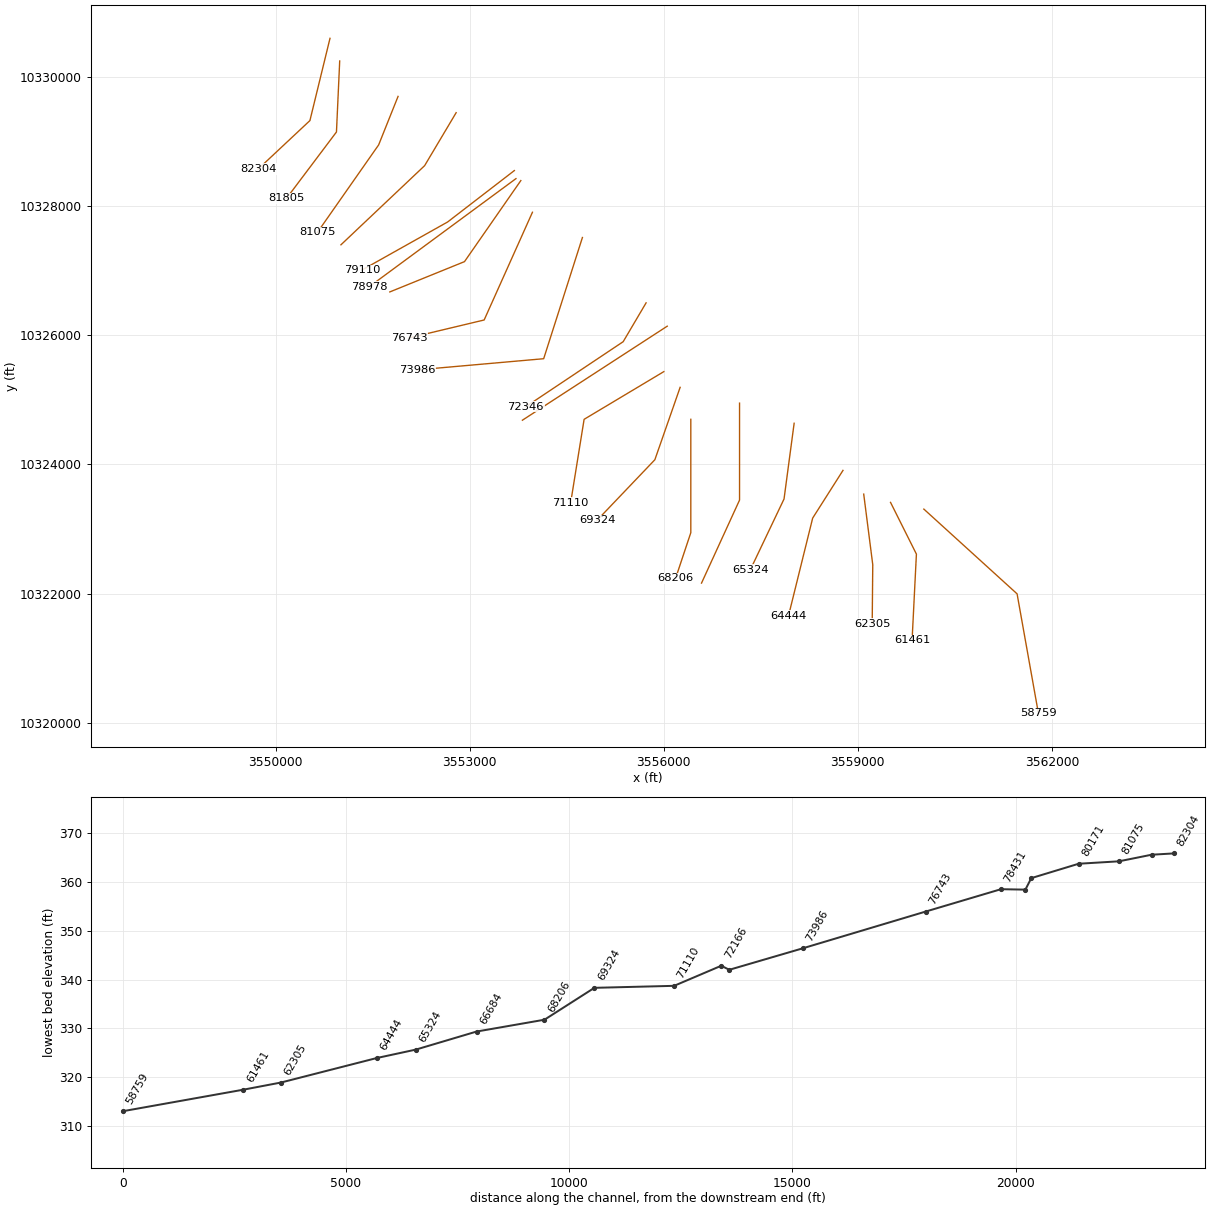
HEC-RAS study LITTLE CEDAR CREEK.prj: LITTLE CEDAR CREEK Base Level Engineering

--- LITTLE CEDAR CREEK.g01 (geometry) --- (continued)

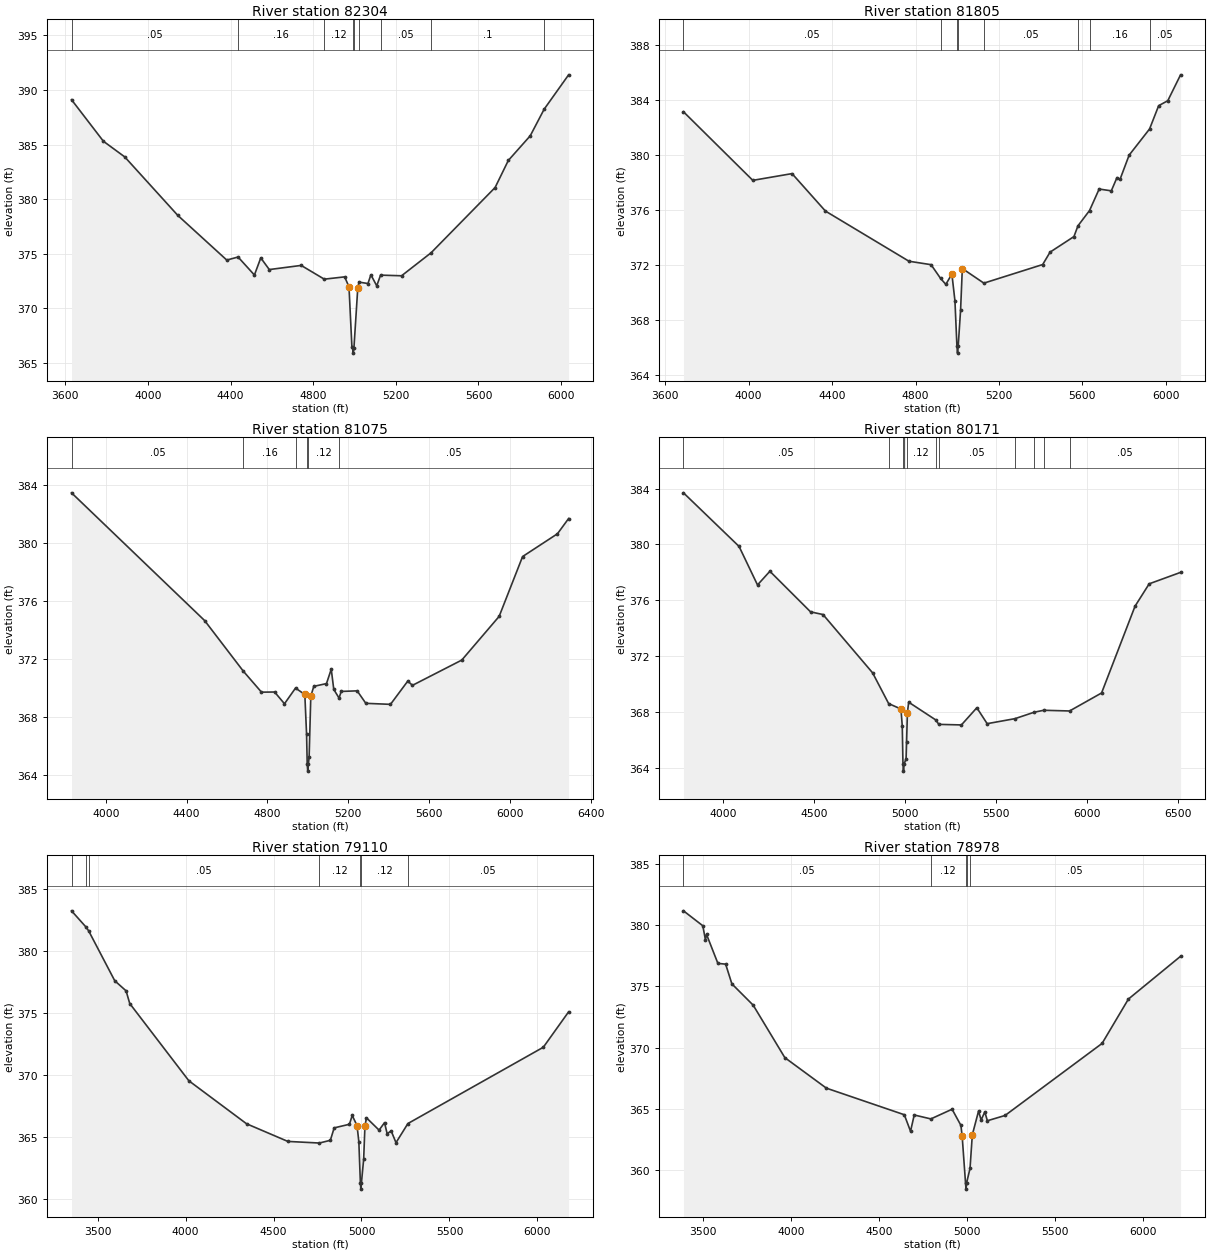
Type RM Length L Ch R = 1 ,82304   ,499,499,499
BEGIN DESCRIPTION:
LITTLE CEDAR CREEK 74.0
END DESCRIPTION:
XS GIS Cut Line= 3
      3550842.11     10330591.68      3550531.69     10329319.42
      3549731.67      10328569.4
#Sta/Elev= 30
  3630.3  389.11  3784.7   385.3  3887.7  383.87    4145   378.5  4381.8  374.41
  4436.5  374.69  4515.6  373.04  4546.4  374.61  4587.6  373.54    4742  373.92
  4853.8  372.66  4952.4  372.87  4973.4  371.96  4987.5  366.47  4991.4  366.38
  4994.2  365.88  4997.4  366.38  5015.9  371.85    5022  372.39  5065.2  372.26
  5079.4  373.06  5107.7  372.05  5126.3  373.03  5227.9  372.97  5370.9  375.08
  5680.7  381.06  5744.6  383.54  5850.7   385.8  5918.1  388.24  6036.5  391.39
#Mann= 9 ,-1 , 0
  3630.3     .05       0  4436.5     .16       0  4853.8     .12       0
  4991.4     .07       0  4997.4     .12       0    5022     .16       0
  5126.3     .05       0  5370.9      .1       0  5918.1     .05       0
Bank Sta=4973.4,5015.9
XS Rating Curve= 0 ,0
Exp/Cntr=0.3,0.1

Type RM Length L Ch R = 1 ,81805   ,730,730,730
BEGIN DESCRIPTION:
LITTLE CEDAR CREEK 73.0
END DESCRIPTION:
XS GIS Cut Line= 3
       3550992.1      10330241.6      3550942.02     10329142.92
      3550170.55      10328117.3
#Sta/Elev= 30
  3687.5  383.13  4019.9  378.15    4208  378.64  4368.2  375.92  4768.6  372.28
  4874.5  372.03  4920.3  371.03  4945.3   370.6  4974.4  371.35    4989  369.41
  4998.6  366.11  5001.4  365.61  5004.6  366.11  5016.1  368.74  5024.4  371.75
  5127.7  370.69  5409.7  372.04  5445.1  372.94  5559.6  374.07  5578.8  374.85
  5634.3  375.96  5680.4  377.52  5738.7  377.39  5765.8  378.35  5780.4  378.22
  5824.1  379.98  5922.1  381.88  5965.7  383.57  6009.4  383.93  6070.7  385.81
#Mann= 8 ,-1 , 0
  3687.5     .05       0  4920.3     .12       0  4998.6     .07       0
  5004.6     .12       0  5127.7     .05       0  5578.8      .1       0
  5634.3     .16       0  5922.1     .05       0
Bank Sta=4974.4,5024.4
XS Rating Curve= 0 ,0
Exp/Cntr=0.3,0.1

Type RM Length L Ch R = 1 ,81075   ,904,904,904
BEGIN DESCRIPTION:
LITTLE CEDAR CREEK 72.0
END DESCRIPTION:
XS GIS Cut Line= 3
      3551894.19     10329693.39      3551594.19     10328943.38
        3550647.     10327589.26
#Sta/Elev= 30
  3830.5  383.43  4489.4  374.63  4680.5  371.15  4770.7   369.7  4835.7  369.71
  4884.5   368.9  4939.1  369.98  4985.2  369.54  4993.9  366.79    4997  364.76
  4999.7  364.26    5003  364.76  5006.5  365.23  5014.8  369.42  5029.6   370.1
  5092.4  370.29    5116  371.28  5128.5  369.89  5154.7  369.29  5165.2  369.75
  5244.2  369.79  5287.2  368.93  5409.2  368.86  5494.7  370.46    5518  370.17
  5762.1  371.91    5947  374.92    6063  379.04  6235.6  380.61  6290.8  381.66
#Mann= 6 ,-1 , 0
  3830.5     .05       0  4680.5     .16       0  4939.1     .12       0
    4997     .07       0    5003     .12       0  5154.7     .05       0
Bank Sta=4985.2,5014.8
XS Rating Curve= 0 ,0
Exp/Cntr=0.3,0.1

Type RM Length L Ch R = 1 ,80171   ,1061,1061,1061
BEGIN DESCRIPTION:
LITTLE CEDAR CREEK 70.0
END DESCRIPTION:
XS GIS Cut Line= 3
      3552792.09     10329441.62      3552304.87     10328622.09
       3551011.5     10327398.16
#Sta/Elev= 30
  3781.6   383.7  4087.4  379.86  4188.8   377.1  4256.9  378.08  4480.8  375.17
  4549.1  374.98    4822   370.8  4910.1   368.6  4977.8  368.21    4985     367
  4988.9  364.26  4991.7  363.76  4994.9  364.26  5006.1  364.65  5008.8  365.88
  5013.3  367.94  5020.2   368.7    5169  367.43    5186  367.11  5310.3  367.07
  5395.2   368.3  5451.9  367.16  5605.2  367.52  5710.4  367.98    5763  368.12
  5905.3  368.07  6081.3  369.36  6265.4  375.58  6343.1  377.18  6515.7     378
#Mann= 11 ,-1 , 0
  3781.6     .05       0  4910.1      .1       0  4988.9     .07       0
  4994.9      .1       0  5008.8     .12       0    5169     .16       0
    5186     .05       0  5605.2     .16       0  5710.4     .05       0
    5763      .1       0  5905.3     .05       0
Bank Sta=4977.8,5013.3
XS Rating Curve= 0 ,0
Exp/Cntr=0.3,0.1

Type RM Length L Ch R = 1 ,79110   ,132,132,132
BEGIN DESCRIPTION:
LITTLE CEDAR CREEK 68.0
END DESCRIPTION:
XS GIS Cut Line= 3
       3553692.1     10328546.43      3552660.84     10327751.28
       3551332.7     10327005.72
#Sta/Elev= 30
  3351.9  383.21  3432.6  381.93  3448.8  381.61  3597.7  377.58    3662  376.77
  3682.8  375.75  4018.9  369.53  4346.8  366.07  4581.4  364.65  4760.6  364.52
    4823  364.74  4844.7  365.74  4931.4  366.03  4947.3  366.74  4974.8  365.92
    4985  364.61  4993.7  361.31  4996.4  360.81  4999.7  361.31  5012.4  363.24
  5019.6  365.89  5028.3  366.55  5099.9  365.56    5131  366.16  5145.8  365.27
  5168.6   365.5  5196.1  364.55  5263.9  366.09  6033.4  372.23  6177.2  375.08
#Mann= 7 ,-1 , 0
  3351.9     .05       0  3432.6      .1       0  3448.8     .05       0
  4760.6     .12       0  4993.7     .07       0  4999.7     .12       0
  5263.9     .05       0
Bank Sta=4974.8,5019.6
XS Rating Curve= 0 ,0
Exp/Cntr=0.3,0.1

Type RM Length L Ch R = 1 ,78978   ,547,547,547
BEGIN DESCRIPTION:
Mapping XS 691346e7
END DESCRIPTION:
XS GIS Cut Line= 2
      3553716.39     10328421.42      3551443.68     10326745.51
#Sta/Elev= 30
  3388.3  381.16  3498.3  379.94    3513  378.79  3519.2  379.24  3583.9  376.87
  3627.9  376.81  3663.3   375.2  3784.4  373.46  3964.1  369.18  4200.1  366.69
  4642.8  364.52  4678.2  363.17  4699.1   364.5  4793.7  364.18  4914.2  364.97
  4964.4  363.65  4971.6  362.75  4990.6  358.95  4993.4  358.45  4996.6  358.95
  5016.1  360.14  5029.1  362.88  5064.6  364.82  5079.2  364.09  5100.1  364.75
  5114.7  364.03    5215  364.46  5766.3  370.34  5915.9  373.96  6212.1  377.45
#Mann= 5 ,-1 , 0
  3388.3     .05       0  4793.7     .12       0  4990.6     .07       0
  4996.6     .12       0  5016.1     .05       0
Bank Sta=4971.6,5029.1
XS Rating Curve= 0 ,0
Exp/Cntr=0.3,0.1

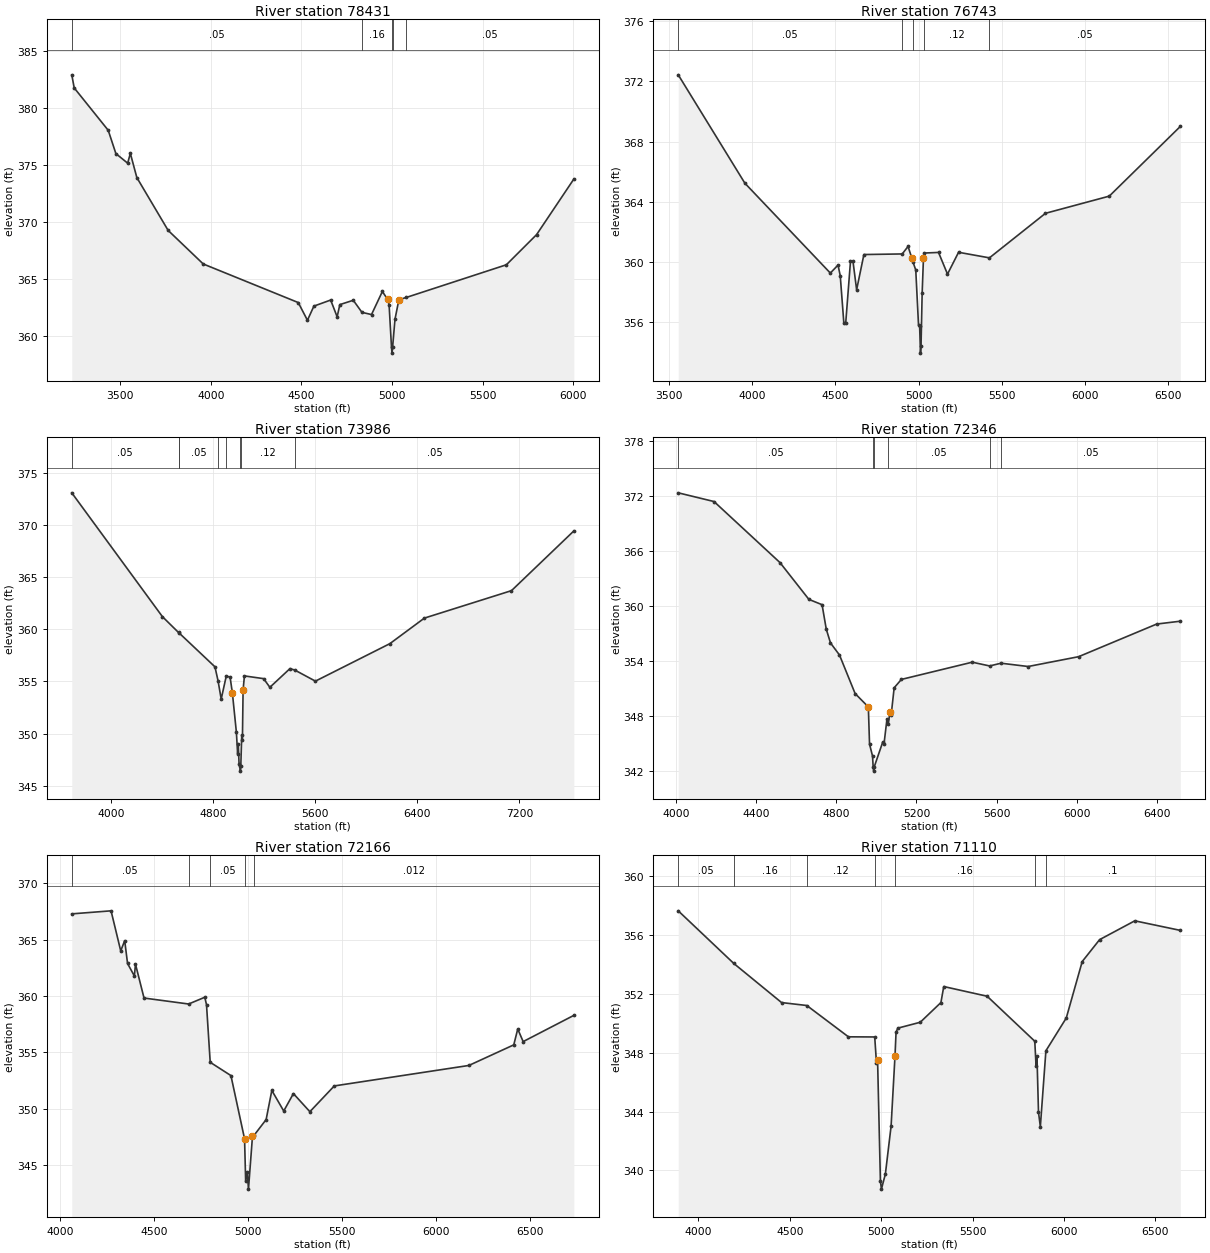
Type RM Length L Ch R = 1 ,78431   ,1688,1688,1688
BEGIN DESCRIPTION:
LITTLE CEDAR CREEK 66.0
END DESCRIPTION:
XS GIS Cut Line= 3
      3553792.13     10328391.68      3552921.19     10327137.71
      3551766.86     10326669.04
#Sta/Elev= 30
  3231.6  382.92  3245.2  381.77  3432.9  378.06  3475.2  376.02  3540.3  375.18
  3555.1  376.04  3590.9  373.92  3763.8  369.29  3957.6  366.35  4482.3  362.97
    4533  361.42  4568.8  362.66  4661.3  363.19  4697.1  361.72  4711.9  362.79
  4786.1  363.17  4834.2  362.11  4886.9  361.92  4946.8  363.94  4976.2  363.24
    4984  362.77  4997.3  359.04  5000.1  358.54  5003.3  359.04  5016.4   361.5
    5038  363.22  5079.4  363.42  5631.6  366.28  5798.4  368.92  6004.2  373.79
#Mann= 5 ,-1 , 0
  3231.6     .05       0  4834.2     .16       0  4997.3     .07       0
  5003.3     .16       0  5079.4     .05       0
Bank Sta=4976.2,5038
XS Rating Curve= 0 ,0
Exp/Cntr=0.3,0.1

Type RM Length L Ch R = 1 ,76743   ,2757,2757,2757
BEGIN DESCRIPTION:
LITTLE CEDAR CREEK 65.0
END DESCRIPTION:
XS GIS Cut Line= 3
      3553971.56     10327901.64      3553225.01     10326234.94
      3552061.78     10325957.15
#Sta/Elev= 30
  3553.4  372.44  3954.5  365.24  4468.9  359.27  4515.3   359.8  4528.6  359.09
  4550.5  355.92  4561.5  355.95  4590.3  360.06  4605.3  360.05  4627.2  358.16
    4671   360.5  4901.8  360.54  4936.9  361.04    4960  360.24  4966.9  359.99
  4983.2  359.47  4999.8  355.81  5006.4  355.76  5011.6  353.95  5014.9  354.45
  5021.7  357.95  5029.6  360.28  5035.1   360.6  5120.3  360.64  5174.2   359.2
  5240.8  360.65  5426.6  360.28    5764  363.24  6147.9  364.38  6575.6  369.01
#Mann= 5 ,-1 , 0
  3553.4     .05       0  4901.8     .12       0  4966.9     .07       0
  5035.1     .12       0  5426.6     .05       0
Bank Sta=4960,5029.6
XS Rating Curve= 0 ,0
Exp/Cntr=0.3,0.1

Type RM Length L Ch R = 1 ,73986   ,1640,1640,1640
BEGIN DESCRIPTION:
LITTLE CEDAR CREEK 64.0
END DESCRIPTION:
XS GIS Cut Line= 3
      3554744.12     10327511.01      3554145.15     10325635.98
      3552185.18     10325462.53
#Sta/Elev= 30
  3690.9  373.06  4401.4   361.2  4527.9  359.68  4532.8  359.63  4813.5  356.39
    4838  355.03  4862.4   353.3  4901.9   355.5    4932  355.41    4950  353.89
  4981.5  350.11  4991.2  348.05  4996.4  348.96  5002.5  347.04    5010   346.9
  5012.7   346.4    5016   346.9  5023.3  349.83  5028.6  349.35    5034  354.19
  5044.5  355.52  5194.7  355.26  5243.9  354.43  5401.4  356.22  5439.6  356.08
  5600.8  355.02  6184.4  358.61  6455.4  361.06  7138.1  363.69  7626.9  369.41
#Mann= 8 ,-1 , 0
  3690.9     .05       0  4527.9      .1       0  4532.8     .05       0
    4838     .16       0  4901.9     .12       0    5010     .07       0
    5016     .12       0  5439.6     .05       0
Bank Sta=4950,5034
XS Rating Curve= 0 ,0
Exp/Cntr=0.3,0.1

Type RM Length L Ch R = 1 ,72346   ,180,180,180
BEGIN DESCRIPTION:
LITTLE CEDAR CREEK 63.0
END DESCRIPTION:
XS GIS Cut Line= 3
      3555728.35     10326500.01      3555374.17     10325899.29
       3553867.2     10324892.33
#Sta/Elev= 30
    4009  372.36  4187.9  371.41  4517.7  364.75  4662.1  360.74    4728  360.16
    4749  357.49  4770.1  355.99  4815.1  354.67  4893.2  350.47  4959.3  349.01
  4965.3  344.95  4980.3  343.65  4983.3  342.51    4986  342.01  4989.3  342.51
  5031.3  345.18  5037.4  344.93  5052.4  347.68  5058.9  347.12  5067.4  348.48
  5073.4  348.13  5088.4   351.1  5124.4  352.01  5478.6  353.89  5565.7  353.48
  5622.5  353.78  5758.1  353.42  6010.4  354.49  6400.8  358.05  6518.8  358.36
#Mann= 6 ,-1 , 0
    4009     .05       0  4983.3     .07       0  4989.3     .05       0
  5058.9     .05       0  5565.7     .12       0  5622.5     .05       0
Bank Sta=4959.3,5067.4
XS Rating Curve= 0 ,0
Exp/Cntr=0.3,0.1

Type RM Length L Ch R = 1 ,72166   ,1056,1056,1056
BEGIN DESCRIPTION:
Mapping XS bfe4d31f
END DESCRIPTION:
XS GIS Cut Line= 2
      3556054.76     10326138.89      3553816.13     10324684.66
#Sta/Elev= 30
  4061.1   367.3    4270  367.57  4321.4  364.01  4342.5  364.92  4357.7  362.89
  4393.9  361.78  4399.9  362.83  4445.3  359.82  4682.4  359.29  4768.3  359.89
  4777.5  359.23  4797.2  354.11  4907.3  352.93  4979.8  347.31  4985.7  343.54
  4994.4  344.38  5000.6  342.84    5022  347.55  5030.2  347.62  5094.5  349.02
  5124.8  351.61  5188.1  349.78  5239.5  351.33  5327.1  349.72  5456.9  352.01
  6172.6  353.83  6411.2  355.66  6432.3  357.07  6461.1  355.95  6730.6  358.28
#Mann= 5 ,-1 , 0
  4061.1     .05       0  4682.4      .1       0  4797.2     .05       0
  4979.8     .07       0  5030.2    .012       0
Bank Sta=4979.8,5022
XS Rating Curve= 0 ,0
Exp/Cntr=0.3,0.1

Type RM Length L Ch R = 1 ,71110   ,1786,1786,1786
BEGIN DESCRIPTION:
LITTLE CEDAR CREEK 62.0
END DESCRIPTION:
XS GIS Cut Line= 3
      3556002.83     10325436.35      3554770.15     10324698.48
      3554561.95     10323405.89
#Sta/Elev= 30
  3890.4  357.65  4194.3  354.07  4455.5  351.41  4593.6  351.21  4821.1  349.08
    4965  349.07  4974.7  347.28  4980.6  347.51  4996.1  339.27  5001.7  338.72
  5023.3  339.75  5054.5     343  5075.9  347.77  5081.7   349.4  5091.4  349.67
  5213.9  350.07    5327  351.41  5342.6   352.5  5579.9  351.84  5840.4  348.78
  5847.4   347.1  5852.4  347.75  5860.7  343.95  5870.8  342.97  5901.2  348.13
  6012.6  350.36  6099.8   354.2  6194.9  355.69  6387.4  356.97  6636.3  356.32
#Mann= 7 ,-1 , 0
  3890.4     .05       0  4194.3     .16       0  4593.6     .12       0
    4965     .07       0  5075.9     .16       0  5840.4     .07       0
  5901.2      .1       0
#XS Ineff= 2 , 0
                         5496.59          351.99
Permanent Ineff=
       F       F
Bank Sta=4980.6,5075.9
XS Rating Curve= 0 ,0
Exp/Cntr=0.3,0.1

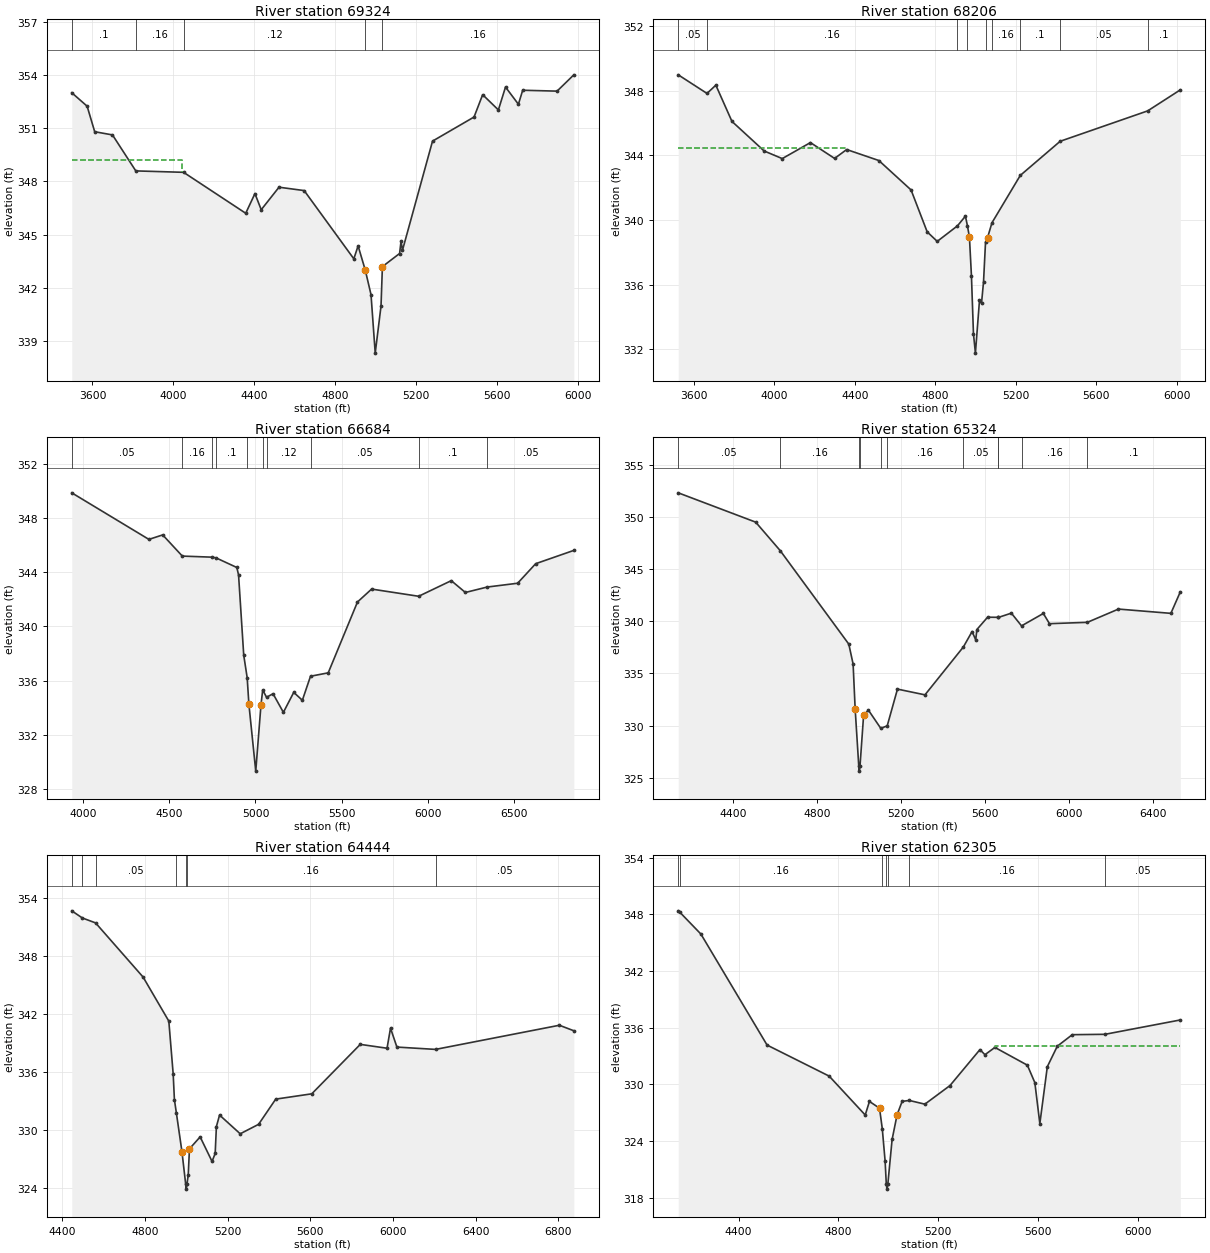
Type RM Length L Ch R = 1 ,69324   ,1118,1118,1118
BEGIN DESCRIPTION:
LITTLE CEDAR CREEK 60.0
END DESCRIPTION:
XS GIS Cut Line= 3
      3556254.53     10325193.29       3555863.9     10324073.48
      3554970.14     10323136.33
#Sta/Elev= 30
  3497.9     353  3573.8  352.24  3611.2   350.8  3699.1  350.62  3814.3  348.59
  4050.4  348.51  4357.5   346.2    4403  347.31  4434.1   346.4    4522  347.67
  4646.3  347.48  4891.7  343.63  4912.8  344.36  4948.3  342.99  4976.6  341.61
  4997.4  338.31    5026  340.96  5032.9  343.19  5117.8  343.93  5125.1  344.63
    5132  344.11  5280.6  350.27  5485.8  351.63  5528.3  352.89    5606  352.03
  5641.2  353.32    5705  352.35  5726.1  353.14    5896  353.09  5978.9  354.01
#Mann= 5 ,-1 , 0
  3497.9      .1       0  3814.3     .16       0  4050.4     .12       0
  4948.3     .07       0  5032.9     .16       0
#XS Ineff= 2 , 0
         4041.48   349.2
Permanent Ineff=
       F       F
Bank Sta=4948.3,5032.9
XS Rating Curve= 0 ,0
Exp/Cntr=0.3,0.1

Type RM Length L Ch R = 1 ,68206   ,1522,1522,1522
BEGIN DESCRIPTION:
LITTLE CEDAR CREEK 58.0
END DESCRIPTION:
XS GIS Cut Line= 3
      3556419.46     10324698.51      3556419.46     10322945.01
      3556185.07     10322241.85
#Sta/Elev= 30
    3523  348.98  3665.9  347.83  3709.9  348.34  3789.9   346.1  3949.9  344.27
  4039.9   343.8  4179.9  344.79  4299.9  343.81  4359.9  344.36  4519.9  343.68
  4679.9  341.86  4759.9  339.27  4809.9  338.68  4910.3  339.64  4949.9  340.24
  4959.9  339.65  4969.9  338.94  4979.9  336.54  4989.9  332.97  4999.6  331.77
  5019.9  335.04  5029.9  334.85  5039.9  336.17  5049.9  338.64  5059.9  338.91
  5081.8  339.83  5222.6  342.76  5420.6  344.87  5855.5  346.75  6017.7  348.05
#Mann= 9 ,-1 , 0
    3523     .05       0  3665.9     .16       0  4910.3     .12       0
  4959.9     .07       0  5049.9     .12       0  5081.8     .16       0
  5222.6      .1       0  5420.6     .05       0  5855.5      .1       0
#XS Ineff= 2 , 0
         4357.39  344.47
Permanent Ineff=
       F       F
Bank Sta=4969.9,5059.9
XS Rating Curve= 0 ,0
Exp/Cntr=0.3,0.1

Type RM Length L Ch R = 1 ,66684   ,1360,1360,1360
BEGIN DESCRIPTION:
LITTLE CEDAR CREEK 57.0
END DESCRIPTION:
XS GIS Cut Line= 3
      3557172.66     10324948.94      3557172.66     10323448.93
      3556585.06     10322165.23
#Sta/Elev= 30
  3934.5  349.84  4381.8  346.41  4461.8  346.74  4575.6  345.18  4749.6   345.1
    4771  345.05  4891.8  344.34  4901.8  343.79  4931.8  337.88  4951.8  336.22
  4961.8  334.26  5001.5  329.34  5031.8  334.21  5041.8  335.32  5064.1  334.78
  5101.8  335.04  5161.8  333.67  5221.8  335.14  5271.8  334.56  5319.1  336.33
  5421.8  336.58  5591.5   341.8  5673.5  342.75  5946.2  342.22  6135.4  343.37
  6217.3   342.5  6343.7   342.9  6520.3  343.18    6625  344.62  6846.3   345.6
#Mann= 10 ,-1 , 0
  3934.5     .05       0  4575.6     .16       0  4749.6     .05       0
    4771      .1       0  4951.8     .07       0  5041.8      .1       0
  5064.1     .12       0  5319.1     .05       0  5946.2      .1       0
  6343.7     .05       0
Bank Sta=4961.8,5031.8
XS Rating Curve= 0 ,0
Exp/Cntr=0.3,0.1

Type RM Length L Ch R = 1 ,65324   ,880,880,880
BEGIN DESCRIPTION:
LITTLE CEDAR CREEK 55.0
END DESCRIPTION:
XS GIS Cut Line= 3
      3558016.67     10324637.67      3557860.43     10323465.84
      3557339.61     10322372.11
#Sta/Elev= 30
  4136.6  352.31  4505.9   349.5  4622.8  346.77  4949.8  337.81  4970.3   335.9
    4980  331.62  4997.2  326.14    5000  325.64  5003.2  326.14  5020.4  331.01
  5043.4  331.48  5102.2  329.74  5132.9  329.98  5181.8   333.5  5312.9  332.95
    5496  337.54  5537.6  339.02  5554.8  338.22  5560.4  339.21  5611.4  340.39
  5662.1  340.38  5662.9  340.37  5724.8  340.78  5773.2  339.56  5877.2  340.75
  5906.5  339.77  6087.2   339.9  6235.4  341.17  6485.2  340.76  6530.2  342.82
#Mann= 11 ,-1 , 0
  4136.6     .05       0  4622.8     .16       0  4997.2     .07       0
  5003.2     .16       0  5102.2     .12       0  5132.9     .16       0
    5496     .05       0  5662.1     .16       0  5662.9      .1       0
  5773.2     .16       0  6087.2      .1       0
Bank Sta=4980,5020.4
XS Rating Curve= 0 ,0
Exp/Cntr=0.3,0.1

Type RM Length L Ch R = 1 ,64444   ,2139,2139,2139
BEGIN DESCRIPTION:
LITTLE CEDAR CREEK 53.0
END DESCRIPTION:
XS GIS Cut Line= 3
      3558771.86     10323908.51      3558303.14      10323170.7
      3557929.86     10321660.25
#Sta/Elev= 30
  4445.9  352.72    4497  351.98  4561.1  351.47  4791.1  345.86  4915.6   341.3
  4936.7  335.83  4942.7  333.16  4951.9  331.83  4979.1  327.79  4997.3   324.4
    5000   323.9  5003.3   324.4  5009.6  325.36  5015.5  328.07  5067.2  329.31
  5124.8  326.77    5140  327.59  5145.9  330.38  5161.2  331.57  5261.1  329.63
  5350.1  330.61    5433  333.22  5607.5  333.77  5842.3  338.89  5971.8  338.49
  5988.6  340.57  6019.5  338.61  6206.5  338.37  6805.8  340.87  6875.9   340.3
#Mann= 7 ,-1 , 0
  4445.9      .1       0    4497     .16       0  4561.1     .05       0
  4951.9     .16       0  4997.3     .07       0  5003.3     .16       0
  6206.5     .05       0
Bank Sta=4979.1,5015.5
XS Rating Curve= 0 ,0
Exp/Cntr=0.3,0.1

Type RM Length L Ch R = 1 ,62305   ,844,844,844
BEGIN DESCRIPTION:
LITTLE CEDAR CREEK 51.0
END DESCRIPTION:
XS GIS Cut Line= 3
       3559092.1     10323541.67      3559231.96     10322450.21
      3559223.27     10321538.74
#Sta/Elev= 30
    4158  348.37  4164.4  348.22  4248.8  345.91    4514  334.15  4762.9  330.86
  4907.3  326.74  4924.2  328.18  4964.6  327.46  4975.7  325.28    4987  321.86
  4991.8  319.39  4994.6  318.89  4997.8  319.39    5015  324.15  5035.1  326.78
  5055.3  328.19  5084.3  328.28  5146.3  327.89  5246.9  329.86    5367  333.67
    5387  333.13    5427   333.9    5557  332.02    5587  330.17    5607  325.83
    5637  331.86    5677  334.03    5737  335.25  5868.1  335.29  6169.9  336.81
#Mann= 7 ,-1 , 0
    4158      .1       0  4164.4     .16       0  4975.7     .12       0
  4991.8     .07       0  4997.8     .12       0  5084.3     .16       0
  5868.1     .05       0
#XS Ineff= 2 , 0
                         5427.56          334.01
Permanent Ineff=
       F       F
Bank Sta=4964.6,5035.1
XS Rating Curve= 0 ,0
Exp/Cntr=0.3,0.1

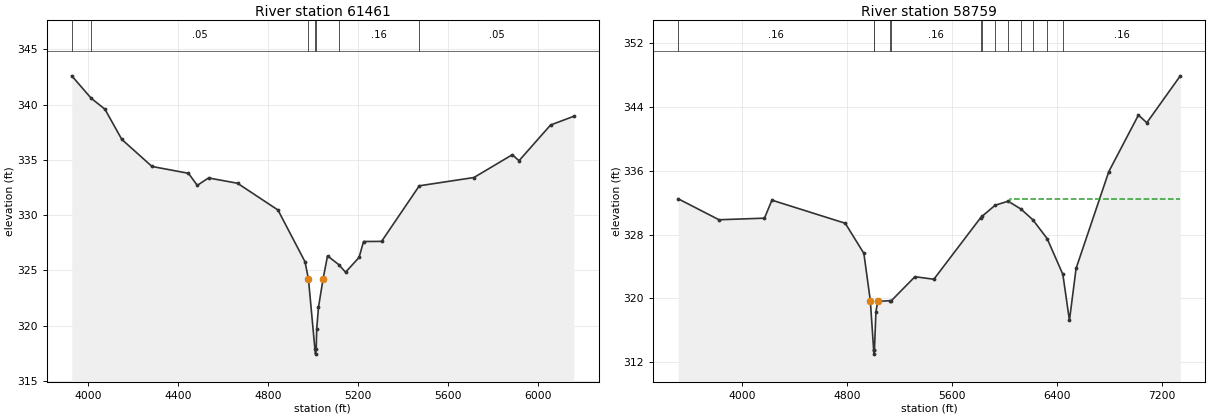
Type RM Length L Ch R = 1 ,61461   ,2702,2702,2702
BEGIN DESCRIPTION:
LITTLE CEDAR CREEK 50.0
END DESCRIPTION:
XS GIS Cut Line= 3
      3559506.69     10323413.51      3559906.69     10322613.52
      3559839.59     10321278.32
#Sta/Elev= 30
  3928.6   342.6  4014.4  340.58    4076  339.58  4150.9  336.85  4285.1   334.4
  4447.2  333.78  4486.3  332.69  4536.6  333.36  4665.2  332.88  4844.9  330.46
  4965.1  325.78  4980.5   324.2    5009  317.92  5011.8  317.42    5015  317.92
  5017.1  319.68  5025.1  321.67  5045.2  324.19  5065.2  326.31  5115.1  325.52
  5145.3  324.83  5205.4  326.17  5225.4  327.61  5305.5  327.62  5473.1  332.65
    5716   333.4  5886.2  335.46  5916.3  334.92  6056.4  338.15  6159.9  338.94
#Mann= 7 ,-1 , 0
  3928.6     .16       0  4014.4     .05       0  4980.5     .12       0
    5009     .07       0    5015     .12       0  5115.1     .16       0
  5473.1     .05       0
Bank Sta=4980.5,5045.2
XS Rating Curve= 0 ,0
Exp/Cntr=0.3,0.1

Type RM Length L Ch R = 1 ,58759   ,2904,2904,2904
BEGIN DESCRIPTION:
LITTLE CEDAR CREEK 49.0
END DESCRIPTION:
XS GIS Cut Line= 3
      3560021.89     10323309.59      3561462.86     10321998.82
      3561792.72     10320149.86
#Sta/Elev= 30
  3514.3   332.5  3824.8  329.87  4171.4  330.07  4228.2  332.33    4787  329.43
  4928.9  325.65  4978.2  319.71  5003.6   313.5  5006.3     313  5009.6   313.5
  5020.8  318.33    5035  319.62  5127.3  319.71  5137.9   319.7  5318.1  322.72
  5462.2   322.4  5818.9  330.13  5830.2  330.31  5929.2  331.69  6028.3   332.2
  6127.3   331.2  6216.4  329.87  6325.5  327.51  6445.4  323.01  6495.5  317.24
  6546.3  323.77  6795.6  335.92  7021.2  343.01  7085.2  342.05  7340.4  347.94
#Mann= 13 ,-1 , 0
  3514.3     .16       0  5003.6     .07       0  5009.6     .16       0
  5127.3     .12       0  5137.9     .16       0  5818.9      .1       0
  5830.2     .16       0  5929.2      .1       0  6028.3     .16       0
  6127.3     .05       0  6216.4     .16       0  6325.5     .05       0
  6445.4     .16       0
#XS Ineff= 2 , 0
                         6045.45          332.48
Permanent Ineff=
       F       F
Bank Sta=4978.2,5035
XS Rating Curve= 0 ,0
Exp/Cntr=0.3,0.1