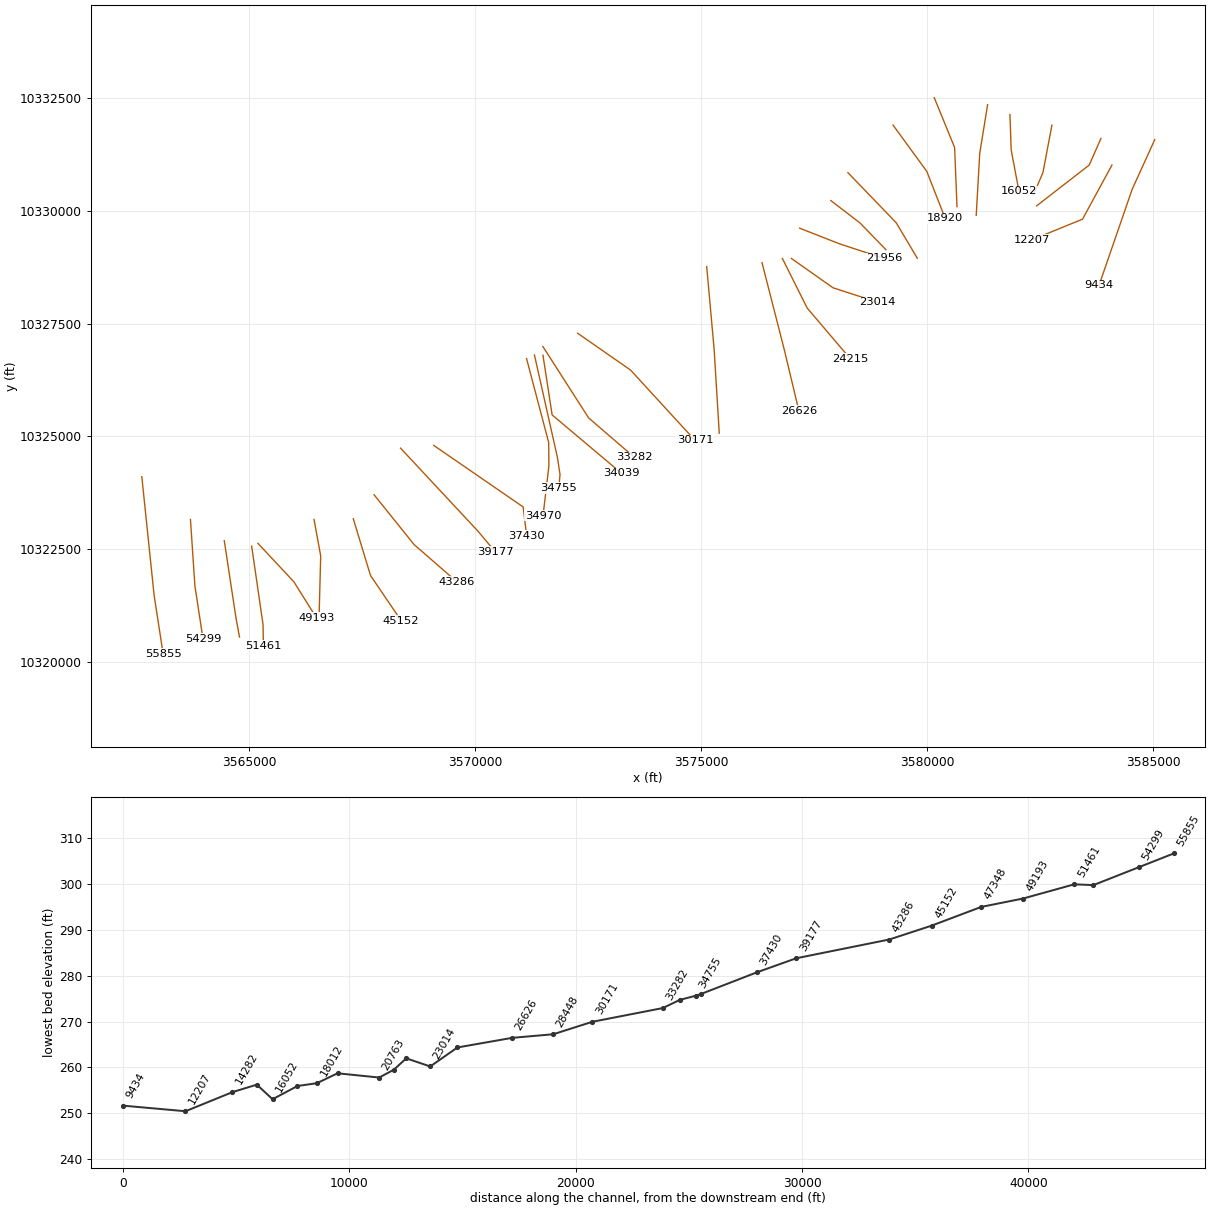
HEC-RAS study LITTLE CEDAR CREEK.prj: LITTLE CEDAR CREEK Base Level Engineering

--- LITTLE CEDAR CREEK.g01 (geometry) --- (continued)

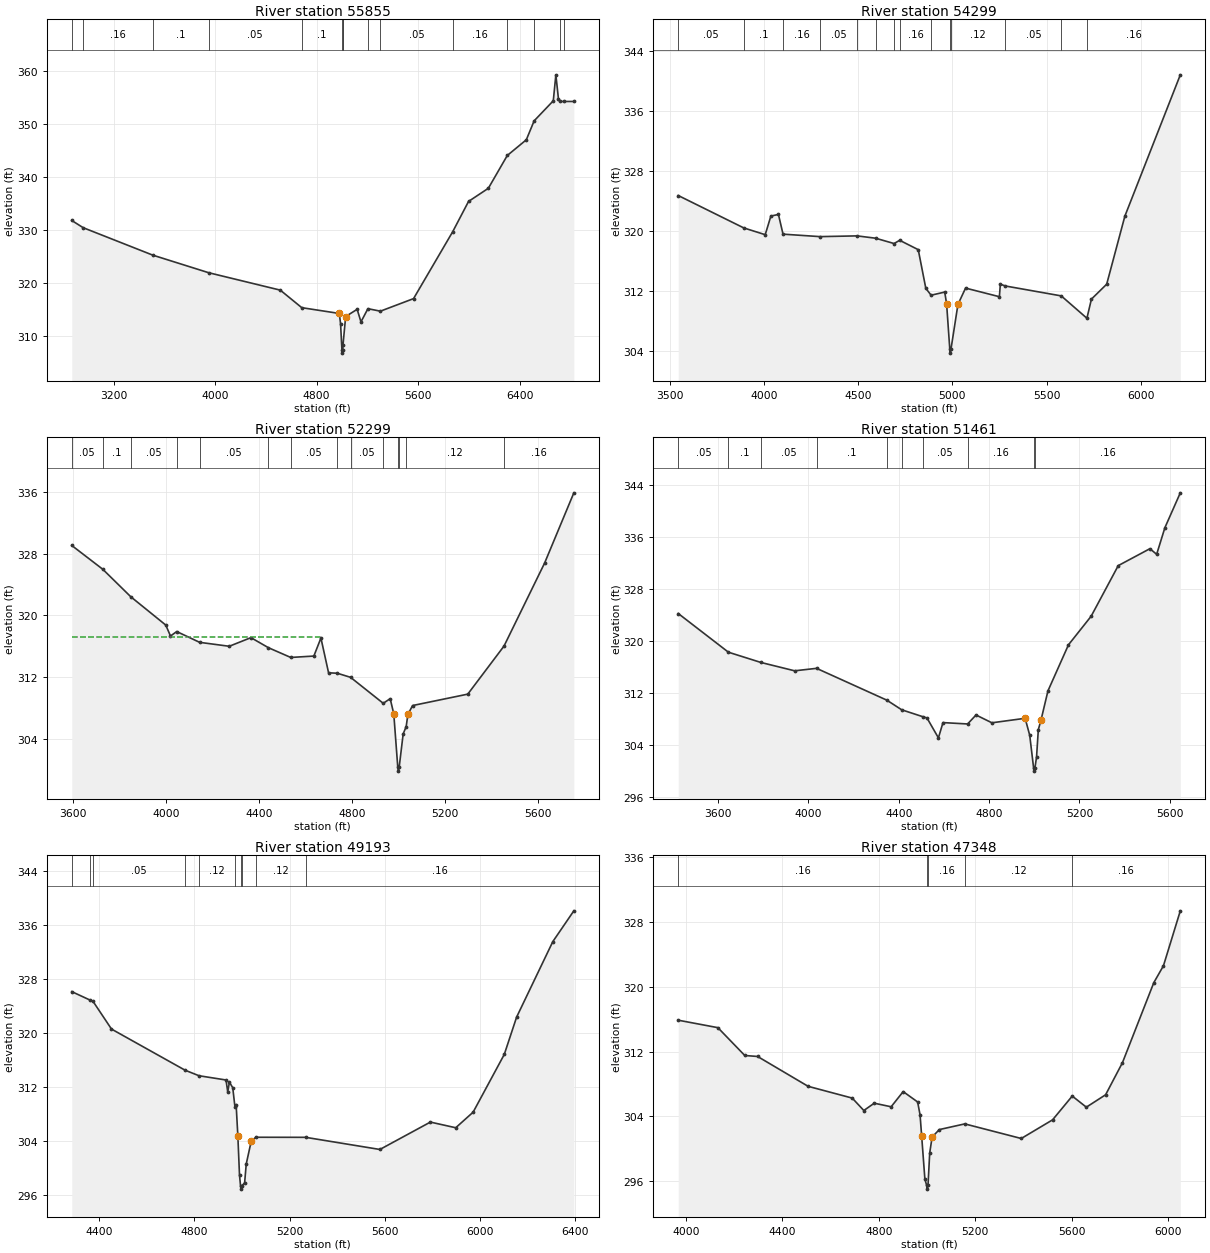
Type RM Length L Ch R = 1 ,55855   ,1556,1556,1556
BEGIN DESCRIPTION:
LITTLE CEDAR CREEK 48.0
END DESCRIPTION:
XS GIS Cut Line= 3
      3562617.37     10324108.23      3562889.67     10321481.57
      3563089.67      10320181.6
#Sta/Elev= 30
  2870.6  331.77  2960.5  330.41  3509.9  325.22  3949.4  321.91  4513.8  318.62
  4682.9  315.31  4978.4  314.22  4988.5  312.29  4999.5  307.23  5002.3  306.73
  5005.5  307.23  5007.3  308.19  5028.7  313.64  5119.2     315  5149.3  312.63
    5204  315.12  5302.3  314.65  5563.6  317.02  5872.5  329.67  5996.9  335.37
  6152.9  337.85  6302.1  344.04  6452.2  347.01  6513.7  350.58  6664.7  354.37
  6684.9  359.27  6705.1  354.78  6717.8  354.24  6750.6  354.24  6826.6  354.24
#Mann= 15 ,-1 , 0
  2870.6      .1       0  2960.5     .16       0  3509.9      .1       0
  3949.4     .05       0  4682.9      .1       0  4999.5     .07       0
  5005.5      .1       0  5007.3     .12       0    5204     .16       0
  5302.3     .05       0  5872.5     .16       0  6302.1      .1       0
  6513.7     .16       0  6717.8      .1       0  6750.6     .16       0
Bank Sta=4978.4,5028.7
XS Rating Curve= 0 ,0
Exp/Cntr=0.3,0.1

Type RM Length L Ch R = 1 ,54299   ,2000,2000,2000
BEGIN DESCRIPTION:
LITTLE CEDAR CREEK 46.0
END DESCRIPTION:
XS GIS Cut Line= 3
      3563693.76     10323161.98      3563792.11     10321691.64
      3563971.37     10320515.55
#Sta/Elev= 30
  3545.8  324.71  3893.6  320.39  4007.2  319.49  4037.2  321.97  4077.3  322.19
  4101.7  319.56  4298.1  319.23  4494.4  319.33  4592.6  319.02  4690.7  318.31
  4720.5  318.74    4819  317.49  4859.1  312.34  4887.1  311.42  4959.3  311.84
  4969.3   310.3  4986.4   304.2  4989.1   303.7  4992.4   304.2  5029.5  310.19
    5070  312.37  5249.4  311.22  5254.4  312.89  5281.3  312.65  5577.5  311.33
  5713.7  308.35  5737.6   310.9  5818.6  312.89    5915  321.96  6209.1   340.8
#Mann= 14 ,-1 , 0
  3545.8     .05       0  3893.6      .1       0  4101.7     .16       0
  4298.1     .05       0  4494.4      .1       0  4592.6     .05       0
  4690.7      .1       0  4720.5     .16       0  4887.1     .12       0
  4986.4     .07       0  4992.4     .12       0  5281.3     .05       0
  5577.5     .12       0  5713.7     .16       0
Bank Sta=4969.3,5029.5
XS Rating Curve= 0 ,0
Exp/Cntr=0.3,0.1

Type RM Length L Ch R = 1 ,52299   ,838,838,838
BEGIN DESCRIPTION:
LITTLE CEDAR CREEK 44.0
END DESCRIPTION:
XS GIS Cut Line= 3
      3564442.11     10322691.63      3564700.71      10320983.2
      3564778.84     10320557.81
#Sta/Elev= 30
  3594.7  329.08  3728.2  325.99  3848.8  322.42  3999.2  318.75  4019.5  317.33
  4046.3  317.91    4145  316.51  4272.3     316  4365.7  317.12  4441.2  315.81
  4536.9  314.55  4636.4  314.73  4666.8  317.07  4699.7  312.56  4737.4   312.5
  4794.4  311.97  4934.9   308.6  4964.8   309.2  4980.3  307.23  4997.5   300.3
  5000.3   299.8  5003.5   300.3  5020.7  304.63  5033.6  305.57    5041  307.15
  5061.2  308.31  5298.7  309.79  5454.7  316.03  5629.2  326.79  5755.1  335.91
#Mann= 14 ,-1 , 0
  3594.7     .05       0  3728.2      .1       0  3848.8     .05       0
  4046.3      .1       0    4145     .05       0  4441.2      .1       0
  4536.9     .05       0  4737.4     .12       0  4794.4     .05       0
  4934.9      .1       0  4997.5     .07       0  5003.5      .1       0
  5033.6     .12       0  5454.7     .16       0
#XS Ineff= 2 , 0
         4666.19  317.25
Permanent Ineff=
       F       F
Bank Sta=4980.3,5041
XS Rating Curve= 0 ,0
Exp/Cntr=0.3,0.1

Type RM Length L Ch R = 1 ,51461   ,2268,2268,2268
BEGIN DESCRIPTION:
LITTLE CEDAR CREEK 42.0
END DESCRIPTION:
XS GIS Cut Line= 3
      3565047.93     10322571.69      3565299.66     10320835.63
      3565308.34     10320366.93
#Sta/Elev= 30
  3423.4  324.21  3645.6  318.26  3788.9  316.69  3938.8   315.4  4035.8  315.78
  4346.9  310.89  4412.7  309.41  4505.1  308.36  4524.8  308.15  4575.4  305.09
  4595.6  307.44  4704.6  307.23  4741.9  308.61  4812.1  307.41  4959.3   308.1
  4979.6   305.5  4996.8  300.48  4999.5  299.98  5002.8  300.48  5009.9  302.15
  5017.7  306.35  5030.1   307.9  5060.4  312.32  5151.3   319.4  5251.6  323.79
  5371.6  331.57  5511.7  334.17  5541.7  333.31  5578.1   337.4  5646.4  342.76
#Mann= 10 ,-1 , 0
  3423.4     .05       0  3645.6      .1       0  3788.9     .05       0
  4035.8      .1       0  4346.9     .05       0  4412.7     .16       0
  4505.1     .05       0  4704.6     .16       0  4996.8     .07       0
  5002.8     .16       0
Bank Sta=4959.3,5030.1
XS Rating Curve= 0 ,0
Exp/Cntr=0.3,0.1

Type RM Length L Ch R = 1 ,49193   ,1845,1845,1845
BEGIN DESCRIPTION:
LITTLE CEDAR CREEK 41.0
END DESCRIPTION:
XS GIS Cut Line= 3
       3565186.8     10322632.52      3565983.08     10321780.53
       3566483.1      10320980.5
#Sta/Elev= 30
  4285.1  326.15  4362.9  324.88    4374  324.73    4452   320.6  4761.3   314.5
  4819.8  313.68  4933.2  313.05  4940.5  311.26  4947.4  312.74  4961.5   311.9
  4970.8  309.04  4975.7  309.41    4983   304.7  4989.9  298.93  4994.2  297.37
  4996.9  296.87  5000.2  297.37  5011.4  297.81  5018.2   300.6  5039.2  303.99
  5058.7  304.56  5267.7  304.55  5579.7  302.75  5791.9  306.81  5898.4  305.97
  5971.5  308.28  6102.4  316.84  6154.3  322.38  6306.4  333.57  6394.7  338.13
#Mann= 10 ,-1 , 0
  4285.1     .05       0  4362.9     .16       0    4374     .05       0
  4761.3     .16       0  4819.8     .12       0  4970.8     .16       0
  4994.2     .07       0  5000.2     .16       0  5058.7     .12       0
  5267.7     .16       0
Bank Sta=4983,5039.2
XS Rating Curve= 0 ,0
Exp/Cntr=0.3,0.1

Type RM Length L Ch R = 1 ,47348   ,2196,2196,2196
BEGIN DESCRIPTION:
LITTLE CEDAR CREEK 39.0
END DESCRIPTION:
XS GIS Cut Line= 3
      3566428.13     10323162.04      3566575.71     10322354.73
      3566542.11     10321091.67
#Sta/Elev= 30
  3967.2  315.86  4131.8  314.94  4243.4  311.51  4296.6  311.39  4506.4  307.71
  4689.5  306.26  4737.6  304.73  4780.9  305.63    4851  305.19    4901  307.06
    4961  305.78    4971   304.2 4977.84  301.53  4991.1  296.27  4998.1  295.54
  5000.8  295.04  5004.1  295.54  5011.1  299.49  5021.1  301.46  5051.1  302.38
  5156.7  303.08  5391.2  301.28  5521.2  303.58  5602.8  306.51  5661.3  305.14
  5741.3  306.67  5811.3  310.63  5941.4  320.49  5981.4  322.57  6051.4  329.34
#Mann= 5 ,-1 , 0
  3967.2     .16       0  4998.1     .07       0  5004.1     .16       0
  5156.7     .12       0  5602.8     .16       0
Bank Sta=4977.84,5021.1
XS Rating Curve= 0 ,0
Exp/Cntr=0.3,0.1

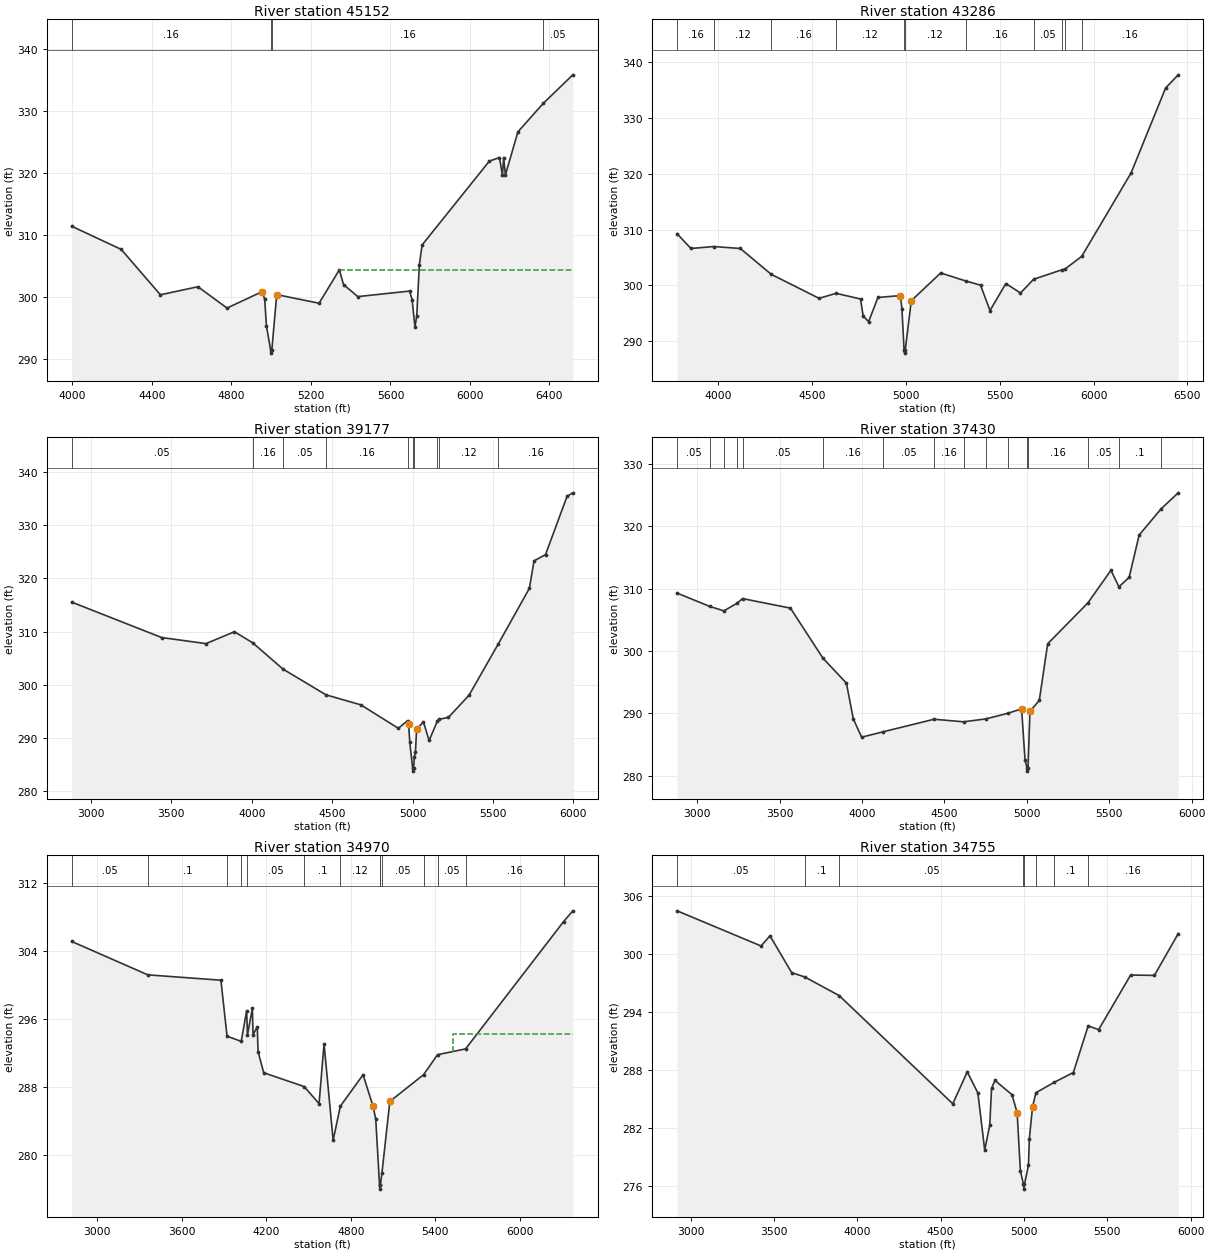
Type RM Length L Ch R = 1 ,45152   ,1866,1866,1866
BEGIN DESCRIPTION:
LITTLE CEDAR CREEK 38.0
END DESCRIPTION:
XS GIS Cut Line= 3
       3567296.2     10323179.35      3567678.14      10321920.7
       3568355.2     10320922.47
#Sta/Elev= 30
  3996.2  311.41  4245.1  307.68  4442.5  300.35  4631.3  301.65  4777.6  298.21
  4955.2  300.87  4967.2  299.62  4976.1   295.3  4997.1  291.44  4999.9  290.94
  5003.1  291.44  5027.8  300.38  5240.8  298.99  5342.9  304.38  5363.9     302
  5435.8  300.06  5696.3  300.95  5709.1  299.54  5723.3  295.16  5732.2  296.88
  5745.4  305.15  5759.3  308.39  6097.7  321.92  6148.6   322.5  6163.5  319.63
  6169.6   322.5  6178.5   319.7  6241.4  326.64  6369.4  331.25  6517.7  335.84
#Mann= 4 ,-1 , 0
  3996.2     .16       0  4997.1     .07       0  5003.1     .16       0
  6369.4     .05       0
#XS Ineff= 2 , 0
                         5341.48          304.39
Permanent Ineff=
       F       F
Bank Sta=4955.2,5027.8
XS Rating Curve= 0 ,0
Exp/Cntr=0.3,0.1

Type RM Length L Ch R = 1 ,43286   ,4109,4109,4109
BEGIN DESCRIPTION:
LITTLE CEDAR CREEK 37.0
END DESCRIPTION:
XS GIS Cut Line= 3
      3567756.27     10323708.89      3568641.68     10322606.46
       3569587.5     10321782.12
#Sta/Elev= 30
  3782.4  309.24  3855.8  306.61  3978.1  306.96  4118.9  306.61  4283.8  301.99
  4538.2  297.71  4629.2   298.6    4759  297.59  4773.4  294.53  4802.2  293.54
  4851.8  297.86  4971.8   298.2  4979.8  295.75  4991.2  288.42  4993.9  287.92
  4997.2  288.42  5029.4  297.29  5186.2  302.24  5318.2  300.82  5398.2  300.06
  5448.6  295.53  5533.1  300.35  5610.9  298.66  5681.3  301.12  5834.6  302.84
  5846.5   302.9  5937.2  305.21  6199.5  320.08  6383.7  335.27    6451  337.63
#Mann= 11 ,-1 , 0
  3782.4     .16       0  3978.1     .12       0  4283.8     .16       0
  4629.2     .12       0  4991.2     .07       0  4997.2     .12       0
  5318.2     .16       0  5681.3     .05       0  5834.6     .16       0
  5846.5     .05       0  5937.2     .16       0
Bank Sta=4971.8,5029.4
XS Rating Curve= 0 ,0
Exp/Cntr=0.3,0.1

Type RM Length L Ch R = 1 ,39177   ,1747,1747,1747
BEGIN DESCRIPTION:
LITTLE CEDAR CREEK 35.0
END DESCRIPTION:
XS GIS Cut Line= 3
      3568342.13     10324741.62      3570056.61      10322901.6
      3570442.09     10322441.66
#Sta/Elev= 30
  2881.2  315.56  3440.3  308.91  3715.9  307.77  3892.7     310  4006.6  307.92
  4194.4  302.99  4461.7  298.15  4678.3  296.27  4911.9  291.86  4968.8   293.3
  4975.4  292.73  4982.7  289.27  5000.7  284.32  5003.5  283.82  5006.7  284.32
    5011  286.52  5017.9  287.32  5025.2  291.71  5067.7  293.06  5102.9  289.58
  5154.9  293.26  5164.5  293.54  5223.1  293.92  5350.6  298.05    5533  307.71
  5726.4  318.16    5755   323.3  5826.5  324.49  5960.6  335.44  5996.3  336.09
#Mann= 10 ,-1 , 0
  2881.2     .05       0  4006.6     .16       0  4194.4     .05       0
  4461.7     .16       0  4968.8     .12       0  5000.7     .07       0
  5006.7     .12       0  5154.9     .16       0  5164.5     .12       0
    5533     .16       0
Bank Sta=4975.4,5025.2
XS Rating Curve= 0 ,0
Exp/Cntr=0.3,0.1

Type RM Length L Ch R = 1 ,37430   ,2460,2460,2460
BEGIN DESCRIPTION:
LITTLE CEDAR CREEK 34.0
END DESCRIPTION:
XS GIS Cut Line= 3
      3569075.74     10324802.62      3571054.87      10323439.8
      3571132.97     10322806.37
#Sta/Elev= 30
  2877.4  309.28  3075.7  307.14  3161.3  306.43  3239.5  307.63  3274.4   308.4
  3565.1  306.87  3761.7  298.87  3904.8  294.84  3946.7   289.1  3997.4  286.17
  4129.5  287.05  4436.7  289.05  4615.9  288.64  4750.1   289.1  4886.3  290.02
    4968  290.72  4988.9  282.53  5000.8  281.23  5003.6  280.73  5006.8  281.23
  5018.7  290.31  5075.5  292.07  5126.2  301.15  5370.1   307.7  5510.3  312.94
  5558.8  310.29  5620.8  311.81  5681.5  318.59  5814.9   322.8  5918.6  325.36
#Mann= 16 ,-1 , 0
  2877.4     .05       0  3075.7      .1       0  3161.3     .05       0
  3239.5      .1       0  3274.4     .05       0  3761.7     .16       0
  4129.5     .05       0  4436.7     .16       0  4615.9      .1       0
  4750.1     .05       0  4886.3     .16       0  5000.8     .07       0
  5006.8     .16       0  5370.1     .05       0  5558.8      .1       0
  5814.9     .05       0
Bank Sta=4968,5018.7
XS Rating Curve= 0 ,0
Exp/Cntr=0.3,0.1

Type RM Length L Ch R = 1 ,34970   ,215,215,215
BEGIN DESCRIPTION:
Mapping XS 1d27dc6a
END DESCRIPTION:
XS GIS Cut Line= 4
      3571130.61     10326725.29      3571620.19     10324865.92
       3571625.4      10324350.3      3571495.19      10323240.9
#Sta/Elev= 30
  2819.7   305.1  3359.4  301.18  3878.2  300.55  3921.8  293.97  4022.3  293.37
  4060.9  296.97  4066.5  294.12  4101.3  297.23  4106.4  294.15  4136.4  295.09
  4141.6  292.17  4181.9  289.68  4468.7  288.06  4574.7  286.05  4609.9  293.08
  4674.5  281.75  4725.9  285.76  4886.7  289.44  4956.7   285.8  4976.7  284.25
  5003.7  276.51  5006.5  276.01  5009.7  276.51  5020.8  277.91  5076.7  286.31
    5316  289.45  5415.3   291.8    5614  292.48  6309.3  307.43  6375.1   308.7
#Mann= 14 ,-1 , 0
  2819.7     .05       0  3359.4      .1       0  3921.8     .05       0
  4022.3     .16       0  4066.5     .05       0  4468.7      .1       0
  4725.9     .12       0  5003.7     .07       0  5009.7     .12       0
  5020.8     .05       0    5316      .1       0  5415.3     .05       0
    5614     .16       0  6309.3      .1       0
#XS Ineff= 2 , 0
                         5522.73          294.23
Permanent Ineff=
       F       F
Bank Sta=4956.7,5076.7
XS Rating Curve= 0 ,0
Exp/Cntr=0.3,0.1

Type RM Length L Ch R = 1 ,34755   ,716,716,716
BEGIN DESCRIPTION:
LITTLE CEDAR CREEK 32.0
END DESCRIPTION:
XS GIS Cut Line= 4
      3571305.96      10326803.4       3571812.9     10324539.54
      3571871.82     10324156.77      3571843.18     10323857.34
#Sta/Elev= 30
  2918.3  304.49    3422  300.85  3475.7   301.9  3605.8  298.09  3685.5  297.63
    3891  295.71  4573.1   284.5  4659.8  287.81  4723.7  285.62  4764.7   279.7
  4795.1   282.3  4805.7   286.1  4826.2  286.92  4928.6  285.44  4959.4  283.57
  4978.8  277.57  4997.4  276.16  5000.1  275.66  5003.4  276.16  5027.3  278.13
  5032.5  280.86  5051.6  284.17  5072.3  285.65  5181.8  286.72  5296.8  287.74
  5385.6  292.57  5448.6  292.18  5640.7  297.84  5783.2   297.8  5926.3  302.13
#Mann= 8 ,-1 , 0
  2918.3     .05       0  3685.5      .1       0    3891     .05       0
  4997.4     .04       0  5003.4     .05       0  5072.3     .16       0
  5181.8      .1       0  5385.6     .16       0
Bank Sta=4959.4,5051.6
XS Rating Curve= 0 ,0
Exp/Cntr=0.3,0.1

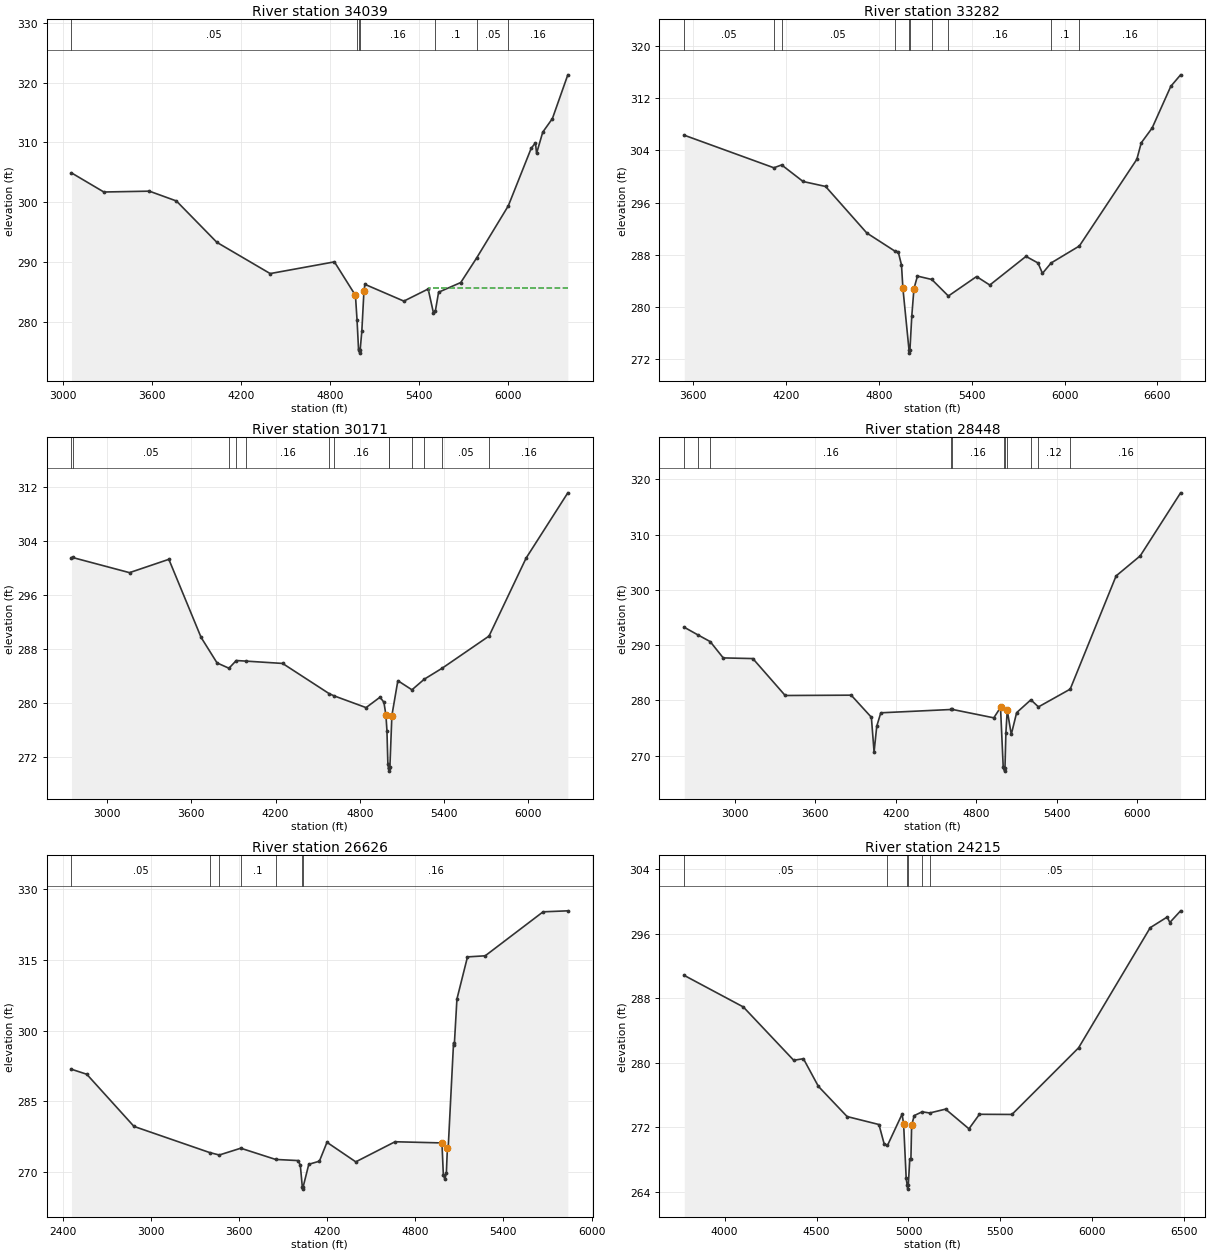
Type RM Length L Ch R = 1 ,34039   ,757,757,757
BEGIN DESCRIPTION:
Mapping XS a826089a
END DESCRIPTION:
XS GIS Cut Line= 3
      3571493.78     10326800.54       3571696.9     10325476.45
      3573231.64      10324183.9
#Sta/Elev= 30
    3057  304.91  3275.1  301.71    3582  301.85  3764.1  300.21  4037.2  293.28
  4396.5  288.05  4829.6  290.01  4971.4   284.4  4982.3   280.2  4992.2  275.37
    4997  275.23  4999.7  274.73    5003  275.23  5014.3  278.36  5028.6  285.07
  5035.1  286.25  5297.8  283.44  5461.6  285.47  5496.8  281.52  5510.4  281.83
  5531.9  284.93  5681.4  286.55  5788.8  290.68  6001.8  299.39  6156.2  309.03
  6184.8  309.94  6192.5  308.18  6234.2  311.74  6299.1     314  6403.1  321.33
#Mann= 7 ,-1 , 0
    3057     .05       0  4982.3     .16       0    4997     .07       0
    5003     .16       0  5510.4      .1       0  5788.8     .05       0
  6001.8     .16       0
#XS Ineff= 2 , 0
                         5465.91          285.62
Permanent Ineff=
       F       F
Bank Sta=4971.4,5028.6
XS Rating Curve= 0 ,0
Exp/Cntr=0.3,0.1

Type RM Length L Ch R = 1 ,33282   ,3111,3111,3111
BEGIN DESCRIPTION:
LITTLE CEDAR CREEK 31.0
END DESCRIPTION:
XS GIS Cut Line= 3
       3571492.1     10326991.66      3572504.52     10325410.28
       3573511.5      10324542.2
#Sta/Elev= 30
  3542.3  306.32  4121.5  301.33  4171.6  301.77  4310.1  299.23  4455.5  298.47
  4721.9  291.34  4902.4  288.58  4924.8  288.46    4946  286.44  4955.2  282.84
  4994.5  273.44  4997.3  272.94  5000.5  273.44  5012.7  278.68  5026.5  282.82
  5049.1  284.74    5142  284.22  5248.9  281.69  5431.1  284.67  5516.6  283.37
  5750.3  287.76  5828.2  286.75  5856.8  285.16  5912.8  286.75  6095.3  289.35
  6466.7  302.63  6495.2  305.15  6565.5  307.42  6686.2  313.81  6749.5  315.57
#Mann= 10 ,-1 , 0
  3542.3     .05       0  4121.5     .16       0  4171.6     .05       0
  4902.4     .16       0  4994.5     .07       0  5000.5     .16       0
    5142     .05       0  5248.9     .16       0  5912.8      .1       0
  6095.3     .16       0
Bank Sta=4955.2,5026.5
XS Rating Curve= 0 ,0
Exp/Cntr=0.3,0.1

Type RM Length L Ch R = 1 ,30171   ,1723,1723,1723
BEGIN DESCRIPTION:
LITTLE CEDAR CREEK 29.0
END DESCRIPTION:
XS GIS Cut Line= 3
      3572261.46     10327285.29      3573433.34     10326469.31
      3574856.45     10324916.05
#Sta/Elev= 30
  2746.8   301.5  2754.4  301.52  3160.1  299.28  3440.2  301.25  3669.8  289.71
  3783.3  285.94  3868.2  285.15  3920.4  286.29    3992   286.2  4250.3  285.86
  4581.4   281.4  4616.5  281.07  4844.7  279.33    4944  280.87  4971.8  280.12
  4985.9  278.25  4993.3  275.93  5000.1  270.92  5004.5  270.44  5007.3  269.94
  5010.5  270.44  5014.3  270.52  5028.5  278.16    5071  283.31  5171.4  281.96
  5259.2  283.53  5387.8  285.17  5720.5  289.91  5984.3  301.43  6281.4  311.08
#Mann= 13 ,-1 , 0
  2746.8     .16       0  2754.4     .05       0  3868.2     .16       0
  3920.4     .05       0    3992     .16       0  4581.4     .05       0
  4616.5     .16       0  5004.5     .07       0  5010.5     .16       0
  5171.4      .1       0  5259.2     .16       0  5387.8     .05       0
  5720.5     .16       0
Bank Sta=4985.9,5028.5
XS Rating Curve= 0 ,0
Exp/Cntr=0.3,0.1

Type RM Length L Ch R = 1 ,28448   ,1822,1822,1822
BEGIN DESCRIPTION:
LITTLE CEDAR CREEK 28.0
END DESCRIPTION:
XS GIS Cut Line= 3
      3575117.37     10328760.94       3575282.3      10326920.7
      3575395.15     10325071.76
#Sta/Elev= 30
  2622.5  293.24  2725.1  291.85  2815.8  290.65    2913   287.7  3133.8  287.58
  3374.8   280.9  3866.8  280.96  4017.4  276.96  4037.5  270.67  4057.5  275.36
  4087.7  277.77  4613.4  278.37  4618.9  278.39    4930  276.86  4980.1  278.74
  5000.2  267.93  5007.2  267.72  5009.9  267.22  5013.2  267.72  5020.2  274.19
  5029.8  278.05  5030.2  278.21  5060.3  273.86  5100.3   277.8  5206.3  280.12
  5262.9  278.84  5499.5  282.05  5841.7  302.53  6021.7  306.16  6322.5  317.56
#Mann= 11 ,-1 , 0
  2622.5     .16       0  2725.1      .1       0  2815.8     .16       0
  4613.4     .12       0  4618.9     .16       0  5007.2     .07       0
  5013.2     .16       0  5029.8     .12       0  5206.3     .16       0
  5262.9     .12       0  5499.5     .16       0
Bank Sta=4980.1,5030.2
XS Rating Curve= 0 ,0
Exp/Cntr=0.3,0.1

Type RM Length L Ch R = 1 ,26626   ,2411,2411,2411
BEGIN DESCRIPTION:
LITTLE CEDAR CREEK 27.0
END DESCRIPTION:
XS GIS Cut Line= 3
      3576341.34     10328847.74      3576836.12     10326912.02
       3577157.2     10325566.96
#Sta/Elev= 30
  2457.8  291.83    2562  290.77  2883.5  279.72    3399  274.18  3464.5  273.66
  3610.9   275.1  3848.4  272.72    4002  272.48  4016.5  271.49    4030  266.93
  4032.7  266.43    4036  266.93  4074.2  271.69  4146.5  272.35  4198.1  276.35
  4394.2  272.21  4661.8  276.47  4981.2  276.22  4990.7   269.5    5001  268.49
  5011.3  269.84  5018.2  275.05  5023.3  274.85  5060.3  297.46  5065.4  296.95
  5083.3  306.71  5155.2  315.64  5275.9  315.87  5670.2  325.19  5838.6   325.4
#Mann= 7 ,-1 , 0
  2457.8     .05       0    3399      .1       0  3464.5     .16       0
  3610.9      .1       0  3848.4     .16       0    4030     .07       0
    4036     .16       0
Bank Sta=4981.2,5018.2
XS Rating Curve= 0 ,0
Exp/Cntr=0.3,0.1

Type RM Length L Ch R = 1 ,24215   ,1201,1201,1201
BEGIN DESCRIPTION:
LITTLE CEDAR CREEK 26.0
END DESCRIPTION:
XS GIS Cut Line= 3
      3576792.11     10328941.63      3577342.11     10327841.64
      3578294.43     10326721.07
#Sta/Elev= 30
  3780.1  290.83  4101.5  286.92  4375.4  280.31  4428.5   280.5  4509.6  277.08
  4666.1  273.33  4839.4  272.34  4867.4  269.96  4885.5  269.74  4965.2  273.63
  4973.6   272.4  4987.6  265.65  4992.9  264.83  4995.7  264.33  4998.9  264.83
  5007.1  268.01  5013.2  268.01  5017.1  272.25  5031.3  273.45  5074.6  273.92
  5115.2  273.77  5201.6  274.25    5329  271.81  5386.1  273.61  5562.9  273.59
  5925.4  281.85  6315.2  296.75  6407.5  298.07  6421.8  297.39  6480.5  298.84
#Mann= 6 ,-1 , 0
  3780.1     .05       0  4885.5     .16       0  4992.9     .07       0
  4998.9     .16       0  5074.6     .12       0  5115.2     .05       0
Bank Sta=4973.6,5017.1
XS Rating Curve= 0 ,0
Exp/Cntr=0.3,0.1

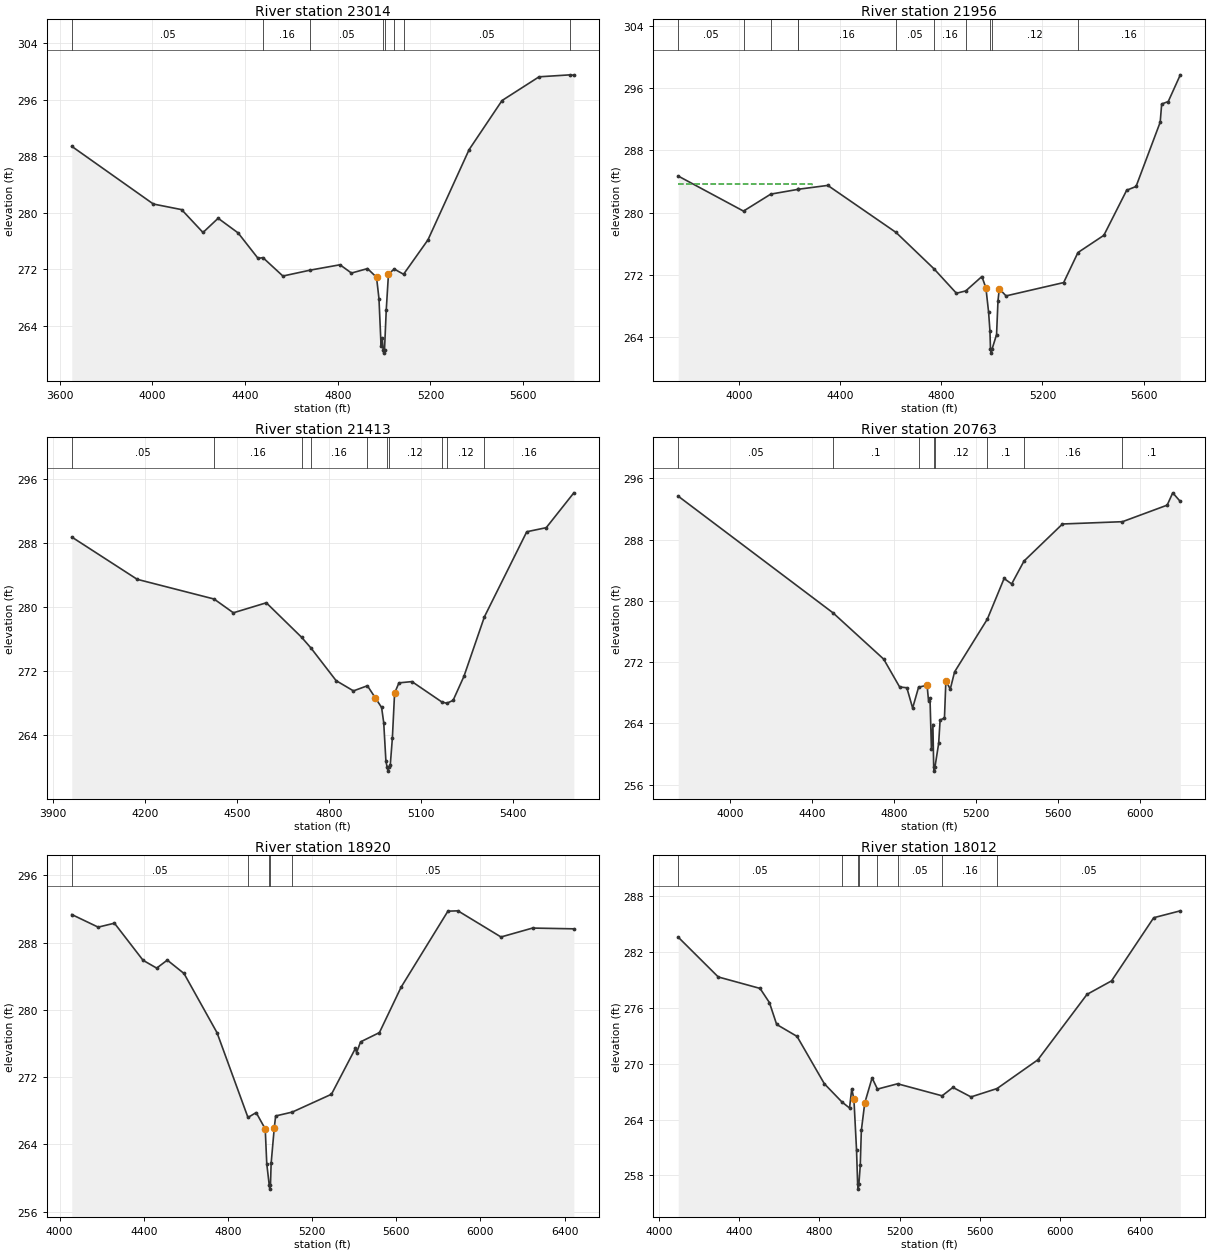
Type RM Length L Ch R = 1 ,23014   ,1058,1058,1058
BEGIN DESCRIPTION:
LITTLE CEDAR CREEK 24.0
END DESCRIPTION:
XS GIS Cut Line= 3
       3576992.1     10328941.65      3577912.51     10328292.23
      3578902.13     10327971.03
#Sta/Elev= 30
  3652.1  289.39  4004.3  281.24  4126.2  280.45  4218.5  277.22  4283.8  279.23
    4370  277.16  4456.2  273.56  4477.1  273.67  4563.3  271.07  4682.3  271.91
  4809.7  272.66  4859.2  271.49  4928.4  272.12  4967.4   270.9  4977.9  267.89
  4987.1  261.13  4992.3  262.25  4995.9  260.68  4998.7  260.18  5001.9  260.68
  5009.4   266.3    5019  271.39  5044.3  272.05  5084.1  271.32  5189.4  276.18
  5366.9  288.92  5509.1  295.86  5668.9  299.21  5803.7  299.49    5819  299.42
#Mann= 8 ,-1 , 0
  3652.1     .05       0  4477.1     .16       0  4682.3     .05       0
  4995.9     .03       0  5001.9     .05       0  5044.3     .16       0
  5084.1     .05       0  5803.7     .16       0
Bank Sta=4967.4,5019
XS Rating Curve= 0 ,0
Exp/Cntr=0.3,0.1

Type RM Length L Ch R = 1 ,21956   ,543,543,543
BEGIN DESCRIPTION:
LITTLE CEDAR CREEK 22.0
END DESCRIPTION:
XS GIS Cut Line= 3
      3577174.69     10329611.66      3578060.08     10329264.45
      3579042.15     10328941.63
#Sta/Elev= 30
    3760   284.7    4018   280.2  4125.8  282.38  4233.2  282.99  4233.5     283
  4351.2   283.5    4621  277.46    4771  272.79  4859.7  269.65  4896.6  269.95
  4960.4   271.8  4976.3  270.33  4986.9  267.23  4992.2  264.84  4994.4  262.46
  4997.2  261.96  5000.4  262.46  5018.4  264.34    5024  268.65  5029.2  270.23
  5055.8  269.31  5283.6  271.02  5340.2  274.88  5442.6  277.09  5532.8  282.88
  5569.8  283.36  5665.3  291.62  5671.1  293.95  5697.1  294.27  5744.8   297.7
#Mann= 11 ,-1 , 0
    3760     .05       0    4018      .1       0  4125.8     .05       0
  4233.2      .1       0  4233.5     .16       0    4621     .05       0
    4771     .16       0  4896.6     .12       0  4994.4     .07       0
  5000.4     .12       0  5340.2     .16       0
#XS Ineff= 2 , 0
         4286.93  283.68
Permanent Ineff=
       F       F
Bank Sta=4976.3,5029.2
XS Rating Curve= 0 ,0
Exp/Cntr=0.3,0.1

Type RM Length L Ch R = 1 ,21413   ,650,650,650
BEGIN DESCRIPTION:
LITTLE CEDAR CREEK 21.0
END DESCRIPTION:
XS GIS Cut Line= 3
        3577864.     10330223.92      3578513.98     10329723.93
      3579083.23     10329135.44
#Sta/Elev= 30
  3960.7  288.72  4174.3  283.44  4425.2  280.98  4488.2  279.26  4595.7  280.51
  4710.7  276.21  4741.1  274.88  4823.5  270.79  4880.1  269.51  4925.7  270.15
  4950.9  268.67    4972  267.44  4978.9  265.55  4986.1  260.72  4990.1  259.99
  4992.8  259.49  4996.1  259.99  5000.3  260.24  5007.2  263.63  5014.4  269.23
  5028.6  270.51    5071  270.67  5167.7  268.15  5184.4  267.96  5205.3  268.32
  5240.8  271.33  5307.7  278.77  5445.8  289.38  5509.4  289.89  5599.5  294.24
#Mann= 10 ,-1 , 0
  3960.7     .05       0  4425.2     .16       0  4710.7     .12       0
  4741.1     .16       0  4925.7     .12       0  4990.1     .07       0
  4996.1     .12       0  5167.7     .16       0  5184.4     .12       0
  5307.7     .16       0
Bank Sta=4950.9,5014.4
XS Rating Curve= 0 ,0
Exp/Cntr=0.3,0.1

Type RM Length L Ch R = 1 ,20763   ,1843,1843,1843
BEGIN DESCRIPTION:
LITTLE CEDAR CREEK 20.0
END DESCRIPTION:
XS GIS Cut Line= 3
      3578242.11     10330841.63      3579310.08      10329733.2
      3579776.97     10328946.41
#Sta/Elev= 30
  3745.2  293.67  4501.9  278.43  4749.4  272.39  4827.4  268.75  4862.6  268.65
  4890.9     266  4920.1  268.73  4961.6  268.97  4968.6  266.95  4975.8  267.26
  4982.7  260.68  4989.9  263.85  4993.9  258.26  4996.6  257.76  4999.9  258.26
  5018.2   261.4  5025.2  264.43  5046.5   264.7  5053.5  269.59  5074.8  268.46
  5095.9  270.72    5256  277.61    5338  282.92    5375  282.21  5435.3   285.2
  5623.4  290.04  5916.6  290.34    6135   292.5  6162.3  294.11  6199.3  292.98
#Mann= 8 ,-1 , 0
  3745.2     .05       0  4501.9      .1       0  4920.1     .12       0
  4993.9     .07       0  4999.9     .12       0    5256      .1       0
  5435.3     .16       0  5916.6      .1       0
Bank Sta=4961.6,5053.5
XS Rating Curve= 0 ,0
Exp/Cntr=0.3,0.1

Type RM Length L Ch R = 1 ,18920   ,908,908,908
BEGIN DESCRIPTION:
LITTLE CEDAR CREEK 18.0
END DESCRIPTION:
XS GIS Cut Line= 3
      3579240.66     10331894.62      3579987.16     10330870.35
      3580395.13     10329828.73
#Sta/Elev= 30
  4057.9  291.34  4183.4  289.84  4260.7  290.31  4396.6   285.9  4461.5  284.97
  4511.8  285.92  4591.3  284.33  4748.2  277.29  4895.3  267.21  4934.3  267.79
  4977.3  265.85  4984.6  261.71  4996.2  259.19    4999  258.69  5002.2  259.19
  5005.4  261.76  5020.1  265.93  5026.8  267.39  5105.7  267.85    5292  269.97
    5406  275.43  5411.3  274.91  5430.4   276.2  5519.9   277.3    5623   282.7
  5845.5  291.74  5893.1  291.78  6097.8  288.67  6247.6  289.73    6444  289.64
#Mann= 5 ,-1 , 0
  4057.9     .05       0  4895.3     .16       0  4996.2     .07       0
  5002.2     .16       0  5105.7     .05       0
Bank Sta=4977.3,5020.1
XS Rating Curve= 0 ,0
Exp/Cntr=0.3,0.1

Type RM Length L Ch R = 1 ,18012   ,863,863,863
BEGIN DESCRIPTION:
LITTLE CEDAR CREEK 17.0
END DESCRIPTION:
XS GIS Cut Line= 3
      3580152.08     10332502.34      3580603.25     10331398.26
      3580655.57     10330089.11
#Sta/Elev= 30
  4096.9  283.58  4296.4  279.31  4504.7  278.08  4551.4  276.56  4587.6  274.21
  4689.1  272.93  4825.4  267.84  4913.3  265.88  4950.9  265.24  4961.9  267.31
  4972.7  266.18  4985.7  260.76  4991.3  257.03    4994  256.53  4997.3  257.03
  5004.3  259.08  5009.7  262.83  5026.7  265.78  5063.2  268.47    5090  267.27
  5190.2  267.84  5412.3  266.55  5466.4  267.45  5556.4  266.43  5686.3  267.33
  5889.4  270.41  6134.7  277.44    6257  278.89  6467.2  285.67  6599.8  286.41
#Mann= 8 ,-1 , 0
  4096.9     .05       0  4913.3     .12       0  4991.3     .07       0
  4997.3     .12       0    5090     .16       0  5190.2     .05       0
  5412.3     .16       0  5686.3     .05       0
Bank Sta=4972.7,5026.7
XS Rating Curve= 0 ,0
Exp/Cntr=0.3,0.1

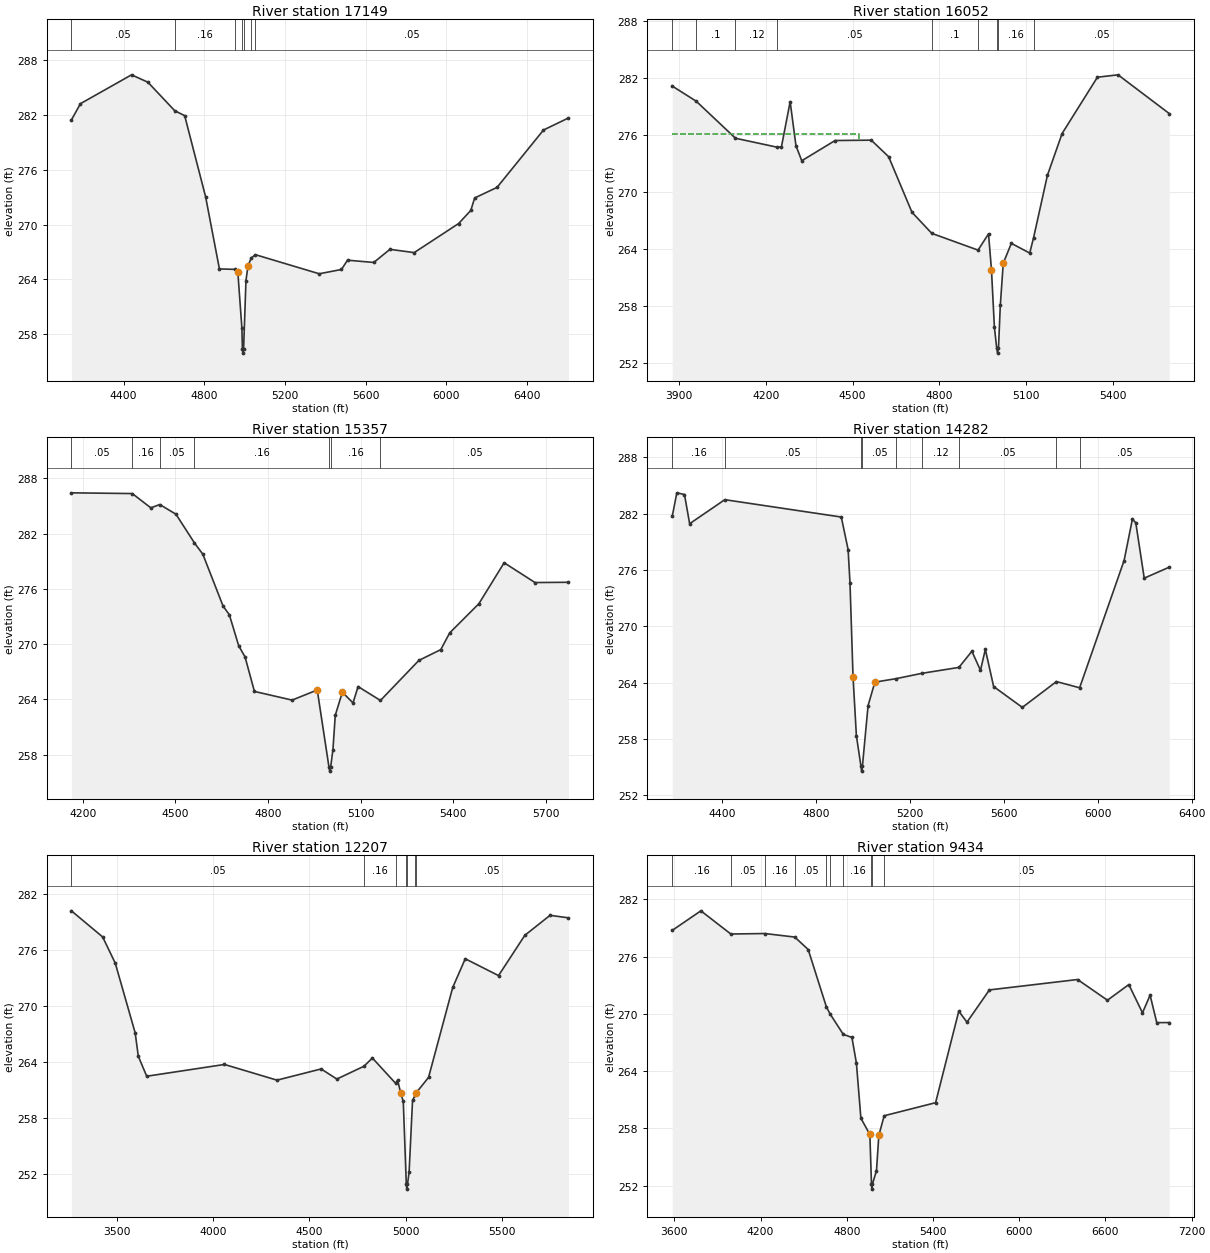
Type RM Length L Ch R = 1 ,17149   ,1097,1097,1097
BEGIN DESCRIPTION:
LITTLE CEDAR CREEK 15.0
END DESCRIPTION:
XS GIS Cut Line= 3
      3581332.65     10332346.04      3581159.04     10331269.66
      3581080.92     10329898.18
#Sta/Elev= 30
  4141.7  281.47  4186.7  283.26  4439.9  286.42  4520.9  285.61  4653.8  282.49
  4703.3  281.94  4807.1  273.04  4875.5  265.14  4954.1  265.09  4966.6  264.85
  4986.9  258.65  4989.4  256.41  4992.2  255.91  4995.4  256.41  5007.1  263.87
  5017.3   265.5  5033.7  266.35  5054.2   266.7  5370.2  264.61  5480.4  265.08
  5510.5   266.1  5640.7  265.85  5720.8  267.29    5841  266.93  6061.4  270.12
  6121.5  271.55  6140.8  272.92  6251.7  274.08    6482  280.37  6605.7  281.69
#Mann= 7 ,-1 , 0
  4141.7     .05       0  4653.8     .16       0  4954.1      .1       0
  4989.4     .07       0  4995.4      .1       0  5033.7     .16       0
  5054.2     .05       0
Bank Sta=4966.6,5017.3
XS Rating Curve= 0 ,0
Exp/Cntr=0.3,0.1

Type RM Length L Ch R = 1 ,16052   ,695,695,695
BEGIN DESCRIPTION:
LITTLE CEDAR CREEK 13.0
END DESCRIPTION:
XS GIS Cut Line= 3
      3581827.44     10332129.04      3581854.75     10331347.72
       3582027.1     10330427.62
#Sta/Elev= 30
  3876.4  281.15  3959.4  279.55  4095.1  275.65  4240.2   274.7    4254  274.76
    4284   279.5  4304.1  274.87  4324.1  273.28  4439.2  275.41  4564.2  275.45
  4624.3  273.71  4705.1  267.85  4773.7  265.63  4933.4  263.87  4969.6  265.58
  4979.8   261.8  4989.9  255.75    4998  253.52  5000.8  253.02    5004  253.52
  5010.3  258.04  5020.5  262.49  5048.5  264.58    5112  263.56  5125.4  265.18
  5173.1  271.74  5223.9  276.15    5346  282.08  5417.2  282.33  5594.3  278.25
#Mann= 9 ,-1 , 0
  3876.4     .05       0  3959.4      .1       0  4095.1     .12       0
  4240.2     .05       0  4773.7      .1       0  4933.4     .16       0
    4998     .07       0    5004     .16       0  5125.4     .05       0
#XS Ineff= 2 , 0
         4522.05  276.11
Permanent Ineff=
       F       F
Bank Sta=4979.8,5020.5
XS Rating Curve= 0 ,0
Exp/Cntr=0.3,0.1

Type RM Length L Ch R = 1 ,15357   ,1075,1075,1075
BEGIN DESCRIPTION:
LITTLE CEDAR CREEK 12.0
END DESCRIPTION:
XS GIS Cut Line= 3
      3582756.26     10331894.66      3582558.34     10330846.54
      3582345.29      10330345.5
#Sta/Elev= 30
  4162.9  286.42  4360.3  286.34  4420.4  284.79  4449.4  285.15  4501.8   284.1
  4561.8  280.98  4588.9  279.76  4654.5  274.13  4674.8  273.19  4705.3  269.81
  4725.7  268.61  4756.2  264.86  4878.3  263.92  4959.8  265.02  4997.5  256.71
  5000.2  256.21  5003.5  256.71  5010.6  258.54  5018.2  262.27  5041.2  264.78
  5075.7  263.61  5092.1  265.39  5164.6  263.88  5289.2  268.23  5360.2   269.4
  5389.2  271.22  5483.8  274.39  5565.6  278.83  5665.6  276.68    5774  276.71
#Mann= 7 ,-1 , 0
  4162.9     .05       0  4360.3     .16       0  4449.4     .05       0
  4561.8     .16       0  4997.5     .07       0  5003.5     .16       0
  5164.6     .05       0
Bank Sta=4959.8,5041.2
XS Rating Curve= 0 ,0
Exp/Cntr=0.3,0.1

Type RM Length L Ch R = 1 ,14282   ,2075,2075,2075
BEGIN DESCRIPTION:
LITTLE CEDAR CREEK 10.0
END DESCRIPTION:
XS GIS Cut Line= 3
      3583841.34     10331599.53      3583580.91     10331009.24
       3582417.8     10330106.53
#Sta/Elev= 30
  4187.1  281.71  4206.7  284.23  4239.4  284.05  4261.3  280.94  4411.1   283.5
  4907.4  281.65  4936.4  278.19  4944.5  274.61  4957.4  264.64  4971.7  258.35
  4991.3  255.08  4994.1  254.58  4997.3  255.08  5021.5  261.56  5050.4  264.06
  5142.5  264.44  5250.7     265  5408.4  265.63  5463.7  267.35  5500.3  265.32
  5521.1  267.55  5556.4  263.59  5678.6  261.37  5823.9  264.12  5922.7  263.46
  6112.2  277.02  6147.5  281.42  6161.9  281.05  6197.9  275.14  6304.6  276.31
#Mann= 9 ,-1 , 0
  4187.1     .16       0  4411.1     .05       0  4991.3     .07       0
  4997.3     .05       0  5142.5     .16       0  5250.7     .12       0
  5408.4     .05       0  5823.9     .16       0  5922.7     .05       0
Bank Sta=4957.4,5050.4
XS Rating Curve= 0 ,0
Exp/Cntr=0.3,0.1

Type RM Length L Ch R = 1 ,12207   ,2773,2773,2773
BEGIN DESCRIPTION:
LITTLE CEDAR CREEK 9.0
END DESCRIPTION:
XS GIS Cut Line= 3
      3584084.39     10331009.26      3583433.34     10329811.32
      3582305.96      10329351.7
#Sta/Elev= 30
  3264.5  280.18  3426.6  277.39  3492.1  274.59  3595.7  267.12  3611.9  264.62
  3655.6  262.48  4059.4  263.74  4332.1  262.06  4561.1  263.26  4642.9  262.18
  4783.7  263.55  4827.4  264.43  4947.7  261.73  4958.4  262.06  4974.8  260.64
  4987.8  259.79  5003.5   250.9  5006.2   250.4  5009.5   250.9    5018  252.21
  5035.9  259.91    5049  260.42  5052.5  260.65  5118.9  262.35  5244.5  271.98
  5309.6  275.05  5482.4  273.25  5618.9  277.56  5749.9   279.7  5845.4  279.43
#Mann= 7 ,-1 , 0
  3264.5     .05       0  4783.7     .16       0  4947.7     .05       0
  5003.5    .035       0  5009.5     .05       0    5049     .16       0
  5052.5     .05       0
Bank Sta=4974.8,5052.5
XS Rating Curve= 0 ,0
Exp/Cntr=0.3,0.1

Type RM Length L Ch R = 1 ,9434    ,1080,1080,1080
BEGIN DESCRIPTION:
LITTLE CEDAR CREEK 8.0
END DESCRIPTION:
XS GIS Cut Line= 3
      3585032.04     10331573.25      3584532.04     10330473.24
      3583798.34     10328345.51
#Sta/Elev= 30
  3585.3  278.75  3784.8   280.8  3993.1  278.37  4229.4  278.42  4438.2  278.05
  4531.7  276.74  4657.8  270.75  4682.8  270.02  4775.8  267.85  4835.9  267.53
  4867.1  264.84  4898.3  259.06  4960.7  257.36  4972.1  252.13  4974.9  251.63
  4978.1  252.13  5006.9  253.57  5023.1  257.26  5060.3  259.32  5418.2  260.69
  5579.5  270.28  5636.6  269.13  5792.6  272.51  6406.2   273.6    6614  271.43
  6762.8  273.07    6858  270.11  6910.9  271.96  6957.3  269.08  7044.3  269.09
#Mann= 10 ,-1 , 0
  3585.3     .16       0  3993.1     .05       0  4229.4     .16       0
  4438.2     .05       0  4657.8     .16       0  4682.8     .05       0
  4775.8     .16       0  4972.1     .07       0  4978.1     .16       0
  5060.3     .05       0
Bank Sta=4960.7,5023.1
XS Rating Curve= 0 ,0
Exp/Cntr=0.3,0.1