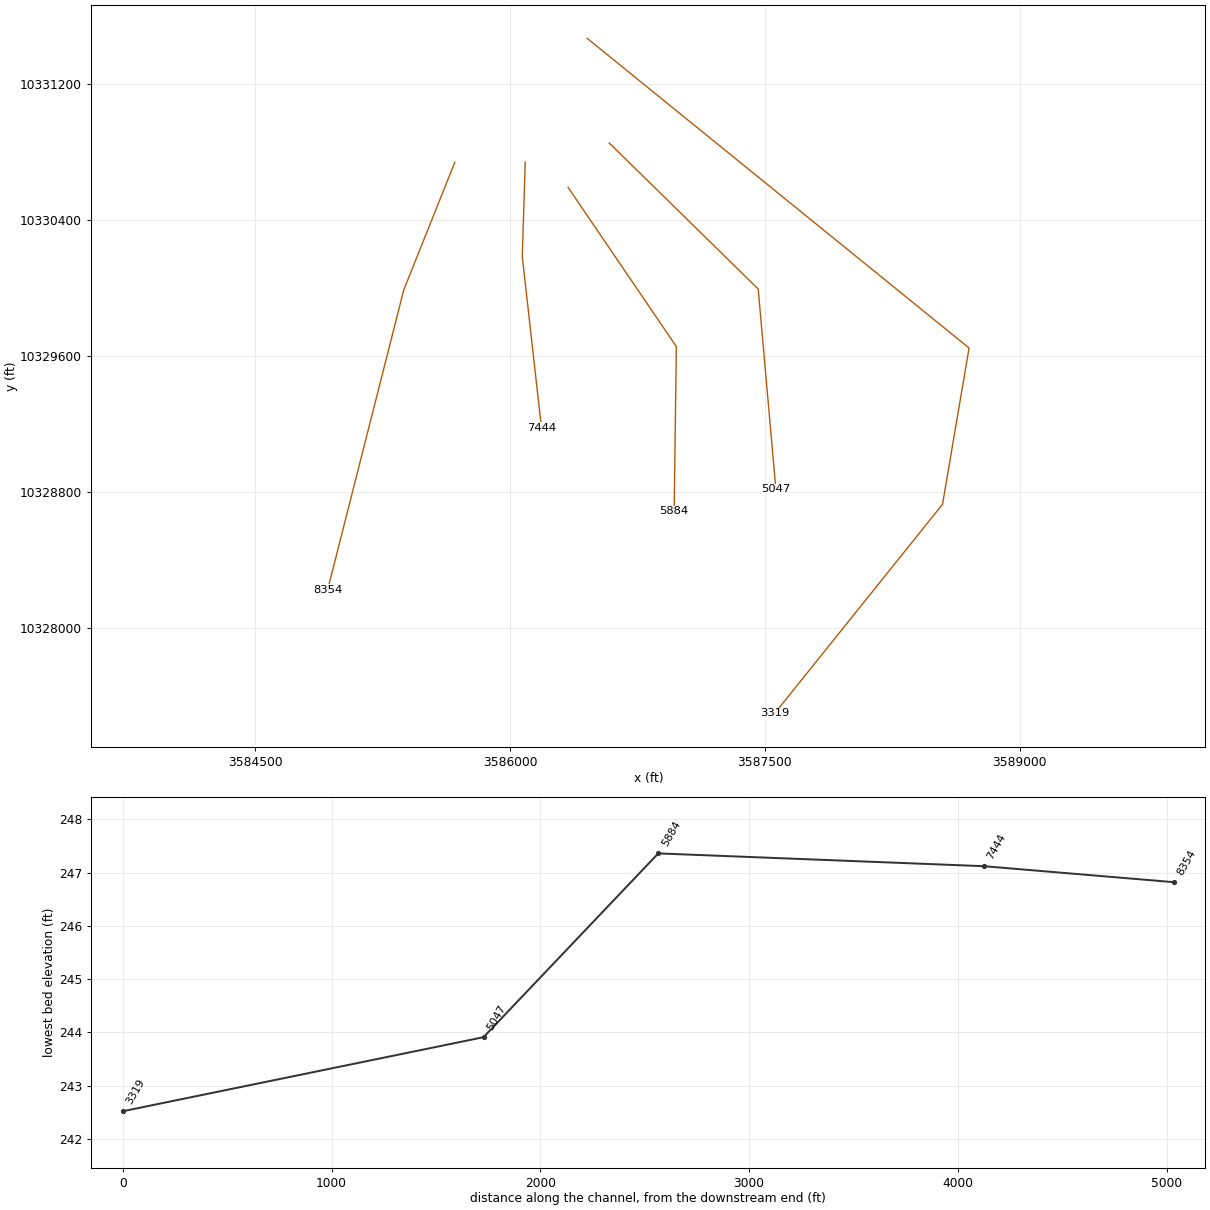
HEC-RAS study LITTLE CEDAR CREEK.prj: LITTLE CEDAR CREEK Base Level Engineering

--- LITTLE CEDAR CREEK.g01 (geometry) --- (continued)

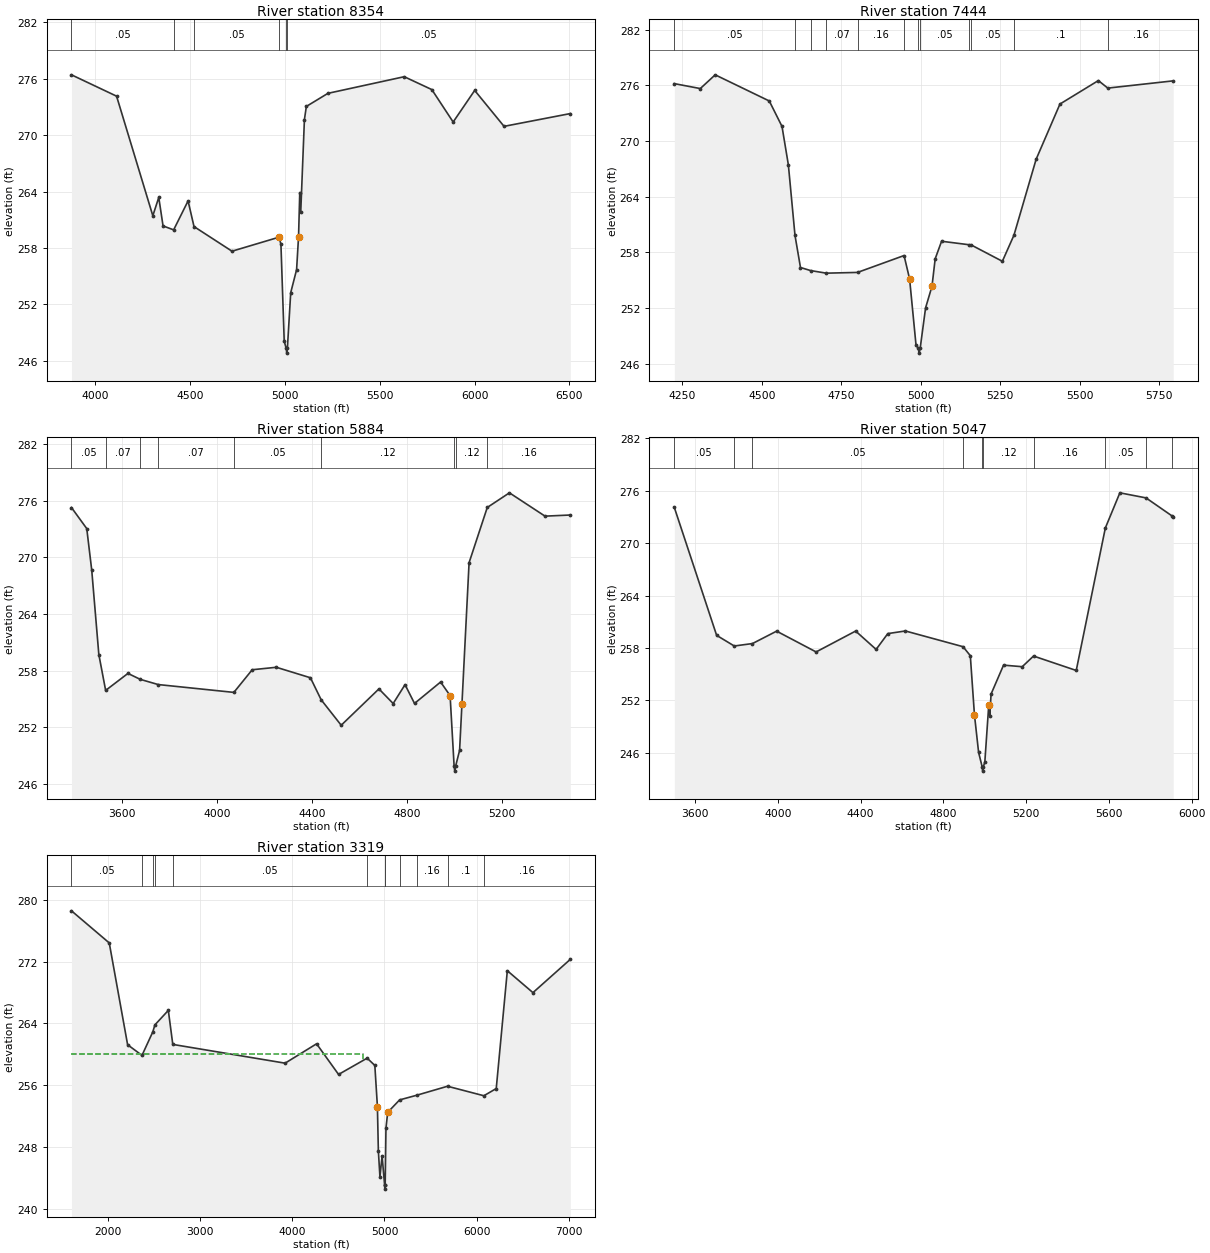
Type RM Length L Ch R = 1 ,8354    ,910,910,910
BEGIN DESCRIPTION:
LITTLE CEDAR CREEK 7.0
END DESCRIPTION:
XS GIS Cut Line= 3
      3585674.75     10330738.87      3585374.74     10329988.86
       3584926.4     10328222.77
#Sta/Elev= 30
  3874.9  276.42  4112.6  274.15  4303.7  261.43    4335  263.38  4357.6  260.35
  4413.4  259.93  4489.5  263.01  4520.8  260.28  4721.1  257.66  4968.7  259.15
  4969.3  259.11    4979  258.41  4996.4  248.07    5007  247.32  5009.7  246.82
    5013  247.32  5030.6  253.25  5061.6   255.7  5071.9  259.22  5078.3   263.9
  5083.4   261.8  5102.8  271.66  5113.1  273.06  5226.6  274.45    5629  276.22
  5774.5  274.85  5886.9   271.4  6000.4  274.76  6155.2  270.94  6504.8   272.3
#Mann= 6 ,-1 , 0
  3874.9     .05       0  4413.4     .16       0  4520.8     .05       0
  4969.3     .16       0    5007     .07       0    5013     .05       0
Bank Sta=4968.7,5071.9
XS Rating Curve= 0 ,0
Exp/Cntr=0.3,0.1

Type RM Length L Ch R = 1 ,7444    ,1560,1560,1560
BEGIN DESCRIPTION:
LITTLE CEDAR CREEK 5.0
END DESCRIPTION:
XS GIS Cut Line= 3
       3586089.6     10330740.19      3586072.23     10330184.59
      3586185.08     10329177.67
#Sta/Elev= 30
  4224.6  276.17  4306.3  275.64  4353.2  277.12  4523.3   274.3  4563.3  271.56
  4583.3  267.42  4604.2   259.8  4621.4  256.35  4653.2  256.02  4702.5  255.74
  4800.9  255.82  4947.2  257.64  4964.6  255.12  4984.7  248.03  4991.8  247.62
  4994.5  247.12  4997.8  247.62  5014.9     252    5035  254.32  5045.1  257.29
  5065.2  259.18  5152.5   258.8  5157.8  258.79  5256.4  257.02  5292.8  259.83
  5362.5  268.01  5437.5  273.97  5558.3   276.5    5588  275.69  5793.7  276.47
#Mann= 12 ,-1 , 0
  4224.6     .05       0  4604.2     .07       0  4653.2     .05       0
  4702.5     .07       0  4800.9     .16       0  4947.2     .05       0
  4991.8    .035       0  4997.8     .05       0  5152.5     .16       0
  5157.8     .05       0  5292.8      .1       0    5588     .16       0
Bank Sta=4964.6,5035
XS Rating Curve= 0 ,0
Exp/Cntr=0.3,0.1

Type RM Length L Ch R = 1 ,5884    ,837,837,837
BEGIN DESCRIPTION:
LITTLE CEDAR CREEK 4.0
END DESCRIPTION:
XS GIS Cut Line= 3
       3586342.1     10330591.65      3586979.17     10329654.78
      3586966.35     10328684.72
#Sta/Elev= 30
  3386.7  275.28  3451.1  273.05  3472.1  268.64    3502  259.71  3530.7  255.91
  3624.7  257.71  3676.8  257.08  3752.3  256.53  4071.2   255.7  4148.6   258.1
  4250.3  258.36    4394  257.25  4439.2  254.92  4523.7  252.22  4682.8  256.07
  4742.8  254.52  4792.8  256.52  4832.8  254.53  4942.8   256.8  4982.8  255.36
  4999.8  247.86  5002.6  247.36  5005.8  247.86  5022.8  249.56  5032.8   254.5
  5062.8  269.44  5139.5  275.29  5232.9  276.84  5382.9  274.37  5489.8  274.49
#Mann= 9 ,-1 , 0
  3386.7     .05       0  3530.7     .07       0  3676.8     .05       0
  3752.3     .07       0  4071.2     .05       0  4439.2     .12       0
  4999.8     .07       0  5005.8     .12       0  5139.5     .16       0
Bank Sta=4982.8,5032.8
XS Rating Curve= 0 ,0
Exp/Cntr=0.3,0.1

Type RM Length L Ch R = 1 ,5047    ,1728,1728,1728
BEGIN DESCRIPTION:
LITTLE CEDAR CREEK 3.0
END DESCRIPTION:
XS GIS Cut Line= 3
      3586584.37     10330853.01      3587461.12     10329993.62
      3587565.13     10328814.89
#Sta/Elev= 30
  3499.8  274.09  3704.3  259.45  3789.5  258.23  3877.5  258.51  3994.2  259.93
    4185  257.55  4376.1  259.94  4475.1  257.84  4531.6  259.65  4616.5  259.95
  4895.2  258.15  4930.3  257.12  4950.3  250.35  4970.4  246.05  4987.5  244.41
  4990.2  243.91  4993.5  244.41  5000.5  244.97  5019.4  251.47  5024.4  250.25
  5030.6  252.73  5090.9  256.04  5181.2  255.86  5235.9  257.08  5442.2  255.43
  5582.9  271.74  5653.1  275.76  5779.4  275.18  5907.3  273.08  5910.8  272.97
#Mann= 10 ,-1 , 0
  3499.8     .05       0  3789.5     .12       0  3877.5     .05       0
  4895.2     .07       0  4987.5     .07       0  4993.5     .12       0
  5235.9     .16       0  5582.9     .05       0  5779.4     .16       0
  5907.3      .1       0
Bank Sta=4950.3,5019.4
XS Rating Curve= 0 ,0
Exp/Cntr=0.3,0.1

Type RM Length L Ch R = 1 ,3319    ,0,0,0
BEGIN DESCRIPTION:
LITTLE CEDAR CREEK 1.0
END DESCRIPTION:
XS GIS Cut Line= 4
      3586454.17     10331469.31      3588702.44     10329646.39
      3588546.19     10328726.26      3587558.09     10327495.46
#Sta/Elev= 30
  1608.3  278.58  2017.6  274.42  2216.5  261.23  2372.3  259.85  2490.1  262.91
    2512   263.8  2657.7  265.68  2706.1  261.27    3923  258.84  4264.1  261.35
  4502.5  257.38  4812.2  259.49  4895.5  258.55  4923.4  253.22  4933.6  247.52
  4950.8  244.12  4974.1  246.83  5001.6  243.02  5004.3  242.52  5007.6  243.02
  5016.1  250.42    5035  252.47  5163.7  254.08    5351  254.69  5683.1  255.85
  6077.1  254.62  6211.1  255.55  6331.2  270.82  6608.9  267.98  7014.4   272.3
#Mann= 12 ,-1 , 0
  1608.3     .05       0  2372.3      .1       0  2490.1     .05       0
    2512      .1       0  2706.1     .05       0  4812.2     .16       0
  5001.6     .07       0  5007.6     .16       0  5163.7     .05       0
    5351     .16       0  5683.1      .1       0  6077.1     .16       0
#XS Ineff= 2 , 0
         4770.45  259.97
Permanent Ineff=
       F       F
Bank Sta=4923.4,5035
XS Rating Curve= 0 ,0
Exp/Cntr=0.3,0.1

Chan Stop Cuts=-1
Use User Specified Reach Order=0
Composite Channel Slope=5