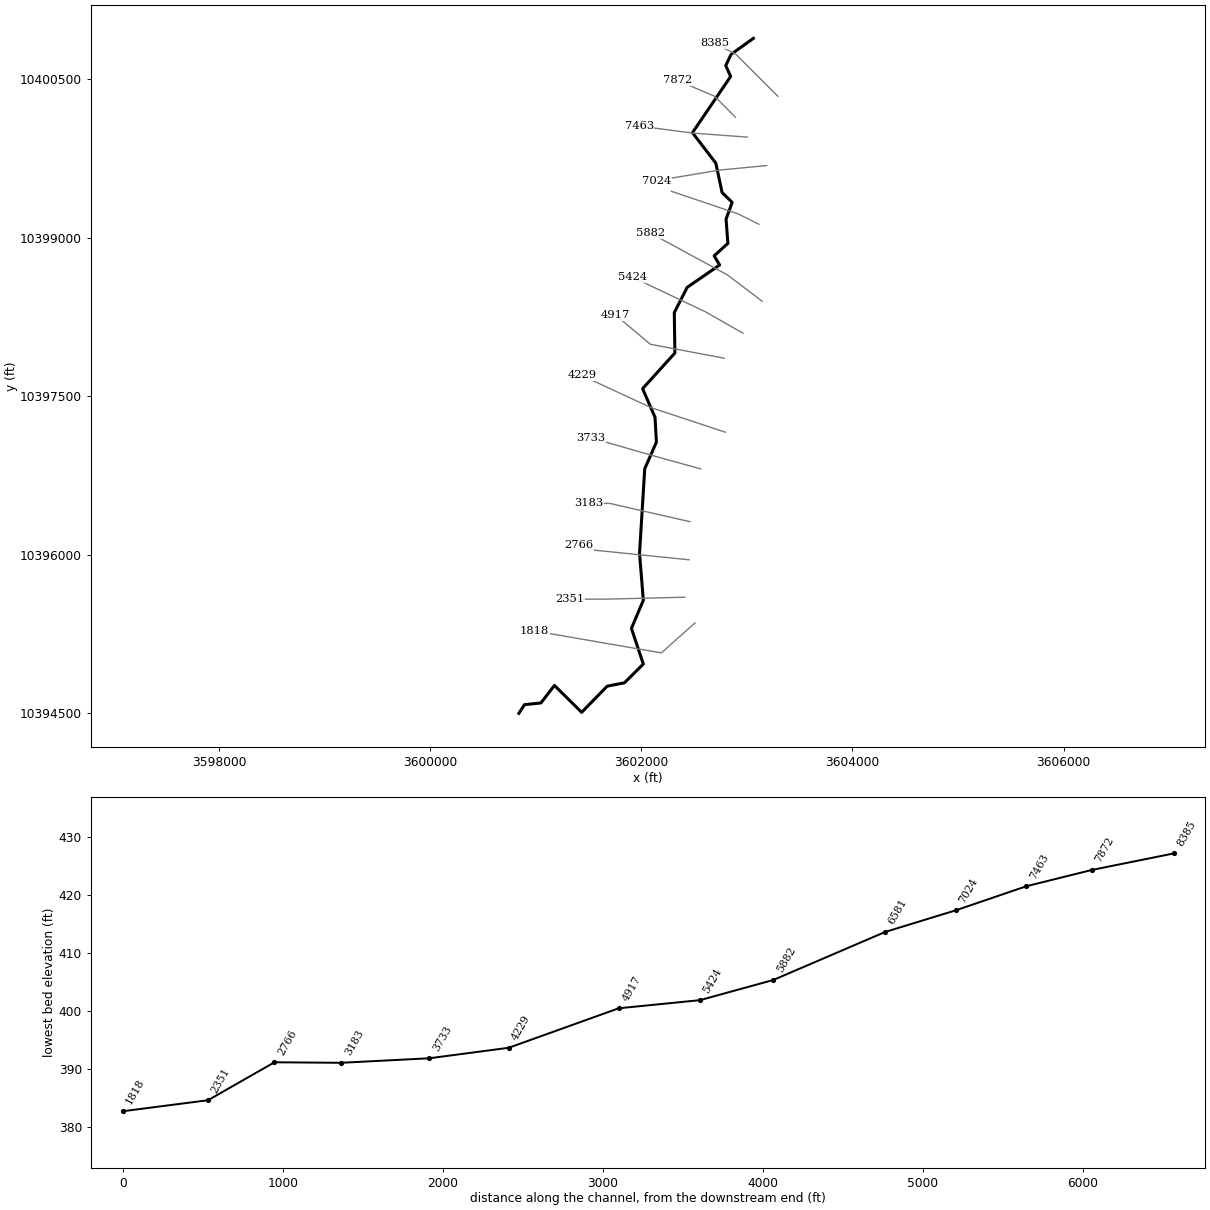
--- LONG GLADE BRANCH.prj (project) ---

Proj Title=LONG GLADE BRANCH Base Level Engineering
Current Plan=p01
Default Exp/Contr=0.3,0.1
English Units
Geom File=g01
Flow File=f01
Plan File=p01
BEGIN DESCRIPTION:
LONG GLADE BRANCH
END DESCRIPTION:

--- LONG GLADE BRANCH.p01 (plan) ---

Plan Title=Multiple Run
Short Identifier=Multiple
Geom File=g01
Flow File=f01
Subcritical Flow
K Sum by GR= 0
Std Step Tol= 0.01
Critical Tol= 0.01
Num of Std Step Trials= 20
Max Error Tol= 0.3
Flow Tol Ratio= 0.001
Split Flow NTrial= 30
Split Flow Tol= 0.02
Split Flow Ratio= 0.02
Log Output Level= 0
Friction Slope Method= 1
Unsteady Friction Slope Method= 2
Unsteady Bridges Friction Slope Method= 1
Parabolic Critical Depth
Global Vel Dist=  1 , 1 , 1
Global Log Level= 0
CheckData=True
Encroach Param= -1, 0, 0, 0
BEGIN DESCRIPTION:
Multiple Run
END DESCRIPTION:

--- LONG GLADE BRANCH.f01 (steady flow) ---

Flow Title=Multiple
Number of Profiles=7
Profile Names=10-year,25-year,50-year,1pct_min,100-year,1pct_plu,500-year
River Rch & RM= LONG GLADE BRANC,Reach-1,8385
    2190    3178    4039    3742    5061    6844    7927
Boundary for River Rch & Prof#=LONG GLADE BRANC,Reach-1,1
Up Type=0
Dn Type=3
Dn Slope=0.005
Boundary for River Rch & Prof#=LONG GLADE BRANC,Reach-1,2
Up Type=0
Dn Type=3
Dn Slope=0.005
Boundary for River Rch & Prof#=LONG GLADE BRANC,Reach-1,3
Up Type=0
Dn Type=3
Dn Slope=0.005
Boundary for River Rch & Prof#=LONG GLADE BRANC,Reach-1,4
Up Type=0
Dn Type=3
Dn Slope=0.005
Boundary for River Rch & Prof#=LONG GLADE BRANC,Reach-1,5
Up Type=0
Dn Type=3
Dn Slope=0.005
Boundary for River Rch & Prof#=LONG GLADE BRANC,Reach-1,6
Up Type=0
Dn Type=3
Dn Slope=0.005
Boundary for River Rch & Prof#=LONG GLADE BRANC,Reach-1,7
Up Type=0
Dn Type=3
Dn Slope=0.005

--- LONG GLADE BRANCH.g01 (geometry) ---

Geom Title=Existing Conditions

River Reach=LONG GLADE BRANC,Reach-1
Reach XY= 30
      3603061.45     10400889.55      3602850.14     10400737.89
      3602799.52     10400631.56      3602845.90     10400528.38
      3602484.28     10399996.26      3602705.35     10399707.67
      3602764.88     10399429.16      3602860.24     10399336.03
      3602802.42     10399176.18      3602819.85     10398947.93
      3602689.77     10398828.96      3602741.90     10398742.71
      3602434.39     10398530.97      3602312.11     10398291.64
      3602317.80     10397908.86      3602012.00     10397571.17
      3602129.59     10397300.52      3602142.59     10397064.21
      3602032.17     10396812.59      3601982.93     10396011.29
      3602019.02     10395567.32      3601906.06     10395300.94
      3602018.69     10394963.02      3601840.11     10394785.06
      3601676.56     10394753.29      3601434.89     10394505.59
      3601176.81     10394760.55      3601049.03     10394594.74
      3600893.31     10394578.29      3600839.68     10394495.74

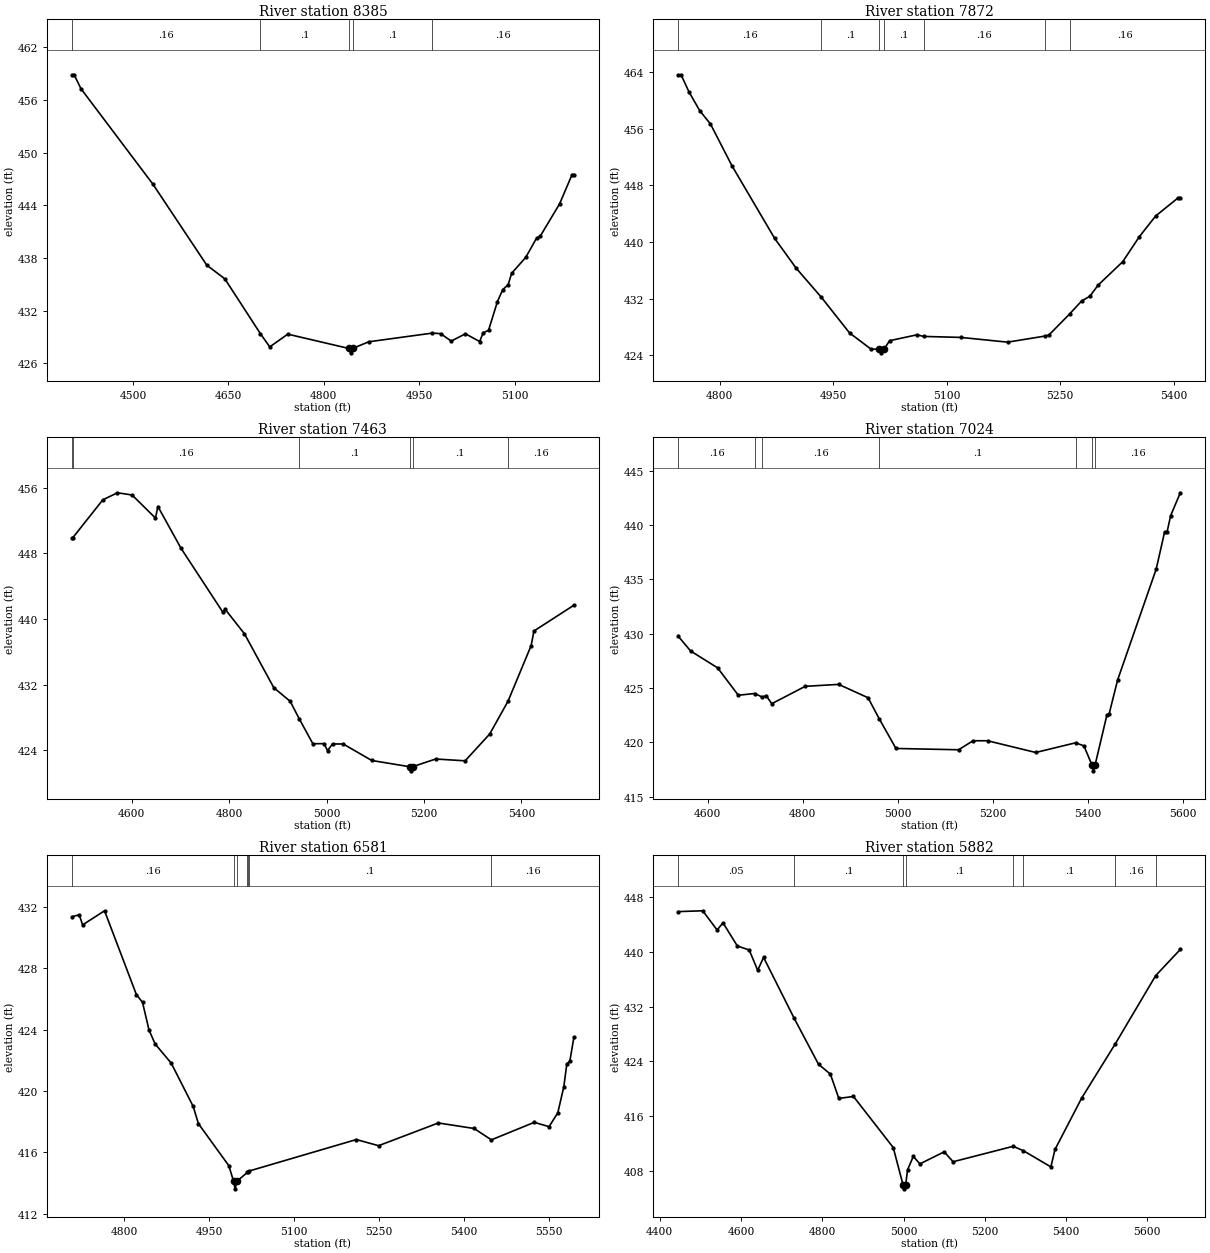
Type RM Length L Ch R = 1,8385,513,513,513
BEGIN DESCRIPTION:
LONG GLADE BRANCH 16.0
END DESCRIPTION:
XS GIS Cut Line= 3
      3603292.11     10400341.64      3602892.11     10400741.64
      3602692.10     10400841.64
#Sta/Elev= 30
  4404.0  458.89  4407.5  458.89  4418.1  457.31  4531.3  446.42  4616.1  437.18
  4644.4  435.63  4700.5  429.36  4715.1  427.87  4743.4  429.32  4839.4  427.69
  4842.2  427.19  4845.4  427.69  4870.7  428.45  4970.6  429.44  4983.7  429.38
  5000.4  428.53  5022.8  429.36  5045.2  428.48  5050.7  429.48  5059.1  429.75
  5073.1  433.03  5081.5  434.40  5089.9  434.95  5095.5  436.26  5117.8  438.09
  5134.6  440.26  5140.2  440.46  5170.9  444.18  5190.5  447.51  5193.3  447.51
#Mann=5,-1,0
  4404.0    0.16       0  4700.5     0.1       0  4839.4    0.07       0
  4845.4     0.1       0  4970.6    0.16       0
Bank Sta=4839.4,4845.4
Exp/Cntr=0.3,0.1

Type RM Length L Ch R = 1,7872,409,409,409
BEGIN DESCRIPTION:
LONG GLADE BRANCH 15.0
END DESCRIPTION:
XS GIS Cut Line= 3
      3602892.11     10400141.64      3602692.11     10400341.64
      3602342.14     10400491.63
#Sta/Elev= 30
  4745.4  463.64  4748.9  463.64  4759.6  461.17  4773.7  458.55  4787.8  456.68
  4816.1  450.79  4872.7  440.50  4901.0  436.31  4934.5  432.17  4971.7  427.14
  5000.0  424.86  5011.1  424.83  5013.9  424.33  5017.1  424.83  5024.7  426.05
  5060.9  426.88  5069.7  426.65  5118.9  426.51  5180.6  425.84  5229.5  426.69
  5235.0  426.82  5262.6  429.82  5278.5  431.66  5289.4  432.33  5300.2  433.89
  5332.9  437.22  5354.6  440.72  5376.4  443.68  5406.3  446.26  5409.0  446.26
#Mann=7,-1,0
  4745.4    0.16       0  4934.5     0.1       0  5011.1    0.07       0
  5017.1     0.1       0  5069.7    0.16       0  5229.5    0.05       0
  5262.6    0.16       0
Bank Sta=5011.1,5017.1
Exp/Cntr=0.3,0.1

Type RM Length L Ch R = 1,7463,439,439,439
BEGIN DESCRIPTION:
LONG GLADE BRANCH 14.0
END DESCRIPTION:
XS GIS Cut Line= 3
      3603005.21     10399953.85      3602492.11     10399991.64
      3601980.89     10400058.02
#Sta/Elev= 30
  4477.6  449.85  4478.8  449.85  4540.9  454.50  4571.0  455.36  4601.0  455.09
  4649.0  452.28  4654.0  453.69  4701.3  448.62  4787.2  440.83  4792.2  441.17
  4831.7  438.19  4891.8  431.64  4925.5  429.98  4944.3  427.82  4972.0  424.82
  4994.6  424.83  5002.2  423.99  5012.3  424.79  5034.2  424.79  5092.9  422.78
  5170.6  422.02  5173.4  421.52  5176.6  422.02  5224.0  422.96  5284.5  422.74
  5334.9  426.00  5372.4  429.98  5420.0  436.77  5425.7  438.54  5507.6  441.67
#Mann=6,-1,0
  4477.6     0.1       0  4478.8    0.16       0  4944.3     0.1       0
  5170.6    0.07       0  5176.6     0.1       0  5372.4    0.16       0
Bank Sta=5170.6,5176.6
Exp/Cntr=0.3,0.1

Type RM Length L Ch R = 1,7024,443,443,443
BEGIN DESCRIPTION:
LONG GLADE BRANCH 13.0
END DESCRIPTION:
XS GIS Cut Line= 3
      3603187.52     10399684.75      3602742.11     10399641.64
      3602142.08     10399541.64
#Sta/Elev= 30
  4538.6  429.75  4564.1  428.42  4621.1  426.86  4664.6  424.34  4698.9  424.50
  4715.0  424.17  4723.2  424.31  4734.9  423.56  4805.3  425.16  4875.6  425.34
  4937.5  424.11  4960.8  422.19  4996.2  419.44  5128.0  419.32  5158.4  420.15
  5188.9  420.15  5290.2  419.07  5374.0  419.96  5391.6  419.68  5408.9  417.88
  5411.6  417.38  5414.9  417.88  5439.8  422.49  5444.8  422.65  5462.6  425.76
  5543.7  435.96  5561.4  439.38  5566.5  439.37  5574.1  440.88  5594.4  442.98
#Mann=7,-1,0
  4538.6    0.16       0  4698.9     0.1       0  4715.0    0.16       0
  4960.8     0.1       0  5374.0    0.16       0  5408.9    0.07       0
  5414.9    0.16       0
Bank Sta=5408.9,5414.9
Exp/Cntr=0.3,0.1

Type RM Length L Ch R = 1,6581,699,699,699
BEGIN DESCRIPTION:
LONG GLADE BRANCH 12.0
END DESCRIPTION:
XS GIS Cut Line= 3
      3603113.66     10399128.07      3602913.70     10399228.05
      3602285.22     10399440.57
#Sta/Elev= 30
  4707.7  431.35  4720.6  431.48  4726.5  430.82  4765.3  431.74  4821.6  426.28
  4832.4  425.78  4843.9  423.97  4854.8  423.06  4883.1  421.82  4921.9  419.00
  4931.3  417.87  4984.9  415.14  4993.3  414.13  4996.0  413.63  4999.3  414.13
  5017.8  414.70  5018.1  414.71  5019.9  414.78  5210.3  416.84  5249.6  416.44
  5355.2  417.92  5418.5  417.56  5448.9  416.82  5524.7  417.96  5550.9  417.68
  5566.3  418.58  5576.9  420.27  5582.3  421.77  5587.6  421.94  5594.7  423.49
#Mann=7,-1,0
  4707.7    0.16       0  4993.3    0.07       0  4999.3    0.16       0
  5017.8    0.05       0  5018.1    0.16       0  5019.9     0.1       0
  5448.9    0.16       0
Bank Sta=4993.3,4999.3
Exp/Cntr=0.3,0.1

Type RM Length L Ch R = 1,5882,458,458,458
BEGIN DESCRIPTION:
LONG GLADE BRANCH 11.0
END DESCRIPTION:
XS GIS Cut Line= 3
      3603144.10     10398400.05      3602814.14     10398649.54
      3602092.10     10399041.64
#Sta/Elev= 30
  4446.0  445.88  4505.8  446.00  4541.2  443.19  4555.7  444.24  4591.1  440.85
  4620.2  440.27  4641.1  437.30  4655.6  439.18  4730.8  430.29  4790.9  423.55
  4820.0  422.12  4840.8  418.56  4876.8  418.85  4974.7  411.38  4999.2  405.84
  5002.0  405.34  5005.2  405.84  5009.9  408.11  5024.1  410.08  5040.3  408.99
  5100.2  410.75  5122.0  409.30  5270.0  411.56  5294.9  410.92  5362.7  408.55
  5372.9  411.10  5438.5  418.61  5521.4  426.56  5620.7  436.52  5681.3  440.35
#Mann=8,-1,0
  4446.0    0.05       0  4730.8     0.1       0  4999.2    0.07       0
  5005.2     0.1       0  5270.0    0.16       0  5294.9     0.1       0
  5521.4    0.16       0  5620.7     0.1       0
Bank Sta=4999.2,5005.2
Exp/Cntr=0.3,0.1

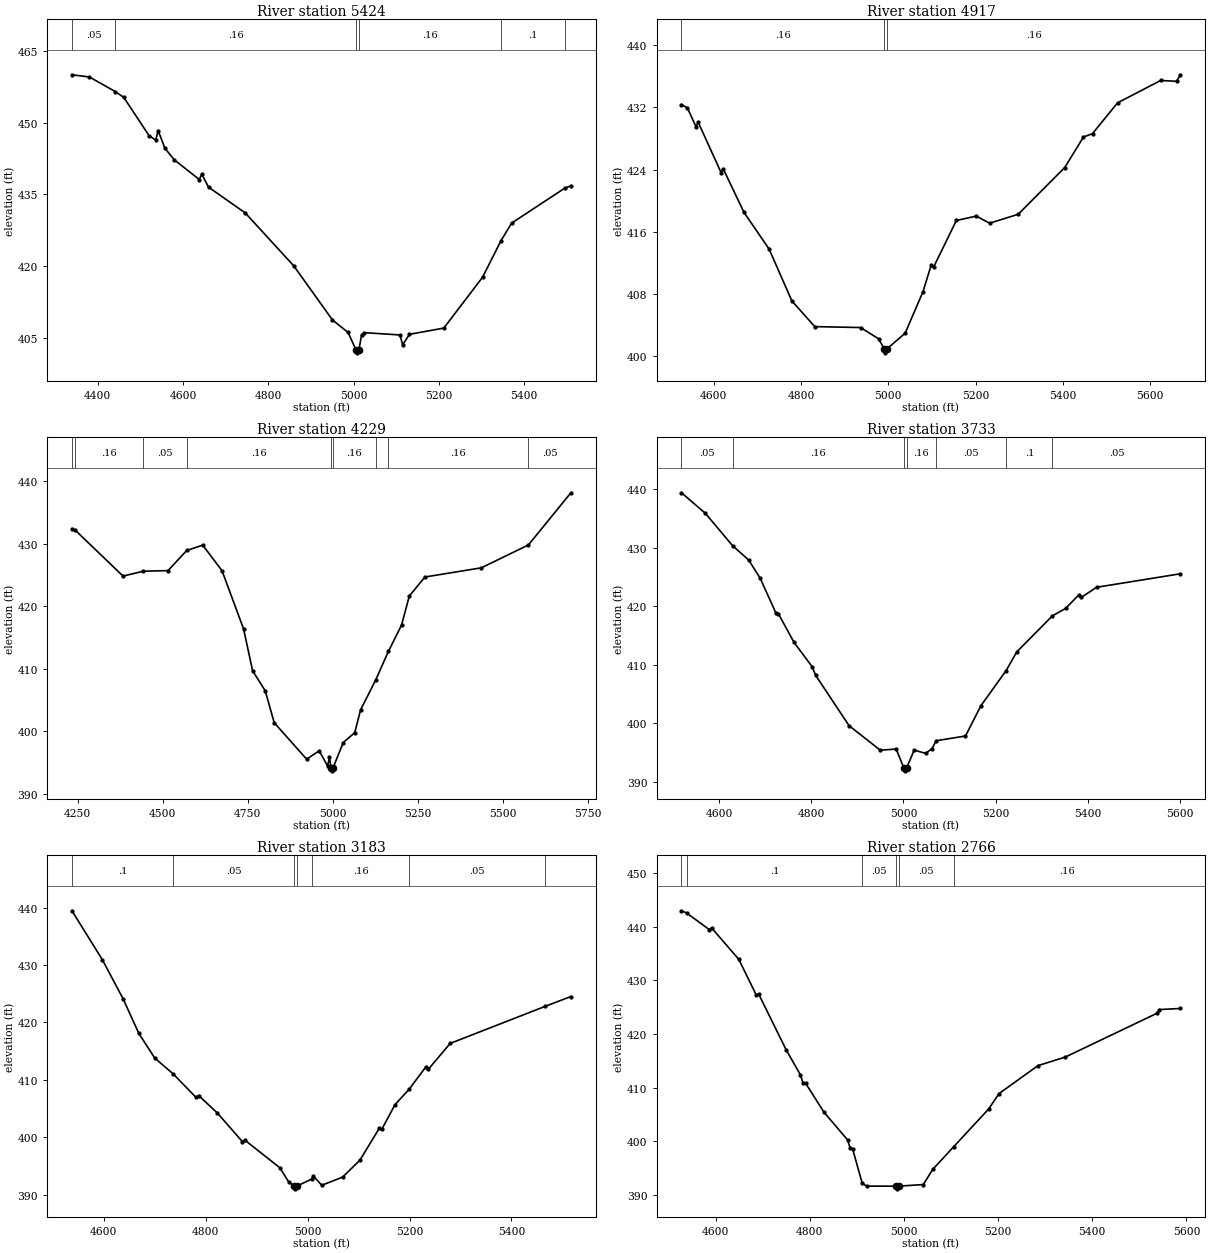
Type RM Length L Ch R = 1,5424,507,507,507
BEGIN DESCRIPTION:
LONG GLADE BRANCH 10.0
END DESCRIPTION:
XS GIS Cut Line= 3
      3602962.99     10398096.46      3602613.00     10398296.45
      3601920.16     10398625.72
#Sta/Elev= 30
  4339.4  460.03  4380.4  459.57  4441.0  456.52  4461.0  455.30  4520.1  447.32
  4535.9  446.36  4541.6  448.34  4557.5  444.66  4579.1  442.26  4638.1  438.12
  4643.9  439.23  4659.7  436.53  4746.0  431.12  4859.6  420.06  4950.5  408.73
  4987.1  406.12  5006.2  402.36  5009.0  401.86  5012.2  402.36  5018.6  405.57
  5024.2  406.09  5108.9  405.60  5115.0  403.53  5131.0  405.74  5211.5  407.03
  5302.3  417.66  5345.6  425.31  5370.5  428.99  5495.7  436.34  5509.6  436.79
#Mann=6,-1,0
  4339.4    0.05       0  4441.0    0.16       0  5006.2    0.07       0
  5012.2    0.16       0  5345.6     0.1       0  5495.7    0.16       0
Bank Sta=5006.2,5012.2
Exp/Cntr=0.3,0.1

Type RM Length L Ch R = 1,4917,688,688,688
BEGIN DESCRIPTION:
LONG GLADE BRANCH 9.0
END DESCRIPTION:
XS GIS Cut Line= 3
      3602785.52     10397859.70      3602085.10     10397992.04
      3601756.20     10398269.01
#Sta/Elev= 30
  4526.3  432.37  4539.9  431.93  4559.5  429.51  4564.6  430.08  4616.9  423.63
  4622.0  424.09  4669.3  418.52  4726.8  413.81  4779.1  407.13  4831.5  403.83
  4936.3  403.71  4977.6  402.27  4990.7  400.96  4993.5  400.46  4996.7  400.96
  5038.6  402.99  5079.3  408.31  5098.5  411.80  5103.5  411.45  5155.9  417.47
  5201.5  418.03  5232.0  417.12  5297.3  418.26  5404.0  424.27  5446.9  428.19
  5467.7  428.63  5524.9  432.58  5623.8  435.46  5660.1  435.35  5669.1  436.19
#Mann=3,-1,0
  4526.3    0.16       0  4990.7    0.07       0  4996.7    0.16       0
Bank Sta=4990.7,4996.7
Exp/Cntr=0.3,0.1

Type RM Length L Ch R = 1,4229,496,496,496
BEGIN DESCRIPTION:
LONG GLADE BRANCH 7.0
END DESCRIPTION:
XS GIS Cut Line= 3
      3602796.91     10397158.70      3602092.11     10397391.64
      3601435.88     10397696.06
#Sta/Elev= 30
  4233.2  432.37  4241.5  432.23  4383.2  424.81  4443.3  425.59  4515.4  425.68
  4570.4  428.91  4617.4  429.76  4674.1  425.67  4737.5  416.34  4764.0  409.64
  4801.0  406.46  4827.4  401.34  4922.6  395.51  4959.6  396.84  4984.2  394.41
  4989.7  395.79  4994.5  394.14  4997.3  393.64  5000.5  394.14  5030.0  398.16
  5063.9  399.75  5081.3  403.42  5125.6  408.19  5162.8  412.75  5201.4  416.96
  5224.3  421.62  5270.1  424.66  5435.9  426.13  5574.1  429.79  5698.9  438.14
#Mann=9,-1,0
  4233.2    0.05       0  4241.5    0.16       0  4443.3    0.05       0
  4570.4    0.16       0  4994.5    0.07       0  5000.5    0.16       0
  5125.6    0.05       0  5162.8    0.16       0  5574.1    0.05       0
Bank Sta=4994.5,5000.5
Exp/Cntr=0.3,0.1

Type RM Length L Ch R = 1,3733,550,550,550
BEGIN DESCRIPTION:
LONG GLADE BRANCH 6.0
END DESCRIPTION:
XS GIS Cut Line= 3
      3602562.50     10396811.49      3602092.11     10396941.64
      3601520.82     10397106.63
#Sta/Elev= 30
  4518.3  439.42  4570.3  435.89  4629.0  430.37  4664.0  427.92  4688.8  424.83
  4723.1  418.85  4728.3  418.75  4762.6  413.80  4802.1  409.62  4809.2  408.20
  4881.9  399.56  4949.7  395.36  4984.0  395.56  5000.8  392.33  5003.5  391.83
  5006.8  392.33  5023.2  395.38  5048.0  394.82  5062.0  395.64  5070.7  396.98
  5134.5  397.79  5168.1  402.99  5222.8  409.00  5245.8  412.19  5323.3  418.37
  5351.9  419.63  5380.3  421.94  5385.5  421.50  5419.2  423.25  5601.0  425.56
#Mann=7,-1,0
  4518.3    0.05       0  4629.0    0.16       0  5000.8    0.07       0
  5006.8    0.16       0  5070.7    0.05       0  5222.8     0.1       0
  5323.3    0.05       0
Bank Sta=5000.8,5006.8
Exp/Cntr=0.3,0.1

Type RM Length L Ch R = 1,3183,417,417,417
BEGIN DESCRIPTION:
LONG GLADE BRANCH 5.0
END DESCRIPTION:
XS GIS Cut Line= 3
      3602460.08     10396311.49      3601700.44     10396484.70
      3601500.47     10396484.70
#Sta/Elev= 30
  4537.5  439.43  4597.0  430.95  4638.0  424.10  4668.8  418.09  4700.1  413.79
  4735.8  411.08  4781.0  406.96  4786.2  407.28  4822.6  404.27  4872.2  399.24
  4877.3  399.49  4945.7  394.70  4963.3  392.18  4973.5  391.55  4976.2  391.05
  4979.5  391.55  5008.2  392.76  5011.4  393.27  5027.7  391.67  5068.8  393.10
  5102.6  396.04  5140.4  401.55  5145.6  401.42  5171.3  405.68  5199.2  408.38
  5231.6  412.22  5236.7  411.83  5279.7  416.35  5466.1  422.80  5516.6  424.51
#Mann=7,-1,0
  4537.5     0.1       0  4735.8    0.05       0  4973.5    0.03       0
  4979.5    0.05       0  5008.2    0.16       0  5199.2    0.05       0
  5466.1     0.1       0
Bank Sta=4973.5,4979.5
Exp/Cntr=0.3,0.1

Type RM Length L Ch R = 1,2766,415,415,415
BEGIN DESCRIPTION:
LONG GLADE BRANCH 4.0
END DESCRIPTION:
XS GIS Cut Line= 3
      3602453.11     10395950.38      3601554.61     10396041.64
      3601405.88     10396091.22
#Sta/Elev= 30
  4527.4  442.97  4538.1  442.57  4586.5  439.46  4591.6  439.75  4649.0  433.93
  4686.3  427.26  4691.3  427.45  4749.5  417.09  4779.7  412.44  4786.0  410.78
  4791.0  410.83  4830.0  405.43  4880.2  400.26  4885.8  398.70  4890.8  398.61
  4911.2  392.20  4920.4  391.65  4982.5  391.64  4985.2  391.14  4988.5  391.64
  5041.0  391.94  5061.1  394.77  5105.9  399.02  5179.9  406.03  5201.9  408.90
  5284.7  414.11  5342.6  415.70  5537.3  423.86  5542.5  424.56  5587.3  424.76
#Mann=6,-1,0
  4527.4    0.05       0  4538.1     0.1       0  4911.2    0.05       0
  4982.5    0.03       0  4988.5    0.05       0  5105.9    0.16       0
Bank Sta=4982.5,4988.5
Exp/Cntr=0.3,0.1

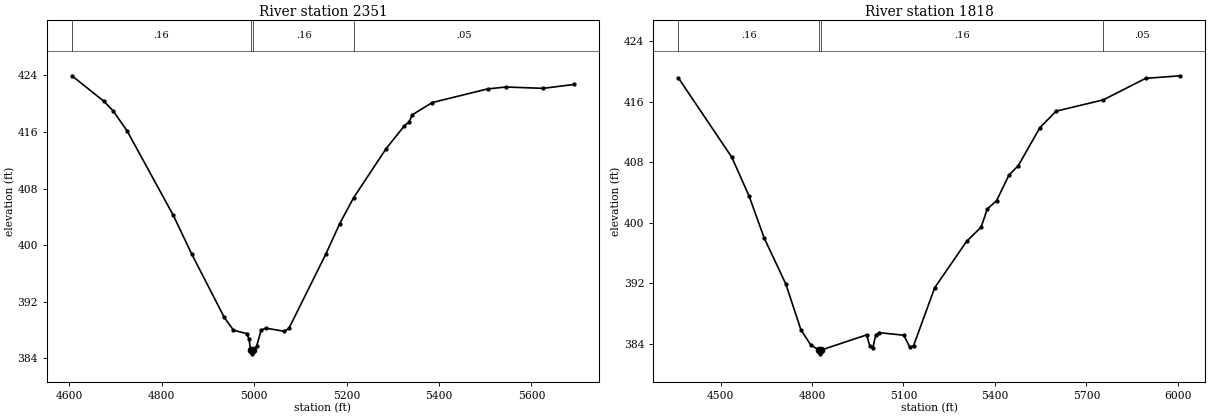
Type RM Length L Ch R = 1,2351,533,533,533
BEGIN DESCRIPTION:
LONG GLADE BRANCH 3.0
END DESCRIPTION:
XS GIS Cut Line= 3
      3602411.46     10395596.20      3601674.05     10395577.75
      3601325.59     10395577.75
#Sta/Elev= 30
  4605.8  423.96  4675.2  420.34  4695.2  418.97  4725.2  416.15  4825.2  404.19
  4865.2  398.69  4935.3  389.76  4955.3  387.94  4984.2  387.45  4989.2  386.66
  4992.3  385.09  4995.0  384.59  4998.3  385.09  5005.3  385.65  5015.3  387.95
  5025.3  388.23  5065.3  387.78  5075.3  388.20  5155.3  398.73  5185.3  403.03
  5215.2  406.68  5285.4  413.62  5325.4  416.90  5335.4  417.41  5341.9  418.42
  5385.4  420.17  5505.4  422.10  5545.4  422.37  5625.4  422.18  5691.9  422.73
#Mann=4,-1,0
  4605.8    0.16       0  4992.3    0.07       0  4998.3    0.16       0
  5215.2    0.05       0
Bank Sta=4992.3,4998.3
Exp/Cntr=0.3,0.1

Type RM Length L Ch R = 1,1818,0,0,0
BEGIN DESCRIPTION:
LONG GLADE BRANCH 1.0
END DESCRIPTION:
XS GIS Cut Line= 3
      3602508.64     10395352.56      3602189.26     10395068.43
      3600988.26     10395276.69
#Sta/Elev= 30
  4361.7  419.11  4536.9  408.64  4593.8  403.49  4643.1  397.98  4714.2  391.89
  4763.5  385.87  4796.4  383.82  4823.9  383.19  4826.6  382.69  4829.9  383.19
  4979.1  385.19  4989.3  383.75  4999.4  383.48  5008.7  385.13  5019.7  385.49
  5100.9  385.15  5121.2  383.53  5133.2  383.78  5202.4  391.42  5307.2  397.55
  5354.6  399.41  5374.9  401.82  5405.4  402.91  5446.0  406.30  5476.2  407.51
  5547.5  412.55  5600.7  414.73  5755.5  416.22  5894.2  419.06  6008.1  419.40
#Mann=4,-1,0
  4361.7    0.16       0  4823.9    0.07       0  4829.9    0.16       0
  5755.5    0.05       0
Bank Sta=4823.9,4829.9
Exp/Cntr=0.3,0.1

Chan Stop Cuts=-1