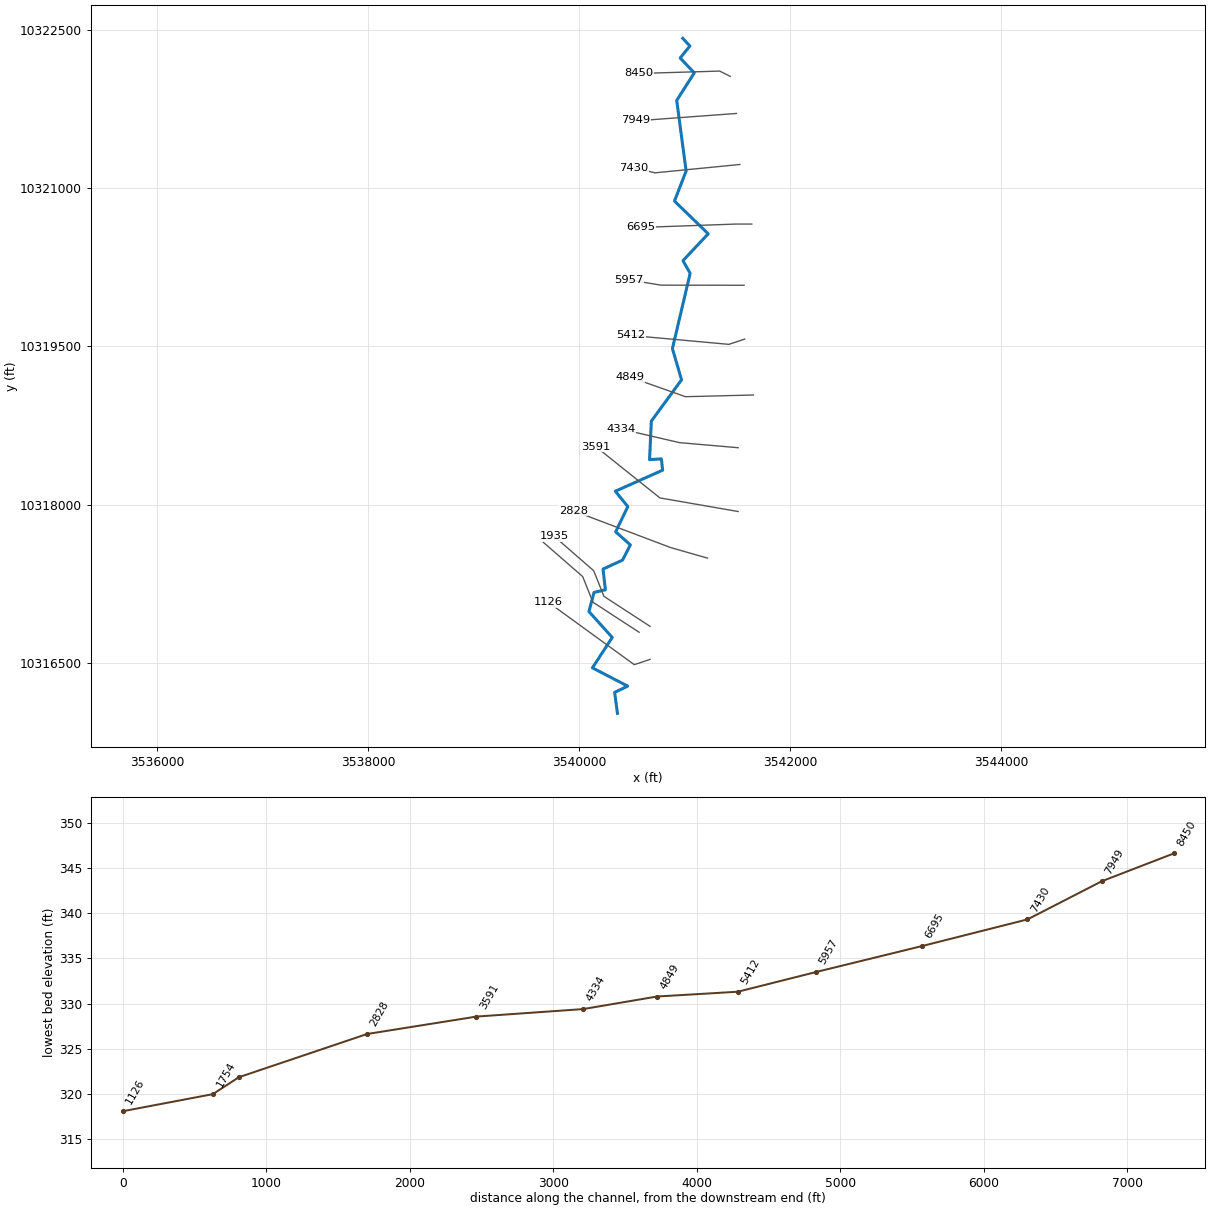
--- MELTON BRANCH.prj (project) ---

Proj Title=MELTON BRANCH Base Level Engineering
Current Plan=p01
Default Exp/Contr=0.3,0.1
English Units
Geom File=g01
Flow File=f01
Plan File=p01
BEGIN DESCRIPTION:
MELTON BRANCH
END DESCRIPTION:

--- MELTON BRANCH.p01 (plan) ---

Plan Title=Multiple Run
Short Identifier=Multiple
Geom File=g01
Flow File=f01
Subcritical Flow
K Sum by GR= 0
Std Step Tol= 0.01
Critical Tol= 0.01
Num of Std Step Trials= 20
Max Error Tol= 0.3
Flow Tol Ratio= 0.001
Split Flow NTrial= 30
Split Flow Tol= 0.02
Split Flow Ratio= 0.02
Log Output Level= 0
Friction Slope Method= 1
Unsteady Friction Slope Method= 2
Unsteady Bridges Friction Slope Method= 1
Parabolic Critical Depth
Global Vel Dist=  1 , 1 , 1
Global Log Level= 0
CheckData=True
Encroach Param= -1, 0, 0, 0
BEGIN DESCRIPTION:
Multiple Run
END DESCRIPTION:

--- MELTON BRANCH.f01 (steady flow) ---

Flow Title=Multiple
Number of Profiles=7
Profile Names=10-year,25-year,50-year,1pct_min,100-year,1pct_plu,500-year
River Rch & RM= MELTON BRANCH,Reach-1,8450
     784    1080    1327    1193    1613    2182    2393
Boundary for River Rch & Prof#=MELTON BRANCH,Reach-1,1
Up Type=0
Dn Type=3
Dn Slope=0.005
Boundary for River Rch & Prof#=MELTON BRANCH,Reach-1,2
Up Type=0
Dn Type=3
Dn Slope=0.005
Boundary for River Rch & Prof#=MELTON BRANCH,Reach-1,3
Up Type=0
Dn Type=3
Dn Slope=0.005
Boundary for River Rch & Prof#=MELTON BRANCH,Reach-1,4
Up Type=0
Dn Type=3
Dn Slope=0.005
Boundary for River Rch & Prof#=MELTON BRANCH,Reach-1,5
Up Type=0
Dn Type=3
Dn Slope=0.005
Boundary for River Rch & Prof#=MELTON BRANCH,Reach-1,6
Up Type=0
Dn Type=3
Dn Slope=0.005
Boundary for River Rch & Prof#=MELTON BRANCH,Reach-1,7
Up Type=0
Dn Type=3
Dn Slope=0.005

--- MELTON BRANCH.g01 (geometry) ---

Geom Title=Existing Conditions

River Reach=MELTON BRANCH,Reach-1
Reach XY= 30
      3540981.22     10322419.38      3541048.43     10322346.93
      3540956.74     10322232.65      3541090.16     10322091.96
      3540923.67     10321831.26      3541012.77     10321161.60
      3540902.50     10320877.03      3541222.21     10320566.94
      3540982.86     10320312.24      3541050.97     10320192.12
      3540883.06     10319478.72      3540969.34     10319182.90
      3540683.03     10318791.29      3540666.36     10318426.52
      3540778.12     10318433.85      3540790.30     10318326.75
      3540341.83     10318127.02      3540460.22     10317981.61
      3540345.04     10317742.66      3540484.51     10317618.40
      3540410.38     10317474.57      3540225.26     10317389.26
      3540247.74     10317192.99      3540139.86     10317167.58
      3540091.64     10316986.71      3540312.56     10316741.50
      3540124.99     10316453.20      3540458.90     10316279.94
      3540335.34     10316220.48      3540362.11     10316021.64

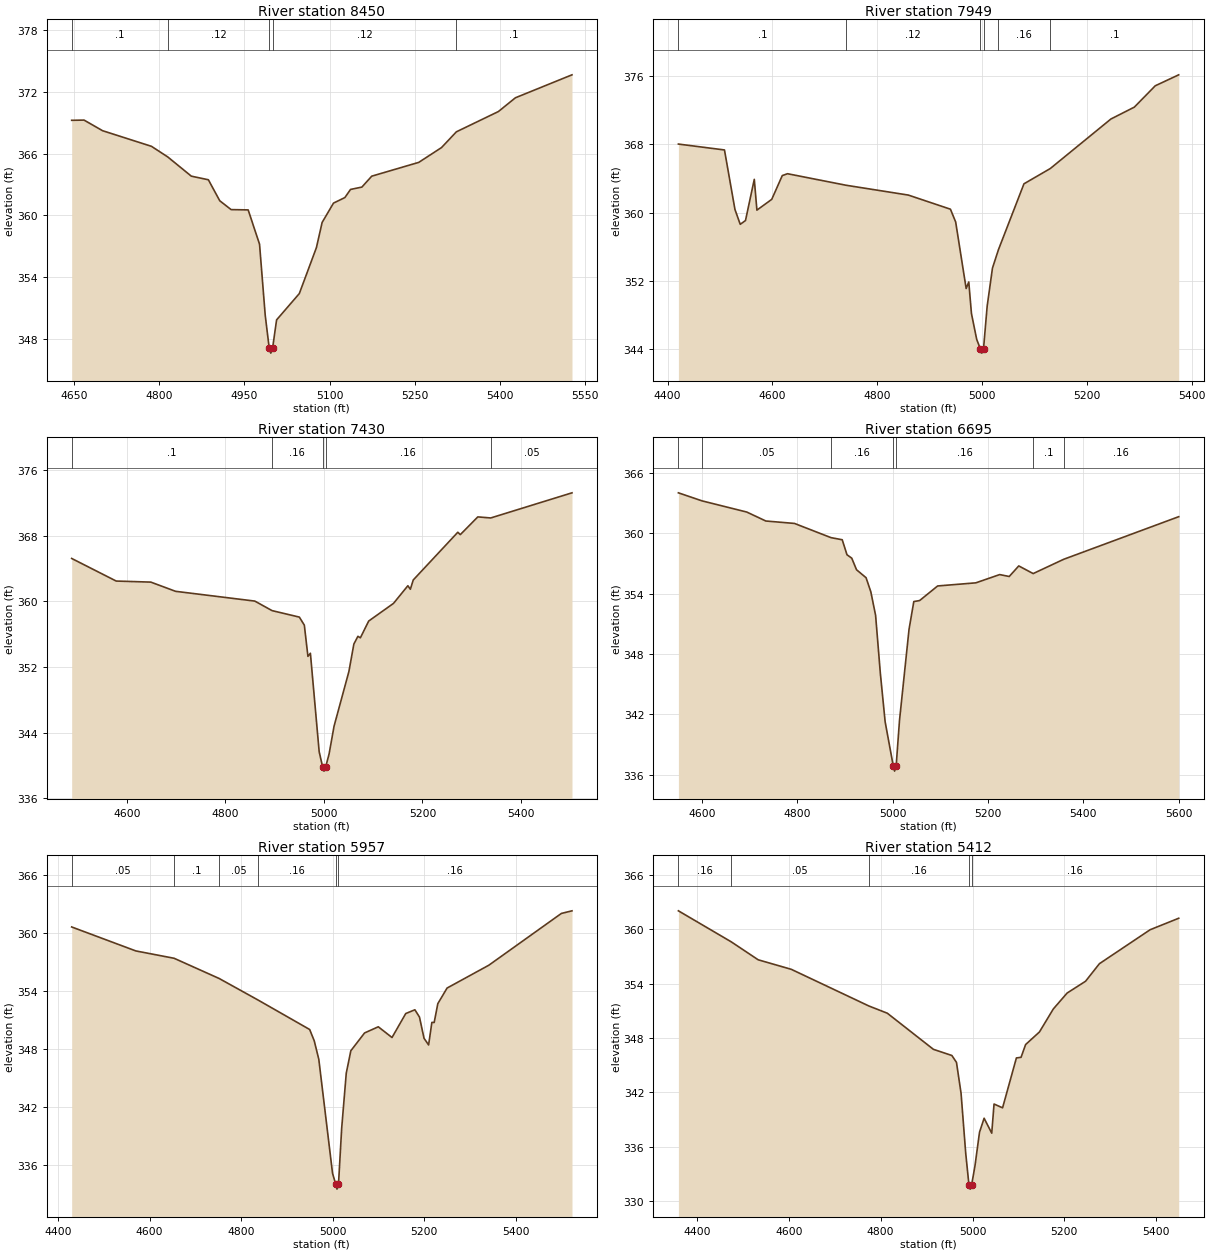
Type RM Length L Ch R = 1,8450,501,501,501
BEGIN DESCRIPTION:
MELTON BRANCH 14.0
END DESCRIPTION:
XS GIS Cut Line= 3
      3541430.72     10322058.98      3541330.68     10322109.00
      3540562.66     10322086.30
#Sta/Elev= 30
  4646.2  369.25  4668.0  369.27  4700.5  368.24  4786.6  366.72  4815.2  365.69
  4856.7  363.82  4886.7  363.47  4906.7  361.43  4926.7  360.57  4956.7  360.54
  4976.7  357.21  4986.7  350.30  4993.7  347.12  4996.5  346.62  4999.7  347.12
  5006.7  349.85  5046.7  352.41  5076.8  356.88  5086.8  359.32  5106.8  361.20
  5126.8  361.74  5136.8  362.53  5156.8  362.76  5174.1  363.82  5256.8  365.16
  5296.9  366.60  5323.0  368.13  5396.9  370.10  5426.9  371.44  5526.4  373.67
#Mann=5,-1,0
  4646.2     0.1       0  4815.2    0.12       0  4993.7    0.07       0
  4999.7    0.12       0  5323.0     0.1       0
Bank Sta=4993.7,4999.7
Exp/Cntr=0.3,0.1

Type RM Length L Ch R = 1,7949,519,519,519
BEGIN DESCRIPTION:
MELTON BRANCH 13.0
END DESCRIPTION:
XS GIS Cut Line= 3
      3541489.75     10321707.43      3540637.41     10321644.51
      3540537.37     10321644.51
#Sta/Elev= 30
  4420.7  368.01  4508.6  367.32  4528.6  360.36  4538.7  358.62  4548.7  359.06
  4565.5  363.88  4570.5  360.28  4598.8  361.54  4618.9  364.32  4628.9  364.54
  4740.7  363.19  4859.5  362.04  4939.8  360.39  4949.8  358.89  4969.8  351.11
  4974.8  351.87  4979.9  348.18  4989.9  345.16  4996.9  344.05  4999.7  343.55
  5002.9  344.05  5009.9  349.05  5020.0  353.50  5031.4  355.65  5080.1  363.36
  5130.2  365.14  5246.0  370.94  5290.7  372.33  5330.7  374.83  5375.4  376.11
#Mann=6,-1,0
  4420.7     0.1       0  4740.7    0.12       0  4996.9    0.07       0
  5002.9    0.12       0  5031.4    0.16       0  5130.2     0.1       0
Bank Sta=4996.9,5002.9
Exp/Cntr=0.3,0.1

Type RM Length L Ch R = 1,7430,735,735,735
BEGIN DESCRIPTION:
MELTON BRANCH 12.0
END DESCRIPTION:
XS GIS Cut Line= 3
      3541521.93     10321223.74      3540716.49     10321144.61
      3540516.75     10321194.54
#Sta/Elev= 30
  4488.3  365.21  4578.6  362.46  4648.9  362.33  4699.1  361.21  4859.9  360.02
  4894.9  358.86  4950.3  358.07  4960.4  357.09  4967.7  353.29  4972.7  353.67
  4990.5  341.68  4997.6  339.82  5000.3  339.32  5003.6  339.82  5010.6  341.40
  5020.7  344.79  5050.8  351.44  5060.9  354.79  5069.1  355.73  5074.1  355.55
  5091.0  357.59  5141.3  359.74  5170.5  361.89  5175.5  361.46  5181.4  362.59
  5271.8  368.40  5276.9  368.11  5312.4  370.27  5338.6  370.14  5503.5  373.20
#Mann=5,-1,0
  4488.3     0.1       0  4894.9    0.16       0  4997.6    0.07       0
  5003.6    0.16       0  5338.6    0.05       0
Bank Sta=4997.6,5003.6
Exp/Cntr=0.3,0.1

Type RM Length L Ch R = 1,6695,738,738,738
BEGIN DESCRIPTION:
MELTON BRANCH 11.0
END DESCRIPTION:
XS GIS Cut Line= 3
      3541635.48     10320659.20      3541485.48     10320659.20
      3540586.95     10320627.21
#Sta/Elev= 30
  4550.7  364.01  4600.3  363.21  4694.1  362.10  4734.1  361.21  4794.1  360.97
  4870.6  359.56  4894.2  359.35  4904.2  357.86  4914.2  357.52  4924.2  356.37
  4944.2  355.58  4954.2  354.18  4964.2  351.84  4974.2  346.06  4984.2  341.27
  5001.3  336.87  5004.0  336.37  5007.3  336.87  5014.3  341.40  5034.3  350.45
  5044.3  353.21  5056.5  353.31  5094.3  354.76  5174.4  355.07  5224.4  355.89
  5244.4  355.70  5264.4  356.75  5294.6  355.99  5358.7  357.41  5599.8  361.64
#Mann=7,-1,0
  4550.7     0.1       0  4600.3    0.05       0  4870.6    0.16       0
  5001.3    0.07       0  5007.3    0.16       0  5294.6     0.1       0
  5358.7    0.16       0
Bank Sta=5001.3,5007.3
Exp/Cntr=0.3,0.1

Type RM Length L Ch R = 1,5957,545,545,545
BEGIN DESCRIPTION:
MELTON BRANCH 10.0
END DESCRIPTION:
XS GIS Cut Line= 3
      3541562.28     10320079.04      3540772.82     10320080.22
      3540472.82     10320130.22
#Sta/Elev= 30
  4429.5  360.63  4569.7  358.15  4653.4  357.39  4752.2  355.29  4836.1  353.09
  4949.7  350.02  4959.7  348.85  4969.7  346.93  4999.7  335.14  5006.7  334.00
  5009.4  333.50  5012.7  334.00  5019.7  339.81  5029.7  345.50  5039.7  347.82
  5069.7  349.66  5099.7  350.30  5129.7  349.19  5159.7  351.67  5179.7  352.06
  5189.7  351.31  5199.7  349.11  5209.7  348.42  5216.8  350.75  5221.9  350.75
  5229.8  352.69  5250.1  354.31  5341.3  356.67  5499.9  362.03  5523.1  362.30
#Mann=6,-1,0
  4429.5    0.05       0  4653.4     0.1       0  4752.2    0.05       0
  4836.1    0.16       0  5006.7    0.07       0  5012.7    0.16       0
Bank Sta=5006.7,5012.7
Exp/Cntr=0.3,0.1

Type RM Length L Ch R = 1,5412,563,563,563
BEGIN DESCRIPTION:
MELTON BRANCH 9.0
END DESCRIPTION:
XS GIS Cut Line= 3
      3541567.74     10319569.00      3541417.72     10319518.99
      3540490.09     10319603.43
#Sta/Elev= 30
  4359.5  362.06  4474.4  358.64  4533.3  356.65  4605.3  355.60  4774.3  351.55
  4814.5  350.75  4914.9  346.76  4955.1  346.08  4965.1  345.32  4975.1  341.90
  4985.2  335.30  4992.2  331.82  4995.0  331.32  4998.2  331.82  5005.3  333.86
  5015.3  337.61  5025.3  339.15  5041.9  337.50  5046.9  340.72  5065.5  340.30
  5095.6  345.81  5105.7  345.88  5115.7  347.29  5145.8  348.68  5176.0  351.22
  5206.1  352.98  5246.2  354.28  5276.4  356.22  5386.8  359.97  5449.1  361.24
#Mann=5,-1,0
  4359.5    0.16       0  4474.4    0.05       0  4774.3    0.16       0
  4992.2    0.07       0  4998.2    0.16       0
Bank Sta=4992.2,4998.2
Exp/Cntr=0.3,0.1

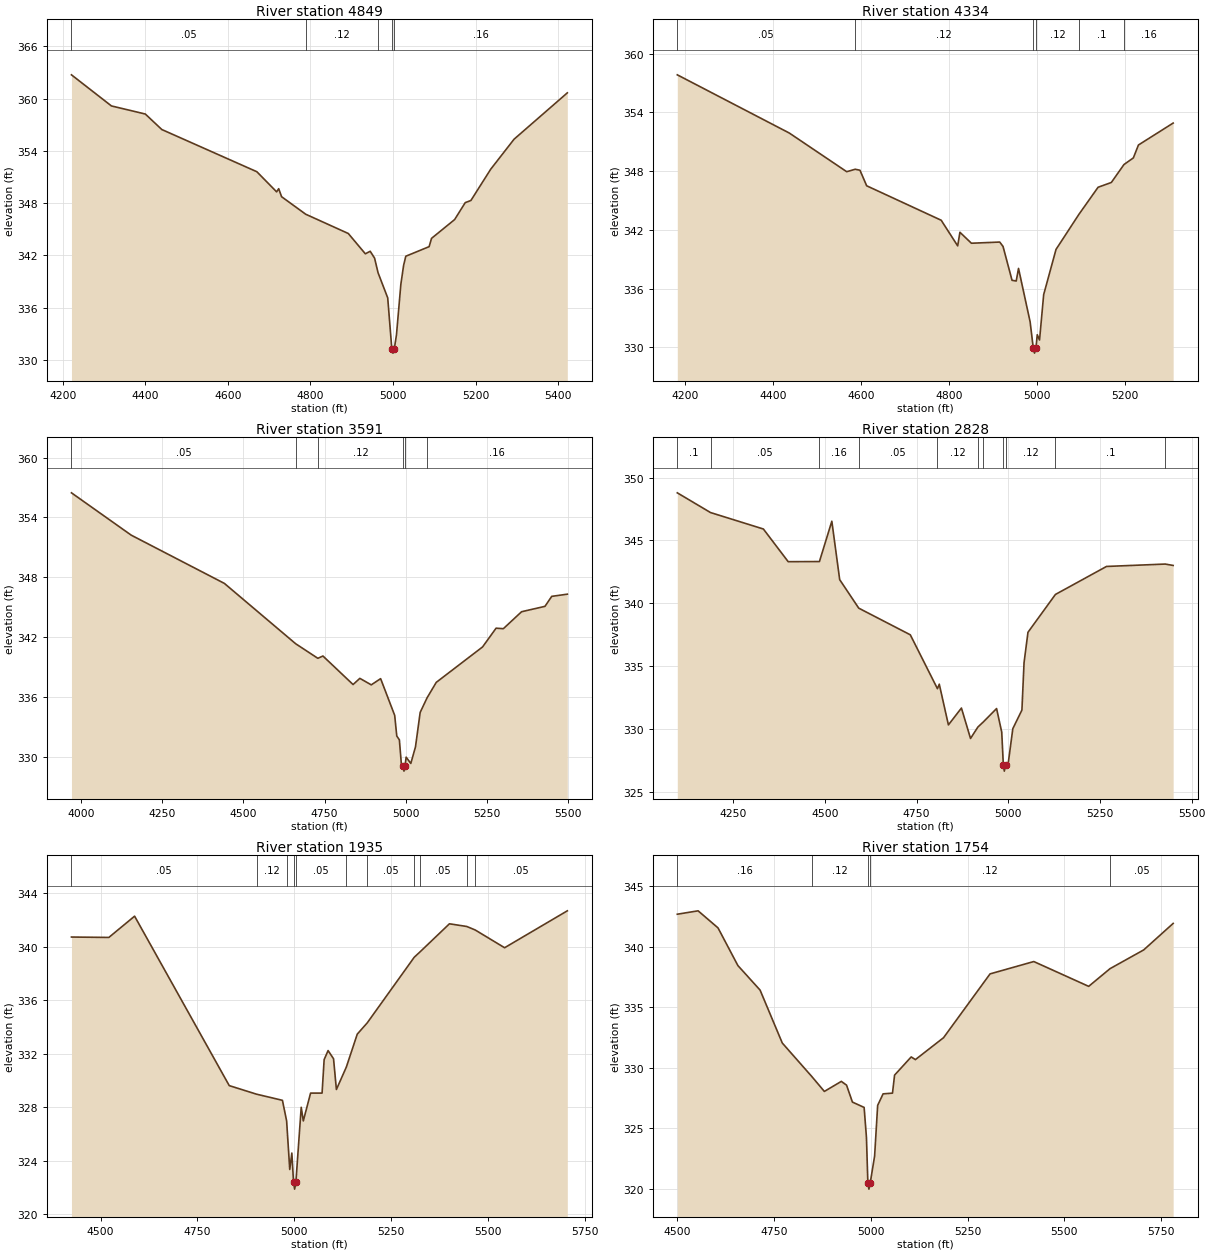
Type RM Length L Ch R = 1,4849,515,515,515
BEGIN DESCRIPTION:
MELTON BRANCH 8.0
END DESCRIPTION:
XS GIS Cut Line= 3
      3541650.99     10319039.13      3541006.04     10319023.01
      3540482.02     10319208.43
#Sta/Elev= 30
  4221.2  362.73  4318.0  359.16  4400.1  358.23  4440.1  356.45  4670.2  351.61
  4718.1  349.30  4723.1  349.66  4730.2  348.74  4788.6  346.73  4891.7  344.52
  4933.0  342.19  4944.8  342.48  4955.4  341.69  4963.7  340.03  4987.2  337.13
  4997.1  331.29  4999.9  330.79  5003.1  331.29  5008.4  332.88  5019.0  338.68
  5025.7  340.87  5031.0  341.91  5087.5  343.01  5093.3  343.96  5149.3  346.12
  5174.9  348.06  5188.7  348.31  5236.7  351.90  5293.2  355.34  5422.2  360.66
#Mann=5,-1,0
  4221.2    0.05       0  4788.6    0.12       0  4963.7    0.16       0
  4997.1    0.07       0  5003.1    0.16       0
Bank Sta=4997.1,5003.1
Exp/Cntr=0.3,0.1

Type RM Length L Ch R = 1,4334,743,743,743
BEGIN DESCRIPTION:
MELTON BRANCH 7.0
END DESCRIPTION:
XS GIS Cut Line= 3
      3541505.87     10318539.33      3540949.61     10318587.70
      3540395.28     10318716.24
#Sta/Elev= 30
  4182.8  357.84  4437.5  351.89  4568.0  347.94  4587.4  348.19  4598.1  348.09
  4613.4  346.50  4782.8  342.98  4820.3  340.36  4825.4  341.75  4851.5  340.63
  4915.9  340.75  4923.4  340.30  4943.9  336.84  4953.4  336.77  4958.6  338.06
  4985.0  332.60  4992.2  329.90  4995.0  329.40  4998.2  329.90  5001.2  331.28
  5006.4  330.74  5015.8  335.38  5043.9  340.00  5095.9  343.58  5139.5  346.35
  5169.7  346.84  5198.3  348.67  5219.7  349.35  5231.3  350.67  5310.2  352.91
#Mann=6,-1,0
  4182.8    0.05       0  4587.4    0.12       0  4992.2    0.07       0
  4998.2    0.12       0  5095.9     0.1       0  5198.3    0.16       0
Bank Sta=4992.2,4998.2
Exp/Cntr=0.3,0.1

Type RM Length L Ch R = 1,3591,763,763,763
BEGIN DESCRIPTION:
MELTON BRANCH 6.0
END DESCRIPTION:
XS GIS Cut Line= 3
      3541505.83     10317934.74      3540764.20     10318063.72
      3540160.09     10318547.00
#Sta/Elev= 30
  3970.6  356.47  4154.4  352.23  4441.3  347.39  4660.8  341.34  4729.1  339.88
  4744.7  340.11  4837.5  337.25  4858.3  337.87  4893.5  337.22  4922.3  337.84
  4965.6  334.16  4972.0  332.09  4980.0  331.71  4986.4  329.18  4991.4  329.07
  4994.1  328.57  4997.4  329.07  5000.8  329.97  5015.2  329.34  5029.6  331.00
  5044.0  334.45  5065.3  335.92  5093.6  337.47  5236.1  341.02  5277.7  342.90
  5300.1  342.85  5356.2  344.55  5428.2  345.09  5449.0  346.09  5497.0  346.31
#Mann=6,-1,0
  3970.6    0.05       0  4660.8    0.16       0  4729.1    0.12       0
  4991.4    0.07       0  4997.4    0.12       0  5065.3    0.16       0
Bank Sta=4991.4,4997.4
Exp/Cntr=0.3,0.1

Type RM Length L Ch R = 1,2828,893,893,893
BEGIN DESCRIPTION:
MELTON BRANCH 4.0
END DESCRIPTION:
XS GIS Cut Line= 3
      3541215.72     10317493.03      3540865.72     10317593.03
      3539941.93     10317942.80
#Sta/Elev= 30
  4097.8  348.79  4188.4  347.22  4332.5  345.91  4400.1  343.31  4485.3  343.32
  4519.1  346.53  4540.5  341.88  4592.5  339.61  4733.0  337.49  4807.0  333.20
  4812.0  333.56  4836.9  330.32  4872.4  331.66  4897.2  329.24  4917.3  330.15
  4931.9  330.55  4968.2  331.62  4982.3  329.74  4986.6  327.14  4989.4  326.64
  4992.6  327.14  5000.3  327.34  5012.5  330.02  5037.3  331.50  5043.1  335.27
  5053.8  337.69  5128.6  340.70  5267.9  342.93  5428.1  343.12  5449.6  343.01
#Mann=11,-1,0
  4097.8     0.1       0  4188.4    0.05       0  4485.3    0.16       0
  4592.5    0.05       0  4807.0    0.12       0  4917.3    0.16       0
  4931.9    0.12       0  4986.6    0.07       0  4992.6    0.12       0
  5128.6     0.1       0  5428.1    0.05       0
Bank Sta=4986.6,4992.6
Exp/Cntr=0.3,0.1

Type RM Length L Ch R = 1,1935,181,181,181
BEGIN DESCRIPTION:
MELTON BRANCH 3.1
END DESCRIPTION:
XS GIS Cut Line= 4
      3540671.39     10316846.08      3540233.90     10317130.79
      3540136.68     10317373.85      3539761.68     10317700.24
#Sta/Elev= 30
  4424.6  340.71  4521.2  340.68  4587.7  342.27  4832.2  329.60  4902.7  328.96
  4969.6  328.50  4980.4  326.96  4988.5  323.33  4993.9  324.56  4998.3  322.36
  5001.1  321.86  5004.3  322.36  5018.1  327.98  5023.5  326.96  5042.3  329.04
  5072.0  329.04  5077.3  331.54  5087.5  332.22  5101.6  331.61  5109.0  329.31
  5134.7  330.99  5162.9  333.45  5188.6  334.29  5310.1  339.20  5324.3  339.58
  5401.0  341.70  5445.7  341.50  5467.4  341.24  5543.5  339.91  5705.5  342.67
#Mann=11,-1,0
  4424.6    0.05       0  4902.7    0.12       0  4980.4    0.05       0
  4998.3    0.04       0  5004.3    0.05       0  5134.7    0.16       0
  5188.6    0.05       0  5310.1    0.16       0  5324.3    0.05       0
  5445.7    0.16       0  5467.4    0.05       0
Bank Sta=4998.3,5004.3
Exp/Cntr=0.3,0.1

Type RM Length L Ch R = 1,1754,628,628,628
BEGIN DESCRIPTION:
MELTON BRANCH 3.0
END DESCRIPTION:
XS GIS Cut Line= 4
      3540567.21     10316790.53      3540129.73     10317075.24
      3540032.51     10317318.29      3539657.50     10317644.70
#Sta/Elev= 30
  4500.2  342.70  4554.0  342.98  4605.4  341.57  4656.7  338.46  4714.1  336.43
  4771.4  332.06  4848.0  329.28  4880.1  328.06  4923.9  328.89  4937.4  328.58
  4952.6  327.18  4982.8  326.74  4988.8  324.27  4992.5  320.49  4995.2  319.99
  4998.5  320.49  5009.9  322.72  5017.8  326.91  5031.8  327.86  5056.1  327.92
  5061.5  329.41  5104.4  330.91  5115.3  330.69  5188.0  332.50  5308.1  337.77
  5421.1  338.79  5562.9  336.74  5617.9  338.20  5705.0  339.75  5781.1  341.94
#Mann=5,-1,0
  4500.2    0.16       0  4848.0    0.12       0  4992.5    0.07       0
  4998.5    0.12       0  5617.9    0.05       0
Bank Sta=4992.5,4998.5
Exp/Cntr=0.3,0.1

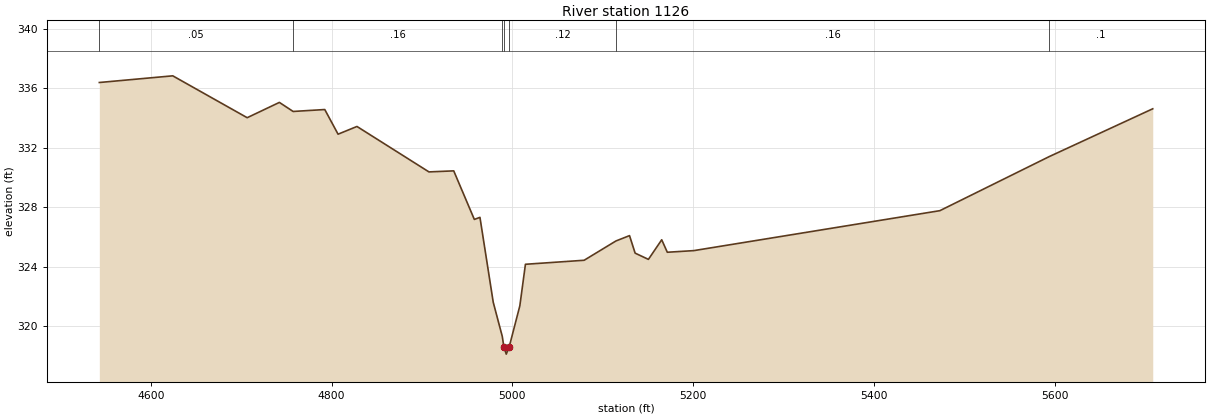
Type RM Length L Ch R = 1,1126,0,0,0
BEGIN DESCRIPTION:
MELTON BRANCH 1.0
END DESCRIPTION:
XS GIS Cut Line= 3
      3540671.25     10316533.30      3540521.27     10316483.31
      3539706.60     10317074.89
#Sta/Elev= 30
  4543.2  336.39  4624.4  336.84  4706.7  334.02  4742.3  335.05  4757.5  334.44
  4792.5  334.57  4807.2  332.91  4828.1  333.43  4907.7  330.37  4935.1  330.44
  4957.9  327.17  4964.1  327.31  4978.8  321.59  4988.8  319.29  4990.5  318.60
  4993.2  318.10  4996.5  318.60  5008.2  321.35  5014.4  324.15  5079.3  324.42
  5114.5  325.72  5129.5  326.08  5135.7  324.90  5150.4  324.48  5165.1  325.80
  5171.3  324.96  5200.6  325.07  5472.7  327.76  5593.6  331.40  5708.1  334.62
#Mann=7,-1,0
  4543.2    0.05       0  4757.5    0.16       0  4988.8    0.12       0
  4990.5    0.07       0  4996.5    0.12       0  5114.5    0.16       0
  5593.6     0.1       0
Bank Sta=4990.5,4996.5
Exp/Cntr=0.3,0.1

Chan Stop Cuts=-1