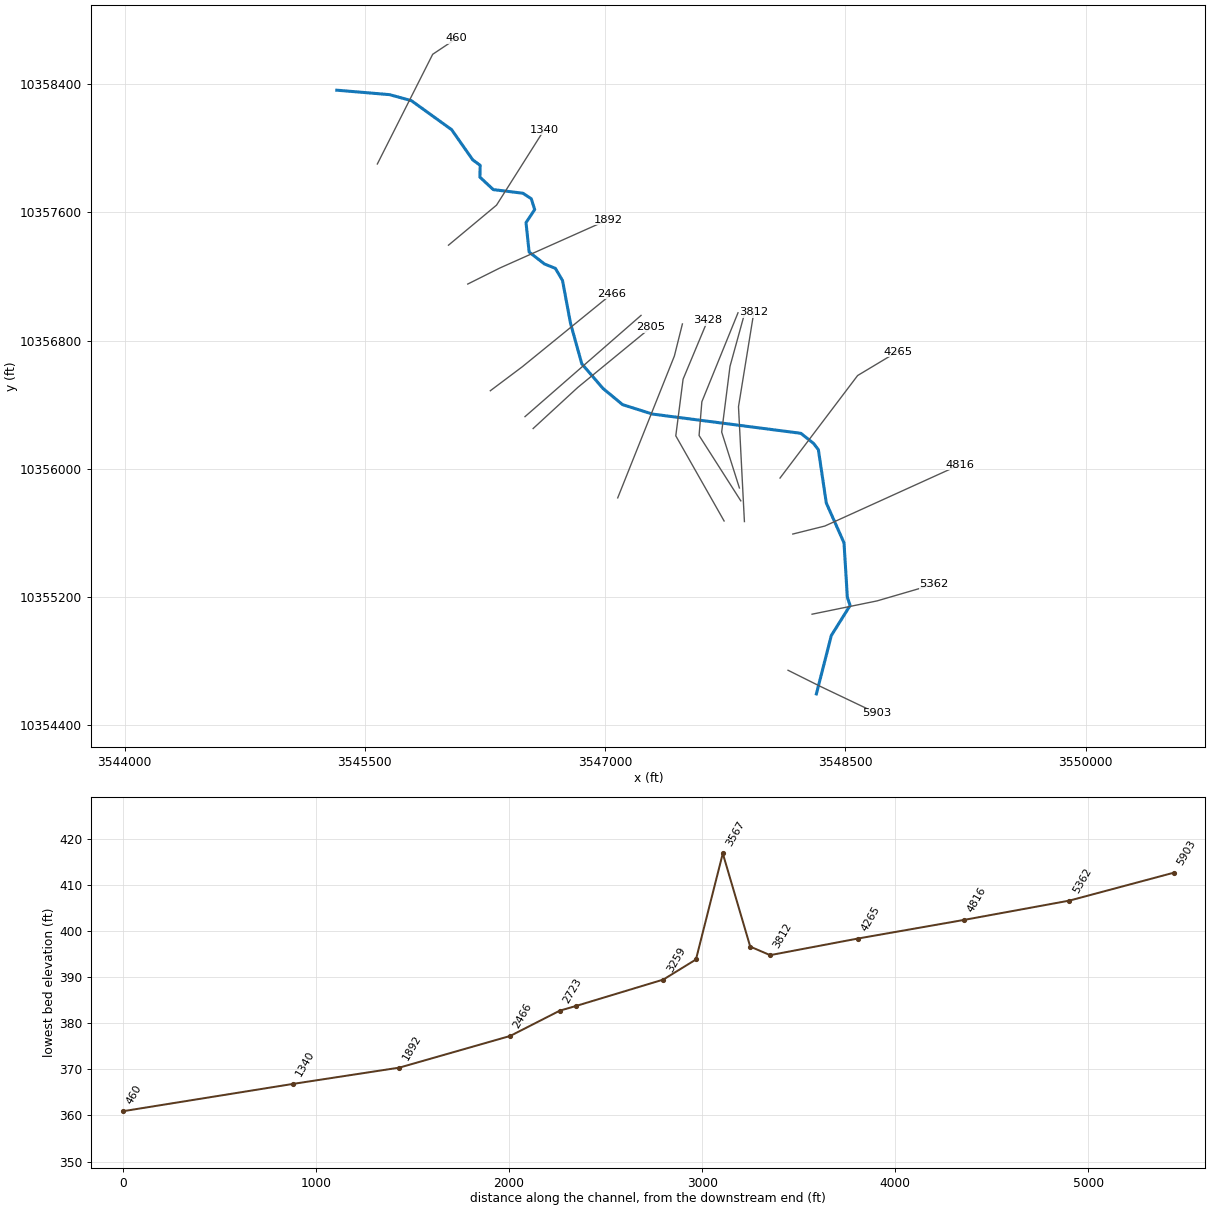
--- MILL CREEK EAST TRIBUTARY 1.prj (project) ---

Proj Title=MILL CREEK EAST TRIBUTARY 1 Base Level Engineering
Current Plan=p01
Default Exp/Contr=0.3,0.1
English Units
Geom File=g01
Flow File=f01
Plan File=p01
BEGIN DESCRIPTION:
MILL CREEK EAST TRIBUTARY 1
END DESCRIPTION:

--- MILL CREEK EAST TRIBUTARY 1.p01 (plan) ---

Plan Title=Multiple Run
Short Identifier=Multiple
Geom File=g01
Flow File=f01
Subcritical Flow
K Sum by GR= 0
Std Step Tol= 0.01
Critical Tol= 0.01
Num of Std Step Trials= 20
Max Error Tol= 0.3
Flow Tol Ratio= 0.001
Split Flow NTrial= 30
Split Flow Tol= 0.02
Split Flow Ratio= 0.02
Log Output Level= 0
Friction Slope Method= 1
Unsteady Friction Slope Method= 2
Unsteady Bridges Friction Slope Method= 1
Parabolic Critical Depth
Global Vel Dist=  1 , 1 , 1
Global Log Level= 0
CheckData=True
Encroach Param= -1, 0, 0, 0
BEGIN DESCRIPTION:
Multiple Run
END DESCRIPTION:

--- MILL CREEK EAST TRIBUTARY 1.f01 (steady flow) ---

Flow Title=Multiple
Number of Profiles=7
Profile Names=10-year,25-year,50-year,1pct_min,100-year,1pct_plu,500-year
River Rch & RM= MILL CREEK EAST ,Reach-1,5903
    1073    1500    1858    1680    2273    3073    3392
Boundary for River Rch & Prof#=MILL CREEK EAST ,Reach-1,1
Up Type=0
Dn Type=3
Dn Slope=0.005
Boundary for River Rch & Prof#=MILL CREEK EAST ,Reach-1,2
Up Type=0
Dn Type=3
Dn Slope=0.005
Boundary for River Rch & Prof#=MILL CREEK EAST ,Reach-1,3
Up Type=0
Dn Type=3
Dn Slope=0.005
Boundary for River Rch & Prof#=MILL CREEK EAST ,Reach-1,4
Up Type=0
Dn Type=3
Dn Slope=0.005
Boundary for River Rch & Prof#=MILL CREEK EAST ,Reach-1,5
Up Type=0
Dn Type=3
Dn Slope=0.005
Boundary for River Rch & Prof#=MILL CREEK EAST ,Reach-1,6
Up Type=0
Dn Type=3
Dn Slope=0.005
Boundary for River Rch & Prof#=MILL CREEK EAST ,Reach-1,7
Up Type=0
Dn Type=3
Dn Slope=0.005

--- MILL CREEK EAST TRIBUTARY 1.g01 (geometry) ---

Geom Title=Existing Conditions

River Reach=MILL CREEK EAST ,Reach-1
Reach XY= 30
      3548319.14     10354594.13      3548412.39     10354958.72
      3548529.75     10355146.22      3548512.39     10355197.61
      3548491.56     10355537.19      3548380.93     10355786.02
      3548331.45     10356119.03      3548301.06     10356158.09
      3548221.85     10356221.02      3547295.44     10356341.17
      3547108.98     10356400.02      3546986.46     10356501.41
      3546854.33     10356655.01      3546784.07     10356907.47
      3546734.15     10357174.81      3546689.64     10357250.77
      3546621.16     10357278.28      3546525.61     10357352.85
      3546506.19     10357536.54      3546560.26     10357617.74
      3546539.11     10357685.29      3546486.77     10357719.91
      3546301.83     10357742.54      3546218.34     10357820.42
      3546219.88     10357894.27      3546173.38     10357928.51
      3546041.87     10358116.66      3545790.19     10358298.11
      3545654.34     10358335.44      3545324.71     10358363.27

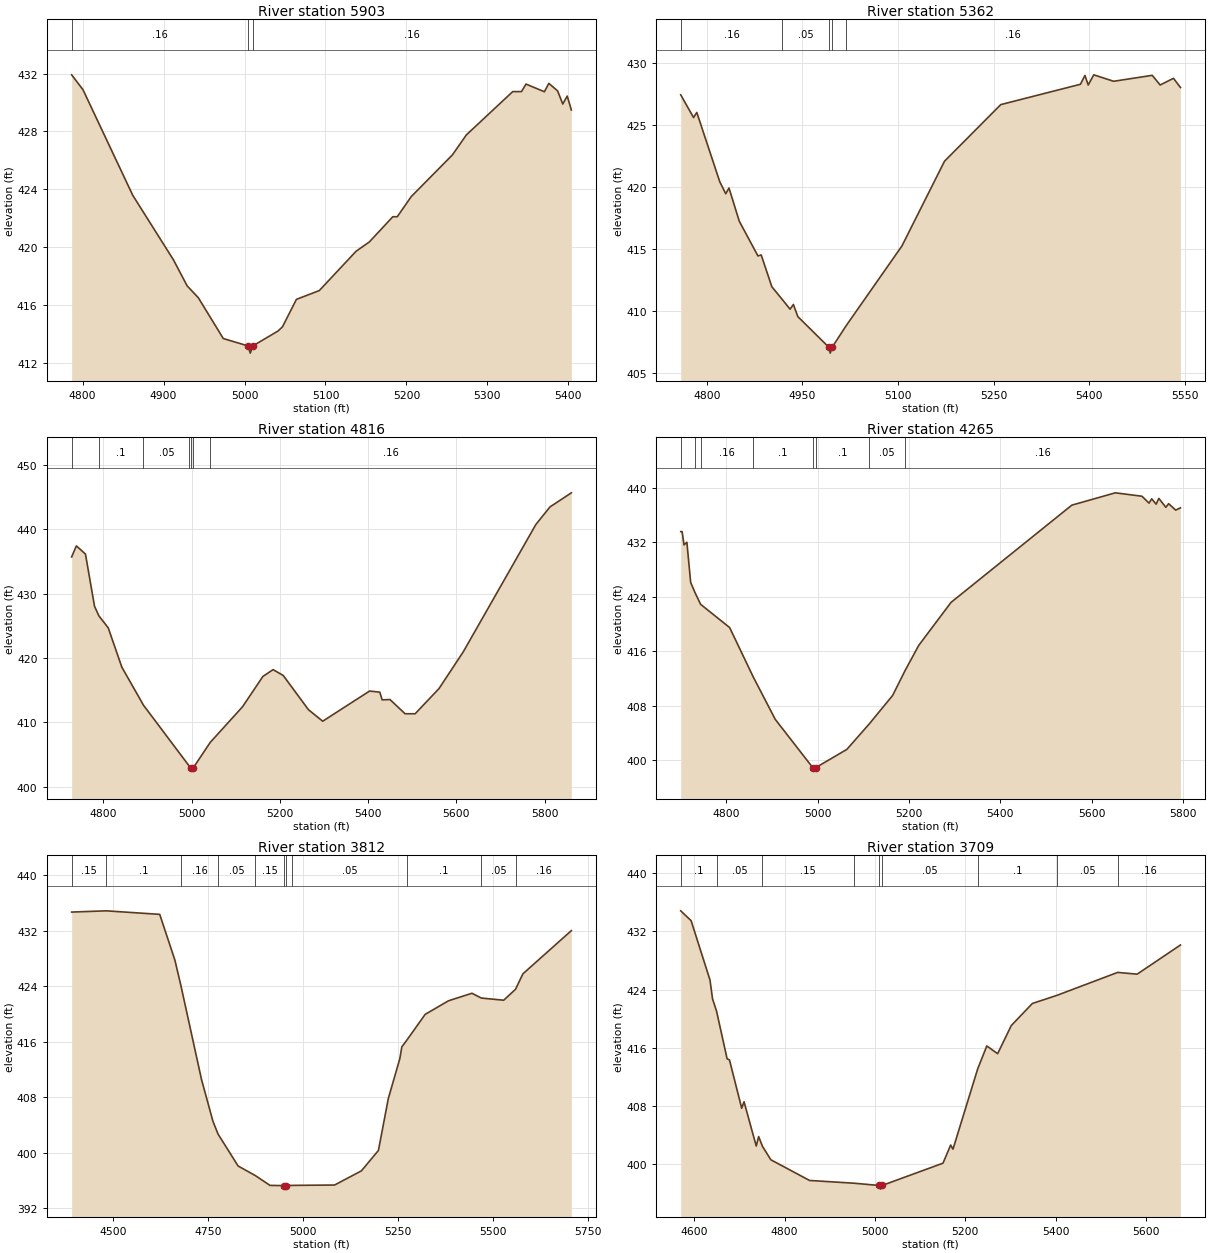
Type RM Length L Ch R = 1,5903,541,541,541
BEGIN DESCRIPTION:
MILL CREEK EAST TRIBUTARY 1 13.0
END DESCRIPTION:
XS GIS Cut Line= 3
      3548142.09     10354741.65      3548342.11     10354641.64
      3548697.45     10354472.42
#Sta/Elev= 30
  4786.5  431.92  4800.5  430.89  4862.0  423.58  4912.3  419.11  4929.1  417.32
  4943.0  416.49  4973.8  413.67  5004.3  413.16  5007.1  412.66  5010.3  413.16
  5041.4  414.19  5046.9  414.48  5064.1  416.38  5092.4  416.99  5137.8  419.71
  5154.1  420.35  5183.2  422.10  5188.7  422.10  5205.9  423.49  5256.8  426.38
  5274.0  427.76  5331.3  430.76  5342.1  430.76  5347.7  431.28  5370.4  430.75
  5375.9  431.33  5386.7  430.81  5393.1  429.90  5398.6  430.45  5403.7  429.49
#Mann=3,-1,0
  4786.5    0.16       0  5004.3    0.07       0  5010.3    0.16       0
Bank Sta=5004.3,5010.3
Exp/Cntr=0.3,0.1

Type RM Length L Ch R = 1,5362,546,546,546
BEGIN DESCRIPTION:
MILL CREEK EAST TRIBUTARY 1 12.0
END DESCRIPTION:
XS GIS Cut Line= 3
      3548292.10     10355091.64      3548697.74     10355174.61
      3549052.61     10355278.11
#Sta/Elev= 30
  4759.2  427.41  4779.3  425.58  4784.4  425.99  4820.4  420.41  4829.8  419.44
  4834.9  419.90  4851.1  417.22  4880.3  414.43  4885.4  414.51  4902.1  411.95
  4918.8  410.90  4930.7  410.14  4935.9  410.52  4942.9  409.54  4991.0  407.10
  4993.7  406.60  4997.0  407.10  5018.8  408.82  5106.2  415.24  5172.9  422.06
  5261.1  426.62  5386.1  428.26  5393.1  428.97  5398.3  428.20  5407.0  429.02
  5438.2  428.50  5498.7  428.98  5511.1  428.20  5532.0  428.74  5542.9  428.00
#Mann=5,-1,0
  4759.2    0.16       0  4918.8    0.05       0  4991.0    0.04       0
  4997.0    0.05       0  5018.8    0.16       0
Bank Sta=4991,4997
Exp/Cntr=0.3,0.1

Type RM Length L Ch R = 1,4816,551,551,551
BEGIN DESCRIPTION:
MILL CREEK EAST TRIBUTARY 1 10.0
END DESCRIPTION:
XS GIS Cut Line= 3
      3548171.71     10355592.04      3548371.68     10355642.04
      3549215.28     10356024.80
#Sta/Elev= 30
  4728.2  435.71  4738.9  437.43  4759.5  436.16  4780.1  428.03  4790.1  426.53
  4811.1  424.69  4842.0  418.57  4891.0  412.66  4995.1  403.16  4997.7  402.91
  5000.4  402.41  5003.7  402.91  5042.3  406.88  5115.4  412.41  5161.6  417.13
  5184.7  418.19  5207.8  417.28  5264.9  411.96  5297.2  410.17  5403.4  414.86
  5426.5  414.69  5432.0  413.49  5449.6  413.54  5483.9  411.33  5506.7  411.33
  5560.7  415.24  5615.6  420.94  5780.3  440.76  5812.3  443.49  5860.7  445.68
#Mann=7,-1,0
  4728.2    0.16       0  4790.1     0.1       0  4891.0    0.05       0
  4995.1     0.1       0  4997.7    0.07       0  5003.7     0.1       0
  5042.3    0.16       0
Bank Sta=4997.7,5003.7
Exp/Cntr=0.3,0.1

Type RM Length L Ch R = 1,4265,453,453,453
BEGIN DESCRIPTION:
MILL CREEK EAST TRIBUTARY 1 9.0
END DESCRIPTION:
XS GIS Cut Line= 3
      3548092.13     10355941.67      3548576.53     10356581.71
      3548826.51     10356731.70
#Sta/Elev= 30
  4700.5  433.56  4703.6  433.56  4707.7  431.61  4714.0  431.99  4722.3  426.09
  4732.3  424.52  4744.0  422.88  4807.6  419.46  4859.3  412.20  4907.5  405.97
  4989.8  398.86  4992.6  398.36  4995.8  398.86  5064.2  401.55  5113.1  405.28
  5164.5  409.48  5191.4  413.09  5221.7  416.84  5292.4  423.16  5556.9  437.45
  5652.1  439.26  5710.4  438.76  5726.0  437.75  5731.8  438.38  5741.5  437.59
  5747.4  438.44  5762.9  437.13  5768.8  437.67  5784.3  436.72  5794.7  437.05
#Mann=8,-1,0
  4700.5    0.16       0  4732.3    0.05       0  4744.0    0.16       0
  4859.3     0.1       0  4989.8    0.07       0  4995.8     0.1       0
  5113.1    0.05       0  5191.4    0.16       0
Bank Sta=4989.8,4995.8
Exp/Cntr=0.3,0.1

Type RM Length L Ch R = 1,3812,103,103,103
BEGIN DESCRIPTION:
MILL CREEK EAST TRIBUTARY 1 8.0
END DESCRIPTION:
XS GIS Cut Line= 3
      3547869.74     10355669.96      3547832.78     10356387.03
      3547928.74     10356977.57
#Sta/Elev= 30
  4390.4  434.66  4481.5  434.84  4622.4  434.33  4662.4  427.74  4677.8  424.17
  4732.5  410.55  4762.6  404.54  4775.9  402.71  4828.9  398.10  4874.0  396.73
  4912.8  395.31  4949.8  395.27  4952.6  394.77  4955.8  395.27  4972.1  395.31
  5083.0  395.36  5153.6  397.40  5198.5  400.34  5224.5  407.80  5254.9  413.56
  5260.1  415.25  5272.7  416.17  5321.6  419.93  5383.2  421.89  5444.8  422.97
  5469.6  422.28  5528.5  421.97  5559.7  423.55  5579.1  425.77  5706.7  431.99
#Mann=11,-1,0
  4390.4    0.15       0  4481.5     0.1       0  4677.8    0.16       0
  4775.9    0.05       0  4874.0    0.15       0  4949.8    0.03       0
  4955.8    0.15       0  4972.1    0.05       0  5272.7     0.1       0
  5469.6    0.05       0  5559.7    0.16       0
Bank Sta=4949.8,4955.8
Exp/Cntr=0.3,0.1

Type RM Length L Ch R = 1,3709,142,142,142
BEGIN DESCRIPTION:
Mapping XS 7014f7df
END DESCRIPTION:
XS GIS Cut Line= 4
      3547838.42     10355879.76      3547727.74     10356229.16
      3547779.82     10356639.32      3547866.63     10356954.00
#Sta/Elev= 30
  4570.2  434.80  4593.2  433.45  4635.1  425.29  4640.6  422.73  4649.5  421.04
  4672.9  414.50  4678.1  414.35  4705.2  407.72  4710.4  408.61  4737.4  402.53
  4742.7  403.83  4751.2  402.49  4769.7  400.65  4855.4  397.81  4954.3  397.43
  5009.9  397.12  5012.7  396.62  5015.9  397.12  5150.9  400.18  5167.9  402.67
  5173.0  402.10  5227.8  413.13  5247.9  416.26  5271.9  415.20  5302.1  419.06
  5348.8  422.09  5403.5  423.21  5537.6  426.35  5580.8  426.11  5676.6  430.11
#Mann=9,-1,0
  4570.2     0.1       0  4649.5    0.05       0  4751.2    0.15       0
  4954.3    0.05       0  5009.9    0.03       0  5015.9    0.05       0
  5227.8     0.1       0  5403.5    0.05       0  5537.6    0.16       0
Bank Sta=5009.9,5015.9
Exp/Cntr=0.3,0.1

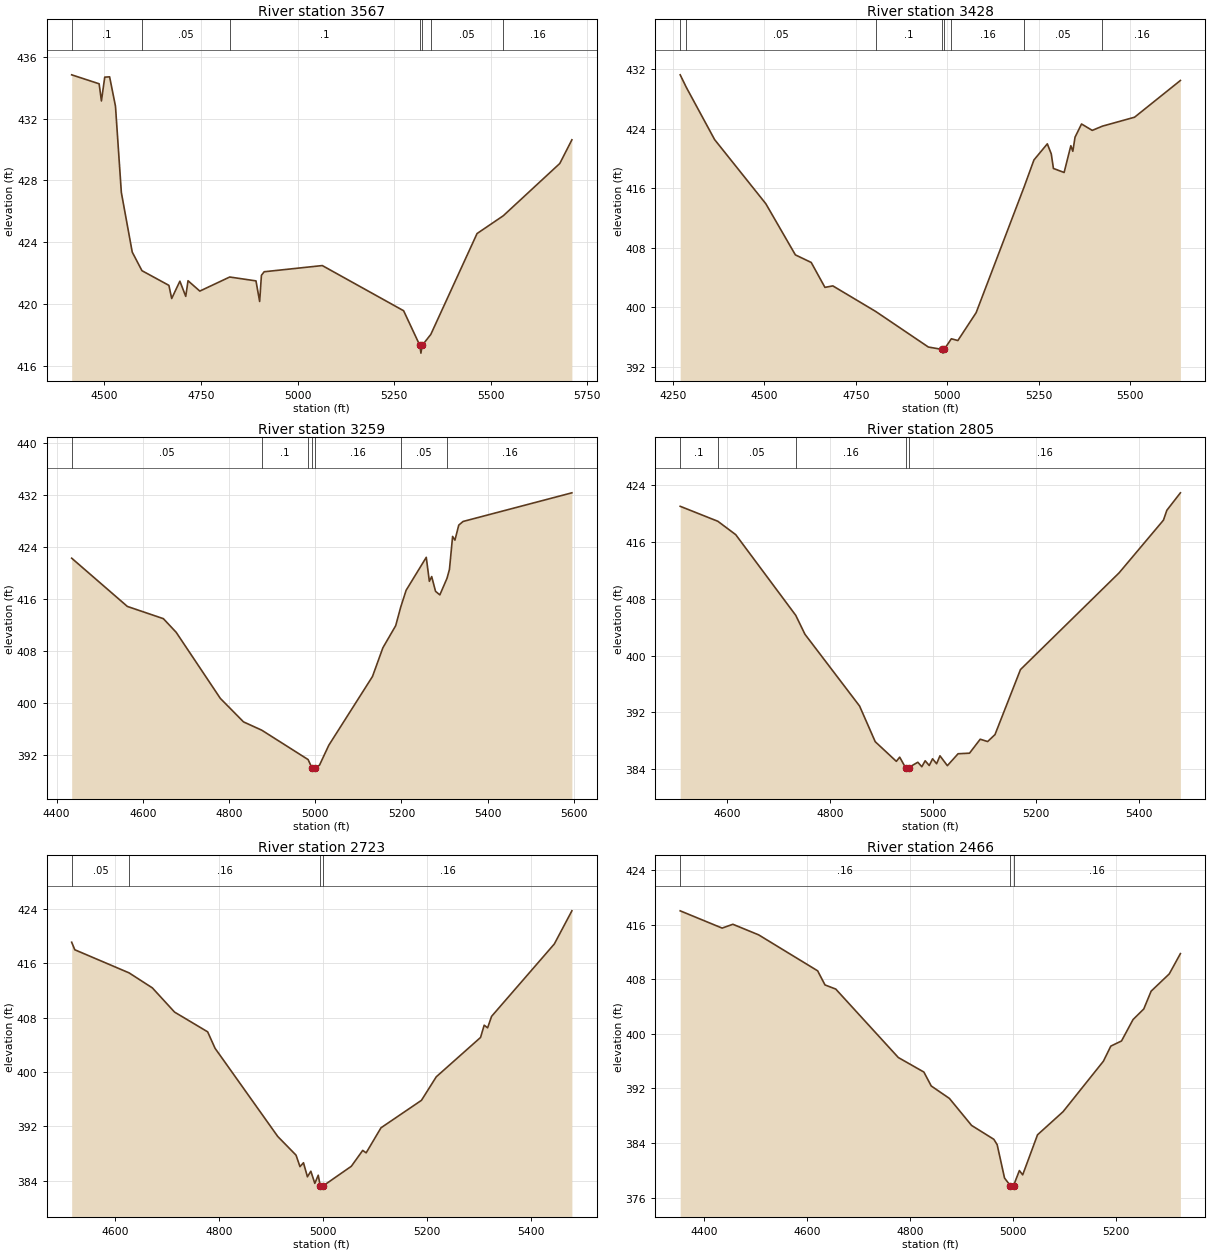
Type RM Length L Ch R = 1,3567,139,139,139
BEGIN DESCRIPTION:
Mapping XS 04e824bc
END DESCRIPTION:
XS GIS Cut Line= 4
      3547847.11     10355799.45      3547586.68     10356207.46
      3547604.04     10356417.96      3547829.73     10356973.51
#Sta/Elev= 30
  4415.4  434.83  4486.5  434.25  4492.4  433.14  4501.0  434.68  4513.6  434.70
  4528.8  432.80  4544.0  427.22  4572.2  423.37  4597.3  422.17  4667.1  421.22
  4674.3  420.37  4695.5  421.49  4710.7  420.51  4716.6  421.52  4747.1  420.85
  4824.5  421.76  4892.5  421.51  4902.0  420.18  4906.6  421.87  4913.7  422.10
  5064.2  422.50  5274.7  419.58  5316.7  417.34  5319.5  416.84  5322.7  417.34
  5345.1  418.05  5464.8  424.57  5532.7  425.72  5679.0  429.10  5710.3  430.63
#Mann=7,-1,0
  4415.4     0.1       0  4597.3    0.05       0  4824.5     0.1       0
  5316.7    0.07       0  5322.7     0.1       0  5345.1    0.05       0
  5532.7    0.16       0
Bank Sta=5316.7,5322.7
Exp/Cntr=0.3,0.1

Type RM Length L Ch R = 1,3428,169,169,169
BEGIN DESCRIPTION:
Mapping XS eb689f01
END DESCRIPTION:
XS GIS Cut Line= 4
      3547742.91     10355673.64      3547441.28     10356205.29
      3547486.85     10356559.02      3547640.66     10356927.29
#Sta/Elev= 30
  4269.9  431.25  4286.7  429.56  4364.0  422.54  4503.9  413.92  4584.7  407.04
  4628.0  406.02  4665.5  402.67  4687.1  402.87  4804.3  399.43  4948.1  394.65
  4985.4  394.33  4988.1  393.83  4991.4  394.33  5010.9  395.76  5028.7  395.52
  5078.7  399.27  5209.9  416.19  5236.6  419.80  5273.2  421.97  5284.0  420.62
  5289.9  418.66  5319.1  418.12  5337.5  421.72  5342.9  420.97  5349.0  422.87
  5366.7  424.64  5396.0  423.78  5423.9  424.35  5511.6  425.55  5636.9  430.49
#Mann=8,-1,0
  4269.9    0.15       0  4286.7    0.05       0  4804.3     0.1       0
  4985.4    0.07       0  4991.4     0.1       0  5010.9    0.16       0
  5209.9    0.05       0  5423.9    0.16       0
Bank Sta=4985.4,4991.4
Exp/Cntr=0.3,0.1

Type RM Length L Ch R = 1,3259,454,454,454
BEGIN DESCRIPTION:
MILL CREEK EAST TRIBUTARY 1 7.0
END DESCRIPTION:
XS GIS Cut Line= 3
      3547078.71     10355817.81      3547432.57     10356703.89
      3547482.57     10356903.91
#Sta/Elev= 30
  4435.1  422.25  4564.3  414.82  4647.8  412.94  4677.5  410.84  4779.9  400.67
  4833.7  397.05  4876.1  395.77  4983.5  391.25  4992.4  389.97  4995.1  389.47
  4998.4  389.97  5009.9  390.38  5031.5  393.45  5132.8  404.03  5157.0  408.46
  5186.7  411.86  5198.3  414.71  5210.9  417.31  5257.6  422.38  5264.8  418.69
  5270.2  419.42  5279.1  417.15  5289.1  416.60  5305.7  419.15  5311.4  420.52
  5318.7  425.60  5324.1  425.03  5333.0  427.34  5342.9  427.90  5595.4  432.31
#Mann=7,-1,0
  4435.1    0.05       0  4876.1     0.1       0  4983.5    0.16       0
  4992.4    0.07       0  4998.4    0.16       0  5198.3    0.05       0
  5305.7    0.16       0
Bank Sta=4992.4,4998.4
Exp/Cntr=0.3,0.1

Type RM Length L Ch R = 1,2805,82,82,82
BEGIN DESCRIPTION:
Mapping XS cc722c09
END DESCRIPTION:
XS GIS Cut Line= 3
      3546550.63     10356250.83      3546829.30     10356507.37
      3547287.40     10356883.49
#Sta/Elev= 30
  4508.6  421.06  4581.7  418.95  4616.5  417.06  4733.1  405.68  4750.9  403.02
  4857.0  392.90  4887.4  387.87  4928.4  385.10  4934.9  385.69  4946.2  384.22
  4949.0  383.72  4952.2  384.22  4970.1  384.97  4977.9  384.34  4984.4  385.18
  4992.3  384.51  4998.8  385.46  5006.6  384.76  5013.1  385.88  5027.5  384.49
  5048.3  386.17  5070.5  386.25  5091.3  388.22  5105.7  387.89  5120.0  388.87
  5169.5  398.04  5361.1  411.68  5447.2  419.11  5453.7  420.49  5480.1  422.96
#Mann=5,-1,0
  4508.6     0.1       0  4581.7    0.05       0  4733.1    0.16       0
  4946.2    0.07       0  4952.2    0.16       0
Bank Sta=4946.2,4952.2
Exp/Cntr=0.3,0.1

Type RM Length L Ch R = 1,2723,257,257,257
BEGIN DESCRIPTION:
Mapping XS 806334f5
END DESCRIPTION:
XS GIS Cut Line= 2
      3546499.85     10356325.06      3547224.41     10356957.26
#Sta/Elev= 30
  4516.5  419.13  4522.5  418.02  4626.9  414.61  4671.6  412.40  4714.3  408.83
  4777.9  405.92  4792.1  403.50  4912.7  390.49  4947.8  387.74  4955.4  386.05
  4962.1  386.62  4969.7  384.55  4976.3  385.37  4983.9  383.58  4990.5  384.78
  4994.3  383.23  4997.0  382.73  5000.3  383.23  5054.1  386.10  5076.0  388.44
  5082.6  388.08  5111.1  391.77  5188.9  395.82  5217.4  399.29  5302.5  405.09
  5309.5  406.90  5316.1  406.51  5323.7  408.20  5444.3  418.87  5478.1  423.76
#Mann=4,-1,0
  4516.5    0.05       0  4626.9    0.16       0  4994.3    0.07       0
  5000.3    0.16       0
Bank Sta=4994.3,5000.3
Exp/Cntr=0.3,0.1

Type RM Length L Ch R = 1,2466,574,574,574
BEGIN DESCRIPTION:
MILL CREEK EAST TRIBUTARY 1 5.0
END DESCRIPTION:
XS GIS Cut Line= 3
      3546283.37     10356486.80      3546483.36     10356636.79
      3547042.13     10357091.66
#Sta/Elev= 30
  4353.8  418.01  4435.2  415.48  4456.0  416.04  4506.0  414.49  4620.5  409.22
  4634.8  407.15  4655.6  406.55  4777.0  396.52  4826.6  394.39  4840.9  392.35
  4876.1  390.53  4919.2  386.57  4962.3  384.54  4968.8  383.75  4983.1  378.86
  4994.5  377.74  4997.3  377.24  5000.5  377.74  5011.9  379.96  5018.3  379.33
  5047.1  385.20  5096.6  388.58  5174.9  395.98  5189.3  398.19  5210.1  398.95
  5232.4  402.08  5253.2  403.63  5267.5  406.24  5302.7  408.77  5324.3  411.74
#Mann=3,-1,0
  4353.8    0.16       0  4994.5    0.07       0  5000.5    0.16       0
Bank Sta=4994.5,5000.5
Exp/Cntr=0.3,0.1

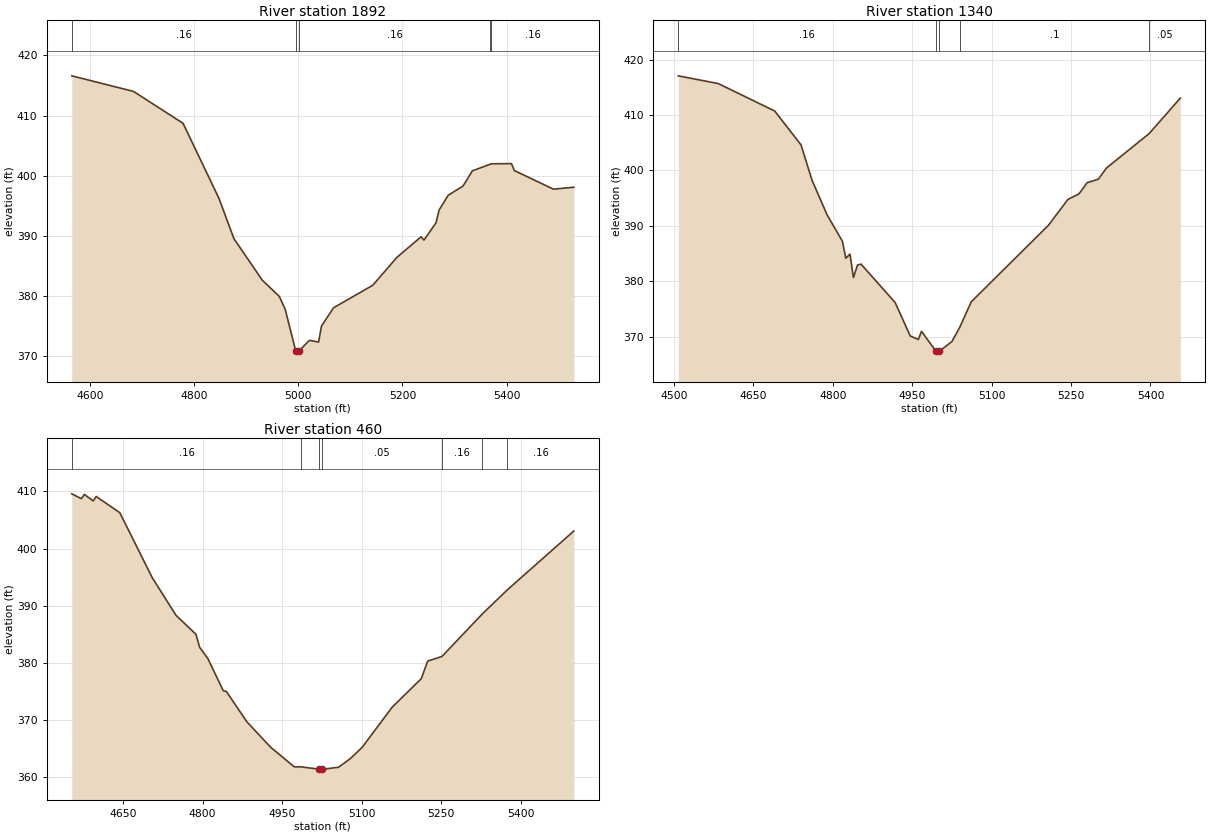
Type RM Length L Ch R = 1,1892,552,552,552
BEGIN DESCRIPTION:
MILL CREEK EAST TRIBUTARY 1 4.0
END DESCRIPTION:
XS GIS Cut Line= 3
      3546142.49     10357152.93      3546342.50     10357252.93
      3547018.33     10357554.55
#Sta/Elev= 30
  4565.3  416.62  4683.8  414.03  4778.9  408.73  4847.9  396.24  4876.6  389.55
  4930.8  382.68  4963.7  379.95  4975.0  377.82  4995.2  370.87  4997.9  370.37
  5001.2  370.87  5021.4  372.66  5039.1  372.38  5044.6  375.03  5067.8  378.07
  5143.0  381.81  5189.4  386.45  5235.8  389.87  5241.3  389.32  5264.5  392.20
  5270.3  394.30  5287.8  396.77  5316.4  398.31  5334.2  400.83  5368.5  401.93
  5369.9  402.00  5409.3  402.03  5414.8  400.88  5489.9  397.78  5529.0  398.11
#Mann=5,-1,0
  4565.3    0.16       0  4995.2    0.07       0  5001.2    0.16       0
  5368.5     0.1       0  5369.9    0.16       0
Bank Sta=4995.2,5001.2
Exp/Cntr=0.3,0.1

Type RM Length L Ch R = 1,1340,880,880,880
BEGIN DESCRIPTION:
MILL CREEK EAST TRIBUTARY 1 3.0
END DESCRIPTION:
XS GIS Cut Line= 3
      3546022.09     10357395.55      3546322.07     10357645.54
      3546620.27     10358116.83
#Sta/Elev= 30
  4508.2  417.07  4583.9  415.67  4690.5  410.71  4740.1  404.60  4760.9  398.22
  4789.6  391.92  4818.2  387.22  4824.7  384.14  4832.5  384.89  4839.1  380.66
  4846.7  382.90  4853.4  383.08  4917.8  376.15  4946.4  370.10  4961.7  369.48
  4967.6  370.95  4995.1  367.33  4997.9  366.83  5001.1  367.33  5025.2  369.12
  5040.0  371.70  5061.7  376.29  5207.5  390.10  5244.0  394.74  5265.2  395.77
  5280.4  397.77  5301.6  398.41  5316.9  400.42  5397.5  406.64  5456.4  413.05
#Mann=5,-1,0
  4508.2    0.16       0  4995.1    0.07       0  5001.1    0.16       0
  5040.0     0.1       0  5397.5    0.05       0
Bank Sta=4995.1,5001.1
Exp/Cntr=0.3,0.1

Type RM Length L Ch R = 1,460,0,0,0
BEGIN DESCRIPTION:
MILL CREEK EAST TRIBUTARY 1 1.0
END DESCRIPTION:
XS GIS Cut Line= 3
      3545577.94     10357902.53      3545923.43     10358587.36
      3546072.92     10358687.01
#Sta/Elev= 30
  4553.5  409.58  4571.6  408.73  4577.2  409.48  4593.9  408.34  4599.5  409.12
  4644.1  406.28  4705.4  394.89  4750.0  388.34  4787.7  385.01  4794.6  382.74
  4810.1  380.77  4839.2  375.14  4844.8  375.04  4883.8  369.70  4928.4  365.27
  4973.0  361.84  4986.2  361.83  5020.2  361.41  5023.0  360.91  5026.2  361.41
  5056.5  361.76  5078.9  363.29  5101.2  365.26  5157.3  372.23  5212.7  377.27
  5224.5  380.32  5251.5  381.14  5327.7  388.58  5374.6  392.77  5500.2  403.08
#Mann=7,-1,0
  4553.5    0.16       0  4986.2    0.05       0  5020.2    0.04       0
  5026.2    0.05       0  5251.5    0.16       0  5327.7    0.05       0
  5374.6    0.16       0
Bank Sta=5020.2,5026.2
Exp/Cntr=0.3,0.1

Chan Stop Cuts=-1