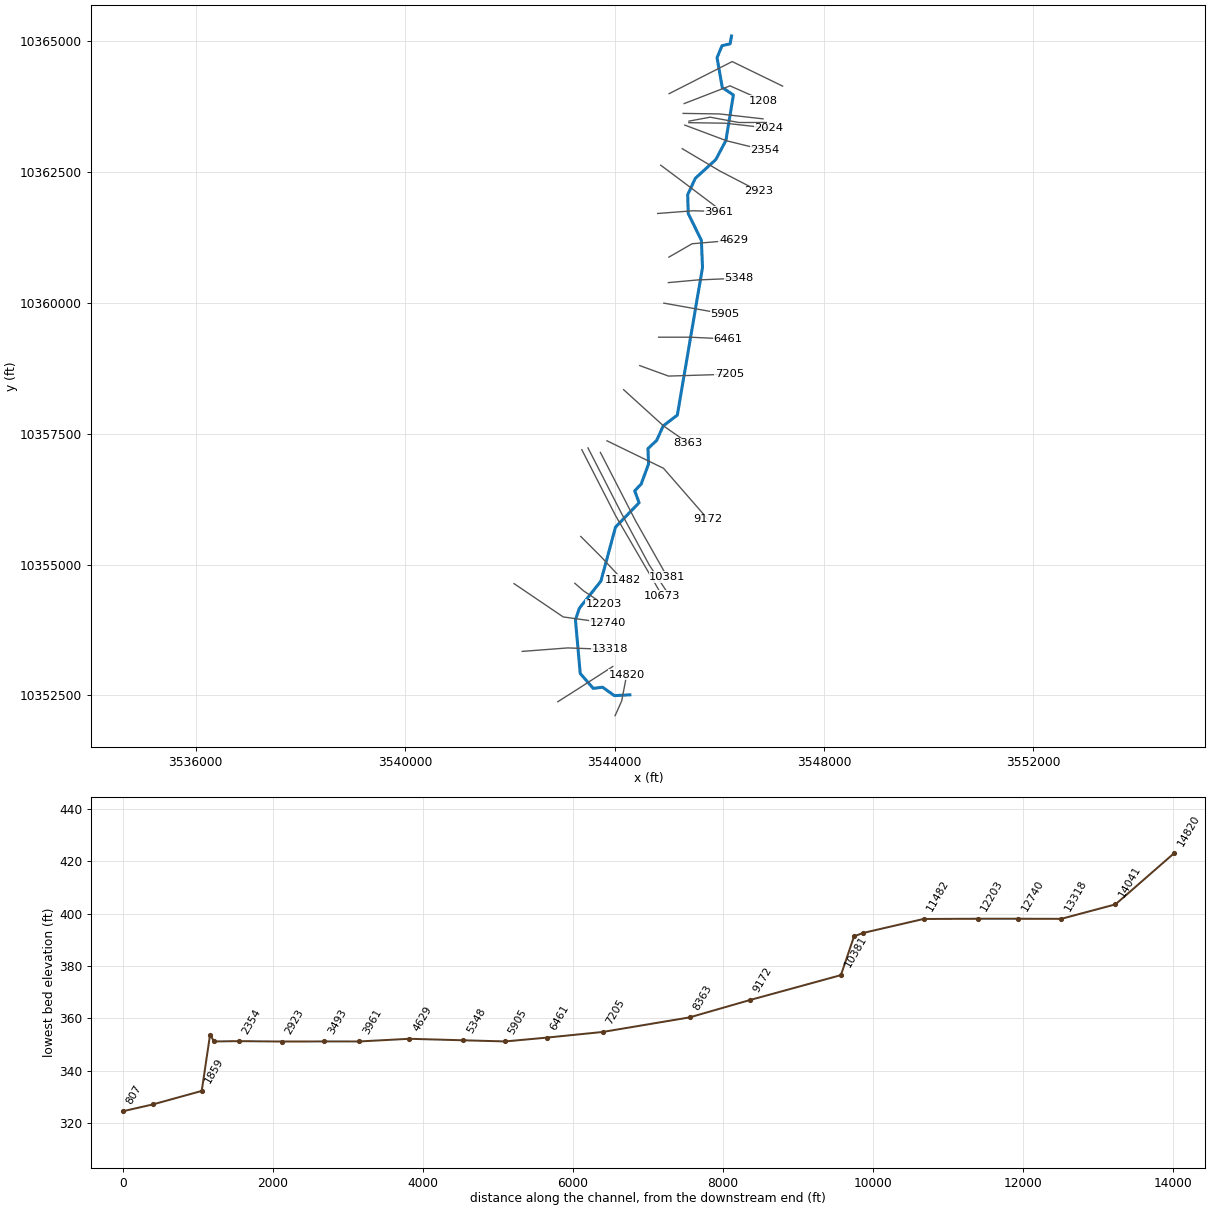
--- MILL CREEK EAST.prj (project) ---

Proj Title=MILL CREEK EAST Base Level Engineering
Current Plan=p01
Default Exp/Contr=0.3,0.1
English Units
Geom File=g01
Flow File=f01
Plan File=p01
BEGIN DESCRIPTION:
MILL CREEK EAST
END DESCRIPTION:

--- MILL CREEK EAST.p01 (plan) ---

Plan Title=Multiple Run
Short Identifier=Multiple
Geom File=g01
Flow File=f01
Subcritical Flow
K Sum by GR= 0
Std Step Tol= 0.01
Critical Tol= 0.01
Num of Std Step Trials= 20
Max Error Tol= 0.3
Flow Tol Ratio= 0.001
Split Flow NTrial= 30
Split Flow Tol= 0.02
Split Flow Ratio= 0.02
Log Output Level= 0
Friction Slope Method= 1
Unsteady Friction Slope Method= 2
Unsteady Bridges Friction Slope Method= 1
Parabolic Critical Depth
Global Vel Dist=  1 , 1 , 1
Global Log Level= 0
CheckData=True
Encroach Param= -1, 0, 0, 0
BEGIN DESCRIPTION:
Multiple Run
END DESCRIPTION:

--- MILL CREEK EAST.f01 (steady flow) ---

Flow Title=Multiple
Number of Profiles=7
Profile Names=10-year,25-year,50-year,1pct_min,100-year,1pct_plu,500-year
River Rch & RM= MILL CREEK EAST,Reach-1,14820
    1145    1599    1980    1789    2420    3272    3617
River Rch & RM= MILL CREEK EAST,Reach-1,12740
    2162    3117    3941    3630    4909    6638    7614
River Rch & RM= MILL CREEK EAST,Reach-1,9172
    2601    3783    4810    4452    6021    8143    9432
River Rch & RM= MILL CREEK EAST,Reach-1,7205
    3316    4859    6211    5772    7805   10556   12322
Boundary for River Rch & Prof#=MILL CREEK EAST,Reach-1,1
Up Type=0
Dn Type=3
Dn Slope=0.005
Boundary for River Rch & Prof#=MILL CREEK EAST,Reach-1,2
Up Type=0
Dn Type=3
Dn Slope=0.005
Boundary for River Rch & Prof#=MILL CREEK EAST,Reach-1,3
Up Type=0
Dn Type=3
Dn Slope=0.005
Boundary for River Rch & Prof#=MILL CREEK EAST,Reach-1,4
Up Type=0
Dn Type=3
Dn Slope=0.005
Boundary for River Rch & Prof#=MILL CREEK EAST,Reach-1,5
Up Type=0
Dn Type=3
Dn Slope=0.005
Boundary for River Rch & Prof#=MILL CREEK EAST,Reach-1,6
Up Type=0
Dn Type=3
Dn Slope=0.005
Boundary for River Rch & Prof#=MILL CREEK EAST,Reach-1,7
Up Type=0
Dn Type=3
Dn Slope=0.005

--- MILL CREEK EAST.g01 (geometry) ---

Geom Title=Existing Conditions

River Reach=MILL CREEK EAST,Reach-1
Reach XY= 30
      3544292.10     10352511.84      3543997.24     10352496.06
      3543770.79     10352657.69      3543593.43     10352634.93
      3543344.53     10352919.57      3543253.28     10353943.38
      3543329.23     10354166.91      3543739.39     10354683.40
      3544018.47     10355714.22      3544468.38     10356180.62
      3544385.21     10356406.87      3544509.28     10356538.82
      3544649.10     10356919.32      3544638.27     10357213.77
      3544805.11     10357371.92      3544929.48     10357647.91
      3545198.62     10357852.72      3545679.84     10360672.01
      3545658.14     10361192.84      3545407.27     10361701.96
      3545396.85     10362063.07      3545542.69     10362375.57
      3545933.71     10362733.25      3546126.78     10363097.90
      3546269.10     10363967.21      3546057.49     10364109.10
      3545957.62     10364679.28      3546052.59     10364908.37
      3546207.10     10364943.53      3546233.36     10365092.23

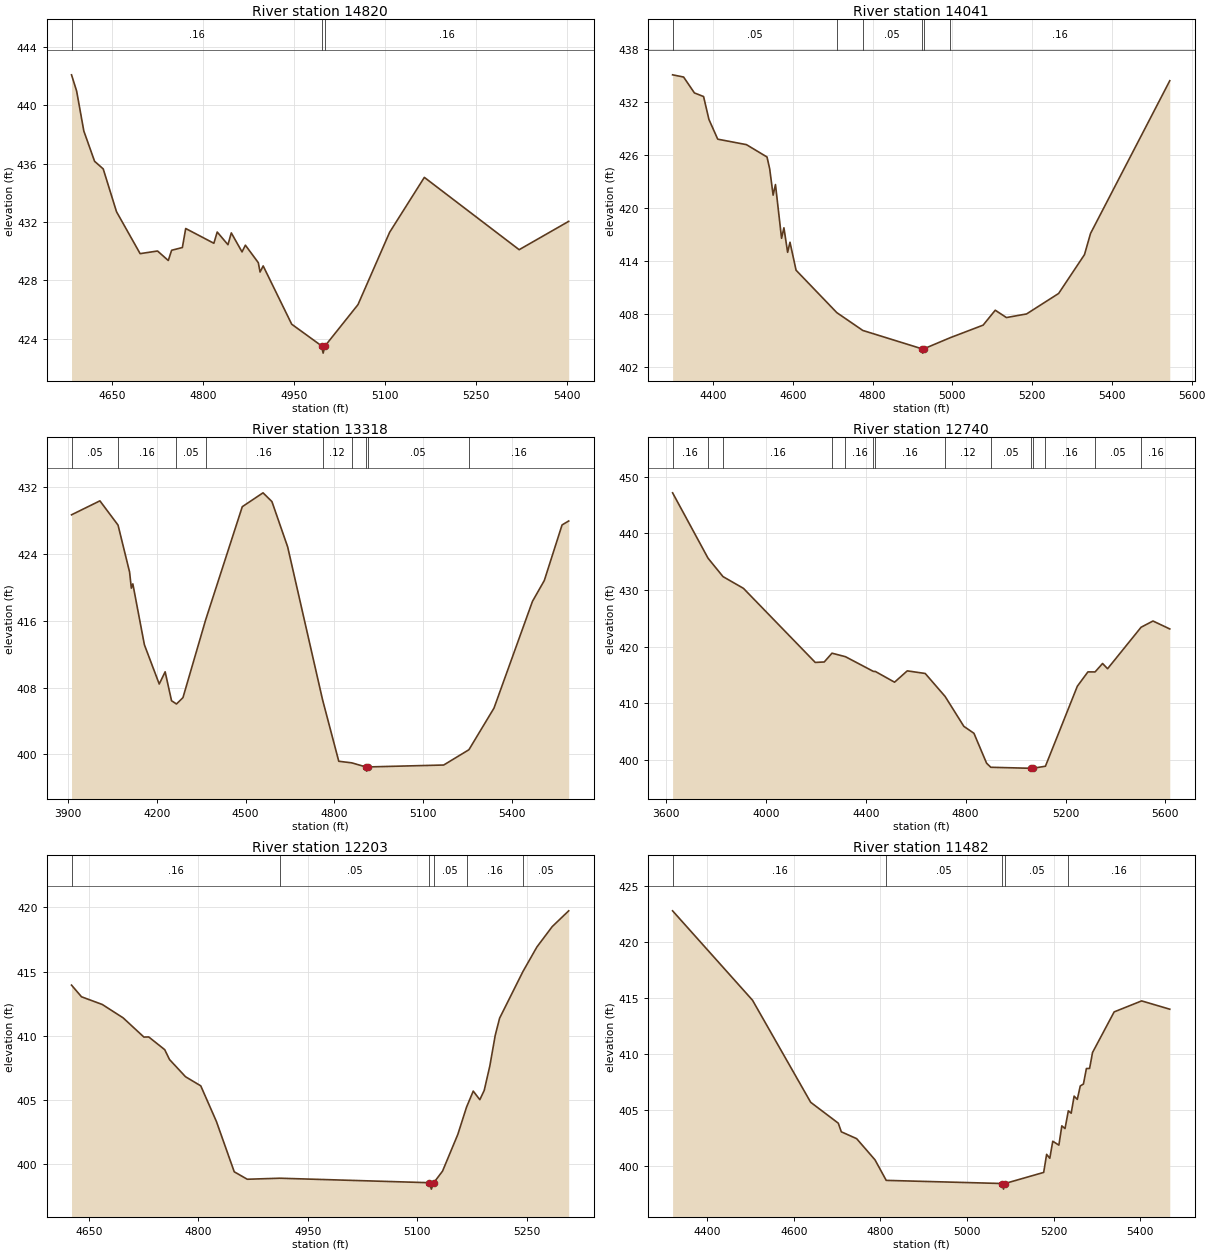
Type RM Length L Ch R = 1,14820,779,779,779
BEGIN DESCRIPTION:
MILL CREEK EAST 30.0
END DESCRIPTION:
XS GIS Cut Line= 3
      3544010.69     10352114.01      3544136.36     10352394.90
      3544232.36     10352897.08
#Sta/Elev= 30
  4583.7  442.07  4592.1  440.96  4604.0  438.22  4621.7  436.15  4635.9  435.63
  4657.8  432.70  4696.7  429.83  4725.4  430.01  4743.1  429.36  4748.6  430.06
  4766.3  430.25  4771.8  431.55  4818.2  430.54  4823.7  431.31  4841.4  430.44
  4846.9  431.25  4864.6  429.95  4870.1  430.41  4891.4  429.21  4894.3  428.57
  4899.4  428.99  4946.4  425.00  4995.5  423.52  4998.2  423.02  5001.5  423.52
  5055.6  426.34  5107.7  431.29  5164.9  435.05  5321.1  430.10  5402.7  432.04
#Mann=3,-1,0
  4583.7    0.16       0  4995.5    0.07       0  5001.5    0.16       0
Bank Sta=4995.5,5001.5
Exp/Cntr=0.3,0.1

Type RM Length L Ch R = 1,14041,723,723,723
BEGIN DESCRIPTION:
MILL CREEK EAST 29.0
END DESCRIPTION:
XS GIS Cut Line= 3
      3542916.54     10352380.12      3543300.96     10352624.08
      3543966.36     10353052.89
#Sta/Elev= 30
  4298.2  435.07  4325.8  434.82  4352.9  433.02  4375.9  432.61  4389.3  430.02
  4411.4  427.78  4483.4  427.16  4535.0  425.76  4541.7  424.42  4550.3  421.44
  4556.2  422.64  4571.5  416.55  4577.4  417.74  4586.7  414.96  4592.6  416.10
  4607.9  412.93  4710.0  408.13  4775.2  406.11  4922.9  404.04  4925.6  403.54
  4928.9  404.04  4994.6  405.29  5077.0  406.71  5107.4  408.40  5135.5  407.57
  5186.0  407.98  5266.4  410.30  5331.2  414.70  5346.4  417.10  5545.1  434.40
#Mann=6,-1,0
  4298.2    0.05       0  4710.0    0.16       0  4775.2    0.05       0
  4922.9    0.07       0  4928.9    0.05       0  4994.6    0.16       0
Bank Sta=4922.9,4928.9
Exp/Cntr=0.3,0.1

Type RM Length L Ch R = 1,13318,578,578,578
BEGIN DESCRIPTION:
MILL CREEK EAST 28.0
END DESCRIPTION:
XS GIS Cut Line= 3
      3542236.41     10353341.19      3543108.75     10353407.72
      3543914.54     10353378.15
#Sta/Elev= 30
  3911.6  428.67  4007.6  430.34  4068.9  427.44  4107.9  421.83  4113.9  419.90
  4118.9  420.41  4158.0  413.13  4208.2  408.43  4228.2  409.89  4249.8  406.43
  4266.5  406.04  4288.4  406.80  4365.3  416.12  4489.0  429.64  4559.2  431.30
  4589.3  430.25  4642.6  424.82  4760.4  406.56  4815.3  399.19  4859.3  399.00
  4906.9  398.51  4909.7  398.01  4912.9  398.51  5170.1  398.74  5255.4  400.57
  5340.2  405.55  5470.3  418.32  5510.3  420.81  5570.4  427.46  5592.8  427.93
#Mann=9,-1,0
  3911.6    0.05       0  4068.9    0.16       0  4266.5    0.05       0
  4365.3    0.16       0  4760.4    0.12       0  4859.3    0.05       0
  4906.9   0.033       0  4912.9    0.05       0  5255.4    0.16       0
Bank Sta=4906.9,4912.9
Exp/Cntr=0.3,0.1

Type RM Length L Ch R = 1,12740,537,537,537
BEGIN DESCRIPTION:
MILL CREEK EAST 27.0
END DESCRIPTION:
XS GIS Cut Line= 3
      3542081.17     10354634.92      3543020.04     10353999.15
      3543868.68     10353881.07
#Sta/Elev= 30
  3626.8  447.18  3768.7  435.64  3828.6  432.39  3910.4  430.32  4198.0  417.24
  4234.0  417.32  4265.1  418.87  4319.0  418.25  4430.6  415.66  4438.8  415.64
  4515.5  413.75  4566.4  415.75  4638.3  415.29  4718.0  411.23  4793.1  405.95
  4833.4  404.73  4883.9  399.46  4900.8  398.73  5061.9  398.55  5064.6  398.05
  5067.9  398.55  5119.6  398.91  5247.4  413.04  5289.8  415.57  5318.4  415.56
  5348.4  417.05  5368.5  416.13  5502.6  423.45  5550.3  424.55  5617.5  423.15
#Mann=14,-1,0
  3626.8    0.16       0  3768.7     0.1       0  3828.6    0.16       0
  4265.1    0.12       0  4319.0    0.16       0  4430.6    0.12       0
  4438.8    0.16       0  4718.0    0.12       0  4900.8    0.05       0
  5061.9   0.033       0  5067.9    0.05       0  5119.6    0.16       0
  5318.4    0.05       0  5502.6    0.16       0
Bank Sta=5061.9,5067.9
Exp/Cntr=0.3,0.1

Type RM Length L Ch R = 1,12203,721,721,721
BEGIN DESCRIPTION:
MILL CREEK EAST 25.0
END DESCRIPTION:
XS GIS Cut Line= 3
      3543242.14     10354641.62      3543411.86     10354494.47
      3543792.14     10354241.62
#Sta/Elev= 30
  4626.1  413.95  4639.8  413.04  4668.3  412.44  4696.8  411.40  4725.3  409.90
  4731.9  409.91  4753.8  408.92  4760.4  408.15  4782.3  406.81  4803.2  406.10
  4824.6  403.33  4849.1  399.40  4866.9  398.82  4911.4  398.90  5116.5  398.55
  5119.2  398.05  5122.5  398.55  5134.5  399.45  5155.5  402.32  5167.4  404.44
  5176.6  405.69  5185.6  405.02  5191.6  405.74  5199.3  407.64  5206.7  410.03
  5212.7  411.37  5244.6  415.00  5263.8  416.92  5284.8  418.51  5307.4  419.74
#Mann=6,-1,0
  4626.1    0.16       0  4911.4    0.05       0  5116.5   0.033       0
  5122.5    0.05       0  5167.4    0.16       0  5244.6    0.05       0
Bank Sta=5116.5,5122.5
Exp/Cntr=0.3,0.1

Type RM Length L Ch R = 1,11482,809,809,809
BEGIN DESCRIPTION:
MILL CREEK EAST 24.0
END DESCRIPTION:
XS GIS Cut Line= 3
      3543355.15     10355535.59      3543755.14     10355135.61
      3544151.11     10354708.89
#Sta/Elev= 30
  4320.2  422.77  4504.7  414.80  4639.0  405.70  4702.7  403.84  4709.7  403.07
  4745.1  402.46  4787.5  400.57  4813.4  398.74  5081.5  398.46  5084.2  397.96
  5087.5  398.46  5176.9  399.45  5183.7  401.06  5191.0  400.71  5197.9  402.23
  5212.0  401.88  5218.8  403.60  5226.2  403.36  5233.8  404.94  5240.4  404.73
  5247.2  406.25  5254.5  405.96  5261.4  407.16  5268.7  407.33  5275.5  408.71
  5282.9  408.72  5289.7  410.14  5339.6  413.76  5403.1  414.74  5468.0  414.00
#Mann=5,-1,0
  4320.2    0.16       0  4813.4    0.05       0  5081.5   0.033       0
  5087.5    0.05       0  5233.8    0.16       0
Bank Sta=5081.5,5087.5
Exp/Cntr=0.3,0.1

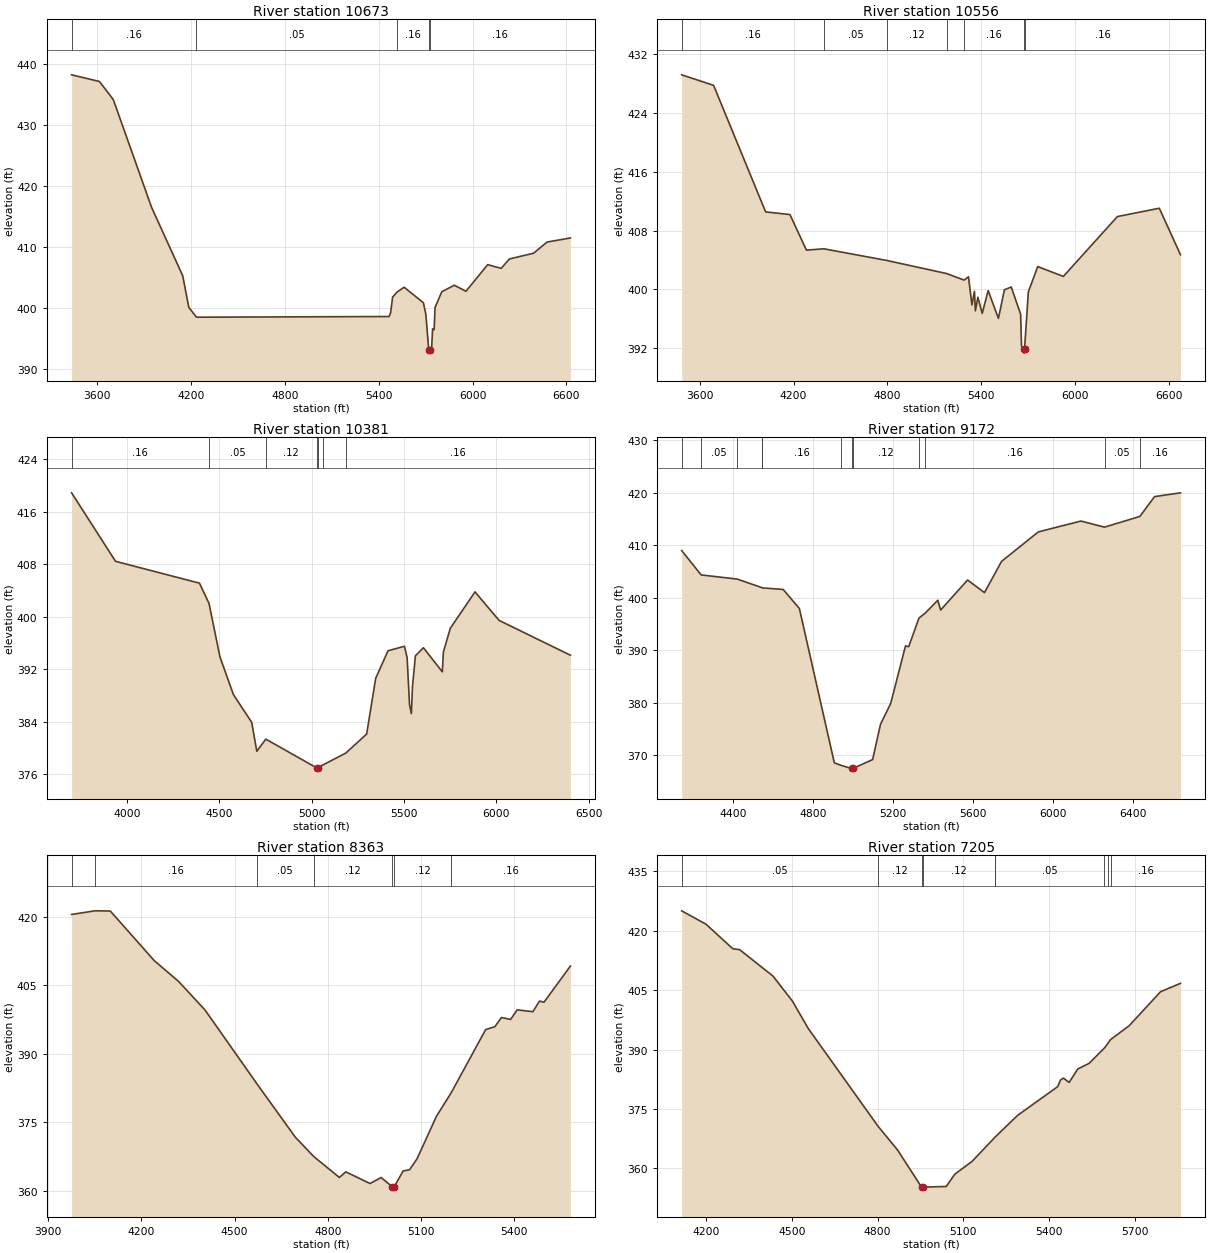
Type RM Length L Ch R = 1,10673,117,117,117
BEGIN DESCRIPTION:
MILL CREEK EAST 22.1
END DESCRIPTION:
XS GIS Cut Line= 3
      3543374.88     10357192.89      3544018.07     10355936.07
      3544912.60     10354398.37
#Sta/Elev= 30
  3434.9  438.29  3612.9  437.20  3701.7  434.22  3946.0  416.56  4145.9  405.28
  4184.7  400.11  4233.8  398.49  5466.1  398.60  5476.0  399.26  5488.2  401.78
  5516.5  402.62  5562.1  403.41  5685.3  400.86  5701.1  398.97  5719.6  393.09
  5722.3  392.59  5725.6  393.09  5738.3  393.50  5744.1  396.57  5754.0  396.43
  5759.8  400.08  5802.9  402.67  5883.1  403.74  5957.6  402.75  6096.6  407.12
  6182.7  406.51  6235.6  408.05  6390.4  409.00  6476.4  410.83  6625.7  411.50
#Mann=5,-1,0
  3434.9    0.16       0  4233.8    0.05       0  5516.5    0.16       0
  5719.6   0.033       0  5725.6    0.16       0
Bank Sta=5719.6,5725.6
Exp/Cntr=0.3,0.1

Type RM Length L Ch R = 1,10556,175,175,175
BEGIN DESCRIPTION:
MILL CREEK EAST 22.0
END DESCRIPTION:
XS GIS Cut Line= 4
      3543493.12     10357226.73      3544136.28     10355969.98
      3544661.51     10354993.23      3545030.82     10354432.26
#Sta/Elev= 30
  3483.9  429.21  3688.2  427.78  4021.3  410.55  4176.8  410.19  4282.2  405.35
  4393.3  405.53  4797.5  403.94  5180.0  402.16  5291.7  401.27  5319.6  401.72
  5341.5  397.89  5357.8  399.75  5363.5  397.09  5379.7  398.94  5407.3  396.74
  5445.4  399.84  5511.2  396.06  5549.3  399.95  5593.1  400.33  5653.2  396.64
  5658.9  392.28  5672.1  391.83  5674.8  391.33  5678.1  391.83  5702.7  399.67
  5762.7  403.11  5926.7  401.77  6272.7  409.92  6540.8  411.05  6676.3  404.73
#Mann=7,-1,0
  3483.9    0.16       0  4393.3    0.05       0  4797.5    0.12       0
  5180.0    0.05       0  5291.7    0.16       0  5672.1    0.07       0
  5678.1    0.16       0
Bank Sta=5672.1,5678.1
Exp/Cntr=0.3,0.1

Type RM Length L Ch R = 1,10381,1209,1209,1209
BEGIN DESCRIPTION:
MILL CREEK EAST 21.0
END DESCRIPTION:
XS GIS Cut Line= 3
      3543729.77     10357141.07      3544402.50     10355832.57
      3545007.92     10354762.01
#Sta/Elev= 30
  3699.2  418.92  3937.1  408.48  4391.7  405.15  4443.2  402.07  4502.6  393.91
  4575.6  388.16  4674.4  383.94  4702.2  379.53  4750.8  381.38  5026.2  377.00
  5029.0  376.50  5032.2  377.00  5059.4  377.43  5183.9  379.25  5297.0  382.15
  5346.0  390.65  5412.8  394.85  5501.9  395.53  5516.2  393.79  5529.3  386.60
  5539.2  385.28  5545.2  389.41  5561.1  394.08  5604.4  395.31  5706.9  391.63
  5712.7  394.67  5750.2  398.28  5883.8  403.82  6014.4  399.47  6400.4  394.17
#Mann=7,-1,0
  3699.2    0.16       0  4443.2    0.05       0  4750.8    0.12       0
  5026.2    0.07       0  5032.2    0.12       0  5059.4    0.05       0
  5183.9    0.16       0
Bank Sta=5026.2,5032.2
Exp/Cntr=0.3,0.1

Type RM Length L Ch R = 1,9172,809,809,809
BEGIN DESCRIPTION:
MILL CREEK EAST 19.0
END DESCRIPTION:
XS GIS Cut Line= 3
      3543855.40     10357362.90      3544934.78     10356838.00
      3545784.96     10355862.14
#Sta/Elev= 30
  4144.5  408.98  4241.9  404.34  4421.8  403.55  4544.7  401.94  4547.2  401.88
  4652.3  401.57  4733.1  397.95  4908.0  368.58  4942.5  368.10  4994.1  367.51
  4996.8  367.01  5000.1  367.51  5099.5  369.21  5139.0  375.94  5189.7  379.87
  5263.9  390.84  5279.9  390.69  5331.3  396.13  5363.3  397.10  5425.3  399.52
  5439.5  397.66  5574.3  403.37  5658.8  400.97  5744.3  406.92  5928.4  412.53
  6141.1  414.59  6259.2  413.43  6435.9  415.47  6509.5  419.24  6639.0  419.96
#Mann=12,-1,0
  4144.5    0.16       0  4241.9    0.05       0  4421.8    0.16       0
  4544.7    0.05       0  4547.2    0.16       0  4942.5    0.12       0
  4994.1    0.07       0  5000.1    0.12       0  5331.3     0.1       0
  5363.3    0.16       0  6259.2    0.05       0  6435.9    0.16       0
Bank Sta=4994.1,5000.1
Exp/Cntr=0.3,0.1

Type RM Length L Ch R = 1,8363,1158,1158,1158
BEGIN DESCRIPTION:
MILL CREEK EAST 17.0
END DESCRIPTION:
XS GIS Cut Line= 3
      3544173.30     10358338.77      3544942.11     10357641.64
      3545407.50     10357318.83
#Sta/Elev= 30
  3975.8  420.50  4050.3  421.30  4100.2  421.26  4242.2  410.35  4319.9  405.84
  4405.0  399.57  4571.1  383.49  4695.0  371.75  4754.5  367.49  4836.9  362.91
  4857.8  364.13  4935.5  361.58  4971.4  362.89  5007.2  360.85  5010.0  360.35
  5013.2  360.85  5042.0  364.32  5062.9  364.61  5086.6  366.97  5149.4  376.33
  5197.1  381.51  5307.4  395.29  5337.2  395.93  5358.1  397.93  5387.8  397.52
  5408.8  399.61  5459.4  399.21  5480.4  401.53  5495.2  401.29  5580.0  409.20
#Mann=7,-1,0
  3975.8    0.05       0  4050.3    0.16       0  4571.1    0.05       0
  4754.5    0.12       0  5007.2    0.07       0  5013.2    0.12       0
  5197.1    0.16       0
Bank Sta=5007.2,5013.2
Exp/Cntr=0.3,0.1

Type RM Length L Ch R = 1,7205,744,744,744
BEGIN DESCRIPTION:
MILL CREEK EAST 15.0
END DESCRIPTION:
XS GIS Cut Line= 3
      3544481.64     10358798.63      3545031.61     10358598.64
      3546191.55     10358634.46
#Sta/Elev= 30
  4114.6  425.04  4200.2  421.64  4293.3  415.48  4317.3  415.24  4434.3  408.56
  4502.2  402.25  4558.0  395.29  4802.1  370.63  4870.4  364.64  4954.2  355.28
  4957.0  354.78  4960.2  355.28  5040.5  355.45  5070.5  358.55  5130.5  361.76
  5212.0  367.95  5212.7  368.00  5290.6  373.42  5430.7  380.66  5440.7  382.36
  5450.7  382.81  5470.7  381.72  5500.7  385.11  5540.7  386.54  5594.1  390.40
  5606.5  391.61  5615.6  392.53  5680.8  396.04  5790.8  404.63  5860.3  406.73
#Mann=9,-1,0
  4114.6    0.05       0  4802.1    0.12       0  4954.2    0.07       0
  4960.2    0.12       0  5212.0    0.16       0  5212.7    0.05       0
  5594.1    0.16       0  5606.5    0.05       0  5615.6    0.16       0
Bank Sta=4954.2,4960.2
Exp/Cntr=0.3,0.1

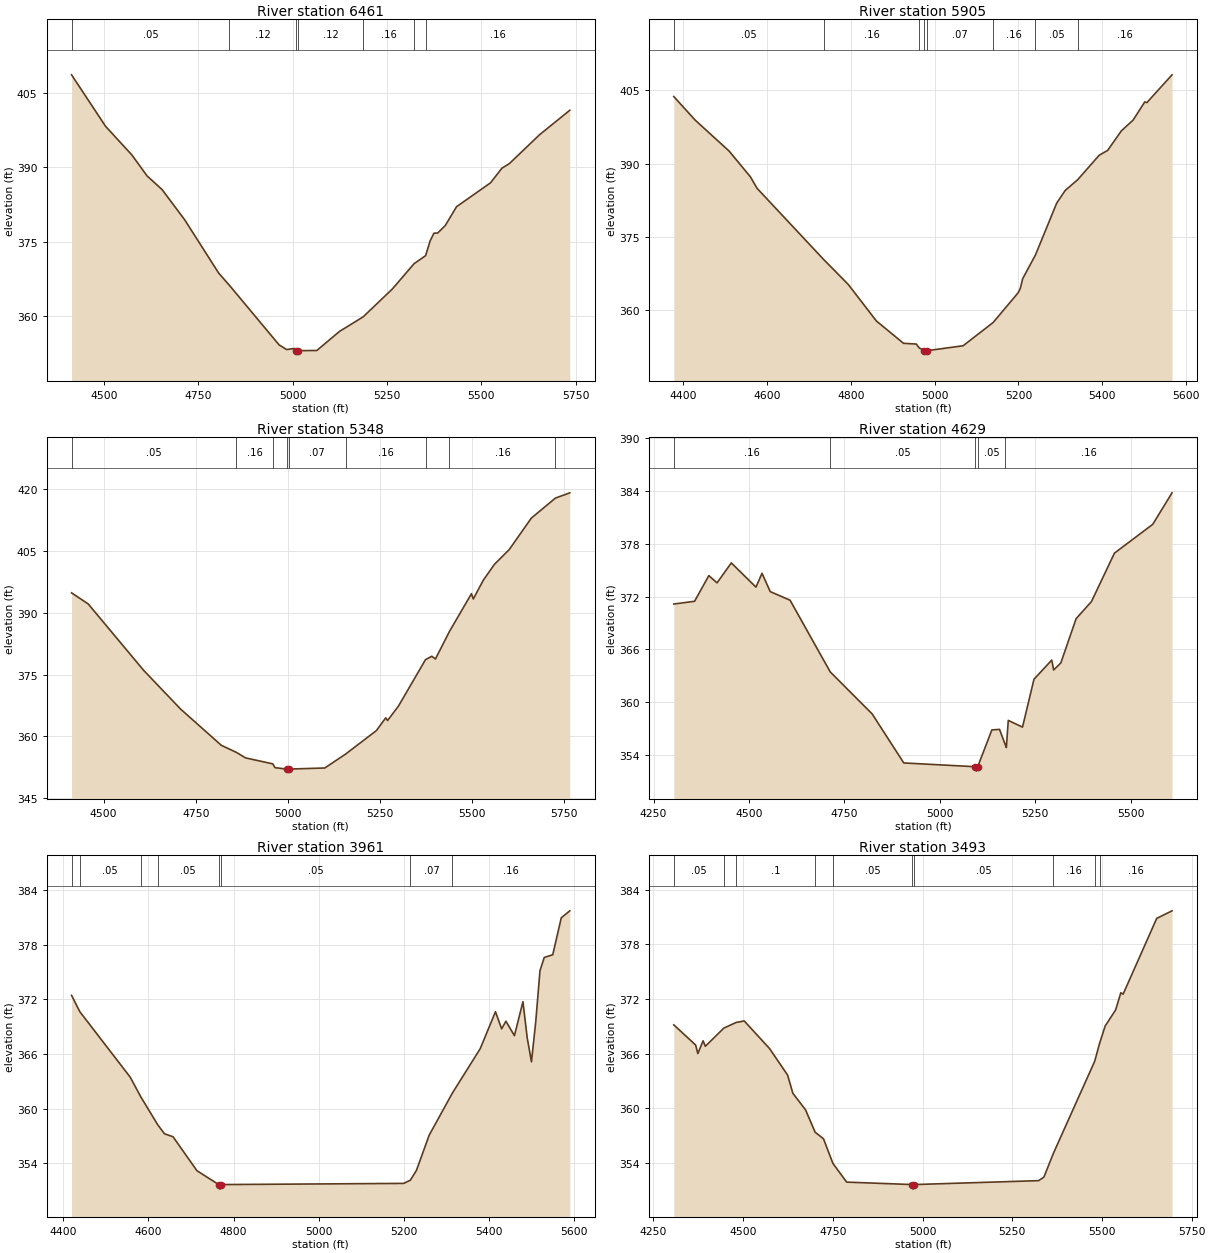
Type RM Length L Ch R = 1,6461,556,556,556
BEGIN DESCRIPTION:
MILL CREEK EAST 13.0
END DESCRIPTION:
XS GIS Cut Line= 3
      3544842.07     10359341.64      3545442.11     10359341.64
      3546161.95     10359307.21
#Sta/Elev= 30
  4413.6  408.63  4503.6  398.28  4573.6  392.49  4613.6  388.30  4653.6  385.53
  4713.6  379.44  4803.6  368.72  4831.3  366.33  4963.6  354.29  4983.6  353.34
  5003.6  353.55  5008.1  353.12  5010.9  352.62  5014.1  353.12  5063.7  353.15
  5123.8  356.99  5186.4  359.91  5263.9  365.53  5321.6  370.63  5352.1  372.24
  5364.0  375.19  5374.0  376.75  5384.1  376.79  5404.1  378.29  5434.1  382.09
  5524.2  386.90  5554.3  389.83  5574.3  390.78  5654.4  396.59  5734.3  401.50
#Mann=7,-1,0
  4413.6    0.05       0  4831.3    0.12       0  5008.1    0.07       0
  5014.1    0.12       0  5186.4    0.16       0  5321.6    0.05       0
  5352.1    0.16       0
Bank Sta=5008.1,5014.1
Exp/Cntr=0.3,0.1

Type RM Length L Ch R = 1,5905,557,557,557
BEGIN DESCRIPTION:
MILL CREEK EAST 12.0
END DESCRIPTION:
XS GIS Cut Line= 3
      3544942.07     10359991.65      3545815.64     10359836.00
      3546113.70     10359786.32
#Sta/Elev= 30
  4377.3  403.72  4428.1  398.91  4509.4  392.55  4560.2  387.27  4576.1  384.92
  4735.5  370.30  4793.8  365.23  4860.9  357.75  4925.8  353.17  4956.3  353.02
  4963.3  352.22  4975.8  351.66  4978.6  351.16  4981.8  351.66  5068.0  352.67
  5139.8  357.44  5199.5  363.54  5204.6  364.44  5210.2  366.40  5240.8  371.28
  5291.5  381.90  5311.7  384.48  5341.7  386.70  5392.8  391.69  5413.1  392.69
  5445.9  396.70  5473.9  398.90  5501.7  402.62  5506.7  402.48  5566.8  408.17
#Mann=8,-1,0
  4377.3    0.05       0  4735.5    0.16       0  4963.3    0.07       0
  4975.8    0.07       0  4981.8    0.07       0  5139.8    0.16       0
  5240.8    0.05       0  5341.7    0.16       0
Bank Sta=4975.8,4981.8
Exp/Cntr=0.3,0.1

Type RM Length L Ch R = 1,5348,719,719,719
BEGIN DESCRIPTION:
MILL CREEK EAST 11.0
END DESCRIPTION:
XS GIS Cut Line= 3
      3545027.29     10360383.85      3545577.32     10360433.86
      3546376.39     10360467.88
#Sta/Elev= 30
  4413.1  394.80  4458.1  392.13  4608.7  376.02  4709.1  366.62  4819.6  357.84
  4860.4  356.13  4885.3  354.80  4959.2  353.35  4965.3  352.42  4997.2  352.09
  5000.0  351.59  5003.2  352.09  5100.3  352.35  5156.7  355.72  5240.4  361.42
  5265.7  364.51  5270.7  363.85  5300.5  367.40  5373.6  378.61  5390.6  379.43
  5400.6  378.78  5438.5  385.43  5498.3  394.60  5503.3  393.32  5530.7  397.91
  5560.7  401.72  5600.8  405.29  5660.8  412.92  5726.1  417.77  5765.2  419.05
#Mann=9,-1,0
  4413.1    0.05       0  4860.4    0.16       0  4959.2    0.07       0
  4997.2    0.07       0  5003.2    0.07       0  5156.7    0.16       0
  5373.6    0.05       0  5438.5    0.16       0  5726.1    0.05       0
Bank Sta=4997.2,5003.2
Exp/Cntr=0.3,0.1

Type RM Length L Ch R = 1,4629,668,668,668
BEGIN DESCRIPTION:
MILL CREEK EAST 9.0
END DESCRIPTION:
XS GIS Cut Line= 3
      3545038.17     10360870.49      3545480.85     10361125.68
      3546272.49     10361193.39
#Sta/Elev= 30
  4302.9  371.15  4357.3  371.46  4394.7  374.38  4416.2  373.55  4453.6  375.82
  4518.2  373.07  4534.0  374.64  4555.6  372.56  4607.6  371.58  4712.8  363.44
  4822.6  358.67  4905.5  353.10  5093.2  352.67  5095.9  352.17  5099.2  352.67
  5136.3  356.85  5156.4  356.91  5171.2  355.20  5174.3  354.85  5179.3  357.93
  5216.6  357.17  5246.7  362.61  5293.2  364.78  5298.2  363.66  5317.0  364.46
  5357.1  369.49  5397.3  371.43  5457.5  376.93  5557.8  380.20  5608.4  383.78
#Mann=5,-1,0
  4302.9    0.16       0  4712.8    0.05       0  5093.2   0.033       0
  5099.2    0.05       0  5171.2    0.16       0
Bank Sta=5093.2,5099.2
Exp/Cntr=0.3,0.1

Type RM Length L Ch R = 1,3961,468,468,468
BEGIN DESCRIPTION:
MILL CREEK EAST 8.0
END DESCRIPTION:
XS GIS Cut Line= 3
      3544824.61     10361703.81      3545496.48     10361755.89
      3545992.09     10361741.64
#Sta/Elev= 30
  4419.7  372.43  4439.0  370.64  4557.6  363.43  4582.1  361.29  4622.1  358.21
  4637.8  357.23  4657.9  356.90  4714.1  353.17  4765.2  351.65  4768.0  351.15
  4771.2  351.65  5199.3  351.78  5215.0  352.13  5229.3  353.20  5259.3  357.08
  5313.9  361.71  5379.3  366.59  5414.9  370.63  5429.4  368.75  5439.4  369.59
  5459.4  368.00  5479.4  371.73  5489.4  367.77  5499.4  365.13  5509.4  369.51
  5519.4  375.14  5529.4  376.59  5549.4  376.89  5569.4  380.95  5589.4  381.71
#Mann=8,-1,0
  4419.7    0.16       0  4439.0    0.05       0  4582.1    0.16       0
  4622.1    0.05       0  4765.2   0.033       0  4771.2    0.05       0
  5215.0    0.07       0  5313.9    0.16       0
Bank Sta=4765.2,4771.2
Exp/Cntr=0.3,0.1

Type RM Length L Ch R = 1,3493,570,570,570
BEGIN DESCRIPTION:
MILL CREEK EAST 7.0
END DESCRIPTION:
XS GIS Cut Line= 3
      3544881.93     10362625.66      3545335.02     10362287.14
      3545992.14     10361791.61
#Sta/Elev= 30
  4306.7  369.17  4367.5  366.96  4373.7  366.02  4388.3  367.42  4394.6  366.82
  4446.4  368.82  4480.4  369.43  4503.0  369.60  4573.8  366.56  4623.9  363.66
  4638.5  361.67  4673.9  359.85  4700.6  357.40  4723.9  356.68  4750.1  353.98
  4788.5  351.93  4970.9  351.66  4973.7  351.16  4976.9  351.66  5323.7  352.09
  5338.2  352.48  5364.7  355.09  5479.7  365.17  5493.4  367.14  5508.9  369.04
  5538.1  370.81  5552.6  372.69  5558.9  372.53  5652.6  380.84  5695.3  381.67
#Mann=10,-1,0
  4306.7    0.05       0  4446.4    0.16       0  4480.4     0.1       0
  4700.6    0.16       0  4750.1    0.05       0  4970.9   0.033       0
  4976.9    0.05       0  5364.7    0.16       0  5479.7    0.07       0
  5493.4    0.16       0
Bank Sta=4970.9,4976.9
Exp/Cntr=0.3,0.1

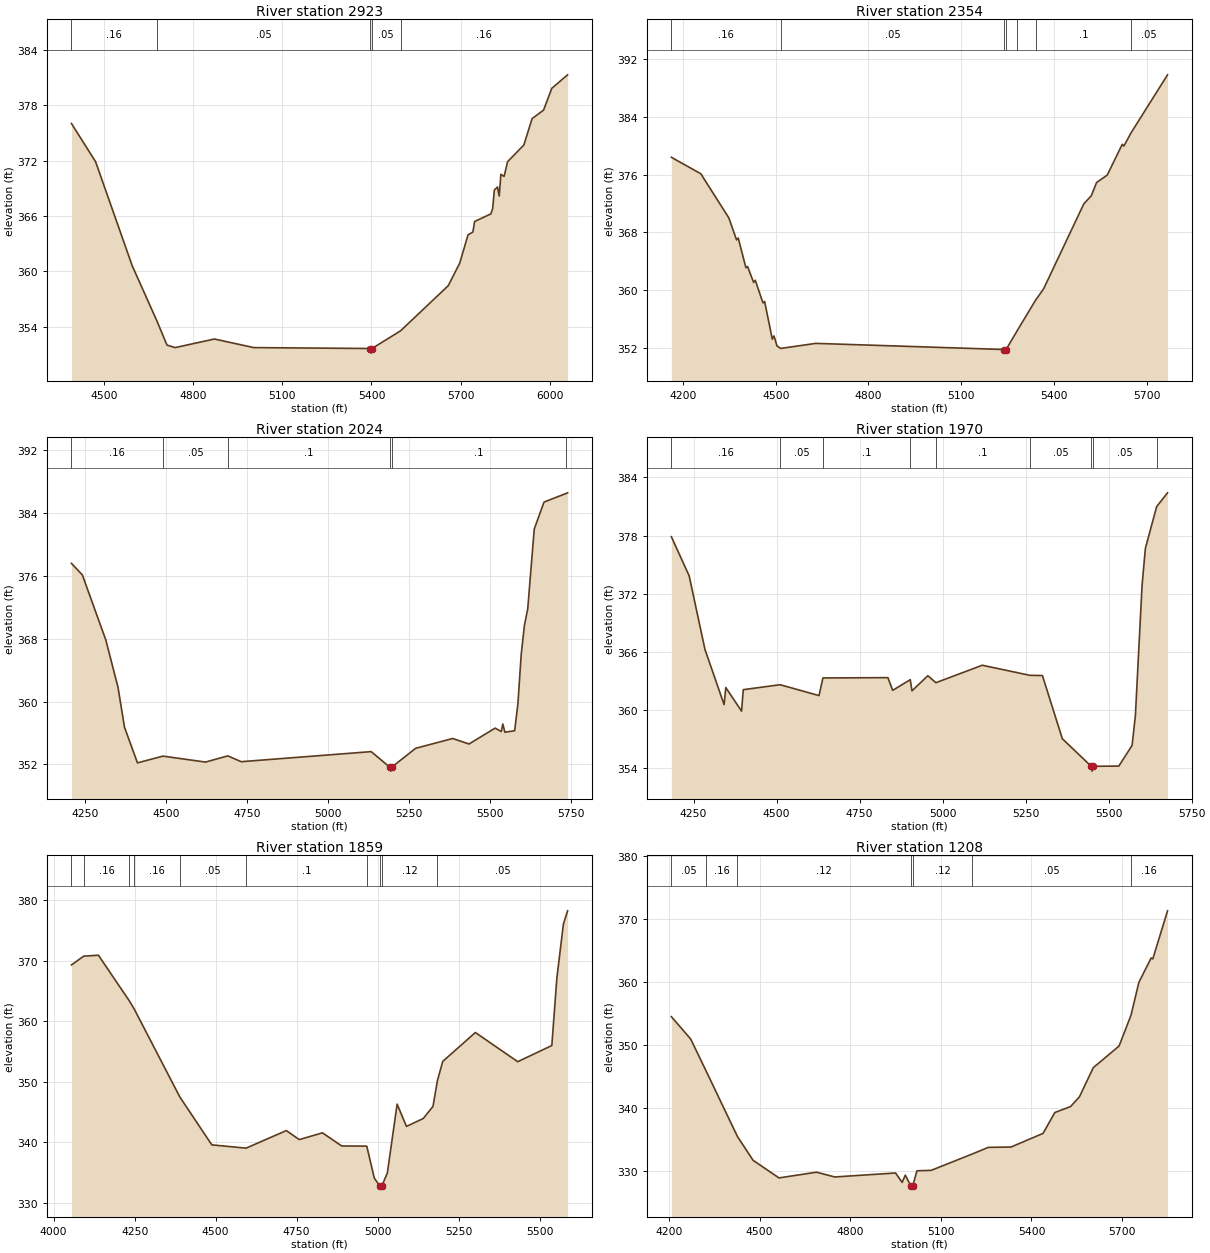
Type RM Length L Ch R = 1,2923,569,569,569
BEGIN DESCRIPTION:
MILL CREEK EAST 5.0
END DESCRIPTION:
XS GIS Cut Line= 3
      3545292.07     10362941.66      3546017.31     10362511.10
      3546751.70     10362130.88
#Sta/Elev= 30
  4389.9  376.03  4471.3  371.87  4594.5  360.59  4677.2  354.64  4711.5  351.99
  4738.8  351.72  4871.2  352.65  5003.7  351.72  5395.6  351.62  5398.4  351.12
  5401.6  351.62  5497.9  353.54  5658.6  358.44  5697.3  360.90  5725.0  363.95
  5741.5  364.26  5747.2  365.40  5801.8  366.22  5808.0  366.80  5813.6  368.81
  5824.3  369.14  5830.1  368.17  5835.7  370.52  5846.6  370.29  5858.1  371.88
  5913.0  373.70  5940.8  376.56  5979.4  377.48  6007.2  379.85  6060.3  381.31
#Mann=5,-1,0
  4389.9    0.16       0  4677.2    0.05       0  5395.6   0.033       0
  5401.6    0.05       0  5497.9    0.16       0
Bank Sta=5395.6,5401.6
Exp/Cntr=0.3,0.1

Type RM Length L Ch R = 1,2354,330,330,330
BEGIN DESCRIPTION:
MILL CREEK EAST 4.0
END DESCRIPTION:
XS GIS Cut Line= 3
      3545342.10     10363391.65      3546142.11     10363091.64
      3546871.43     10362912.15
#Sta/Elev= 30
  4162.2  378.39  4257.4  376.11  4348.2  369.99  4373.1  366.95  4378.5  367.21
  4403.4  363.09  4408.7  363.27  4428.3  361.06  4433.7  361.36  4458.6  358.22
  4463.9  358.42  4488.8  353.20  4494.2  353.65  4504.0  352.26  4516.0  351.92
  4629.5  352.62  5239.4  351.77  5242.1  351.27  5245.4  351.77  5282.1  354.44
  5341.0  358.62  5366.8  360.18  5496.7  371.93  5521.2  373.08  5538.2  374.90
  5572.7  375.93  5621.2  380.19  5626.4  379.94  5649.3  381.75  5767.7  389.81
#Mann=7,-1,0
  4162.2    0.16       0  4516.0    0.05       0  5239.4   0.033       0
  5245.4    0.05       0  5282.1    0.16       0  5341.0     0.1       0
  5649.3    0.05       0
Bank Sta=5239.4,5245.4
Exp/Cntr=0.3,0.1

Type RM Length L Ch R = 1,2024,54,54,54
BEGIN DESCRIPTION:
MILL CREEK EAST 3.2
END DESCRIPTION:
XS GIS Cut Line= 3
      3545418.40     10363438.18      3546116.27     10363427.77
      3546944.43     10363334.01
#Sta/Elev= 30
  4207.3  377.57  4241.0  376.09  4313.3  367.83  4351.0  361.80  4371.0  356.73
  4411.0  352.20  4489.7  353.06  4621.1  352.30  4689.9  353.09  4731.1  352.35
  5132.5  353.63  5189.9  351.65  5192.7  351.15  5195.9  351.65  5269.6  354.05
  5384.1  355.30  5434.4  354.60  5515.0  356.62  5533.8  356.19  5538.8  357.14
  5545.1  356.10  5575.3  356.29  5585.4  359.76  5595.5  365.98  5605.5  369.70
  5615.6  371.77  5635.7  381.92  5665.9  385.36  5732.7  386.44  5738.7  386.54
#Mann=6,-1,0
  4207.3    0.16       0  4489.7    0.05       0  4689.9     0.1       0
  5189.9    0.07       0  5195.9     0.1       0  5732.7    0.16       0
Bank Sta=5189.9,5195.9
Exp/Cntr=0.3,0.1

Type RM Length L Ch R = 1,1970,111,111,111
BEGIN DESCRIPTION:
MILL CREEK EAST 3.1
END DESCRIPTION:
XS GIS Cut Line= 4
      3545421.23     10363467.43      3545824.92     10363542.96
      3546374.40     10363441.40      3546898.82     10363441.40
#Sta/Elev= 30
  4183.4  377.88  4236.9  373.85  4284.4  366.27  4342.1  360.57  4347.2  362.33
  4394.7  359.90  4399.8  362.11  4510.8  362.62  4627.9  361.50  4639.7  363.32
  4835.3  363.35  4849.8  362.04  4902.7  363.14  4907.8  361.99  4955.6  363.55
  4979.9  362.83  5119.5  364.63  5262.7  363.59  5300.6  363.57  5360.6  357.05
  5447.6  354.21  5450.3  353.71  5453.6  354.21  5530.6  354.23  5570.6  356.36
  5580.6  359.46  5600.6  372.83  5610.6  376.68  5644.6  380.99  5677.3  382.41
#Mann=9,-1,0
  4183.4    0.16       0  4510.8    0.05       0  4639.7     0.1       0
  4902.7    0.12       0  4979.9     0.1       0  5262.7    0.05       0
  5447.6    0.07       0  5453.6    0.05       0  5644.6    0.16       0
Bank Sta=5447.6,5453.6
Exp/Cntr=0.3,0.1

Type RM Length L Ch R = 1,1859,651,651,651
BEGIN DESCRIPTION:
MILL CREEK EAST 3.0
END DESCRIPTION:
XS GIS Cut Line= 3
      3545308.98     10363615.27      3546006.89     10363604.85
      3546835.01     10363511.10
#Sta/Elev= 30
  4055.0  369.27  4092.7  370.72  4138.1  370.88  4233.1  363.38  4248.5  362.01
  4389.3  347.48  4488.2  339.55  4594.0  339.01  4718.2  341.91  4758.2  340.42
  4829.8  341.54  4889.1  339.37  4966.5  339.34  4989.7  334.08  5006.8  332.74
  5009.6  332.24  5012.8  332.74  5030.0  334.90  5060.2  346.28  5089.0  342.60
  5140.7  343.90  5170.9  345.90  5184.6  350.18  5201.1  353.34  5301.7  358.11
  5432.5  353.29  5537.7  355.96  5553.3  367.11  5573.4  376.01  5586.4  378.21
#Mann=10,-1,0
  4055.0    0.05       0  4092.7    0.16       0  4233.1    0.05       0
  4248.5    0.16       0  4389.3    0.05       0  4594.0     0.1       0
  4966.5    0.12       0  5006.8    0.07       0  5012.8    0.12       0
  5184.6    0.05       0
Bank Sta=5006.8,5012.8
Exp/Cntr=0.3,0.1

Type RM Length L Ch R = 1,1208,401,401,401
BEGIN DESCRIPTION:
MILL CREEK EAST 2.0
END DESCRIPTION:
XS GIS Cut Line= 3
      3545329.78     10363802.75      3546204.81     10364141.31
      3546848.86     10363855.64
#Sta/Elev= 30
  4207.7  354.46  4271.5  350.92  4322.0  345.91  4426.3  335.45  4478.3  331.66
  4564.0  328.87  4688.5  329.78  4748.4  329.02  4950.0  329.65  4971.8  328.16
  4982.2  329.31  5000.7  327.59  5003.4  327.09  5006.7  327.59  5020.9  330.00
  5068.0  330.07  5204.7  332.68  5257.0  333.72  5332.3  333.77  5438.4  335.94
  5477.4  339.25  5529.4  340.19  5558.7  341.73  5604.7  346.37  5690.0  349.80
  5729.6  354.69  5755.6  359.90  5796.3  363.78  5801.8  363.63  5850.5  371.26
#Mann=7,-1,0
  4207.7    0.05       0  4322.0    0.16       0  4426.3    0.12       0
  5000.7    0.07       0  5006.7    0.12       0  5204.7    0.05       0
  5729.6    0.16       0
Bank Sta=5000.7,5006.7
Exp/Cntr=0.3,0.1

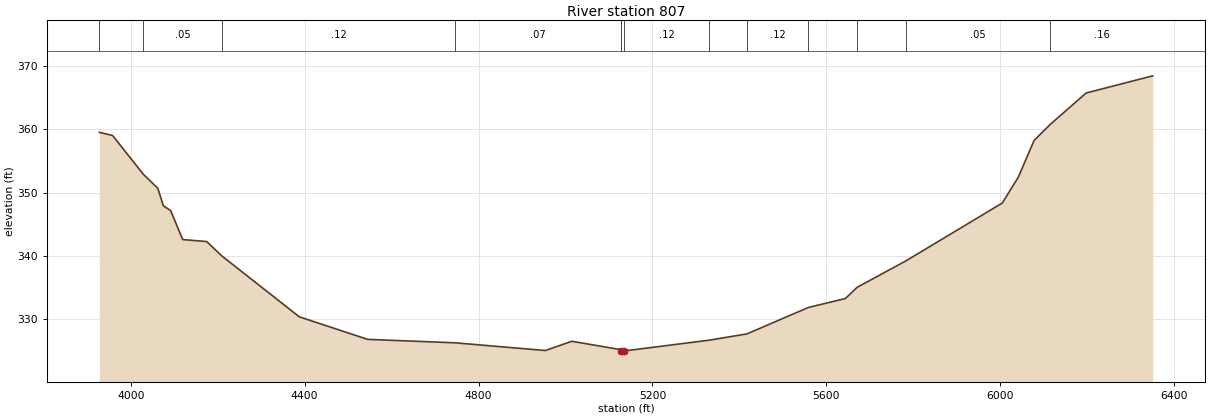
Type RM Length L Ch R = 1,807,0,0,0
BEGIN DESCRIPTION:
MILL CREEK EAST 1.0
END DESCRIPTION:
XS GIS Cut Line= 3
      3545042.15     10363991.66      3546246.48     10364604.85
      3547210.06     10364136.08
#Sta/Elev= 30
  3927.7  359.51  3958.2  359.01  4028.9  352.88  4062.3  350.66  4075.0  347.90
  4091.7  347.15  4119.5  342.57  4174.5  342.26  4209.8  339.97  4387.7  330.37
  4544.8  326.81  4745.3  326.27  4953.5  325.05  5014.6  326.51  5126.8  325.19
  5128.4  324.98  5131.1  324.48  5134.4  324.98  5330.3  326.68  5417.1  327.67
  5558.7  331.85  5643.8  333.26  5670.8  335.03  5782.8  339.20  6004.6  348.34
  6041.6  352.44  6077.8  358.23  6115.5  360.79  6197.3  365.71  6350.7  368.43
#Mann=13,-1,0
  3927.7    0.16       0  4028.9    0.05       0  4209.8    0.12       0
  4745.3    0.07       0  5126.8    0.12       0  5128.4    0.07       0
  5134.4    0.12       0  5330.3    0.16       0  5417.1    0.12       0
  5558.7    0.16       0  5670.8    0.12       0  5782.8    0.05       0
  6115.5    0.16       0
Bank Sta=5128.4,5134.4
Exp/Cntr=0.3,0.1

Chan Stop Cuts=-1