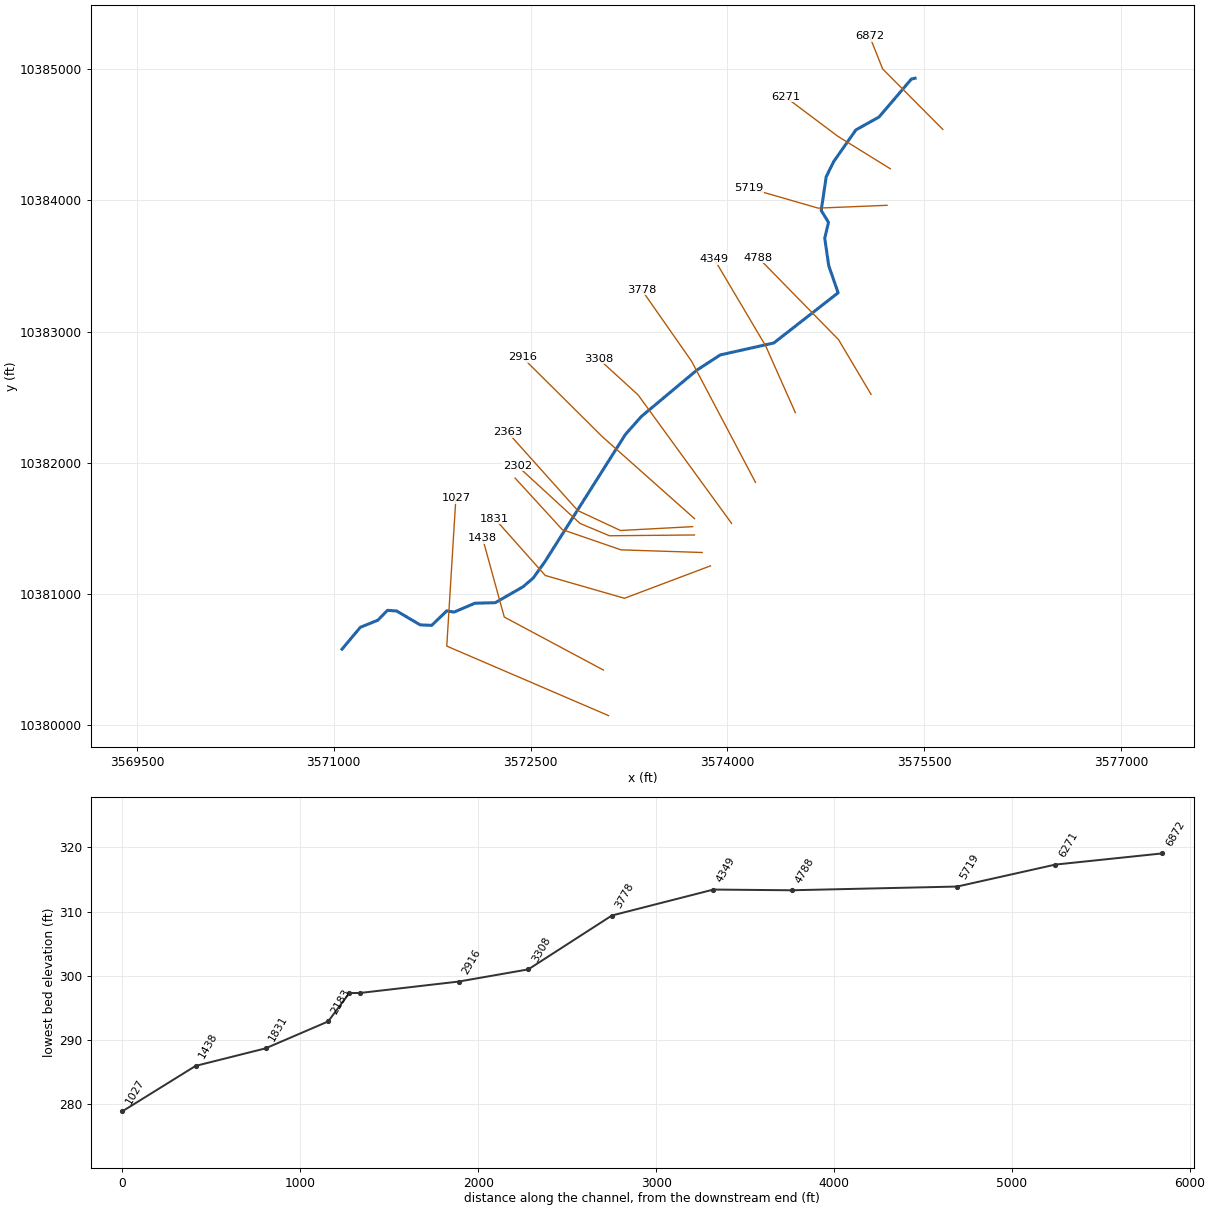
--- MILLER BRANCH.prj (project) ---

Proj Title=MILLER BRANCH Base Level Engineering
Current Plan=p01
Default Exp/Contr=0.3,0.1
English Units
Geom File=g01
Flow File=f01
Plan File=p01
Y Axis Title=Elevation
X Axis Title(PF)=Main Channel Distance
X Axis Title(XS)=Station
BEGIN DESCRIPTION:
MILLER BRANCH
END DESCRIPTION:
DSS Export Rating Curves= 0
DSS Export Rating Curve Sorted= 0
DSS Export Volume Flow Curves= 0
DXF OffsetX= 0
DXF OffsetY= 0
DXF ScaleX= 1
DXF ScaleY= 10

--- MILLER BRANCH.p01 (plan) ---

Plan Title=Multiple Run
Short Identifier=Multiple
Geom File=g01
Flow File=f01
Subcritical Flow
K Sum by GR= 0
Std Step Tol= 0.01
Critical Tol= 0.01
Num of Std Step Trials= 20
Max Error Tol= 0.3
Flow Tol Ratio= 0.001
Split Flow NTrial= 30
Split Flow Tol= 0.02
Split Flow Ratio= 0.02
Log Output Level= 0
Friction Slope Method= 1
Unsteady Friction Slope Method= 2
Unsteady Bridges Friction Slope Method= 1
Parabolic Critical Depth
Global Vel Dist=  1 , 1 , 1
Global Log Level= 0
CheckData=True
Encroach Param= -1, 0, 0, 0
BEGIN DESCRIPTION:
Multiple Run
END DESCRIPTION:

--- MILLER BRANCH.f01 (steady flow) ---

Flow Title=Multiple
Number of Profiles=7
Profile Names=10-year,25-year,50-year,1pct_min,100-year,1pct_plu,500-year
River Rch & RM= MILLER BRANCH,Reach-1,6872
    1785    2559    3226    2966    4011    5424    6185
Boundary for River Rch & Prof#=MILLER BRANCH,Reach-1,1
Up Type=0
Dn Type=3
Dn Slope=0.005
Boundary for River Rch & Prof#=MILLER BRANCH,Reach-1,2
Up Type=0
Dn Type=3
Dn Slope=0.005
Boundary for River Rch & Prof#=MILLER BRANCH,Reach-1,3
Up Type=0
Dn Type=3
Dn Slope=0.005
Boundary for River Rch & Prof#=MILLER BRANCH,Reach-1,4
Up Type=0
Dn Type=3
Dn Slope=0.005
Boundary for River Rch & Prof#=MILLER BRANCH,Reach-1,5
Up Type=0
Dn Type=3
Dn Slope=0.005
Boundary for River Rch & Prof#=MILLER BRANCH,Reach-1,6
Up Type=0
Dn Type=3
Dn Slope=0.005
Boundary for River Rch & Prof#=MILLER BRANCH,Reach-1,7
Up Type=0
Dn Type=3
Dn Slope=0.005

--- MILLER BRANCH.g01 (geometry) ---

Geom Title=Existing Conditions
Program Version=4.10

River Reach=MILLER BRANCH   ,Reach-1
Reach XY= 30
      3575430.66     10384931.86      3575402.82     10384925.24
      3575155.73     10384635.68      3574979.83     10384537.81
       3574811.8     10384298.18      3574753.64       10384181.
      3574715.45     10383924.05        3574771.     10383832.91
      3574742.36     10383713.11      3574772.74     10383503.04
      3574844.35     10383296.43      3574354.12     10382913.95
      3573946.13      10382822.8      3573766.01     10382705.61
      3573345.01     10382354.05      3573223.48     10382217.33
      3572607.78     10381244.04       3572520.8     10381122.68
       3572443.2     10381056.02      3572231.74     10380934.66
      3572076.01      10380930.5      3571916.29     10380862.79
      3571862.12     10380872.68      3571747.02     10380761.75
      3571659.52     10380765.39      3571480.35     10380871.12
      3571409.52     10380876.33       3571336.6     10380801.33
      3571203.13     10380747.03      3571063.37      10380580.4

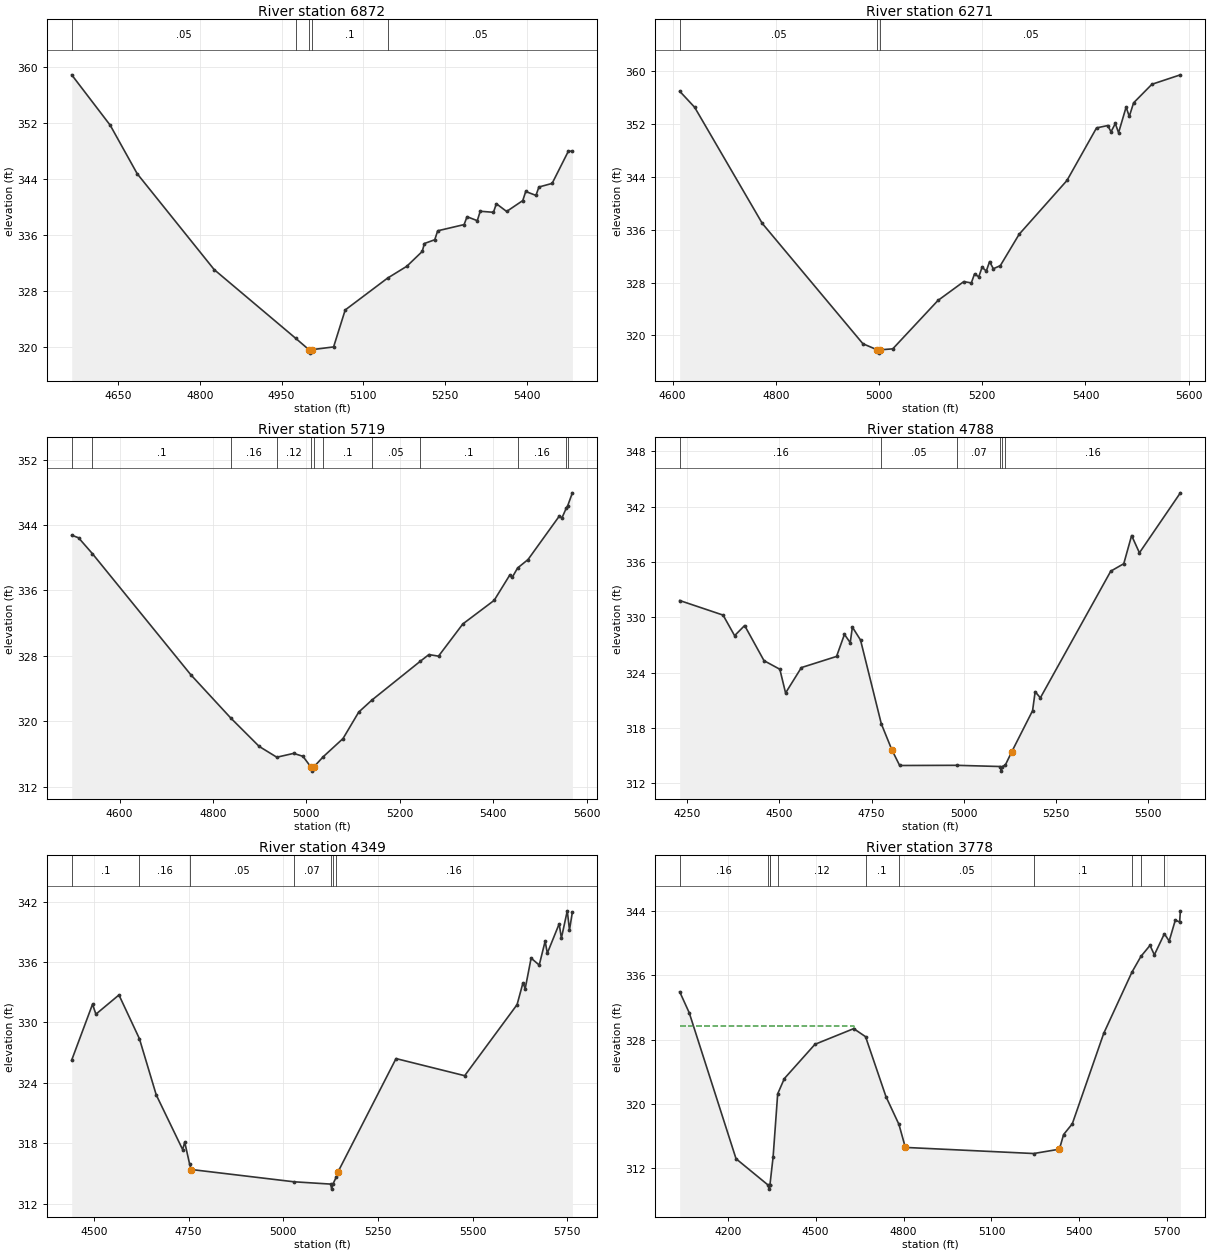
Type RM Length L Ch R = 1 ,6872    ,601,601,601
BEGIN DESCRIPTION:
MILLER BRANCH 16.0
END DESCRIPTION:
XS GIS Cut Line= 3
      3575642.11     10384541.64      3575183.77     10385002.41
      3575083.76     10385252.44
#Sta/Elev= 30
  4564.7  358.93  4635.4  351.71  4684.9  344.77  4826.3  331.03  4976.1  321.18
  5000.1  319.57  5002.8  319.07  5006.1  319.57  5045.5  319.96  5066.8  325.25
  5144.5  329.81  5179.9  331.51  5208.2  333.63  5212.2  334.77  5231.2  335.31
  5236.6  336.59  5285.1  337.48  5290.5  338.61  5309.3  338.04  5314.7  339.39
    5339  339.24  5344.3  340.47  5363.2  339.36  5392.8  340.92  5398.2  342.22
    5417  341.66  5422.4  342.86  5446.7  343.38  5476.3  347.96  5483.9  348.02
#Mann= 5 ,-1 , 0
  4564.7     .05       0  4976.1      .1       0  5000.1     .07       0
  5006.1      .1       0  5144.5     .05       0
Bank Sta=5000.1,5006.1
XS Rating Curve= 0 ,0
Exp/Cntr=0.3,0.1

Type RM Length L Ch R = 1 ,6271    ,552,552,552
BEGIN DESCRIPTION:
MILLER BRANCH 14.0
END DESCRIPTION:
XS GIS Cut Line= 3
      3575242.11     10384241.64      3574842.11     10384489.21
      3574442.13      10384789.2
#Sta/Elev= 30
  4613.6  356.95  4642.6  354.52  4773.7  336.95  4968.7  318.75  4996.5  317.83
  4999.2  317.33  5002.5  317.83  5026.6  317.98  5114.2   325.3  5164.2  328.15
  5178.8  327.95    5185   329.3  5193.3  328.87  5199.6  330.32  5207.9  329.75
  5214.2  331.18  5221.5   330.1    5235  330.56  5271.5  335.31  5364.2  343.45
  5421.5   351.4  5443.3  351.76  5449.6  350.81  5457.9  352.07  5464.2  350.67
  5478.8  354.54    5485  353.14  5493.3  355.19  5528.8     358    5584  359.43
#Mann= 3 ,-1 , 0
  4613.6     .05       0  4996.5     .03       0  5002.5     .05       0
Bank Sta=4996.5,5002.5
XS Rating Curve= 0 ,0
Exp/Cntr=0.3,0.1

Type RM Length L Ch R = 1 ,5719    ,931,931,931
BEGIN DESCRIPTION:
MILLER BRANCH 13.0
END DESCRIPTION:
XS GIS Cut Line= 3
       3575216.8     10383963.11      3574692.11     10383941.64
      3574166.78     10384093.23
#Sta/Elev= 30
  4497.5  342.76  4512.2  342.44  4541.7  340.51  4752.4   325.7  4837.9  320.41
  4898.9  316.93  4936.6  315.61  4972.6  316.08  4992.6  315.72  5009.6  314.41
  5012.4  313.91  5015.6  314.41    5036  315.67  5078.3  317.89    5112  321.13
    5140  322.59  5244.1  327.36  5262.2  328.16  5282.8  327.97  5334.9  331.91
  5401.9  334.79  5435.6  337.91  5440.8  337.63  5452.1  338.75  5474.4  339.78
  5541.7  345.12  5546.9  344.86  5556.1  346.04  5559.4  346.37  5569.4  347.94
#Mann= 12 ,-1 , 0
  4497.5     .05       0  4541.7      .1       0  4837.9     .16       0
  4936.6     .12       0  5009.6     .07       0  5015.6     .12       0
    5036      .1       0    5140     .05       0  5244.1      .1       0
  5452.1     .16       0  5556.1      .1       0  5559.4     .16       0
Bank Sta=5009.6,5015.6
XS Rating Curve= 0 ,0
Exp/Cntr=0.3,0.1

Type RM Length L Ch R = 1 ,4788    ,439,439,439
BEGIN DESCRIPTION:
MILLER BRANCH 11.0
END DESCRIPTION:
XS GIS Cut Line= 3
      3575095.28     10382522.15      3574847.89     10382938.81
      3574236.53     10383563.17
#Sta/Elev= 30
  4229.5  331.82  4347.2  330.24  4378.5  328.01  4405.7  329.11  4458.3   325.3
  4501.2  324.37  4516.8   321.8  4559.6  324.55  4655.1  325.76  4676.5  328.15
  4692.2  327.25    4698  328.94  4720.1  327.54  4776.5  318.46    4805  315.65
  4826.3  313.94  4980.7  313.96    5099  313.83  5101.8  313.33    5105  313.83
    5113  313.99  5130.3  315.42  5186.9  319.88  5193.9  321.94    5208  321.27
    5399     335  5434.3  335.81  5455.6  338.86  5476.8  336.99  5587.9  343.49
#Mann= 6 ,-1 , 0
  4229.5     .16       0  4776.5     .05       0  4980.7     .07       0
    5099     .07       0    5105     .07       0    5113     .16       0
Bank Sta=4805,5130.3
XS Rating Curve= 0 ,0
Exp/Cntr=0.3,0.1

Type RM Length L Ch R = 1 ,4349    ,571,571,571
BEGIN DESCRIPTION:
MILLER BRANCH 10.0
END DESCRIPTION:
XS GIS Cut Line= 3
      3574518.04     10382383.24      3574292.11     10382891.64
      3573901.72     10383550.77
#Sta/Elev= 30
  4441.3  326.26  4496.3  331.81  4505.2  330.82  4566.1  332.73  4620.1  328.39
  4664.6   322.8  4734.3  317.37  4739.8  318.11  4752.5  315.97  4756.9  315.39
  5028.1  314.17  5125.2  313.94    5128  313.44  5131.2  313.94  5139.6   314.6
  5143.9   315.1  5297.9  326.41  5479.2  324.71  5617.6  331.77  5633.2  333.94
    5639  333.35  5654.7  336.39  5676.1   335.7  5691.7  338.07  5697.5  336.88
  5728.8   339.8  5734.6  338.37  5750.2  341.09    5756  339.19  5763.7  340.97
#Mann= 7 ,-1 , 0
  4441.3      .1       0  4620.1     .16       0  4752.5     .05       0
  5028.1     .07       0  5125.2    .033       0  5131.2     .07       0
  5139.6     .16       0
Bank Sta=4756.9,5143.9
XS Rating Curve= 0 ,0
Exp/Cntr=0.3,0.1

Type RM Length L Ch R = 1 ,3778    ,470,470,470
BEGIN DESCRIPTION:
MILLER BRANCH 9.0
END DESCRIPTION:
XS GIS Cut Line= 3
       3574214.4     10381851.95       3573728.1     10382773.88
      3573346.66     10383320.04
#Sta/Elev= 30
  4036.1  333.96  4068.6  331.35  4228.4  313.18    4338   309.9  4340.8   309.4
    4344   309.9  4344.1  309.93  4354.9  313.41  4370.5  321.26  4393.3  323.16
  4497.7  327.42  4629.9  329.37  4670.3  328.37    4740  320.91  4784.2  317.46
  4806.1  314.59  5244.2  313.83  5331.8  314.37  5346.1  316.19  5375.8  317.53
  5483.1  328.79  5579.6  336.42    5610  338.36    5641  339.73  5655.8  338.55
  5689.9  341.17  5706.4  340.27  5727.3  342.87  5742.1  342.64  5744.6  344.03
#Mann= 11 ,-1 , 0
  4036.1     .16       0    4338    .033       0    4344     .16       0
  4344.1      .1       0  4370.5     .12       0  4670.3      .1       0
  4784.2     .05       0  5244.2      .1       0  5579.6     .16       0
    5610      .1       0  5689.9     .16       0
#XS Ineff= 2 , 0
            4630  329.68
Permanent Ineff=
       F       F
Bank Sta=4806.1,5331.8
XS Rating Curve= 0 ,0
Exp/Cntr=0.3,0.1

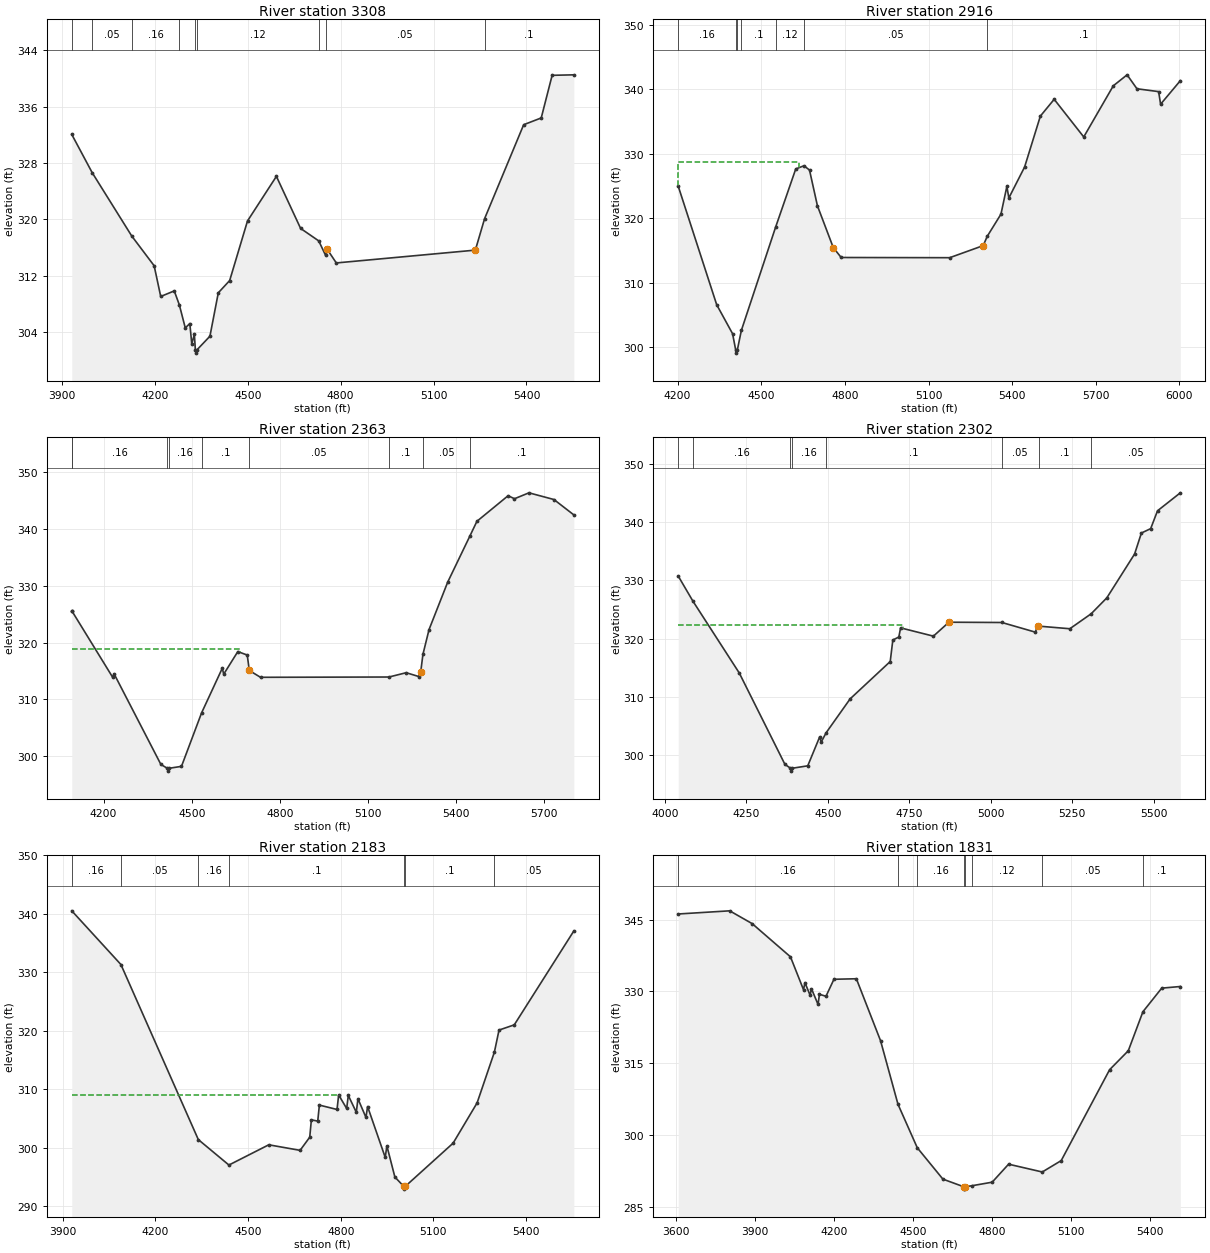
Type RM Length L Ch R = 1 ,3308    ,392,392,392
BEGIN DESCRIPTION:
MILLER BRANCH 8.0
END DESCRIPTION:
XS GIS Cut Line= 3
      3574032.12     10381539.44      3573320.12      10382517.8
      3573016.72     10382795.19
#Sta/Elev= 30
  3931.9  332.05  3997.6  326.64  4125.4  317.64  4197.9  313.41  4219.1  309.05
  4262.8  309.84  4279.2  307.86  4298.4  304.59  4313.1  305.21  4319.3  302.33
  4327.7  303.67  4330.9  301.51  4333.7  301.01  4336.9  301.51    4378  303.41
    4405  309.57  4441.7  311.31  4499.3  319.77 4592.61   326.1  4670.8  318.71
  4729.3  316.94  4751.4  314.89  4756.6  315.75    4786  313.81    5235  315.63
  5264.7  320.08    5391  333.43  5447.7  334.39  5482.9  340.44    5553  340.51
#Mann= 9 ,-1 , 0
  3931.9     .16       0  3997.6     .05       0  4125.4     .16       0
  4279.2     .12       0  4330.9    .033       0  4336.9     .12       0
  4729.3     .07       0  4751.4     .05       0  5264.7      .1       0
#XS Ineff= 2 , 0
         4592.61  326.03
Permanent Ineff=
       F       F
Bank Sta=4756.6,5235
XS Rating Curve= 0 ,0
Exp/Cntr=0.3,0.1

Type RM Length L Ch R = 1 ,2916    ,553,553,553
BEGIN DESCRIPTION:
MILLER BRANCH 7.0
END DESCRIPTION:
XS GIS Cut Line= 3
      3573750.18     10381574.84      3573049.32     10382197.81
      3572436.53     10382806.03
#Sta/Elev= 30
  4202.2  324.96  4340.2   306.6  4397.1  302.12  4408.3  299.61  4411.1  299.11
  4414.3  299.61  4428.6  302.62  4551.6  318.63  4623.7  327.63  4653.3  328.13
  4673.1  327.46  4701.5  321.93  4758.4  315.45  4786.8  313.92    5176  313.89
  5296.2  315.76  5310.8  317.21  5359.9  320.63  5381.1  324.93  5388.2  323.14
  5444.7  327.93  5501.3  335.82  5550.8  338.42  5656.9  332.59  5762.9  340.51
  5812.4  342.21  5847.8  340.05  5925.5  339.61  5932.6  337.66  6003.3   341.3
#Mann= 7 ,-1 , 0
  4202.2     .16       0  4408.3    .033       0  4414.3     .16       0
  4428.6      .1       0  4551.6     .12       0  4653.3     .05       0
  5310.8      .1       0
#XS Ineff= 2 , 0
         4636.36  328.75
Permanent Ineff=
       F       F
Bank Sta=4758.4,5296.2
XS Rating Curve= 0 ,0
Exp/Cntr=0.3,0.1

Type RM Length L Ch R = 1 ,2363    ,61,61,61
BEGIN DESCRIPTION:
MILLER BRANCH 6.1
END DESCRIPTION:
XS GIS Cut Line= 4
        3573735.     10381514.09      3573185.57     10381484.81
      3572860.05     10381636.72      3572326.81     10382232.11
#Sta/Elev= 30
  4091.7  325.51  4092.7  325.51  4230.8  313.88  4235.8  314.47    4395  298.52
  4416.8  297.84  4419.6  297.34  4422.8  297.84  4465.1  298.18  4533.5   307.6
  4603.9  315.46  4608.9  314.43  4656.8   318.4  4688.9  317.79  4695.9  315.07
    4734  313.87  5171.3  313.92  5229.8  314.68  5272.4  314.01  5279.1  314.75
  5286.8  317.91  5307.6  322.28  5371.1  330.64  5446.8  338.78  5470.5  341.35
  5576.7  345.86  5598.4  345.33  5647.7  346.37  5732.7  345.19  5800.4  342.48
#Mann= 9 ,-1 , 0
  4091.7     .05       0  4092.7     .16       0  4416.8    .033       0
  4422.8     .16       0  4533.5      .1       0  4695.9     .05       0
  5171.3      .1       0  5286.8     .05       0  5446.8      .1       0
#XS Ineff= 2 , 0
         4664.77  318.84
Permanent Ineff=
       F       F
Bank Sta=4695.9,5279.1
XS Rating Curve= 0 ,0
Exp/Cntr=0.3,0.1

Type RM Length L Ch R = 1 ,2302    ,119,119,119
BEGIN DESCRIPTION:
MILLER BRANCH 6.0
END DESCRIPTION:
XS GIS Cut Line= 4
      3573749.33     10381450.72      3573101.72     10381444.65
      3572877.76      10381538.4      3572399.58      10381977.6
#Sta/Elev= 30
  4041.5  330.76  4086.2  326.49  4228.7  314.14  4368.7  298.48  4385.7  297.82
  4388.5  297.32  4391.7  297.82  4438.7  298.23  4475.1  303.17  4480.1  302.32
  4495.3  303.92  4568.7  309.71  4691.6  316.11  4699.6   319.8    4718  320.31
  4723.4  321.88    4824  320.46  4871.6  322.85  5034.1   322.8  5136.4  321.15
  5143.3  322.12  5146.4  322.18  5242.4  321.73  5307.7  324.29  5355.9  327.03
    5441  334.54  5461.9  338.14  5490.3  338.89  5511.3  341.95  5581.2  345.03
#Mann= 8 ,-1 , 0
  4041.5     .05       0  4086.2     .16       0  4385.7     .07       0
  4391.7     .16       0  4495.3      .1       0  5034.1     .05       0
  5146.4      .1       0  5307.7     .05       0
#XS Ineff= 2 , 0
         4731.82  322.29
Permanent Ineff=
       F       F
Bank Sta=4871.6,5143.3
XS Rating Curve= 0 ,0
Exp/Cntr=0.3,0.1

Type RM Length L Ch R = 1 ,2183    ,352,352,352
BEGIN DESCRIPTION:
MILLER BRANCH 5.0
END DESCRIPTION:
XS GIS Cut Line= 4
      3573808.25     10381317.22      3573189.91     10381337.24
      3572742.11     10381491.64      3572382.59     10381884.14
#Sta/Elev= 30
  3929.8  340.49  4088.8  331.31  4339.3  301.37  4438.3  297.02  4567.3  300.48
  4668.6  299.53  4699.8  301.78  4705.1  304.75  4725.7  304.53    4731  307.27
  4788.1  306.52  4793.4     309  4819.3  306.69  4824.6  308.92  4850.5  306.04
  4855.8  308.36  4881.7  305.16    4887  307.02  4944.1  298.32  4949.4   300.3
  4975.3  294.97  5003.5   293.4  5006.3   292.9  5009.5   293.4  5163.7  300.76
  5241.3  307.64  5297.3  316.33  5312.3   320.1  5361.6  320.99  5554.4  337.05
#Mann= 7 ,-1 , 0
  3929.8     .16       0  4088.8     .05       0  4339.3     .16       0
  4438.3      .1       0  5003.5     .07       0  5009.5      .1       0
  5297.3     .05       0
#XS Ineff= 2 , 0
         4793.07  308.92
Permanent Ineff=
       F       F
Bank Sta=5003.5,5009.5
XS Rating Curve= 0 ,0
Exp/Cntr=0.3,0.1

Type RM Length L Ch R = 1 ,1831    ,393,393,393
BEGIN DESCRIPTION:
MILLER BRANCH 4.0
END DESCRIPTION:
XS GIS Cut Line= 4
      3573871.16     10381215.22      3573215.95     10380968.32
      3572612.65     10381141.93      3572226.76     10381575.51
#Sta/Elev= 30
    3607  346.19  3802.6  346.85  3887.9  344.18  4033.6  337.24  4083.3  330.35
  4088.6  331.85  4108.2  329.21  4113.5  330.57  4138.4  327.29  4143.7  329.41
  4168.6     329  4198.8  332.55  4284.1  332.66  4376.1   319.7  4442.3  306.43
  4515.6  297.35    4613   290.8  4691.9  289.21  4694.7  288.71  4697.9  289.21
  4723.5  289.42  4800.3  290.16  4862.7  293.92  4990.7  292.29  5062.7  294.67
  5246.7  313.66  5317.7  317.62  5373.3  325.77  5444.8   330.7  5515.4  331.04
#Mann= 8 ,-1 , 0
    3607     .16       0  4442.3     .05       0  4515.6     .16       0
  4691.9    .035       0  4697.9     .16       0  4723.5     .12       0
  4990.7     .05       0  5373.3      .1       0
Bank Sta=4691.9,4697.9
XS Rating Curve= 0 ,0
Exp/Cntr=0.3,0.1

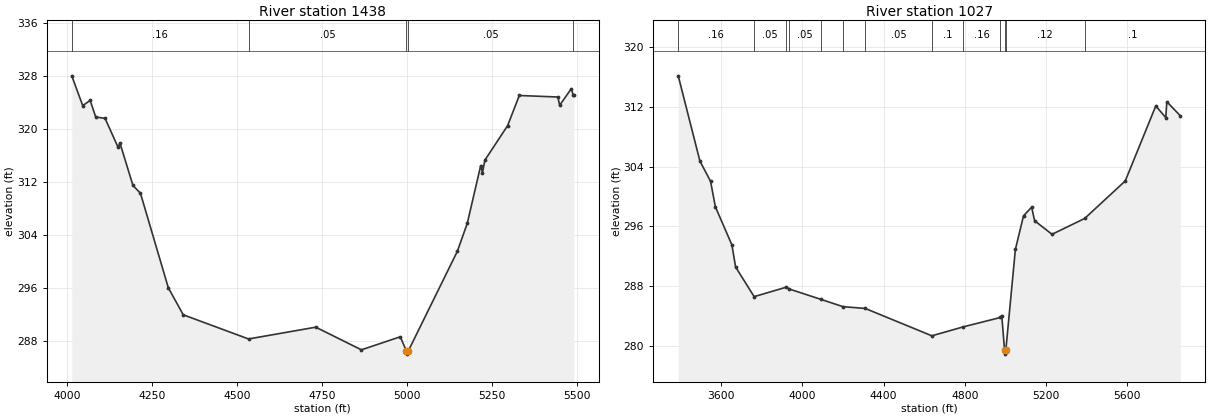
Type RM Length L Ch R = 1 ,1438    ,411,411,411
BEGIN DESCRIPTION:
MILLER BRANCH 3.0
END DESCRIPTION:
XS GIS Cut Line= 3
      3573055.38     10380421.44      3572300.15     10380825.09
      3572135.22     10381424.07
#Sta/Elev= 30
  4013.8  328.01    4046  323.51  4067.9   324.3  4084.2   321.8  4111.8  321.58
    4150  317.23  4155.7  317.84  4193.9  311.45  4215.9  310.28    4298  295.99
  4341.9  291.92    4534  288.27  4731.8  290.05  4866.2  286.63  4980.6   288.6
  4998.4  286.48  5001.1  285.98  5004.4  286.48  5148.5   301.5  5177.7  305.72
  5217.3  314.45  5222.5  313.39  5229.6  315.27  5296.5  320.49  5330.9  325.04
  5444.4  324.81  5449.6  323.56    5484  326.07  5489.3  325.14  5491.4  325.14
#Mann= 5 ,-1 , 0
  4013.8     .16       0    4534     .05       0  4998.4    .035       0
  5004.4     .05       0  5489.3      .1       0
Bank Sta=4998.4,5004.4
XS Rating Curve= 0 ,0
Exp/Cntr=0.3,0.1

Type RM Length L Ch R = 1 ,1027    ,0,0,0
BEGIN DESCRIPTION:
MILLER BRANCH 1.0
END DESCRIPTION:
XS GIS Cut Line= 3
       3573094.4     10380074.23      3571861.78     10380603.74
      3571931.22     10381732.16
#Sta/Elev= 30
  3388.6  316.15  3495.3  304.75  3547.8  302.04  3571.4  298.63  3652.9  293.53
    3671  290.58  3762.4  286.61  3921.1  287.88  3934.4  287.64  4090.5  286.25
  4199.9  285.27  4309.3  285.03  4637.5  281.37  4789.6  282.55  4974.9  283.82
  4981.6  284.07  4995.5  279.42  4998.3  278.92  5001.5  279.42  5048.6  292.92
  5088.7  297.42  5128.8  298.58  5143.1  296.77    5229  294.95  5389.9  297.07
  5589.7  302.09  5739.9  312.12  5789.3  310.56  5794.3  312.68  5860.7  310.81
#Mann= 13 ,-1 , 0
  3388.6     .16       0  3762.4     .05       0  3921.1     .16       0
  3934.4     .05       0  4090.5     .16       0  4199.9     .12       0
  4309.3     .05       0  4637.5      .1       0  4789.6     .16       0
  4974.9     .12       0  4995.5     .07       0  5001.5     .12       0
  5389.9      .1       0
Bank Sta=4995.5,5001.5
XS Rating Curve= 0 ,0
Exp/Cntr=0.3,0.1

Chan Stop Cuts=-1
Use User Specified Reach Order=0
Composite Channel Slope=5