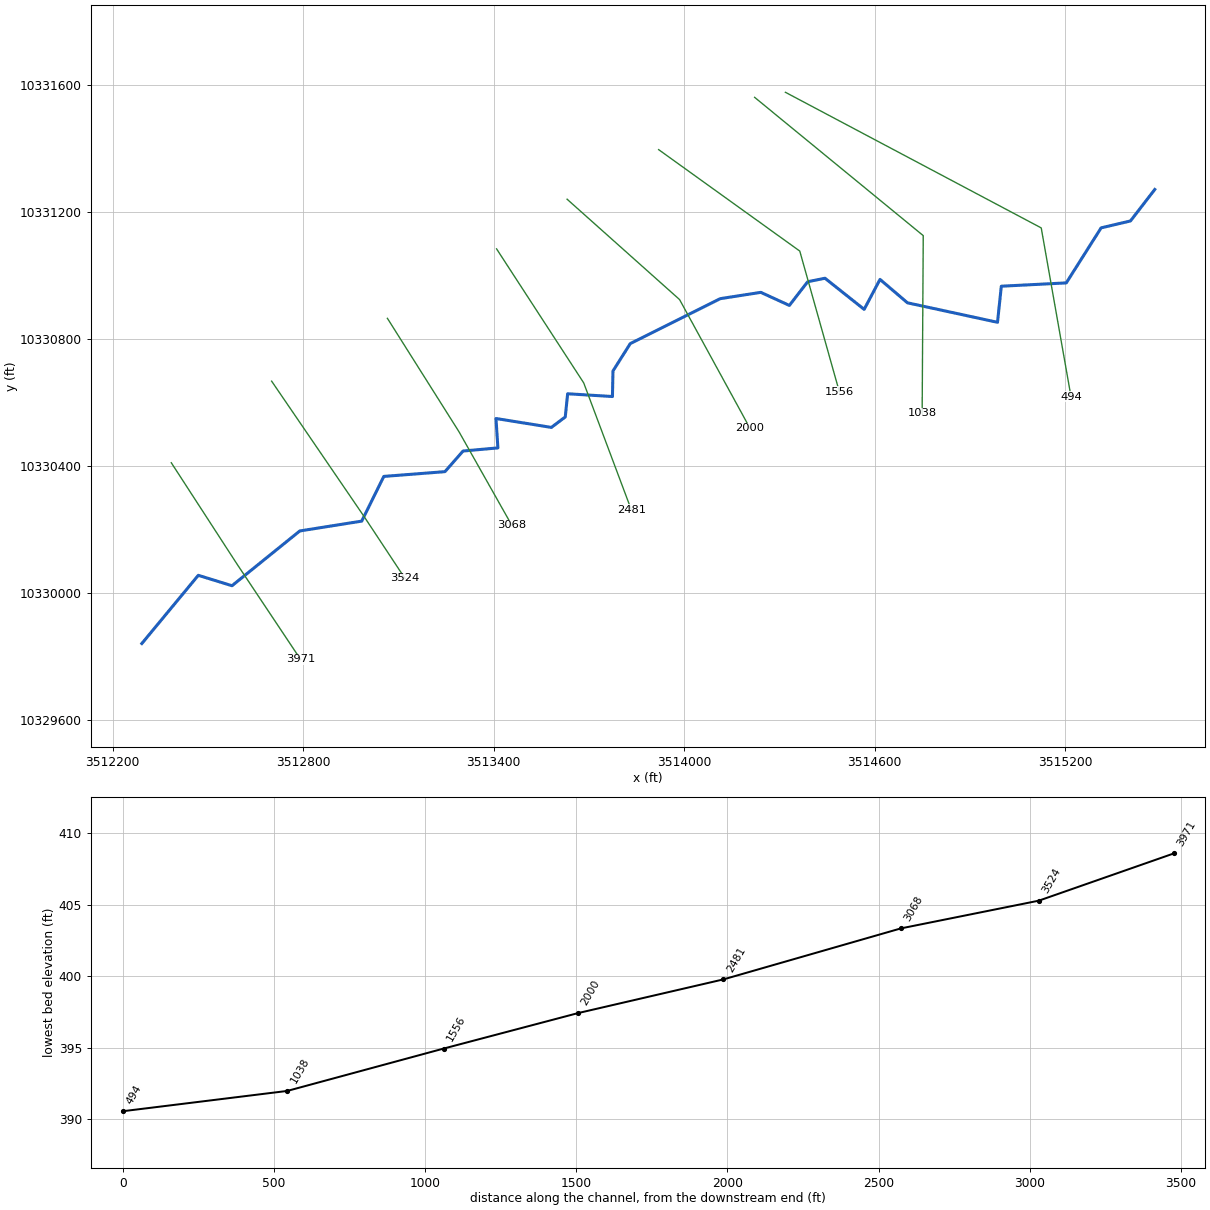
--- MOORES BRANCH TRIBUTARY 2.prj (project) ---

Proj Title=MOORES BRANCH TRIBUTARY 2 Base Level Engineering
Current Plan=p01
Default Exp/Contr=0.3,0.1
English Units
Geom File=g01
Flow File=f01
Plan File=p01
BEGIN DESCRIPTION:
MOORES BRANCH TRIBUTARY 2
END DESCRIPTION:

--- MOORES BRANCH TRIBUTARY 2.p01 (plan) ---

Plan Title=Multiple Run
Short Identifier=Multiple
Geom File=g01
Flow File=f01
Subcritical Flow
K Sum by GR= 0
Std Step Tol= 0.01
Critical Tol= 0.01
Num of Std Step Trials= 20
Max Error Tol= 0.3
Flow Tol Ratio= 0.001
Split Flow NTrial= 30
Split Flow Tol= 0.02
Split Flow Ratio= 0.02
Log Output Level= 0
Friction Slope Method= 1
Unsteady Friction Slope Method= 2
Unsteady Bridges Friction Slope Method= 1
Parabolic Critical Depth
Global Vel Dist=  1 , 1 , 1
Global Log Level= 0
CheckData=True
Encroach Param= -1, 0, 0, 0
BEGIN DESCRIPTION:
Multiple Run
END DESCRIPTION:

--- MOORES BRANCH TRIBUTARY 2.f01 (steady flow) ---

Flow Title=Multiple
Number of Profiles=7
Profile Names=10-year,25-year,50-year,1pct_min,100-year,1pct_plu,500-year
River Rch & RM= MOORES BRANCH TR,Reach-1,3971
     636     880    1083     979    1323    1790    1980
River Rch & RM= MOORES BRANCH TR,Reach-1,3524
     737    1025    1266    1147    1551    2098    2336
Boundary for River Rch & Prof#=MOORES BRANCH TR,Reach-1,1
Up Type=0
Dn Type=3
Dn Slope=0.005
Boundary for River Rch & Prof#=MOORES BRANCH TR,Reach-1,2
Up Type=0
Dn Type=3
Dn Slope=0.005
Boundary for River Rch & Prof#=MOORES BRANCH TR,Reach-1,3
Up Type=0
Dn Type=3
Dn Slope=0.005
Boundary for River Rch & Prof#=MOORES BRANCH TR,Reach-1,4
Up Type=0
Dn Type=3
Dn Slope=0.005
Boundary for River Rch & Prof#=MOORES BRANCH TR,Reach-1,5
Up Type=0
Dn Type=3
Dn Slope=0.005
Boundary for River Rch & Prof#=MOORES BRANCH TR,Reach-1,6
Up Type=0
Dn Type=3
Dn Slope=0.005
Boundary for River Rch & Prof#=MOORES BRANCH TR,Reach-1,7
Up Type=0
Dn Type=3
Dn Slope=0.005

--- MOORES BRANCH TRIBUTARY 2.g01 (geometry) ---

Geom Title=Existing Conditions

River Reach=MOORES BRANCH TR,Reach-1
Reach XY= 30
      3512292.11     10329841.64      3512469.92     10330056.53
      3512576.16     10330023.79      3512789.67     10330196.23
      3512984.71     10330227.23      3513054.18     10330367.97
      3513246.74     10330383.00      3513303.80     10330447.97
      3513413.47     10330457.79      3513407.43     10330550.35
      3513581.90     10330522.33      3513625.63     10330555.21
      3513633.11     10330628.29      3513774.22     10330619.55
      3513775.87     10330700.03      3513830.39     10330786.30
      3514113.72     10330927.77      3514241.49     10330947.64
      3514331.37     10330906.46      3514388.99     10330981.04
      3514443.52     10330992.09      3514566.89     10330894.08
      3514616.84     10330988.45      3514703.30     10330914.72
      3514986.87     10330853.32      3514998.87     10330966.97
      3515203.43     10330977.45      3515313.14     10331150.72
      3515405.59     10331172.46      3515482.11     10331271.64

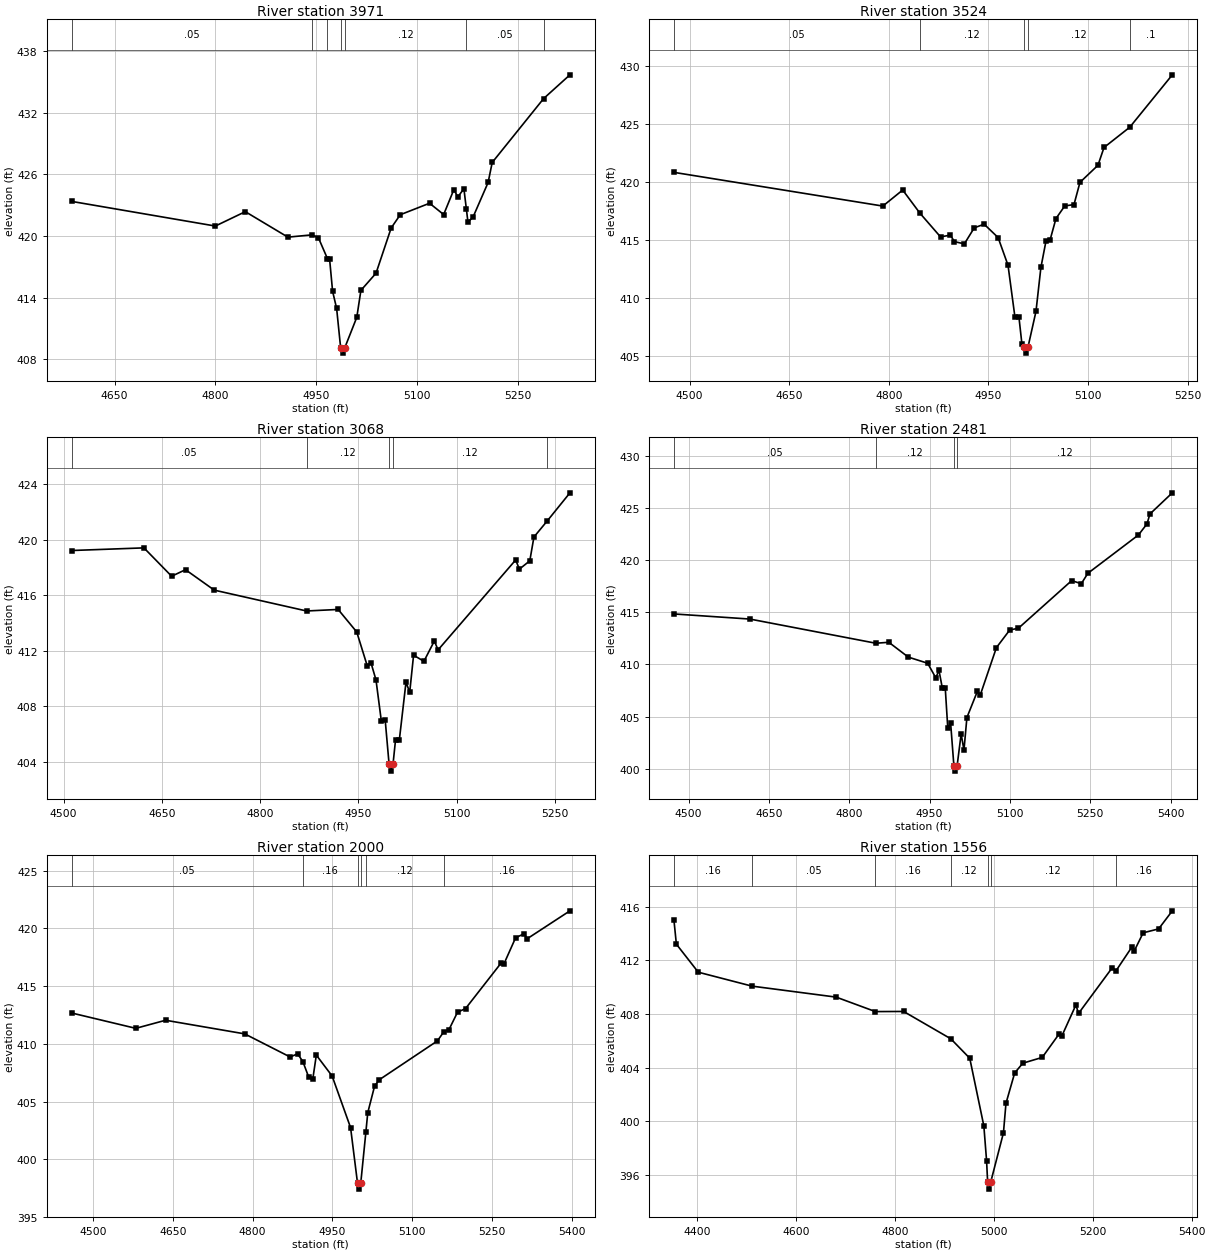
Type RM Length L Ch R = 1,3971,447,447,447
BEGIN DESCRIPTION:
MOORES BRANCH TRIBUTARY 2 8.0
END DESCRIPTION:
XS GIS Cut Line= 3
      3512384.96     10330411.03      3512592.11     10330091.64
      3512792.09     10329791.67
#Sta/Elev= 30
  4586.0  423.36  4799.8  420.96  4844.4  422.36  4907.7  419.88  4943.3  420.10
  4953.1  419.82  4966.6  417.78  4969.7  417.78  4974.2  414.61  4980.2  412.94
  4986.2  409.09  4989.0  408.59  4992.2  409.09  5010.2  412.08  5016.3  414.70
  5038.8  416.37  5061.3  420.77  5074.8  422.06  5118.4  423.18  5139.4  422.08
  5154.5  424.50  5160.5  423.80  5169.5  424.59  5173.1  422.65  5175.5  421.35
  5183.0  421.82  5205.5  425.20  5211.6  427.15  5288.1  433.37  5327.2  435.68
#Mann=7,-1,0
  4586.0    0.05       0  4943.3    0.16       0  4966.6    0.12       0
  4986.2    0.07       0  4992.2    0.12       0  5173.1    0.05       0
  5288.1     0.1       0
Bank Sta=4986.2,4992.2
Exp/Cntr=0.3,0.1

Type RM Length L Ch R = 1,3524,456,456,456
BEGIN DESCRIPTION:
MOORES BRANCH TRIBUTARY 2 7.0
END DESCRIPTION:
XS GIS Cut Line= 3
      3512700.92     10330668.00      3512992.11     10330241.64
      3513120.98     10330046.58
#Sta/Elev= 30
  4476.6  420.83  4791.0  417.93  4820.9  419.31  4846.8  417.32  4877.8  415.28
  4892.7  415.43  4898.7  414.87  4913.7  414.68  4928.6  416.06  4943.5  416.37
  4964.5  415.22  4979.4  412.84  4989.9  408.35  4995.9  408.35  5000.4  406.03
  5003.4  405.78  5006.2  405.28  5009.4  405.78  5021.5  408.87  5028.9  412.65
  5036.6  414.93  5042.5  414.97  5051.6  416.86  5064.8  417.94  5078.7  418.06
  5087.7  419.97  5114.8  421.44  5123.9  422.97  5162.6  424.71  5226.7  429.22
#Mann=5,-1,0
  4476.6    0.05       0  4846.8    0.12       0  5003.4    0.07       0
  5009.4    0.12       0  5162.6     0.1       0
Bank Sta=5003.4,5009.4
Exp/Cntr=0.3,0.1

Type RM Length L Ch R = 1,3068,587,587,587
BEGIN DESCRIPTION:
MOORES BRANCH TRIBUTARY 2 6.0
END DESCRIPTION:
XS GIS Cut Line= 3
      3513065.52     10330865.88      3513291.22     10330508.24
      3513457.52     10330213.75
#Sta/Elev= 30
  4512.1  419.21  4622.6  419.40  4664.9  417.36  4686.1  417.83  4730.0  416.36
  4871.0  414.86  4919.2  414.97  4947.6  413.35  4963.6  410.92  4969.3  411.14
  4977.0  409.90  4985.2  406.93  4991.0  407.04  4997.0  403.84  4999.7  403.34
  5003.0  403.84  5006.9  405.61  5012.6  405.56  5022.8  409.73  5028.5  409.02
  5034.4  411.68  5050.2  411.24  5066.1  412.70  5071.8  412.06  5190.3  418.53
  5196.0  417.87  5211.9  418.47  5218.2  420.18  5238.9  421.36  5273.2  423.36
#Mann=5,-1,0
  4512.1    0.05       0  4871.0    0.12       0  4997.0    0.07       0
  5003.0    0.12       0  5238.9    0.16       0
Bank Sta=4997,5003
Exp/Cntr=0.3,0.1

Type RM Length L Ch R = 1,2481,481,481,481
BEGIN DESCRIPTION:
MOORES BRANCH TRIBUTARY 2 5.0
END DESCRIPTION:
XS GIS Cut Line= 3
      3513409.29     10331084.60      3513683.77     10330662.48
      3513833.76     10330262.50
#Sta/Elev= 30
  4472.6  414.85  4614.3  414.36  4849.6  412.04  4873.9  412.13  4910.2  410.71
  4946.4  410.12  4961.6  408.72  4967.5  409.44  4973.6  407.79  4979.2  407.79
  4984.0  403.88  4989.3  404.38  4995.4  400.27  4998.1  399.77  5001.4  400.27
  5008.9  403.34  5014.2  401.79  5019.7  404.91  5039.2  407.42  5044.5  407.05
  5074.8  411.62  5099.7  413.31  5115.9  413.48  5215.4  418.05  5233.3  417.75
  5245.6  418.75  5340.1  422.43  5356.0  423.49  5361.5  424.44  5403.3  426.47
#Mann=4,-1,0
  4472.6    0.05       0  4849.6    0.12       0  4995.4    0.07       0
  5001.4    0.12       0
Bank Sta=4995.4,5001.4
Exp/Cntr=0.3,0.1

Type RM Length L Ch R = 1,2000,444,444,444
BEGIN DESCRIPTION:
MOORES BRANCH TRIBUTARY 2 4.0
END DESCRIPTION:
XS GIS Cut Line= 3
      3513631.46     10331240.91      3513985.66     10330924.90
      3514207.49     10330519.38
#Sta/Elev= 30
  4459.6  412.67  4580.3  411.34  4636.3  412.04  4785.1  410.86  4870.4  408.86
  4884.6  409.13  4894.4  408.46  4905.5  407.10  4913.0  406.92  4919.7  409.02
  4949.4  407.21  4984.1  402.74  4997.2  397.91  5000.0  397.41  5003.2  397.91
  5012.9  402.37  5016.4  404.03  5029.2  406.33  5038.2  406.89  5147.3  410.25
  5159.5  411.05  5169.1  411.23  5185.2  412.74  5200.2  413.05  5266.8  416.98
  5272.5  416.93  5294.3  419.18  5310.4  419.54  5316.1  419.10  5396.5  421.52
#Mann=6,-1,0
  4459.6    0.05       0  4894.4    0.16       0  4997.2    0.07       0
  5003.2    0.16       0  5012.9    0.12       0  5159.5    0.16       0
Bank Sta=4997.2,5003.2
Exp/Cntr=0.3,0.1

Type RM Length L Ch R = 1,1556,518,518,518
BEGIN DESCRIPTION:
MOORES BRANCH TRIBUTARY 2 3.0
END DESCRIPTION:
XS GIS Cut Line= 3
      3513919.73     10331397.10      3514364.14     10331077.68
      3514488.65     10330634.95
#Sta/Elev= 30
  4353.7  414.99  4358.6  413.21  4402.8  411.12  4511.4  410.08  4681.5  409.26
  4760.8  408.18  4817.8  408.19  4913.2  406.15  4951.5  404.70  4980.0  399.65
  4985.5  397.06  4987.7  395.43  4990.4  394.93  4993.7  395.43  5019.6  399.13
  5024.7  401.33  5042.3  403.60  5058.8  404.33  5098.0  404.76  5132.1  406.51
  5137.3  406.33  5166.1  408.68  5171.3  408.04  5239.4  411.45  5247.0  411.22
  5278.7  412.97  5283.9  412.70  5302.0  414.06  5333.2  414.35  5360.9  415.70
#Mann=7,-1,0
  4353.7    0.16       0  4511.4    0.05       0  4760.8    0.16       0
  4913.2    0.12       0  4987.7    0.07       0  4993.7    0.12       0
  5247.0    0.16       0
Bank Sta=4987.7,4993.7
Exp/Cntr=0.3,0.1

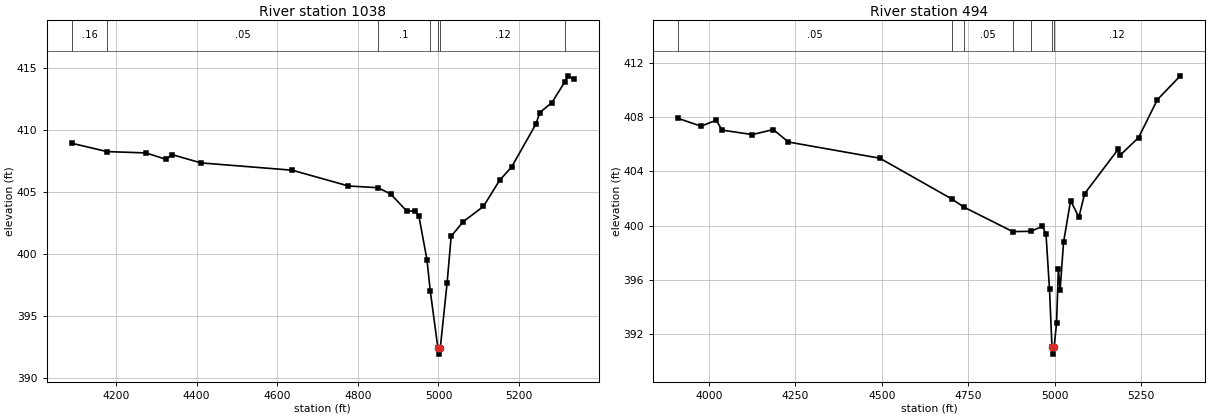
Type RM Length L Ch R = 1,1038,544,544,544
BEGIN DESCRIPTION:
MOORES BRANCH TRIBUTARY 2 2.0
END DESCRIPTION:
XS GIS Cut Line= 3
      3514221.98     10331561.77      3514753.02     10331126.29
      3514749.55     10330567.26
#Sta/Elev= 30
  4090.1  408.94  4177.6  408.27  4274.7  408.16  4324.2  407.64  4338.6  408.03
  4410.3  407.36  4637.1  406.77  4776.6  405.50  4849.9  405.36  4881.5  404.85
  4921.5  403.47  4941.5  403.50  4951.5  403.06  4971.5  399.55  4979.7  397.04
  4998.5  392.46  5001.3  391.96  5004.5  392.46  5021.5  397.72  5031.5  401.45
  5061.5  402.63  5111.5  403.85  5151.5  405.95  5181.5  407.03  5241.5  410.47
  5251.5  411.41  5281.5  412.22  5313.1  413.86  5321.5  414.37  5335.9  414.09
#Mann=7,-1,0
  4090.1    0.16       0  4177.6    0.05       0  4849.9     0.1       0
  4979.7    0.12       0  4998.5    0.07       0  5004.5    0.12       0
  5313.1    0.16       0
Bank Sta=4998.5,5004.5
Exp/Cntr=0.3,0.1

Type RM Length L Ch R = 1,494,0,0,0
BEGIN DESCRIPTION:
MOORES BRANCH TRIBUTARY 2 1.0
END DESCRIPTION:
XS GIS Cut Line= 3
      3514318.97     10331577.70      3515124.55     10331150.60
      3515218.31     10330619.31
#Sta/Elev= 30
  3911.8  407.91  3977.8  407.34  4021.8  407.78  4038.2  407.05  4126.1  406.72
  4186.5  407.09  4230.4  406.17  4494.4  404.98  4702.3  401.98  4737.1  401.38
  4878.7  399.57  4932.0  399.59  4964.7  399.97  4974.9  399.37  4985.0  395.31
  4992.2  391.04  4994.9  390.54  4998.2  391.04  5005.3  392.81  5010.7  396.81
  5015.7  395.29  5025.6  398.78  5045.9  401.85  5069.9  400.63  5086.6  402.37
  5183.3  405.63  5188.4  405.18  5242.5  406.50  5296.7  409.29  5363.1  411.05
#Mann=7,-1,0
  3911.8    0.05       0  4702.3     0.1       0  4737.1    0.05       0
  4878.7     0.1       0  4932.0    0.12       0  4992.2    0.07       0
  4998.2    0.12       0
Bank Sta=4992.2,4998.2
Exp/Cntr=0.3,0.1

Chan Stop Cuts=-1