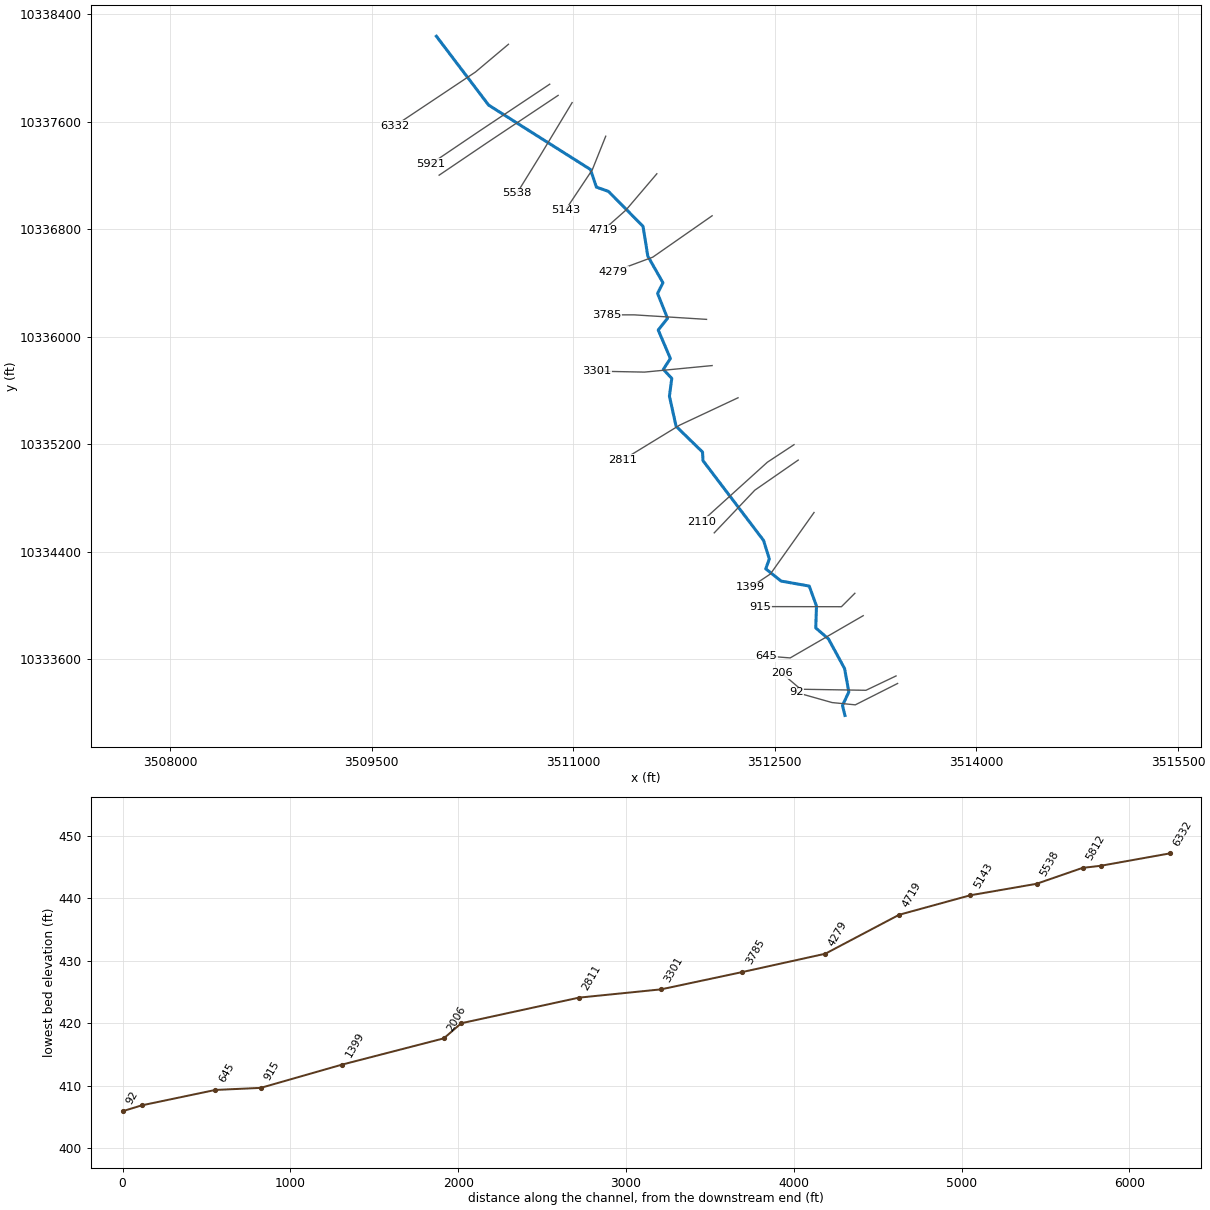
--- MOORES BRANCH TRIBUTARY 3.prj (project) ---

Proj Title=MOORES BRANCH TRIBUTARY 3 Base Level Engineering
Current Plan=p01
Default Exp/Contr=0.3,0.1
English Units
Geom File=g01
Flow File=f01
Plan File=p01
Y Axis Title=Elevation
X Axis Title(PF)=Main Channel Distance
X Axis Title(XS)=Station
BEGIN DESCRIPTION:
MOORES BRANCH TRIBUTARY 3
END DESCRIPTION:
DSS Export Rating Curves= 0
DSS Export Rating Curve Sorted= 0
DSS Export Volume Flow Curves= 0
DXF OffsetX= 0
DXF OffsetY= 0
DXF ScaleX= 1
DXF ScaleY= 10

--- MOORES BRANCH TRIBUTARY 3.p01 (plan) ---

Plan Title=Multiple Run
Short Identifier=Multiple
Geom File=g01
Flow File=f01
Subcritical Flow
K Sum by GR= 0
Std Step Tol= 0.01
Critical Tol= 0.01
Num of Std Step Trials= 20
Max Error Tol= 0.3
Flow Tol Ratio= 0.001
Split Flow NTrial= 30
Split Flow Tol= 0.02
Split Flow Ratio= 0.02
Log Output Level= 0
Friction Slope Method= 1
Unsteady Friction Slope Method= 2
Unsteady Bridges Friction Slope Method= 1
Parabolic Critical Depth
Global Vel Dist=  1 , 1 , 1
Global Log Level= 0
CheckData=True
Encroach Param= -1, 0, 0, 0
BEGIN DESCRIPTION:
Multiple Run
END DESCRIPTION:

--- MOORES BRANCH TRIBUTARY 3.f01 (steady flow) ---

Flow Title=Multiple
Program Version=4.10
Number of Profiles= 7
Profile Names=10-year,25-year,50-year,1pct_min,100-year,1pct_plu,500-year
River Rch & RM=MOORES BRANCH TR,Reach-1         ,6332
     541     735     893     796    1077    1457    1570
River Rch & RM=MOORES BRANCH TR,Reach-1         ,2811
     609     833    1017     910    1231    1665    1809
Boundary for River Rch & Prof#=MOORES BRANCH TR,Reach-1         , 1
Up Type= 0
Dn Type= 3
Dn Slope=0.006
Boundary for River Rch & Prof#=MOORES BRANCH TR,Reach-1         , 2
Up Type= 0
Dn Type= 3
Dn Slope=0.006
Boundary for River Rch & Prof#=MOORES BRANCH TR,Reach-1         , 3
Up Type= 0
Dn Type= 3
Dn Slope=0.006
Boundary for River Rch & Prof#=MOORES BRANCH TR,Reach-1         , 4
Up Type= 0
Dn Type= 3
Dn Slope=0.006
Boundary for River Rch & Prof#=MOORES BRANCH TR,Reach-1         , 5
Up Type= 0
Dn Type= 3
Dn Slope=0.006
Boundary for River Rch & Prof#=MOORES BRANCH TR,Reach-1         , 6
Up Type= 0
Dn Type= 3
Dn Slope=0.006
Boundary for River Rch & Prof#=MOORES BRANCH TR,Reach-1         , 7
Up Type= 0
Dn Type= 3
Dn Slope=0.006
DSS Import GetInterval= 0
DSS Import GetPeak= 0
DSS Import FillOption= 0

--- MOORES BRANCH TRIBUTARY 3.g01 (geometry) ---

Geom Title=Existing Conditions
Program Version=4.10

River Reach=MOORES BRANCH TR,Reach-1
Reach XY= 30
       3509982.2     10338235.39      3510370.69     10337723.29
      3511128.58     10337243.93       3511172.9     10337112.67
      3511262.04     10337081.31      3511519.88     10336820.74
      3511555.29     10336599.26      3511667.97     10336400.98
      3511627.94     10336321.82      3511701.79      10336136.9
      3511632.88     10336049.35      3511723.16     10335837.54
      3511670.64     10335756.81      3511733.57     10335689.54
      3511716.08     10335557.72      3511765.65     10335333.11
      3511962.43     10335141.57       3511965.9     10335077.33
      3512416.44     10334484.04      3512459.46     10334346.04
      3512432.85     10334272.62      3512546.98      10334181.5
      3512756.47     10334144.29       3512810.3     10333996.02
      3512804.93     10333832.75      3512899.91      10333750.8
      3513019.33     10333530.49      3513051.02     10333356.54
      3513003.69     10333256.04      3513022.11     10333181.64

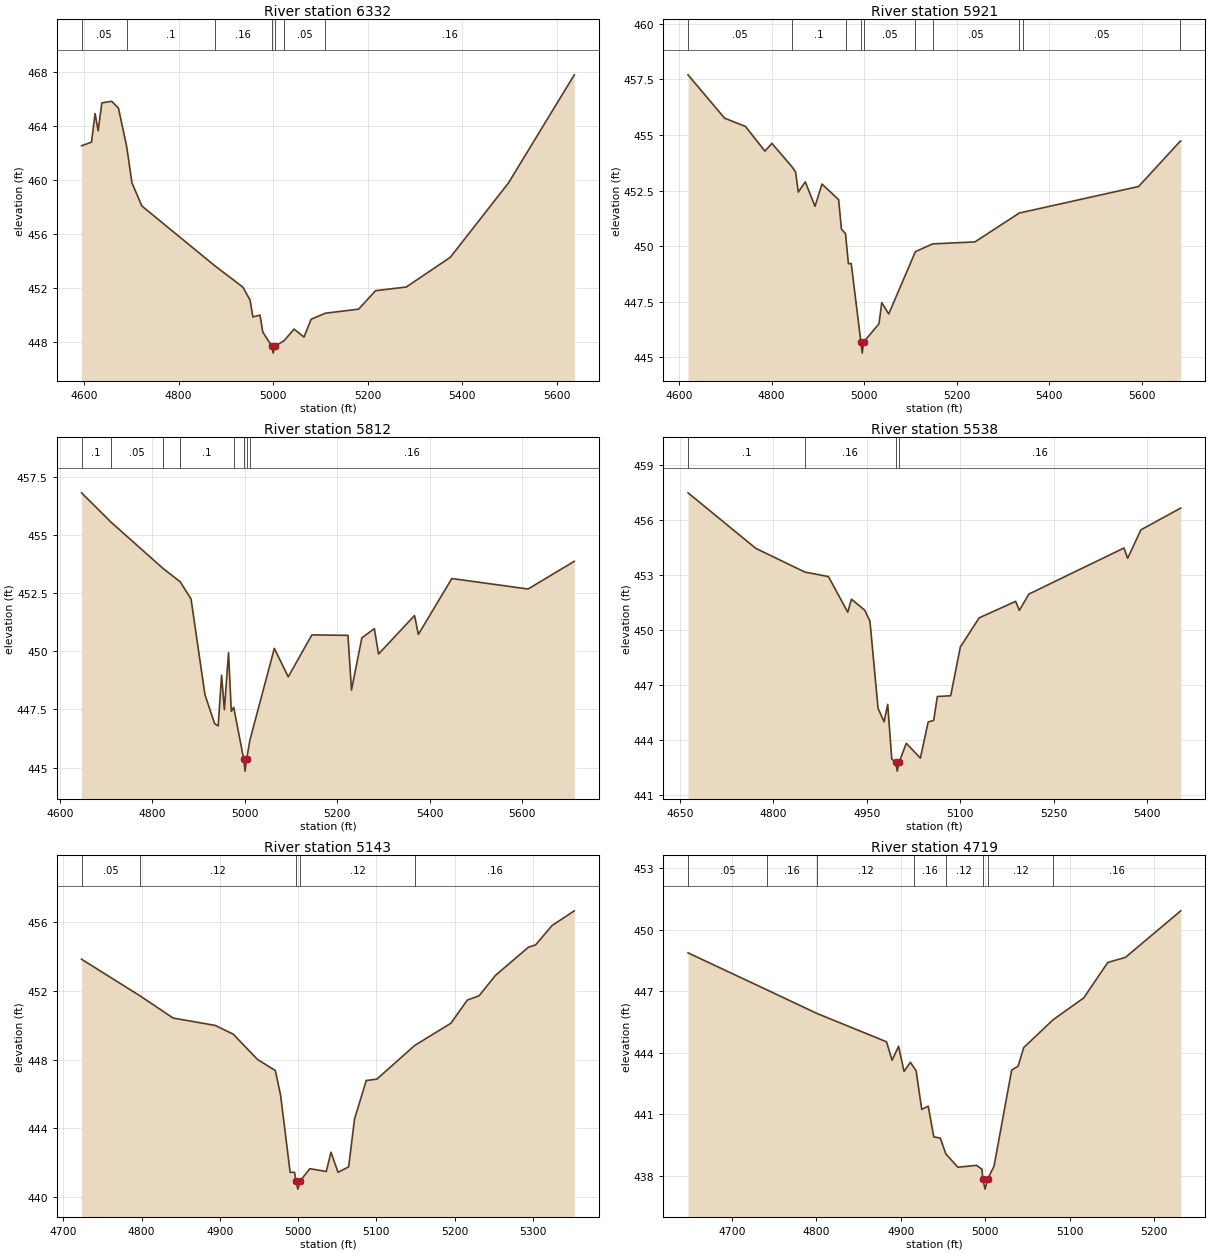
Type RM Length L Ch R = 1 ,6332    ,411,411,411
BEGIN DESCRIPTION:
MOORES BRANCH TRIBUTARY 3 14.0
END DESCRIPTION:
XS GIS Cut Line= 3
      3510518.24     10338175.66      3510272.31     10337968.73
      3509672.33     10337568.73
#Sta/Elev= 30
  4594.7  462.54  4615.8  462.81  4623.3  464.93  4629.8  463.65  4637.6  465.72
  4658.4  465.84  4672.7  465.34    4690  462.52  4701.3   459.8  4722.2  458.08
  4876.5  453.65  4936.1  452.06  4951.2   451.1  4957.2  449.85  4972.2  449.99
  4978.2  448.73  4997.5  447.67  5000.2  447.17  5003.5  447.67  5023.2  448.09
  5044.3  448.95  5065.3  448.36  5080.4  449.68  5110.7  450.13  5180.8  450.43
  5216.8   451.8  5281.7  452.07  5374.8  454.27    5498  459.79  5637.2   467.8
#Mann= 7 ,-1 , 0
  4594.7     .05       0    4690      .1       0  4876.5     .16       0
  4997.5     .07       0  5003.5     .16       0  5023.2     .05       0
  5110.7     .16       0
Bank Sta=4997.5,5003.5
XS Rating Curve= 0 ,0
Exp/Cntr=0.3,0.1

Type RM Length L Ch R = 1 ,5921    ,109,109,109
BEGIN DESCRIPTION:
MOORES BRANCH TRIBUTARY 3 13.1
END DESCRIPTION:
XS GIS Cut Line= 3
      3510825.49     10337878.76      3510294.28     10337524.62
       3509941.3     10337285.84
#Sta/Elev= 30
  4619.5   457.7  4698.6  455.75  4743.6  455.38  4785.7  454.27  4800.7  454.62
  4843.6  453.58  4851.8  453.34  4857.8  452.43  4872.8  452.89  4893.9  451.79
  4908.9  452.79  4944.9  452.09  4950.9  450.77  4959.8  450.56    4966  449.21
  4972.1  449.22    4993  445.69  4995.8  445.19    4999  445.69  5032.1  446.51
  5038.1  447.46  5053.1  446.95  5110.7  449.75    5148   450.1  5239.4  450.19
  5335.4  451.49  5342.3  451.52    5593  452.68  5683.1  454.72  5684.1  454.72
#Mann= 10 ,-1 , 0
  4619.5     .05       0  4843.6      .1       0  4959.8     .05       0
    4993     .04       0    4999     .05       0  5110.7     .16       0
    5148     .05       0  5335.4     .16       0  5342.3     .05       0
  5683.1     .16       0
Bank Sta=4993,4999
XS Rating Curve= 0 ,0
Exp/Cntr=0.3,0.1

Type RM Length L Ch R = 1 ,5812    ,274,274,274
BEGIN DESCRIPTION:
MOORES BRANCH TRIBUTARY 3 13.0
END DESCRIPTION:
XS GIS Cut Line= 3
      3510888.04     10337795.46      3510356.78     10337441.29
       3510002.6     10337201.69
#Sta/Elev= 30
  4646.6   456.8  4709.9  455.55  4822.5  453.56  4860.1  452.98  4883.5  452.24
  4913.5  448.14  4934.5  446.89  4942.2  446.79  4949.6  448.97  4955.6  447.49
  4964.6  449.94  4970.6  447.42  4975.8  447.59  4997.6  445.35  5000.4  444.85
  5003.6  445.35  5010.7  446.17  5063.7  450.12  5093.8   448.9  5144.9   450.7
    5223  450.68  5230.6  448.33    5253  450.57  5280.1  450.97  5289.2  449.88
    5367  451.53  5375.3  450.72  5447.7  453.12  5612.7  452.67  5712.7  453.86
#Mann= 8 ,-1 , 0
  4646.6      .1       0  4709.9     .05       0  4822.5     .16       0
  4860.1      .1       0  4975.8     .05       0  4997.6     .04       0
  5003.6     .05       0  5010.7     .16       0
Bank Sta=4997.6,5003.6
XS Rating Curve= 0 ,0
Exp/Cntr=0.3,0.1

Type RM Length L Ch R = 1 ,5538    ,395,395,395
BEGIN DESCRIPTION:
MOORES BRANCH TRIBUTARY 3 12.0
END DESCRIPTION:
XS GIS Cut Line= 3
      3510992.11     10337741.65      3510757.82     10337352.74
      3510580.84     10337066.45
#Sta/Elev= 30
  4663.1  457.48  4771.9  454.45  4850.5  453.16  4888.4  452.91  4919.4  450.97
  4925.3  451.68  4946.6  451.08    4955  450.48    4968  445.73  4977.7  444.99
  4983.5  445.94    4990  442.96    4996   442.8  4998.8   442.3    5002   442.8
  5013.3  443.82  5035.9  443.01  5048.4  444.98  5057.3  445.07  5063.1  446.37
  5084.5  446.41    5100  449.07  5130.2  450.66  5188.8  451.56  5194.7  451.07
  5210.1  451.96  5362.6  454.47  5368.5  453.91  5389.7  455.46  5453.7  456.65
#Mann= 4 ,-1 , 0
  4663.1      .1       0  4850.5     .16       0    4996     .07       0
    5002     .16       0
Bank Sta=4996,5002
XS Rating Curve= 0 ,0
Exp/Cntr=0.3,0.1

Type RM Length L Ch R = 1 ,5143    ,424,424,424
BEGIN DESCRIPTION:
MOORES BRANCH TRIBUTARY 3 11.0
END DESCRIPTION:
XS GIS Cut Line= 3
       3511242.1     10337491.63      3511142.11     10337241.64
      3510942.11     10336941.65
#Sta/Elev= 30
  4723.3  453.86  4798.2  451.72  4840.4  450.43  4894.3     450  4917.2  449.49
  4948.1  448.02    4971  447.37  4977.7  445.93  4989.9  441.44  4995.6  441.44
  4997.1  440.96  4999.8  440.46  5003.1  440.96  5015.1  441.65  5036.1  441.49
  5042.1  442.61  5051.1  441.44  5064.7  441.76  5072.2  444.55  5087.2  446.79
  5100.7  446.87    5149  448.83  5195.4  450.13  5216.4  451.48  5231.4  451.73
  5252.4  452.92  5294.5  454.56  5303.5  454.69  5324.6  455.82  5353.1  456.68
#Mann= 5 ,-1 , 0
  4723.3     .05       0  4798.2     .12       0  4997.1     .07       0
  5003.1     .12       0    5149     .16       0
Bank Sta=4997.1,5003.1
XS Rating Curve= 0 ,0
Exp/Cntr=0.3,0.1

Type RM Length L Ch R = 1 ,4719    ,440,440,440
BEGIN DESCRIPTION:
MOORES BRANCH TRIBUTARY 3 10.0
END DESCRIPTION:
XS GIS Cut Line= 3
      3511622.39     10337212.11      3511392.11     10336941.64
      3511221.38     10336790.26
#Sta/Elev= 30
  4647.9  448.87    4741  447.07  4800.1  445.92  4882.9  444.53  4889.5  443.63
  4897.2  444.31  4903.7  443.08  4911.2  443.53  4915.9  443.24    4918  443.11
  4924.6  441.23  4932.3  441.39  4938.9  439.89  4946.6  439.83  4953.1  439.06
  4967.4  438.41  4989.4   438.5    4996  438.31  4996.8  437.84  4999.6  437.34
  5002.8  437.84  5010.2  438.46  5031.1  443.15  5038.7  443.34  5045.4  444.25
  5080.3  445.61  5116.4  446.67  5144.9   448.4  5165.8  448.65  5231.3  450.92
#Mann= 8 ,-1 , 0
  4647.9     .05       0    4741     .16       0  4800.1     .12       0
  4915.9     .16       0  4953.1     .12       0  4996.8     .07       0
  5002.8     .12       0  5080.3     .16       0
Bank Sta=4996.8,5002.8
XS Rating Curve= 0 ,0
Exp/Cntr=0.3,0.1

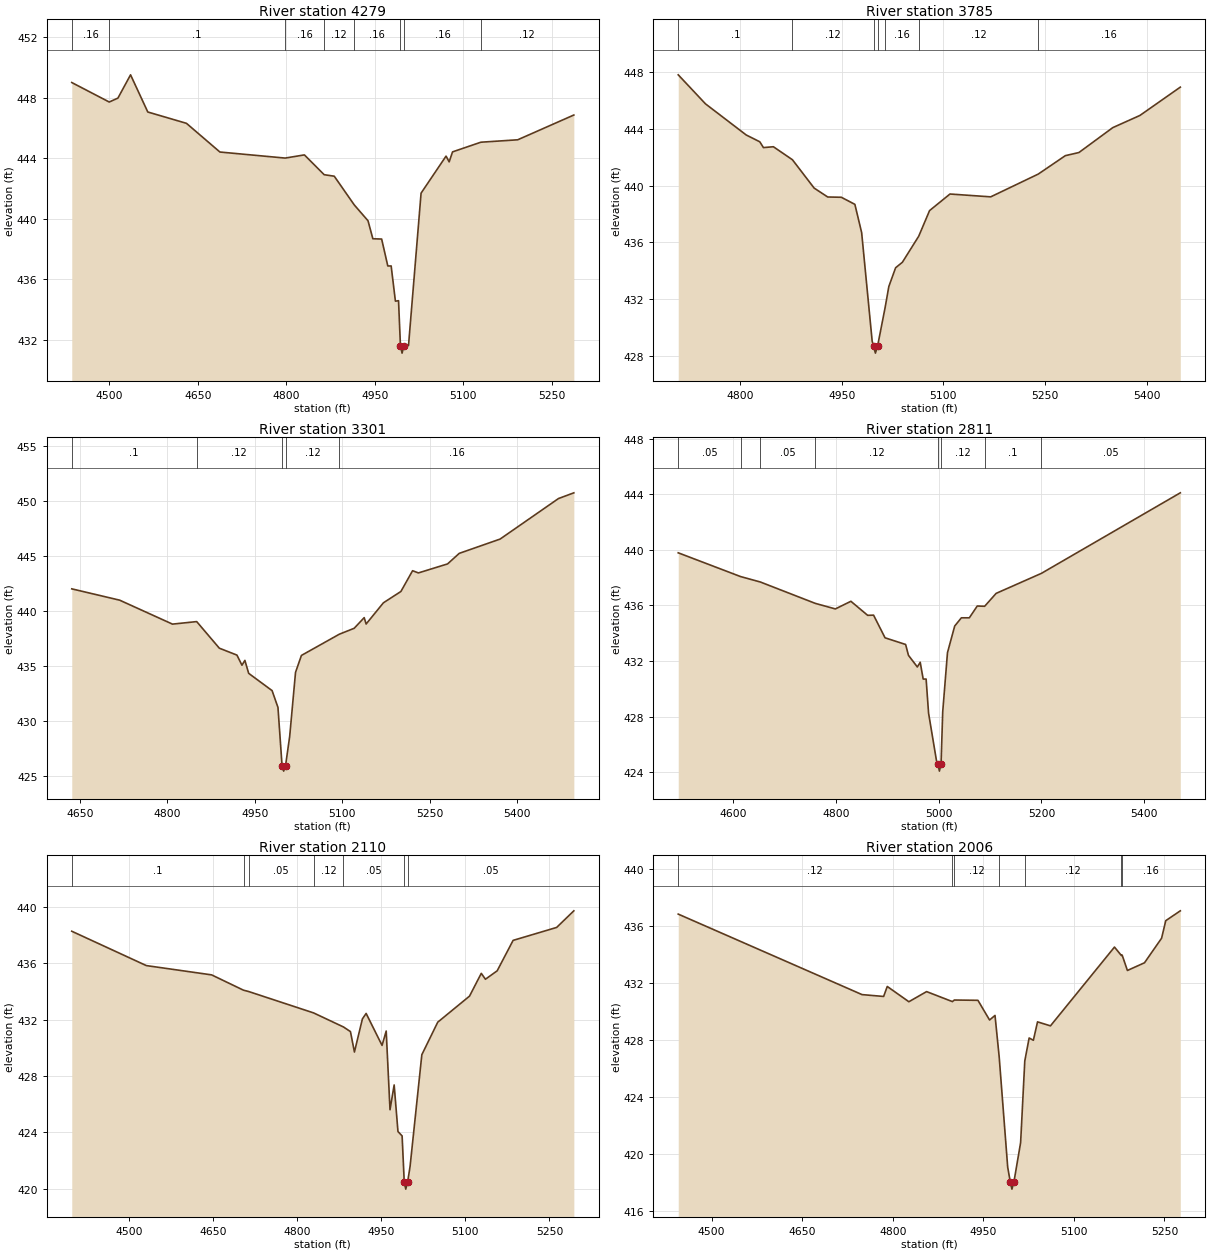
Type RM Length L Ch R = 1 ,4279    ,494,494,494
BEGIN DESCRIPTION:
MOORES BRANCH TRIBUTARY 3 9.0
END DESCRIPTION:
XS GIS Cut Line= 3
      3512033.82     10336899.59      3511592.11     10336591.64
      3511299.51     10336482.96
#Sta/Elev= 30
  4436.5  449.01    4500  447.72  4514.7  447.98  4536.1  449.52  4565.3  447.06
  4630.8  446.31  4687.5  444.41    4798  444.01  4830.6  444.22  4864.1  442.91
  4881.2  442.81  4915.1  440.91  4938.4  439.86  4946.6  438.67  4961.5  438.65
  4971.9  436.87  4977.6  436.87  4984.8  434.54  4990.1  434.57  4993.3   431.6
  4996.1   431.1  4999.3   431.6    5007   431.6  5028.3  441.69  5070.6  444.14
  5075.9  443.76  5081.6  444.42  5129.6  445.06    5192  445.22  5287.1  446.86
#Mann= 8 ,-1 , 0
  4436.5     .16       0    4500      .1       0    4798     .16       0
  4864.1     .12       0  4915.1     .16       0  4993.3     .07       0
  4999.3     .16       0  5129.6     .12       0
Bank Sta=4993.3,4999.3
XS Rating Curve= 0 ,0
Exp/Cntr=0.3,0.1

Type RM Length L Ch R = 1 ,3785    ,484,484,484
BEGIN DESCRIPTION:
MOORES BRANCH TRIBUTARY 3 8.0
END DESCRIPTION:
XS GIS Cut Line= 3
       3511992.2     10336128.79      3511452.52     10336162.48
      3511252.55     10336162.48
#Sta/Elev= 30
  4708.9  447.83  4749.1  445.78  4809.2  443.58  4829.2   443.1  4834.6  442.69
  4849.3  442.75  4877.4  441.83  4909.4  439.83  4929.4   439.2  4949.5  439.18
  4969.5  438.68  4979.5  436.68    4995  429.02    4997  428.67  4999.8  428.17
    5003  428.67    5014  431.36  5019.6  432.88  5029.6   434.2  5039.6  434.59
  5063.7  436.43  5079.7  438.24  5109.8  439.41  5169.9  439.21  5240.1  440.82
    5280  442.12    5300  442.34    5350   444.1    5390  444.96  5449.6  446.96
#Mann= 7 ,-1 , 0
  4708.9      .1       0  4877.4     .12       0    4997     .07       0
    5003     .12       0    5014     .16       0  5063.7     .12       0
  5240.1     .16       0
Bank Sta=4997,5003
XS Rating Curve= 0 ,0
Exp/Cntr=0.3,0.1

Type RM Length L Ch R = 1 ,3301    ,490,490,490
BEGIN DESCRIPTION:
MOORES BRANCH TRIBUTARY 3 7.0
END DESCRIPTION:
XS GIS Cut Line= 3
      3512033.86     10335785.04      3511530.65     10335736.43
      3511175.77     10335743.34
#Sta/Elev= 30
  4636.3  441.99  4718.4  440.96  4808.9  438.78  4850.4  439.01  4889.2  436.59
  4919.4  435.96    4928  435.04    4933  435.48  4939.5   434.3  4979.6  432.73
  4989.7   431.2  4996.7   425.9  4999.5   425.4  5002.7   425.9  5009.8  428.57
  5019.8  434.39  5029.9  435.93  5094.8  437.86  5120.3   438.4  5137.5  439.37
  5140.8  438.79  5170.4  440.72  5200.4  441.75  5220.4  443.64  5230.4  443.44
  5280.4  444.26  5300.4  445.22  5370.4  446.52  5470.5  450.21  5496.8  450.73
#Mann= 5 ,-1 , 0
  4636.3      .1       0  4850.4     .12       0  4996.7     .07       0
  5002.7     .12       0  5094.8     .16       0
Bank Sta=4996.7,5002.7
XS Rating Curve= 0 ,0
Exp/Cntr=0.3,0.1

Type RM Length L Ch R = 1 ,2811    ,701,701,701
BEGIN DESCRIPTION:
MOORES BRANCH TRIBUTARY 3 6.0
END DESCRIPTION:
XS GIS Cut Line= 3
      3512226.58     10335545.46      3511792.11     10335341.64
       3511367.2     10335081.91
#Sta/Elev= 30
  4492.7  439.79  4614.1  438.08  4652.5  437.69  4759.6  436.15  4798.7  435.75
    4829   436.3  4861.6  435.29  4873.2   435.3  4895.5  433.67  4935.6  433.19
  4941.1  432.41  4958.4  431.57    4964  431.91  4969.8   430.7  4975.5   430.7
  4980.3  428.24  4995.8   424.8  4998.6  424.57  5001.4  424.07  5004.6  424.57
  5007.8  428.32  5017.1   432.6  5031.2  434.52  5044.2  435.11  5059.7  435.11
  5075.1  435.96  5089.5  435.94  5111.9  436.87    5200  438.31  5470.6  444.11
#Mann= 8 ,-1 , 0
  4492.7     .05       0  4614.1      .1       0  4652.5     .05       0
  4759.6     .12       0  4998.6     .07       0  5004.6     .12       0
  5089.5      .1       0    5200     .05       0
Bank Sta=4998.6,5004.6
XS Rating Curve= 0 ,0
Exp/Cntr=0.3,0.1

Type RM Length L Ch R = 1 ,2110    ,104,104,104
BEGIN DESCRIPTION:
MOORES BRANCH TRIBUTARY 3 5.0
END DESCRIPTION:
XS GIS Cut Line= 3
      3512643.25      10335196.5      3512445.32     10335066.29
      3511956.39     10334624.17
#Sta/Elev= 30
  4397.4  438.29  4530.5  435.85    4647  435.19    4704   434.1  4712.9  434.01
  4828.9  432.49  4882.3  431.49  4894.8  431.16  4901.9  429.71  4916.1  432.06
  4922.8  432.45  4951.2  430.18  4958.6   431.2  4965.4  425.61  4972.8  427.37
  4979.6  424.06    4987  423.75  4990.8  420.47  4993.5  419.97  4996.8  420.47
  5001.2  421.58  5022.2  429.52  5050.6  431.83  5107.3  433.68  5128.3   435.3
  5135.7  434.88  5156.7  435.48  5185.1  437.64  5262.8  438.56  5293.5  439.74
#Mann= 7 ,-1 , 0
  4397.4      .1       0    4704     .12       0  4712.9     .05       0
  4828.9     .12       0  4882.3     .05       0  4990.8     .04       0
  4996.8     .05       0
Bank Sta=4990.8,4996.8
XS Rating Curve= 0 ,0
Exp/Cntr=0.3,0.1

Type RM Length L Ch R = 1 ,2006    ,607,607,607
BEGIN DESCRIPTION:
MOORES BRANCH TRIBUTARY 3 4.0
END DESCRIPTION:
XS GIS Cut Line= 3
      3512674.45     10335081.89      3512351.57     10334857.95
      3512049.51     10334540.27
#Sta/Elev= 30
  4444.9  436.82  4749.2  431.18    4785  431.05    4791  431.75  4826.8  430.68
  4856.1  431.39  4898.8  430.69  4902.1   430.8  4941.1  430.78  4960.4   429.4
  4969.4  429.72  4976.3  426.82  4990.4  419.09  4994.7  418.05  4997.4  417.55
  5000.7  418.05  5011.8  420.81  5018.7  426.53  5025.9  428.14  5032.9  427.98
  5039.8  429.27  5061.2  428.99  5167.2  434.51  5178.6  433.92  5179.9  433.95
  5188.6  432.87  5216.9  433.41  5245.2  435.13  5252.1  436.36  5276.2  437.05
#Mann= 7 ,-1 , 0
  4444.9     .12       0  4898.8     .16       0  4902.1     .12       0
  4976.3     .05       0  5018.7     .12       0  5178.6     .05       0
  5179.9     .16       0
Bank Sta=4994.7,5000.7
XS Rating Curve= 0 ,0
Exp/Cntr=0.3,0.1

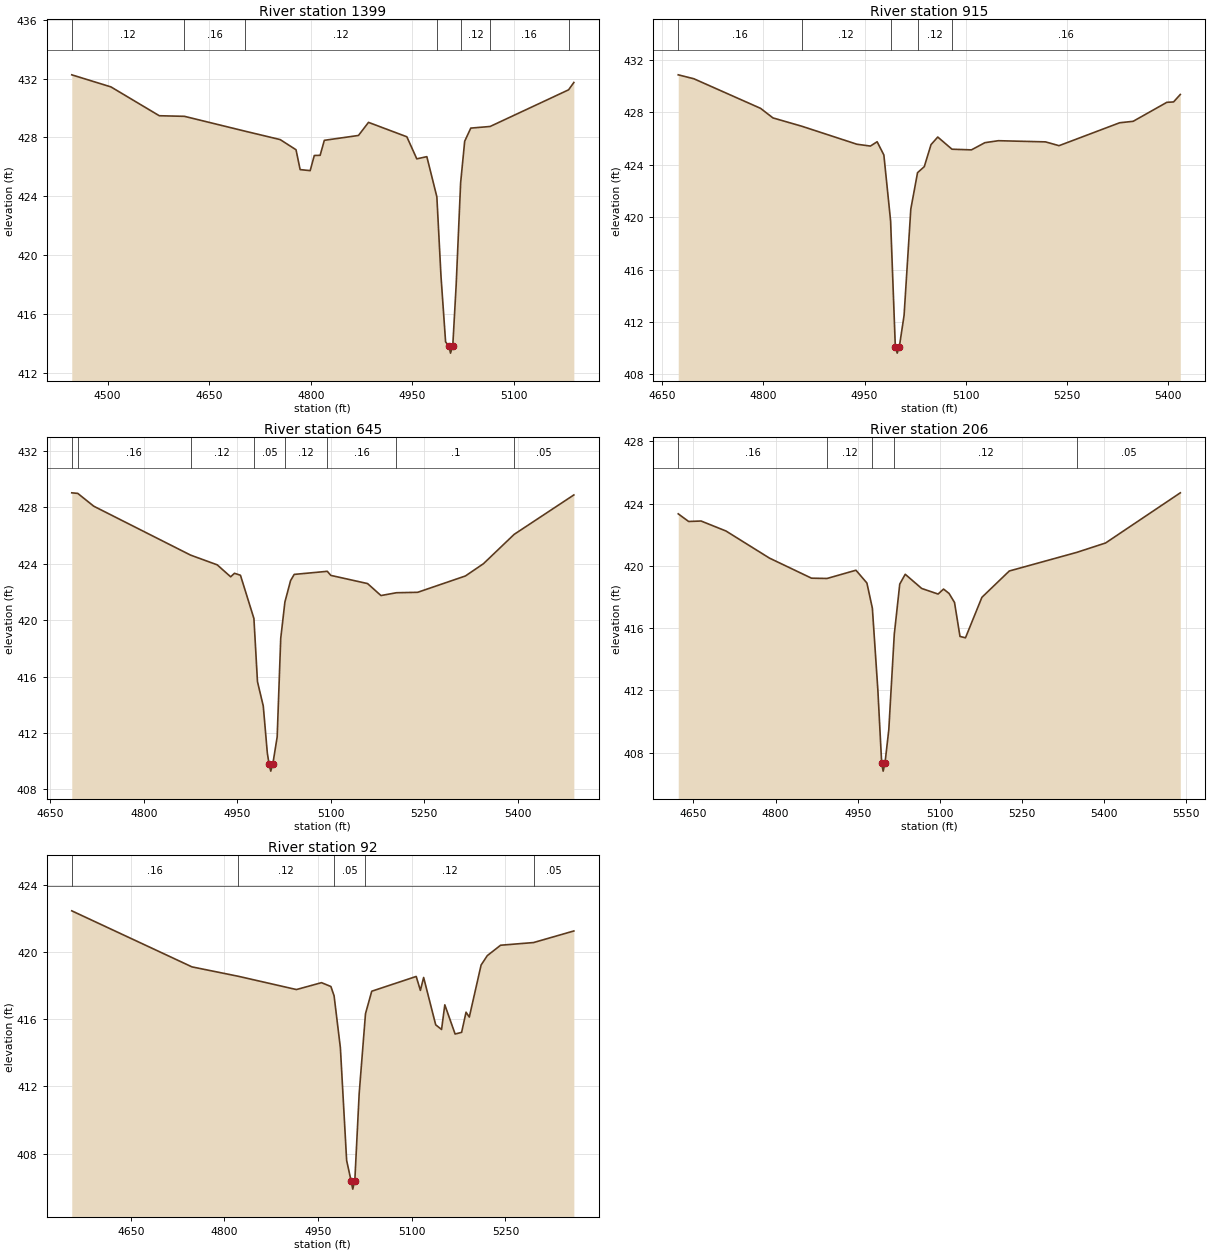
Type RM Length L Ch R = 1 ,1399    ,484,484,484
BEGIN DESCRIPTION:
MOORES BRANCH TRIBUTARY 3 3.0
END DESCRIPTION:
XS GIS Cut Line= 3
      3512792.12     10334691.66      3512467.58     10334234.33
      3512317.54     10334134.31
#Sta/Elev= 30
  4447.1  432.25  4504.9  431.43  4576.3  429.47  4613.4  429.43    4703  428.42
  4754.7  427.85  4778.1  427.16  4784.2  425.81    4799  425.74  4805.1  426.77
  4813.7  426.78  4819.9   427.8  4870.3  428.13  4885.1  429.02  4941.7  428.04
  4956.4  426.54  4971.2  426.69    4986  423.96  4992.1  418.57  4998.9   414.1
  5003.5  413.84  5006.2  413.34  5009.5  413.84  5014.5  417.97  5021.1  424.92
  5027.1  427.74  5036.1  428.63  5064.6  428.74  5180.4  431.23  5188.2  431.73
#Mann= 7 ,-1 , 0
  4447.1     .12       0  4613.4     .16       0    4703     .12       0
    4986     .05       0  5021.1     .12       0  5064.6     .16       0
  5180.4     .05       0
Bank Sta=5003.5,5009.5
XS Rating Curve= 0 ,0
Exp/Cntr=0.3,0.1

Type RM Length L Ch R = 1 ,915     ,270,270,270
BEGIN DESCRIPTION:
MOORES BRANCH TRIBUTARY 3 2.0
END DESCRIPTION:
XS GIS Cut Line= 3
      3513095.89     10334090.71      3512995.88      10333990.7
      3512392.12     10333991.64
#Sta/Elev= 30
  4673.5  430.87  4696.7  430.57  4795.7  428.31  4814.1  427.58  4857.2  426.94
  4938.7  425.57  4958.7  425.43  4968.7  425.76  4978.7  424.75  4988.7  419.72
  4995.7  410.12  4998.5  409.62  5001.7  410.12  5008.7   412.5  5018.7  420.62
  5028.7   423.4  5038.7  423.86  5048.7  425.54  5058.7  426.12  5079.8  425.19
  5108.7  425.14  5128.7  425.69  5148.7  425.84  5218.7  425.75  5238.7  425.46
  5328.7  427.21  5348.7  427.32  5398.7  428.77  5408.7   428.8  5418.7  429.37
#Mann= 5 ,-1 , 0
  4673.5     .16       0  4857.2     .12       0  4988.7     .05       0
  5028.7     .12       0  5079.8     .16       0
Bank Sta=4995.7,5001.7
XS Rating Curve= 0 ,0
Exp/Cntr=0.3,0.1

Type RM Length L Ch R = 1 ,645     ,439,439,439
BEGIN DESCRIPTION:
MOORES BRANCH TRIBUTARY 3 1.011
END DESCRIPTION:
XS GIS Cut Line= 3
      3513158.06     10333924.04      3512614.64     10333609.79
      3512437.53     10333623.68
#Sta/Elev= 30
  4684.6  429.04  4694.2     429  4719.9  428.09  4875.2  424.62  4917.9  423.93
  4939.5  423.08  4945.6  423.33  4955.2  423.19  4976.8  420.12  4982.5  415.64
  4991.8  413.91  4998.3  410.58  5001.1  409.79  5003.8  409.29  5007.1  409.79
  5014.1  411.72  5019.8  418.71  5026.5  421.29  5035.6  422.81  5041.4  423.25
  5094.5  423.47  5100.2  423.18  5159.1   422.6  5180.6  421.75  5205.5  421.95
  5239.5  421.98  5316.1  423.14    5345  424.01  5394.2  426.09    5490  428.89
#Mann= 8 ,-1 , 0
  4684.6     .05       0  4694.2     .16       0  4875.2     .12       0
  4976.8     .05       0  5026.5     .12       0  5094.5     .16       0
  5205.5      .1       0  5394.2     .05       0
Bank Sta=5001.1,5007.1
XS Rating Curve= 0 ,0
Exp/Cntr=0.3,0.1

Type RM Length L Ch R = 1 ,206     ,114,114,114
BEGIN DESCRIPTION:
MOORES BRANCH TRIBUTARY 3 1.0
END DESCRIPTION:
XS GIS Cut Line= 4
      3513402.42     10333475.68      3513178.44      10333368.9
      3512692.76     10333376.71      3512553.41     10333495.23
#Sta/Elev= 30
  4622.3  423.34  4641.3  422.85    4664  422.88  4709.4  422.24  4788.8   420.5
  4865.6  419.21    4894  419.19  4946.8  419.72  4966.8   418.9  4976.8  417.28
  4986.8  412.04  4993.8  407.32  4996.5  406.82  4999.8  407.32  5006.8  409.48
  5016.8   415.6  5026.8  418.83  5036.8  419.46  5066.8  418.55  5096.8  418.19
  5106.8  418.51  5116.8  418.23  5126.8  417.65  5136.8  415.47  5146.8  415.38
  5176.8  417.98  5226.8  419.67  5350.4  420.87  5402.7  421.47  5539.1  424.69
#Mann= 5 ,-1 , 0
  4622.3     .16       0    4894     .12       0  4976.8     .05       0
  5016.8     .12       0  5350.4     .05       0
Bank Sta=4993.8,4999.8
XS Rating Curve= 0 ,0
Exp/Cntr=0.3,0.1

Type RM Length L Ch R = 1 ,92      ,0,0,0
BEGIN DESCRIPTION:
MOORES BRANCH TRIBUTARY 3 1.01
END DESCRIPTION:
XS GIS Cut Line= 4
      3513413.89     10333419.64      3513099.16     10333260.58
      3512926.57      10333277.5      3512659.21     10333353.08
#Sta/Elev= 30
  4555.6  422.46  4748.1  419.12  4822.3  418.56  4915.3  417.77  4955.5  418.18
  4970.5  417.95  4975.6   417.4  4985.7   414.3  4995.7  407.59  5002.8  406.38
  5005.5  405.88  5008.8  406.38  5015.8  411.58  5025.9  416.33  5035.9  417.67
  5107.1  418.55  5113.8  417.72    5119  418.49  5138.3  415.67  5147.7  415.39
  5152.9  416.86  5169.4  415.12  5179.8  415.22  5186.9  416.42  5192.1  416.13
    5211  419.23  5220.9  419.79  5242.2  420.41    5295  420.57  5359.5  421.26
#Mann= 5 ,-1 , 0
  4555.6     .16       0  4822.3     .12       0  4975.6     .05       0
  5025.9     .12       0    5295     .05       0
Bank Sta=5002.8,5008.8
XS Rating Curve= 0 ,0
Exp/Cntr=0.3,0.1

Chan Stop Cuts=-1
Use User Specified Reach Order=0
Composite Channel Slope=5