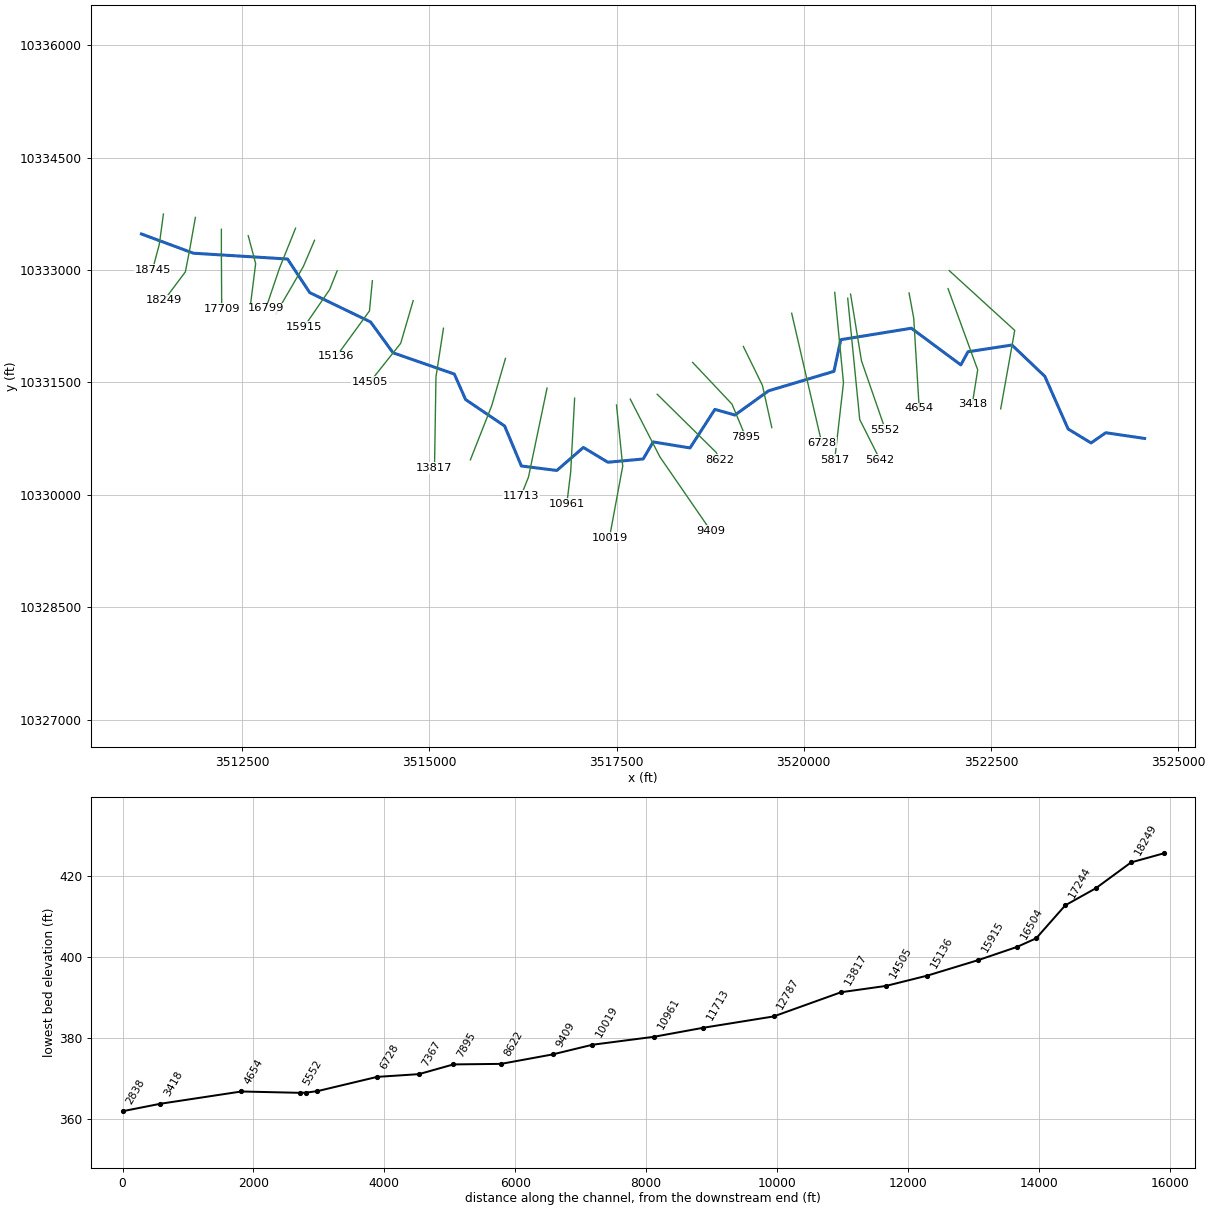
--- MOORES BRANCH.prj (project) ---

Proj Title=MOORES BRANCH Base Level Engineering
Current Plan=p01
Default Exp/Contr=0.3,0.1
English Units
Geom File=g01
Flow File=f01
Plan File=p01
Y Axis Title=Elevation
X Axis Title(PF)=Main Channel Distance
X Axis Title(XS)=Station
BEGIN DESCRIPTION:
MOORES BRANCH
END DESCRIPTION:
DSS Export Rating Curves= 0
DSS Export Rating Curve Sorted= 0
DSS Export Volume Flow Curves= 0
DXF OffsetX= 0
DXF OffsetY= 0
DXF ScaleX= 1
DXF ScaleY= 10

--- MOORES BRANCH.p01 (plan) ---

Plan Title=Multiple Run
Short Identifier=Multiple
Geom File=g01
Flow File=f01
Subcritical Flow
K Sum by GR= 0
Std Step Tol= 0.01
Critical Tol= 0.01
Num of Std Step Trials= 20
Max Error Tol= 0.3
Flow Tol Ratio= 0.001
Split Flow NTrial= 30
Split Flow Tol= 0.02
Split Flow Ratio= 0.02
Log Output Level= 0
Friction Slope Method= 1
Unsteady Friction Slope Method= 2
Unsteady Bridges Friction Slope Method= 1
Parabolic Critical Depth
Global Vel Dist=  1 , 1 , 1
Global Log Level= 0
CheckData=True
Encroach Param= -1, 0, 0, 0
BEGIN DESCRIPTION:
Multiple Run
END DESCRIPTION:

--- MOORES BRANCH.f01 (steady flow) ---

Flow Title=Multiple
Program Version=4.10
Number of Profiles= 7
Profile Names=10-year,25-year,50-year,1pct_min,100-year,1pct_plu,500-year
River Rch & RM=MOORES BRANCH,Reach-1         ,18745
     530     722     879     786    1063    1437    1557
River Rch & RM=MOORES BRANCH,Reach-1         ,16799
    1042    1465    1824    1660    2245    3036    3416
River Rch & RM=MOORES BRANCH,Reach-1         ,13817
    1625    2332    2941    2709    3663    4954    5708
River Rch & RM=MOORES BRANCH,Reach-1         ,12787
    1625    2332    2941    2709    3663    4954    5708
River Rch & RM=MOORES BRANCH,Reach-1         ,7895
    1805    2595    3277    3020    4084    5524    6374
River Rch & RM=MOORES BRANCH,Reach-1         ,5642
    1850    2660    3358    3095    4186    5661    6530
Boundary for River Rch & Prof#=MOORES BRANCH,Reach-1         , 1
Up Type= 0
Dn Type= 3
Dn Slope=0.005
Boundary for River Rch & Prof#=MOORES BRANCH,Reach-1         , 2
Up Type= 0
Dn Type= 3
Dn Slope=0.005
Boundary for River Rch & Prof#=MOORES BRANCH,Reach-1         , 3
Up Type= 0
Dn Type= 3
Dn Slope=0.005
Boundary for River Rch & Prof#=MOORES BRANCH,Reach-1         , 4
Up Type= 0
Dn Type= 3
Dn Slope=0.005
Boundary for River Rch & Prof#=MOORES BRANCH,Reach-1         , 5
Up Type= 0
Dn Type= 3
Dn Slope=0.005
Boundary for River Rch & Prof#=MOORES BRANCH,Reach-1         , 6
Up Type= 0
Dn Type= 3
Dn Slope=0.005
Boundary for River Rch & Prof#=MOORES BRANCH,Reach-1         , 7
Up Type= 0
Dn Type= 3
Dn Slope=0.005
DSS Import GetInterval= 0
DSS Import GetPeak= 0
DSS Import FillOption= 0

--- MOORES BRANCH.g01 (geometry) ---

Geom Title=Existing Conditions
Program Version=4.10

River Reach=MOORES BRANCH   ,Reach-1
Reach XY= 30
      3511153.41     10333480.34      3511848.07     10333223.53
      3513104.75     10333145.99      3513401.18     10332697.85
      3514214.27     10332305.96       3514513.9     10331894.47
      3515332.67     10331610.65      3515482.67      10331270.8
      3516004.28     10330917.93      3516228.06     10330384.17
       3516701.2     10330324.38      3517056.04      10330631.5
      3517383.73     10330434.01      3517855.05     10330477.73
      3517988.19     10330705.12      3518480.88     10330624.92
      3518812.73     10331139.56       3519080.8     10331064.03
      3519529.17     10331387.15      3520402.97     10331647.23
      3520494.42     10332069.65      3521437.08     10332222.47
      3522097.72     10331732.98      3522193.05     10331908.27
      3522780.78     10331998.27      3523219.54     10331580.52
      3523530.68     10330877.72      3523837.37     10330691.51
      3524033.28      10330827.9      3524552.11     10330751.64

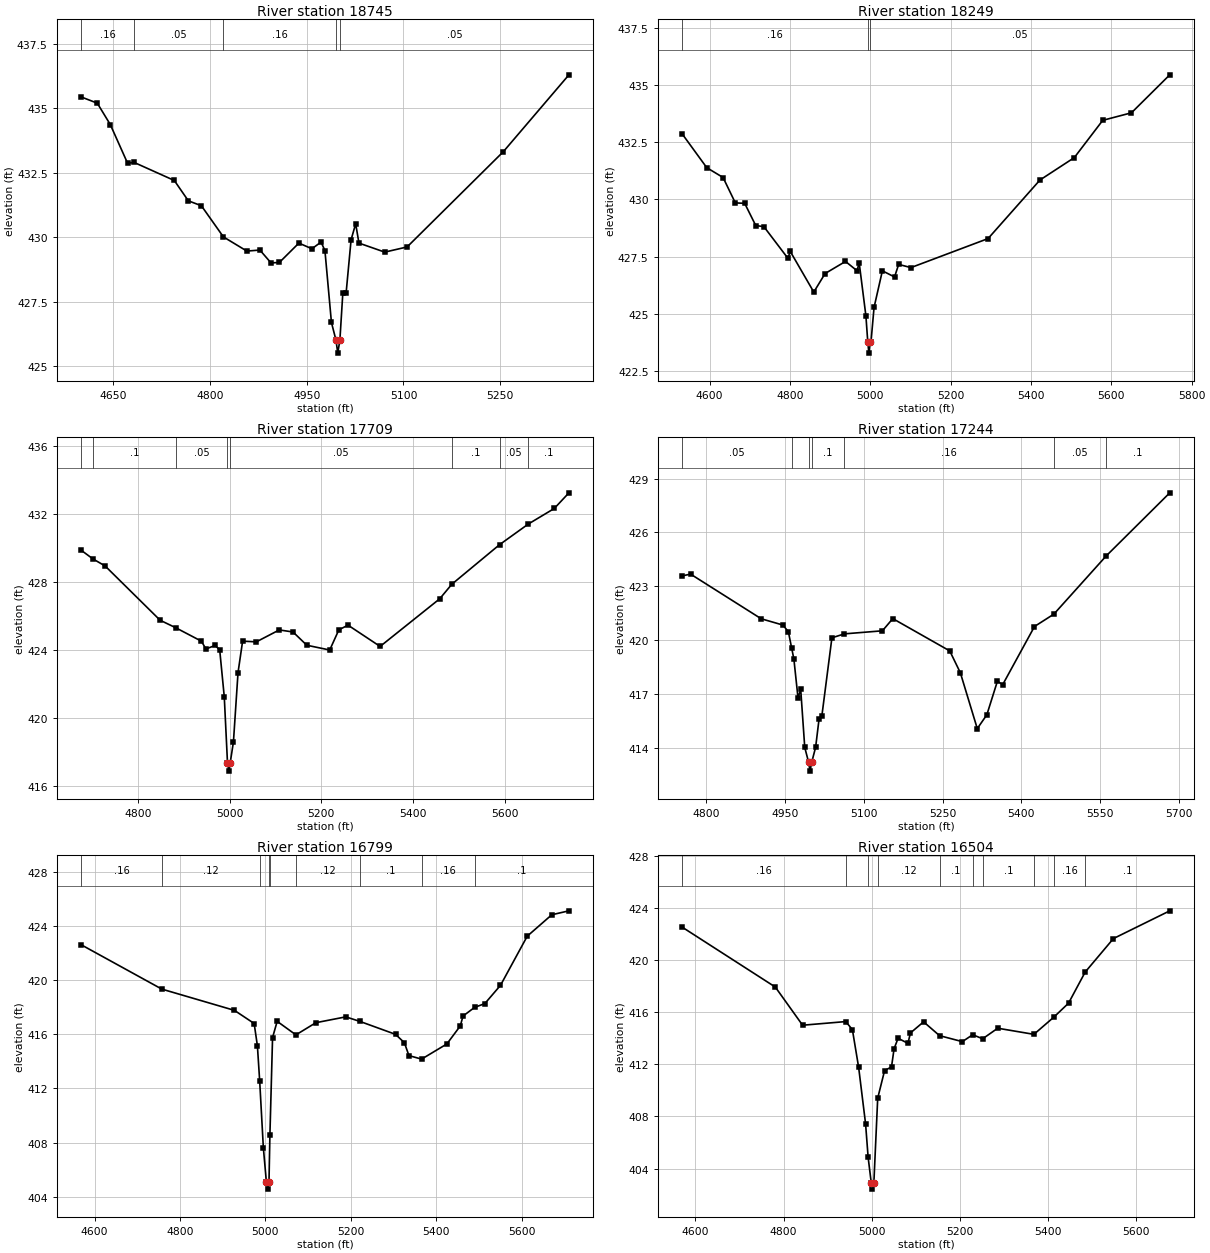
Type RM Length L Ch R = 1 ,18745   ,496,496,496
BEGIN DESCRIPTION:
MOORES BRANCH 26.0
END DESCRIPTION:
XS GIS Cut Line= 3
      3511446.95     10333746.23      3511392.11     10333341.64
      3511301.47     10333005.33
#Sta/Elev= 30
  4600.1  435.44  4624.9   435.2  4645.1  434.37  4671.9  432.87  4682.1   432.9
  4744.4   432.2  4766.2  431.41  4786.4  431.22  4820.6  430.01    4857  429.46
  4877.2   429.5  4894.5     429  4907.5  429.02  4937.7  429.77  4957.9  429.55
  4972.1  429.81  4978.1  429.48  4988.2  426.69  4995.3     426    4998   425.5
  5001.3     426  5005.9  427.84    5011  427.84  5018.7   429.9  5025.8  430.52
  5030.9  429.77  5070.9  429.42  5105.6  429.62    5255  433.32  5356.7   436.3
#Mann= 5 ,-1 , 0
  4600.1     .16       0  4682.1     .05       0  4820.6     .16       0
  4995.3     .03       0  5001.3     .05       0
Bank Sta=4995.3,5001.3
XS Rating Curve= 0 ,0
Exp/Cntr=0.3,0.1

Type RM Length L Ch R = 1 ,18249   ,540,540,540
BEGIN DESCRIPTION:
MOORES BRANCH 25.0
END DESCRIPTION:
XS GIS Cut Line= 4
      3511874.04     10333701.97      3511792.11     10333241.64
      3511739.78      10332974.6      3511455.39     10332595.37
#Sta/Elev= 30
  4531.8  432.87  4593.1  431.39  4633.7  430.96  4664.2  429.85  4687.5  429.83
    4715  428.86  4735.3  428.81  4795.4  427.42  4800.5  427.74  4859.5  425.95
  4887.6  426.76  4938.4  427.29  4967.3  426.88  4972.4  427.24  4989.2  424.91
  4993.8  423.78  4996.6  423.28  4999.8  423.78  5001.9  423.78  5009.5  425.28
  5030.2  426.88  5060.5  426.61  5070.7  427.16  5101.3  427.02  5293.3  428.29
  5422.4  430.85  5507.9  431.83  5578.7  433.46  5650.2  433.79  5745.5  435.45
#Mann= 3 ,-1 , 0
  4531.8     .16       0  4993.8     .03       0  4999.8     .05       0
Bank Sta=4993.8,4999.8
XS Rating Curve= 0 ,0
Exp/Cntr=0.3,0.1

Type RM Length L Ch R = 1 ,17709   ,465,465,465
BEGIN DESCRIPTION:
MOORES BRANCH 24.0
END DESCRIPTION:
XS GIS Cut Line= 3
      3512220.75     10333543.69      3512220.75     10333293.73
      3512225.32      10332479.6
#Sta/Elev= 30
  4676.2  429.87  4701.3  429.37  4728.2  428.95  4848.2  425.76  4882.2  425.32
  4938.2  424.53  4948.2  424.07  4968.2  424.28  4978.2  424.02  4988.2  421.26
  4995.2  417.39    4998  416.89  5001.2  417.39  5008.2  418.61  5018.2  422.68
  5028.2  424.53  5058.2  424.49  5108.2  425.19  5138.2  425.07  5168.3  424.29
  5218.3  424.01  5238.3   425.2  5258.3  425.47  5328.3  424.22  5458.3  427.02
  5484.9  427.88  5588.8   430.2  5651.9  431.42  5708.3  432.33  5740.3  433.25
#Mann= 8 ,-1 , 0
  4676.2     .05       0  4701.3      .1       0  4882.2     .05       0
  4995.2     .03       0  5001.2     .05       0  5484.9      .1       0
  5588.8     .05       0  5651.9      .1       0
Bank Sta=4995.2,5001.2
XS Rating Curve= 0 ,0
Exp/Cntr=0.3,0.1

Type RM Length L Ch R = 1 ,17244   ,445,445,445
BEGIN DESCRIPTION:
MOORES BRANCH 23.0
END DESCRIPTION:
XS GIS Cut Line= 3
      3512579.76     10333457.17      3512678.72     10333084.77
      3512611.07     10332546.13
#Sta/Elev= 30
  4754.3  423.58  4770.4  423.68  4904.9  421.19  4946.3  420.84  4956.6  420.46
  4962.7  419.57    4967  418.95  4974.9  416.77    4980  417.26  4987.7  414.02
    4995   413.2  4997.8   412.7    5001   413.2  5008.4  414.03    5015  415.62
  5020.2  415.76  5039.4  420.13  5063.2  420.35  5135.5  420.52  5155.3   421.2
  5263.7   419.4  5283.9  418.18  5316.1  415.07  5334.3  415.84  5354.4  417.71
  5364.5  417.52    5425  420.76  5461.9  421.45  5561.4  424.69  5682.5  428.21
#Mann= 7 ,-1 , 0
  4754.3     .05       0  4962.7      .1       0    4995     .07       0
    5001      .1       0  5063.2     .16       0  5461.9     .05       0
  5561.4      .1       0
Bank Sta=4995,5001
XS Rating Curve= 0 ,0
Exp/Cntr=0.3,0.1

Type RM Length L Ch R = 1 ,16799   ,295,295,295
BEGIN DESCRIPTION:
MOORES BRANCH 22.01
END DESCRIPTION:
XS GIS Cut Line= 3
      3513211.95     10333557.24      3512997.63     10333024.82
      3512814.89     10332486.74
#Sta/Elev= 30
  4568.9   422.6  4757.5  419.33  4927.6  417.76  4973.8  416.79  4981.4  415.14
  4986.8  412.51  4995.3  407.63  5002.5  405.06  5005.3  404.56  5008.5  405.06
  5010.7  408.57  5016.9  415.75  5027.7  416.95  5071.6  415.95  5118.4  416.85
  5188.4  417.28    5221  416.95  5304.9  415.99  5325.7  415.37  5336.3  414.42
    5366  414.16  5425.2  415.28  5456.6  416.61    5463  417.34  5490.1  417.98
  5514.1  418.26  5550.8  419.61  5613.5  423.24    5671  424.82  5711.1  425.11
#Mann= 9 ,-1 , 0
  4568.9     .16       0  4757.5     .12       0  4986.8     .07       0
  5008.5     .12       0  5010.7     .16       0  5071.6     .12       0
    5221      .1       0    5366     .16       0  5490.1      .1       0
Bank Sta=5002.5,5008.5
XS Rating Curve= 0 ,0
Exp/Cntr=0.3,0.1

Type RM Length L Ch R = 1 ,16504   ,589,589,589
BEGIN DESCRIPTION:
MOORES BRANCH 22.0
END DESCRIPTION:
XS GIS Cut Line= 3
      3513465.55     10333395.83      3513315.54     10333045.81
      3512951.29     10332418.97
#Sta/Elev= 30
  4570.1  422.53  4781.4  417.93  4843.3     415  4941.2  415.28  4956.2  414.66
  4970.4  411.76  4986.1  407.43  4991.9  404.86  4998.9  402.92  5001.6  402.42
  5004.9  402.92  5013.6   409.4  5029.2  411.52  5044.9   411.8  5050.7  413.19
  5059.8     414  5082.1  413.61  5087.9  414.41  5117.7  415.26  5153.8   414.2
  5205.5  413.74    5229  414.27  5251.6  413.96  5285.8  414.77  5367.8   414.3
    5413  415.62  5446.3  416.69  5484.1  419.08  5548.1  421.65  5675.9  423.78
#Mann= 10 ,-1 , 0
  4570.1     .16       0  4941.2     .12       0  4991.9     .07       0
  5013.6     .12       0  5153.8      .1       0    5229     .12       0
  5251.6      .1       0  5367.8     .12       0    5413     .16       0
  5484.1      .1       0
Bank Sta=4998.9,5004.9
XS Rating Curve= 0 ,0
Exp/Cntr=0.3,0.1

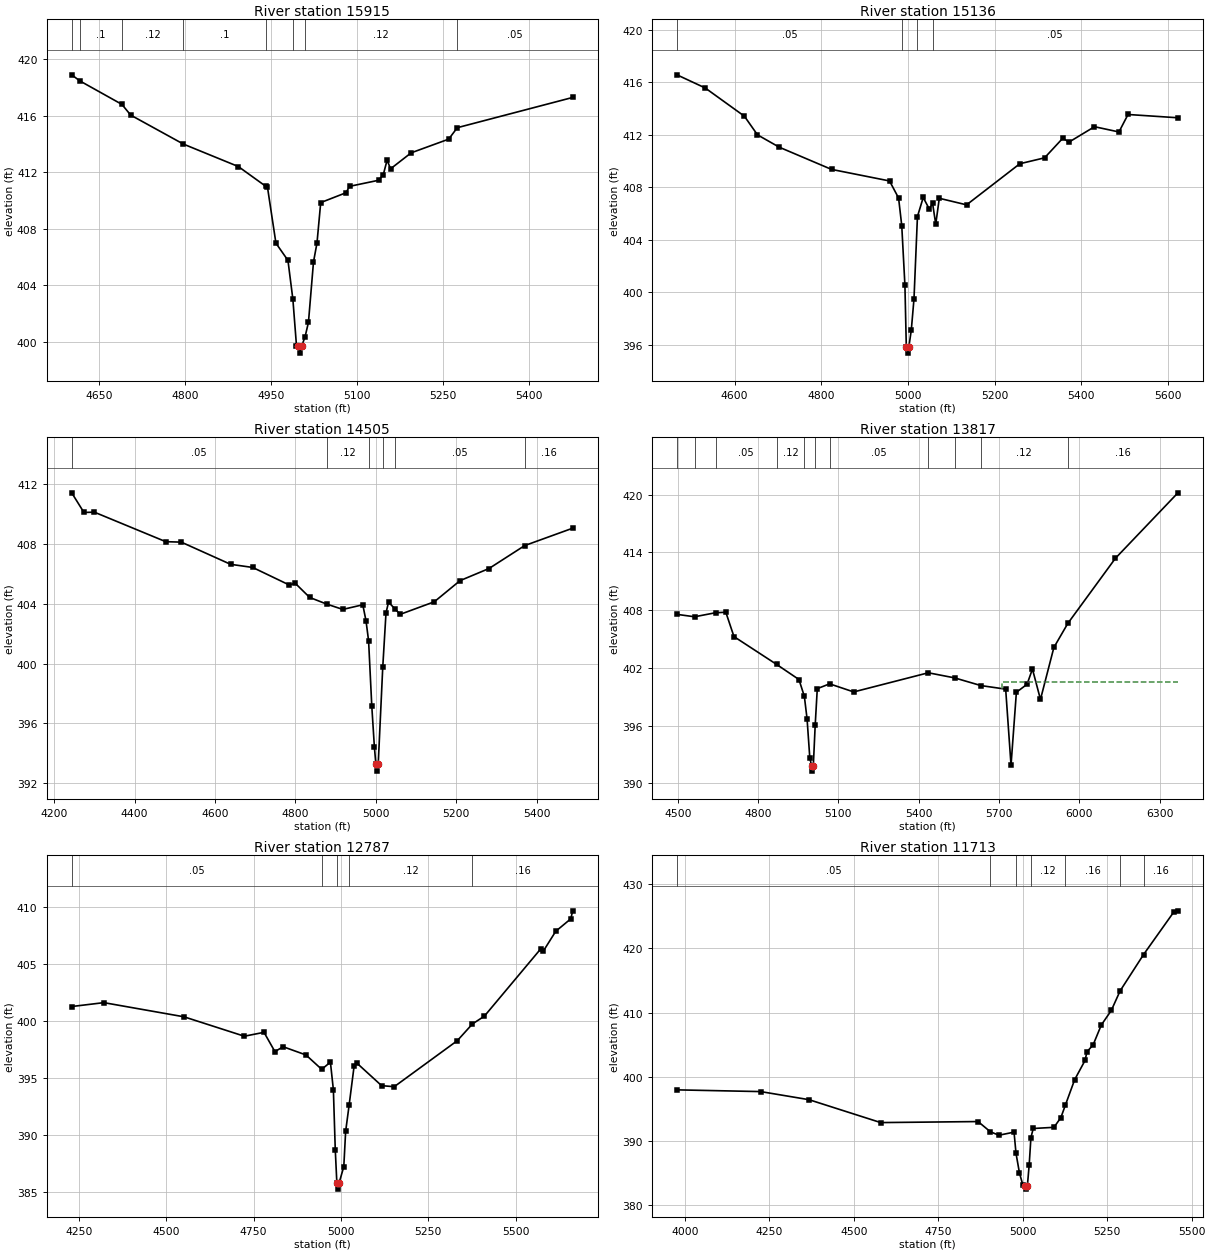
Type RM Length L Ch R = 1 ,15915   ,779,779,779
BEGIN DESCRIPTION:
MOORES BRANCH 21.0
END DESCRIPTION:
XS GIS Cut Line= 3
       3513767.1     10332987.97      3513667.11       10332738.
      3513323.66     10332239.24
#Sta/Elev= 30
  4601.7  418.88  4615.9  418.45  4689.3  416.79  4704.7  416.03  4796.7  413.98
  4892.7  412.39  4940.7  410.99  4943.4  410.97  4958.3  406.97  4979.3  405.75
  4987.9     403  4994.2  399.71  4997.2  399.69    5000  399.19  5003.2  399.69
  5009.1  400.33  5015.1  401.37  5023.9  405.64    5030  406.98  5036.5  409.84
  5080.8  410.54  5086.8  410.99  5137.6  411.42  5145.8  411.82  5152.4  412.84
  5158.5  412.23  5194.4  413.36    5260  414.33    5275  415.14  5476.5  417.28
#Mann= 8 ,-1 , 0
  4601.7     .12       0  4615.9      .1       0  4689.3     .12       0
  4796.7      .1       0  4940.7     .12       0  4987.9     .07       0
  5009.1     .12       0    5275     .05       0
Bank Sta=4997.2,5003.2
XS Rating Curve= 0 ,0
Exp/Cntr=0.3,0.1

Type RM Length L Ch R = 1 ,15136   ,631,631,631
BEGIN DESCRIPTION:
MOORES BRANCH 20.0
END DESCRIPTION:
XS GIS Cut Line= 3
      3514237.75     10332856.43      3514198.69     10332452.82
      3513756.75      10331847.1
#Sta/Elev= 30
  4467.3  416.55  4532.4  415.55  4622.8   413.4    4653  411.98  4703.2  411.04
  4823.7  409.35  4957.5  408.47  4978.4  407.17  4985.7  405.07    4993  400.53
  4996.2  395.86    4999  395.36  5002.2  395.86  5007.7  397.11  5013.9  399.48
  5021.9  405.76  5035.2  407.21  5049.4  406.32  5056.7  406.78  5064.1  405.18
  5072.3  407.15  5135.2  406.65    5258  409.78  5315.1  410.23    5357  411.72
  5371.5  411.43  5430.2   412.6  5486.6   412.2  5507.5  413.53  5622.6  413.28
#Mann= 4 ,-1 , 0
  4467.3     .05       0  4985.7     .07       0  5021.9     .16       0
  5056.7     .05       0
Bank Sta=4996.2,5002.2
XS Rating Curve= 0 ,0
Exp/Cntr=0.3,0.1

Type RM Length L Ch R = 1 ,14505   ,688,688,688
BEGIN DESCRIPTION:
MOORES BRANCH 19.0
END DESCRIPTION:
XS GIS Cut Line= 3
      3514782.88     10332590.83      3514616.22      10332021.4
      3514209.95     10331510.96
#Sta/Elev= 30
  4243.8  411.39  4274.2  410.08  4300.1   410.1  4477.7  408.13  4516.3   408.1
  4638.9  406.62  4693.9  406.41  4784.8  405.24  4799.4  405.36  4835.5  404.41
  4877.4  403.97  4917.9  403.61  4967.6  403.92  4975.6  402.85    4982  401.52
    4990  397.14  4996.4  394.44    5000  393.32  5002.7  392.82    5006  393.32
  5017.2  399.74  5025.3  403.38  5031.6  404.09  5048.3  403.63  5060.5  403.28
  5145.4  404.12  5209.4  405.53  5281.5  406.34  5370.2  407.87  5489.5  409.03
#Mann= 6 ,-1 , 0
  4243.8     .05       0  4877.4     .12       0    4982     .07       0
  5017.2     .12       0  5048.3     .05       0  5370.2     .16       0
Bank Sta=5000,5006
XS Rating Curve= 0 ,0
Exp/Cntr=0.3,0.1

Type RM Length L Ch R = 1 ,13817   ,1030,1030,1030
BEGIN DESCRIPTION:
MOORES BRANCH 18.0
END DESCRIPTION:
XS GIS Cut Line= 3
      3515187.24     10332222.15      3515087.24      10331572.2
      3515067.61     10330358.16
#Sta/Elev= 30
  4496.9  407.55  4562.7   407.3  4641.2  407.72  4679.5  407.77  4709.9  405.24
  4869.2  402.35  4952.7  400.78  4972.9  399.03  4983.1  396.67  4993.2  392.65
  5000.3  391.76    5003  391.26  5006.3  391.76  5013.4  396.04  5021.2  399.83
  5067.3  400.33  5157.3  399.49    5436  401.48  5534.3  400.95  5632.6  400.15
  5725.1  399.78  5745.1  391.88  5765.1  399.45  5805.1  400.29  5825.1  401.87
  5855.1  398.71  5905.2  404.11  5957.3  406.61  6135.2  413.38  6368.7  420.18
#Mann= 11 ,-1 , 0
  4496.9     .05       0  4562.7      .1       0  4641.2     .05       0
  4869.2     .12       0  4972.9     .07       0  5013.4     .12       0
  5067.3     .05       0    5436      .1       0  5534.3     .05       0
  5632.6     .12       0  5957.3     .16       0
#XS Ineff= 2 , 0
                         5711.65          400.56
Permanent Ineff=
       F       F
Bank Sta=5000.3,5006.3
XS Rating Curve= 0 ,0
Exp/Cntr=0.3,0.1

Type RM Length L Ch R = 1 ,12787   ,1074,1074,1074
BEGIN DESCRIPTION:
MOORES BRANCH 17.0
END DESCRIPTION:
XS GIS Cut Line= 3
      3516015.51     10331819.97       3515831.5     10331188.07
       3515547.1     10330466.65
#Sta/Elev= 30
  4229.5  401.28  4321.5  401.62  4550.8  400.38  4723.5  398.68  4779.8  399.02
    4811  397.33  4834.4  397.76  4899.8  397.04  4944.9  395.78  4969.8  396.41
  4978.3  393.99  4983.7  388.75  4988.3  385.79    4991  385.29  4994.3  385.79
  5008.1  387.26  5013.4  390.35  5023.5  392.68  5037.8  396.11    5045  396.34
  5116.3  394.35  5152.5  394.26  5332.9  398.29  5376.1  399.75  5410.5  400.44
  5571.7  406.33  5579.2  406.14  5614.7  407.87  5657.7  408.96  5663.1  409.66
#Mann= 5 ,-1 , 0
  4229.5     .05       0  4944.9     .12       0  4988.3     .07       0
  5023.5     .12       0  5376.1     .16       0
Bank Sta=4988.3,4994.3
XS Rating Curve= 0 ,0
Exp/Cntr=0.3,0.1

Type RM Length L Ch R = 1 ,11713   ,752,752,752
BEGIN DESCRIPTION:
MOORES BRANCH 16.0
END DESCRIPTION:
XS GIS Cut Line= 3
      3516571.08     10331424.19      3516322.66     10330235.39
       3516222.9     10329985.98
#Sta/Elev= 30
  3976.3  397.97  4224.1   397.7  4367.1  396.44  4579.5  392.87  4867.7  393.03
  4904.1  391.44  4929.4   390.9  4974.2  391.38  4980.1  388.06  4990.3  385.01
  5000.5  383.11  5007.7     383  5010.5   382.5  5013.7     383  5019.1  386.31
  5024.2  390.54  5031.1  391.95  5092.4  392.13  5112.9  393.65  5126.1  395.58
  5153.7  399.56  5184.4  402.55  5190.1   403.9  5208.4  404.99  5232.6  408.08
  5262.2  410.35  5288.2  413.39  5357.7  419.06    5448  425.75  5459.4  425.87
#Mann= 7 ,-1 , 0
  3976.3     .05       0  4904.1     .12       0  4980.1     .07       0
  5024.2     .12       0  5126.1     .16       0  5288.2      .1       0
  5357.7     .16       0
Bank Sta=5007.7,5013.7
XS Rating Curve= 0 ,0
Exp/Cntr=0.3,0.1

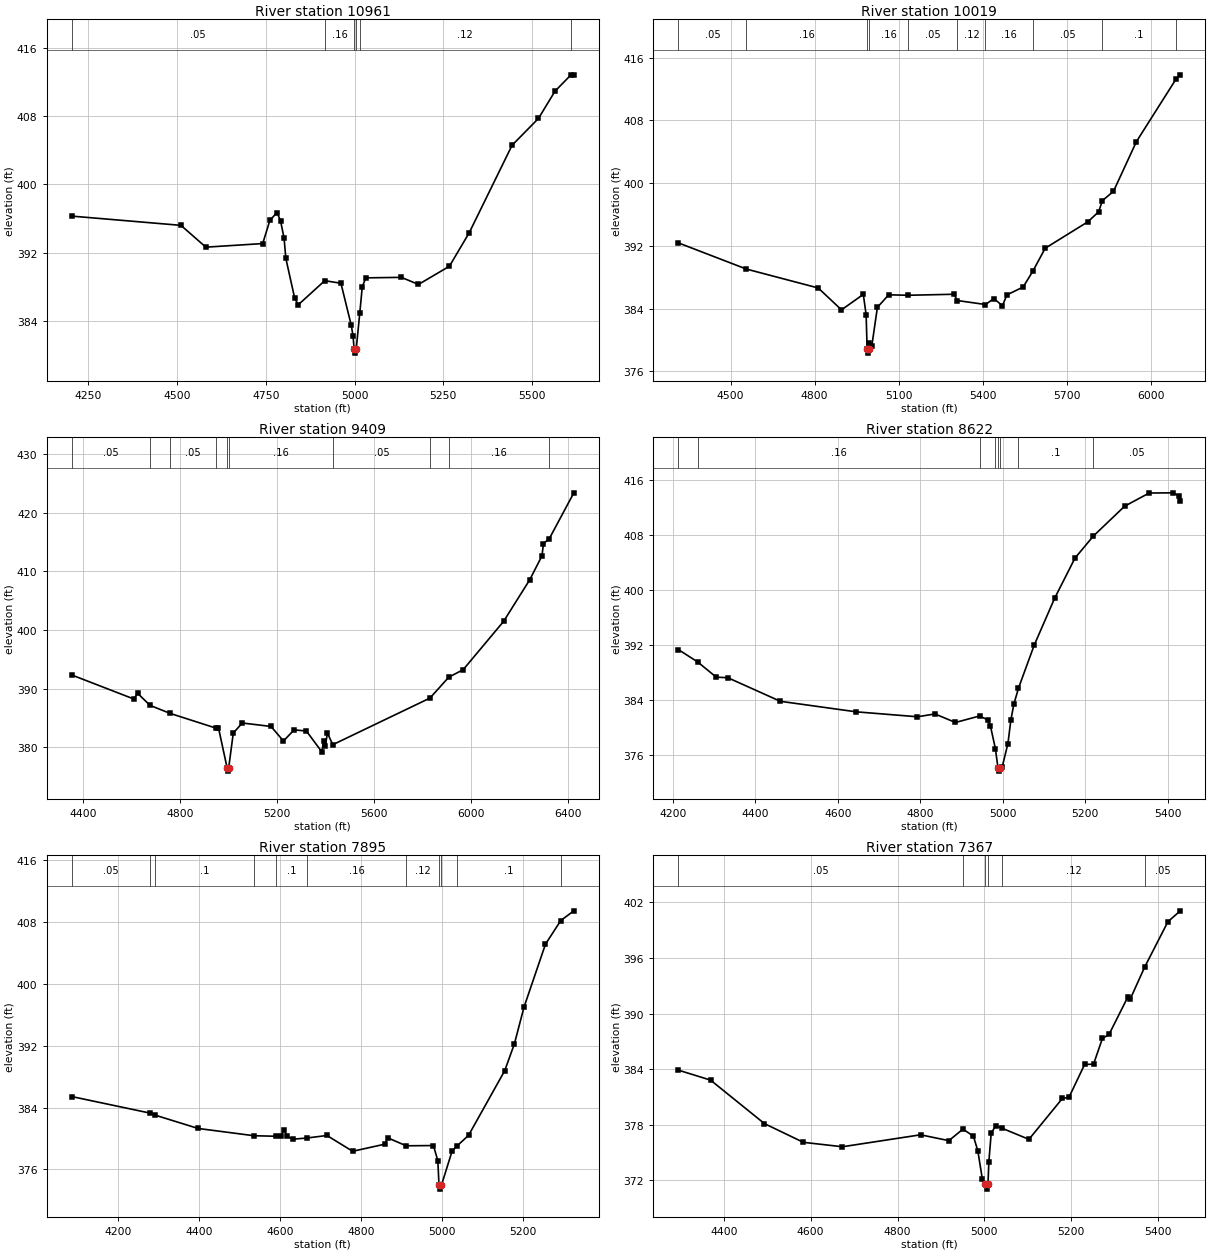
Type RM Length L Ch R = 1 ,10961   ,942,942,942
BEGIN DESCRIPTION:
MOORES BRANCH 15.0
END DESCRIPTION:
XS GIS Cut Line= 3
      3516939.14     10331288.79      3516887.05     10330309.59
      3516834.97     10329879.01
#Sta/Elev= 30
  4203.4   396.3    4511  395.22  4581.1  392.67  4741.3  393.09  4761.3  395.79
  4781.4  396.72  4791.4  395.77  4801.4  393.74  4806.4  391.36  4831.4  386.69
  4841.4  385.93    4916  388.75  4961.6  388.45  4990.7  383.53  4995.7  382.29
  4998.7  380.78  5001.4  380.28  5004.7  380.78  5014.6  384.93  5021.7  388.03
  5031.7  389.08  5131.9  389.14    5180  388.31  5267.2  390.44  5322.9  394.35
  5443.8  404.59    5518  407.72  5564.7  410.91  5609.5  412.81  5617.7  412.82
#Mann= 6 ,-1 , 0
  4203.4     .05       0    4916     .16       0  4998.7     .07       0
  5004.7     .16       0  5014.6     .12       0  5609.5      .1       0
Bank Sta=4998.7,5004.7
XS Rating Curve= 0 ,0
Exp/Cntr=0.3,0.1

Type RM Length L Ch R = 1 ,10019   ,610,610,610
BEGIN DESCRIPTION:
MOORES BRANCH 13.0
END DESCRIPTION:
XS GIS Cut Line= 3
      3517498.16     10331198.52       3517581.5     10330382.51
      3517404.42     10329427.65
#Sta/Elev= 30
  4313.3  392.38  4556.7  389.03  4812.8  386.62  4895.8  383.83  4973.6   385.8
  4983.7  383.23  4987.3  378.81    4990  378.31  4993.3  378.81  4995.3  379.64
  5003.8  379.18  5023.9  384.15  5064.1  385.75  5133.5  385.69  5297.2  385.82
    5309  385.02  5409.6  384.51  5439.6  385.27  5470.1  384.35    5486  385.74
  5543.9  386.74  5578.8  388.78  5622.6  391.69  5775.2  395.07  5813.3  396.34
  5826.6  397.76  5866.1  398.94  5948.1  405.29  6089.3  413.26  6104.7  413.81
#Mann= 10 ,-1 , 0
  4313.3     .05       0  4556.7     .16       0  4987.3     .07       0
  4993.3     .16       0  5133.5     .05       0    5309     .12       0
  5409.6     .16       0  5578.8     .05       0  5826.6      .1       0
  6089.3     .16       0
Bank Sta=4987.3,4993.3
XS Rating Curve= 0 ,0
Exp/Cntr=0.3,0.1

Type RM Length L Ch R = 1 ,9409    ,787,787,787
BEGIN DESCRIPTION:
MOORES BRANCH 12.0
END DESCRIPTION:
XS GIS Cut Line= 3
      3517682.18     10331276.63      3518078.03     10330505.77
      3518760.18     10329516.39
#Sta/Elev= 30
  4354.2  392.32  4609.3  388.23  4625.8  389.18  4676.8  387.13  4759.9  385.76
  4947.2  383.27  4958.6  383.31  4994.4  376.42  4997.1  375.92  5000.4  376.42
  5019.6  382.42  5056.8  384.13  5174.9  383.54  5226.3  381.06  5270.1  382.96
  5320.8  382.76  5383.7  379.24  5392.5  381.05  5398.6  380.22  5407.4  382.41
  5429.5  380.43  5829.7  388.38  5907.2  391.94  5966.7  393.23  6132.9  401.45
  6240.5  408.54  6291.2  412.64  6297.3  414.72  6321.6  415.59  6422.5  423.39
#Mann= 10 ,-1 , 0
  4354.2     .05       0  4676.8     .16       0  4759.9     .05       0
  4947.2     .16       0  4994.4     .07       0  5000.4     .16       0
  5429.5     .05       0  5829.7      .1       0  5907.2     .16       0
  6321.6      .1       0
Bank Sta=4994.4,5000.4
XS Rating Curve= 0 ,0
Exp/Cntr=0.3,0.1

Type RM Length L Ch R = 1 ,8622    ,727,727,727
BEGIN DESCRIPTION:
MOORES BRANCH 10.0
END DESCRIPTION:
XS GIS Cut Line= 3
      3518042.07     10331341.68      3518829.61      10330565.6
      3518879.35     10330466.11
#Sta/Elev= 30
  4213.5  391.29  4260.6  389.48  4305.5  387.27  4333.8  387.18  4461.1  383.75
  4644.9  382.22  4793.4   381.5  4835.8  381.91  4885.4  380.67  4943.7  381.61
  4963.1  381.07  4970.2  380.15  4982.2  376.87  4988.4  374.09  4991.1  373.59
  4994.4  374.09  4998.5  374.15  5012.6  377.61  5019.7  381.02  5026.8   383.3
  5038.1  385.65  5076.2  391.91  5125.8  398.75  5175.2   404.6  5219.7   407.8
  5295.4  412.14  5354.9  414.06    5413  414.09  5427.6  413.62  5430.4  412.85
#Mann= 8 ,-1 , 0
  4213.5     .05       0  4260.6     .16       0  4943.7      .1       0
  4982.2     .12       0  4988.4     .07       0  4994.4     .12       0
  5038.1      .1       0  5219.7     .05       0
Bank Sta=4988.4,4994.4
XS Rating Curve= 0 ,0
Exp/Cntr=0.3,0.1

Type RM Length L Ch R = 1 ,7895    ,528,528,528
BEGIN DESCRIPTION:
MOORES BRANCH 9.0
END DESCRIPTION:
XS GIS Cut Line= 3
       3518515.5     10331766.22      3519041.57      10331208.9
      3519223.84     10330771.44
#Sta/Elev= 30
  4085.5  385.42  4279.2  383.28  4290.2  383.04  4397.5   381.3  4535.5  380.36
  4590.7  380.29  4602.6  380.38  4609.9  381.15  4616.8  380.31  4630.9  379.91
  4665.7  380.06  4715.9  380.39  4779.4  378.35  4859.8  379.28  4865.7   380.1
  4911.5  379.06  4978.9  379.09  4989.8  377.14  4992.7  373.96  4995.5  373.46
  4998.7  373.96    5025  378.37  5037.2  379.04  5065.6   380.4    5155  388.76
  5178.8  392.21  5202.6  396.96  5255.7  405.11  5293.6  408.17  5325.8  409.42
#Mann= 11 ,-1 , 0
  4085.5     .05       0  4279.2     .16       0  4290.2      .1       0
  4535.5     .16       0  4590.7      .1       0  4665.7     .16       0
  4911.5     .12       0  4992.7     .07       0  4998.7     .12       0
  5037.2      .1       0  5293.6     .05       0
Bank Sta=4992.7,4998.7
XS Rating Curve= 0 ,0
Exp/Cntr=0.3,0.1

Type RM Length L Ch R = 1 ,7367    ,639,639,639
BEGIN DESCRIPTION:
MOORES BRANCH 7.0
END DESCRIPTION:
XS GIS Cut Line= 3
      3519192.59     10331979.77      3519447.82      10331458.9
      3519572.78     10330896.56
#Sta/Elev= 30
  4295.1   383.9  4369.5  382.82  4493.5  378.13  4583.1  376.11  4673.1  375.63
  4853.1  376.92  4918.2  376.29  4950.7  377.53  4974.8  376.77    4985  375.18
  4995.3  372.16  5002.3  371.56    5005  371.06  5008.3  371.56  5010.4  374.04
  5015.7  377.07    5026  377.91  5041.7  377.61  5102.6  376.43  5179.6  380.84
  5194.8  380.96  5230.9  384.51  5251.4  384.54  5271.8  387.31    5287  387.74
  5330.5   391.8  5335.6  391.53  5368.9  394.99  5422.7  399.91  5451.2  401.08
#Mann= 6 ,-1 , 0
  4295.1     .05       0  4950.7     .16       0  5002.3     .07       0
  5008.3     .16       0  5041.7     .12       0  5368.9     .05       0
Bank Sta=5002.3,5008.3
XS Rating Curve= 0 ,0
Exp/Cntr=0.3,0.1

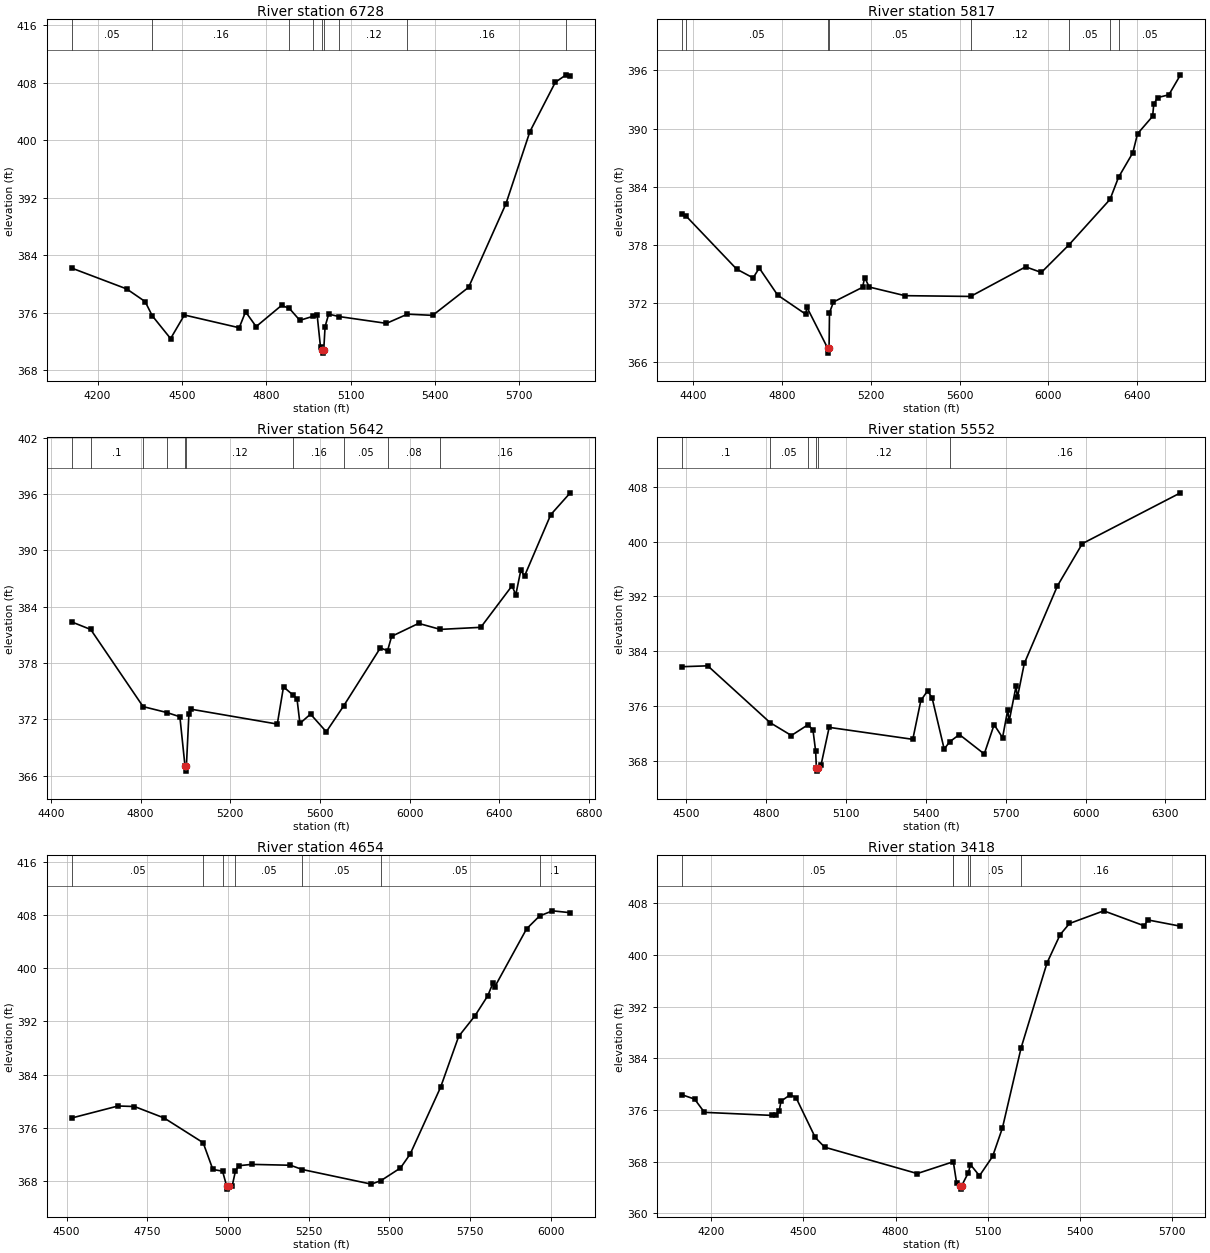
Type RM Length L Ch R = 1 ,6728    ,911,911,911
BEGIN DESCRIPTION:
MOORES BRANCH 6.0
END DESCRIPTION:
XS GIS Cut Line= 3
      3519838.44     10332422.46      3520042.11     10331541.64
       3520239.1     10330694.91
#Sta/Elev= 30
  4107.8  382.21  4303.6  379.31  4369.3  377.55  4394.7  375.57  4459.9   372.4
  4508.9  375.68  4703.9  373.91  4726.5  376.13  4764.1  374.07  4854.6  377.02
  4882.2   376.6  4919.5  374.94  4967.9  375.52  4981.1  375.67  4993.1  371.18
  4998.6  370.88  5001.3  370.38  5004.6  370.88  5009.3  374.07  5022.1   375.8
  5059.9  375.46  5227.5  374.52  5302.2   375.8  5391.9  375.63  5519.7  379.53
  5652.6  391.16  5737.8  401.19  5828.2  408.05  5866.5  409.08  5881.2  408.94
#Mann= 9 ,-1 , 0
  4107.8     .05       0  4394.7     .16       0  4882.2     .05       0
  4967.9     .16       0  4998.6     .07       0  5004.6     .16       0
  5059.9     .12       0  5302.2     .16       0  5866.5     .05       0
Bank Sta=4998.6,5004.6
XS Rating Curve= 0 ,0
Exp/Cntr=0.3,0.1

Type RM Length L Ch R = 1 ,5817    ,175,175,175
BEGIN DESCRIPTION:
Mapping XS 2cfa32a7
END DESCRIPTION:
XS GIS Cut Line= 3
      3520413.16     10332700.61      3520530.35       10331494.
      3520413.16     10330469.67
#Sta/Elev= 30
  4350.5  381.25  4370.9  380.96  4596.9  375.53    4671  374.62  4698.9  375.63
  4781.5  372.85  4907.8  370.88  4912.9  371.61  5006.8  367.37  5009.5  366.87
  5012.8  367.37  5014.8  371.03  5032.7  372.14  5163.3  373.65  5173.3  374.66
  5193.4  373.68  5354.2  372.79  5649.4  372.71  5897.3  375.76  5967.8  375.18
    6091     378  6276.9  382.71    6315  384.98  6379.3  387.51  6400.6  389.47
  6468.5  391.27  6473.6  392.52  6491.2   393.2  6541.5  393.48  6593.8  395.54
#Mann= 8 ,-1 , 0
  4350.5     .08       0  4370.9     .05       0  5006.8     .04       0
  5012.8     .05       0  5649.4     .12       0    6091     .05       0
  6276.9     .16       0    6315     .05       0
Bank Sta=5006.8,5012.8
XS Rating Curve= 0 ,0
Exp/Cntr=0.3,0.1

Type RM Length L Ch R = 1 ,5642    ,90,90,90
BEGIN DESCRIPTION:
Mapping XS e52cc461
END DESCRIPTION:
XS GIS Cut Line= 3
      3520586.77     10332622.43      3520747.36     10331003.55
      3521016.47     10330469.66
#Sta/Elev= 30
  4491.8  382.39  4577.1  381.58  4810.7  373.37  4916.5  372.74  4974.9  372.29
  4997.9     367  5000.6   366.5  5003.9     367  5015.1  372.55  5025.2  373.09
  5409.5  371.51  5437.2  375.47  5481.8  374.56  5497.5  374.19  5510.4  371.58
  5557.8  372.57  5628.1  370.69  5704.9  373.42  5869.3  379.62  5901.4  379.32
  5919.6  380.85  6040.1  382.23  6136.6  381.59  6317.4  381.81  6456.8  386.23
  6473.5  385.27  6495.8  387.87  6512.5  387.27  6629.7  393.81  6716.5  396.13
#Mann= 10 ,-1 , 0
  4491.8     .05       0  4577.1      .1       0  4810.7     .05       0
  4916.5     .12       0  4997.9     .07       0  5003.9     .12       0
  5481.8     .16       0  5704.9     .05       0  5901.4     .08       0
  6136.6     .16       0
Bank Sta=4997.9,5003.9
XS Rating Curve= 0 ,0
Exp/Cntr=0.3,0.1

Type RM Length L Ch R = 1 ,5552    ,898,898,898
BEGIN DESCRIPTION:
MOORES BRANCH 5.0
END DESCRIPTION:
XS GIS Cut Line= 3
       3520624.9     10332677.65      3520770.74     10331787.02
      3521088.46     10330870.31
#Sta/Elev= 30
  4483.7  381.72    4581  381.85  4815.6  373.53  4895.1  371.66  4957.8  373.24
  4976.2  372.45  4986.3  369.34  4988.9  366.95  4991.6  366.45  4994.9  366.95
  5006.6  367.37    5037  372.85  5351.1   371.1  5381.3  376.78  5406.7   378.2
  5423.6  377.16    5469  369.67  5489.3  370.73    5526   371.8  5619.4  368.96
  5656.5  373.24  5688.2  371.35  5707.6  375.41  5712.8  373.71  5738.7  378.83
    5744  377.22  5769.8   382.2  5894.4  393.55  5987.8  399.72  6356.4  407.15
#Mann= 6 ,-1 , 0
  4483.7      .1       0  4815.6     .05       0  4957.8     .12       0
  4988.9     .07       0  4994.9     .12       0  5489.3     .16       0
Bank Sta=4988.9,4994.9
XS Rating Curve= 0 ,0
Exp/Cntr=0.3,0.1

Type RM Length L Ch R = 1 ,4654    ,1236,1236,1236
BEGIN DESCRIPTION:
MOORES BRANCH 3.0
END DESCRIPTION:
XS GIS Cut Line= 3
      3521406.16     10332693.24      3521468.65     10332354.73
      3521541.57     10331156.78
#Sta/Elev= 30
  4515.5  377.47  4659.5  379.28  4710.3   379.2  4801.9  377.48  4922.9  373.76
    4953  369.74    4983  369.48  4995.5  367.28  4998.2  366.78  5001.5  367.28
  5013.1  367.31  5023.1  369.53  5033.1   370.3  5073.2   370.5  5193.4  370.37
  5229.9  369.73  5443.9  367.53    5474  368.07  5534.1  369.96  5564.1  372.05
  5658.3  382.09  5714.4  389.75  5764.5  392.82  5804.6  395.86  5820.7  397.79
  5825.7  397.15  5924.8  405.92  5964.8  407.84  6004.9  408.62  6059.9  408.34
#Mann= 7 ,-1 , 0
  4515.5     .05       0  4922.9     .05       0    4983    .035       0
  5023.1     .05       0  5229.9     .05       0    5474     .05       0
  5964.8      .1       0
Bank Sta=4995.5,5001.5
XS Rating Curve= 0 ,0
Exp/Cntr=0.3,0.1

Type RM Length L Ch R = 1 ,3418    ,580,580,580
BEGIN DESCRIPTION:
MOORES BRANCH 2.0
END DESCRIPTION:
XS GIS Cut Line= 3
      3521926.97     10332750.59      3522322.82     10331667.23
      3522250.13     10331205.13
#Sta/Elev= 30
  4105.3  378.37  4146.8  377.69  4178.7  375.64    4397  375.17  4412.9  375.28
  4422.2  375.92  4427.6  377.37  4458.1  378.37  4476.8  377.89  4539.1  371.75
  4569.6  370.25  4870.7  366.17  4987.9     368  4998.5  364.77  5008.7  364.26
  5011.5  363.76  5014.7  364.26  5036.9  366.31  5043.7  367.55    5073  365.83
  5115.6  368.81  5147.6  373.22  5208.5  385.65  5292.6  398.76  5335.2  403.13
  5365.6  404.86    5477  406.82  5608.6   404.5  5620.5  405.41  5726.5  404.44
#Mann= 6 ,-1 , 0
  4105.3     .05       0  4987.9     .16       0  4987.9     .03       0
  5036.9     .16       0  5043.7     .05       0  5208.5     .16       0
Bank Sta=5008.7,5014.7
XS Rating Curve= 0 ,0
Exp/Cntr=0.3,0.1

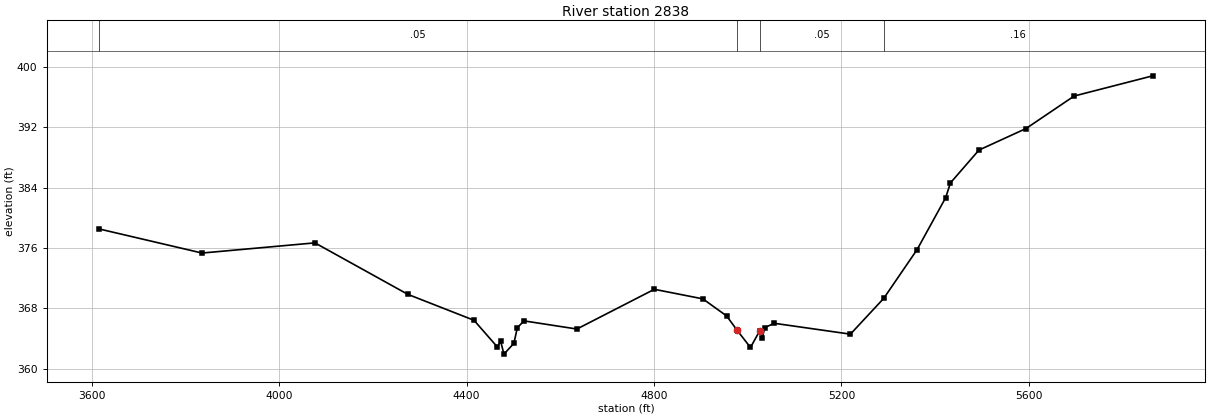
Type RM Length L Ch R = 1 ,2838    ,0,0,0
BEGIN DESCRIPTION:
MOORES BRANCH 1.0
END DESCRIPTION:
XS GIS Cut Line= 3
      3521942.13     10332991.62      3522817.61     10332193.27
      3522630.14     10331146.56
#Sta/Elev= 30
  3616.2  378.51  3835.4  375.32  4076.3  376.67  4274.6  369.84  4415.8   366.4
  4465.8  362.85  4472.5  363.66  4479.7  361.91  4500.9  363.34  4508.3  365.41
  4522.5  366.32  4635.4  365.24  4800.7  370.51  4904.3  369.24  4955.1  366.97
  4977.3  365.08  5005.9  362.79  5025.9  365.04    5031  364.04  5036.3  365.43
  5056.7     366  5219.2  364.56  5290.3  369.31  5361.4  375.77  5422.4  382.66
  5432.7  384.63  5493.5  388.98    5594  391.84  5696.7  396.15  5864.4  398.83
#Mann= 4 ,-1 , 0
  3616.2     .05       0  4977.3     .03       0  5025.9     .05       0
  5290.3     .16       0
Bank Sta=4977.3,5025.9
XS Rating Curve= 0 ,0
Exp/Cntr=0.3,0.1

Chan Stop Cuts=-1
Use User Specified Reach Order=0
Composite Channel Slope=5