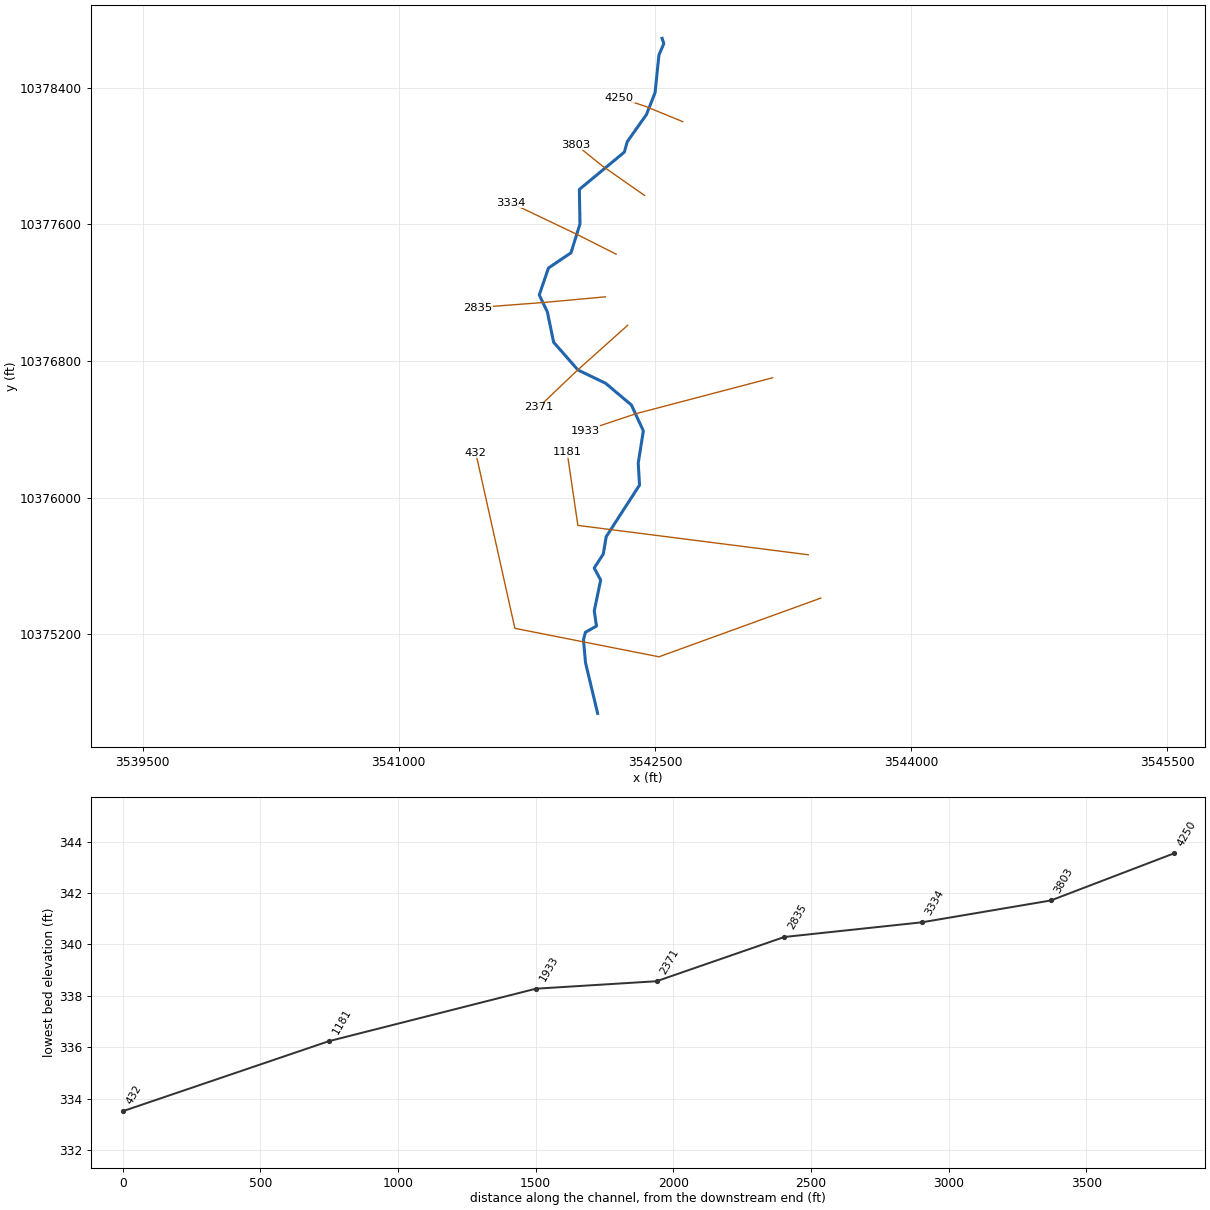
--- MORTON BRANCH.prj (project) ---

Proj Title=MORTON BRANCH Base Level Engineering
Current Plan=p01
Default Exp/Contr=0.3,0.1
English Units
Geom File=g01
Flow File=f01
Plan File=p01
Y Axis Title=Elevation
X Axis Title(PF)=Main Channel Distance
X Axis Title(XS)=Station
BEGIN DESCRIPTION:
MORTON BRANCH
END DESCRIPTION:
DSS Export Rating Curves= 0
DSS Export Rating Curve Sorted= 0
DSS Export Volume Flow Curves= 0
DXF OffsetX= 0
DXF OffsetY= 0
DXF ScaleX= 1
DXF ScaleY= 10

--- MORTON BRANCH.p01 (plan) ---

Plan Title=Multiple Run
Short Identifier=Multiple
Geom File=g01
Flow File=f01
Subcritical Flow
K Sum by GR= 0
Std Step Tol= 0.01
Critical Tol= 0.01
Num of Std Step Trials= 20
Max Error Tol= 0.3
Flow Tol Ratio= 0.001
Split Flow NTrial= 30
Split Flow Tol= 0.02
Split Flow Ratio= 0.02
Log Output Level= 0
Friction Slope Method= 1
Unsteady Friction Slope Method= 2
Unsteady Bridges Friction Slope Method= 1
Parabolic Critical Depth
Global Vel Dist=  1 , 1 , 1
Global Log Level= 0
CheckData=True
Encroach Param= -1, 0, 0, 0
BEGIN DESCRIPTION:
Multiple Run
END DESCRIPTION:

--- MORTON BRANCH.f01 (steady flow) ---

Flow Title=Multiple
Number of Profiles=7
Profile Names=10-year,25-year,50-year,1pct_min,100-year,1pct_plu,500-year
River Rch & RM= MORTON BRANCH,Reach-1,4250
     858    1178    1441    1287    1741    2354    2534
Boundary for River Rch & Prof#=MORTON BRANCH,Reach-1,1
Up Type=0
Dn Type=3
Dn Slope=0.005
Boundary for River Rch & Prof#=MORTON BRANCH,Reach-1,2
Up Type=0
Dn Type=3
Dn Slope=0.005
Boundary for River Rch & Prof#=MORTON BRANCH,Reach-1,3
Up Type=0
Dn Type=3
Dn Slope=0.005
Boundary for River Rch & Prof#=MORTON BRANCH,Reach-1,4
Up Type=0
Dn Type=3
Dn Slope=0.005
Boundary for River Rch & Prof#=MORTON BRANCH,Reach-1,5
Up Type=0
Dn Type=3
Dn Slope=0.005
Boundary for River Rch & Prof#=MORTON BRANCH,Reach-1,6
Up Type=0
Dn Type=3
Dn Slope=0.005
Boundary for River Rch & Prof#=MORTON BRANCH,Reach-1,7
Up Type=0
Dn Type=3
Dn Slope=0.005

--- MORTON BRANCH.g01 (geometry) ---

Geom Title=Existing Conditions
Program Version=4.10

River Reach=MORTON BRANCH   ,Reach-1
Reach XY= 30
      3542542.11     10378689.08       3542552.1     10378658.05
      3542523.41      10378591.1      3542500.91     10378371.02
      3542450.25     10378242.41      3542338.17     10378084.08
      3542320.93     10378022.74      3542057.49     10377804.25
      3542061.15     10377602.12      3542008.46       10377433.
      3541876.85     10377344.32       3541822.6     10377186.33
      3541870.18     10377086.57      3541906.88     10376909.11
      3542049.54     10376746.62      3542211.08     10376669.17
      3542362.31     10376541.72      3542432.21     10376390.65
      3542402.35     10376201.37      3542409.81     10376072.76
      3542214.65     10375770.59      3542197.51      10375668.8
      3542144.56     10375586.98      3542182.33      10375516.7
      3542144.82     10375336.09      3542157.85     10375247.11
      3542092.93     10375210.87      3542081.51       10375167.
      3542093.71     10375031.83      3542164.57     10374735.84

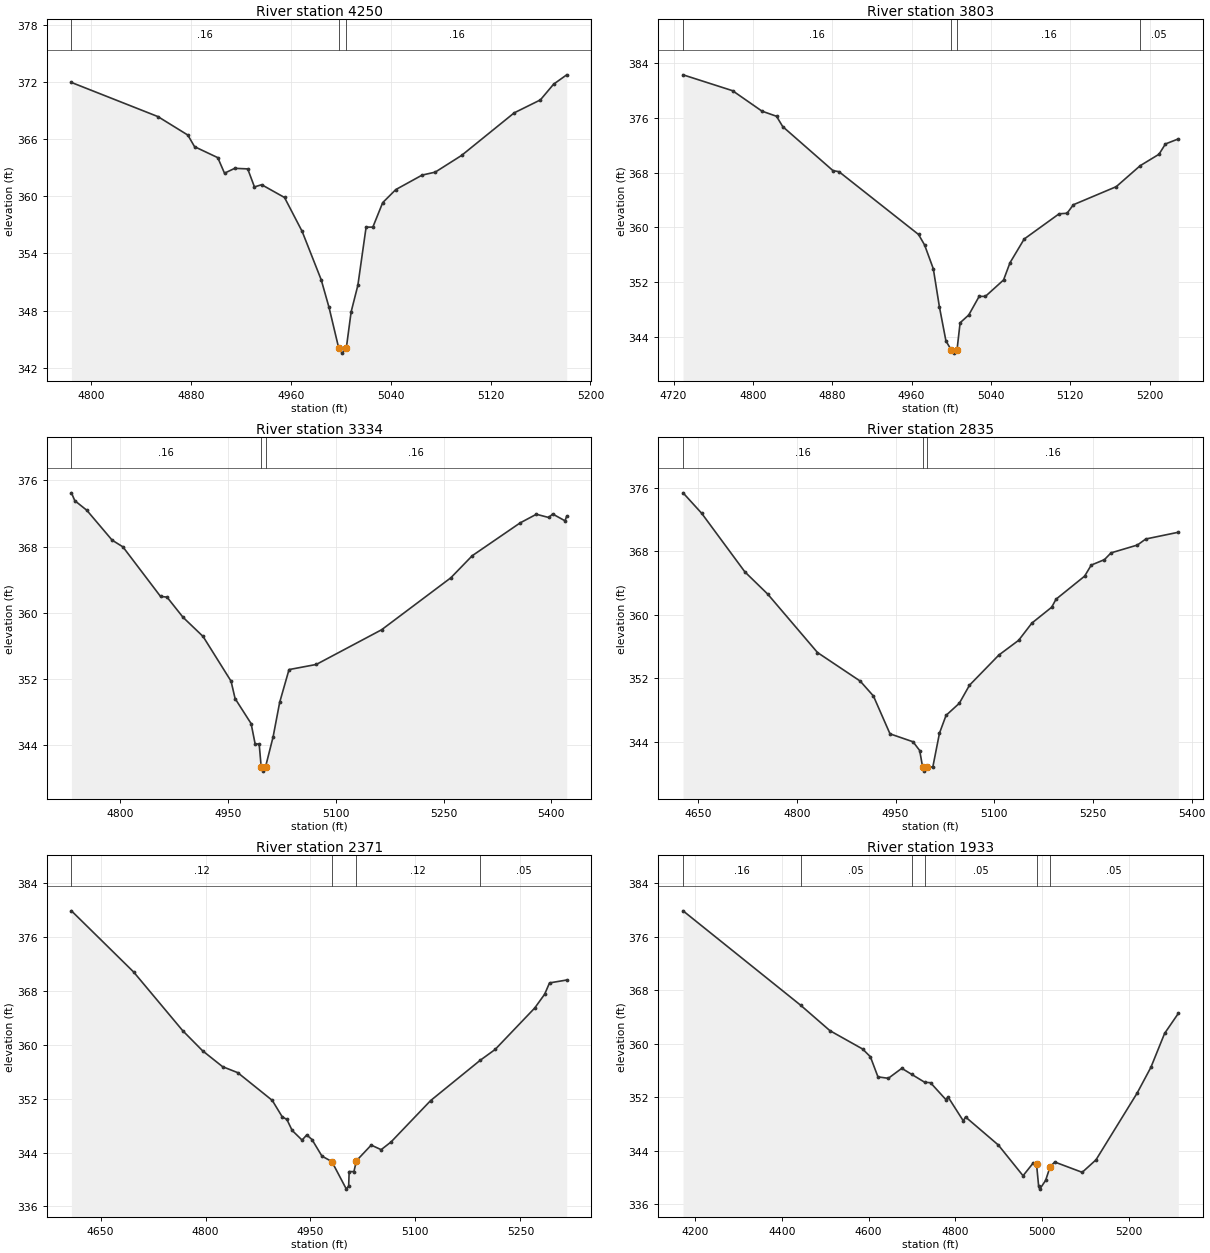
Type RM Length L Ch R = 1 ,4250    ,447,447,447
BEGIN DESCRIPTION:
MORTON BRANCH 9.0
END DESCRIPTION:
XS GIS Cut Line= 3
      3542663.27     10378201.28      3542442.11     10378291.64
      3542292.13     10378341.63
#Sta/Elev= 30
    4784  371.94  4853.3  368.36  4877.3  366.42  4882.7   365.2  4901.3  364.05
  4906.7  362.42  4914.9  362.93  4925.3  362.87  4930.7  360.98  4936.5  361.21
  4954.8  359.87  4968.9  356.32  4984.2  351.24  4990.5  348.33  4998.3  344.04
  5001.1  343.54  5004.3  344.04  5008.2  347.87  5013.6  350.66  5020.2  356.76
  5025.6  356.76  5033.5  359.33    5044   360.7  5065.1  362.22  5075.6  362.53
  5096.7  364.28  5138.9  368.75  5159.9  370.11  5170.5  371.76    5181  372.74
#Mann= 3 ,-1 , 0
    4784     .16       0  4998.3     .07       0  5004.3     .16       0
Bank Sta=4998.3,5004.3
XS Rating Curve= 0 ,0
Exp/Cntr=0.3,0.1

Type RM Length L Ch R = 1 ,3803    ,469,469,469
BEGIN DESCRIPTION:
MORTON BRANCH 8.0
END DESCRIPTION:
XS GIS Cut Line= 3
      3542439.33     10377768.98      3542192.11     10377941.64
      3542038.26     10378065.88
#Sta/Elev= 30
  4729.6  382.22  4779.5  379.91  4809.2  376.93  4823.8  376.19  4830.1  374.68
  4880.7  368.28  4886.8  368.12    4967  358.98  4973.1  357.45  4981.9  353.98
    4988  348.47  4994.6  343.49  4999.8  342.21  5002.6  341.71  5005.8  342.21
  5008.9  346.13  5017.6  347.26  5028.1  349.97  5034.4  349.97  5052.7  352.36
  5059.2  354.87  5073.5  358.32  5108.7  361.99  5116.7  362.07  5123.1  363.31
  5166.3  365.94  5190.4  368.99  5209.4  370.66  5215.9  372.16  5228.9  372.89
#Mann= 4 ,-1 , 0
  4729.6     .16       0  4999.8     .07       0  5005.8     .16       0
  5190.4     .05       0
Bank Sta=4999.8,5005.8
XS Rating Curve= 0 ,0
Exp/Cntr=0.3,0.1

Type RM Length L Ch R = 1 ,3334    ,499,499,499
BEGIN DESCRIPTION:
MORTON BRANCH 7.0
END DESCRIPTION:
XS GIS Cut Line= 3
      3542272.67     10377425.23      3542042.11     10377541.64
      3541653.54       10377727.
#Sta/Elev= 30
  4732.5  374.49  4737.2  373.54  4753.9  372.38  4789.1  368.77  4804.1  367.96
  4856.4  361.97  4865.4  361.89  4887.7  359.45  4915.6  357.13  4954.5  351.73
  4960.1  349.63  4982.4   346.6    4988  344.14  4993.6  344.14  4996.4  341.36
  4999.1  340.86  5002.4  341.36    5013  345.01  5022.1  349.17  5035.1  353.13
    5073  353.75  5163.8  357.94  5260.1  364.22  5289.9  366.89  5356.4  370.85
  5379.1   371.9  5396.2  371.51  5401.8  371.93  5418.9  371.11  5421.3  371.67
#Mann= 3 ,-1 , 0
  4732.5     .16       0  4996.4     .07       0  5002.4     .16       0
Bank Sta=4996.4,5002.4
XS Rating Curve= 0 ,0
Exp/Cntr=0.3,0.1

Type RM Length L Ch R = 1 ,2835    ,464,464,464
BEGIN DESCRIPTION:
MORTON BRANCH 6.0
END DESCRIPTION:
XS GIS Cut Line= 3
      3542210.19     10377175.24      3541842.11     10377141.64
      3541460.12     10377112.73
#Sta/Elev= 30
  4627.1  375.37  4655.3   372.8  4721.1   365.4  4755.7  362.61  4831.4  355.24
  4896.3  351.64  4916.4  349.76  4941.6  344.99  4976.6  343.99  4986.7  342.89
  4991.2  340.79    4994  340.29  4997.2  340.79  5006.7  340.82  5016.8  345.08
  5026.8  347.32  5046.9  348.84  5062.4  351.12    5107  354.92  5137.1  356.78
  5157.2  358.95  5187.3  360.95  5193.9  361.96  5237.4  364.87  5247.4  366.26
  5267.5  366.95  5277.5   367.8  5317.6  368.79  5330.3  369.55  5379.8   370.4
#Mann= 3 ,-1 , 0
  4627.1     .16       0  4991.2     .07       0  4997.2     .16       0
Bank Sta=4991.2,4997.2
XS Rating Curve= 0 ,0
Exp/Cntr=0.3,0.1

Type RM Length L Ch R = 1 ,2371    ,438,438,438
BEGIN DESCRIPTION:
MORTON BRANCH 5.0
END DESCRIPTION:
XS GIS Cut Line= 3
      3542340.37     10377008.57      3542042.11     10376741.64
      3541819.54      10376529.4
#Sta/Elev= 30
  4608.4  379.84  4697.3  370.77  4767.5  362.06  4795.9  359.08  4824.4  356.73
  4846.1  355.84  4895.4  351.73  4909.6   349.3  4916.3   348.9  4923.8  347.28
    4938  345.84  4944.7  346.61  4952.2  345.92  4966.4  343.47  4980.6  342.65
  5001.3  338.57  5004.6  339.07  5005.3  341.17  5012.1  341.17  5015.7  342.78
  5036.8   345.1    5051  344.42  5065.1  345.56  5121.7   351.7  5192.6  357.68
  5213.9  359.28  5270.5  365.43  5284.7  367.48  5291.6  369.15  5316.2  369.58
#Mann= 4 ,-1 , 0
  4608.4     .12       0  4980.6    .035       0  5015.7     .12       0
  5192.6     .05       0
Bank Sta=4980.6,5015.7
XS Rating Curve= 0 ,0
Exp/Cntr=0.3,0.1

Type RM Length L Ch R = 1 ,1933    ,752,752,752
BEGIN DESCRIPTION:
MORTON BRANCH 4.0
END DESCRIPTION:
XS GIS Cut Line= 3
      3543189.28     10376701.26      3542392.11     10376491.64
      3542092.11     10376391.64
#Sta/Elev= 30
  4172.7  379.86  4443.2  365.77    4511  361.95  4586.3  359.21  4604.1  358.05
  4621.5  355.05  4645.4  354.84  4676.4  356.33  4699.6  355.41    4729  354.25
  4742.5  354.18  4777.7  351.67  4782.9  352.05    4818  348.48  4823.2  349.06
  4898.7  344.87  4955.6  340.28  4979.4  342.22  4986.6  342.06  4991.4  338.78
  4994.1  338.28  5007.5  339.58  5018.1  341.65  5028.6  342.33  5091.8  340.79
  5123.5  342.65  5218.3  352.63    5250  356.48  5281.6  361.55  5313.2  364.54
#Mann= 6 ,-1 , 0
  4172.7     .16       0  4443.2     .05       0  4699.6      .1       0
    4729     .05       0  4986.6     .03       0  5018.1     .05       0
Bank Sta=4986.6,5018.1
XS Rating Curve= 0 ,0
Exp/Cntr=0.3,0.1

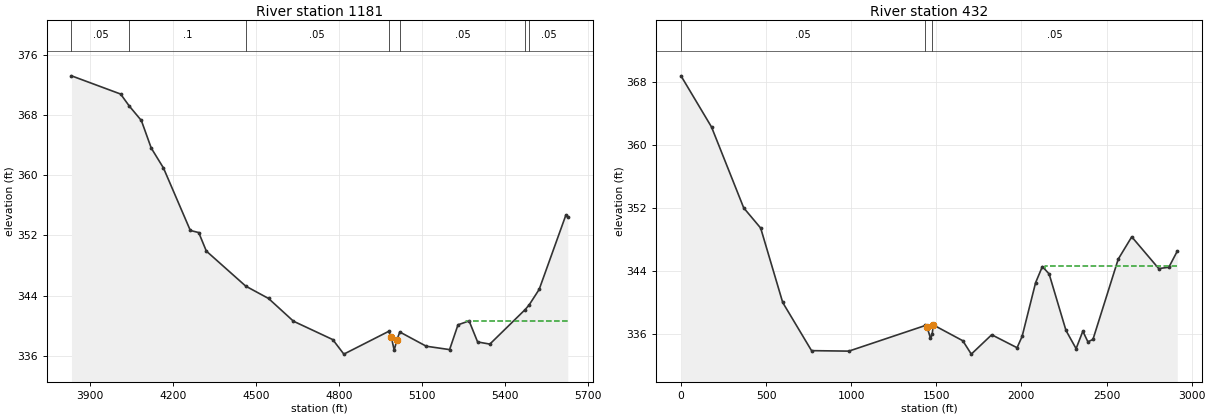
Type RM Length L Ch R = 1 ,1181    ,749,749,749
BEGIN DESCRIPTION:
MORTON BRANCH 1.0
END DESCRIPTION:
XS GIS Cut Line= 3
      3543397.69     10375664.81       3542048.7     10375836.69
      3541986.21     10376263.75
#Sta/Elev= 30
  3834.7  373.19  4012.1  370.77  4043.3  369.18  4086.9  367.26  4122.6   363.6
  4166.8  360.95  4263.7  352.66    4294  352.38  4321.5  349.92  4463.7  345.27
    4546  343.63    4636  340.61  4777.9  338.17  4817.9  336.24  4979.5  339.26
  4989.5  338.46  4999.6  336.76  5009.7  338.17  5019.8  339.18  5115.3  337.29
  5199.6  336.84  5229.9  340.13    5270  340.65  5300.7  337.86  5344.9  337.57
  5472.5  342.16  5486.9  342.78    5523  344.84  5619.5  354.72  5626.2  354.45
#Mann= 7 ,-1 , 0
  3834.7     .05       0  4043.3      .1       0  4463.7     .05       0
  4979.5     .03       0  5019.8     .05       0  5472.5     .16       0
  5486.9     .05       0
#XS Ineff= 2 , 0
                         5259.94          340.61
Permanent Ineff=
       F       F
Bank Sta=4989.5,5009.7
XS Rating Curve= 0 ,0
Exp/Cntr=0.3,0.1

Type RM Length L Ch R = 1 ,432     ,0,0,0
XS GIS Cut Line= 4
     3543471.615    10375410.969     3542523.698    10375067.219
     3541679.948    10375233.885     3541450.781    10376261.663
#Sta/Elev= 30
       0368.7224179.2999362.2542 368.561352.0163468.1721349.4616597.6664340.0484
767.0053333.9561986.1497333.89481435.734337.14051445.727336.95011465.712335.5344
1475.705336.0369 1482.25  337.211655.577  335.211705.541333.51531825.456335.9668
 1974.49334.32522004.211 335.7652083.468342.56292123.095 344.5972162.724343.6608
2261.794 336.5112321.236334.20962360.864336.41532390.585335.06812420.306335.3747
2568.911345.53992648.167348.35712806.679344.33832866.122344.50862915.656346.5405
#Mann= 3 ,-1 , 0
       0     .05       01435.734     .03       01475.705     .05       0
#XS Ineff= 2 , 0
                          2137.5          344.67
Permanent Ineff=
       F       F
Bank Sta=1445.727,1482.25
XS Rating Curve= 0 ,0
Exp/Cntr=0.3,0.1

Chan Stop Cuts=-1
Use User Specified Reach Order=0
Composite Channel Slope=5