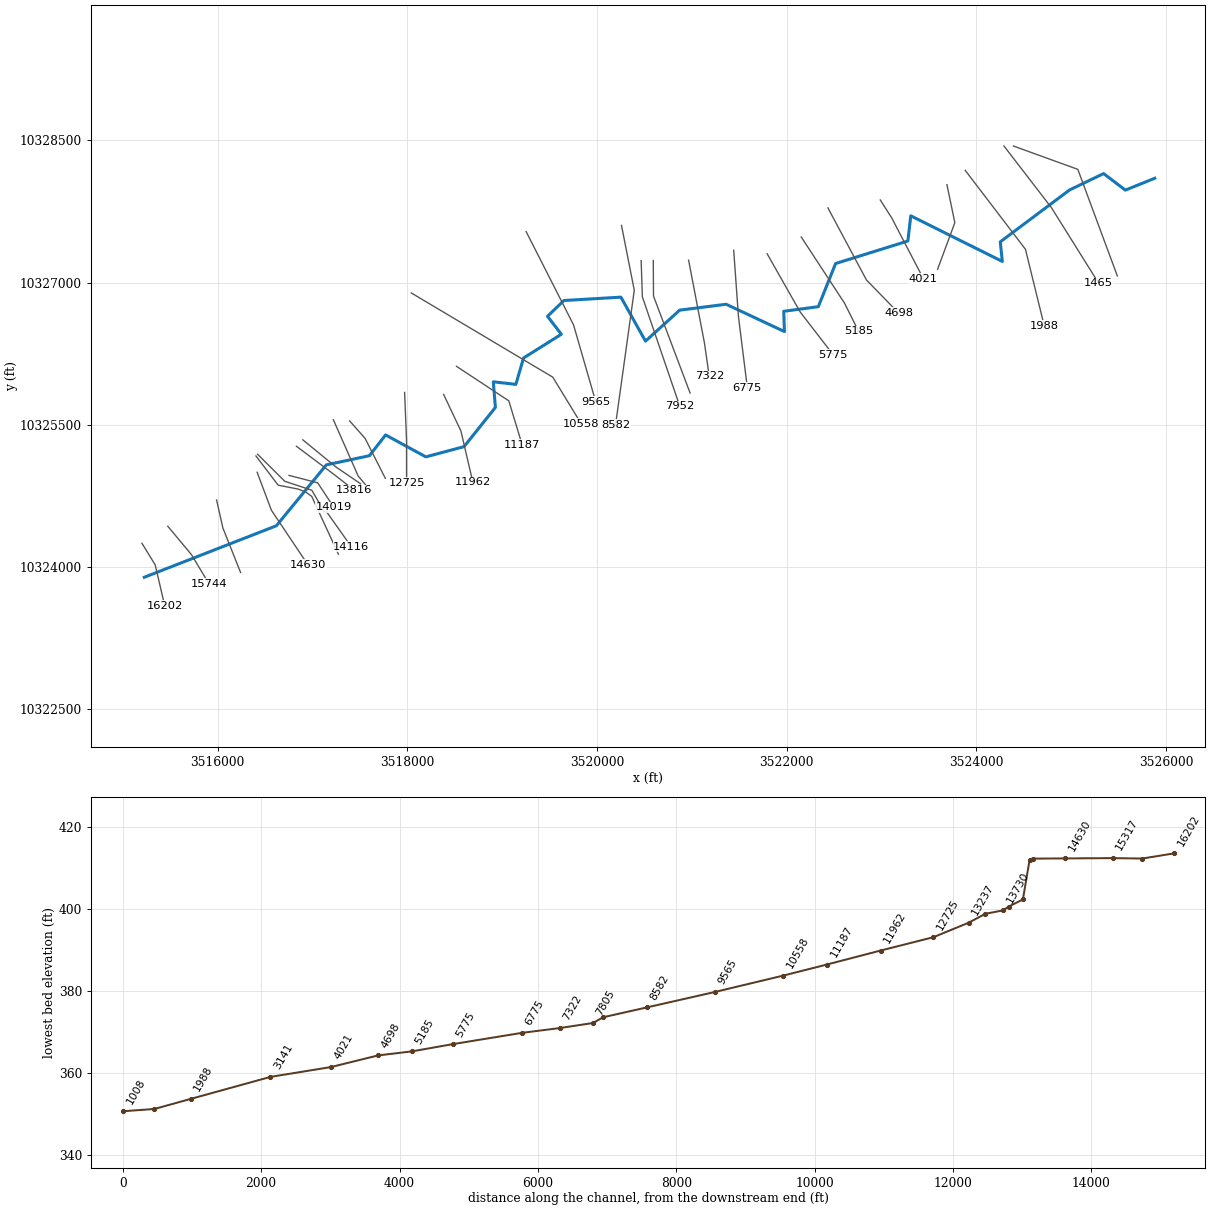
--- MOSS SPRING BRANCH.prj (project) ---

Proj Title=MOSS SPRING BRANCH Base Level Engineering
Current Plan=p01
Default Exp/Contr=0.3,0.1
English Units
Geom File=g01
Flow File=f01
Plan File=p01
Y Axis Title=Elevation
X Axis Title(PF)=Main Channel Distance
X Axis Title(XS)=Station
BEGIN DESCRIPTION:
MOSS SPRING BRANCH
END DESCRIPTION:
DSS Export Rating Curves= 0
DSS Export Rating Curve Sorted= 0
DSS Export Volume Flow Curves= 0
DXF OffsetX= 0
DXF OffsetY= 0
DXF ScaleX= 1
DXF ScaleY= 10

--- MOSS SPRING BRANCH.p01 (plan) ---

Plan Title=Multiple Run
Short Identifier=Multiple
Geom File=g01
Flow File=f01
Subcritical Flow
K Sum by GR= 0
Std Step Tol= 0.01
Critical Tol= 0.01
Num of Std Step Trials= 20
Max Error Tol= 0.3
Flow Tol Ratio= 0.001
Split Flow NTrial= 30
Split Flow Tol= 0.02
Split Flow Ratio= 0.02
Log Output Level= 0
Friction Slope Method= 1
Unsteady Friction Slope Method= 2
Unsteady Bridges Friction Slope Method= 1
Parabolic Critical Depth
Global Vel Dist=  1 , 1 , 1
Global Log Level= 0
CheckData=True
Encroach Param= -1, 0, 0, 0
BEGIN DESCRIPTION:
Multiple Run
END DESCRIPTION:

--- MOSS SPRING BRANCH.f01 (steady flow) ---

Flow Title=Multiple
Number of Profiles=7
Profile Names=10-year,25-year,50-year,1pct_min,100-year,1pct_plu,500-year
River Rch & RM= MOSS SPRING BRAN,Reach-1,16202
     624     861    1057     953    1288    1742    1918
River Rch & RM= MOSS SPRING BRAN,Reach-1,11187
     949    1330    1653    1503    2032    2749    3085
River Rch & RM= MOSS SPRING BRAN,Reach-1,4021
     991    1389    1726    1569    2122    2870    3219
Boundary for River Rch & Prof#=MOSS SPRING BRAN,Reach-1,1
Up Type=0
Dn Type=3
Dn Slope=0.005
Boundary for River Rch & Prof#=MOSS SPRING BRAN,Reach-1,2
Up Type=0
Dn Type=3
Dn Slope=0.005
Boundary for River Rch & Prof#=MOSS SPRING BRAN,Reach-1,3
Up Type=0
Dn Type=3
Dn Slope=0.005
Boundary for River Rch & Prof#=MOSS SPRING BRAN,Reach-1,4
Up Type=0
Dn Type=3
Dn Slope=0.005
Boundary for River Rch & Prof#=MOSS SPRING BRAN,Reach-1,5
Up Type=0
Dn Type=3
Dn Slope=0.005
Boundary for River Rch & Prof#=MOSS SPRING BRAN,Reach-1,6
Up Type=0
Dn Type=3
Dn Slope=0.005
Boundary for River Rch & Prof#=MOSS SPRING BRAN,Reach-1,7
Up Type=0
Dn Type=3
Dn Slope=0.005

--- MOSS SPRING BRANCH.g01 (geometry) ---

Geom Title=Existing Conditions
Program Version=4.10

River Reach=MOSS SPRING BRAN,Reach-1
Reach XY= 30
      3515227.11     10323891.64      3516619.88     10324435.03
      3517146.54     10325077.38       3517601.1     10325174.25
      3517771.29     10325393.17      3518195.91     10325161.78
      3518598.25     10325269.63      3518929.02     10325683.46
      3518907.33     10325953.83      3519144.84     10325926.59
      3519226.21     10326205.52      3519624.55     10326455.49
      3519478.51     10326645.22      3519652.11     10326811.64
      3520252.64     10326846.96      3520511.84     10326383.06
      3520872.68     10326709.91      3521362.67     10326772.07
      3521976.85     10326484.05       3521969.8     10326697.91
      3522334.15     10326746.57      3522516.61     10327201.89
      3523278.39     10327439.29       3523309.2     10327705.36
      3524274.52     10327223.84      3524252.88     10327430.66
      3524983.53     10327978.11      3525342.67      10328150.9
      3525571.78     10327976.46      3525882.11     10328101.64

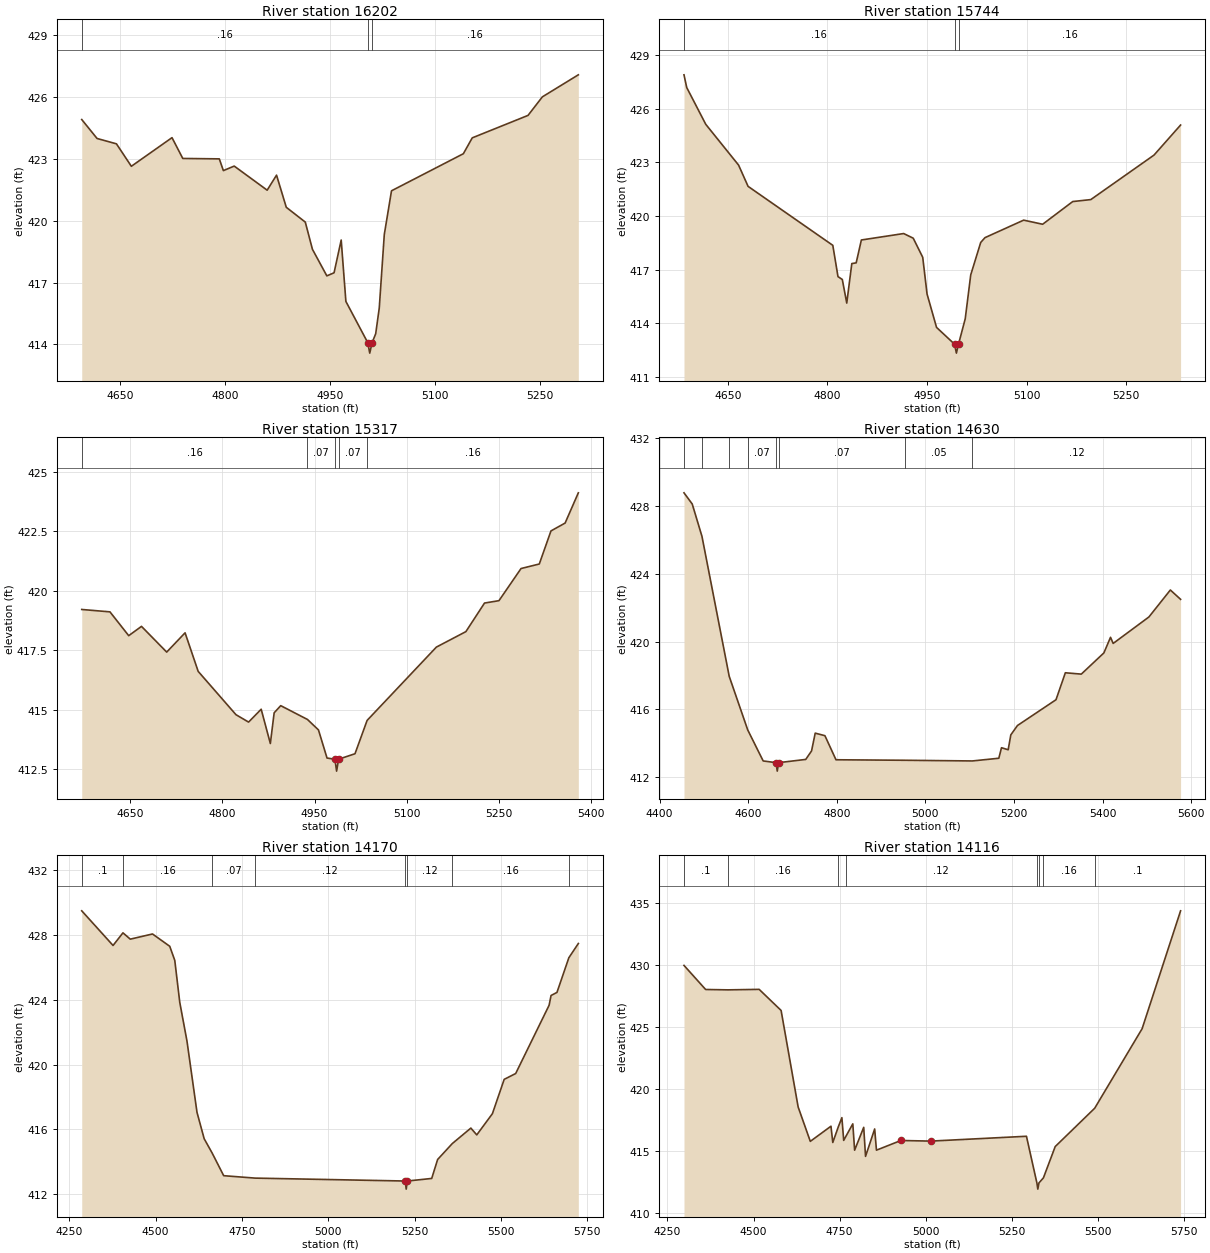
Type RM Length L Ch R = 1 ,16202   ,458,458,458
BEGIN DESCRIPTION:
MOSS SPRING BRANCH 30.0
END DESCRIPTION:
XS GIS Cut Line= 3
        3515202.     10324250.33      3515341.82     10324022.21
      3515442.12      10323591.6
#Sta/Elev= 30
  4595.3  424.92  4617.2     424  4644.9  423.74  4666.2  422.65  4724.3  424.04
  4739.7  423.03  4791.9  423.01  4797.7  422.44  4813.2  422.66  4860.3  421.49
  4873.7  422.22  4887.6  420.66  4914.8  419.94    4925  418.62  4945.6  417.33
  4955.9  417.48  4966.1  419.07  4972.8  416.09  5004.2  414.08  5006.9  413.58
  5010.2  414.08  5015.4  414.52  5020.5  415.77  5027.7  419.34    5038  421.46
  5140.7  423.26  5153.4  424.03  5233.1  425.12  5253.6  426.02    5305  427.09
#Mann= 3 ,-1 , 0
  4595.3     .16       0  5004.2     .07       0  5010.2     .16       0
Bank Sta=5004.2,5010.2
XS Rating Curve= 0 ,0
Exp/Cntr=0.3,0.1

Type RM Length L Ch R = 1 ,15744   ,427,427,427
BEGIN DESCRIPTION:
MOSS SPRING BRANCH 29.0
END DESCRIPTION:
XS GIS Cut Line= 3
      3515474.56     10324429.91      3515724.54     10324129.93
      3515908.36     10323823.53
#Sta/Elev= 30
  4584.2   427.9  4588.3  427.19    4617  425.13  4666.4  422.85  4680.7  421.66
  4808.3  418.36  4816.1  416.61  4822.6  416.45  4829.3  415.13  4836.9  417.34
  4843.5  417.38  4851.3  418.66    4915  419.02  4929.4  418.76  4943.7  417.69
  4950.2  415.64  4964.5  413.77  4991.6  412.83  4994.4  412.33  4997.6  412.83
  5007.7  414.25    5016  416.71    5031  418.52  5037.4  418.79  5095.7  419.77
  5124.3  419.54  5169.6  420.81  5196.8  420.92    5292  423.41    5332  425.09
#Mann= 3 ,-1 , 0
  4584.2     .16       0  4991.6     .07       0  4997.6     .16       0
Bank Sta=4991.6,4997.6
XS Rating Curve= 0 ,0
Exp/Cntr=0.3,0.1

Type RM Length L Ch R = 1 ,15317   ,687,687,687
BEGIN DESCRIPTION:
MOSS SPRING BRANCH 28.0
END DESCRIPTION:
XS GIS Cut Line= 3
      3515989.28     10324706.45      3516055.49     10324412.16
       3516242.1     10323941.66
#Sta/Elev= 30
  4571.3  419.22  4617.2  419.12  4647.7  418.12  4668.5  418.51  4709.5  417.43
  4739.4  418.24  4760.7  416.62  4822.2   414.8  4842.7  414.49  4863.2  415.03
  4878.1  413.59  4884.3  414.88    4895  415.18  4938.5   414.6  4956.4  414.16
  4970.3  412.98  4983.1  412.93  4985.9  412.43  4989.1  412.93  5015.8  413.16
  5035.5  414.56  5148.2  417.64  5196.2  418.29  5226.5  419.49    5250  419.59
  5285.9  420.94  5315.6  421.13  5334.6  422.52  5357.6  422.85  5379.1  424.12
#Mann= 5 ,-1 , 0
  4571.3     .16       0  4938.5     .07       0  4983.1     .07       0
  4989.1     .07       0  5035.5     .16       0
Bank Sta=4983.1,4989.1
XS Rating Curve= 0 ,0
Exp/Cntr=0.3,0.1

Type RM Length L Ch R = 1 ,14630   ,460,460,460
BEGIN DESCRIPTION:
MOSS SPRING BRANCH 26.0
END DESCRIPTION:
XS GIS Cut Line= 3
      3516417.01     10324999.04      3516567.03       10324599.
       3516953.1     10324022.22
#Sta/Elev= 30
    4455  428.77  4473.6  428.11  4495.6   426.2  4557.1  417.95  4598.9  414.79
  4633.8  412.96  4662.8  412.86  4665.6  412.36  4668.8  412.86  4729.9  413.05
    4743  413.55  4751.3   414.6  4773.2  414.45  4798.2  413.03  4954.8     413
  5106.2  412.96  5165.9  413.12  5171.9  413.74    5187  413.62    5193   414.5
    5208  415.05    5295  416.57  5316.1  418.16  5352.1  418.08  5403.1  419.33
  5418.1  420.25  5424.1  419.89  5504.8  421.45  5553.2  423.04  5576.3  422.49
#Mann= 8 ,-1 , 0
    4455     .16       0  4495.6     .12       0  4557.1     .16       0
  4598.9     .07       0  4662.8    .033       0  4668.8     .07       0
  4954.8     .05       0  5106.2     .12       0
Bank Sta=4662.8,4668.8
XS Rating Curve= 0 ,0
Exp/Cntr=0.3,0.1

Type RM Length L Ch R = 1 ,14170   ,54,54,54
BEGIN DESCRIPTION:
MOSS SPRING BRANCH 25.2
END DESCRIPTION:
XS GIS Cut Line= 6
      3516404.12     10325171.33       3516638.5     10324863.16
      3516850.09     10324821.93      3516931.47     10324789.38
      3516992.23     10324744.89      3517273.77      10324134.8
#Sta/Elev= 30
  4285.9   429.5  4376.6  427.36  4405.3  428.14  4426.5  427.75  4490.9  428.07
  4540.8  427.31  4555.4  426.44  4569.9  423.84  4590.7  421.46  4619.8  417.05
  4640.6  415.42  4663.4  414.55  4697.1  413.14  4788.4  412.99  5223.1  412.81
  5225.8  412.31  5229.1  412.81  5299.7  412.97  5316.8  414.14  5359.1  415.12
  5413.1  416.08  5430.2  415.66  5475.5  416.97  5509.6  419.09  5542.9  419.45
  5639.8  423.67  5645.4  424.27  5662.5  424.46  5696.9   426.6  5724.4  427.48
#Mann= 8 ,-1 , 0
  4285.9      .1       0  4405.3     .16       0  4663.4     .07       0
  4788.4     .12       0  5223.1     .07       0  5229.1     .12       0
  5359.1     .16       0  5696.9      .1       0
Bank Sta=5223.1,5229.1
XS Rating Curve= 0 ,0
Exp/Cntr=0.3,0.1

Type RM Length L Ch R = 1 ,14116   ,97,97,97
BEGIN DESCRIPTION:
MOSS SPRING BRANCH 25.1
END DESCRIPTION:
XS GIS Cut Line= 6
      3516421.48     10325189.78      3516707.95     10324904.39
      3516993.32     10324809.99      3517124.61     10324583.21
      3517151.74     10324578.87      3517409.97     10324213.22
#Sta/Elev= 30
  4298.1  429.99  4360.9  428.05  4425.8  428.02  4516.4  428.06  4580.1  426.36
  4629.6  418.58  4664.9  415.81  4724.9  417.03  4730.2  415.72  4746.5     417
  4756.6  417.72  4761.9  415.89  4767.6  416.18  4788.3  417.22  4793.6   415.1
    4820  416.94  4825.3   414.6  4851.8  416.81    4857   415.1    4928  415.88
  5014.5  415.83  5292.6  416.22  5322.9  412.46  5325.6  411.96  5328.9  412.46
  5341.9  412.87  5376.1  415.39  5490.8  418.48  5628.5  424.89  5740.2  434.39
#Mann= 8 ,-1 , 0
  4298.1      .1       0  4425.8     .16       0  4746.5     .07       0
  4767.6     .12       0  5322.9     .07       0  5328.9     .12       0
  5341.9     .16       0  5490.8      .1       0
Bank Sta=4928,5014.5
XS Rating Curve= 0 ,0
Exp/Cntr=0.3,0.1

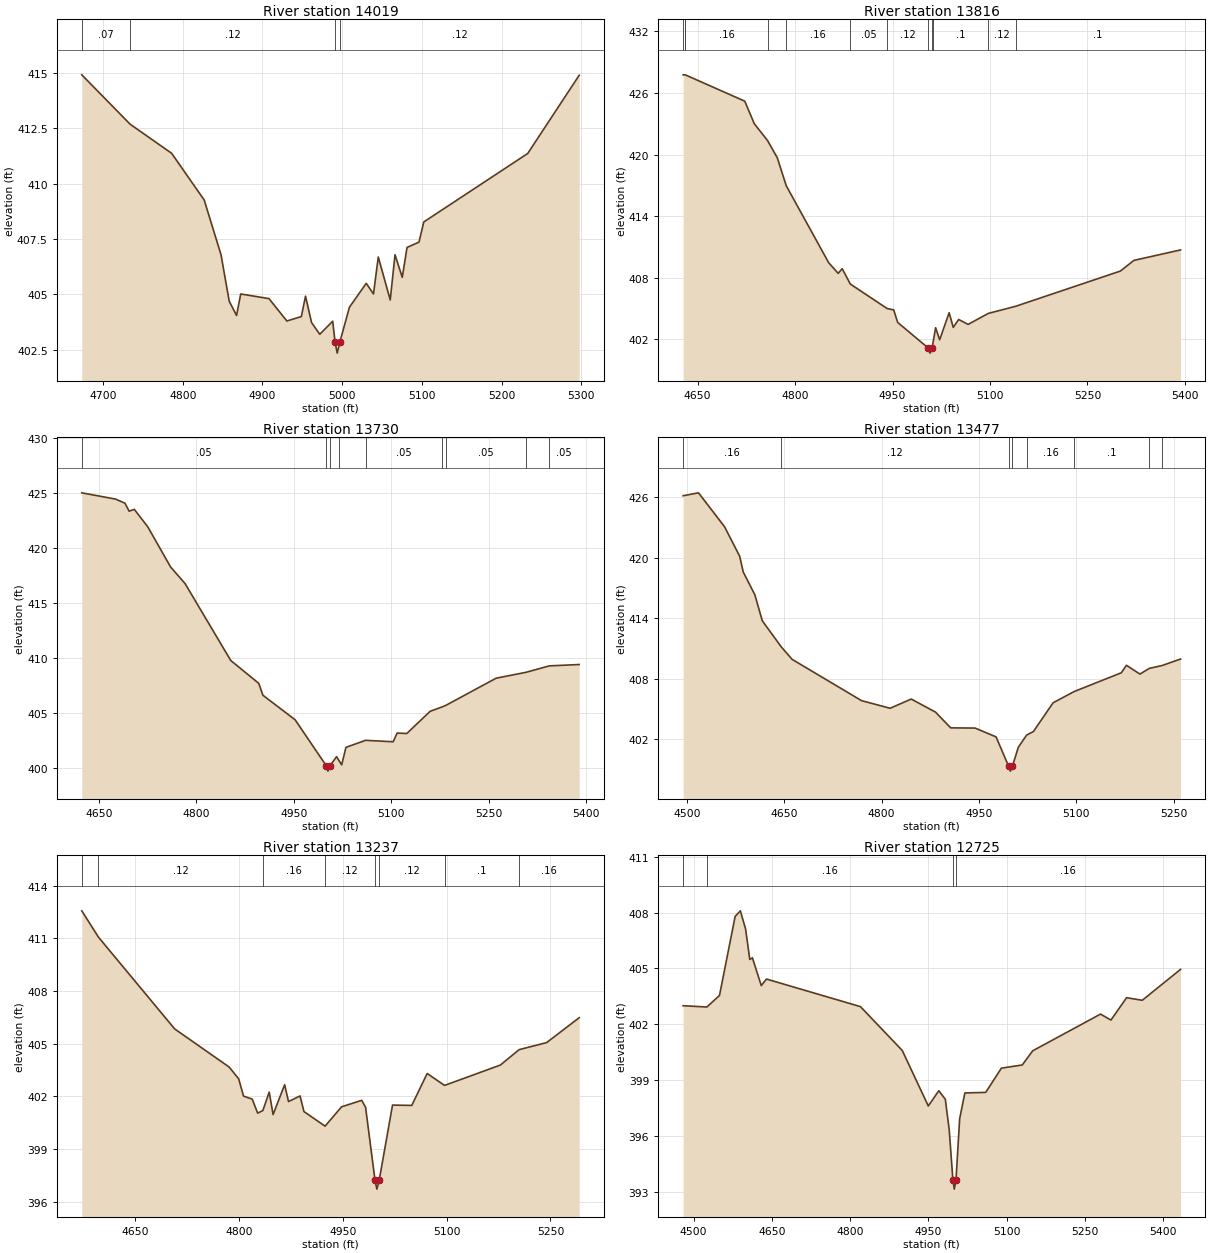
Type RM Length L Ch R = 1 ,14019   ,203,203,203
BEGIN DESCRIPTION:
MOSS SPRING BRANCH 25.0
END DESCRIPTION:
XS GIS Cut Line= 3
      3516753.01      10324966.3      3517055.13     10324888.17
      3517227.01     10324627.73
#Sta/Elev= 30
  4673.3  414.91    4734  412.68    4786  411.37  4826.9  409.26    4848  406.79
  4858.3  404.69  4867.5  404.05  4872.7  405.02  4908.2  404.81  4930.6   403.8
  4948.8     404    4954  404.92  4961.6  403.73  4971.9   403.2  4988.1  403.79
  4991.1  402.85  4993.8  402.35  4997.1  402.85  5009.1  404.42  5030.2   405.5
  5039.3  405.02  5045.3  406.69  5060.3  404.75  5066.3  406.79  5075.4  405.77
  5081.4  407.12  5096.4  407.36  5102.4  408.27  5232.8  411.36  5297.4  414.89
#Mann= 4 ,-1 , 0
  4673.3     .07       0    4734     .12       0  4991.1     .07       0
  4997.1     .12       0
Bank Sta=4991.1,4997.1
XS Rating Curve= 0 ,0
Exp/Cntr=0.3,0.1

Type RM Length L Ch R = 1 ,13816   ,86,86,86
BEGIN DESCRIPTION:
MOSS SPRING BRANCH 24.1
END DESCRIPTION:
XS GIS Cut Line= 3
      3516831.16     10325273.59        3517227.     10324976.71
      3517440.55     10324810.04
#Sta/Elev= 30
  4627.6  427.77  4630.4  427.77  4630.9  427.77  4722.5   425.2  4737.1  423.01
  4757.6  421.36  4772.5  419.69  4786.4  416.95  4851.7  409.45  4866.3  408.42
  4872.5  408.87  4884.9  407.38  4941.8  404.98  4951.7  404.86  4957.9  403.63
  5004.9  401.14  5007.7  400.64  5010.9  401.14  5012.2  401.62  5016.3  403.12
  5022.5  401.94  5037.1  404.58  5043.4  403.15  5051.7  403.92  5066.3  403.44
  5097.3  404.51  5139.7  405.21  5300.7  408.64  5321.5  409.68  5393.3   410.7
#Mann= 12 ,-1 , 0
  4627.6      .1       0  4630.4     .05       0  4630.9     .16       0
  4757.6     .05       0  4786.4     .16       0  4884.9     .05       0
  4941.8     .12       0  5004.9     .07       0  5010.9     .12       0
  5012.2      .1       0  5097.3     .12       0  5139.7      .1       0
Bank Sta=5004.9,5010.9
XS Rating Curve= 0 ,0
Exp/Cntr=0.3,0.1

Type RM Length L Ch R = 1 ,13730   ,253,253,253
BEGIN DESCRIPTION:
MOSS SPRING BRANCH 24.0
END DESCRIPTION:
XS GIS Cut Line= 3
      3516898.87      10325341.3      3517248.71     10325054.47
      3517507.69     10324878.14
#Sta/Elev= 30
  4623.9  424.99  4675.9  424.42  4690.3  424.05  4696.8  423.32  4704.7  423.49
  4725.5   421.9  4760.6  418.25  4782.9  416.74  4853.2  409.75  4896.3  407.67
  4902.7  406.59  4952.3  404.36  5000.1  400.19  5002.8  399.69  5006.1  400.19
  5016.1     401  5020.4   400.6    5024  400.26  5030.5  401.85  5060.8  402.49
  5103.3  402.36  5109.3  403.15  5124.2  403.11  5160.2  405.13  5178.8  405.53
  5184.7  405.68  5261.8  408.14  5307.5  408.67  5343.7  409.26  5389.6  409.38
#Mann= 9 ,-1 , 0
  4623.9     .05       0  5000.1     .04       0  5006.1     .05       0
  5020.4      .1       0  5060.8     .05       0  5178.8      .1       0
  5184.7     .05       0  5307.5      .1       0  5343.7     .05       0
Bank Sta=5000.1,5006.1
XS Rating Curve= 0 ,0
Exp/Cntr=0.3,0.1

Type RM Length L Ch R = 1 ,13477   ,240,240,240
BEGIN DESCRIPTION:
Mapping XS 560de427
END DESCRIPTION:
XS GIS Cut Line= 3
      3517220.57      10325553.3       3517482.3     10324959.53
      3517558.09     10324869.61
#Sta/Elev= 30
  4494.3  426.11    4518   426.4  4558.1  423.05  4581.5  420.12  4586.9  418.57
  4604.8  416.32  4616.3  413.74  4645.8  411.14  4662.4  409.92  4769.3  405.84
  4813.3  405.09  4845.8     406  4883.2  404.71  4906.6  403.15  4944.2  403.13
  4976.5  402.26  4995.8  399.37  4998.6  398.87  5001.8  399.37  5010.8  401.23
  5023.7  402.44  5034.1  402.79  5064.4  405.63  5096.8  406.74  5169.6   408.6
  5177.4  409.34  5198.2  408.47  5212.9  409.04  5232.6  409.32  5260.8  409.96
#Mann= 8 ,-1 , 0
  4494.3     .16       0  4645.8     .12       0  4995.8     .07       0
  5001.8     .12       0  5023.7     .16       0  5096.8      .1       0
  5212.9     .05       0  5232.6     .16       0
Bank Sta=4995.8,5001.8
XS Rating Curve= 0 ,0
Exp/Cntr=0.3,0.1

Type RM Length L Ch R = 1 ,13237   ,512,512,512
BEGIN DESCRIPTION:
MOSS SPRING BRANCH 23.0
END DESCRIPTION:
XS GIS Cut Line= 3
      3517392.09     10325541.66      3517555.13     10325356.92
      3517768.65     10324935.08
#Sta/Elev= 30
  4572.4  412.57  4596.5  411.07  4706.7  405.84  4785.4  403.67  4799.2     403
  4806.3  402.01  4818.8  401.84  4826.7  401.04  4834.2  401.19  4843.4  402.24
    4849  400.96  4865.7  402.66  4871.3   401.7    4888  402.02  4893.6  401.13
  4924.2   400.3    4948   401.4  4977.1  401.77  4982.7  401.38  4996.4  397.21
  4999.1  396.71  5002.4  397.21  5021.7   401.5  5049.5  401.48  5071.8   403.3
  5096.9  402.62  5177.6  403.78  5204.8  404.66  5244.5  405.06  5291.6  406.48
#Mann= 8 ,-1 , 0
  4572.4     .16       0  4596.5     .12       0  4834.2     .16       0
  4924.2     .12       0  4996.4     .07       0  5002.4     .12       0
  5096.9      .1       0  5204.8     .16       0
Bank Sta=4996.4,5002.4
XS Rating Curve= 0 ,0
Exp/Cntr=0.3,0.1

Type RM Length L Ch R = 1 ,12725   ,763,763,763
BEGIN DESCRIPTION:
MOSS SPRING BRANCH 22.0
END DESCRIPTION:
XS GIS Cut Line= 3
      3517971.79     10325841.29      3517992.11     10325341.64
      3517992.63     10324888.21
#Sta/Elev= 30
  4479.8     403  4525.4  402.93  4549.5  403.55  4579.5  407.79  4589.5  408.09
  4599.5  407.12  4607.6  405.48  4612.6  405.57  4629.6  404.08  4639.6  404.43
  4819.7  402.95  4899.8   400.6  4949.8  397.62  4969.9  398.44  4982.4  397.98
  4989.9  396.33  4996.9  393.66  4999.6  393.16  5002.9  393.66  5009.9  396.94
  5019.9  398.32  5059.9  398.35  5089.9  399.65  5129.9  399.82  5149.9  400.58
  5279.9  402.55  5299.9  402.23  5329.9  403.43  5359.9  403.29  5433.3  404.95
#Mann= 4 ,-1 , 0
  4479.8     .12       0  4525.4     .16       0  4996.9     .07       0
  5002.9     .16       0
Bank Sta=4996.9,5002.9
XS Rating Curve= 0 ,0
Exp/Cntr=0.3,0.1

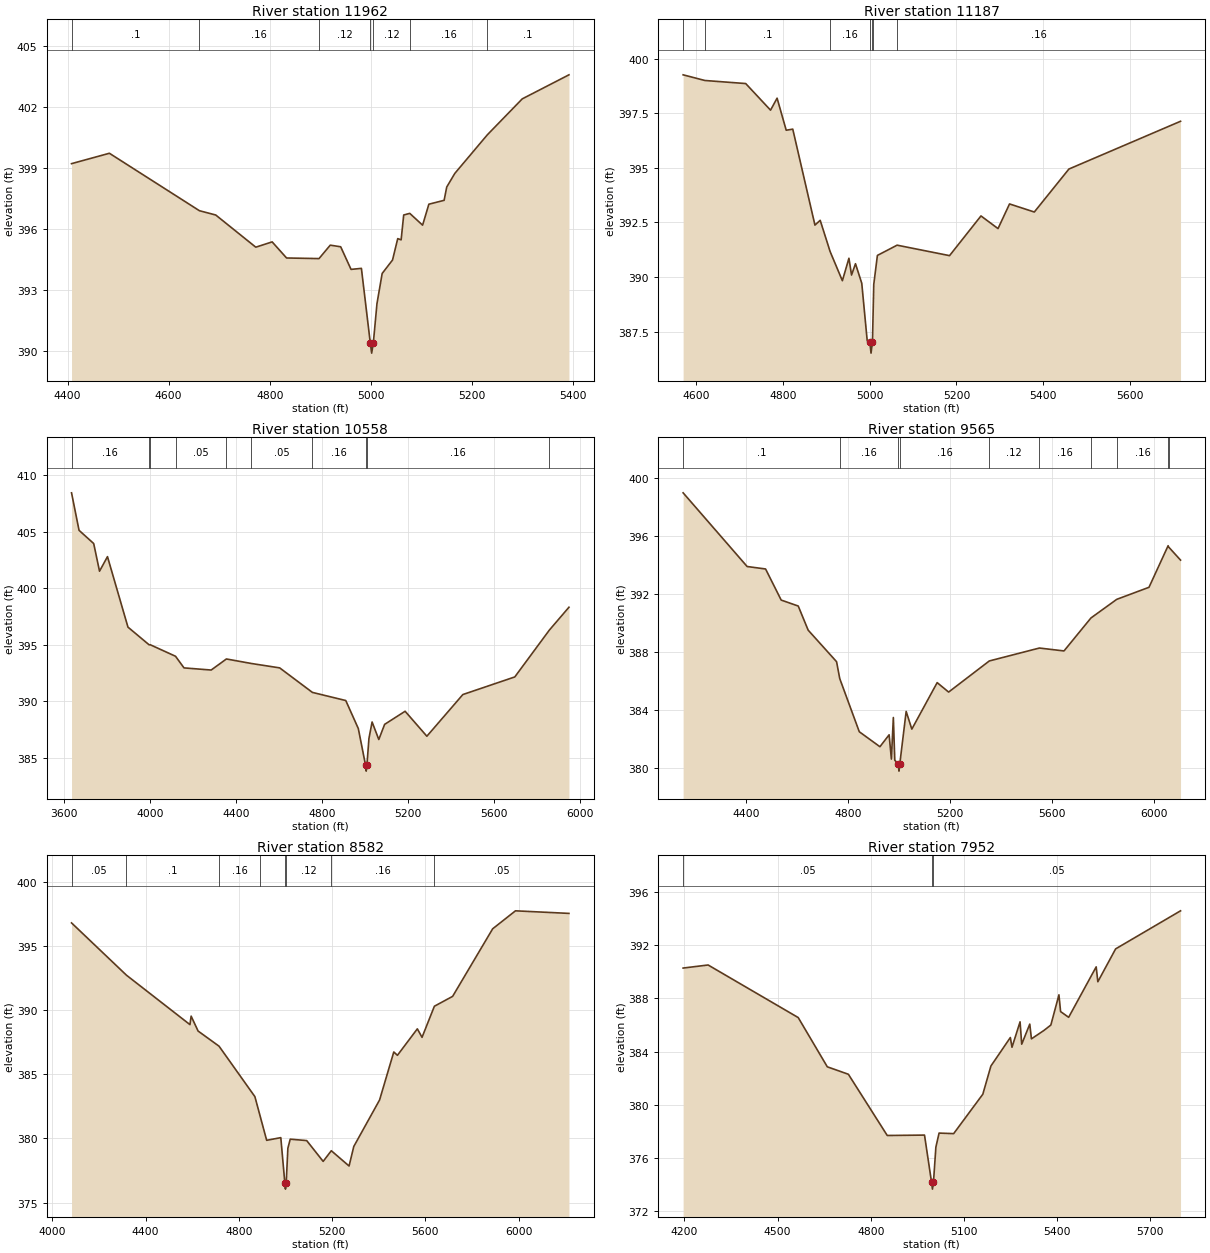
Type RM Length L Ch R = 1 ,11962   ,775,775,775
BEGIN DESCRIPTION:
MOSS SPRING BRANCH 21.0
END DESCRIPTION:
XS GIS Cut Line= 3
      3518383.24     10325820.49      3518565.54     10325435.05
       3518692.1     10324891.67
#Sta/Elev= 30
  4407.8  399.21  4482.7  399.72  4660.9   396.9  4693.1  396.69  4772.4  395.11
  4804.8  395.37  4833.3  394.58  4897.5  394.55  4919.8  395.21  4940.4  395.13
  4960.9  394.02  4981.4  394.07    4999  390.41  5001.7  389.91    5005  390.41
  5012.2  392.34  5022.5  393.82    5043  394.48  5053.3  395.53    5060  395.47
  5065.1  396.69  5077.1  396.77  5102.5  396.19  5114.9  397.22  5145.1  397.41
  5150.2  398.06  5166.2  398.73  5230.4  400.62  5299.7  402.39  5392.1  403.57
#Mann= 7 ,-1 , 0
  4407.8      .1       0  4660.9     .16       0  4897.5     .12       0
    4999     .07       0    5005     .12       0  5077.1     .16       0
  5230.4      .1       0
Bank Sta=4999,5005
XS Rating Curve= 0 ,0
Exp/Cntr=0.3,0.1

Type RM Length L Ch R = 1 ,11187   ,629,629,629
BEGIN DESCRIPTION:
MOSS SPRING BRANCH 20.0
END DESCRIPTION:
XS GIS Cut Line= 3
      3518518.64     10326117.36      3519070.75     10325752.75
      3519211.36     10325289.25
#Sta/Elev= 30
  4570.3  399.27  4620.5  399.01  4714.5  398.87  4771.7  397.65  4786.8   398.2
  4807.8  396.73  4822.9  396.78    4874  392.38  4886.1   392.6  4908.9  391.17
  4937.2  389.83  4952.3  390.86  4958.3  390.09  4967.4  390.61  4981.9  389.71
  4994.4  387.08  5000.5  387.01  5003.2  386.51  5006.5  387.01  5007.9  388.25
  5009.5  389.66  5017.9  390.99  5063.3  391.46  5184.1  390.98  5256.5   392.8
  5295.8  392.22  5322.3  393.35  5379.4  392.98  5459.1  394.95  5716.3  397.14
#Mann= 7 ,-1 , 0
  4570.3     .05       0  4620.5      .1       0  4908.9     .16       0
  5000.5     .07       0  5006.5     .16       0  5007.9      .1       0
  5063.3     .16       0
Bank Sta=5000.5,5006.5
XS Rating Curve= 0 ,0
Exp/Cntr=0.3,0.1

Type RM Length L Ch R = 1 ,10558   ,993,993,993
BEGIN DESCRIPTION:
MOSS SPRING BRANCH 18.0
END DESCRIPTION:
XS GIS Cut Line= 3
      3518042.13     10326891.63      3519534.29     10326002.75
      3519836.39     10325507.93
#Sta/Elev= 30
  3633.7  408.46  3668.7  405.14  3736.9  403.97  3764.1  401.52  3801.1  402.81
  3896.5  396.57  3995.2     395  4000.2  395.01    4118  393.99  4157.5  392.96
    4284  392.77    4355  393.75  4471.3  393.35  4603.2  392.96  4755.5  390.79
  4910.9  390.07  4969.3  387.59  5003.3  384.32    5006  383.82  5009.3  384.32
  5018.8  386.71  5033.5  388.17  5064.7  386.62  5091.9  387.96  5187.3  389.12
  5288.6  386.91  5456.2   390.6  5698.1  392.16  5859.2  396.31  5950.3  398.33
#Mann= 10 ,-1 , 0
  3633.7     .16       0  3995.2     .05       0  4000.2      .1       0
    4118     .05       0    4355      .1       0  4471.3     .05       0
  4755.5     .16       0  5003.3     .07       0  5009.3     .16       0
  5859.2     .05       0
Bank Sta=5003.3,5009.3
XS Rating Curve= 0 ,0
Exp/Cntr=0.3,0.1

Type RM Length L Ch R = 1 ,9565    ,983,983,983
BEGIN DESCRIPTION:
MOSS SPRING BRANCH 17.0
END DESCRIPTION:
XS GIS Cut Line= 3
      3519253.04     10327539.22      3519753.04     10326554.84
      3519987.27     10325742.84
#Sta/Elev= 30
  4153.2  398.96    4404  393.89  4476.3  393.72  4537.5  391.58  4604.3  391.17
  4643.2  389.51  4754.5  387.34  4766.9  386.18  4843.5  382.52  4924.4  381.49
  4960.4  382.31  4969.3  380.64    4977   383.5  4982.6  380.56  4996.3  380.31
    4999  379.81  5002.3  380.31  5027.2  383.92  5049.4   382.7  5148.7   385.9
  5193.6  385.25  5352.9  387.39  5549.3  388.28  5645.7  388.08  5751.4  390.35
  5852.4  391.63  5978.8  392.46  6053.7  395.32  6055.4  395.24  6102.4  394.33
#Mann= 10 ,-1 , 0
  4153.2      .1       0  4766.9     .16       0  4996.3     .07       0
  5002.3     .16       0  5352.9     .12       0  5549.3     .16       0
  5751.4     .05       0  5852.4     .16       0  6053.7     .05       0
  6055.4     .16       0
Bank Sta=4996.3,5002.3
XS Rating Curve= 0 ,0
Exp/Cntr=0.3,0.1

Type RM Length L Ch R = 1 ,8582    ,630,630,630
BEGIN DESCRIPTION:
MOSS SPRING BRANCH 15.0
END DESCRIPTION:
XS GIS Cut Line= 3
      3520258.77     10327604.16      3520393.67     10326919.42
      3520195.75     10325497.53
#Sta/Elev= 30
  4082.3  396.78  4317.8  392.71  4590.2  388.86  4595.3  389.52  4625.1  388.36
    4715  387.18  4868.8  383.25  4889.7  381.84  4919.3  379.85  4979.9  380.06
  4997.1  376.55  4999.8  376.05  5003.1  376.55  5010.2  379.23  5020.3  379.94
  5090.9  379.83  5161.6  378.21  5196.5  379.04  5272.7  377.85  5292.9  379.37
  5403.5  382.99  5464.5  386.73  5480.1  386.47  5565.5  388.53  5585.7  387.87
  5638.6  390.29  5716.9  391.06  5888.6  396.32  5986.4  397.72  6215.8  397.52
#Mann= 8 ,-1 , 0
  4082.3     .05       0  4317.8      .1       0    4715     .16       0
  4889.7     .12       0  4997.1     .07       0  5003.1     .12       0
  5196.5     .16       0  5638.6     .05       0
Bank Sta=4997.1,5003.1
XS Rating Curve= 0 ,0
Exp/Cntr=0.3,0.1

Type RM Length L Ch R = 1 ,7952    ,147,147,147
BEGIN DESCRIPTION:
MOSS SPRING BRANCH 14.0
END DESCRIPTION:
XS GIS Cut Line= 3
      3520466.04     10327232.08      3520479.06     10326850.11
      3520873.69     10325695.69
#Sta/Elev= 30
  4195.7  390.27  4276.2   390.5  4566.4  386.55  4660.1  382.85    4728  382.29
  4853.2  377.69  4973.2  377.72    4996  374.16  4998.8  373.66    5002  374.16
  5009.8  376.81  5020.1  377.87  5067.1  377.83    5161  380.79  5187.1  382.91
  5249.7  385.05    5255  384.32    5281  386.23  5286.3  384.55  5312.3  386.06
  5317.6  384.95  5358.3  385.59  5380.2  385.99  5406.2  388.26  5411.5     387
  5437.5  386.57  5526.2  390.36  5531.5  389.24  5588.8  391.71  5797.9  394.57
#Mann= 3 ,-1 , 0
  4195.7     .05       0    4996     .04       0    5002     .05       0
Bank Sta=4996,5002
XS Rating Curve= 0 ,0
Exp/Cntr=0.3,0.1

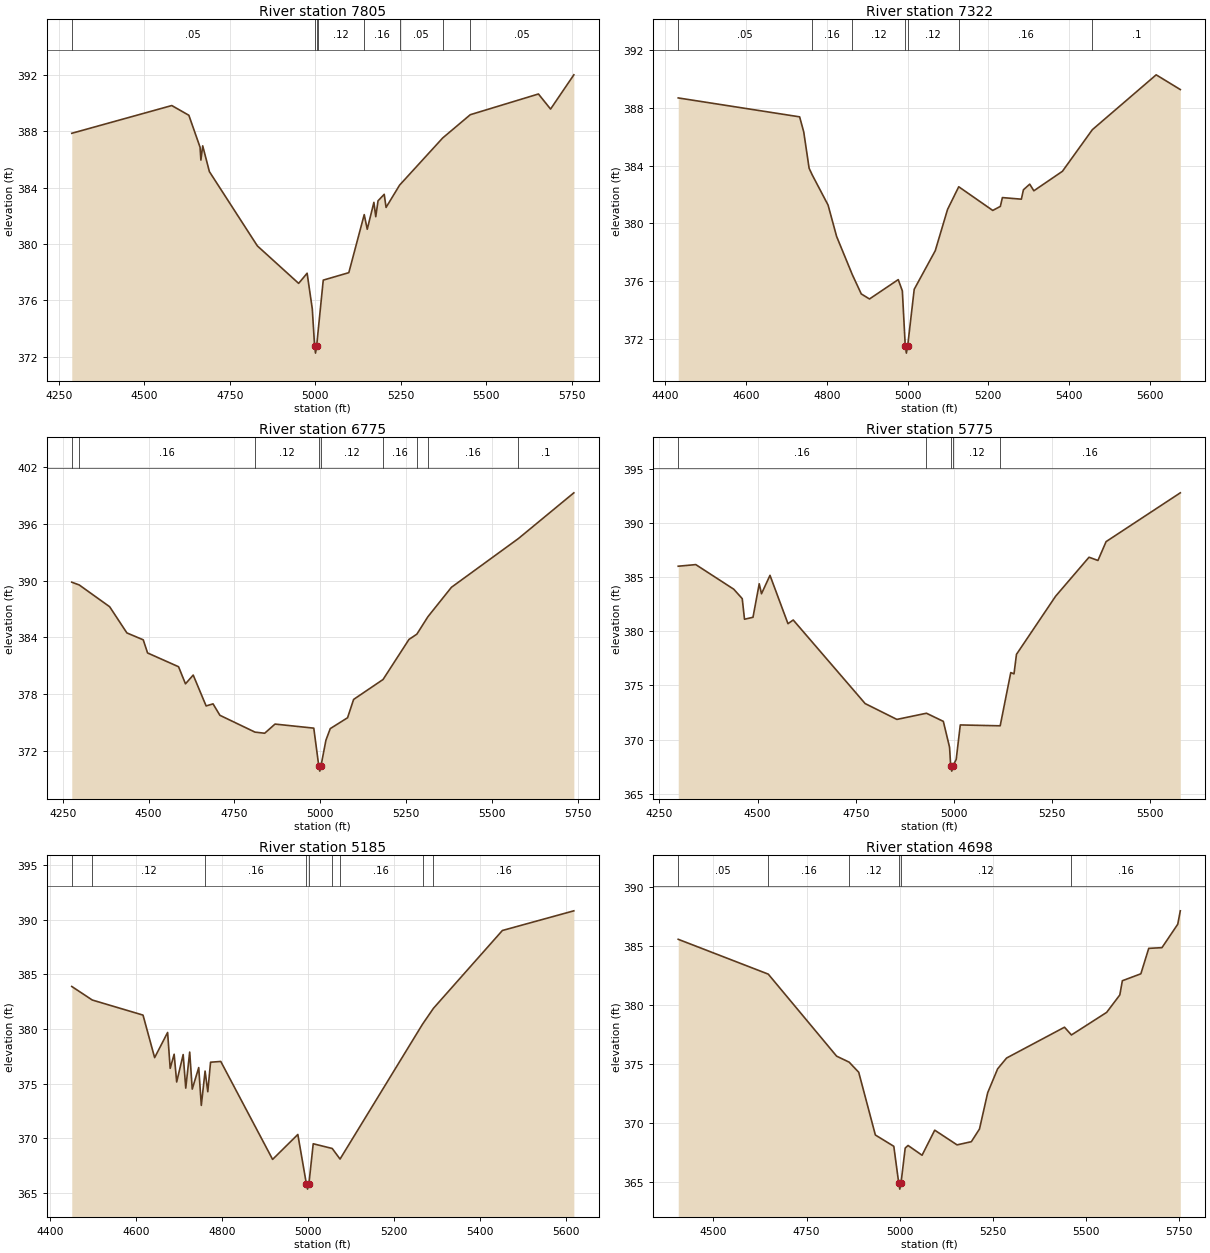
Type RM Length L Ch R = 1 ,7805    ,483,483,483
BEGIN DESCRIPTION:
Mapping XS 908fffc6
END DESCRIPTION:
XS GIS Cut Line= 3
      3520594.08     10327234.22      3520596.25     10326858.79
      3520982.12     10325835.57
#Sta/Elev= 30
  4287.6  387.86  4580.2  389.83  4630.2  389.14    4663  386.87  4665.4  385.96
  4670.7  386.97  4690.3  385.14  4830.6  379.87  4951.4  377.21  4976.2  377.93
  4991.3  375.41  4998.1  372.76  5000.8  372.26  5004.1  372.76  5008.7   373.9
  5023.4  377.44  5098.2  377.97  5143.3  382.09  5152.1  381.05  5171.6  382.96
    5177  381.94  5183.7  383.07  5201.8  383.53  5207.2   382.6  5246.7  384.18
  5372.9  387.53  5453.6  389.18    5653  390.65  5688.5  389.58  5756.6  392.01
#Mann= 8 ,-1 , 0
  4287.6     .05       0  4998.1     .04       0  5004.1     .05       0
  5008.7     .12       0  5143.3     .16       0  5246.7     .05       0
  5372.9     .16       0  5453.6     .05       0
Bank Sta=4998.1,5004.1
XS Rating Curve= 0 ,0
Exp/Cntr=0.3,0.1

Type RM Length L Ch R = 1 ,7322    ,547,547,547
BEGIN DESCRIPTION:
MOSS SPRING BRANCH 13.0
END DESCRIPTION:
XS GIS Cut Line= 3
      3520966.59     10327237.09      3521133.77     10326362.48
      3521183.77     10326012.48
#Sta/Elev= 30
  4431.6  388.69  4732.4  387.38  4742.6  386.33  4755.9  383.82  4763.8  383.35
  4802.9  381.27    4824   379.1    4863  376.45  4885.1  375.12  4905.5  374.77
  4976.7  376.11  4986.9  375.33  4994.1  371.52  4996.9  371.02  5000.1  371.52
  5016.3  375.44  5068.4  378.11  5098.9  380.97  5126.6  382.54  5210.9   380.9
  5229.7  381.18  5234.8  381.79  5281.8  381.68  5286.9  382.33  5302.5  382.72
  5312.7  382.26  5383.5  383.61  5457.6  386.49  5615.8  390.29  5675.6  389.27
#Mann= 7 ,-1 , 0
  4431.6     .05       0  4763.8     .16       0    4863     .12       0
  4994.1     .07       0  5000.1     .12       0  5126.6     .16       0
  5457.6      .1       0
Bank Sta=4994.1,5000.1
XS Rating Curve= 0 ,0
Exp/Cntr=0.3,0.1

Type RM Length L Ch R = 1 ,6775    ,1000,1000,1000
BEGIN DESCRIPTION:
MOSS SPRING BRANCH 11.0
END DESCRIPTION:
XS GIS Cut Line= 3
       3521442.1     10327341.66      3521492.11     10326641.64
      3521586.37     10325888.21
#Sta/Elev= 30
  4276.5  389.85  4298.1  389.56  4386.8  387.25  4436.9  384.48  4484.5  383.75
  4497.1  382.36  4587.3   380.9  4607.4  379.09  4629.9  380.02  4667.5  376.75
  4687.6  376.97  4707.6  375.76  4809.6  373.98  4837.9  373.86    4868  374.83
  4980.8   374.4  4995.5  370.35  4998.2  369.85  5001.5  370.35  5016.1  373.12
  5028.7  374.35  5079.1   375.5  5096.7  377.44  5182.4  379.55  5257.8  383.79
  5280.8  384.35  5312.8  386.19  5381.4  389.31  5576.3  394.47  5737.6  399.31
#Mann= 9 ,-1 , 0
  4276.5      .1       0  4298.1     .16       0  4809.6     .12       0
  4995.5     .07       0  5001.5     .12       0  5182.4     .16       0
  5280.8      .1       0  5312.8     .16       0  5576.3      .1       0
Bank Sta=4995.5,5001.5
XS Rating Curve= 0 ,0
Exp/Cntr=0.3,0.1

Type RM Length L Ch R = 1 ,5775    ,590,590,590
BEGIN DESCRIPTION:
MOSS SPRING BRANCH 9.0
END DESCRIPTION:
XS GIS Cut Line= 3
      3521794.69     10327304.87      3522142.11     10326691.64
      3522492.64     10326237.11
#Sta/Elev= 30
  4297.8     386  4342.5  386.15  4439.2  383.88  4460.8  383.01  4466.6  381.11
  4488.2  381.29  4504.1  384.38  4509.9  383.46  4531.5  385.16  4577.3   380.7
  4590.7  381.04  4773.9  373.33  4854.7  371.87    4930  372.44    4973  371.69
  4988.9   369.3  4991.7   367.6  4994.4   367.1  4997.7   367.6  5005.8  368.18
  5016.2  371.36  5117.8  371.28  5144.8  376.19    5153  376.07  5159.3  377.87
  5258.9  383.23  5344.1  386.83  5366.8  386.53  5387.6  388.27  5576.6  392.77
#Mann= 5 ,-1 , 0
  4297.8     .16       0    4930     .12       0  4991.7     .07       0
  4997.7     .12       0  5117.8     .16       0
Bank Sta=4991.7,4997.7
XS Rating Curve= 0 ,0
Exp/Cntr=0.3,0.1

Type RM Length L Ch R = 1 ,5185    ,487,487,487
BEGIN DESCRIPTION:
MOSS SPRING BRANCH 8.0
END DESCRIPTION:
XS GIS Cut Line= 3
      3522154.11     10327481.89      3522610.86     10326783.31
      3522760.03     10326484.97
#Sta/Elev= 30
  4450.7  383.88  4498.4  382.64  4616.5  381.26  4643.5  377.37  4673.7  379.67
  4679.7  376.39  4688.9  377.68  4694.8  375.14  4709.9  377.65  4715.9  374.58
  4725.1  377.88    4731  374.49  4746.1  376.46  4752.1     373  4760.9  376.14
  4767.2  374.25  4773.6  376.95  4797.4  377.02    4918  368.06  4976.7  370.34
  4996.5  365.84  4999.3  365.34  5002.5  365.84  5012.5  369.49  5056.7  369.06
  5074.9  368.09    5267  380.44  5292.2  381.88  5452.6     389  5618.9   390.8
#Mann= 9 ,-1 , 0
  4450.7     .16       0  4498.4     .12       0  4760.9     .16       0
  4996.5     .07       0  5002.5     .16       0  5056.7     .12       0
  5074.9     .16       0    5267     .12       0  5292.2     .16       0
Bank Sta=4996.5,5002.5
XS Rating Curve= 0 ,0
Exp/Cntr=0.3,0.1

Type RM Length L Ch R = 1 ,4698    ,677,677,677
BEGIN DESCRIPTION:
MOSS SPRING BRANCH 7.0
END DESCRIPTION:
XS GIS Cut Line= 3
      3522435.34      10327789.2      3522841.58      10327028.8
      3523180.12     10326679.84
#Sta/Elev= 30
  4405.4  385.59  4647.2  382.63  4830.7  375.66  4864.4  375.15  4890.1  374.29
  4934.8  368.96  4984.3     368  4997.6  364.86  5000.4  364.36  5003.6  364.86
  5014.9  367.85  5022.6  368.07  5060.2  367.24  5094.2  369.37  5154.2  368.12
  5192.5  368.39  5214.4  369.47  5236.4  372.55  5263.1  374.58  5287.1   375.5
  5442.7  378.12  5461.3  377.46  5555.9  379.38  5591.2  380.86  5598.1  382.07
  5647.8  382.66  5668.9  384.82  5704.4  384.88  5746.8  386.87  5753.7  388.01
#Mann= 6 ,-1 , 0
  4405.4     .05       0  4647.2     .16       0  4864.4     .12       0
  4997.6     .07       0  5003.6     .12       0  5461.3     .16       0
Bank Sta=4997.6,5003.6
XS Rating Curve= 0 ,0
Exp/Cntr=0.3,0.1

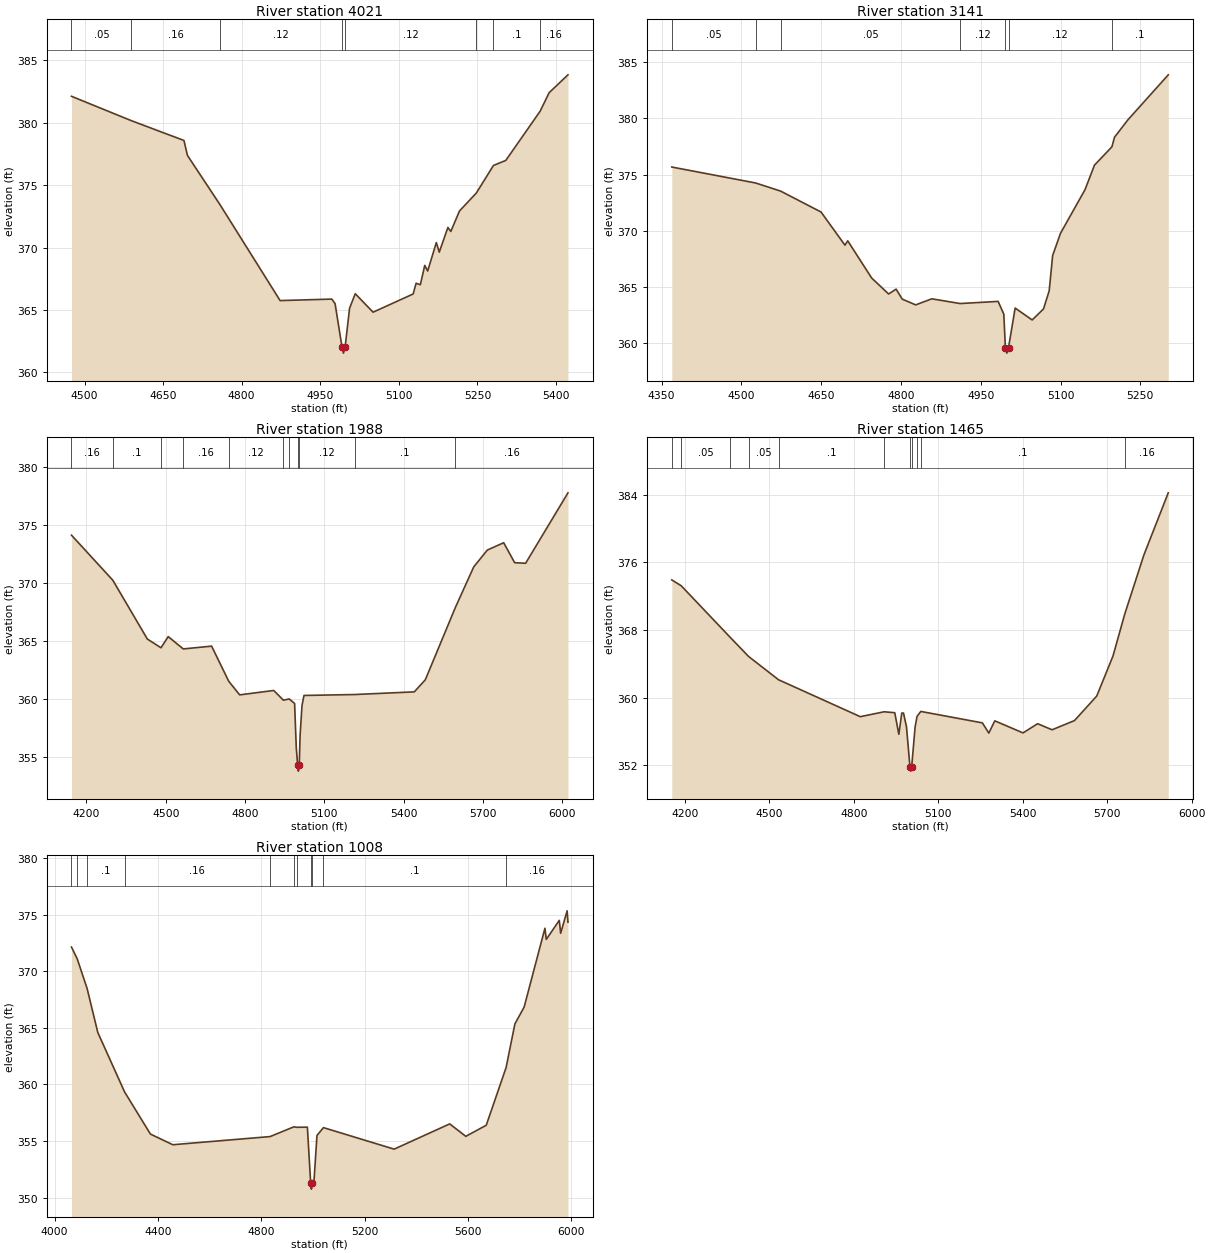
Type RM Length L Ch R = 1 ,4021    ,880,880,880
BEGIN DESCRIPTION:
MOSS SPRING BRANCH 6.0
END DESCRIPTION:
XS GIS Cut Line= 3
      3522987.42     10327872.54      3523107.21     10327685.05
      3523442.09     10327041.67
#Sta/Elev= 30
  4475.1  382.12  4589.2  380.17  4689.8  378.58  4696.5  377.38  4758.1  373.47
  4873.4  365.75    4972  365.87  4978.3  365.51  4991.5  362.04  4994.3  361.54
  4997.5  362.04    5006  365.14  5016.8   366.3  5050.9  364.82  5127.4  366.28
    5133  367.14  5141.1  367.02  5149.5  368.57  5155.1  368.12  5171.6   370.4
  5177.2  369.63  5193.7  371.61  5199.3  371.29  5215.8  372.93    5248  374.37
  5280.7  376.58  5304.2  376.98  5369.7  380.92    5387  382.41  5422.9  383.84
#Mann= 8 ,-1 , 0
  4475.1     .05       0  4589.2     .16       0  4758.1     .12       0
  4991.5     .07       0  4997.5     .12       0    5248     .16       0
  5280.7      .1       0  5369.7     .16       0
Bank Sta=4991.5,4997.5
XS Rating Curve= 0 ,0
Exp/Cntr=0.3,0.1

Type RM Length L Ch R = 1 ,3141    ,1153,1153,1153
BEGIN DESCRIPTION:
MOSS SPRING BRANCH 4.0
END DESCRIPTION:
XS GIS Cut Line= 3
      3523690.55     10328033.99      3523773.88     10327632.96
      3523592.09     10327141.61
#Sta/Elev= 30
  4369.1  375.67  4526.9  374.25  4573.7  373.53  4649.7  371.67  4694.7  368.72
  4699.9  369.11  4744.9   365.8  4776.8  364.38  4790.8  364.81  4802.5  363.92
  4827.6  363.41    4858  363.95  4911.2  363.53  4982.7  363.72  4993.4  362.58
  4996.3  359.62  4999.1  359.12  5002.3  359.62  5014.7  363.13  5046.7  362.07
    5068  363.05  5078.7  364.66  5085.2   367.8    5100  369.78    5146  373.65
  5163.9  375.84  5196.7  377.47  5201.5  378.32  5226.6  379.86  5302.6  383.87
#Mann= 7 ,-1 , 0
  4369.1     .05       0  4526.9     .16       0  4573.7     .05       0
  4911.2     .12       0  4996.3     .07       0  5002.3     .12       0
  5196.7      .1       0
Bank Sta=4996.3,5002.3
XS Rating Curve= 0 ,0
Exp/Cntr=0.3,0.1

Type RM Length L Ch R = 1 ,1988    ,523,523,523
BEGIN DESCRIPTION:
MOSS SPRING BRANCH 3.0
END DESCRIPTION:
XS GIS Cut Line= 3
      3523883.26     10328185.04      3524518.67     10327351.71
      3524716.31     10326545.53
#Sta/Elev= 30
  4143.4  374.09  4299.7  370.21  4430.4  365.14    4482  364.39  4509.3  365.35
  4566.3  364.29  4673.5  364.53  4738.1  361.51  4779.6  360.33  4908.4  360.71
  4945.1  359.87    4967  359.98  4987.4  359.59  4993.7  355.77  4998.9  354.26
  5001.7  353.76  5004.9  354.26  5008.2  356.88  5015.4  359.42  5022.8  360.28
  5214.2  360.36  5440.2  360.59  5481.8  361.63  5595.5  367.86    5665  371.36
  5716.5  372.81  5778.3  373.44  5819.7  371.72  5861.3  371.67  6021.4  377.74
#Mann= 11 ,-1 , 0
  4143.4     .16       0  4299.7      .1       0    4482     .05       0
  4566.3     .16       0  4738.1     .12       0  4945.1     .16       0
    4967     .12       0  4998.9     .07       0  5004.9     .12       0
  5214.2      .1       0  5595.5     .16       0
Bank Sta=4998.9,5004.9
XS Rating Curve= 0 ,0
Exp/Cntr=0.3,0.1

Type RM Length L Ch R = 1 ,1465    ,457,457,457
BEGIN DESCRIPTION:
MOSS SPRING BRANCH 2.0
END DESCRIPTION:
XS GIS Cut Line= 3
      3524292.09     10328441.67      3524792.11     10327791.64
      3525292.11     10326991.63
#Sta/Elev= 30
  4153.4  373.93  4186.8  373.24  4361.6  367.11  4426.7  364.86  4532.5  362.12
    4823  357.75  4907.6  358.33  4945.4  358.22  4959.9  355.67  4970.3  358.18
  4976.4  358.18  4987.1  356.55  4999.4  351.81  5002.1  351.31  5005.4  351.81
  5017.7  356.54  5024.6  357.79  5037.9  358.37  5256.5  357.02  5279.5  355.81
  5300.7  357.26    5401  355.83  5452.9  356.92  5504.2   356.2  5583.8  357.29
  5662.8  360.19  5720.5  364.92  5762.5  369.91  5830.2  376.87  5916.9  384.23
#Mann= 11 ,-1 , 0
  4153.4     .16       0  4186.8     .05       0  4361.6      .1       0
  4426.7     .05       0  4532.5      .1       0  4907.6     .16       0
  4999.4     .07       0  5005.4     .16       0  5024.6     .12       0
  5037.9      .1       0  5762.5     .16       0
Bank Sta=4999.4,5005.4
XS Rating Curve= 0 ,0
Exp/Cntr=0.3,0.1

Type RM Length L Ch R = 1 ,1008    ,0,0,0
BEGIN DESCRIPTION:
MOSS SPRING BRANCH 1.0
END DESCRIPTION:
XS GIS Cut Line= 3
       3524392.1     10328441.64      3525070.75     10328195.46
      3525487.24     10327070.93
#Sta/Elev= 30
  4065.3  372.13  4087.3   371.1  4125.7  368.48  4167.1  364.59  4270.8  359.34
  4370.8  355.62  4457.4  354.68  4833.9   355.4  4925.8  356.26  4937.1  356.22
  4978.1  356.23  4990.9  351.26  4993.7  350.76  4996.9  351.26  5003.1  351.28
  5015.2   355.5  5040.3  356.19  5313.8  354.29  5528.9  356.52  5591.1  355.42
  5670.2   356.4  5747.1   361.5  5781.1  365.35  5816.8  366.83  5897.3  373.79
  5902.6  372.81  5952.8  374.49  5958.1  373.35  5983.2  375.33  5986.4  374.33
#Mann= 11 ,-1 , 0
  4065.3      .1       0  4087.3     .05       0  4125.7      .1       0
  4270.8     .16       0  4833.9     .12       0  4925.8     .16       0
  4937.1     .12       0  4990.9     .07       0  4996.9     .12       0
  5040.3      .1       0  5747.1     .16       0
Bank Sta=4990.9,4996.9
XS Rating Curve= 0 ,0
Exp/Cntr=0.3,0.1

Chan Stop Cuts=-1
Use User Specified Reach Order=0
Composite Channel Slope=5