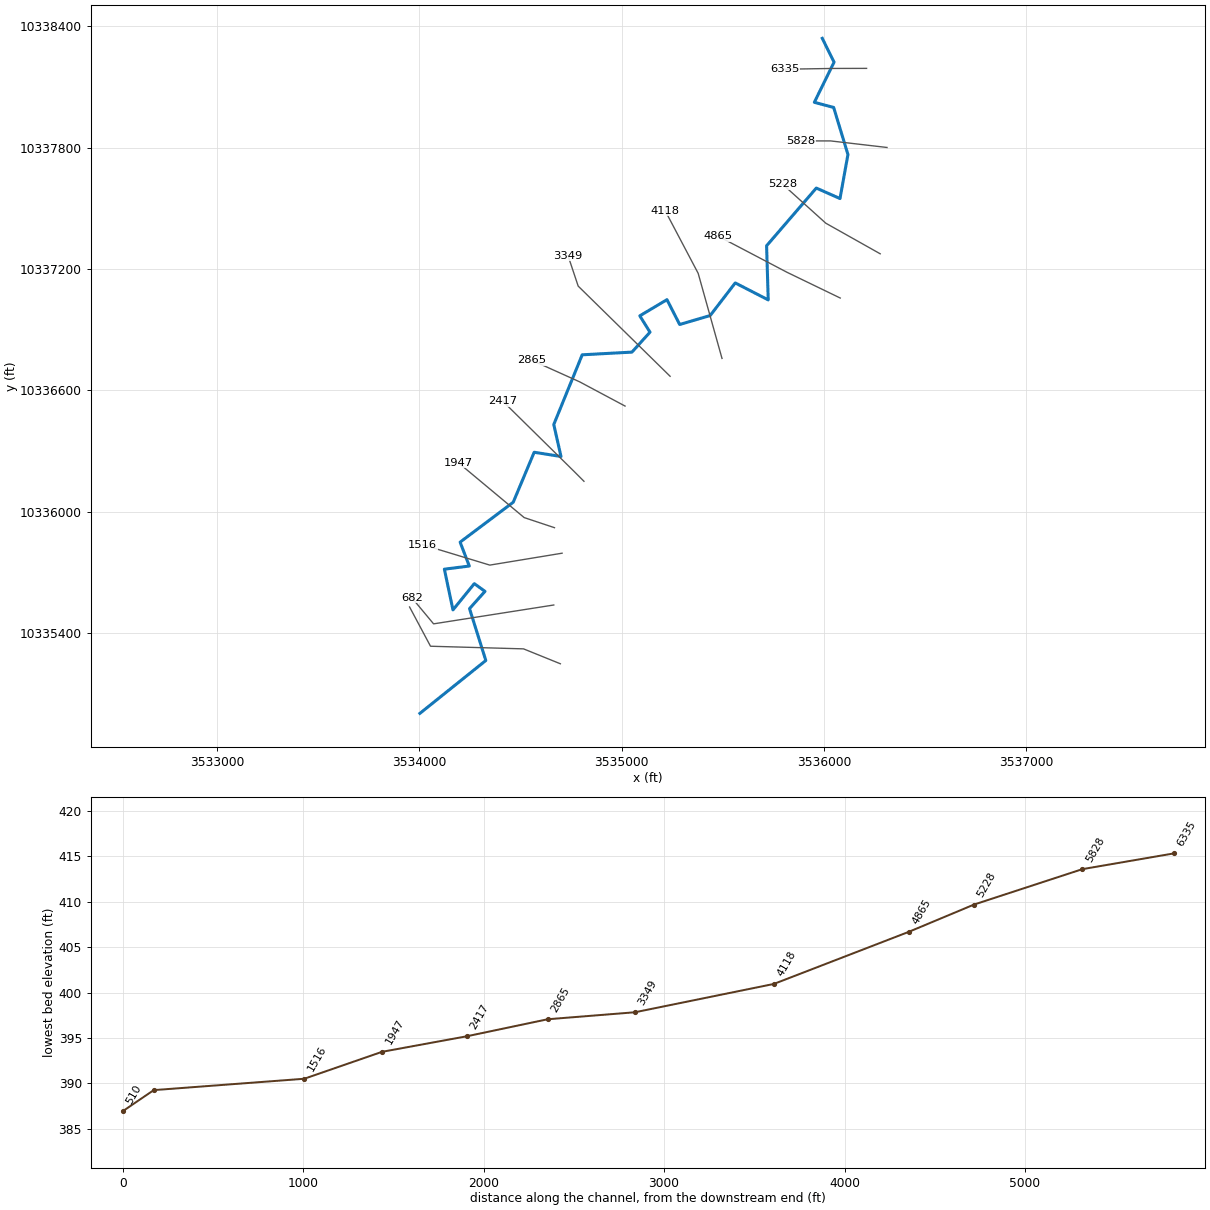
--- MYRTLE CREEK.prj (project) ---

Proj Title=MYRTLE CREEK Base Level Engineering
Current Plan=p01
Default Exp/Contr=0.3,0.1
English Units
Geom File=g01
Flow File=f01
Plan File=p01
BEGIN DESCRIPTION:
MYRTLE CREEK
END DESCRIPTION:

--- MYRTLE CREEK.p01 (plan) ---

Plan Title=Multiple Run
Short Identifier=Multiple
Geom File=g01
Flow File=f01
Subcritical Flow
K Sum by GR= 0
Std Step Tol= 0.01
Critical Tol= 0.01
Num of Std Step Trials= 20
Max Error Tol= 0.3
Flow Tol Ratio= 0.001
Split Flow NTrial= 30
Split Flow Tol= 0.02
Split Flow Ratio= 0.02
Log Output Level= 0
Friction Slope Method= 1
Unsteady Friction Slope Method= 2
Unsteady Bridges Friction Slope Method= 1
Parabolic Critical Depth
Global Vel Dist=  1 , 1 , 1
Global Log Level= 0
CheckData=True
Encroach Param= -1, 0, 0, 0
BEGIN DESCRIPTION:
Multiple Run
END DESCRIPTION:

--- MYRTLE CREEK.f01 (steady flow) ---

Flow Title=Multiple
Number of Profiles=7
Profile Names=10-year,25-year,50-year,1pct_min,100-year,1pct_plu,500-year
River Rch & RM= MYRTLE CREEK,Reach-1,6335
     473     635     767     679     919    1243    1321
Boundary for River Rch & Prof#=MYRTLE CREEK,Reach-1,1
Up Type=0
Dn Type=3
Dn Slope=0.005
Boundary for River Rch & Prof#=MYRTLE CREEK,Reach-1,2
Up Type=0
Dn Type=3
Dn Slope=0.005
Boundary for River Rch & Prof#=MYRTLE CREEK,Reach-1,3
Up Type=0
Dn Type=3
Dn Slope=0.005
Boundary for River Rch & Prof#=MYRTLE CREEK,Reach-1,4
Up Type=0
Dn Type=3
Dn Slope=0.005
Boundary for River Rch & Prof#=MYRTLE CREEK,Reach-1,5
Up Type=0
Dn Type=3
Dn Slope=0.005
Boundary for River Rch & Prof#=MYRTLE CREEK,Reach-1,6
Up Type=0
Dn Type=3
Dn Slope=0.005
Boundary for River Rch & Prof#=MYRTLE CREEK,Reach-1,7
Up Type=0
Dn Type=3
Dn Slope=0.005

--- MYRTLE CREEK.g01 (geometry) ---

Geom Title=Existing Conditions

River Reach=MYRTLE CREEK,Reach-1
Reach XY= 30
      3535992.33     10338340.60      3536050.71     10338222.72
      3535953.11     10338024.10      3536048.69     10337998.72
      3536119.31     10337765.96      3536080.04     10337548.11
      3535962.88     10337599.98      3535716.96     10337314.52
      3535725.09     10337046.84      3535561.91     10337130.79
      3535437.98     10336969.55      3535287.05     10336925.13
      3535224.15     10337048.01      3535089.87     10336967.98
      3535140.29     10336887.19      3535050.99     10336788.52
      3534804.93     10336775.27      3534664.30     10336430.44
      3534700.04     10336272.17      3534567.41     10336293.23
      3534463.74     10336045.98      3534201.06     10335848.56
      3534246.45     10335730.45      3534123.13     10335714.87
      3534165.66     10335513.48      3534271.22     10335643.34
      3534324.00     10335605.14      3534247.61     10335519.73
      3534328.17     10335263.24      3534002.11     10335001.64

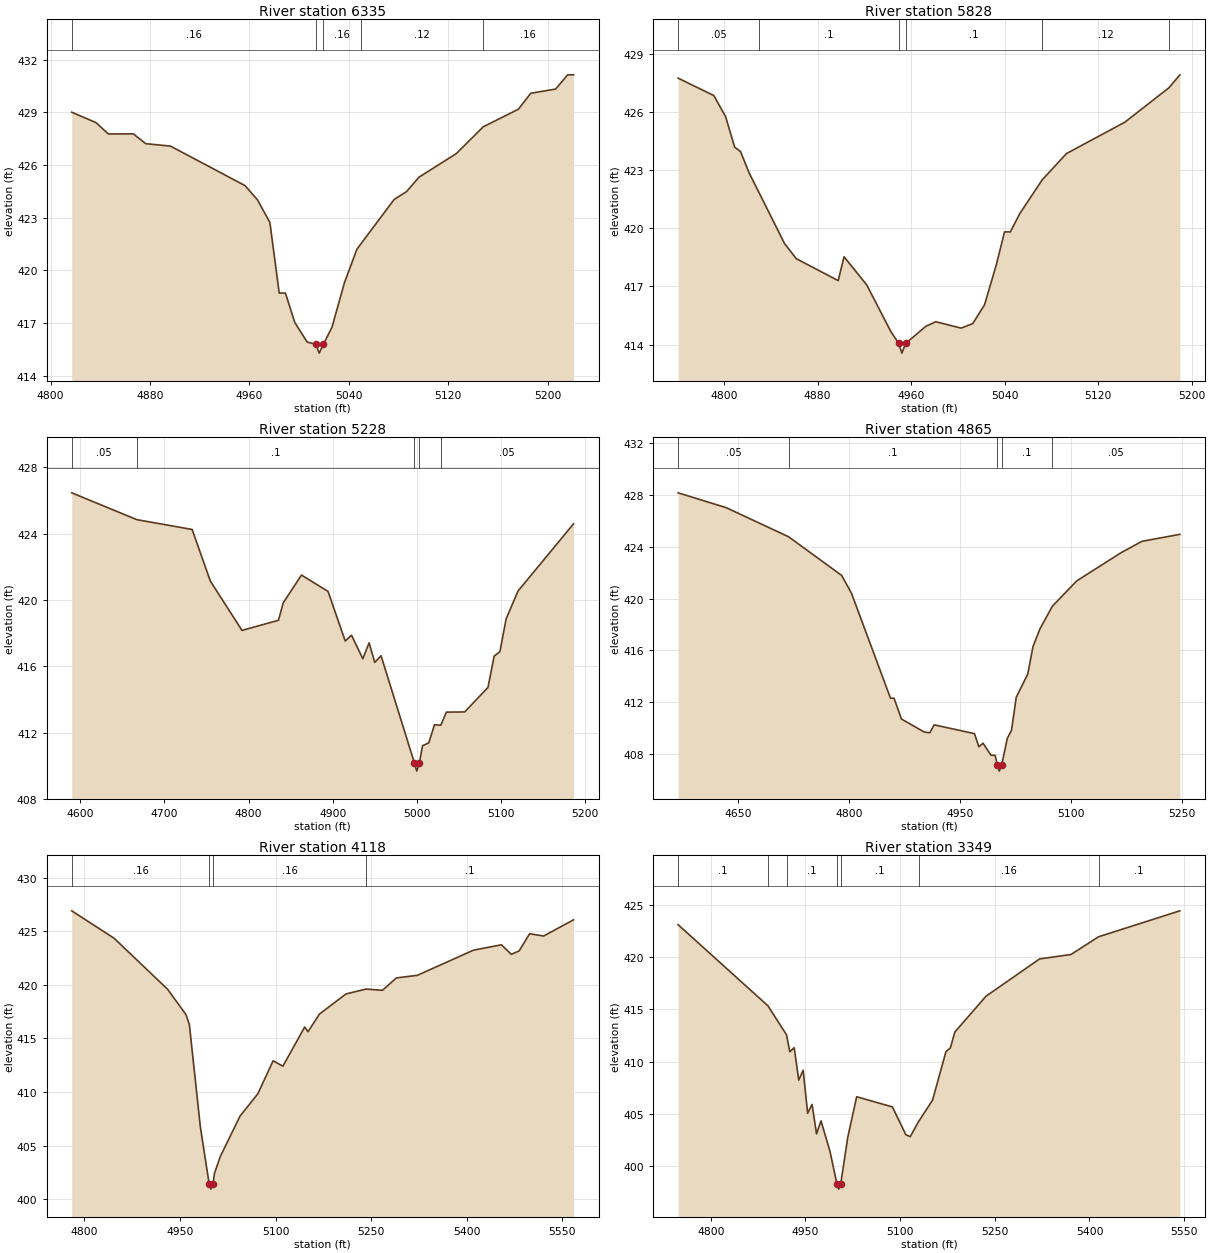
Type RM Length L Ch R = 1,6335,507,507,507
BEGIN DESCRIPTION:
MYRTLE CREEK 11.0
END DESCRIPTION:
XS GIS Cut Line= 3
      3536211.56     10338192.01      3536042.11     10338191.64
      3535807.69     10338187.80
#Sta/Elev= 30
  4817.0  429.01  4836.5  428.42  4846.5  427.77  4866.5  427.78  4876.5  427.22
  4896.5  427.08  4956.5  424.83  4966.5  424.02  4976.5  422.73  4984.0  418.71
  4989.0  418.71  4996.5  417.04  5006.5  415.92  5013.5  415.79  5016.2  415.29
  5019.5  415.79  5026.5  416.77  5036.5  419.30  5046.5  421.20  5049.5  421.49
  5076.5  424.04  5086.5  424.49  5096.5  425.31  5126.5  426.65  5148.2  428.18
  5176.5  429.18  5186.5  430.09  5206.5  430.33  5216.2  431.14  5220.9  431.14
#Mann=5,-1,0
  4817.0    0.16       0  5013.5    0.07       0  5019.5    0.16       0
  5049.5    0.12       0  5148.2    0.16       0
Bank Sta=5013.5,5019.5
Exp/Cntr=0.3,0.1

Type RM Length L Ch R = 1,5828,600,600,600
BEGIN DESCRIPTION:
MYRTLE CREEK 10.0
END DESCRIPTION:
XS GIS Cut Line= 3
      3536312.54     10337800.75      3536033.21     10337833.23
      3535885.12     10337833.23
#Sta/Elev= 30
  4760.6  427.74  4791.2  426.84  4801.3  425.75  4809.0  424.18  4814.0  423.96
  4821.4  422.85  4829.6  421.87  4851.6  419.22  4861.7  418.43  4897.6  417.30
  4902.6  418.53  4922.1  417.07  4942.3  414.71  4949.3  414.06  4952.1  413.56
  4955.3  414.06  4972.5  414.94  4981.1  415.18  5002.7  414.85  5012.7  415.08
  5022.8  416.05  5032.9  418.12  5039.9  419.81  5044.9  419.81  5052.9  420.75
  5072.2  422.50  5092.9  423.85  5142.9  425.47  5180.5  427.24  5189.9  427.91
#Mann=6,-1,0
  4760.6    0.05       0  4829.6     0.1       0  4949.3    0.07       0
  4955.3     0.1       0  5072.2    0.12       0  5180.5    0.16       0
Bank Sta=4949.3,4955.3
Exp/Cntr=0.3,0.1

Type RM Length L Ch R = 1,5228,363,363,363
BEGIN DESCRIPTION:
MYRTLE CREEK 9.0
END DESCRIPTION:
XS GIS Cut Line= 3
      3536278.93     10337274.84      3536009.66     10337426.31
      3535796.13     10337618.90
#Sta/Elev= 30
  4589.8  426.46  4667.2  424.84  4732.9  424.25  4754.6  421.13  4792.2  418.16
  4835.5  418.77  4841.3  419.83  4862.9  421.50  4894.5  420.51  4914.9  417.52
  4922.4  417.87  4935.8  416.45  4943.3  417.41  4950.0  416.23  4957.5  416.63
  4997.1  410.17  4999.9  409.67  5003.1  410.17  5006.8  411.20  5014.3  411.38
  5021.0  412.47  5028.5  412.44  5035.2  413.23  5056.9  413.24  5084.6  414.72
  5092.0  416.61  5098.8  416.88  5106.2  418.86  5120.4  420.54  5186.3  424.59
#Mann=5,-1,0
  4589.8    0.05       0  4667.2     0.1       0  4997.1    0.07       0
  5003.1     0.1       0  5028.5    0.05       0
Bank Sta=4997.1,5003.1
Exp/Cntr=0.3,0.1

Type RM Length L Ch R = 1,4865,747,747,747
BEGIN DESCRIPTION:
MYRTLE CREEK 8.0
END DESCRIPTION:
XS GIS Cut Line= 3
      3536081.22     10337056.06      3535818.32     10337183.23
      3535476.20     10337362.75
#Sta/Elev= 30
  4568.5  428.18  4633.7  427.03  4718.0  424.78  4789.7  421.79  4802.9  420.42
  4855.7  412.30  4860.5  412.30  4870.5  410.69  4901.4  409.68  4909.0  409.63
  4914.7  410.24  4969.2  409.56  4975.2  408.54  4980.8  408.82  4991.6  407.89
  4997.2  407.88  5000.1  407.16  5002.8  406.66  5006.1  407.16  5013.6  409.19
  5019.3  409.82  5025.7  412.37  5041.3  414.17  5048.3  416.28  5057.7  417.65
  5074.5  419.41  5107.5  421.37  5168.0  423.57  5195.7  424.43  5246.9  424.97
#Mann=5,-1,0
  4568.5    0.05       0  4718.0     0.1       0  5000.1    0.07       0
  5006.1     0.1       0  5074.5    0.05       0
Bank Sta=5000.1,5006.1
Exp/Cntr=0.3,0.1

Type RM Length L Ch R = 1,4118,769,769,769
BEGIN DESCRIPTION:
MYRTLE CREEK 7.0
END DESCRIPTION:
XS GIS Cut Line= 3
      3535496.39     10336757.36      3535378.59     10337178.08
      3535215.22     10337488.06
#Sta/Elev= 30
  4780.2  426.91  4846.7  424.35  4930.6  419.59  4959.5  417.22  4964.7  416.31
  4982.0  406.74  4995.8  401.44  4998.6  400.94  5001.8  401.44  5004.0  402.38
  5013.1  403.96  5044.3  407.76  5072.2  409.84  5096.2  412.92  5111.5  412.41
  5145.7  416.07  5150.9  415.63  5168.9  417.28  5210.4  419.15  5241.8  419.61
  5267.6  419.49  5289.6  420.65  5322.4  420.89  5410.5  423.24  5454.5  423.74
  5469.8  422.85  5482.2  423.17  5498.6  424.77  5520.6  424.56  5567.5  426.07
#Mann=4,-1,0
  4780.2    0.16       0  4995.8    0.07       0  5001.8    0.16       0
  5241.8     0.1       0
Bank Sta=4995.8,5001.8
Exp/Cntr=0.3,0.1

Type RM Length L Ch R = 1,3349,484,484,484
BEGIN DESCRIPTION:
MYRTLE CREEK 6.0
END DESCRIPTION:
XS GIS Cut Line= 3
      3535239.74     10336669.02      3534784.98     10337115.11
      3534734.99     10337265.07
#Sta/Elev= 30
  4748.1  423.08  4890.5  415.33  4919.9  412.57  4925.1  410.95  4932.1  411.33
  4939.3  408.24  4946.3  409.18  4953.4  405.07  4960.4  405.92  4967.5  403.11
  4974.6  404.35  4988.7  401.46  4999.8  398.33  5002.6  397.83  5005.8  398.33
  5017.0  402.78  5031.1  406.65  5087.7  405.68  5109.0  403.03  5116.0  402.84
  5129.2  404.28  5151.3  406.32  5172.6  410.96  5179.6  411.31  5186.7  412.83
  5236.1  416.25  5321.0  419.81  5370.6  420.23  5414.3  421.92  5543.2  424.40
#Mann=7,-1,0
  4748.1     0.1       0  4890.5    0.16       0  4919.9     0.1       0
  4999.8    0.07       0  5005.8     0.1       0  5129.2    0.16       0
  5414.3     0.1       0
Bank Sta=4999.8,5005.8
Exp/Cntr=0.3,0.1

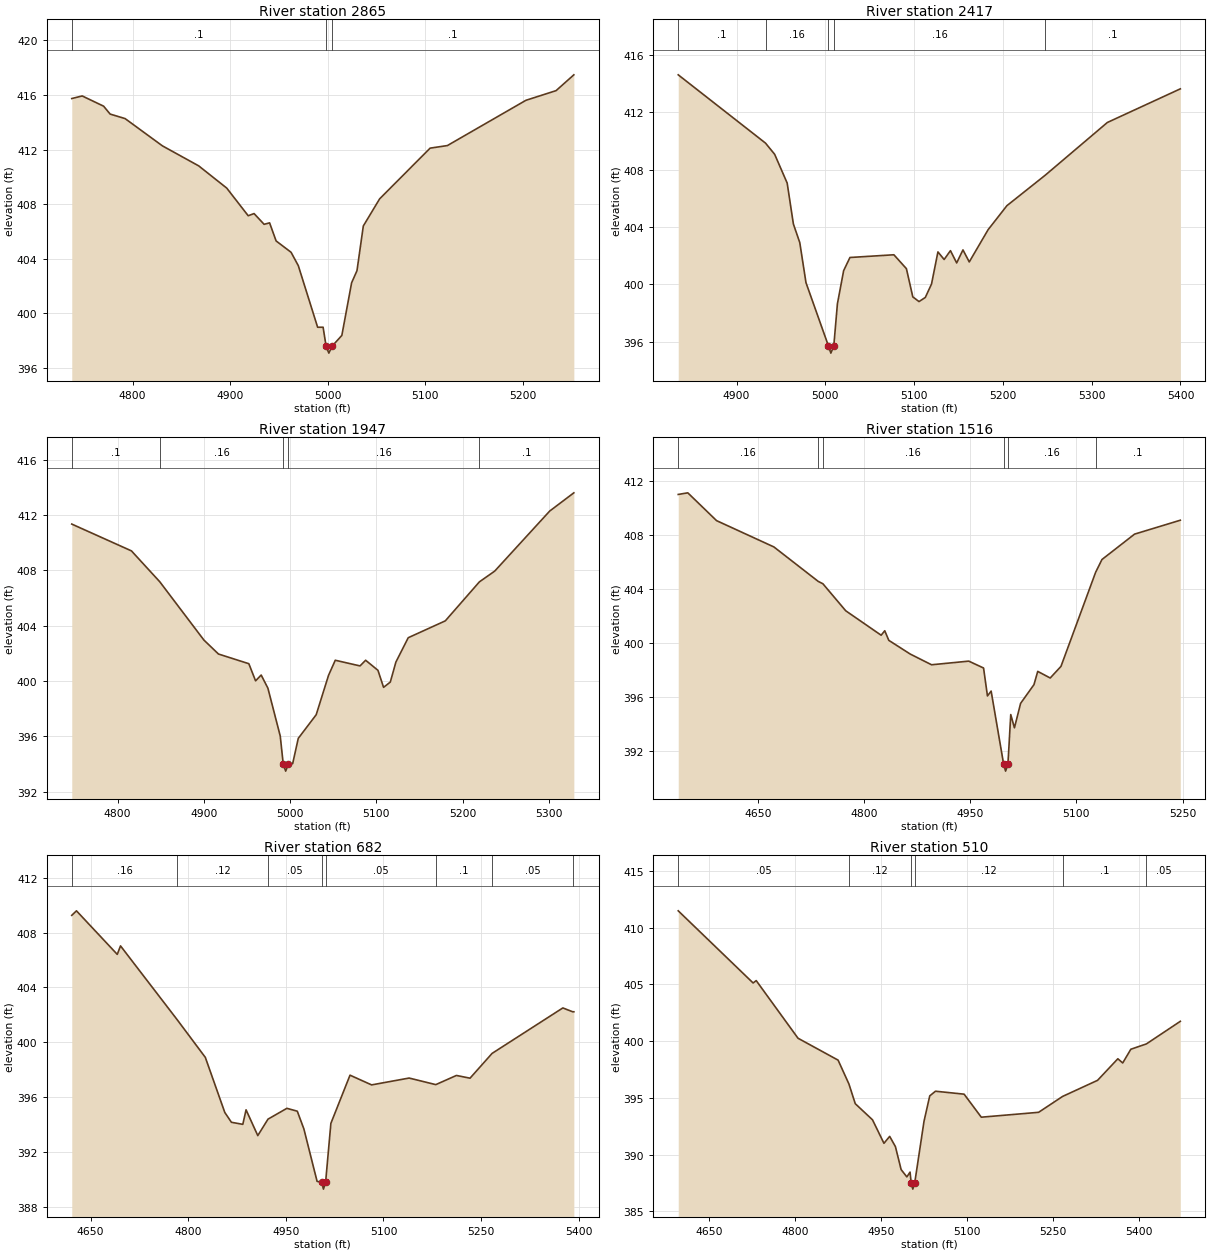
Type RM Length L Ch R = 1,2865,448,448,448
BEGIN DESCRIPTION:
MYRTLE CREEK 5.0
END DESCRIPTION:
XS GIS Cut Line= 3
      3535016.80     10336521.75      3534792.11     10336641.64
      3534555.50     10336748.27
#Sta/Elev= 30
  4737.8  415.74  4748.5  415.93  4770.4  415.18  4777.1  414.60  4792.4  414.27
  4830.6  412.27  4867.8  410.80  4896.5  409.17  4918.5  407.14  4924.5  407.30
  4934.8  406.51  4940.4  406.62  4947.1  405.29  4962.4  404.46  4969.8  403.48
  4989.6  398.96  4995.2  398.96  4998.3  397.56  5001.1  397.06  5004.3  397.56
  5014.4  398.36  5024.4  402.22  5029.9  403.11  5036.4  406.39  5053.1  408.38
  5104.8  412.10  5122.5  412.29  5202.9  415.61  5233.8  416.32  5252.0  417.48
#Mann=3,-1,0
  4737.8     0.1       0  4998.3    0.07       0  5004.3     0.1       0
Bank Sta=4998.3,5004.3
Exp/Cntr=0.3,0.1

Type RM Length L Ch R = 1,2417,470,470,470
BEGIN DESCRIPTION:
MYRTLE CREEK 4.0
END DESCRIPTION:
XS GIS Cut Line= 3
      3534813.61     10336149.59      3534763.63     10336199.57
      3534411.13     10336546.82
#Sta/Elev= 30
  4834.3  414.63  4932.6  409.86  4942.9  409.08  4957.0  407.07  4964.0  404.21
  4971.2  402.91  4978.2  400.11  5003.5  395.69  5006.2  395.19  5009.5  395.69
  5013.6  398.64  5020.6  400.95  5027.7  401.87  5077.2  402.06  5091.3  401.09
  5098.5  399.12  5105.5  398.79  5112.6  399.08  5119.6  400.02  5126.8  402.26
  5133.8  401.73  5140.9  402.35  5147.9  401.49  5155.0  402.40  5162.1  401.56
  5183.3  403.81  5204.5  405.49  5247.7  407.62  5317.6  411.30  5399.8  413.65
#Mann=5,-1,0
  4834.3     0.1       0  4932.6    0.16       0  5003.5    0.07       0
  5009.5    0.16       0  5247.7     0.1       0
Bank Sta=5003.5,5009.5
Exp/Cntr=0.3,0.1

Type RM Length L Ch R = 1,1947,431,431,431
BEGIN DESCRIPTION:
MYRTLE CREEK 3.0
END DESCRIPTION:
XS GIS Cut Line= 3
      3534667.79     10335920.14      3534517.83     10335970.12
      3534192.12     10336241.63
#Sta/Elev= 30
  4746.9  411.35  4816.1  409.41  4848.9  407.18  4900.1  402.96  4917.0  401.95
  4952.2  401.25  4960.0  400.01  4966.5  400.43  4974.3  399.48  4988.6  396.02
  4992.1  393.98  4994.9  393.48  4998.1  393.98  5003.0  394.02  5009.5  395.85
  5030.3  397.56  5044.6  400.41  5052.4  401.50  5081.1  401.09  5087.6  401.50
  5101.9  400.77  5108.4  399.54  5116.2  399.92  5122.7  401.37  5137.0  403.13
  5180.0  404.35  5219.5  407.17  5237.3  407.95  5301.0  412.29  5329.0  413.61
#Mann=5,-1,0
  4746.9     0.1       0  4848.9    0.16       0  4992.1    0.07       0
  4998.1    0.16       0  5219.5     0.1       0
Bank Sta=4992.1,4998.1
Exp/Cntr=0.3,0.1

Type RM Length L Ch R = 1,1516,834,834,834
BEGIN DESCRIPTION:
MYRTLE CREEK 2.1
END DESCRIPTION:
XS GIS Cut Line= 3
      3534705.45     10335793.93      3534347.83     10335735.03
      3534016.33     10335835.74
#Sta/Elev= 30
  4537.8  411.02  4551.3  411.14  4591.9  409.08  4672.9  407.13  4735.4  404.58
  4742.1  404.40  4774.3  402.40  4824.3  400.59  4829.4  400.92  4835.1  400.21
  4865.5  399.19  4895.5  398.40  4948.0  398.67  4968.9  398.16  4974.4  396.09
  4979.6  396.45  4997.3  391.02  5000.0  390.52  5003.3  391.02  5007.3  394.71
  5012.5  393.73  5021.2  395.54  5040.1  396.93  5045.4  397.91  5063.0  397.42
  5078.2  398.28  5127.2  405.26  5136.1  406.20  5182.1  408.08  5246.7  409.11
#Mann=6,-1,0
  4537.8    0.16       0  4735.4     0.1       0  4742.1    0.16       0
  4997.3    0.07       0  5003.3    0.16       0  5127.2     0.1       0
Bank Sta=4997.3,5003.3
Exp/Cntr=0.3,0.1

Type RM Length L Ch R = 1,682,172,172,172
BEGIN DESCRIPTION:
MYRTLE CREEK 2.0
END DESCRIPTION:
XS GIS Cut Line= 3
      3534664.40     10335537.74      3534069.80     10335444.43
      3533961.28     10335574.66
#Sta/Elev= 30
  4621.1  409.26  4628.3  409.59  4691.0  406.41  4696.0  407.03  4782.9  401.65
  4826.3  398.89  4856.2  394.87  4866.4  394.15  4883.9  394.00  4888.9  395.06
  4906.9  393.18  4922.6  394.38  4951.6  395.17  4967.6  394.96  4977.7  393.67
  4998.0  389.84  5005.1  389.77  5007.8  389.27  5011.1  389.77  5019.2  394.07
  5048.6  397.59  5081.8  396.88  5139.4  397.38  5180.4  396.90  5212.1  397.57
  5233.0  397.37  5266.9  399.18  5375.6  402.50  5390.6  402.22  5392.5  402.22
#Mann=8,-1,0
  4621.1    0.16       0  4782.9    0.12       0  4922.6    0.05       0
  5005.1    0.04       0  5011.1    0.05       0  5180.4     0.1       0
  5266.9    0.05       0  5390.6     0.1       0
Bank Sta=5005.1,5011.1
Exp/Cntr=0.3,0.1

Type RM Length L Ch R = 1,510,0,0,0
BEGIN DESCRIPTION:
MYRTLE CREEK 1.0
END DESCRIPTION:
XS GIS Cut Line= 4
      3534696.94     10335246.96      3534514.68     10335320.73
      3534054.61     10335333.75      3533951.07     10335527.90
#Sta/Elev= 30
  4595.7  411.48  4726.5  405.12  4731.9  405.33  4804.9  400.25  4874.9  398.32
  4893.8  396.22  4904.9  394.48  4935.0  393.06  4955.0  390.99  4965.0  391.60
  4975.0  390.70  4985.0  388.67  4995.0  388.03  5000.6  388.45  5002.6  387.45
  5005.4  386.95  5008.6  387.45  5025.0  392.94  5035.0  395.17  5045.0  395.58
  5095.0  395.32  5125.0  393.29  5225.1  393.72  5267.0  395.12  5328.1  396.54
  5363.5  398.44  5372.0  398.07  5386.2  399.28  5413.4  399.75  5472.6  401.74
#Mann=6,-1,0
  4595.7    0.05       0  4893.8    0.12       0  5002.6    0.07       0
  5008.6    0.12       0  5267.0     0.1       0  5413.4    0.05       0
Bank Sta=5002.6,5008.6
Exp/Cntr=0.3,0.1

Chan Stop Cuts=-1