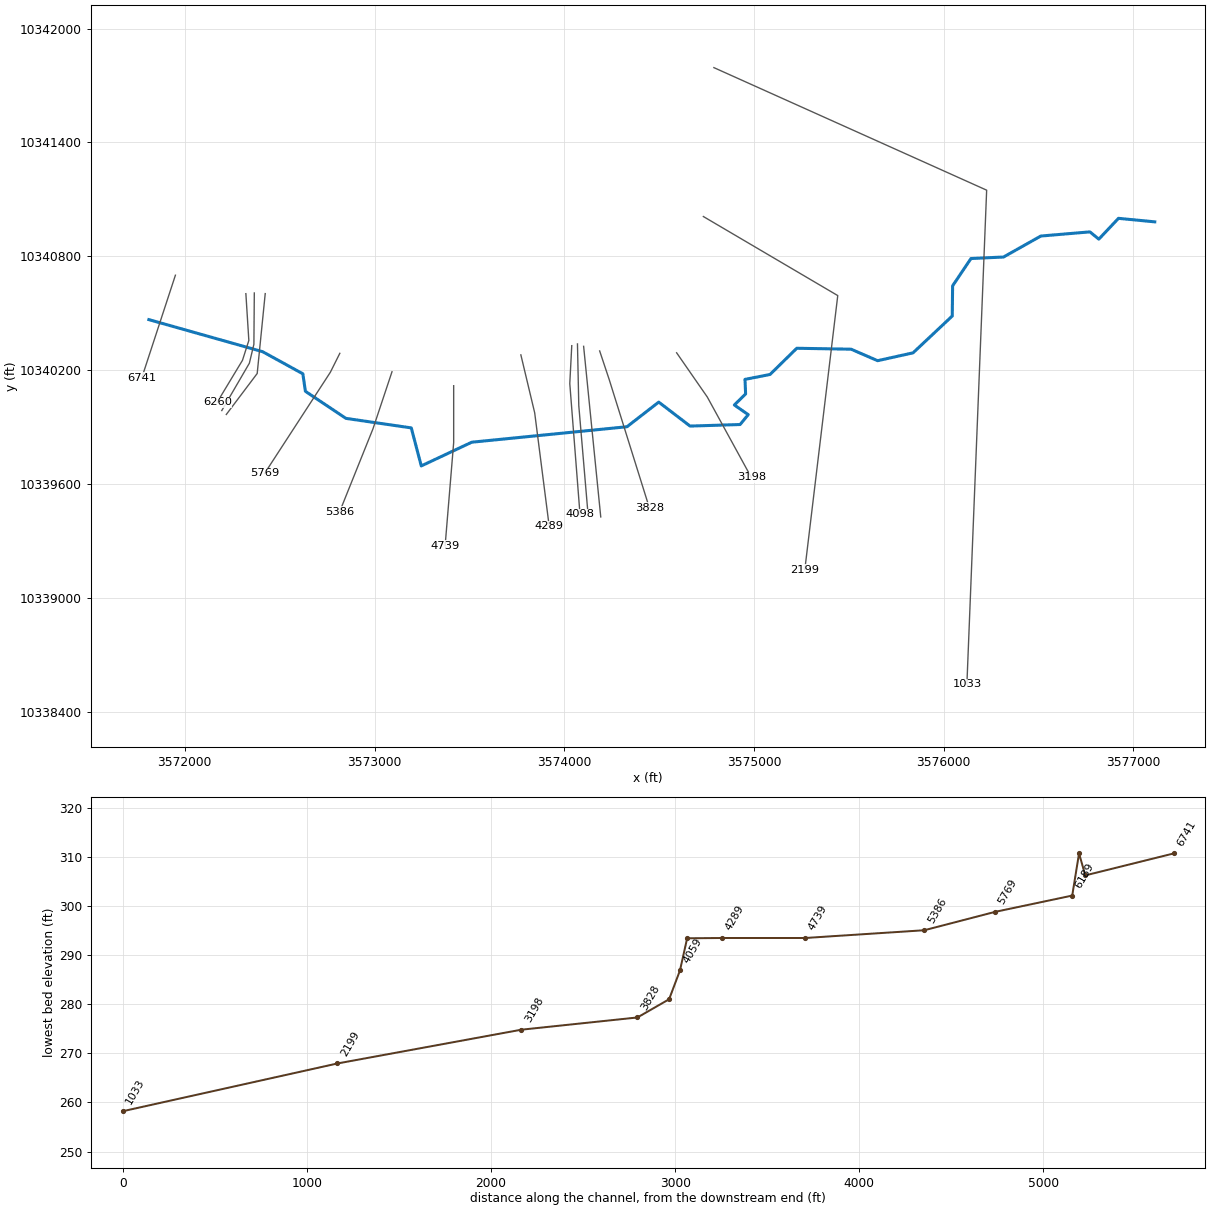
--- NAVASOTA RIVER TRIBUTARY 1 1.prj (project) ---

Proj Title=NAVASOTA RIVER TRIBUTARY 1 1 Base Level Engineering
Current Plan=p01
Default Exp/Contr=0.3,0.1
English Units
Geom File=g01
Flow File=f01
Plan File=p01
BEGIN DESCRIPTION:
NAVASOTA RIVER TRIBUTARY 1 1
END DESCRIPTION:

--- NAVASOTA RIVER TRIBUTARY 1 1.p01 (plan) ---

Plan Title=Multiple Run
Short Identifier=Multiple
Geom File=g01
Flow File=f01
Subcritical Flow
K Sum by GR= 0
Std Step Tol= 0.01
Critical Tol= 0.01
Num of Std Step Trials= 20
Max Error Tol= 0.3
Flow Tol Ratio= 0.001
Split Flow NTrial= 30
Split Flow Tol= 0.02
Split Flow Ratio= 0.02
Log Output Level= 0
Friction Slope Method= 1
Unsteady Friction Slope Method= 2
Unsteady Bridges Friction Slope Method= 1
Parabolic Critical Depth
Global Vel Dist=  1 , 1 , 1
Global Log Level= 0
CheckData=True
Encroach Param= -1, 0, 0, 0
BEGIN DESCRIPTION:
Multiple Run
END DESCRIPTION:

--- NAVASOTA RIVER TRIBUTARY 1 1.f01 (steady flow) ---

Flow Title=Multiple
Number of Profiles=7
Profile Names=10-year,25-year,50-year,1pct_min,100-year,1pct_plu,500-year
River Rch & RM= NAVASOTA RIVER T,Reach-1,6741
     410     545     654     576     779    1054    1109
Boundary for River Rch & Prof#=NAVASOTA RIVER T,Reach-1,1
Up Type=0
Dn Type=3
Dn Slope=0.005
Boundary for River Rch & Prof#=NAVASOTA RIVER T,Reach-1,2
Up Type=0
Dn Type=3
Dn Slope=0.005
Boundary for River Rch & Prof#=NAVASOTA RIVER T,Reach-1,3
Up Type=0
Dn Type=3
Dn Slope=0.005
Boundary for River Rch & Prof#=NAVASOTA RIVER T,Reach-1,4
Up Type=0
Dn Type=3
Dn Slope=0.005
Boundary for River Rch & Prof#=NAVASOTA RIVER T,Reach-1,5
Up Type=0
Dn Type=3
Dn Slope=0.005
Boundary for River Rch & Prof#=NAVASOTA RIVER T,Reach-1,6
Up Type=0
Dn Type=3
Dn Slope=0.005
Boundary for River Rch & Prof#=NAVASOTA RIVER T,Reach-1,7
Up Type=0
Dn Type=3
Dn Slope=0.005

--- NAVASOTA RIVER TRIBUTARY 1 1.g01 (geometry) ---

Geom Title=Existing Conditions

River Reach=NAVASOTA RIVER T,Reach-1
Reach XY= 30
      3571810.51     10340466.39      3572410.23     10340297.34
      3572622.19     10340180.89      3572635.68     10340088.64
      3572849.26     10339945.92      3573193.73     10339895.69
      3573246.37     10339695.29      3573512.54     10339820.31
      3574330.47     10339901.79      3574497.83     10340031.65
      3574663.11     10339905.26      3574926.65     10339913.48
      3574969.53     10339965.57      3574896.38     10340016.38
      3574955.75     10340074.69      3574952.55     10340151.43
      3575084.50     10340177.27      3575225.35     10340315.38
      3575511.58     10340310.49      3575651.44     10340249.89
      3575838.13     10340291.23      3576044.73     10340485.23
      3576046.73     10340644.59      3576143.41     10340788.28
      3576315.04     10340796.31      3576511.58     10340906.85
      3576770.29     10340928.82      3576817.21     10340890.33
      3576920.91     10341000.17      3577112.11     10340981.64

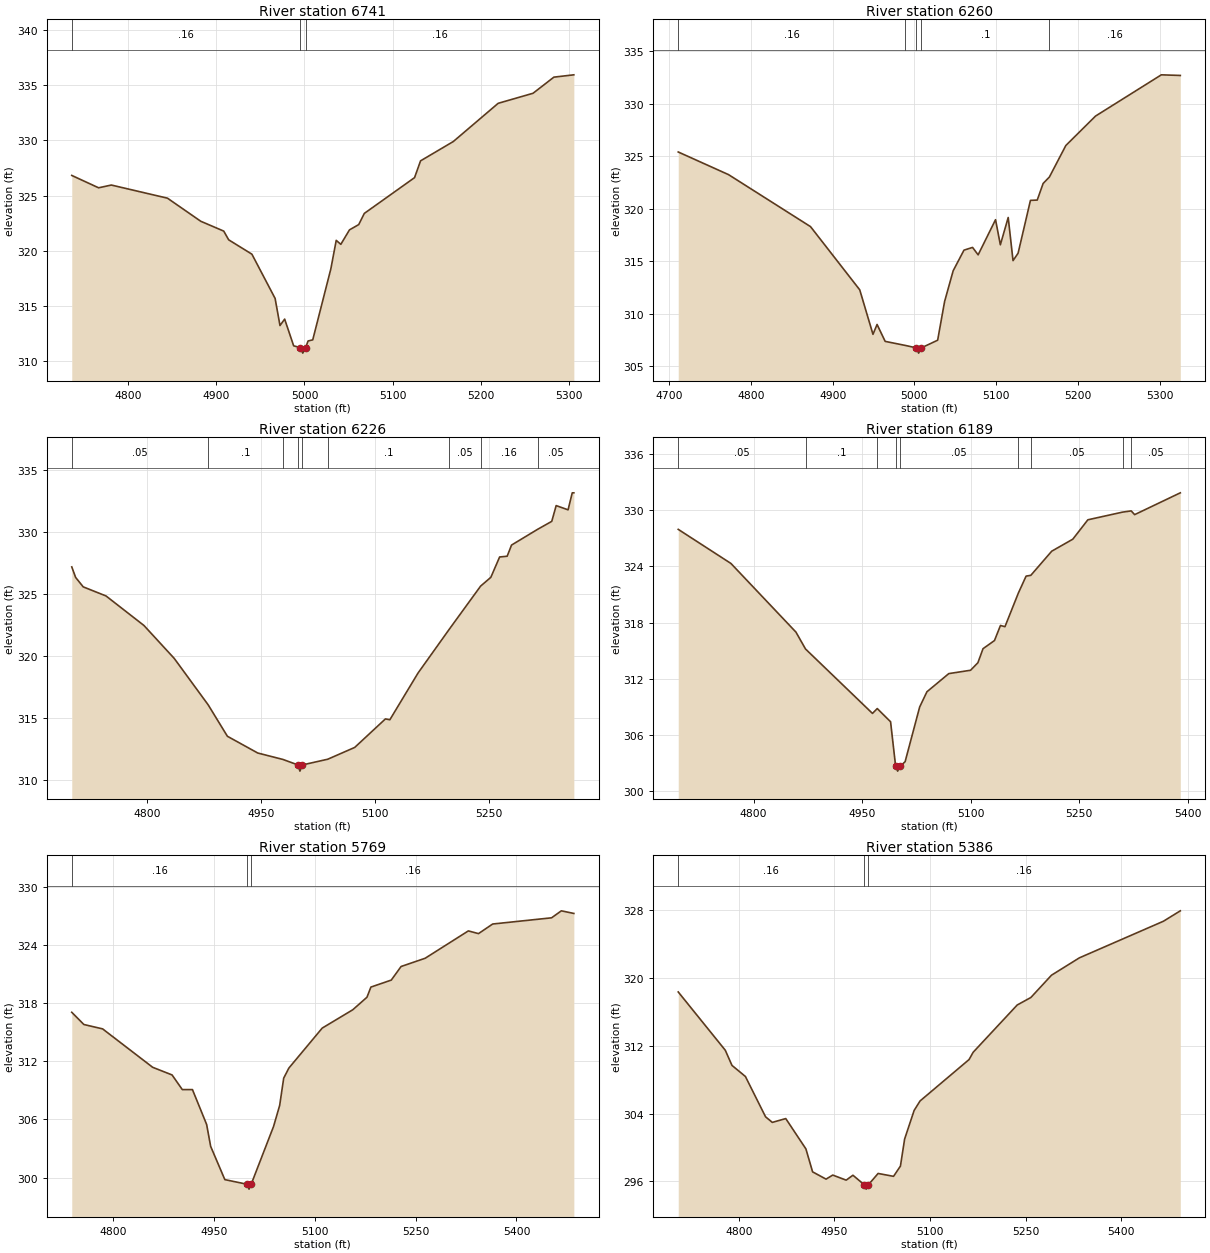
Type RM Length L Ch R = 1,6741,481,481,481
BEGIN DESCRIPTION:
NAVASOTA RIVER TRIBUTARY 1.1 12.0
END DESCRIPTION:
XS GIS Cut Line= 2
      3571950.61     10340700.49      3571773.54     10340160.17
#Sta/Elev= 30
  4736.5  326.83  4766.9  325.71  4781.3  325.96  4844.9  324.77  4882.6  322.68
  4908.6  321.79  4914.2  321.00  4940.5  319.70  4966.8  315.69  4972.3  313.24
  4977.6  313.82  4987.8  311.40  4995.4  311.24  4998.1  310.74  5001.4  311.24
  5004.1  311.84  5009.4  311.94  5029.9  318.37  5036.0  320.95  5041.2  320.59
  5051.0  321.90  5061.5  322.38  5067.8  323.39  5124.7  326.63  5131.5  328.15
  5168.6  329.90  5219.4  333.36  5258.9  334.27  5282.5  335.73  5305.1  335.94
#Mann=3,-1,0
  4736.5    0.16       0  4995.4    0.07       0  5001.4    0.16       0
Bank Sta=4995.4,5001.4
Exp/Cntr=0.3,0.1

Type RM Length L Ch R = 1,6260,34,34,34
BEGIN DESCRIPTION:
NAVASOTA RIVER TRIBUTARY 1.1 12.01
END DESCRIPTION:
XS GIS Cut Line= 4
      3572321.96     10340603.15      3572337.59     10340356.58
      3572304.06     10340251.98      3572171.18     10340031.78
#Sta/Elev= 30
  4711.1  325.42  4772.7  323.26  4872.9  318.31  4933.1  312.29  4949.3  308.05
  4954.3  308.99  4964.2  307.38  4989.0  306.99  5002.4  306.76  5005.1  306.26
  5008.4  306.76  5028.4  307.49  5036.9  311.18  5047.4  314.11  5060.6  316.07
  5071.1  316.33  5077.9  315.62  5099.2  318.97  5105.1  316.58  5114.7  319.18
  5120.6  315.07  5126.8  315.78  5141.9  320.81  5150.2  320.84  5157.4  322.42
  5165.1  323.04  5185.2  326.04  5221.5  328.84  5302.0  332.77  5325.2  332.71
#Mann=5,-1,0
  4711.1    0.16       0  4989.0     0.1       0  5002.4    0.07       0
  5008.4     0.1       0  5165.1    0.16       0
Bank Sta=5002.4,5008.4
Exp/Cntr=0.3,0.1

Type RM Length L Ch R = 1,6226,37,37,37
BEGIN DESCRIPTION:
Mapping XS f5c77e46
END DESCRIPTION:
XS GIS Cut Line= 4
      3572366.43     10340606.71      3572364.26     10340336.48
      3572340.39     10340236.66      3572195.00     10339987.10
#Sta/Elev= 30
  4700.4  327.20  4705.5  326.35  4715.5  325.59  4745.5  324.86  4795.5  322.48
  4835.5  319.82  4880.2  316.08  4905.5  313.55  4945.5  312.20  4978.8  311.68
  4998.4  311.24  5001.1  310.74  5004.4  311.24  5037.8  311.70  5073.3  312.65
  5113.8  314.95  5119.6  314.88  5156.8  318.65  5198.1  322.19  5239.2  325.65
  5252.7  326.36  5264.3  328.00  5274.2  328.06  5280.0  328.96  5314.4  330.23
  5333.0  330.87  5338.8  332.14  5354.5  331.80  5360.0  333.17  5362.1  333.17
#Mann=9,-1,0
  4700.4    0.05       0  4880.2     0.1       0  4978.8    0.05       0
  4998.4    0.04       0  5004.4    0.05       0  5037.8     0.1       0
  5198.1    0.05       0  5239.2    0.16       0  5314.4    0.05       0
Bank Sta=4998.4,5004.4
Exp/Cntr=0.3,0.1

Type RM Length L Ch R = 1,6189,420,420,420
BEGIN DESCRIPTION:
Mapping XS 052de449
END DESCRIPTION:
XS GIS Cut Line= 3
      3572423.95     10340603.44      3572381.62     10340182.40
      3572218.90     10339966.52
#Sta/Elev= 30
  4696.0  327.96  4768.8  324.32  4858.6  316.99  4871.8  315.19  4964.3  308.31
  4970.9  308.83  4989.3  307.42  4996.3  302.65  4999.1  302.15  5002.3  302.65
  5009.4  303.16  5029.5  309.00  5039.5  310.62  5069.7  312.56  5099.8  312.92
  5109.9  313.72  5117.0  315.22  5132.8  316.09  5141.1  317.70  5147.3  317.57
  5165.7  321.14  5176.5  322.97  5183.0  323.05  5211.9  325.63  5241.0  326.91
  5261.8  328.98  5309.7  329.80  5321.7  329.93  5326.4  329.53  5389.5  331.86
#Mann=9,-1,0
  4696.0    0.05       0  4871.8     0.1       0  4970.9    0.05       0
  4996.3    0.04       0  5002.3    0.05       0  5165.7     0.1       0
  5183.0    0.05       0  5309.7    0.16       0  5321.7    0.05       0
Bank Sta=4996.3,5002.3
Exp/Cntr=0.3,0.1

Type RM Length L Ch R = 1,5769,383,383,383
BEGIN DESCRIPTION:
NAVASOTA RIVER TRIBUTARY 1.1 11.0
END DESCRIPTION:
XS GIS Cut Line= 3
      3572817.09     10340288.84      3572767.11     10340188.86
      3572420.86     10339656.06
#Sta/Elev= 30
  4738.2  317.05  4756.2  315.79  4784.1  315.34  4858.6  311.38  4887.5  310.59
  4902.7  309.08  4917.8  309.08  4938.9  305.49  4944.9  303.23  4966.0  299.80
  4999.2  299.32  5002.0  298.82  5005.2  299.32  5038.5  305.28  5047.6  307.45
  5053.6  310.26  5061.3  311.30  5110.9  315.42  5156.4  317.31  5177.5  318.60
  5183.4  319.65  5213.7  320.37  5228.3  321.77  5264.1  322.62  5328.4  325.44
  5343.5  325.16  5364.6  326.15  5452.3  326.79  5466.8  327.51  5485.4  327.24
#Mann=3,-1,0
  4738.2    0.16       0  4999.2    0.07       0  5005.2    0.16       0
Bank Sta=4999.2,5005.2
Exp/Cntr=0.3,0.1

Type RM Length L Ch R = 1,5386,647,647,647
BEGIN DESCRIPTION:
NAVASOTA RIVER TRIBUTARY 1.1 10.0
END DESCRIPTION:
XS GIS Cut Line= 3
      3573092.11     10340191.65      3572992.11     10339891.64
      3572816.36     10339454.16
#Sta/Elev= 30
  4704.9  318.37  4778.7  311.49  4789.2  309.70  4810.3  308.39  4841.9  303.63
  4852.5  302.97  4873.6  303.42  4905.2  299.84  4915.7  297.13  4936.8  296.27
  4947.3  296.75  4968.4  296.15  4979.0  296.73  4997.0  295.59  4999.8  295.09
  5003.0  295.59  5018.5  296.94  5042.7  296.60  5053.5  297.81  5060.1  301.01
  5075.0  304.38  5084.3  305.50  5161.2  310.39  5167.6  311.25  5236.7  316.83
  5258.2  317.72  5290.5  320.35  5334.3  322.40  5466.1  326.72  5492.6  327.95
#Mann=3,-1,0
  4704.9    0.16       0  4997.0    0.07       0  5003.0    0.16       0
Bank Sta=4997,5003
Exp/Cntr=0.3,0.1

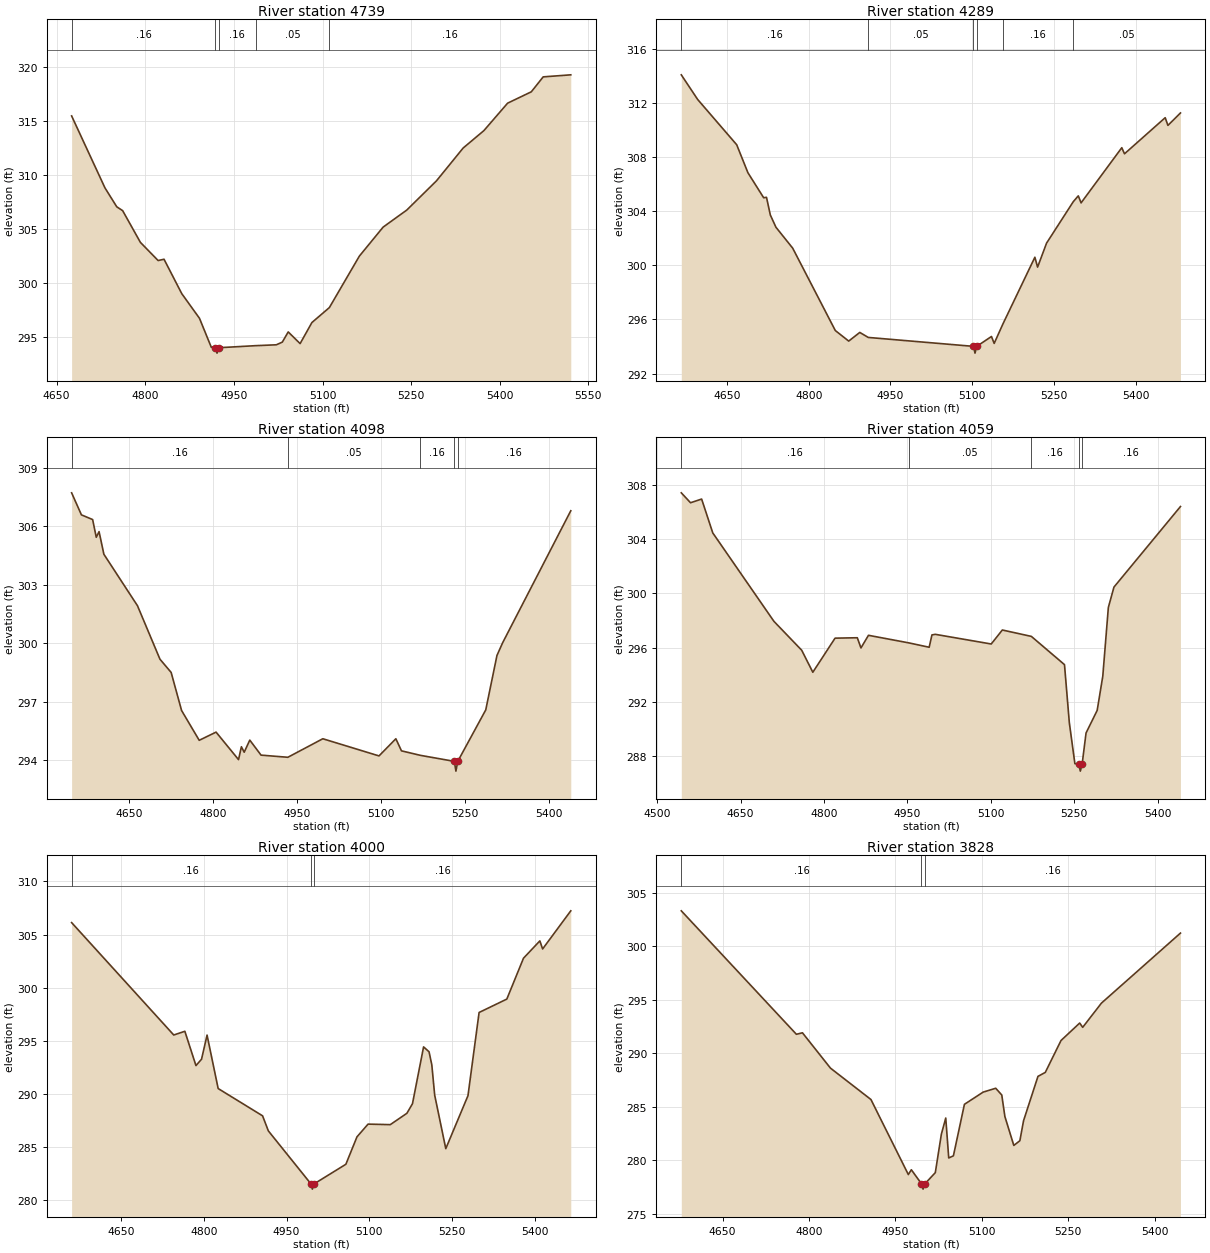
Type RM Length L Ch R = 1,4739,450,450,450
BEGIN DESCRIPTION:
NAVASOTA RIVER TRIBUTARY 1.1 9.0
END DESCRIPTION:
XS GIS Cut Line= 3
      3573417.11     10340118.02      3573417.11     10339818.03
      3573372.04     10339275.09
#Sta/Elev= 30
  4675.4  315.44  4731.8  308.79  4751.8  307.04  4761.8  306.68  4791.8  303.75
  4821.8  302.07  4831.8  302.19  4861.8  299.01  4891.8  296.73  4911.8  294.05
  4918.8  294.01  4921.5  293.51  4924.8  294.01  4987.0  294.20  5021.9  294.28
  5032.0  294.53  5042.0  295.47  5062.1  294.39  5082.1  296.34  5111.6  297.72
  5162.4  302.48  5202.6  305.16  5242.7  306.74  5292.9  309.44  5338.0  312.47
  5373.1  314.08  5413.3  316.62  5453.4  317.67  5473.5  319.05  5520.2  319.24
#Mann=5,-1,0
  4675.4    0.16       0  4918.8   0.033       0  4924.8    0.16       0
  4987.0    0.05       0  5111.6    0.16       0
Bank Sta=4918.8,4924.8
Exp/Cntr=0.3,0.1

Type RM Length L Ch R = 1,4289,191,191,191
BEGIN DESCRIPTION:
NAVASOTA RIVER TRIBUTARY 1.1 8.0
END DESCRIPTION:
XS GIS Cut Line= 3
      3573771.26     10340280.57      3573844.14     10339974.99
      3573920.52     10339377.80
#Sta/Elev= 30
  4566.1  314.09  4596.1  312.27  4667.8  308.92  4688.4  306.85  4717.3  305.00
  4722.5  305.03  4729.5  303.73  4739.8  302.82  4770.6  301.27  4848.8  295.18
  4873.4  294.40  4893.7  295.04  4909.3  294.67  5102.4  294.01  5105.2  293.51
  5108.4  294.01  5135.4  294.74  5140.4  294.23  5156.6  295.68  5215.1  300.60
  5220.1  299.87  5236.5  301.64  5285.6  304.71  5294.8  305.14  5299.9  304.62
  5374.6  308.70  5379.6  308.25  5454.3  310.92  5459.3  310.35  5482.3  311.27
#Mann=6,-1,0
  4566.1    0.16       0  4909.3    0.05       0  5102.4   0.033       0
  5108.4    0.05       0  5156.6    0.16       0  5285.6    0.05       0
Bank Sta=5102.4,5108.4
Exp/Cntr=0.3,0.1

Type RM Length L Ch R = 1,4098,39,39,39
BEGIN DESCRIPTION:
Mapping XS c0091c48
END DESCRIPTION:
XS GIS Cut Line= 3
      3574039.48     10340329.11      3574029.06     10340129.48
      3574082.88     10339440.28
#Sta/Elev= 30
  4547.4  307.72  4564.9  306.59  4584.9  306.35  4591.4  305.44  4596.4  305.73
  4605.0  304.57  4665.0  301.93  4705.1  299.19  4725.1  298.51  4743.7  296.56
  4775.2  295.03  4805.3  295.45  4845.4  294.04  4850.5  294.70  4855.5  294.42
  4865.5  295.04  4885.6  294.27  4933.5  294.16  4995.9  295.11  5096.2  294.23
  5126.3  295.11  5136.3  294.49  5170.0  294.26  5230.8  293.95  5233.5  293.45
  5236.8  293.95  5286.8  296.59  5306.8  299.38  5316.9  300.03  5438.6  306.80
#Mann=5,-1,0
  4547.4    0.16       0  4933.5    0.05       0  5170.0    0.16       0
  5230.8   0.033       0  5236.8    0.16       0
Bank Sta=5230.8,5236.8
Exp/Cntr=0.3,0.1

Type RM Length L Ch R = 1,4059,59,59,59
BEGIN DESCRIPTION:
Mapping XS c5d36827
END DESCRIPTION:
XS GIS Cut Line= 3
      3574069.56     10340338.19      3574076.50     10340013.57
      3574125.11     10339442.43
#Sta/Elev= 30
  4543.3  307.39  4559.9  306.66  4579.9  306.93  4599.9  304.44  4709.9  297.93
  4759.9  295.80  4779.9  294.18  4819.9  296.69  4859.9  296.72  4866.5  295.97
  4880.0  296.90  4952.9  296.34  4989.2  296.02  4994.2  296.93  5000.4  296.97
  5100.8  296.26  5120.8  297.29  5173.0  296.82  5232.6  294.74  5241.3  290.47
  5251.3  287.45  5258.3  287.40  5261.1  286.90  5264.3  287.40  5271.4  289.71
  5291.4  291.37  5301.5  293.89  5311.5  298.95  5321.6  300.45  5441.2  306.38
#Mann=5,-1,0
  4543.3    0.16       0  4952.9    0.05       0  5173.0    0.16       0
  5258.3   0.033       0  5264.3    0.16       0
Bank Sta=5258.3,5264.3
Exp/Cntr=0.3,0.1

Type RM Length L Ch R = 1,4000,172,172,172
BEGIN DESCRIPTION:
Mapping XS 60cd4758
END DESCRIPTION:
XS GIS Cut Line= 2
      3574101.98     10340325.64      3574192.25     10339426.46
#Sta/Elev= 30
  4560.9  306.12  4745.8  295.54  4765.9  295.89  4786.0  292.66  4796.1  293.26
  4806.1  295.53  4826.2  290.50  4906.6  287.93  4917.1  286.51  4994.1  281.53
  4996.8  281.03  5000.1  281.53  5057.4  283.37  5077.5  285.95  5097.6  287.15
  5137.8  287.10  5167.9  288.17  5178.0  289.07  5198.1  294.42  5208.0  293.96
  5213.0  292.73  5218.2  289.88  5238.3  284.84  5278.5  289.83  5298.6  297.66
  5348.8  298.92  5379.0  302.77  5408.6  304.40  5413.6  303.64  5464.6  307.23
#Mann=3,-1,0
  4560.9    0.16       0  4994.1    0.07       0  5000.1    0.16       0
Bank Sta=4994.1,5000.1
Exp/Cntr=0.3,0.1

Type RM Length L Ch R = 1,3828,630,630,630
BEGIN DESCRIPTION:
NAVASOTA RIVER TRIBUTARY 1.1 6.0
END DESCRIPTION:
XS GIS Cut Line= 3
      3574186.56     10340301.33      3574236.55     10340151.36
      3574448.06     10339475.77
#Sta/Elev= 30
  4578.5  303.31  4778.2  291.78  4788.7  291.92  4837.3  288.62  4907.5  285.69
  4972.4  278.68  4977.6  279.13  4995.2  277.82  4998.0  277.32  5001.2  277.82
  5019.2  278.86  5029.7  282.45  5037.3  283.96  5042.5  280.23  5050.6  280.43
  5069.7  285.24  5102.2  286.38  5124.0  286.74  5134.5  286.11  5139.9  284.10
  5155.4  281.40  5165.9  281.84  5172.3  283.71  5197.3  287.85  5210.0  288.22
  5237.3  291.20  5269.7  292.83  5274.9  292.43  5307.4  294.69  5444.5  301.23
#Mann=3,-1,0
  4578.5    0.16       0  4995.2    0.07       0  5001.2    0.16       0
Bank Sta=4995.2,5001.2
Exp/Cntr=0.3,0.1

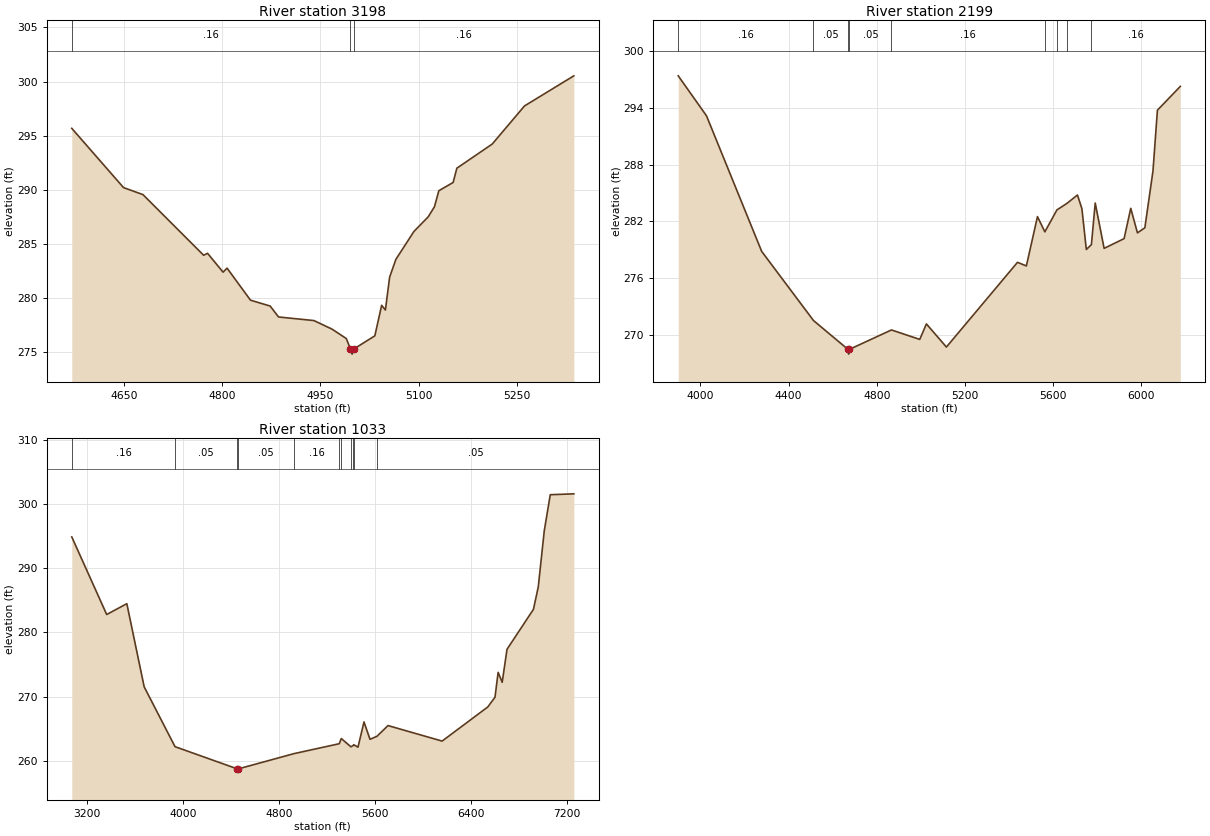
Type RM Length L Ch R = 1,3198,999,999,999
BEGIN DESCRIPTION:
NAVASOTA RIVER TRIBUTARY 1.1 5.0
END DESCRIPTION:
XS GIS Cut Line= 3
      3574592.13     10340291.61      3574753.86     10340058.33
      3574985.63     10339634.98
#Sta/Elev= 30
  4570.3  295.68  4649.3  290.21  4679.0  289.56  4771.6  283.96  4777.6  284.14
  4801.3  282.40  4807.4  282.77  4843.2  279.81  4873.2  279.27  4886.0  278.26
  4940.0  277.93  4967.6  277.14  4989.4  276.27  4995.6  275.33  4998.3  274.83
  5001.6  275.33  5033.0  276.52  5043.4  279.34  5049.1  278.90  5055.6  281.95
  5065.2  283.59  5092.7  286.16  5114.5  287.51  5124.0  288.44  5130.7  289.92
  5152.5  290.68  5158.2  292.00  5212.2  294.23  5261.5  297.75  5336.8  300.53
#Mann=3,-1,0
  4570.3    0.16       0  4995.6    0.07       0  5001.6    0.16       0
Bank Sta=4995.6,5001.6
Exp/Cntr=0.3,0.1

Type RM Length L Ch R = 1,2199,1166,1166,1166
BEGIN DESCRIPTION:
NAVASOTA RIVER TRIBUTARY 1.1 2.0
END DESCRIPTION:
XS GIS Cut Line= 3
      3574733.07     10341009.69      3575441.36     10340593.05
      3575267.75     10339148.60
#Sta/Elev= 30
  3900.0  297.42  4028.3  293.18  4278.4  278.83  4513.2  271.51  4669.8  268.45
  4672.6  267.95  4675.8  268.45  4866.8  270.51  4995.1  269.51  5025.3  271.15
  5116.0  268.70  5438.3  277.67  5478.6  277.29  5528.9  282.51  5562.4  280.90
  5617.1  283.22  5661.8  283.90  5710.2  284.80  5730.4  283.35  5750.5  279.03
  5773.5  279.55  5790.8  283.95  5831.1  279.15  5921.7  280.18  5951.9  283.39
  5982.2  280.79  6015.9  281.33  6052.7  287.35  6072.8  293.78  6176.6  296.30
#Mann=9,-1,0
  3900.0    0.16       0  4513.2    0.05       0  4669.8    0.07       0
  4675.8    0.05       0  4866.8    0.16       0  5562.4    0.08       0
  5617.1    0.05       0  5661.8    0.08       0  5773.5    0.16       0
Bank Sta=4669.8,4675.8
Exp/Cntr=0.3,0.1

Type RM Length L Ch R = 1,1033,0,0,0
BEGIN DESCRIPTION:
NAVASOTA RIVER TRIBUTARY 1.1 1.0
END DESCRIPTION:
XS GIS Cut Line= 3
      3574788.57     10341794.45      3576226.08     10341148.61
      3576121.96     10338545.52
#Sta/Elev= 30
  3075.5  294.90  3366.4  282.80  3534.1  284.49  3678.5  271.52  3935.3  262.19
  4455.1  258.72  4457.9  258.22  4461.1  258.72  4927.3  261.11  5303.1  262.65
  5319.9  263.46  5400.2  262.17  5419.8  262.37  5423.1  262.50  5459.0  262.11
  5509.1  266.05  5559.1  263.34  5616.3  263.80  5709.2  265.48  6159.6  263.06
  6539.9  268.38  6600.0  269.90  6626.2  273.78  6660.0  272.23  6700.0  277.37
  6920.2  283.61  6960.2  287.09  7010.3  295.85  7060.3  301.48  7256.6  301.62
#Mann=11,-1,0
  3075.5    0.16       0  3935.3    0.05       0  4455.1    0.07       0
  4461.1    0.05       0  4927.3    0.16       0  5303.1    0.12       0
  5319.9    0.16       0  5400.2    0.12       0  5419.8    0.16       0
  5423.1    0.08       0  5616.3    0.05       0
Bank Sta=4455.1,4461.1
Exp/Cntr=0.3,0.1

Chan Stop Cuts=-1