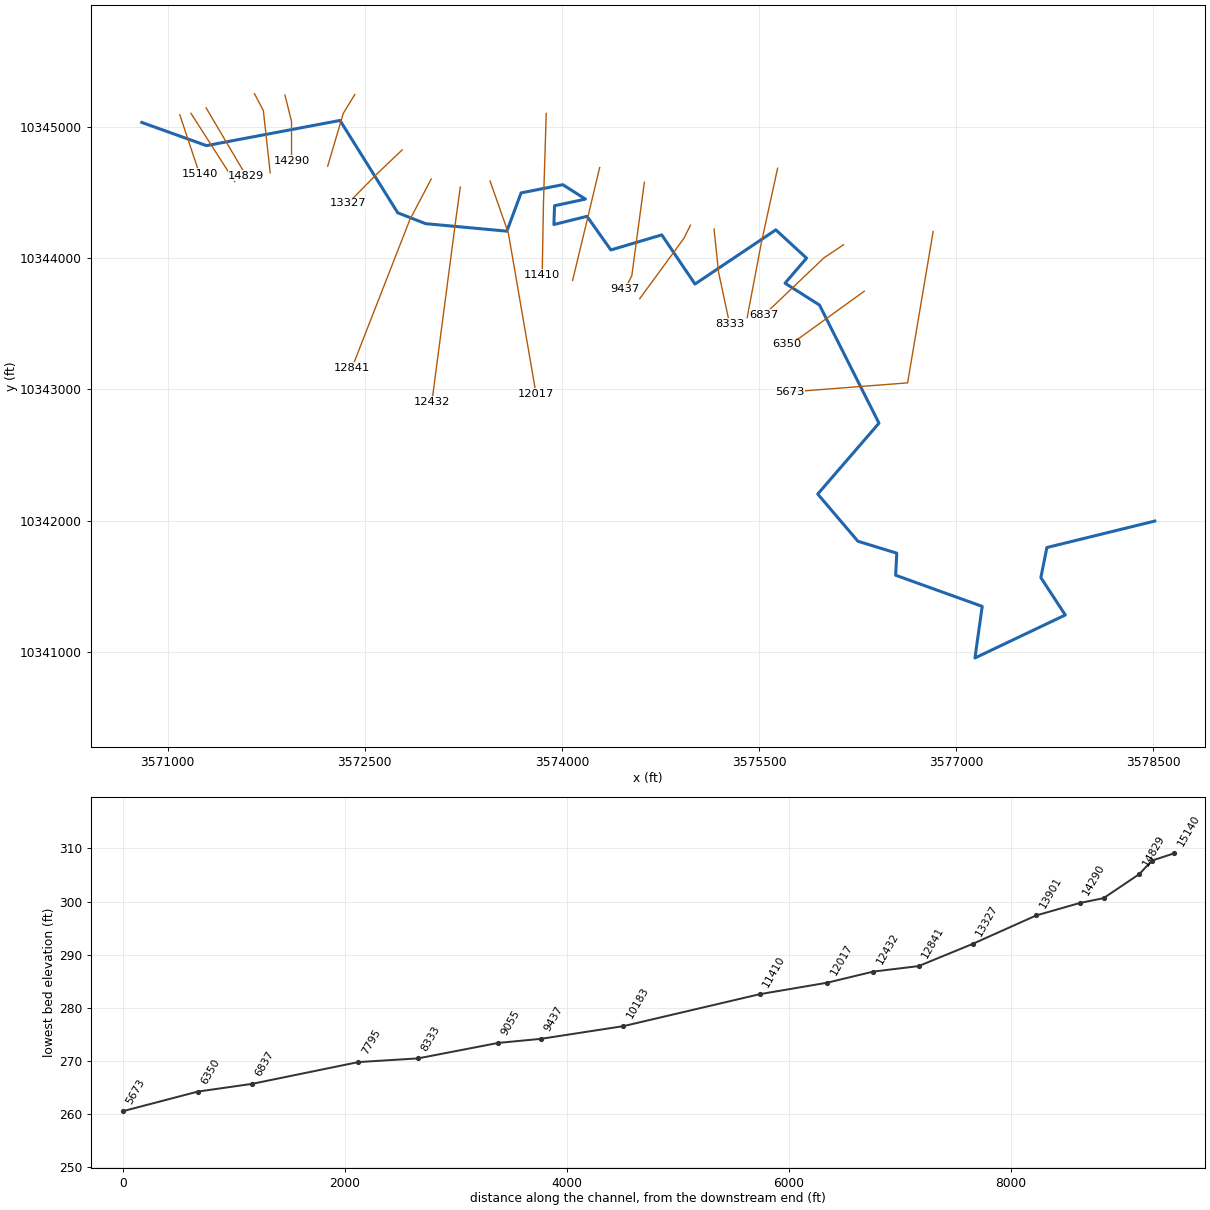
--- NAVASOTA RIVER TRIBUTARY 1.prj (project) ---

Proj Title=NAVASOTA RIVER TRIBUTARY 1 Base Level Engineering
Current Plan=p01
Default Exp/Contr=0.3,0.1
English Units
Geom File=g01
Flow File=f01
Plan File=p01
BEGIN DESCRIPTION:
NAVASOTA RIVER TRIBUTARY 1
END DESCRIPTION:

--- NAVASOTA RIVER TRIBUTARY 1.p01 (plan) ---

Plan Title=Multiple Run
Short Identifier=Multiple
Geom File=g01
Flow File=f01
Subcritical Flow
K Sum by GR= 0
Std Step Tol= 0.01
Critical Tol= 0.01
Num of Std Step Trials= 20
Max Error Tol= 0.3
Flow Tol Ratio= 0.001
Split Flow NTrial= 30
Split Flow Tol= 0.02
Split Flow Ratio= 0.02
Log Output Level= 0
Friction Slope Method= 1
Unsteady Friction Slope Method= 2
Unsteady Bridges Friction Slope Method= 1
Parabolic Critical Depth
Global Vel Dist=  1 , 1 , 1
Global Log Level= 0
CheckData=True
Encroach Param= -1, 0, 0, 0
BEGIN DESCRIPTION:
Multiple Run
END DESCRIPTION:

--- NAVASOTA RIVER TRIBUTARY 1.f01 (steady flow) ---

Flow Title=Multiple
Number of Profiles=7
Profile Names=10-year,25-year,50-year,1pct_min,100-year,1pct_plu,500-year
River Rch & RM= NAVASOTA RIVER T,Reach-1,15140
     398     527     629     552     746    1009    1051
River Rch & RM= NAVASOTA RIVER T,Reach-1,12017
     696     947    1154    1029    1392    1882    2031
Boundary for River Rch & Prof#=NAVASOTA RIVER T,Reach-1,1
Up Type=0
Dn Type=3
Dn Slope=0.005
Boundary for River Rch & Prof#=NAVASOTA RIVER T,Reach-1,2
Up Type=0
Dn Type=3
Dn Slope=0.005
Boundary for River Rch & Prof#=NAVASOTA RIVER T,Reach-1,3
Up Type=0
Dn Type=3
Dn Slope=0.005
Boundary for River Rch & Prof#=NAVASOTA RIVER T,Reach-1,4
Up Type=0
Dn Type=3
Dn Slope=0.005
Boundary for River Rch & Prof#=NAVASOTA RIVER T,Reach-1,5
Up Type=0
Dn Type=3
Dn Slope=0.005
Boundary for River Rch & Prof#=NAVASOTA RIVER T,Reach-1,6
Up Type=0
Dn Type=3
Dn Slope=0.005
Boundary for River Rch & Prof#=NAVASOTA RIVER T,Reach-1,7
Up Type=0
Dn Type=3
Dn Slope=0.005

--- NAVASOTA RIVER TRIBUTARY 1.g01 (geometry) ---

Geom Title=Existing Conditions

River Reach=NAVASOTA RIVER T,Reach-1
Reach XY= 30
      3570802.93     10345033.55      3571295.00     10344857.03
      3572311.23     10345048.85      3572750.52     10344345.53
      3572962.21     10344262.86      3573580.79     10344205.62
      3573689.30     10344497.06      3574006.66     10344559.68
      3574178.79     10344449.76      3573943.72     10344399.13
      3573938.90     10344256.10      3574190.62     10344318.59
      3574372.23     10344062.64      3574759.73     10344177.17
      3575012.36     10343802.80      3575627.54     10344215.50
      3575861.48     10344000.22      3575697.68     10343809.51
      3575959.79     10343642.97      3576412.53     10342743.42
      3575946.56     10342203.63      3576252.38     10341844.08
      3576547.81     10341753.34      3576539.48     10341585.29
      3577198.04     10341348.20      3577142.94     10340955.28
      3577830.26     10341282.49      3577644.30     10341567.56
      3577690.30     10341796.40      3578511.23     10341997.94

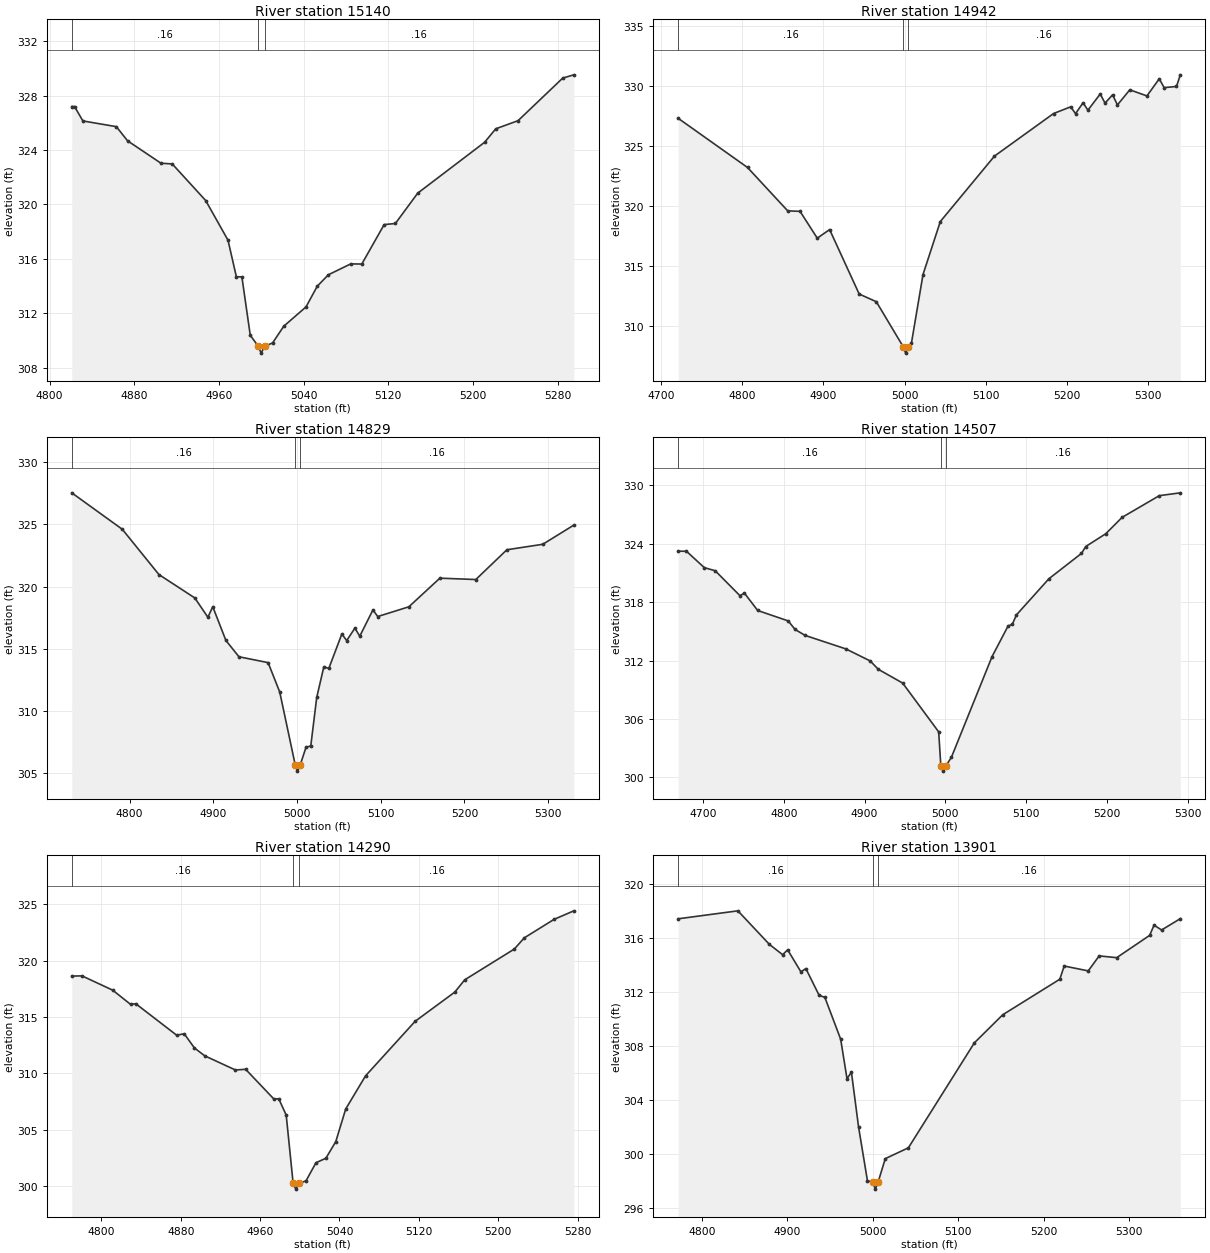
Type RM Length L Ch R = 1,15140,198,198,198
BEGIN DESCRIPTION:
NAVASOTA RIVER TRIBUTARY 1 19.0
END DESCRIPTION:
XS GIS Cut Line= 3
      3571092.11     10345091.63      3571142.11     10344941.64
      3571242.10     10344641.67
#Sta/Elev= 30
  4821.0  327.20  4823.6  327.20  4831.5  326.14  4863.1  325.72  4873.7  324.68
  4905.3  323.03  4915.9  322.98  4947.5  320.29  4968.6  317.37  4976.5  314.68
  4981.7  314.68  4989.6  310.39  4997.2  309.57  4999.9  309.07  5003.2  309.57
  5010.7  309.82  5021.3  311.05  5042.3  312.47  5052.9  313.99  5063.4  314.83
  5084.5  315.63  5095.0  315.62  5116.1  318.52  5126.7  318.60  5147.8  320.83
  5211.0  324.57  5221.5  325.56  5242.6  326.16  5284.8  329.29  5295.3  329.53
#Mann=3,-1,0
  4821.0    0.16       0  4997.2    0.07       0  5003.2    0.16       0
Bank Sta=4997.2,5003.2
Exp/Cntr=0.3,0.1

Type RM Length L Ch R = 1,14942,113,113,113
BEGIN DESCRIPTION:
NAVASOTA RIVER TRIBUTARY 1 18.0
END DESCRIPTION:
XS GIS Cut Line= 2
      3571176.57     10345103.49      3571509.66     10344582.70
#Sta/Elev= 30
  4721.4  327.30  4806.7  323.20  4856.2  319.58  4871.4  319.54  4892.6  317.30
  4907.8  318.02  4944.2  312.64  4965.3  312.00  4998.7  308.21  5001.4  307.71
  5004.7  308.21  5008.5  308.53  5022.8  314.27  5044.1  318.69  5110.8  324.15
  5183.5  327.70  5204.6  328.26  5210.6  327.69  5219.9  328.60  5225.8  327.98
  5241.0  329.33  5246.9  328.57  5256.2  329.26  5262.2  328.42  5277.4  329.68
  5298.5  329.17  5313.7  330.60  5319.7  329.86  5334.9  329.96  5339.6  330.93
#Mann=3,-1,0
  4721.4    0.16       0  4998.7    0.07       0  5004.7    0.16       0
Bank Sta=4998.7,5004.7
Exp/Cntr=0.3,0.1

Type RM Length L Ch R = 1,14829,322,322,322
BEGIN DESCRIPTION:
Mapping XS b51064c1
END DESCRIPTION:
XS GIS Cut Line= 2
      3571292.68     10345143.62      3571597.40     10344627.11
#Sta/Elev= 30
  4731.0  327.52  4791.4  324.59  4835.1  320.96  4878.0  319.08  4893.6  317.53
  4899.4  318.38  4915.1  315.67  4930.7  314.36  4965.5  313.89  4979.4  311.53
  4997.9  305.68  5000.6  305.18  5003.9  305.68  5010.7  307.08  5016.5  307.21
  5023.6  311.10  5032.1  313.56  5038.0  313.42  5053.6  316.19  5059.4  315.66
  5069.2  316.66  5075.0  316.01  5090.7  318.12  5096.5  317.59  5133.6  318.37
  5170.7  320.67  5213.6  320.56  5250.7  322.95  5293.6  323.39  5330.7  324.93
#Mann=3,-1,0
  4731.0    0.16       0  4997.9    0.07       0  5003.9    0.16       0
Bank Sta=4997.9,5003.9
Exp/Cntr=0.3,0.1

Type RM Length L Ch R = 1,14507,217,217,217
BEGIN DESCRIPTION:
Mapping XS 7c16457f
END DESCRIPTION:
XS GIS Cut Line= 3
      3571660.48     10345252.19      3571727.77     10345124.13
      3571779.85     10344649.94
#Sta/Elev= 30
  4669.3  323.23  4679.5  323.22  4701.6  321.54  4715.1  321.22  4745.7  318.66
  4751.3  318.92  4767.7  317.14  4805.5  316.07  4814.0  315.19  4826.5  314.58
  4876.8  313.20  4907.0  311.96  4917.1  311.10  4947.2  309.69  4991.8  304.68
  4994.5  301.15  4997.3  300.65  5000.5  301.15  5007.6  302.08  5057.9  312.41
  5077.8  315.56  5082.9  315.71  5088.1  316.69  5128.3  320.40  5168.6  323.00
  5173.9  323.71  5198.7  325.02  5218.9  326.70  5265.0  328.93  5291.0  329.22
#Mann=3,-1,0
  4669.3    0.16       0  4994.5    0.07       0  5000.5    0.16       0
Bank Sta=4994.5,5000.5
Exp/Cntr=0.3,0.1

Type RM Length L Ch R = 1,14290,389,389,389
BEGIN DESCRIPTION:
NAVASOTA RIVER TRIBUTARY 1 17.0
END DESCRIPTION:
XS GIS Cut Line= 3
      3571892.10     10345241.68      3571942.11     10345041.64
      3571942.11     10344741.64
#Sta/Elev= 30
  4770.1  318.62  4780.4  318.64  4811.4  317.37  4829.4  316.11  4834.6  316.17
  4875.8  313.38  4883.5  313.50  4893.8  312.24  4904.1  311.55  4935.1  310.29
  4945.4  310.35  4973.7  307.73  4978.8  307.73  4986.3  306.29  4993.3  300.22
  4996.0  299.72  4999.3  300.22  5006.3  300.46  5016.3  302.06  5026.3  302.46
  5036.3  303.94  5046.3  306.83  5066.3  309.77  5116.3  314.61  5156.3  317.20
  5166.3  318.29  5216.3  321.02  5226.3  322.01  5256.3  323.65  5276.3  324.41
#Mann=3,-1,0
  4770.1    0.16       0  4993.3    0.07       0  4999.3    0.16       0
Bank Sta=4993.3,4999.3
Exp/Cntr=0.3,0.1

Type RM Length L Ch R = 1,13901,574,574,574
BEGIN DESCRIPTION:
NAVASOTA RIVER TRIBUTARY 1 16.0
END DESCRIPTION:
XS GIS Cut Line= 3
      3572423.37     10345246.32      3572335.84     10345102.16
      3572217.44     10344700.61
#Sta/Elev= 30
  4772.5  317.43  4842.3  318.02  4879.2  315.53  4894.6  314.77  4900.5  315.13
  4916.0  313.50  4921.8  313.74  4937.3  311.76  4944.0  311.61  4962.5  308.51
  4969.9  305.59  4975.1  306.06  4983.4  302.02  4993.8  298.03  5000.2  297.90
  5003.0  297.40  5006.2  297.90  5014.7  299.66  5041.7  300.46  5118.9  308.24
  5152.1  310.32  5218.8  312.95  5224.0  313.93  5252.1  313.57  5264.9  314.68
  5285.4  314.55  5323.9  316.20  5329.1  316.96  5337.9  316.60  5359.8  317.44
#Mann=3,-1,0
  4772.5    0.16       0  5000.2    0.07       0  5006.2    0.16       0
Bank Sta=5000.2,5006.2
Exp/Cntr=0.3,0.1

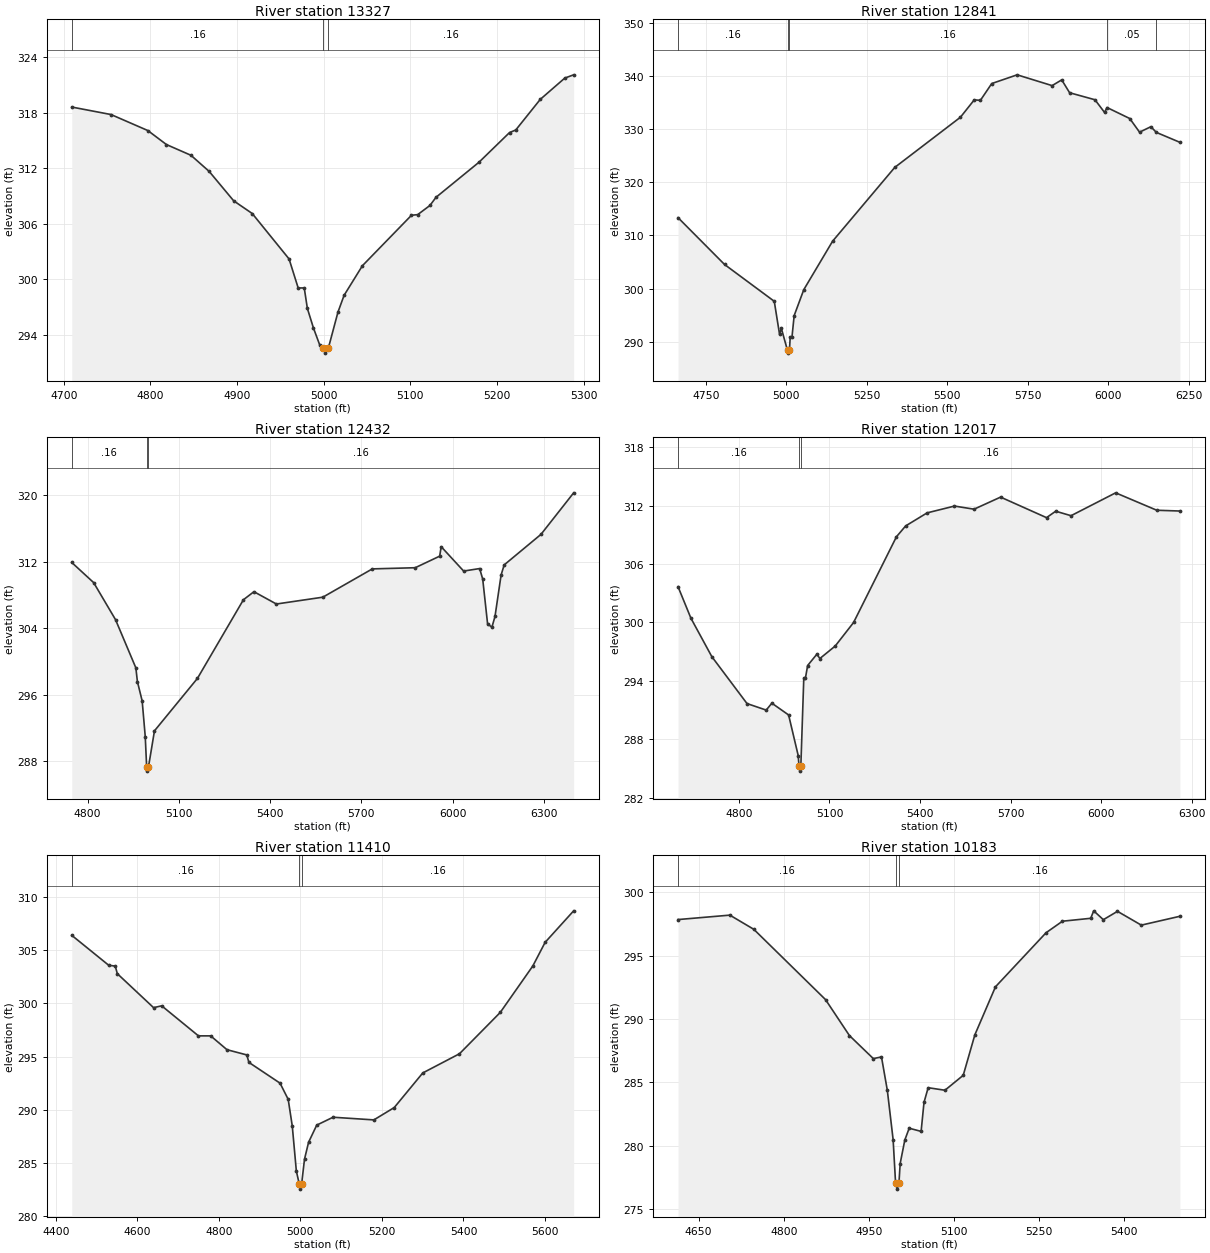
Type RM Length L Ch R = 1,13327,486,486,486
BEGIN DESCRIPTION:
NAVASOTA RIVER TRIBUTARY 1 15.0
END DESCRIPTION:
XS GIS Cut Line= 3
      3572783.80     10344824.16      3572592.11     10344641.64
      3572371.88     10344417.39
#Sta/Elev= 30
  4709.3  318.61  4754.6  317.80  4797.1  316.07  4818.5  314.56  4846.8  313.40
  4867.8  311.66  4896.1  308.48  4917.5  307.11  4960.0  302.20  4970.5  299.07
  4977.5  299.07  4981.1  296.86  4988.1  294.75  4995.2  292.95  4999.2  292.53
  5002.0  292.03  5005.2  292.53  5016.4  296.46  5023.5  298.28  5044.6  301.47
  5101.2  306.92  5108.4  306.99  5122.5  307.98  5129.5  308.86  5179.1  312.65
  5214.4  315.86  5221.5  316.13  5249.8  319.44  5278.1  321.74  5288.3  322.09
#Mann=3,-1,0
  4709.3    0.16       0  4999.2    0.07       0  5005.2    0.16       0
Bank Sta=4999.2,5005.2
Exp/Cntr=0.3,0.1

Type RM Length L Ch R = 1,12841,409,409,409
BEGIN DESCRIPTION:
NAVASOTA RIVER TRIBUTARY 1 14.0
END DESCRIPTION:
XS GIS Cut Line= 3
      3573005.18     10344602.78      3572842.11     10344291.64
      3572402.83     10343166.43
#Sta/Elev= 30
  4663.9  313.35  4808.4  304.54  4962.9  297.61  4979.3  291.39  4984.9  292.52
  5004.0  288.36  5006.7  287.86  5010.0  288.36  5012.4  290.88  5017.9  290.88
  5024.7  294.92  5054.6  299.80  5144.1  308.92  5337.2  322.80  5541.2  332.24
  5584.2  335.51  5603.3  335.42  5638.5  338.58  5717.4  340.22  5826.0  338.19
  5855.9  339.27  5880.4  336.85  5959.2  335.53  5989.0  333.14  5996.6  334.07
  6067.2  332.00  6097.7  329.43  6132.9  330.46  6149.8  329.39  6223.1  327.52
#Mann=5,-1,0
  4663.9    0.16       0  5004.0    0.07       0  5010.0    0.16       0
  5996.6    0.05       0  6149.8    0.16       0
Bank Sta=5004,5010
Exp/Cntr=0.3,0.1

Type RM Length L Ch R = 1,12432,415,415,415
BEGIN DESCRIPTION:
NAVASOTA RIVER TRIBUTARY 1 13.0
END DESCRIPTION:
XS GIS Cut Line= 3
      3573226.55     10344540.97      3573192.11     10344291.64
      3573010.50     10342905.19
#Sta/Elev= 30
  4747.9  311.89  4819.9  309.47  4891.8  305.02  4958.6  299.23  4963.7  297.58
  4979.4  295.25  4989.5  290.97  4994.1  287.32  4996.8  286.82  5000.1  287.32
  5019.8  291.66  5161.0  297.96  5312.2  307.41  5346.8  308.38  5420.6  306.90
  5573.3  307.72  5736.0  311.12  5877.0  311.26  5957.4  312.65  5962.4  313.79
  6036.2  310.86  6088.8  311.16  6098.9  309.90  6115.0  304.50  6129.2  304.12
  6139.3  305.40  6159.4  310.39  6169.5  311.60  6290.5  315.27  6397.9  320.26
#Mann=3,-1,0
  4747.9    0.16       0  4994.1    0.07       0  5000.1    0.16       0
Bank Sta=4994.1,5000.1
Exp/Cntr=0.3,0.1

Type RM Length L Ch R = 1,12017,607,607,607
BEGIN DESCRIPTION:
NAVASOTA RIVER TRIBUTARY 1 12.0
END DESCRIPTION:
XS GIS Cut Line= 3
      3573453.08     10344587.31      3573592.11     10344191.64
      3573803.09     10342966.05
#Sta/Elev= 30
  4598.3  303.68  4641.0  300.44  4710.3  296.49  4826.9  291.67  4890.5  291.00
  4909.2  291.71  4964.7  290.50  4996.5  286.33  4999.2  285.23  5001.9  284.73
  5005.2  285.23  5015.0  294.25  5020.2  294.25  5027.8  295.58  5058.3  296.74
  5068.4  296.30  5119.1  297.58  5180.0  300.00  5322.1  308.81  5352.5  309.92
  5423.6  311.26  5514.2  311.96  5579.2  311.64  5667.1  312.88  5819.3  310.77
  5849.7  311.43  5900.5  310.97  6048.4  313.32  6184.6  311.53  6261.3  311.45
#Mann=3,-1,0
  4598.3    0.16       0  4999.2    0.07       0  5005.2    0.16       0
Bank Sta=4999.2,5005.2
Exp/Cntr=0.3,0.1

Type RM Length L Ch R = 1,11410,1227,1227,1227
BEGIN DESCRIPTION:
NAVASOTA RIVER TRIBUTARY 1 11.0
END DESCRIPTION:
XS GIS Cut Line= 3
      3573880.42     10345102.18      3573859.83     10344432.84
      3573849.53     10343871.69
#Sta/Elev= 30
  4439.3  306.40  4529.9  303.59  4546.0  303.51  4551.0  302.80  4639.9  299.61
  4659.9  299.78  4750.0  296.96  4780.0  296.96  4820.0  295.66  4868.6  295.17
  4873.7  294.47  4950.1  292.52  4970.1  291.00  4980.1  288.50  4990.1  284.27
  4997.1  283.07  4999.9  282.57  5003.1  283.07  5010.1  285.38  5020.1  286.97
  5040.1  288.58  5080.1  289.32  5180.2  289.07  5230.2  290.23  5300.2  293.48
  5390.2  295.28  5490.2  299.16  5570.2  303.53  5600.2  305.74  5670.2  308.70
#Mann=3,-1,0
  4439.3    0.16       0  4997.1    0.07       0  5003.1    0.16       0
Bank Sta=4997.1,5003.1
Exp/Cntr=0.3,0.1

Type RM Length L Ch R = 1,10183,746,746,746
BEGIN DESCRIPTION:
NAVASOTA RIVER TRIBUTARY 1 10.0
END DESCRIPTION:
XS GIS Cut Line= 3
      3574287.15     10344690.25      3574192.11     10344291.64
      3574081.22     10343830.47
#Sta/Elev= 30
  4613.8  297.85  4705.1  298.20  4747.3  297.08  4873.6  291.53  4915.7  288.69
  4957.8  286.87  4972.2  287.00  4982.5  284.36  4992.7  280.47  4997.0  277.06
  4999.7  276.56  5003.0  277.06  5005.1  278.58  5013.3  280.44  5021.0  281.37
  5042.0  281.12  5047.1  283.41  5054.4  284.57  5084.0  284.37  5116.2  285.55
  5136.7  288.75  5173.0  292.54  5262.1  296.81  5291.0  297.72  5340.8  297.95
  5346.0  298.54  5363.0  297.84  5387.9  298.50  5429.9  297.41  5497.9  298.11
#Mann=3,-1,0
  4613.8    0.16       0  4997.0    0.07       0  5003.0    0.16       0
Bank Sta=4997,5003
Exp/Cntr=0.3,0.1

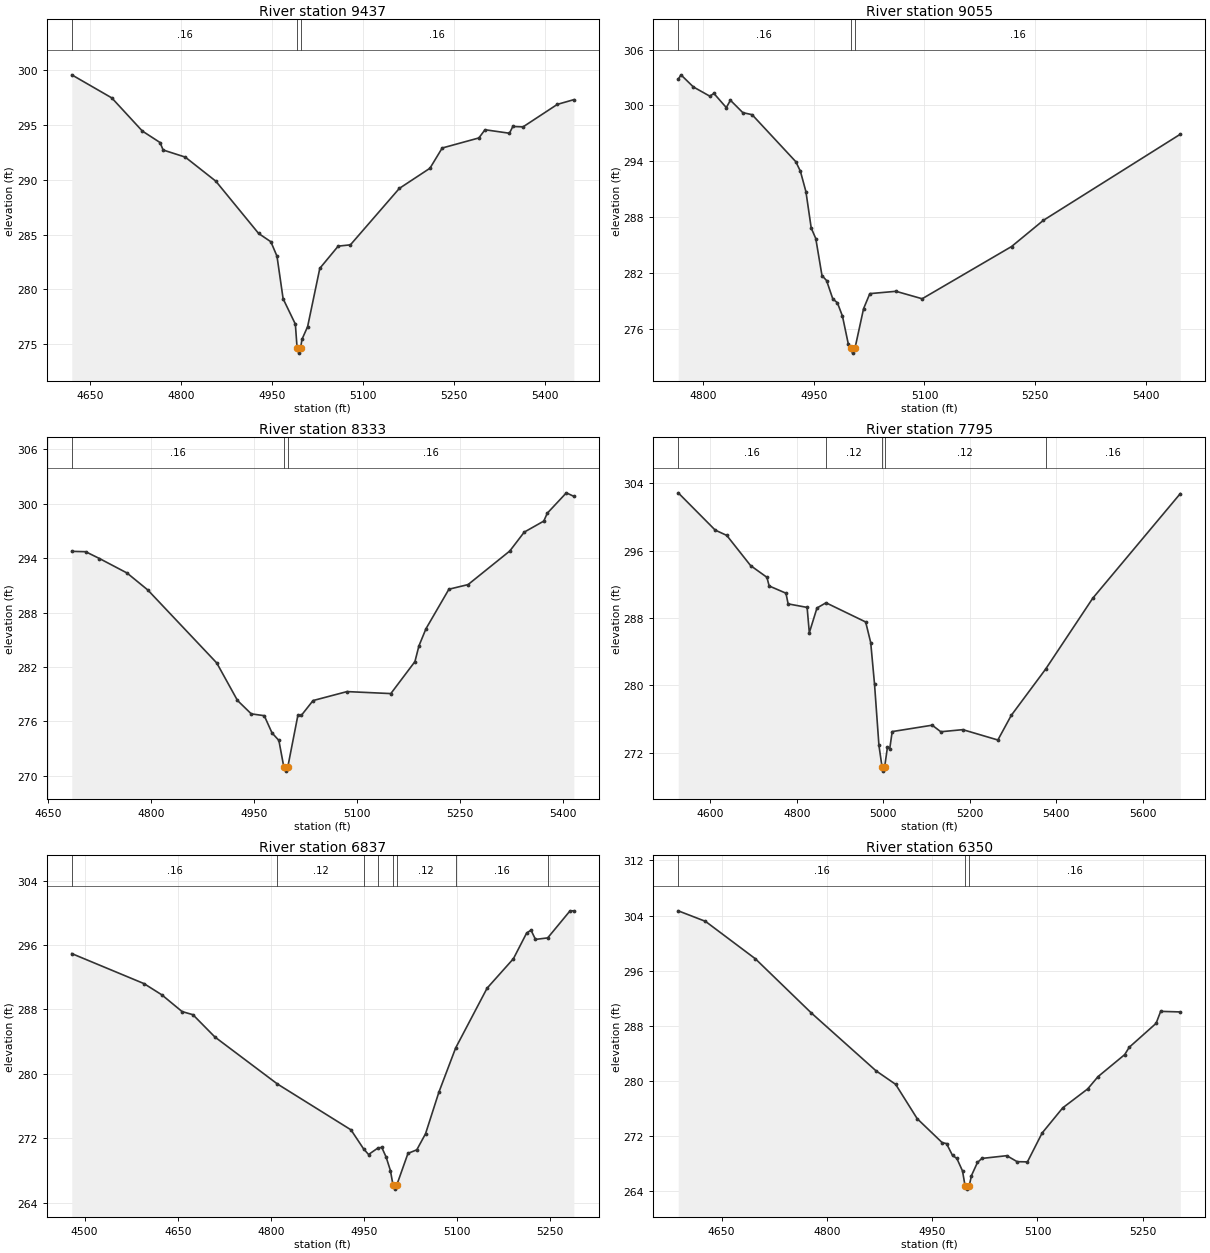
Type RM Length L Ch R = 1,9437,382,382,382
BEGIN DESCRIPTION:
NAVASOTA RIVER TRIBUTARY 1 9.0
END DESCRIPTION:
XS GIS Cut Line= 3
      3574626.97     10344577.04      3574531.81     10343867.28
      3574481.82     10343767.30
#Sta/Elev= 30
  4619.2  299.60  4685.2  297.49  4735.6  294.46  4764.8  293.41  4769.8  292.73
  4806.3  292.08  4856.7  289.88  4927.3  285.10  4947.5  284.34  4957.6  283.02
  4967.7  279.13  4987.9  276.81  4990.7  274.66  4993.4  274.16  4996.7  274.66
  4998.7  275.41  5008.1  276.58  5028.2  281.91  5058.5  283.94  5078.7  284.06
  5159.4  289.22  5209.8  291.06  5230.0  292.91  5290.5  293.83  5300.6  294.58
  5340.9  294.26  5346.5  294.88  5363.3  294.84  5419.9  296.90  5447.1  297.33
#Mann=3,-1,0
  4619.2    0.16       0  4990.7    0.07       0  4996.7    0.16       0
Bank Sta=4990.7,4996.7
Exp/Cntr=0.3,0.1

Type RM Length L Ch R = 1,9055,722,722,722
BEGIN DESCRIPTION:
NAVASOTA RIVER TRIBUTARY 1 8.0
END DESCRIPTION:
XS GIS Cut Line= 3
      3574978.13     10344251.22      3574928.15     10344151.25
      3574592.12     10343691.66
#Sta/Elev= 30
  4766.0  302.81  4769.7  303.29  4786.5  301.99  4808.8  301.00  4814.4  301.29
  4831.2  299.77  4836.8  300.56  4853.6  299.23  4866.2  299.01  4925.5  293.96
  4931.7  292.94  4939.2  290.75  4946.4  286.84  4952.6  285.70  4961.0  281.73
  4967.2  281.20  4975.7  279.22  4981.9  278.81  4988.8  277.37  4996.6  274.42
  4999.7  273.90  5002.5  273.40  5005.7  273.90  5017.4  278.17  5025.9  279.79
  5061.4  280.04  5096.9  279.24  5218.2  284.85  5261.3  287.66  5447.1  296.91
#Mann=3,-1,0
  4766.0    0.16       0  4999.7    0.07       0  5005.7    0.16       0
Bank Sta=4999.7,5005.7
Exp/Cntr=0.3,0.1

Type RM Length L Ch R = 1,8333,538,538,538
BEGIN DESCRIPTION:
NAVASOTA RIVER TRIBUTARY 1 7.0
END DESCRIPTION:
XS GIS Cut Line= 3
      3575157.28     10344221.71      3575192.11     10343891.64
      3575275.68     10343500.98
#Sta/Elev= 30
  4685.0  294.75  4705.2  294.71  4725.3  293.96  4765.5  292.36  4795.7  290.49
  4896.2  282.43  4926.4  278.29  4946.5  276.81  4965.4  276.61  4976.7  274.71
  4986.7  273.88  4993.8  270.99  4996.5  270.49  4999.8  270.99  5014.4  276.65
  5019.5  276.65  5036.5  278.28  5086.0  279.27  5149.8  279.05  5184.9  282.58
  5190.7  284.31  5201.0  286.21  5234.4  290.57  5262.3  291.08  5323.1  294.79
  5344.1  296.87  5372.6  298.09  5377.7  298.96  5405.5  301.21  5416.4  300.82
#Mann=3,-1,0
  4685.0    0.16       0  4993.8    0.07       0  4999.8    0.16       0
Bank Sta=4993.8,4999.8
Exp/Cntr=0.3,0.1

Type RM Length L Ch R = 1,7795,958,958,958
BEGIN DESCRIPTION:
NAVASOTA RIVER TRIBUTARY 1 6.0
END DESCRIPTION:
XS GIS Cut Line= 3
      3575641.25     10344685.17      3575517.67     10344118.78
      3575409.56     10343547.33
#Sta/Elev= 30
  4525.8  302.87  4611.3  298.44  4638.0  297.81  4693.2  294.22  4730.9  292.83
  4736.1  291.80  4774.9  290.94  4780.0  289.67  4823.9  289.25  4829.0  286.24
  4846.7  289.18  4867.6  289.80  4959.3  287.52  4971.0  285.07  4979.8  280.15
  4990.0  272.86  4997.2  270.29  5000.0  269.79  5003.2  270.29  5009.8  272.66
  5015.0  272.45  5020.7  274.49  5113.2  275.25  5133.1  274.47  5184.0  274.72
  5265.1  273.49  5296.0  276.41  5375.5  281.91  5484.7  290.35  5687.1  302.78
#Mann=5,-1,0
  4525.8    0.16       0  4867.6    0.12       0  4997.2    0.07       0
  5003.2    0.12       0  5375.5    0.16       0
Bank Sta=4997.2,5003.2
Exp/Cntr=0.3,0.1

Type RM Length L Ch R = 1,6837,487,487,487
BEGIN DESCRIPTION:
NAVASOTA RIVER TRIBUTARY 1 5.0
END DESCRIPTION:
XS GIS Cut Line= 3
      3576142.89     10344101.93      3575992.90     10344001.94
      3575538.29     10343567.90
#Sta/Elev= 30
  4479.2  294.94  4595.6  291.21  4624.4  289.81  4656.9  287.74  4674.4  287.35
  4709.8  284.58  4810.6  278.74  4929.0  273.05  4949.3  270.69  4957.3  269.99
  4972.5  270.80  4978.6  270.87  4985.6  269.67  4992.5  268.00  4996.7  266.19
  4999.5  265.69  5002.7  266.19  5020.8  270.13  5035.0  270.57  5049.1  272.57
  5070.5  277.71  5097.6  283.22  5148.2  290.64  5190.7  294.31  5212.0  297.50
  5219.0  297.85  5226.2  296.70  5245.9  296.89  5281.9  300.25  5288.0  300.25
#Mann=8,-1,0
  4479.2    0.16       0  4810.6    0.12       0  4949.3    0.16       0
  4972.5    0.12       0  4996.7    0.07       0  5002.7    0.12       0
  5097.6    0.16       0  5245.9     0.1       0
Bank Sta=4996.7,5002.7
Exp/Cntr=0.3,0.1

Type RM Length L Ch R = 1,6350,677,677,677
BEGIN DESCRIPTION:
NAVASOTA RIVER TRIBUTARY 1 4.0
END DESCRIPTION:
XS GIS Cut Line= 3
      3576300.29     10343748.10      3575811.21     10343394.51
      3575711.22     10343344.51
#Sta/Elev= 30
  4588.2  304.68  4627.0  303.15  4698.1  297.71  4777.8  289.84  4869.9  281.44
  4897.9  279.47  4928.7  274.47  4964.3  270.99  4970.4  270.86  4979.0  269.13
  4985.1  268.71  4993.2  266.88  4996.8  264.74  4999.6  264.24  5002.8  264.74
  5006.0  266.22  5014.5  268.11  5020.7  268.70  5056.3  269.10  5071.0  268.23
  5085.7  268.20  5106.6  272.39  5136.0  276.05  5171.5  278.80  5186.3  280.59
  5224.3  283.79  5230.7  284.85  5269.0  288.33  5275.5  290.07  5303.5  289.99
#Mann=3,-1,0
  4588.2    0.16       0  4996.8    0.07       0  5002.8    0.16       0
Bank Sta=4996.8,5002.8
Exp/Cntr=0.3,0.1

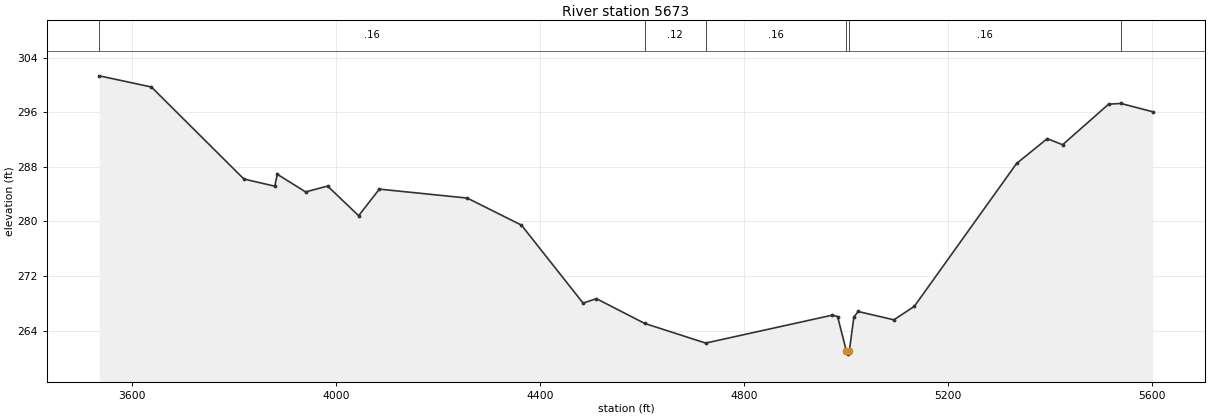
Type RM Length L Ch R = 1,5673,0,0,0
BEGIN DESCRIPTION:
NAVASOTA RIVER TRIBUTARY 1 1.0
END DESCRIPTION:
XS GIS Cut Line= 3
      3576824.79     10344203.20      3576630.35     10343050.42
      3575735.79     10342981.08
#Sta/Elev= 30
  3535.5  301.34  3637.6  299.70  3819.1  286.21  3879.6  285.16  3884.6  286.91
  3940.1  284.32  3983.3  285.18  4044.1  280.83  4084.7  284.73  4257.1  283.42
  4363.5  279.45  4484.4  268.02  4510.6  268.67  4605.2  265.04  4724.9  262.16
  4973.6  266.26  4983.6  266.05  5000.7  261.04  5003.4  260.54  5006.7  261.04
  5015.5  265.94  5023.8  266.79  5094.0  265.57  5134.1  267.54  5334.7  288.49
  5394.9  292.13  5425.0  291.24  5515.2  297.18  5539.4  297.29  5601.8  296.07
#Mann=6,-1,0
  3535.5    0.16       0  4605.2    0.12       0  4724.9    0.16       0
  5000.7    0.07       0  5006.7    0.16       0  5539.4     0.1       0
Bank Sta=5000.7,5006.7
Exp/Cntr=0.3,0.1

Chan Stop Cuts=-1