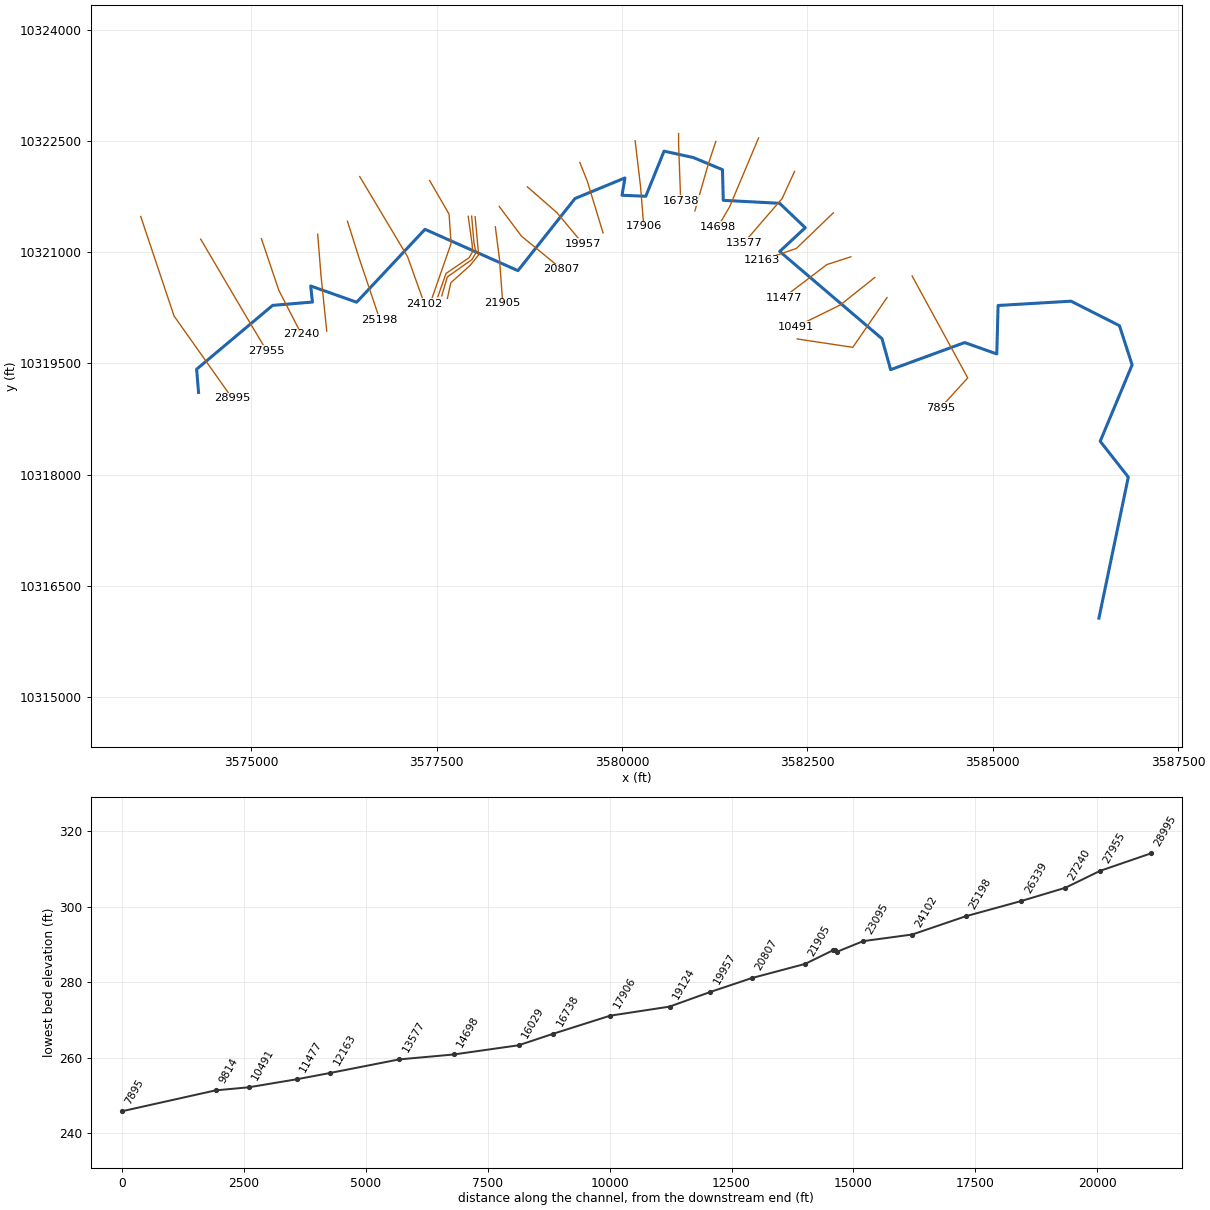
--- NAVASOTA RIVER TRIBUTARY 2 1.prj (project) ---

Proj Title=NAVASOTA RIVER TRIBUTARY 2 1 Base Level Engineering
Current Plan=p01
Default Exp/Contr=0.3,0.1
English Units
Geom File=g01
Flow File=f01
Plan File=p01
Y Axis Title=Elevation
X Axis Title(PF)=Main Channel Distance
X Axis Title(XS)=Station
BEGIN DESCRIPTION:
NAVASOTA RIVER TRIBUTARY 2 1
END DESCRIPTION:
DSS Export Rating Curves= 0
DSS Export Rating Curve Sorted= 0
DSS Export Volume Flow Curves= 0
DXF OffsetX= 0
DXF OffsetY= 0
DXF ScaleX= 1
DXF ScaleY= 10

--- NAVASOTA RIVER TRIBUTARY 2 1.p01 (plan) ---

Plan Title=Multiple Run
Short Identifier=Multiple
Geom File=g01
Flow File=f01
Subcritical Flow
K Sum by GR= 0
Std Step Tol= 0.01
Critical Tol= 0.01
Num of Std Step Trials= 20
Max Error Tol= 0.3
Flow Tol Ratio= 0.001
Split Flow NTrial= 30
Split Flow Tol= 0.02
Split Flow Ratio= 0.02
Log Output Level= 0
Friction Slope Method= 1
Unsteady Friction Slope Method= 2
Unsteady Bridges Friction Slope Method= 1
Parabolic Critical Depth
Global Vel Dist=  1 , 1 , 1
Global Log Level= 0
CheckData=True
Encroach Param= -1, 0, 0, 0
BEGIN DESCRIPTION:
Multiple Run
END DESCRIPTION:

--- NAVASOTA RIVER TRIBUTARY 2 1.f01 (steady flow) ---

Flow Title=Multiple
Number of Profiles=7
Profile Names=10-year,25-year,50-year,1pct_min,100-year,1pct_plu,500-year
River Rch & RM= NAVASOTA RIVER T,Reach-1,28995
     669     898    1083     956    1293    1748    1845
River Rch & RM= NAVASOTA RIVER T,Reach-1,20807
     817    1106    1342    1190    1609    2176    2320
Boundary for River Rch & Prof#=NAVASOTA RIVER T,Reach-1,1
Up Type=0
Dn Type=3
Dn Slope=0.005
Boundary for River Rch & Prof#=NAVASOTA RIVER T,Reach-1,2
Up Type=0
Dn Type=3
Dn Slope=0.005
Boundary for River Rch & Prof#=NAVASOTA RIVER T,Reach-1,3
Up Type=0
Dn Type=3
Dn Slope=0.005
Boundary for River Rch & Prof#=NAVASOTA RIVER T,Reach-1,4
Up Type=0
Dn Type=3
Dn Slope=0.005
Boundary for River Rch & Prof#=NAVASOTA RIVER T,Reach-1,5
Up Type=0
Dn Type=3
Dn Slope=0.005
Boundary for River Rch & Prof#=NAVASOTA RIVER T,Reach-1,6
Up Type=0
Dn Type=3
Dn Slope=0.005
Boundary for River Rch & Prof#=NAVASOTA RIVER T,Reach-1,7
Up Type=0
Dn Type=3
Dn Slope=0.005

--- NAVASOTA RIVER TRIBUTARY 2 1.g01 (geometry) ---

Geom Title=Existing Conditions
Program Version=4.10

River Reach=NAVASOTA RIVER T,Reach-1
Reach XY= 30
       3574289.5     10319108.09      3574263.63     10319421.11
      3575288.88     10320282.35      3575825.52     10320327.25
      3575801.78     10320543.85      3576421.64     10320324.99
      3577343.14      10321308.6      3578596.93     10320750.83
      3579366.04     10321723.72      3580039.94     10322001.95
      3580000.45     10321767.86      3580320.79     10321754.64
       3580567.5     10322363.15       3580961.1     10322277.19
      3581355.29     10322113.37      3581365.85     10321699.53
      3582126.02     10321659.48      3582471.61     10321330.37
      3582127.37      10321009.8      3583506.65     10319832.59
      3583623.04     10319414.81      3584621.91     10319780.66
      3585054.62     10319627.05      3585072.34      10320280.9
      3586056.34     10320338.84       3586709.1      10320008.4
      3586879.98     10319479.67      3586449.43     10318448.59
      3586828.25     10317965.43      3586432.11     10316061.64

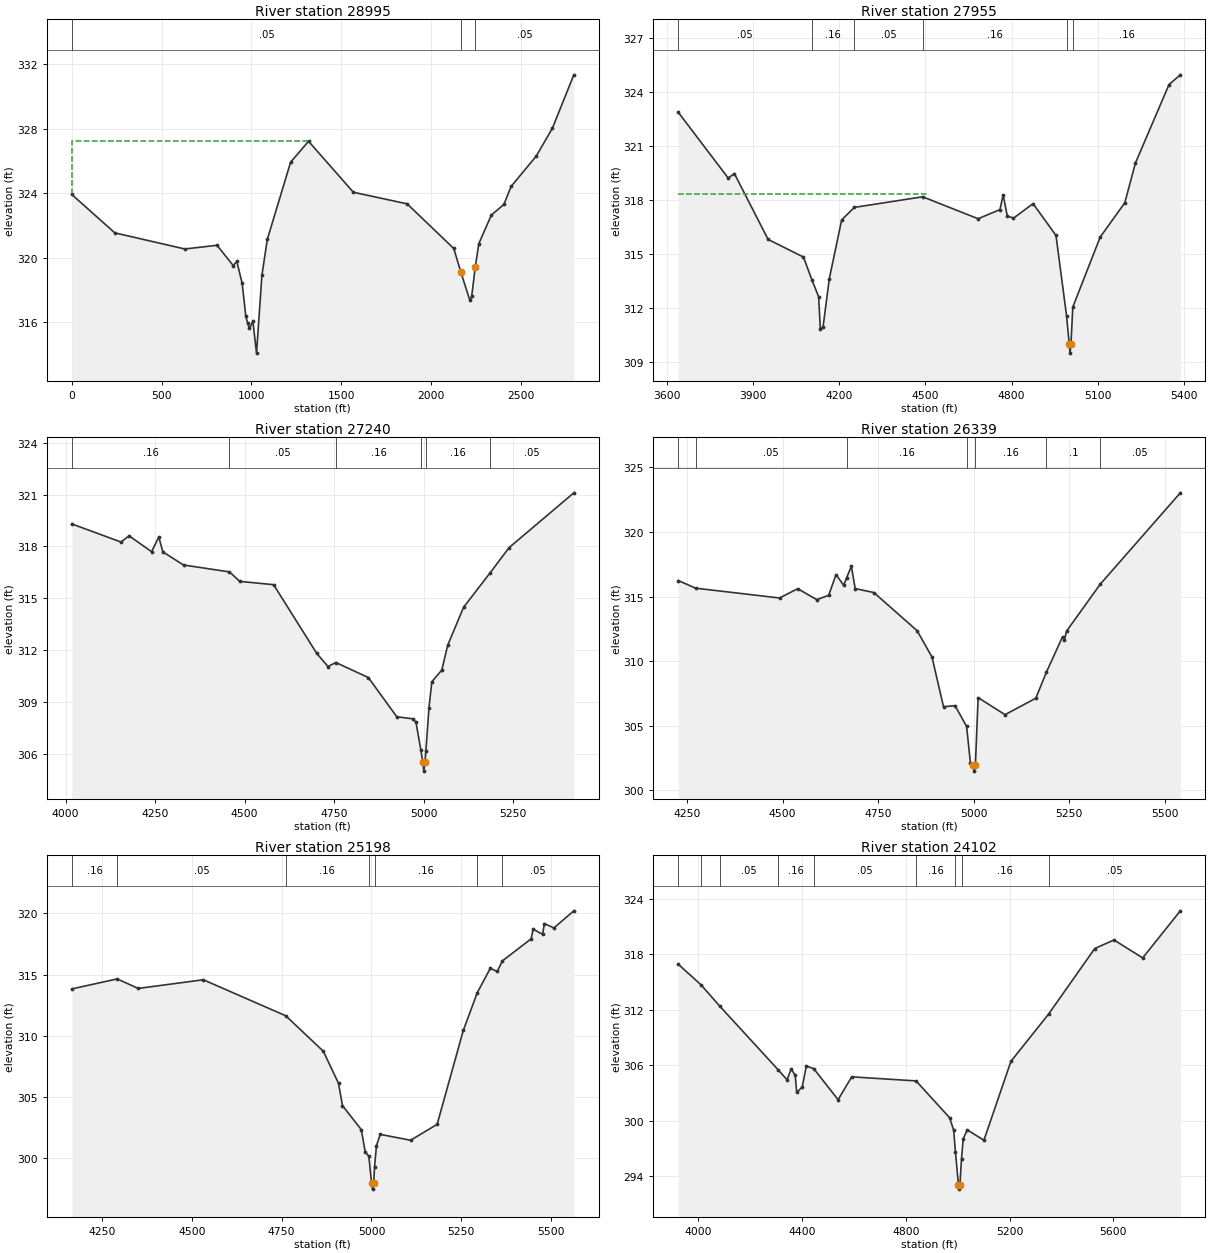
Type RM Length L Ch R = 1 ,28995   ,1040,1040,1040
BEGIN DESCRIPTION:
NAVASOTA RIVER TRIBUTARY 2.1 29.0
END DESCRIPTION:
XS GIS Cut Line= 3
     3573509.752    10321481.258      3573959.08      10320139.1
      3574742.94     10319029.72
#Sta/Elev= 30
       0 323.919239.7978321.5422629.4693320.5458809.3177320.7719899.2419319.5172
 919.225319.7797949.1998318.4153969.1829316.4069979.1745315.9702989.1661315.6231
1009.149316.05841029.132314.09821059.107 318.9091089.082321.13371218.972325.9155
1318.888 327.2111568.578324.05581868.113323.3387 2127.71320.57722167.648319.1034
2217.571 317.3612227.555 317.6132247.524319.42172267.493320.88122337.385322.6454
2407.276323.30552447.214324.41442586.997326.29172676.858328.01322796.672331.3254
#Mann= 3 , 0 , 0
       0     .05       02167.648     .07       02247.524     .05       0
#XS Ineff= 2 , 0
         1317.61  327.22
Permanent Ineff=
       F       F
Bank Sta=2167.648,2247.524
XS Rating Curve= 0 ,0
Exp/Cntr=0.3,0.1

Type RM Length L Ch R = 1 ,27955   ,715,715,715
BEGIN DESCRIPTION:
NAVASOTA RIVER TRIBUTARY 2.1 28.0
END DESCRIPTION:
XS GIS Cut Line= 3
      3574318.46     10321175.55      3574884.11      10320213.5
      3575206.95     10319672.53
#Sta/Elev= 30
  3640.5  322.87  3814.3  319.21  3835.8  319.46    3953   315.8    4076  314.82
  4105.4  313.55  4128.8  312.61  4134.6  310.83  4143.9  310.91  4165.9  313.62
  4208.8  316.88  4252.7  317.58  4490.4  318.17  4683.4  316.95  4759.4  317.46
  4770.3  318.28  4784.8  317.11  4806.2  316.98  4874.4  317.79  4954.2  316.02
  4991.2  311.52  5000.2  309.98    5003  309.48  5006.2  309.98  5012.6  312.04
  5107.9  315.93  5193.5  317.84  5230.5  320.05  5347.3  324.41  5386.5  324.95
#Mann= 6 ,-1 , 0
  3640.5     .05       0  4105.4     .16       0  4252.7     .05       0
  4490.4     .16       0  4991.2     .07       0  5012.6     .16       0
#XS Ineff= 2 , 0
         4503.07  318.32
Permanent Ineff=
       F       F
Bank Sta=5000.2,5006.2
XS Rating Curve= 0 ,0
Exp/Cntr=0.3,0.1

Type RM Length L Ch R = 1 ,27240   ,901,901,901
BEGIN DESCRIPTION:
NAVASOTA RIVER TRIBUTARY 2.1 27.0
END DESCRIPTION:
XS GIS Cut Line= 3
      3575137.16     10321182.04      3575372.75       10320484.
      3575677.62     10319891.68
#Sta/Elev= 30
  4017.1   319.3  4154.7  318.25  4177.2  318.61  4240.1  317.69  4260.3  318.54
  4271.6  317.68  4329.3  316.92  4457.8  316.52  4486.6  315.97    4581  315.78
  4701.6   311.8    4733  311.04    4755  311.27  4845.8   310.4  4925.2  308.13
  4970.2  308.01  4978.8  307.82  4992.7  306.18    4998  305.48  5000.7  304.98
    5004  305.48  5006.6  306.15  5015.2  308.65  5023.2  310.16    5051  310.83
  5067.5  312.27  5111.9  314.47  5186.6  316.48  5239.3  317.93    5420   321.1
#Mann= 6 ,-1 , 0
  4017.1     .16       0  4457.8     .05       0    4755     .16       0
  4992.7     .07       0  5006.6     .16       0  5186.6     .05       0
Bank Sta=4998,5004
XS Rating Curve= 0 ,0
Exp/Cntr=0.3,0.1

Type RM Length L Ch R = 1 ,26339   ,1141,1141,1141
BEGIN DESCRIPTION:
NAVASOTA RIVER TRIBUTARY 2.1 26.0
END DESCRIPTION:
XS GIS Cut Line= 3
       3575896.3     10321243.13      3575939.93     10320693.42
      3576018.33      10319935.5
#Sta/Elev= 30
  4227.1  316.24  4272.5  315.65  4492.2  314.89  4539.6  315.61  4589.7  314.76
  4620.6   315.1  4639.9   316.7  4659.9  315.87  4667.4  316.45    4680  317.34
    4690  315.62    4739  315.31    4852  312.36  4890.9  310.32  4921.1  306.47
  4951.2  306.56  4981.4  304.95  4991.4  302.15  4998.5  301.99  5001.2  301.49
  5004.5  301.99  5011.6  307.18  5081.9  305.86  5162.4  307.13  5190.2  309.15
  5232.4  311.89  5237.4  311.65  5242.8  312.32  5330.8  315.95  5540.5  323.03
#Mann= 7 ,-1 , 0
  4227.1     .16       0  4272.5     .05       0  4667.4     .16       0
  4981.4     .07       0  5004.5     .16       0  5190.2      .1       0
  5330.8     .05       0
Bank Sta=4998.5,5004.5
XS Rating Curve= 0 ,0
Exp/Cntr=0.3,0.1

Type RM Length L Ch R = 1 ,25198   ,1096,1096,1096
BEGIN DESCRIPTION:
NAVASOTA RIVER TRIBUTARY 2.1 25.0
END DESCRIPTION:
XS GIS Cut Line= 3
      3576297.68     10321417.68      3576454.75     10320920.29
      3576733.97     10320091.35
#Sta/Elev= 30
  4166.5  313.82  4292.9  314.64  4351.1  313.86  4532.3  314.57  4761.8  311.62
  4866.1  308.72  4908.3   306.1  4919.4  304.27  4971.6  302.31  4982.4  300.51
  4992.7  300.12  5000.2  297.94    5003  297.44  5006.2  297.94  5008.6  299.29
  5013.9     301  5024.3  301.92  5108.8  301.44  5182.6  302.74  5255.3  310.42
  5294.4  313.52  5330.4   315.5  5349.8  315.25  5363.9  316.11  5444.2  317.92
  5449.5  318.71  5475.7  318.29    5481  319.17  5507.2  318.81  5562.8  320.21
#Mann= 7 ,-1 , 0
  4166.5     .16       0  4292.9     .05       0  4761.8     .16       0
  4992.7     .07       0  5008.6     .16       0  5294.4      .1       0
  5363.9     .05       0
Bank Sta=5000.2,5006.2
XS Rating Curve= 0 ,0
Exp/Cntr=0.3,0.1

Type RM Length L Ch R = 1 ,24102   ,1007,1007,1007
BEGIN DESCRIPTION:
NAVASOTA RIVER TRIBUTARY 2.1 24.0
END DESCRIPTION:
XS GIS Cut Line= 3
      3576463.45     10322019.78      3577109.18     10320937.74
      3577336.07     10320300.71
#Sta/Elev= 30
  3921.9  316.93  4009.4  314.71  4082.8  312.37  4306.7  305.53  4341.8  304.42
  4357.4  305.61    4373  304.91  4378.8  303.06  4400.2  303.66  4415.8  305.92
  4444.7  305.63  4538.4  302.28  4590.9  304.75  4839.1  304.31  4968.5  300.33
    4984     299  4991.1   296.6  5002.4  293.11  5005.2  292.61  5008.4  293.11
  5014.4  295.92    5021  298.06  5036.6  299.02  5100.8   297.9    5205  306.43
  5350.1  311.53  5528.1  318.62  5602.4  319.55  5713.1  317.61  5858.2   322.7
#Mann= 9 ,-1 , 0
  3921.9     .05       0  4009.4     .16       0  4082.8     .05       0
  4306.7     .16       0  4444.7     .05       0  4839.1     .16       0
  4991.1     .07       0  5014.4     .16       0  5350.1     .05       0
Bank Sta=5002.4,5008.4
XS Rating Curve= 0 ,0
Exp/Cntr=0.3,0.1

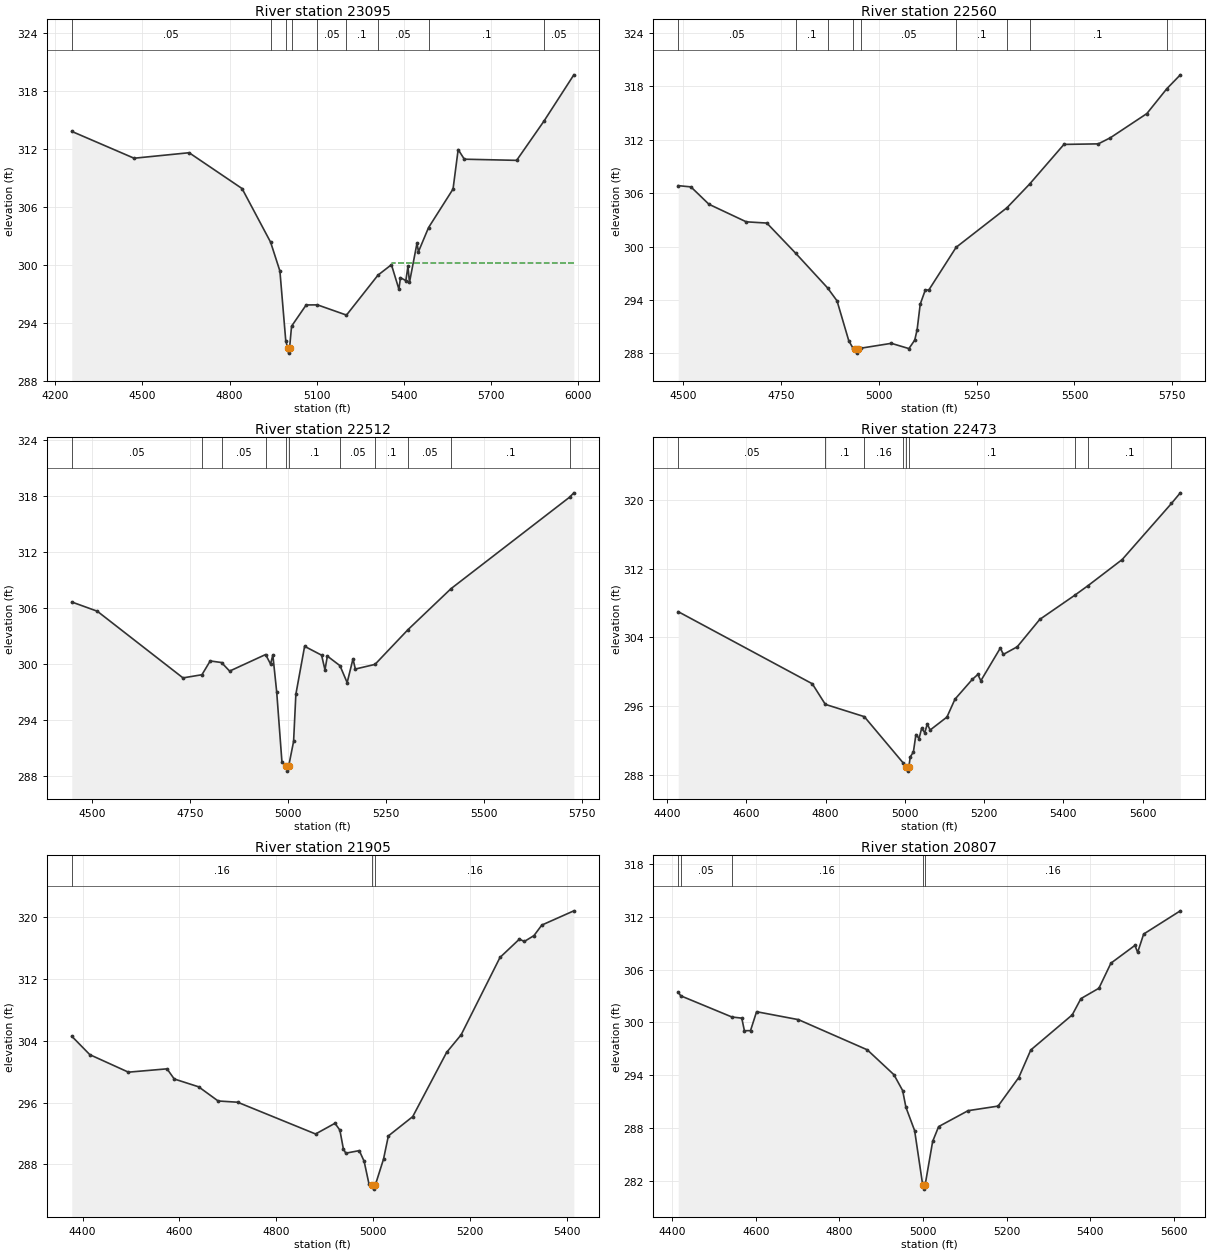
Type RM Length L Ch R = 1 ,23095   ,535,535,535
BEGIN DESCRIPTION:
NAVASOTA RIVER TRIBUTARY 2.1 23.0
END DESCRIPTION:
XS GIS Cut Line= 4
      3577405.85      10321967.4      3577667.63     10321513.65
       3577695.5     10321117.35       3577429.5     10320355.79
#Sta/Elev= 30
  4257.2  313.82  4471.7  311.04    4661  311.61  4843.2   307.9  4941.5  302.34
  4973.5  299.35  4993.6  292.13  5000.6  291.35  5003.4  290.85  5006.6  291.35
  5013.6  293.64  5063.8  295.84  5102.7  295.85  5202.6  294.79    5311  298.93
  5357.3  300.01    5383  297.47  5388.3  298.67  5406.8  298.36  5414.1  299.84
  5419.4  298.18  5445.1  302.22  5450.4  301.37  5484.9  303.85  5569.3  307.85
  5586.9  311.94  5608.1  310.94  5788.1  310.82  5882.5   314.9    5985  319.68
#Mann= 9 ,-1 , 0
  4257.2     .05       0  4941.5      .1       0  4993.6     .07       0
  5013.6      .1       0  5102.7     .05       0  5202.6      .1       0
    5311     .05       0  5484.9      .1       0  5882.5     .05       0
#XS Ineff= 2 , 0
                         5357.73          300.14
Permanent Ineff=
       F       F
Bank Sta=5000.6,5006.6
XS Rating Curve= 0 ,0
Exp/Cntr=0.3,0.1

Type RM Length L Ch R = 1 ,22560   ,48,48,48
BEGIN DESCRIPTION:
Mapping XS 1f10aeeb
END DESCRIPTION:
XS GIS Cut Line= 6
      3577926.15     10321483.76      3577978.24     10321111.33
      3577986.05     10321009.77      3577939.18     10320926.44
      3577626.68     10320712.89       3577517.3      10320400.4
#Sta/Elev= 30
  4487.4  306.84  4519.8   306.7  4565.9  304.75  4661.2  302.78  4713.8  302.64
  4787.6  299.25  4868.9  295.37  4893.2  293.91  4923.3  289.42  4933.3  288.66
  4940.4  288.54  4943.1  288.04  4946.4  288.54  4953.4  288.59    5032  289.14
  5076.9  288.55  5091.8   289.5  5097.9  290.67  5105.8  293.53  5118.9  295.14
  5127.7  295.12  5197.6  299.92  5327.5  304.36  5385.2  307.01  5473.1  311.47
  5560.9  311.53  5591.9  312.22    5685  314.93  5735.8  317.71  5770.5  319.28
#Mann= 9 ,-1 , 0
  4487.4     .05       0  4787.6      .1       0  4868.9     .05       0
  4933.3     .07       0  4953.4     .05       0  5197.6      .1       0
  5327.5     .05       0  5385.2      .1       0  5735.8     .05       0
Bank Sta=4940.4,4946.4
XS Rating Curve= 0 ,0
Exp/Cntr=0.3,0.1

Type RM Length L Ch R = 1 ,22512   ,39,39,39
BEGIN DESCRIPTION:
Mapping XS 3df319de
END DESCRIPTION:
XS GIS Cut Line= 6
       3577972.6     10321486.41      3578002.98     10321132.69
      3578031.19      10320993.8      3577976.94     10320900.48
       3577644.9     10320666.11      3577568.94     10320409.98
#Sta/Elev= 30
  4449.1  306.64  4514.1  305.65  4732.7  298.49    4781  298.83  4802.1  300.31
  4830.9  300.14  4851.6  299.22  4943.4     301    4956  299.97  4961.8  300.95
  4971.7  296.95    4985  289.46    4996  288.98  4998.8  288.48    5002  288.98
  5014.7  291.67  5020.5  296.73  5042.8  301.88  5086.1  300.93  5094.7  299.35
  5100.8  300.83    5133   299.8  5151.3  297.98  5166.1  300.52  5172.2  299.44
  5222.3  299.94  5306.4  303.67  5416.1  308.07  5718.4  317.89  5729.3  318.36
#Mann= 11 ,-1 , 0
  4449.1     .05       0    4781      .1       0  4830.9     .05       0
  4943.4      .1       0    4996     .07       0    5002      .1       0
    5133     .05       0  5222.3      .1       0  5306.4     .05       0
  5416.1      .1       0  5718.4     .05       0
Bank Sta=4996,5002
XS Rating Curve= 0 ,0
Exp/Cntr=0.3,0.1

Type RM Length L Ch R = 1 ,22473   ,568,568,568
BEGIN DESCRIPTION:
Mapping XS 79b6c709
END DESCRIPTION:
XS GIS Cut Line= 5
       3578019.9     10321478.56      3578066.78     10320962.89
      3577949.59     10320819.67      3577691.78     10320587.89
      3577645.15     10320375.48
#Sta/Elev= 30
    4428  306.99  4766.3  298.59  4799.2  296.19  4897.5  294.76  4995.4  289.38
    5004  288.91  5006.7  288.41    5010  288.91  5013.5  290.07  5021.4  290.63
  5027.8  292.67  5035.7  292.21  5042.2  293.39  5050.1  292.89  5056.5   293.9
  5063.7   293.2  5106.1  294.71  5126.3  296.79  5169.9  299.09  5184.1  299.68
  5191.6  298.94  5240.9  302.76  5248.4  302.01  5283.5   302.9  5340.3  306.09
  5428.5   308.9  5462.3  310.03  5548.2  313.06  5672.6   319.6    5695  320.84
#Mann= 9 ,-1 , 0
    4428     .05       0  4799.2      .1       0  4897.5     .16       0
  4995.4      .1       0    5004     .07       0    5010      .1       0
  5428.5     .05       0  5462.3      .1       0  5672.6     .05       0
Bank Sta=5004,5010
XS Rating Curve= 0 ,0
Exp/Cntr=0.3,0.1

Type RM Length L Ch R = 1 ,21905   ,1098,1098,1098
BEGIN DESCRIPTION:
NAVASOTA RIVER TRIBUTARY 2.1 22.0
END DESCRIPTION:
XS GIS Cut Line= 3
      3578292.11     10321341.62      3578348.25     10320902.84
      3578391.87      10320309.5
#Sta/Elev= 30
  4377.5  304.56  4414.8  302.18  4494.5  299.92  4574.3  300.35  4589.2  299.04
  4639.6  298.03  4679.9   296.2  4720.2  296.04  4881.2  291.94  4921.3  293.32
  4931.4  292.44  4938.5  290.06  4943.5  289.46  4971.5  289.79  4981.5  288.42
  4991.5   285.5  4998.5  285.32  5001.3  284.82  5004.5  285.32  5021.6   288.7
  5031.6  291.69  5081.9  294.18  5151.9  302.47    5182  304.75  5262.2  314.73
  5302.4   317.1  5312.4  316.79  5332.4  317.55  5348.6  318.91  5414.8  320.75
#Mann= 3 ,-1 , 0
  4377.5     .16       0  4998.5     .07       0  5004.5     .16       0
Bank Sta=4998.5,5004.5
XS Rating Curve= 0 ,0
Exp/Cntr=0.3,0.1

Type RM Length L Ch R = 1 ,20807   ,850,850,850
BEGIN DESCRIPTION:
NAVASOTA RIVER TRIBUTARY 2.1 21.0
END DESCRIPTION:
XS GIS Cut Line= 3
      3578344.45     10321616.17      3578644.46     10321216.16
      3579185.94     10320771.94
#Sta/Elev= 30
  4414.7  303.44  4420.6  303.03    4543  300.62  4566.6  300.49  4572.9  299.06
  4587.5  299.07    4602  301.22    4702  300.32  4866.6  296.89  4930.4  294.06
  4951.2  292.26  4959.1  290.35  4979.9   287.7  4999.1  281.55  5001.9  281.05
  5005.1  281.55    5023  286.48  5037.3  288.16  5107.7  289.97  5179.4  290.49
  5228.9  293.74  5257.6  296.87  5356.7  300.86  5377.5  302.71  5420.5  303.89
  5449.2  306.74  5506.6  308.76  5513.1  307.97  5527.5  310.05  5615.1  312.69
#Mann= 5 ,-1 , 0
  4414.7     .16       0  4420.6     .05       0    4543     .16       0
  4999.1     .07       0  5005.1     .16       0
Bank Sta=4999.1,5005.1
XS Rating Curve= 0 ,0
Exp/Cntr=0.3,0.1

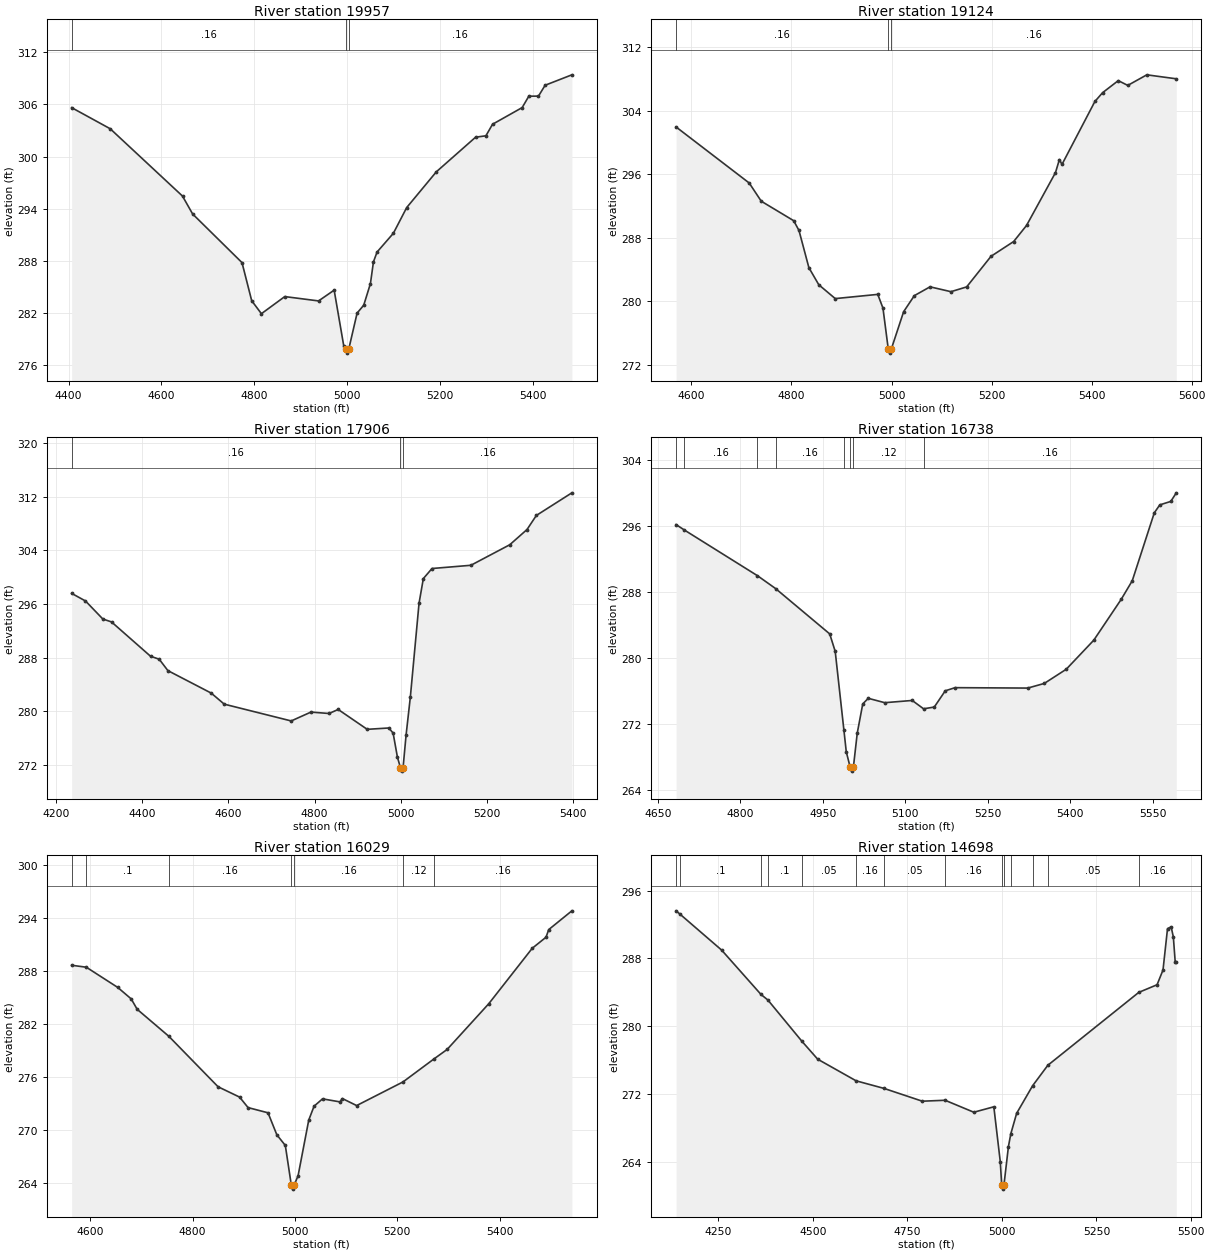
Type RM Length L Ch R = 1 ,19957   ,833,833,833
BEGIN DESCRIPTION:
NAVASOTA RIVER TRIBUTARY 2.1 19.0
END DESCRIPTION:
XS GIS Cut Line= 3
      3578724.66     10321881.25      3579124.65     10321531.25
      3579473.84     10321112.29
#Sta/Elev= 30
  4406.7  305.63  4489.7   303.2  4645.3  295.45  4667.1  293.39  4773.4  287.79
  4794.3   283.4  4815.2  281.91  4865.5  283.88  4938.2  283.38  4971.8  284.62
  4992.6  278.16  4997.4  277.87  5000.1  277.37  5003.4  277.87  5021.2  281.98
  5035.5  282.89  5049.9  285.38  5056.4  287.88  5064.2  289.01  5099.3  291.17
    5128  294.13  5191.7  298.24  5276.3  302.23  5298.5  302.39  5312.8  303.72
  5376.6  305.64  5390.9  306.95  5411.7  306.96    5426  308.21  5483.6  309.41
#Mann= 3 ,-1 , 0
  4406.7     .16       0  4997.4     .07       0  5003.4     .16       0
Bank Sta=4997.4,5003.4
XS Rating Curve= 0 ,0
Exp/Cntr=0.3,0.1

Type RM Length L Ch R = 1 ,19124   ,1218,1218,1218
BEGIN DESCRIPTION:
NAVASOTA RIVER TRIBUTARY 2.1 18.0
END DESCRIPTION:
XS GIS Cut Line= 3
      3579431.73     10322209.75      3579531.72     10321959.79
      3579744.36     10321260.63
#Sta/Elev= 30
  4569.3  301.95  4715.5   294.9  4739.6  292.61  4804.4  290.16    4815  288.93
  4834.8  284.25  4854.6   282.1  4887.5  280.36  4972.5  280.89  4982.9  279.16
  4993.5     274  4996.3   273.5  4999.5     274  5024.2  278.71  5045.6  280.73
    5077  281.84  5118.8  281.23  5150.2  281.83  5198.9  285.68  5244.2  287.54
  5269.9  289.56  5327.8  296.21  5335.6  297.85  5340.8  297.24  5406.6  305.16
  5421.9  306.26  5453.3  307.78  5472.3  307.18  5510.4  308.51  5569.3  308.01
#Mann= 3 ,-1 , 0
  4569.3     .16       0  4993.5     .07       0  4999.5     .16       0
Bank Sta=4993.5,4999.5
XS Rating Curve= 0 ,0
Exp/Cntr=0.3,0.1

Type RM Length L Ch R = 1 ,17906   ,1168,1168,1168
BEGIN DESCRIPTION:
NAVASOTA RIVER TRIBUTARY 2.1 16.0
END DESCRIPTION:
XS GIS Cut Line= 3
      3580177.34     10322503.55      3580249.71     10321891.04
       3580294.1     10321347.82
#Sta/Elev= 30
  4235.9  297.59    4268  296.46  4308.3  293.77  4328.4  293.34  4419.1  288.22
  4439.2  287.78  4459.4  286.08    4560  282.73  4590.3  281.08  4745.8  278.58
  4791.6   279.9  4833.7  279.69  4854.9  280.29  4922.3  277.33  4972.5  277.53
  4982.5  276.77  4992.5  273.18  4999.6   271.6  5002.3   271.1  5005.6   271.6
  5012.6  276.47  5022.6   282.2  5042.7  296.12  5052.7   299.8  5072.8   301.3
  5163.1  301.78  5253.4  304.84  5293.5  307.11  5315.2  309.21  5397.7  312.58
#Mann= 3 ,-1 , 0
  4235.9     .16       0  4999.6     .07       0  5005.6     .16       0
Bank Sta=4999.6,5005.6
XS Rating Curve= 0 ,0
Exp/Cntr=0.3,0.1

Type RM Length L Ch R = 1 ,16738   ,709,709,709
BEGIN DESCRIPTION:
NAVASOTA RIVER TRIBUTARY 2.1 14.0
END DESCRIPTION:
XS GIS Cut Line= 3
      3580763.57     10322601.09      3580763.57     10322451.06
      3580792.11     10321691.63
#Sta/Elev= 30
  4682.9  296.17  4698.1  295.51    4831  289.98  4863.8  288.43  4962.4  282.93
  4972.4  280.81  4988.2  271.28  4992.5  268.66  4999.5  266.81  5002.2  266.31
  5005.5  266.81  5012.5  270.92  5022.5  274.45  5032.5  275.13  5062.5   274.6
  5112.5  274.87  5133.1  273.86  5152.6  274.07  5172.6  276.04  5190.5  276.42
  5322.7  276.37  5352.7  276.93  5392.7  278.65  5442.8  282.17  5492.8  287.13
  5512.8  289.37  5552.9   297.6  5562.9  298.56  5582.9  298.98  5592.9  300.02
#Mann= 8 ,-1 , 0
  4682.9     .05       0  4698.1     .16       0    4831     .05       0
  4863.8     .16       0  4988.2     .12       0  4999.5     .07       0
  5005.5     .12       0  5133.1     .16       0
Bank Sta=4999.5,5005.5
XS Rating Curve= 0 ,0
Exp/Cntr=0.3,0.1

Type RM Length L Ch R = 1 ,16029   ,1331,1331,1331
BEGIN DESCRIPTION:
NAVASOTA RIVER TRIBUTARY 2.1 13.0
END DESCRIPTION:
XS GIS Cut Line= 3
      3581265.19     10322493.07      3581165.18     10322193.04
      3580983.43     10321557.27
#Sta/Elev= 30
  4563.7  288.63  4592.3  288.41  4653.7  286.12    4680  284.82  4691.7  283.64
  4753.4  280.59  4849.8  274.86  4891.8  273.69  4908.4   272.5  4947.4  271.91
  4964.6  269.42  4981.2  268.21  4992.8  263.76  4995.6  263.26  4998.8  263.76
  5006.2  264.79    5027  271.09  5037.4  272.66  5053.9  273.49  5087.7  273.15
  5092.9  273.52  5120.6  272.73  5211.2  275.41  5271.8  278.02  5297.4  279.09
  5378.9  284.28  5463.8  290.56  5490.7  291.81  5495.9  292.67  5541.2   294.8
#Mann= 7 ,-1 , 0
  4563.7     .05       0  4592.3      .1       0  4753.4     .16       0
  4992.8     .07       0  4998.8     .16       0  5211.2     .12       0
  5271.8     .16       0
Bank Sta=4992.8,4998.8
XS Rating Curve= 0 ,0
Exp/Cntr=0.3,0.1

Type RM Length L Ch R = 1 ,14698   ,1121,1121,1121
BEGIN DESCRIPTION:
NAVASOTA RIVER TRIBUTARY 2.1 11.0
END DESCRIPTION:
XS GIS Cut Line= 3
       3581842.1     10322541.64      3581452.86     10321614.88
      3581292.11     10321341.65
#Sta/Elev= 30
  4138.9  293.61  4148.4  293.25  4259.4  288.98  4363.3  283.76  4381.6   283.1
  4471.7  278.23  4513.2  276.13  4614.8  273.58  4688.3  272.69  4789.7  271.18
    4850  271.29  4925.9  269.88  4978.8  270.52  4995.8  264.07  4999.6  261.32
  5002.3  260.82  5005.6  261.32  5017.4  265.84  5023.7  267.34  5039.1  269.75
  5081.3     273  5121.5  275.41  5361.9     284  5410.3   284.9    5426  286.64
  5437.9  291.51  5447.5  291.72  5453.3  290.54  5458.2  287.61  5461.1  287.61
#Mann= 14 ,-1 , 0
  4138.9     .05       0  4148.4      .1       0  4363.3     .05       0
  4381.6      .1       0  4471.7     .05       0  4614.8     .16       0
  4688.3     .05       0    4850     .16       0  4999.6     .07       0
  5005.6     .16       0  5023.7     .05       0  5081.3     .16       0
  5121.5     .05       0  5361.9     .16       0
Bank Sta=4999.6,5005.6
XS Rating Curve= 0 ,0
Exp/Cntr=0.3,0.1

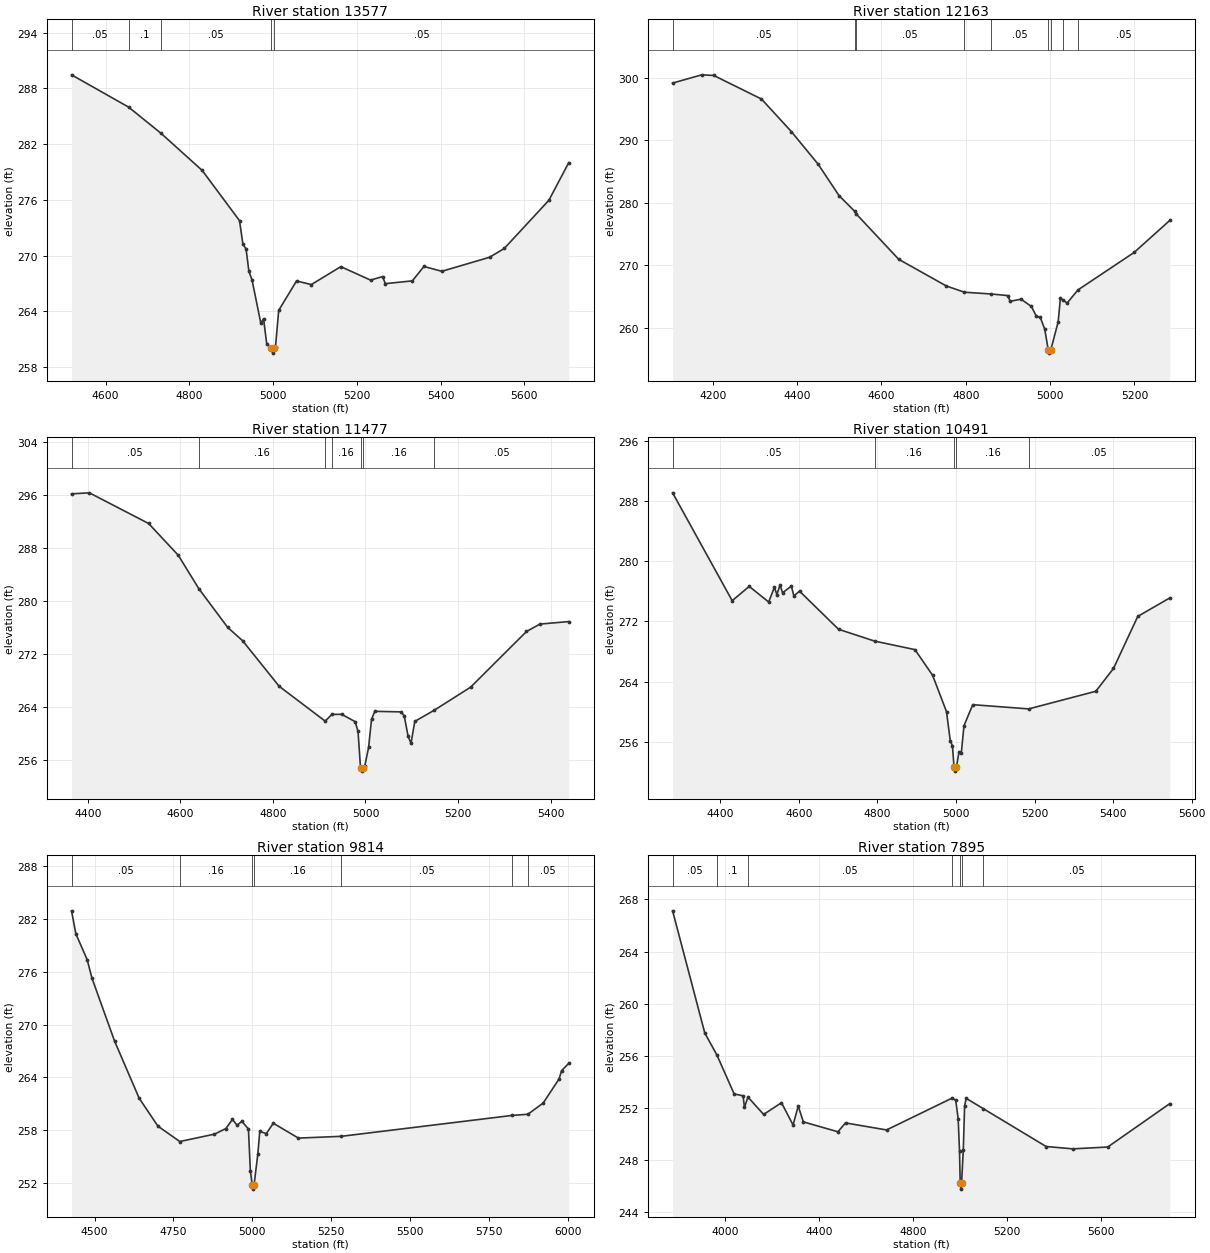
Type RM Length L Ch R = 1 ,13577   ,1414,1414,1414
BEGIN DESCRIPTION:
NAVASOTA RIVER TRIBUTARY 2.1 10.0
END DESCRIPTION:
XS GIS Cut Line= 3
      3582327.22     10322089.58      3582159.45     10321723.11
      3581646.83     10321129.98
#Sta/Elev= 30
  4518.7  289.47  4654.8     286    4732  283.19  4830.6  279.18  4919.8  273.77
  4927.8  271.26  4935.5  270.71  4942.1  268.33  4949.7  267.38  4970.6  262.74
  4977.2   263.2  4984.8  260.48  4996.1  260.01  4998.8  259.51  5002.1  260.01
  5005.7   260.2  5013.3  264.11  5055.9  267.28  5091.2  266.89  5161.6  268.82
  5232.7  267.37  5261.3  267.75  5267.9  266.99  5332.5  267.29    5360  268.84
  5402.8  268.32  5516.8  269.83  5551.9  270.78  5658.3  275.96  5705.7  280.01
#Mann= 5 ,-1 , 0
  4518.7     .05       0  4654.8      .1       0    4732     .05       0
  4996.1    .035       0  5002.1     .05       0
Bank Sta=4996.1,5002.1
XS Rating Curve= 0 ,0
Exp/Cntr=0.3,0.1

Type RM Length L Ch R = 1 ,12163   ,686,686,686
BEGIN DESCRIPTION:
NAVASOTA RIVER TRIBUTARY 2.1 8.0
END DESCRIPTION:
XS GIS Cut Line= 3
      3582850.72     10321531.07       3582352.6     10321051.34
      3581892.08     10320891.63
#Sta/Elev= 30
  4104.9  299.15  4174.1  300.47  4202.4  300.37  4315.6   296.6  4386.4  291.39
  4450.1  286.16  4499.6  281.13  4536.5  278.64  4539.4  278.27  4641.1  270.94
  4754.3  266.66    4797  265.67  4859.9  265.39    4900  265.13  4905.2  264.21
  4931.1  264.56  4955.8  263.39  4967.5  261.81  4976.9  261.63  4987.5  259.73
  4995.7  256.42  4998.4  255.92  5001.7  256.42  5019.2  260.93  5024.5  264.67
  5030.6  264.44  5040.4  263.93  5066.2  266.04  5199.2  272.03  5283.9  277.16
#Mann= 9 ,-1 , 0
  4104.9     .05       0  4536.5     .16       0  4539.4     .05       0
    4797     .16       0  4859.9     .05       0  4995.7    .035       0
  5001.7     .05       0  5030.6     .16       0  5066.2     .05       0
Bank Sta=4995.7,5001.7
XS Rating Curve= 0 ,0
Exp/Cntr=0.3,0.1

Type RM Length L Ch R = 1 ,11477   ,986,986,986
BEGIN DESCRIPTION:
NAVASOTA RIVER TRIBUTARY 2.1 6.0
END DESCRIPTION:
XS GIS Cut Line= 3
      3583086.34     10320937.74       3582763.5     10320833.03
      3582178.89     10320388.04
#Sta/Elev= 30
    4365  296.23  4403.6  296.38  4531.5  291.74  4595.5  286.94  4640.4  281.83
  4702.5     276  4734.5     274  4813.5   267.1    4913  261.82  4927.5  262.84
  4948.7  262.85  4977.7  261.74    4984  260.26  4989.3  254.75    4992  254.25
  4995.3  254.75  4998.6  255.06  5006.8  257.84  5013.1   262.1  5020.3   263.3
  5077.5  263.22  5083.8  262.59  5092.1  259.53  5098.4  258.46  5106.6  261.78
  5148.9  263.48  5227.2  266.96  5347.9  275.39  5376.9  276.51  5439.1  276.89
#Mann= 7 ,-1 , 0
    4365     .05       0  4640.4     .16       0    4913     .05       0
  4927.5     .16       0  4989.3     .07       0  4995.3     .16       0
  5148.9     .05       0
Bank Sta=4989.3,4995.3
XS Rating Curve= 0 ,0
Exp/Cntr=0.3,0.1

Type RM Length L Ch R = 1 ,10491   ,677,677,677
BEGIN DESCRIPTION:
NAVASOTA RIVER TRIBUTARY 2.1 4.0
END DESCRIPTION:
XS GIS Cut Line= 3
      3583409.19     10320658.51       3582944.5     10320288.06
      3582342.06     10319991.62
#Sta/Elev= 30
  4278.6  289.06  4430.3  274.74  4473.6  276.64  4523.2  274.57  4537.7  276.52
    4544  275.56  4552.1  276.83  4558.5  275.79  4580.9  276.68  4587.3  275.38
  4601.7  276.01    4701  270.95  4792.8  269.38  4895.5  268.25  4940.4  264.85
  4975.9  260.01  4985.4  256.17    4991  255.48  4995.1  252.62  4997.9  252.12
  5001.1  252.62  5007.8  254.71  5013.4  254.46  5020.4  258.15  5042.7  260.94
  5185.1  260.38    5356  262.72    5401  265.75  5462.8  272.66  5544.3  275.11
#Mann= 5 ,-1 , 0
  4278.6     .05       0  4792.8     .16       0  4995.1     .07       0
  5001.1     .16       0  5185.1     .05       0
Bank Sta=4995.1,5001.1
XS Rating Curve= 0 ,0
Exp/Cntr=0.3,0.1

Type RM Length L Ch R = 1 ,9814    ,1919,1919,1919
BEGIN DESCRIPTION:
NAVASOTA RIVER TRIBUTARY 2.1 3.0
END DESCRIPTION:
XS GIS Cut Line= 3
      3583574.97     10320387.98      3583112.53     10319716.13
      3582362.08     10319829.57
#Sta/Elev= 30
  4427.1  282.94  4440.9  280.32  4476.8  277.38  4491.7   275.3  4563.4  268.14
  4641.2  261.65  4700.7  258.47    4770  256.72  4879.9  257.56  4915.8  258.19
  4936.7  259.23  4951.6  258.57  4966.5  259.02  4987.4  258.14  4993.5   253.4
  4999.3  251.81  5002.1  251.31  5005.3  251.81  5017.2  255.33  5023.3  257.86
  5044.3  257.63  5066.1   258.8  5145.7  257.11    5281  257.31  5823.3  259.69
  5872.5  259.82  5920.8  261.09  5971.3  263.84  5979.2  264.78  6001.7   265.6
#Mann= 7 ,-1 , 0
  4427.1     .05       0    4770     .16       0  4999.3     .07       0
  5005.3     .16       0    5281     .05       0  5823.3      .1       0
  5872.5     .05       0
Bank Sta=4999.3,5005.3
XS Rating Curve= 0 ,0
Exp/Cntr=0.3,0.1

Type RM Length L Ch R = 1 ,7895    ,0,0,0
BEGIN DESCRIPTION:
NAVASOTA RIVER TRIBUTARY 2.1 1.0
END DESCRIPTION:
XS GIS Cut Line= 3
      3583912.73     10320678.68      3584662.73     10319303.68
      3584292.94     10318897.43
#Sta/Elev= 30
  3777.3  267.13    3914  257.77    3966  256.06  4039.3  253.08  4077.3  252.94
    4083  252.05    4098  252.84  4164.6  251.51  4240.6  252.41  4289.9   250.7
  4311.8  252.15  4333.6  250.94  4480.7  250.18    4513  250.86  4687.7  250.32
  4966.3  252.76  4981.9   252.6  4992.4  251.19  4998.1  248.74  5001.1  246.28
  5003.9  245.78  5007.1  246.28  5014.2  248.77  5019.9  252.19  5026.9  252.74
  5099.7  251.95  5366.7  249.05  5480.2  248.87  5628.8  249.01  5892.9  252.34
#Mann= 7 ,-1 , 0
  3777.3     .05       0    3966      .1       0    4098     .05       0
  4966.3      .1       0  5001.1     .07       0  5007.1      .1       0
  5099.7     .05       0
Bank Sta=5001.1,5007.1
XS Rating Curve= 0 ,0
Exp/Cntr=0.3,0.1

Chan Stop Cuts=-1
Use User Specified Reach Order=0
Composite Channel Slope=5