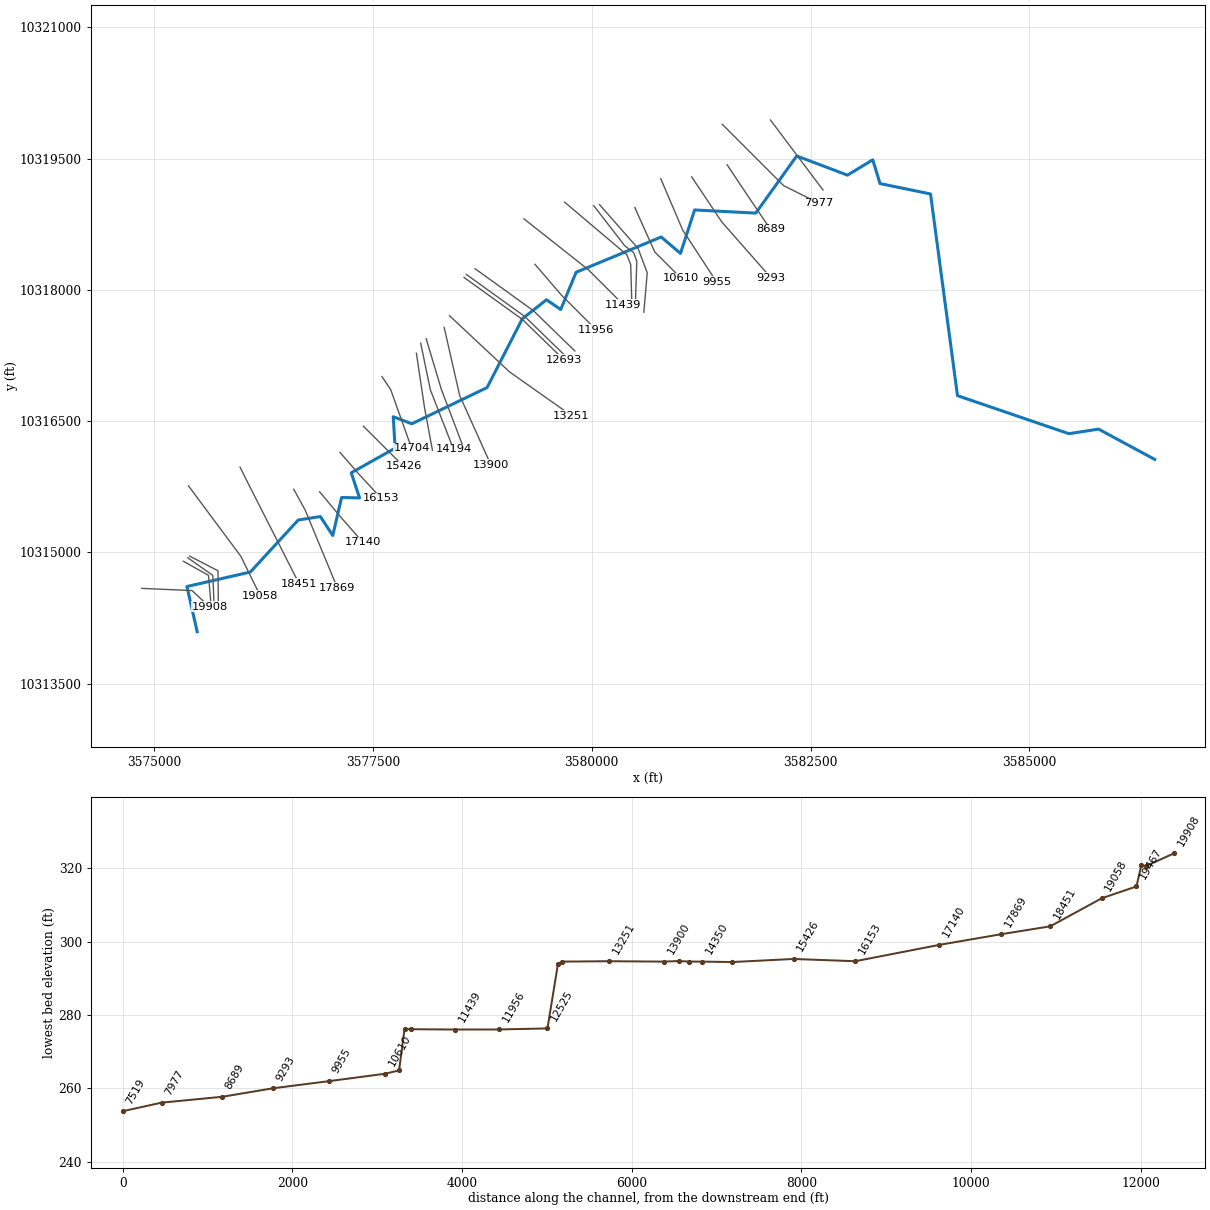
--- NAVASOTA RIVER TRIBUTARY 2 2.prj (project) ---

Proj Title=NAVASOTA RIVER TRIBUTARY 2 2 Base Level Engineering
Current Plan=p01
Default Exp/Contr=0.3,0.1
English Units
Geom File=g01
Flow File=f01
Plan File=p01
Y Axis Title=Elevation
X Axis Title(PF)=Main Channel Distance
X Axis Title(XS)=Station
BEGIN DESCRIPTION:
NAVASOTA RIVER TRIBUTARY 2 2
END DESCRIPTION:
DSS Export Rating Curves= 0
DSS Export Rating Curve Sorted= 0
DSS Export Volume Flow Curves= 0
DXF OffsetX= 0
DXF OffsetY= 0
DXF ScaleX= 1
DXF ScaleY= 10

--- NAVASOTA RIVER TRIBUTARY 2 2.p01 (plan) ---

Plan Title=Multiple Run
Short Identifier=Multiple
Geom File=g01
Flow File=f01
Subcritical Flow
K Sum by GR= 0
Std Step Tol= 0.01
Critical Tol= 0.01
Num of Std Step Trials= 20
Max Error Tol= 0.3
Flow Tol Ratio= 0.001
Split Flow NTrial= 30
Split Flow Tol= 0.02
Split Flow Ratio= 0.02
Log Output Level= 0
Friction Slope Method= 1
Unsteady Friction Slope Method= 2
Unsteady Bridges Friction Slope Method= 1
Parabolic Critical Depth
Global Vel Dist=  1 , 1 , 1
Global Log Level= 0
CheckData=True
Encroach Param= -1, 0, 0, 0
BEGIN DESCRIPTION:
Multiple Run
END DESCRIPTION:

--- NAVASOTA RIVER TRIBUTARY 2 2.f01 (steady flow) ---

Flow Title=Multiple
Number of Profiles=7
Profile Names=10-year,25-year,50-year,1pct_min,100-year,1pct_plu,500-year
River Rch & RM= NAVASOTA RIVER T,Reach-1,19908
     631     854    1037     923    1249    1689    1813
River Rch & RM= NAVASOTA RIVER T,Reach-1,12525
    1030    1427    1759    1586    2144    2900    3196
Boundary for River Rch & Prof#=NAVASOTA RIVER T,Reach-1,1
Up Type=0
Dn Type=3
Dn Slope=0.005
Boundary for River Rch & Prof#=NAVASOTA RIVER T,Reach-1,2
Up Type=0
Dn Type=3
Dn Slope=0.005
Boundary for River Rch & Prof#=NAVASOTA RIVER T,Reach-1,3
Up Type=0
Dn Type=3
Dn Slope=0.005
Boundary for River Rch & Prof#=NAVASOTA RIVER T,Reach-1,4
Up Type=0
Dn Type=3
Dn Slope=0.005
Boundary for River Rch & Prof#=NAVASOTA RIVER T,Reach-1,5
Up Type=0
Dn Type=3
Dn Slope=0.005
Boundary for River Rch & Prof#=NAVASOTA RIVER T,Reach-1,6
Up Type=0
Dn Type=3
Dn Slope=0.005
Boundary for River Rch & Prof#=NAVASOTA RIVER T,Reach-1,7
Up Type=0
Dn Type=3
Dn Slope=0.005

--- NAVASOTA RIVER TRIBUTARY 2 2.g01 (geometry) ---

Geom Title=Existing Conditions
Program Version=4.10

River Reach=NAVASOTA RIVER T,Reach-1
Reach XY= 30
        3575493.     10314092.62      3575375.99     10314609.03
      3576100.51     10314774.74      3576647.72     10315369.55
      3576900.43     10315408.51      3577041.87     10315191.99
       3577142.8     10315626.97      3577347.66     10315621.76
      3577253.04     10315909.09      3577753.91     10316190.34
      3577733.08     10316549.72      3577945.58     10316469.42
      3578804.52     10316883.19      3579207.39     10317669.67
      3579483.25     10317887.09       3579646.1     10317775.57
      3579821.35     10318200.74      3580793.45     10318604.59
      3581014.18     10318416.85      3581175.53     10318913.53
      3581874.43     10318877.39       3582341.9     10319530.81
      3582921.53     10319311.47      3583210.62      10319486.9
      3583293.57     10319214.87      3583870.41     10319096.58
      3584178.45     10316790.86      3585450.62     10316356.11
       3585790.6     10316408.36      3586432.11     10316061.64

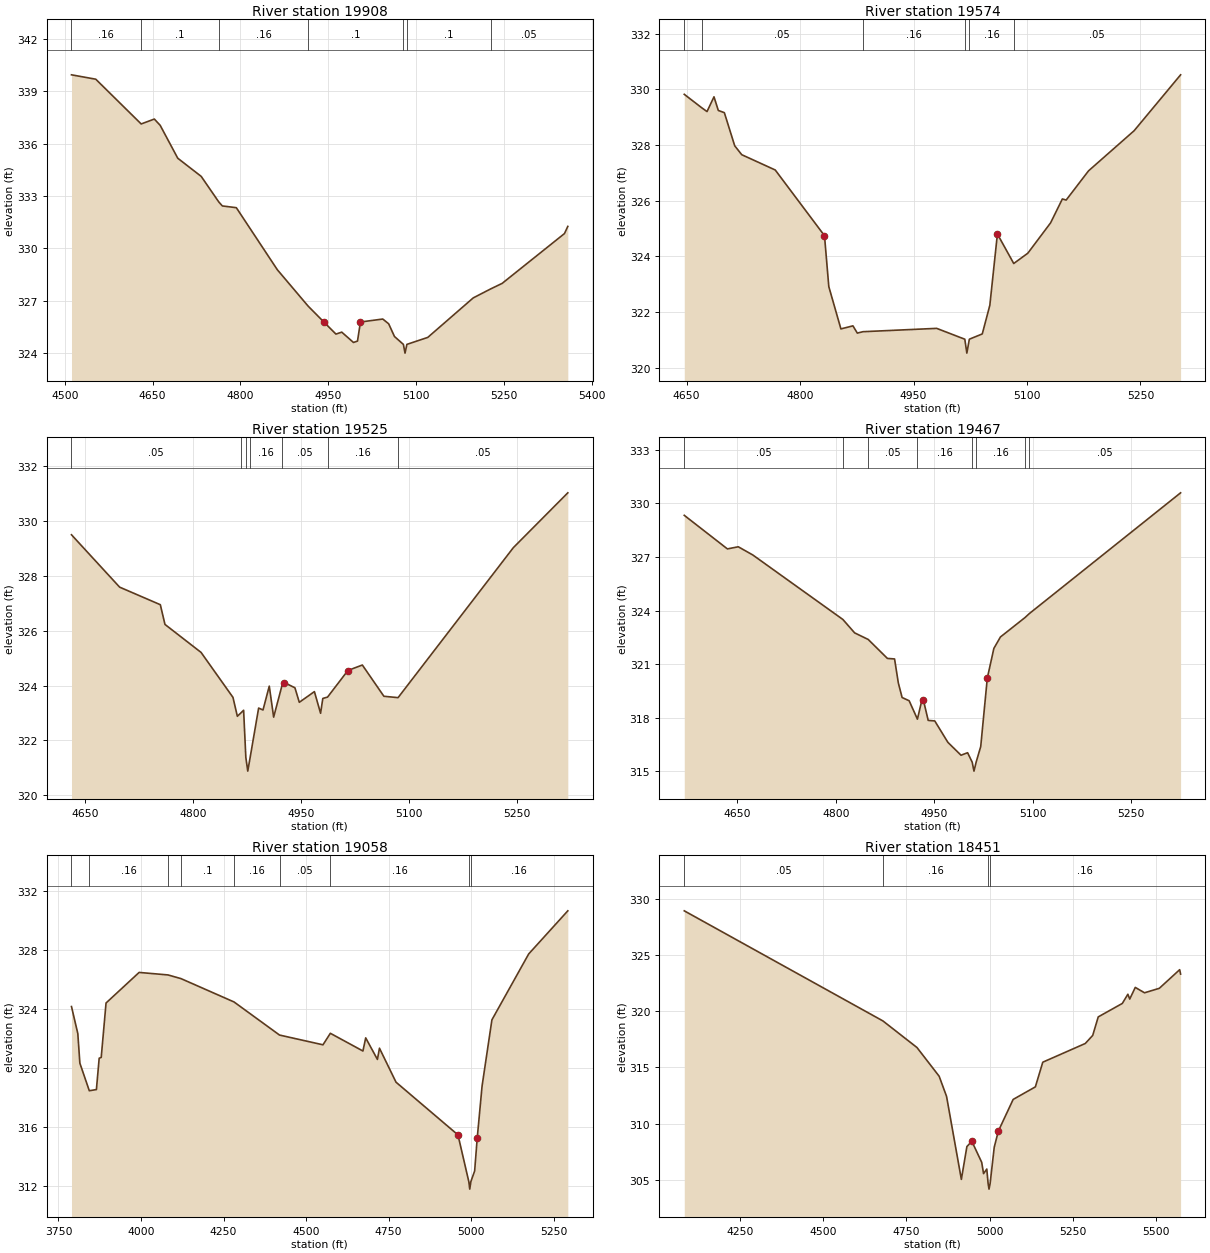
Type RM Length L Ch R = 1 ,19908   ,334,334,334
BEGIN DESCRIPTION:
NAVASOTA RIVER TRIBUTARY 2.2 32.0
END DESCRIPTION:
XS GIS Cut Line= 3
      3574860.64     10314587.81      3575433.58     10314563.07
      3575634.85     10314376.09
#Sta/Elev= 30
  4511.3  339.93  4552.8  339.68  4630.4  337.12  4652.9   337.4  4662.9  337.04
  4692.9  335.16    4733  334.12    4763  332.66  4769.1  332.43    4793  332.33
  4863.1  328.78  4915.7   326.7  4943.2  325.77  4963.2   325.1  4973.2  325.21
  4993.2  324.62  5000.1   324.7  5005.1  325.79  5043.3  325.96  5053.3  325.69
  5063.3  324.96  5078.5  324.51  5081.3  324.01  5084.5  324.51  5120.2  324.91
  5197.9  327.17  5227.5  327.68  5247.3     328  5353.8  330.85  5359.5  331.26
#Mann= 7 ,-1 , 0
  4511.3     .16       0  4630.4      .1       0    4763     .16       0
  4915.7      .1       0  5078.5     .07       0  5084.5      .1       0
  5227.5     .05       0
Bank Sta=4943.2,5005.1
XS Rating Curve= 0 ,0
Exp/Cntr=0.3,0.1

Type RM Length L Ch R = 1 ,19574   ,49,49,49
BEGIN DESCRIPTION:
Mapping XS 0d2bb834
END DESCRIPTION:
XS GIS Cut Line= 3
      3575335.85     10314897.55      3575622.29     10314736.97
       3575650.5     10314410.37
#Sta/Elev= 30
  4646.9  329.82  4669.8  329.34    4677   329.2  4686.2  329.73  4691.9  329.24
  4699.9  329.16  4713.6  327.97  4722.9  327.65  4767.2   327.1  4832.3  324.74
    4838  322.91    4854  321.39  4869.9   321.5  4875.7  321.24  4883.2  321.29
  4980.6  321.41  5017.8  321.02  5020.5  320.52  5023.8  321.02  5040.9  321.21
  5050.9  322.24  5060.9   324.8  5082.5  323.74  5101.1  324.11  5131.2   325.2
  5146.8  326.06  5151.8  326.02  5181.4  327.07  5241.6  328.51  5303.1  330.52
#Mann= 6 ,-1 , 0
  4646.9      .1       0  4669.8     .05       0  4883.2     .16       0
  5017.8     .07       0  5023.8     .16       0  5082.5     .05       0
Bank Sta=4832.3,5060.9
XS Rating Curve= 0 ,0
Exp/Cntr=0.3,0.1

Type RM Length L Ch R = 1 ,19525   ,58,58,58
BEGIN DESCRIPTION:
NAVASOTA RIVER TRIBUTARY 2.2 31.0
END DESCRIPTION:
XS GIS Cut Line= 3
      3575385.78     10314937.68       3575672.2     10314735.88
      3575686.28     10314395.95
#Sta/Elev= 30
  4630.6   329.5  4697.6  327.59  4754.2  326.95  4760.7  326.23  4810.9  325.21
  4855.3  323.57  4861.4  322.88  4866.2     323  4870.1   323.1  4873.2  321.38
  4875.9  320.88  4879.2  321.38    4891  323.18  4897.1  323.11  4905.8  323.98
  4911.9  322.85  4923.2  323.97  4926.7  324.11  4941.5  323.92  4947.6  323.39
  4968.6  323.78  4977.2  322.99  4980.3  323.53  4986.9  323.58  5015.2  324.55
  5035.3  324.75  5065.3  323.61    5085  323.56  5245.4  329.03  5321.2  331.03
#Mann= 7 ,-1 , 0
  4630.6     .05       0  4866.2     .16       0  4873.2     .07       0
  4879.2     .16       0  4923.2     .05       0  4986.9     .16       0
    5085     .05       0
Bank Sta=4926.7,5015.2
XS Rating Curve= 0 ,0
Exp/Cntr=0.3,0.1

Type RM Length L Ch R = 1 ,19467   ,409,409,409
BEGIN DESCRIPTION:
Mapping XS a8e6f17c
END DESCRIPTION:
XS GIS Cut Line= 3
      3575407.44     10314956.16       3575730.8     10314789.05
      3575735.14     10314397.36
#Sta/Elev= 30
  4569.3  329.33    4635  327.45  4651.5  327.57  4673.7  327.11  4810.8   323.5
  4828.7  322.75  4849.4  322.38  4878.6  321.32  4889.5  321.29  4895.2  319.95
    4901  319.13  4911.7  318.95  4924.3  317.92  4931.2     319  4933.3     319
  4940.7  317.85  4950.7  317.82  4970.7  316.62  4990.7   315.9  5000.7  316.04
  5007.7  315.51  5010.4  315.01  5013.7  315.51  5020.7  316.39  5030.7  320.22
  5040.7  321.88  5050.7  322.52  5088.2  323.61  5094.7  323.83    5325  330.59
#Mann= 8 ,-1 , 0
  4569.3     .05       0  4810.8      .1       0  4849.4     .05       0
  4924.3     .16       0  5007.7     .07       0  5013.7     .16       0
  5088.2      .1       0  5094.7     .05       0
Bank Sta=4933.3,5030.7
XS Rating Curve= 0 ,0
Exp/Cntr=0.3,0.1

Type RM Length L Ch R = 1 ,19058   ,607,607,607
BEGIN DESCRIPTION:
NAVASOTA RIVER TRIBUTARY 2.2 30.0
END DESCRIPTION:
XS GIS Cut Line= 3
      3575393.88     10315759.67      3575991.14     10314955.67
      3576212.51      10314505.3
#Sta/Elev= 30
  3789.4  324.15  3808.6  322.32  3814.8  320.32  3843.4  318.45  3864.9  318.53
  3873.3  320.65  3879.5  320.71  3894.1  324.39  3994.3  326.46  4081.8  326.29
  4121.2  326.04  4281.8  324.46  4419.6  322.22  4551.2  321.56  4573.5  322.34
  4672.2  321.14  4680.6  322.03  4716.1  320.57  4722.3  321.33  4772.4  319.03
  4960.1  315.46    4993  312.29  4995.8  311.79    4999  312.29  5010.6  313.02
  5018.3  315.22  5033.1  318.77  5062.9  323.25  5174.3  327.71  5292.8  330.63
#Mann= 9 ,-1 , 0
  3789.4      .1       0  3843.4     .16       0  4081.8     .05       0
  4121.2      .1       0  4281.8     .16       0  4419.6     .05       0
  4573.5     .16       0    4993     .07       0    4999     .16       0
Bank Sta=4960.1,5018.3
XS Rating Curve= 0 ,0
Exp/Cntr=0.3,0.1

Type RM Length L Ch R = 1 ,18451   ,582,582,582
BEGIN DESCRIPTION:
NAVASOTA RIVER TRIBUTARY 2.2 28.0
END DESCRIPTION:
XS GIS Cut Line= 3
      3575982.68     10315973.59      3576082.69     10315773.57
      3576657.22     10314641.89
#Sta/Elev= 30
  4081.9  328.97  4679.4  319.15  4781.8  316.78  4848.5  314.22  4870.8  312.42
  4915.3  305.02    4932  307.95  4946.9  308.41  4976.5  306.54  4982.1  305.53
  4991.8  305.94  4995.8  304.65  4998.5  304.15  5001.8  304.65  5014.2  307.89
  5026.6  309.33  5071.1  312.15  5137.9  313.27  5160.2  315.47  5288.1  317.14
  5310.4  317.86    5327  319.51  5399.4  320.71  5416.1  321.53  5421.7   321.1
  5438.4  322.14  5466.2  321.66  5510.7  322.06  5571.9  323.72  5574.7  323.33
#Mann= 4 ,-1 , 0
  4081.9     .05       0  4679.4     .16       0  4995.8     .07       0
  5001.8     .16       0
Bank Sta=4946.9,5026.6
XS Rating Curve= 0 ,0
Exp/Cntr=0.3,0.1

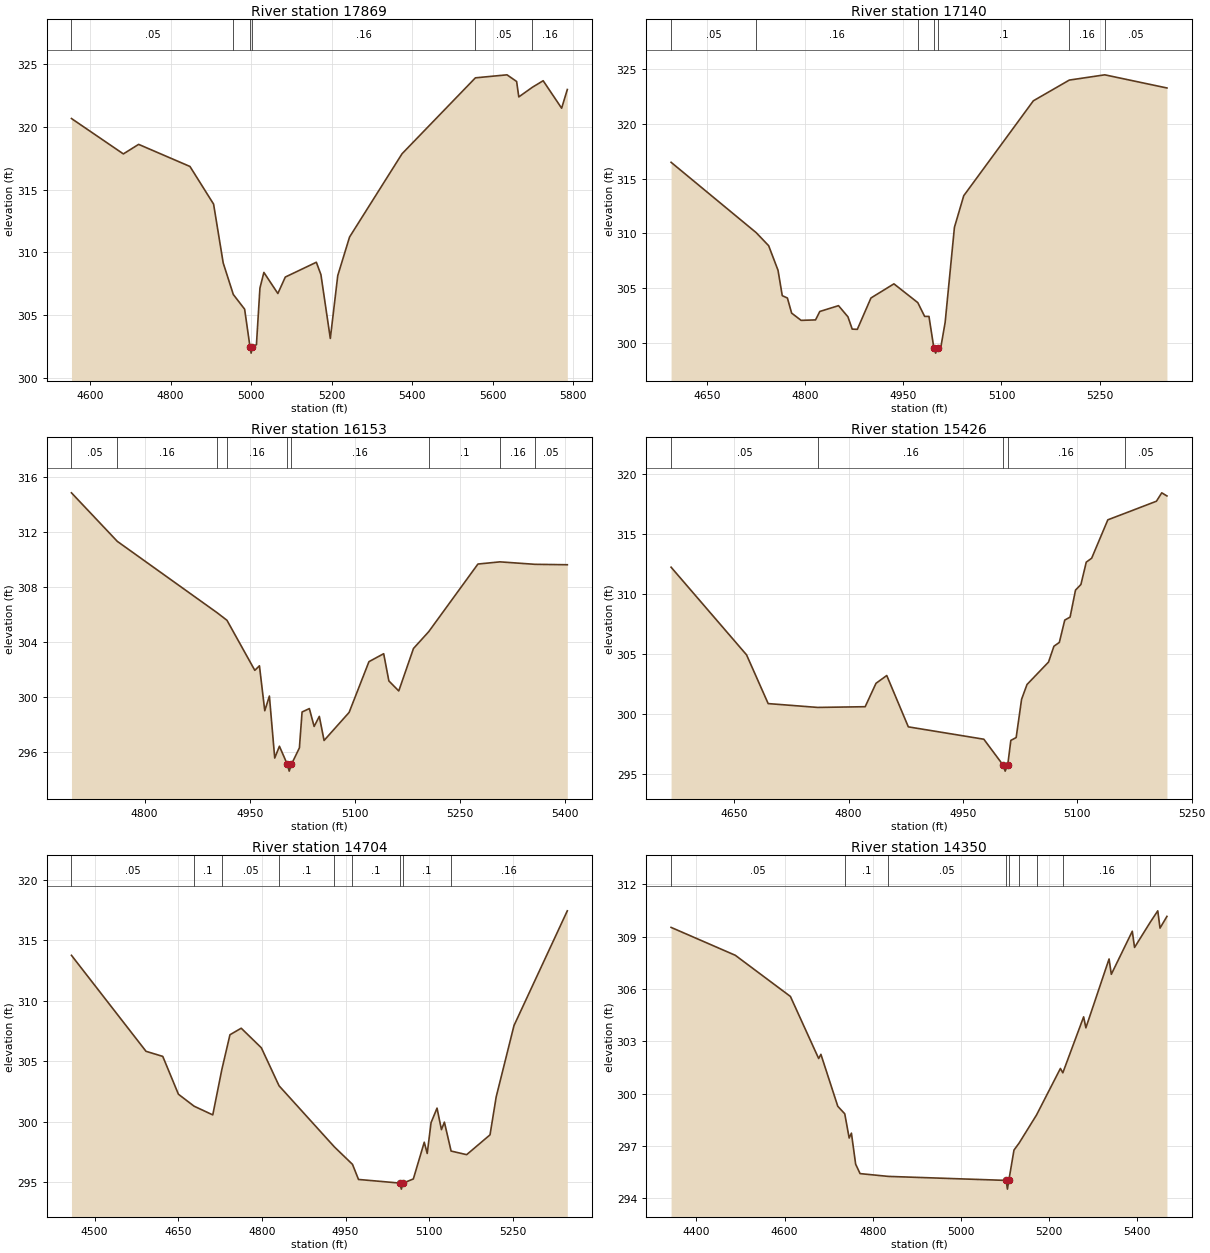
Type RM Length L Ch R = 1 ,17869   ,729,729,729
BEGIN DESCRIPTION:
NAVASOTA RIVER TRIBUTARY 2.2 27.0
END DESCRIPTION:
XS GIS Cut Line= 3
      3576596.05     10315721.35      3576726.21       10315484.
      3577093.57      10314596.2
#Sta/Elev= 30
  4553.6  320.67  4682.5  317.85  4720.4  318.61  4847.9  316.85  4906.6  313.85
  4930.5  309.16  4955.6  306.65  4983.7  305.48    4997  302.48  4999.8  301.98
    5003  302.48    5013  302.65  5021.7  307.16  5031.5  308.41  5066.2  306.73
  5084.7  308.04  5161.8  309.22  5173.2  308.23  5196.5  303.15    5215  308.16
  5244.3  311.23  5374.6  317.86  5556.8  323.91  5635.3  324.15  5659.2  323.62
  5664.6  322.39  5698.4  323.16  5725.1  323.68    5771  321.49  5785.1  322.98
#Mann= 6 ,-1 , 0
  4553.6     .05       0  4955.6     .16       0    4997     .07       0
    5003     .16       0  5556.8     .05       0  5698.4     .16       0
Bank Sta=4997,5003
XS Rating Curve= 0 ,0
Exp/Cntr=0.3,0.1

Type RM Length L Ch R = 1 ,17140   ,987,987,987
BEGIN DESCRIPTION:
NAVASOTA RIVER TRIBUTARY 2.2 26.0
END DESCRIPTION:
XS GIS Cut Line= 3
      3576892.14      10315691.6      3577142.11     10315391.64
      3577384.63     10315116.55
#Sta/Elev= 30
  4595.5  316.49  4725.5  310.07  4744.5  308.88  4758.8  306.64  4765.3  304.32
  4773.1  304.11  4779.6  302.73    4794  302.07  4816.1  302.11  4822.6  302.88
  4851.2  303.41  4865.6  302.39  4872.1  301.27  4879.9  301.25  4900.7  304.11
  4935.8   305.4  4972.2  303.69  4982.7  302.43  4989.3  302.43  4996.7  299.58
  4999.5  299.08  5002.7  299.58  5007.3  299.58    5014  301.88  5028.2  310.56
  5042.4  313.44  5148.7   322.1  5203.6  323.99  5257.8  324.47  5352.7  323.27
#Mann= 7 ,-1 , 0
  4595.5     .05       0  4725.5     .16       0  4972.2      .1       0
  4996.7     .07       0  5002.7      .1       0  5203.6     .16       0
  5257.8     .05       0
Bank Sta=4996.7,5002.7
XS Rating Curve= 0 ,0
Exp/Cntr=0.3,0.1

Type RM Length L Ch R = 1 ,16153   ,727,727,727
BEGIN DESCRIPTION:
NAVASOTA RIVER TRIBUTARY 2.2 24.0
END DESCRIPTION:
XS GIS Cut Line= 3
      3577124.36     10316142.51      3577342.11     10315891.64
      3577596.93     10315616.51
#Sta/Elev= 30
  4695.6  314.88    4761  311.35  4903.1  306.17  4917.4  305.61  4957.1  301.97
  4963.7   302.3  4971.3  299.03  4977.9   300.1  4985.5  295.59  4992.2  296.45
  5003.4  295.14  5006.2  294.64  5009.4  295.14  5020.7  296.33  5024.5  298.94
  5034.9  299.19  5041.7  297.89  5049.1  298.62  5055.9  296.87  5091.6  298.91
  5119.9   302.6  5140.9  303.18  5148.3   301.2  5162.4  300.47  5183.4  303.56
  5205.1  304.78  5275.3   309.7  5306.7  309.86  5356.9  309.68  5402.8  309.65
#Mann= 9 ,-1 , 0
  4695.6     .05       0    4761     .16       0  4903.1     .05       0
  4917.4     .16       0  5003.4     .07       0  5009.4     .16       0
  5205.1      .1       0  5306.7     .16       0  5356.9     .05       0
Bank Sta=5003.4,5009.4
XS Rating Curve= 0 ,0
Exp/Cntr=0.3,0.1

Type RM Length L Ch R = 1 ,15426   ,722,722,722
BEGIN DESCRIPTION:
NAVASOTA RIVER TRIBUTARY 2.2 23.0
END DESCRIPTION:
XS GIS Cut Line= 3
      3577392.12     10316441.63      3577692.11     10316141.64
      3577851.75     10315981.73
#Sta/Elev= 30
  4567.3  312.25  4666.3  304.94  4694.6  300.88  4759.5  300.56  4821.8  300.62
    4836  302.57  4850.1  303.22  4878.4  298.94  4977.4  297.91  5002.7  295.75
  5005.4  295.25  5008.7  295.75  5012.8  297.81  5019.8  298.05  5026.9  301.24
    5034  302.47  5062.2  304.34  5069.3  305.66  5076.4  305.98  5083.5  307.84
  5090.5  308.09  5097.6  310.34  5104.7  310.81  5111.7  312.67  5118.8     313
    5140   316.2  5162.3  316.74  5203.7  317.75  5210.7  318.45  5217.5  318.19
#Mann= 5 ,-1 , 0
  4567.3     .05       0  4759.5     .16       0  5002.7     .07       0
  5008.7     .16       0  5162.3     .05       0
Bank Sta=5002.7,5008.7
XS Rating Curve= 0 ,0
Exp/Cntr=0.3,0.1

Type RM Length L Ch R = 1 ,14704   ,354,354,354
BEGIN DESCRIPTION:
NAVASOTA RIVER TRIBUTARY 2.2 22.0
END DESCRIPTION:
XS GIS Cut Line= 3
      3577603.82     10317009.17      3577703.82     10316859.18
      3577942.12     10316191.61
#Sta/Elev= 30
  4458.6  313.76  4592.3  305.82  4622.3   305.4  4650.4  302.27  4678.5  301.28
    4712  300.56    4728  304.26  4742.8  307.19    4763  307.73  4799.1  306.11
  4830.8  302.97  4930.1  297.91  4962.5  296.47  4973.3  295.22  5047.4  294.92
  5050.1  294.42  5053.4  294.92  5071.6  295.26  5091.2   298.3  5096.5  297.37
  5103.4  299.92  5114.1  301.12    5122  299.34  5127.3  299.96  5139.3  297.57
  5167.2  297.27  5209.1  298.91  5220.2  302.06  5252.1  307.95  5347.7  317.44
#Mann= 9 ,-1 , 0
  4458.6     .05       0  4678.5      .1       0    4728     .05       0
  4830.8      .1       0  4930.1     .05       0  4962.5      .1       0
  5047.4     .07       0  5053.4      .1       0  5139.3     .16       0
Bank Sta=5047.4,5053.4
XS Rating Curve= 0 ,0
Exp/Cntr=0.3,0.1

Type RM Length L Ch R = 1 ,14350   ,156,156,156
BEGIN DESCRIPTION:
NAVASOTA RIVER TRIBUTARY 2.2 21.0
END DESCRIPTION:
XS GIS Cut Line= 3
      3577997.27     10317275.72      3578092.11     10316641.64
      3578180.92     10316166.09
#Sta/Elev= 30
  4342.4  309.54  4488.1  307.94  4613.1  305.58  4677.2  302.02  4682.3  302.26
  4720.6  299.28  4736.4  298.85  4746.4  297.46  4751.5  297.74  4761.1  295.96
  4771.2  295.42  4835.1  295.26  5102.6  295.03  5105.4  294.53  5108.6  295.03
  5120.3  296.77  5131.9  297.17  5171.4  298.78  5225.6  301.45  5231.1   301.2
  5278.3  304.41  5283.4  303.78    5336  307.73  5341.1  306.85  5388.7  309.32
  5393.8  308.39  5429.5  309.84  5446.5  310.49  5451.6   309.5  5467.3  310.17
#Mann= 9 ,-1 , 0
  4342.4     .05       0  4736.4      .1       0  4835.1     .05       0
  5102.6    .033       0  5108.6     .05       0  5131.9     .16       0
  5171.4      .1       0  5231.1     .16       0  5429.5     .05       0
Bank Sta=5102.6,5108.6
XS Rating Curve= 0 ,0
Exp/Cntr=0.3,0.1

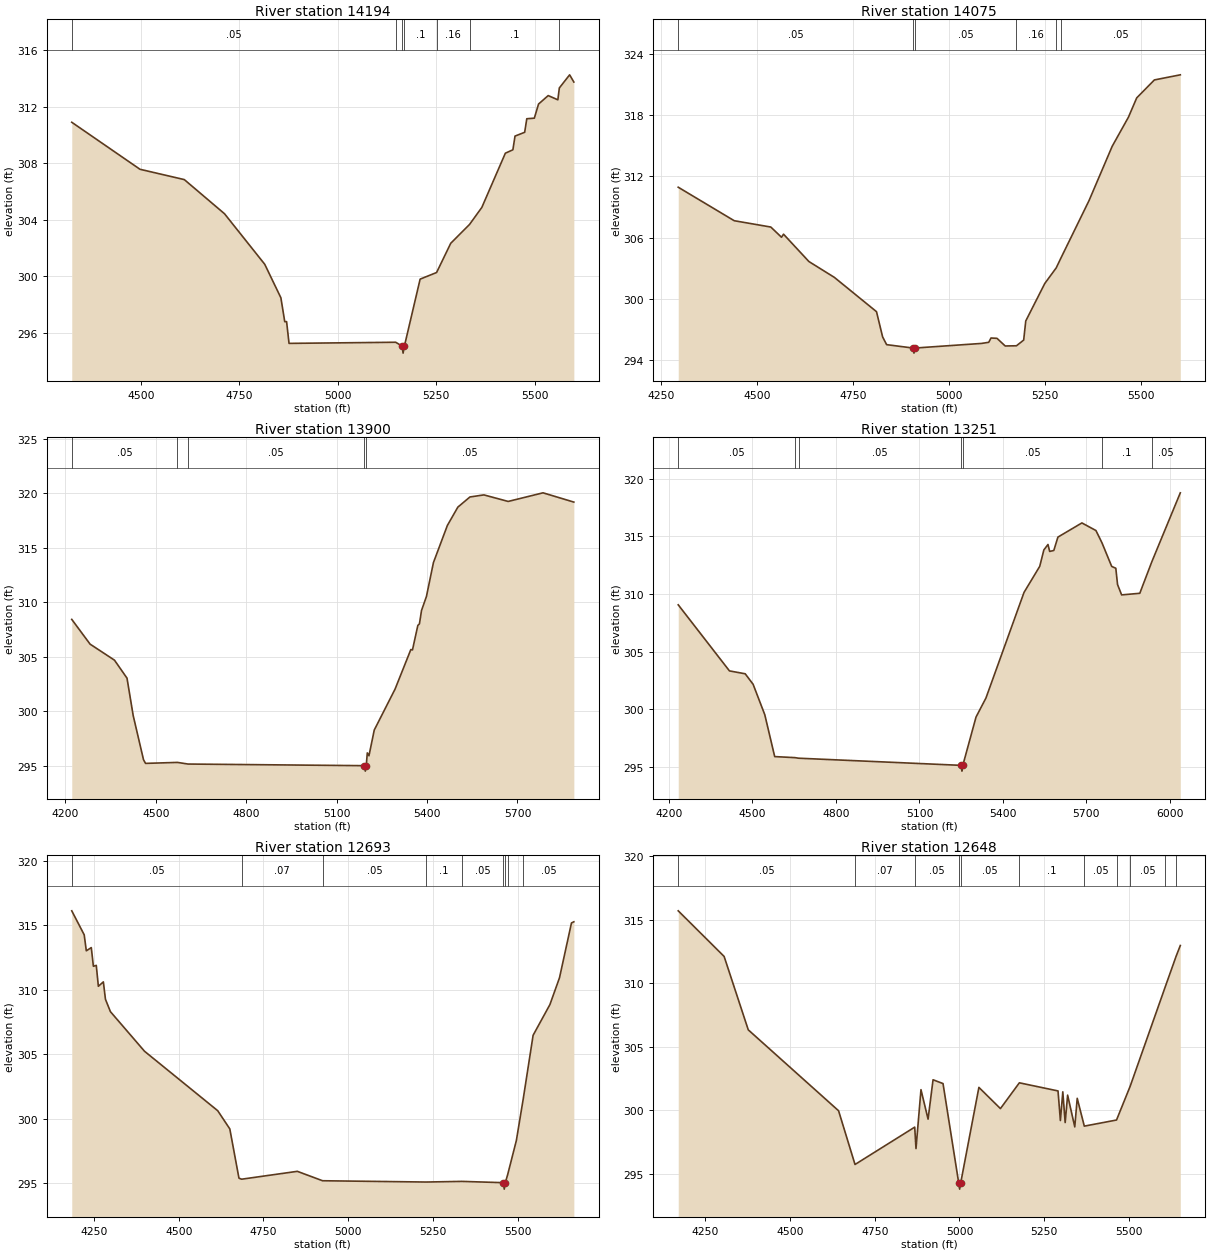
Type RM Length L Ch R = 1 ,14194   ,119,119,119
BEGIN DESCRIPTION:
Mapping XS 86dec1c3
END DESCRIPTION:
XS GIS Cut Line= 3
      3578046.15     10317391.27      3578156.82     10316857.45
      3578421.58     10316178.19
#Sta/Elev= 30
  4324.7  310.89  4497.9  307.56  4610.3  306.83  4712.4  304.41  4814.5  300.83
  4855.4  298.46  4865.2  296.77  4869.9  296.77  4876.1  295.23  5146.8  295.31
  5162.9  295.04  5165.6  294.54  5168.9  295.04  5208.8  299.78  5250.6  300.25
  5286.5  302.32  5334.1  303.65  5365.4  304.86  5425.1   308.7  5444.2  308.94
  5449.6  309.91  5474.1  310.18  5479.5  311.14  5498.6  311.18  5509.3  312.18
  5533.8  312.78  5558.3  312.48  5562.1  313.32  5588.2  314.25  5598.9  313.74
#Mann= 7 ,-1 , 0
  4324.7     .05       0  5146.8      .1       0  5162.9    .033       0
  5168.9      .1       0  5250.6     .16       0  5334.1      .1       0
  5562.1     .05       0
Bank Sta=5162.9,5168.9
XS Rating Curve= 0 ,0
Exp/Cntr=0.3,0.1

Type RM Length L Ch R = 1 ,14075   ,175,175,175
BEGIN DESCRIPTION:
Mapping XS 86a9b68f
END DESCRIPTION:
XS GIS Cut Line= 3
      3578109.07     10317441.25      3578282.69     10316861.79
      3578531.78     10316205.49
#Sta/Elev= 30
  4295.6  310.94  4441.3  307.66  4536.6  307.04  4564.4  306.04  4569.7  306.34
  4635.8  303.66    4702  302.11  4811.7  298.75  4827.6  296.28    4838  295.52
  4906.5  295.19  4909.2  294.69  4912.5  295.19    5085  295.64  5103.9  295.75
  5109.7  296.17  5125.3  296.14  5146.7  295.39    5176  295.41  5194.8  295.97
  5200.2  297.84  5249.7  301.51  5279.5  303.04  5291.3  303.97  5364.9  309.63
  5425.2  314.95  5467.6  317.81    5489  319.69    5535  321.45  5602.5  321.95
#Mann= 6 ,-1 , 0
  4295.6     .05       0  4906.5    .033       0  4912.5     .05       0
    5176     .16       0  5279.5      .1       0  5291.3     .05       0
Bank Sta=4906.5,4912.5
XS Rating Curve= 0 ,0
Exp/Cntr=0.3,0.1

Type RM Length L Ch R = 1 ,13900   ,649,649,649
BEGIN DESCRIPTION:
NAVASOTA RIVER TRIBUTARY 2.2 20.0
END DESCRIPTION:
XS GIS Cut Line= 3
      3578314.59     10317570.35      3578492.11     10316791.64
      3578847.75     10316000.71
#Sta/Elev= 30
  4221.2  308.45    4282  306.18  4362.9  304.71  4404.5  303.06    4425  299.63
  4459.2  295.58    4466  295.24  4571.9  295.33  4606.9  295.18  5192.3  295.03
  5195.1  294.53  5198.3  295.03  5201.8   296.2  5207.3  295.94  5224.9   298.3
    5294  302.06  5346.2  305.68  5351.7  305.65  5369.4  307.89  5374.8  308.04
  5381.7  309.27    5398  310.55  5421.2  313.66  5467.5  317.07  5502.3  318.75
  5542.4  319.68  5588.7  319.87  5669.2  319.27  5784.9  320.06  5887.1  319.21
#Mann= 5 ,-1 , 0
  4221.2     .05       0  4571.9     .07       0  4606.9     .05       0
  5192.3    .033       0  5198.3     .05       0
Bank Sta=5192.3,5198.3
XS Rating Curve= 0 ,0
Exp/Cntr=0.3,0.1

Type RM Length L Ch R = 1 ,13251   ,558,558,558
BEGIN DESCRIPTION:
NAVASOTA RIVER TRIBUTARY 2.2 19.0
END DESCRIPTION:
XS GIS Cut Line= 3
      3578375.35     10317704.92      3579061.11     10317062.55
       3579767.8     10316563.97
#Sta/Elev= 30
  4233.1  309.06  4417.2  303.33  4473.8  303.08  4502.2  302.17  4544.2  299.53
  4579.8   295.9  4652.4  295.81  4666.2  295.76  5249.9  295.14  5252.7  294.64
  5255.9  295.14  5303.4  299.33  5339.1  300.98  5475.8  310.13  5532.4   312.4
  5547.2  313.82    5562  314.29  5568.1  313.69  5582.9  313.77  5597.7  314.93
  5683.9  316.16  5734.4   315.5    5756  314.44    5791  312.39  5805.8  312.23
    5812  310.82  5826.7  309.92    5892  310.06    5935  312.78  6037.6  318.77
#Mann= 7 ,-1 , 0
  4233.1     .05       0  4652.4     .07       0  4666.2     .05       0
  5249.9    .033       0  5255.9     .05       0    5756      .1       0
    5935     .05       0
Bank Sta=5249.9,5255.9
XS Rating Curve= 0 ,0
Exp/Cntr=0.3,0.1

Type RM Length L Ch R = 1 ,12693   ,45,45,45
BEGIN DESCRIPTION:
NAVASOTA RIVER TRIBUTARY 2.2 18.1
END DESCRIPTION:
XS GIS Cut Line= 3
      3578542.14     10318141.62      3579208.68     10317661.51
       3579681.8     10317201.41
#Sta/Elev= 30
  4184.5  316.11  4221.2  314.25  4227.4  313.01  4242.1  313.26  4248.3  311.81
  4256.8  311.88    4263  310.26  4277.7   310.6  4283.9  309.25  4298.6  308.29
  4399.2  305.22  4615.2  300.61  4650.8   299.2  4677.8  295.38  4685.8   295.3
    4850  295.91  4924.5  295.18  5230.1  295.08  5335.5  295.13  5457.8  295.03
  5460.6  294.53  5463.8  295.03  5470.9  295.68  5496.3   298.3  5516.6  301.53
  5545.7  306.46  5595.3  308.84  5623.6  310.92  5658.9  315.17  5665.9  315.26
#Mann= 9 ,-1 , 0
  4184.5     .05       0  4685.8     .07       0  4924.5     .05       0
  5230.1      .1       0  5335.5     .05       0  5457.8     .03       0
  5463.8     .05       0  5470.9      .1       0  5516.6     .05       0
Bank Sta=5457.8,5463.8
XS Rating Curve= 0 ,0
Exp/Cntr=0.3,0.1

Type RM Length L Ch R = 1 ,12648   ,123,123,123
BEGIN DESCRIPTION:
NAVASOTA RIVER TRIBUTARY 2.2 18.0
END DESCRIPTION:
XS GIS Cut Line= 3
      3578568.17     10318176.35      3579234.72     10317696.23
      3579707.19     10317236.77
#Sta/Elev= 30
  4170.7  315.69    4306   312.1  4377.2  306.32  4643.5  299.95    4692  295.72
    4868  298.66  4871.8  296.97  4886.5  301.61  4907.4  299.29  4922.1  302.39
  4951.5  302.09  4997.7  294.28  5000.5  293.78  5003.7  294.28  5057.3  301.79
  5120.8  300.12  5176.6  302.15  5290.6  301.51  5297.6  299.18  5304.7  301.44
  5311.7  299.02  5318.9  301.18    5340  298.68  5347.2  300.93  5368.1  298.74
  5463.1  299.22  5503.5  301.89  5606.3  309.67  5638.9  312.12  5651.2  312.96
#Mann= 11 ,-1 , 0
  4170.7     .05       0    4692     .07       0    4868     .05       0
  4997.7     .03       0  5003.7     .05       0  5176.6      .1       0
  5368.1     .05       0  5463.1      .1       0  5503.5     .05       0
  5606.3     .16       0  5638.9     .05       0
Bank Sta=4997.7,5003.7
XS Rating Curve= 0 ,0
Exp/Cntr=0.3,0.1

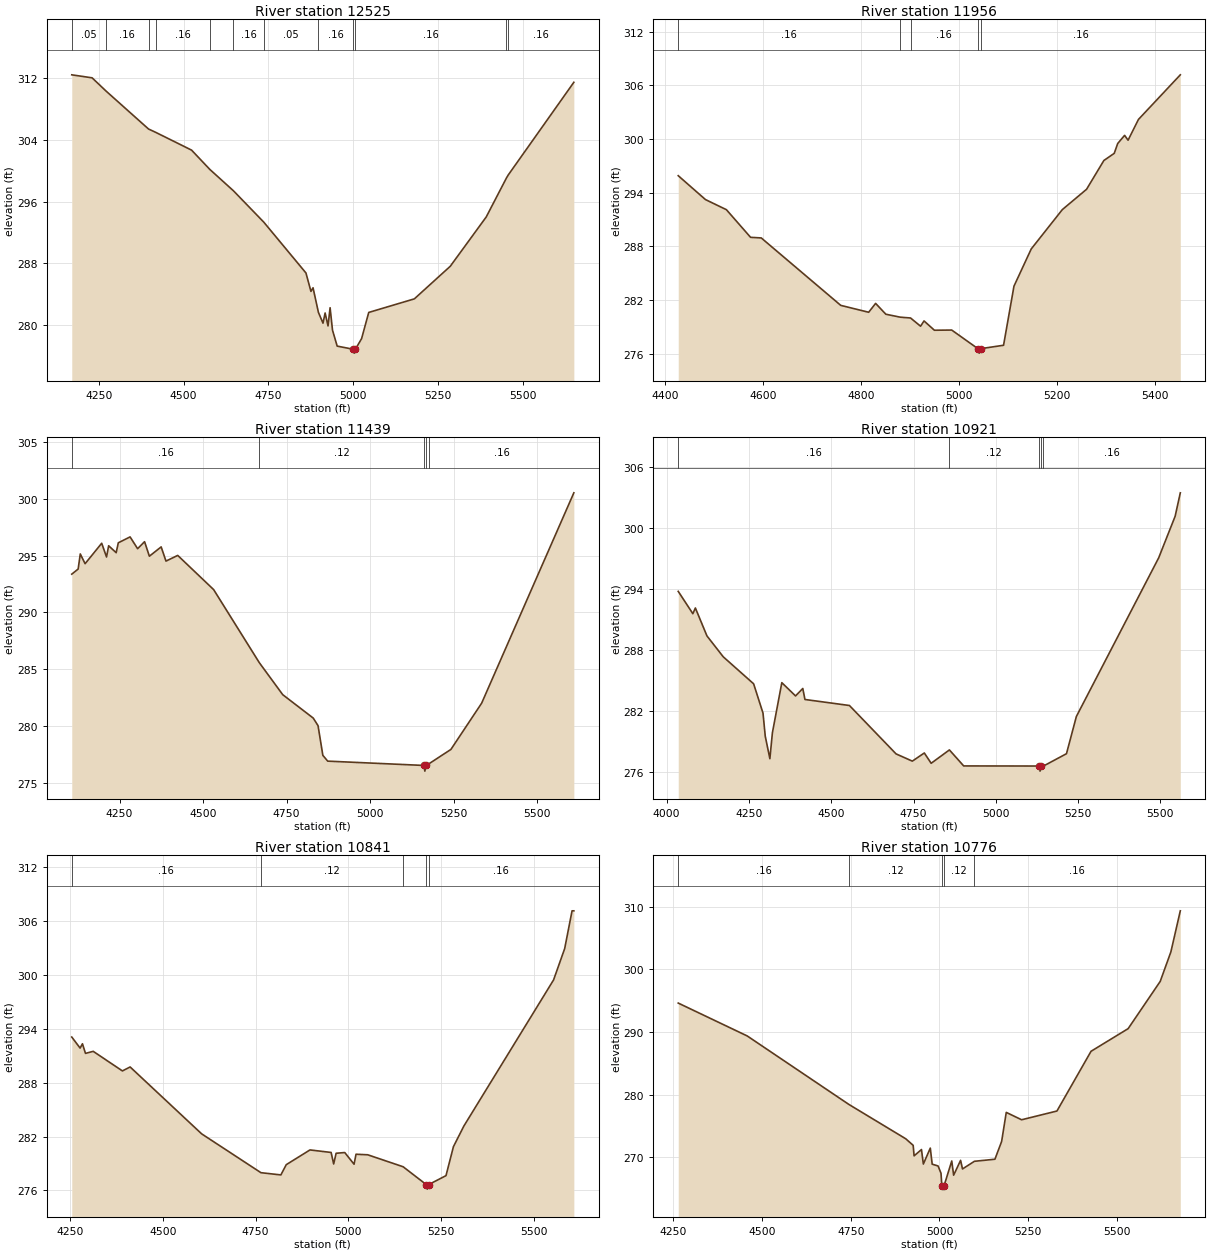
Type RM Length L Ch R = 1 ,12525   ,569,569,569
BEGIN DESCRIPTION:
NAVASOTA RIVER TRIBUTARY 2.2 17.0
END DESCRIPTION:
XS GIS Cut Line= 3
        3578668.     10318241.45      3579334.55     10317761.34
      3579807.38     10317301.52
#Sta/Elev= 30
  4170.4  312.44  4230.4  312.05  4271.6  310.33  4396.8  305.41  4418.3  304.97
  4523.8  302.67  4577.6  300.17  4647.4  297.39  4736.9  293.32  4861.2  286.73
  4875.9  284.34  4882.1  284.81    4898  281.61  4911.5  280.22  4917.7  281.54
  4926.3  279.86  4932.4  282.22  4939.5  279.31  4953.3  277.24    5001  276.83
  5003.7  276.33    5007  276.83  5025.3  278.21  5046.4  281.61  5180.9  283.37
  5286.9   287.6    5393     294  5452.2  299.02  5457.5  299.42  5651.4  311.47
#Mann= 12 ,-1 , 0
  4170.4     .05       0  4271.6     .16       0  4396.8     .05       0
  4418.3     .16       0  4577.6     .05       0  4647.4     .16       0
  4736.9     .05       0    4898     .16       0    5001     .07       0
    5007     .16       0  5452.2      .1       0  5457.5     .16       0
Bank Sta=5001,5007
XS Rating Curve= 0 ,0
Exp/Cntr=0.3,0.1

Type RM Length L Ch R = 1 ,11956   ,517,517,517
BEGIN DESCRIPTION:
NAVASOTA RIVER TRIBUTARY 2.2 16.0
END DESCRIPTION:
XS GIS Cut Line= 3
      3579352.88     10318291.28      3579652.87      10317941.3
      3580052.84     10317541.33
#Sta/Elev= 30
  4426.1  295.89  4481.8  293.22  4524.6  292.09    4574     289  4595.9  288.93
  4758.4  281.39  4815.5  280.62  4829.7  281.61  4850.6   280.4  4880.1  280.07
  4901.1  279.98  4921.6  279.06  4928.7  279.65  4949.9  278.61  4985.3  278.63
  5038.8  276.55  5041.6  276.05  5044.8  276.55  5091.3  276.93  5112.6  283.54
  5147.9   287.7  5211.5   292.1    5261  294.37  5296.4  297.59  5317.6  298.39
  5324.7  299.49  5338.8   300.4  5345.9  299.86  5367.1  302.18  5452.7  307.17
#Mann= 5 ,-1 , 0
  4426.1     .16       0  4880.1     .12       0  4901.1     .16       0
  5038.8     .07       0  5044.8     .16       0
Bank Sta=5038.8,5044.8
XS Rating Curve= 0 ,0
Exp/Cntr=0.3,0.1

Type RM Length L Ch R = 1 ,11439   ,518,518,518
BEGIN DESCRIPTION:
NAVASOTA RIVER TRIBUTARY 2.2 15.0
END DESCRIPTION:
XS GIS Cut Line= 3
      3579226.08     10318811.66      3579961.38     10318230.53
      3580361.37     10317830.53
#Sta/Elev= 30
  4106.8  293.37  4125.9  293.82  4132.3  295.15  4146.7  294.29  4196.4  296.09
  4210.9  294.88  4217.2  295.87  4239.7  295.26  4246.1  296.13  4281.4  296.65
  4303.9  295.61  4324.7  296.23  4339.1  294.95  4374.4  295.77  4388.8  294.52
    4424  295.02  4531.5  292.01  4667.9  285.59  4738.3  282.76  4829.6   280.7
    4844  280.03  4858.4  277.42  4872.9  276.91    5161  276.53  5163.7  276.03
    5167  276.53  5176.1  276.68  5241.7  277.94  5333.7  282.01  5609.7  300.53
#Mann= 5 ,-1 , 0
  4106.8     .16       0  4667.9     .12       0    5161     .07       0
    5167     .12       0  5176.1     .16       0
Bank Sta=5161,5167
XS Rating Curve= 0 ,0
Exp/Cntr=0.3,0.1

Type RM Length L Ch R = 1 ,10921   ,80,80,80
BEGIN DESCRIPTION:
Mapping XS a4fb0908
END DESCRIPTION:
XS GIS Cut Line= 4
      3579690.27     10319002.79      3580402.05     10318400.38
      3580445.45     10318289.27      3580459.32     10317815.95
#Sta/Elev= 30
  4035.2  293.75  4079.6  291.56  4087.3  292.12  4122.4  289.38  4171.9  287.33
  4264.2  284.68  4292.7  281.81  4299.6  279.53  4313.6  277.33  4321.3  279.88
  4349.9  284.79  4391.6  283.49  4413.6  284.22  4420.2  283.14  4555.3  282.55
    4697   277.8  4746.4  277.09  4782.8  277.89  4803.6  276.88    4859  278.19
  4902.4  276.62  5131.6  276.61  5134.4  276.11  5137.6  276.61  5144.8  276.61
  5214.7  277.82  5244.7  281.47  5494.8  297.04  5544.8  301.12  5560.5  303.42
#Mann= 5 ,-1 , 0
  4035.2     .16       0    4859     .12       0  5131.6     .07       0
  5137.6     .12       0  5144.8     .16       0
Bank Sta=5131.6,5137.6
XS Rating Curve= 0 ,0
Exp/Cntr=0.3,0.1

Type RM Length L Ch R = 1 ,10841   ,65,65,65
BEGIN DESCRIPTION:
Mapping XS ed0dd2b5
END DESCRIPTION:
XS GIS Cut Line= 5
      3580022.42     10318963.25      3580378.32     10318503.17
      3580478.15     10318427.22      3580515.04     10318327.39
      3580497.68       10317787.
#Sta/Elev= 30
  4254.1  293.07  4276.6  291.84  4282.9  292.32  4291.1  291.25  4311.9  291.48
  4390.7   289.3  4411.5  289.74  4604.4   282.3  4764.3  277.98  4818.1  277.73
  4832.6  278.87  4896.6  280.51  4953.6  280.23  4960.5  278.95  4967.1  280.14
  4990.4  280.22  5015.5  278.92  5020.8  280.03  5052.4  279.97  5147.8  278.64
  5210.5  276.65  5213.2  276.15  5216.5  276.65  5263.5  277.65  5283.5  280.87
  5311.7  283.17  5553.6  299.42  5583.6  302.91  5603.5  307.11  5608.3  307.11
#Mann= 5 ,-1 , 0
  4254.1     .16       0  4764.3     .12       0  5147.8     .16       0
  5210.5     .07       0  5216.5     .16       0
Bank Sta=5210.5,5216.5
XS Rating Curve= 0 ,0
Exp/Cntr=0.3,0.1

Type RM Length L Ch R = 1 ,10776   ,166,166,166
BEGIN DESCRIPTION:
NAVASOTA RIVER TRIBUTARY 2.2 14.0
END DESCRIPTION:
XS GIS Cut Line= 4
       3580089.7     10318974.08      3580530.23     10318472.79
       3580634.4     10318195.01      3580595.47     10317745.12
#Sta/Elev= 30
  4263.4  294.63    4458  289.37  4744.9  278.41  4904.9  272.93  4925.8  271.88
  4928.4   270.2  4949.2  271.21  4954.5  268.89  4974.1  271.44  4979.4  268.87
  4996.1  268.58  5004.3  267.41  5006.7  265.38  5009.4  264.88  5012.7  265.38
  5034.6  269.38  5039.9  267.11  5059.5  269.48  5064.9  268.11  5098.5  269.33
  5156.3  269.66  5175.2   272.5  5188.3  277.15  5231.6  275.97  5331.2  277.37
  5427.3  286.92  5531.9  290.54  5622.3  298.09  5652.4  302.81    5679  309.38
#Mann= 5 ,-1 , 0
  4263.4     .16       0  4744.9     .12       0  5006.7     .07       0
  5012.7     .12       0  5098.5     .16       0
Bank Sta=5006.7,5012.7
XS Rating Curve= 0 ,0
Exp/Cntr=0.3,0.1

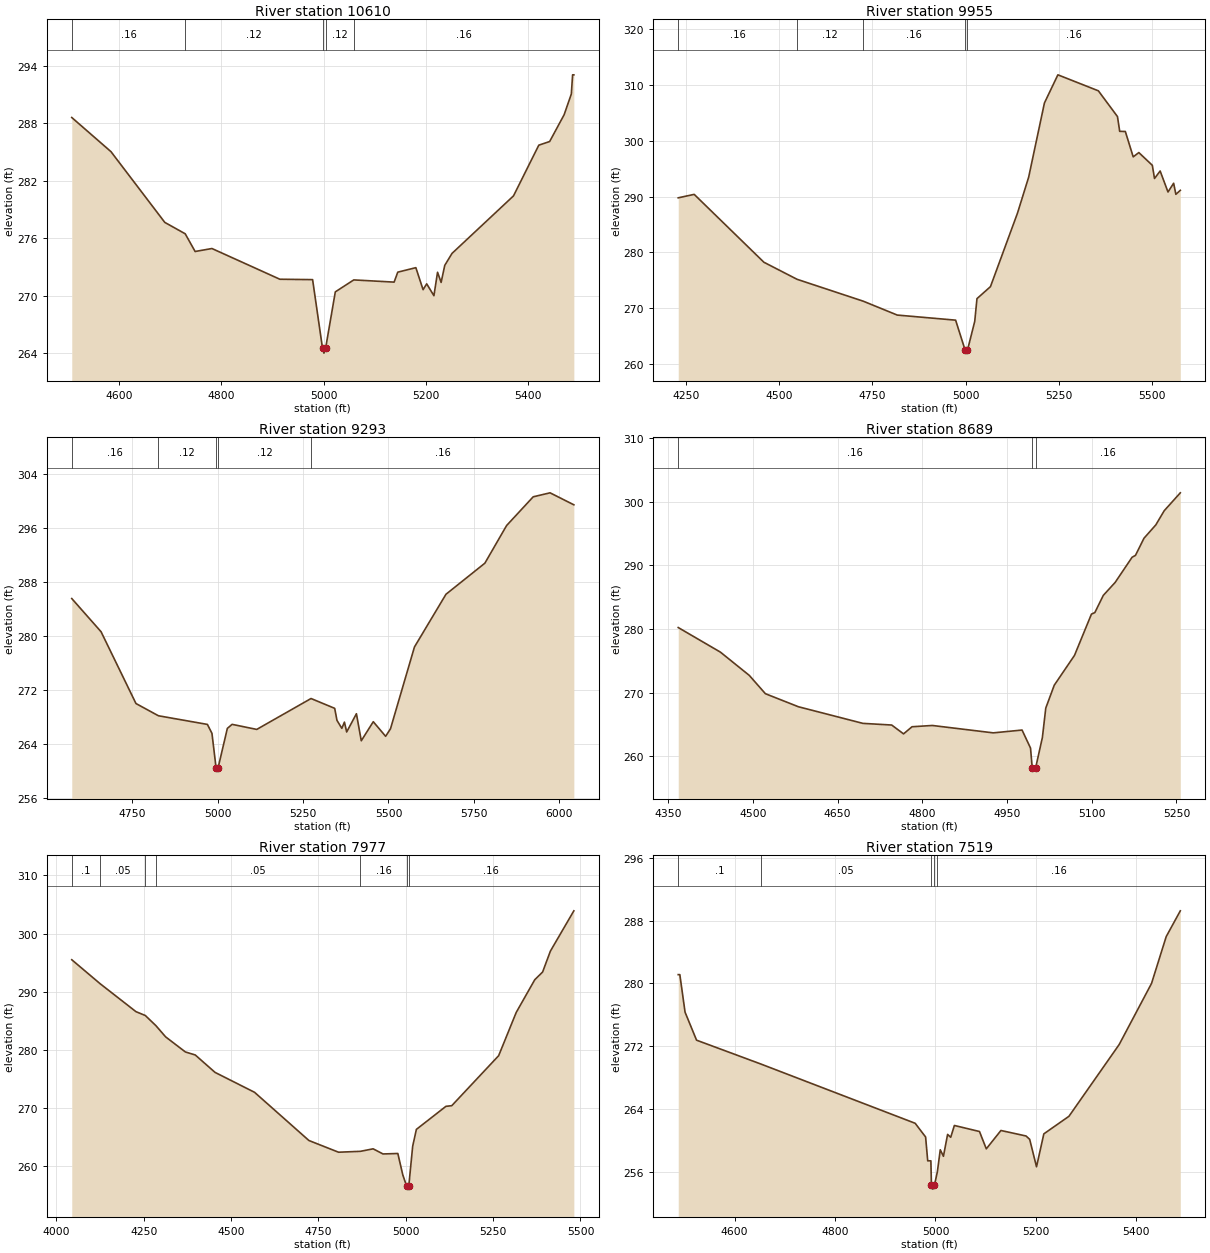
Type RM Length L Ch R = 1 ,10610   ,655,655,655
BEGIN DESCRIPTION:
NAVASOTA RIVER TRIBUTARY 2.2 12.0
END DESCRIPTION:
XS GIS Cut Line= 3
       3580492.1     10318941.65      3580720.58     10318433.14
      3581020.55     10318133.17
#Sta/Elev= 30
  4507.7   288.6  4584.4  285.03  4689.6  277.64  4729.5  276.45  4748.9   274.6
  4781.8  274.91  4914.6   271.7  4978.6  271.66    4998  264.48  5000.8  263.98
    5004  264.48    5023  270.38  5059.1  271.63    5138   271.4  5145.1  272.44
  5180.5  272.91  5194.6  270.61  5201.7  271.22  5215.8  269.98  5222.9  272.43
  5229.9  271.37    5237  273.15  5251.2   274.4  5371.4  280.41  5420.9  285.71
  5442.1  286.09  5470.4  288.89  5484.5  291.06    5487  293.06  5489.4  293.06
#Mann= 5 ,-1 , 0
  4507.7     .16       0  4729.5     .12       0    4998     .07       0
    5004     .12       0  5059.1     .16       0
Bank Sta=4998,5004
XS Rating Curve= 0 ,0
Exp/Cntr=0.3,0.1

Type RM Length L Ch R = 1 ,9955    ,662,662,662
BEGIN DESCRIPTION:
NAVASOTA RIVER TRIBUTARY 2.2 11.0
END DESCRIPTION:
XS GIS Cut Line= 3
      3580788.53      10319271.8      3581040.28     10318681.48
      3581426.56      10318091.2
#Sta/Elev= 30
  4228.8  289.77  4271.6  290.39  4458.7  278.24  4547.7  275.19  4725.4  271.27
  4816.5  268.79  4973.1  267.88  4998.8  262.48  5001.6  261.98  5004.8  262.48
  5024.4  267.66  5030.4  271.73  5066.6  273.88    5139  287.01  5169.1  293.47
  5211.4  306.74  5247.5  311.78  5356.1  308.92  5407.4  304.31  5413.4  301.67
  5428.5  301.64  5449.6   297.1  5464.7  297.87  5500.9  295.59  5506.8  293.23
  5521.9  294.57    5543  290.81  5558.1  292.38  5564.1   290.4    5576  291.11
#Mann= 5 ,-1 , 0
  4228.8     .16       0  4547.7     .12       0  4725.4     .16       0
  4998.8     .07       0  5004.8     .16       0
Bank Sta=4998.8,5004.8
XS Rating Curve= 0 ,0
Exp/Cntr=0.3,0.1

Type RM Length L Ch R = 1 ,9293    ,604,604,604
BEGIN DESCRIPTION:
NAVASOTA RIVER TRIBUTARY 2.2 10.0
END DESCRIPTION:
XS GIS Cut Line= 3
      3581142.08     10319291.68       3581486.1     10318776.41
      3582047.15     10318139.02
#Sta/Elev= 30
  4573.6  285.56  4659.3  280.65  4761.4  270.03  4827.1  268.22  4970.4  266.94
  4983.7  265.62  4995.7  260.53  4998.4  260.03  5001.7  260.53  5028.7  266.35
  5042.6  266.95  5114.7   266.2  5273.5  270.77  5342.7  269.32  5349.4  267.54
  5363.6  266.36  5371.2  267.28  5377.8  265.82  5406.3  268.52  5420.5  264.52
  5455.6  267.34  5491.7  265.18  5505.9  266.29  5576.1   278.4  5668.2  286.19
    5782  290.79  5845.6  296.36  5923.4  300.61  5972.7   301.2  6042.3  299.43
#Mann= 5 ,-1 , 0
  4573.6     .16       0  4827.1     .12       0  4995.7     .07       0
  5001.7     .12       0  5273.5     .16       0
Bank Sta=4995.7,5001.7
XS Rating Curve= 0 ,0
Exp/Cntr=0.3,0.1

Type RM Length L Ch R = 1 ,8689    ,712,712,712
BEGIN DESCRIPTION:
NAVASOTA RIVER TRIBUTARY 2.2 8.0
END DESCRIPTION:
XS GIS Cut Line= 3
      3581546.52     10319430.09      3581746.51      10319130.1
      3582042.09     10318691.67
#Sta/Elev= 30
  4367.6  280.25  4442.3  276.39  4493.4  272.74    4522  269.86  4580.5  267.81
  4694.7   265.2  4745.7  264.94  4766.7  263.55  4781.7  264.67  4817.7  264.87
  4925.6  263.71  4976.6  264.15  4991.6  261.32  4994.6   258.2  4997.3   257.7
  5000.6   258.2  5012.6  262.98  5018.6   267.6  5033.6  271.19  5069.5  275.88
  5099.5  282.36  5105.5   282.6  5120.5   285.3  5141.5  287.34  5171.5  291.29
  5177.5  291.59  5192.5  294.27  5213.5  296.37  5228.4   298.6  5256.9  301.41
#Mann= 3 ,-1 , 0
  4367.6     .16       0  4994.6     .07       0  5000.6     .16       0
Bank Sta=4994.6,5000.6
XS Rating Curve= 0 ,0
Exp/Cntr=0.3,0.1

Type RM Length L Ch R = 1 ,7977    ,458,458,458
BEGIN DESCRIPTION:
NAVASOTA RIVER TRIBUTARY 2.2 7.0
END DESCRIPTION:
XS GIS Cut Line= 3
      3581492.13     10319891.62      3582192.11     10319191.64
      3582592.08     10318991.66
#Sta/Elev= 30
    4044  295.51  4125.2  291.39  4227.8  286.59  4254.5  285.93  4284.5  284.21
  4312.7  282.26  4369.2  279.67  4397.5  279.15  4454.1  276.16  4567.2  272.74
  4722.8  264.46  4807.6  262.45  4869.9   262.6  4906.6  263.03  4934.9  262.15
  4977.3  262.23  4991.5  258.56  5002.6  256.61  5005.4  256.11  5008.6  256.61
  5019.8  263.48  5030.4  266.37    5115  270.33  5131.7  270.44  5265.9  279.03
  5316.2  286.46  5369.3  292.08  5391.7   293.4    5414  296.99  5481.1  303.91
#Mann= 7 ,-1 , 0
    4044      .1       0  4125.2     .05       0  4254.5     .16       0
  4284.5     .05       0  4869.9     .16       0  5002.6     .07       0
  5008.6     .16       0
Bank Sta=5002.6,5008.6
XS Rating Curve= 0 ,0
Exp/Cntr=0.3,0.1

Type RM Length L Ch R = 1 ,7519    ,557,557,557
BEGIN DESCRIPTION:
NAVASOTA RIVER TRIBUTARY 2.2 6.0
END DESCRIPTION:
XS GIS Cut Line= 3
      3582042.09     10319941.67      3582342.11     10319541.64
      3582642.09     10319141.67
#Sta/Elev= 30
  4487.7  281.13  4490.9  281.13  4501.3  276.34  4524.2  272.77  4652.2  269.73
  4959.6  262.17  4980.4  260.42  4984.6  257.38  4990.9  257.38    4992  254.27
  4994.8  253.77    4998  254.27  5003.8  255.97  5009.6  258.79  5015.9  257.96
  5024.2  260.75  5030.4  260.38  5037.7  261.89  5087.7  261.12  5101.3  258.91
  5130.4  261.25  5180.4  260.55  5187.7  260.12  5201.3  256.62  5215.9  260.82
  5265.9  263.06  5365.9  272.21  5430.4  280.01  5459.6  285.98  5487.7  289.27
#Mann= 5 ,-1 , 0
  4487.7      .1       0  4652.2     .05       0    4992    .035       0
    4998     .05       0  5003.8     .16       0
Bank Sta=4992,4998
XS Rating Curve= 0 ,0
Exp/Cntr=0.3,0.1