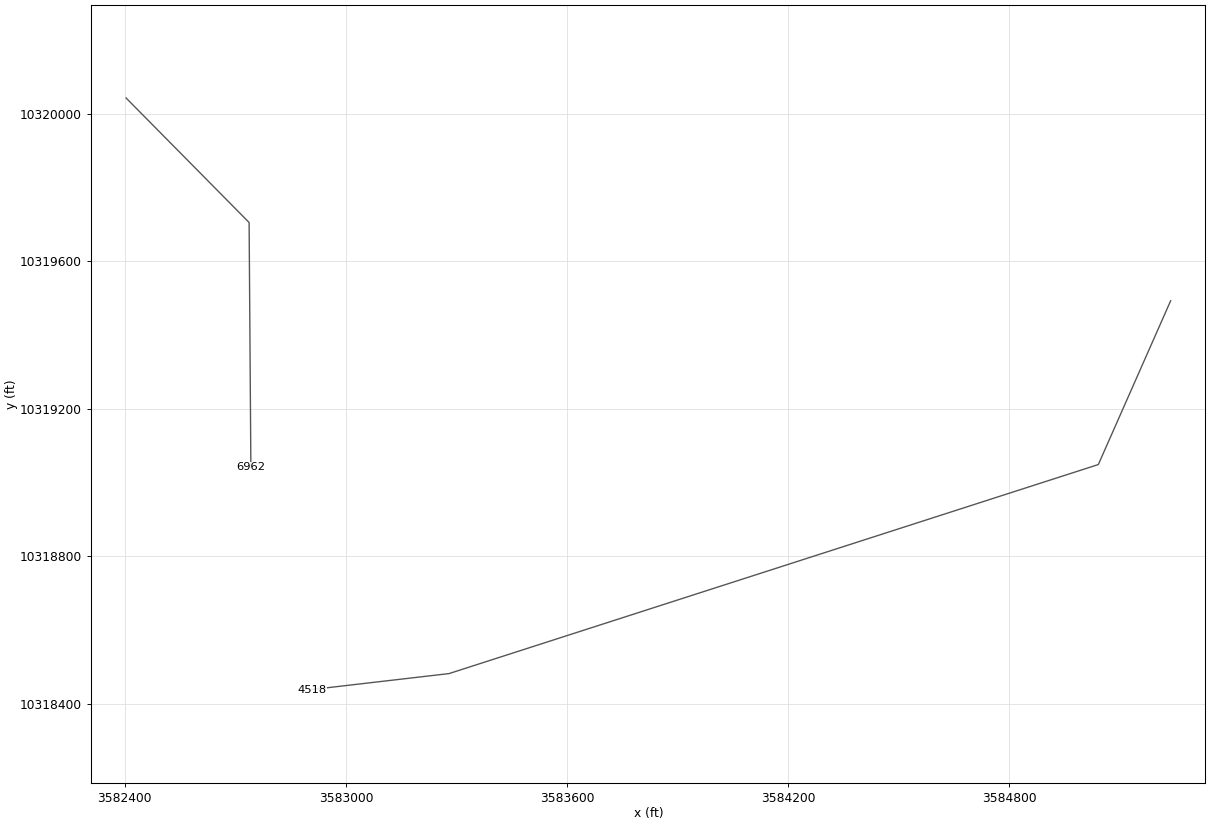
HEC-RAS study NAVASOTA RIVER TRIBUTARY 2 2.prj: NAVASOTA RIVER TRIBUTARY 2 2 Base Level Engineering

--- NAVASOTA RIVER TRIBUTARY 2 2.g01 (geometry) --- (continued)

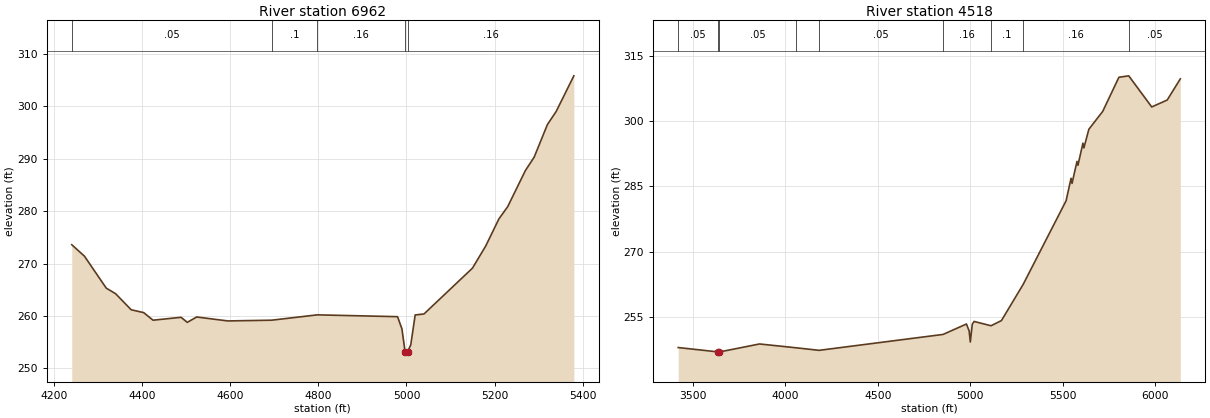
Type RM Length L Ch R = 1 ,6962    ,2444,2444,2444
BEGIN DESCRIPTION:
NAVASOTA RIVER TRIBUTARY 2.2 5.0
END DESCRIPTION:
XS GIS Cut Line= 3
      3582403.46     10320043.69      3582737.33     10319705.78
      3582742.11     10319041.62
#Sta/Elev= 30
  4240.6  273.59  4269.4  271.41  4318.9  265.31  4340.1  264.25  4375.4  261.19
  4403.7  260.65    4425   259.2  4488.6  259.75  4502.7  258.79    4524  259.81
  4594.7  259.06    4694   259.2  4797.8  260.22  4979.8  259.87  4989.8  257.52
  4996.8  253.23  4999.5  252.73  5002.8  253.23  5009.8  254.51  5019.8   260.2
  5039.8  260.39  5149.8  269.13  5179.8  273.34  5209.8  278.52  5229.8  280.86
  5269.8  287.73  5289.8   290.3  5319.8   296.5  5339.8  299.02  5379.8   305.8
#Mann= 5 ,-1 , 0
  4240.6     .05       0    4694      .1       0  4797.8     .16       0
  4996.8     .07       0  5002.8     .16       0
Bank Sta=4996.8,5002.8
XS Rating Curve= 0 ,0
Exp/Cntr=0.3,0.1

Type RM Length L Ch R = 1 ,4518    ,0,0,0
BEGIN DESCRIPTION:
NAVASOTA RIVER TRIBUTARY 2.2 1.0
END DESCRIPTION:
XS GIS Cut Line= 4
      3585237.84     10319493.33      3585041.65     10319049.03
      3583279.86     10318481.82      3582906.81     10318438.45
#Sta/Elev= 30
  3422.5  248.02  3639.3  247.01  3642.1  246.51  3645.3  247.01  3861.6  248.84
  4057.7  247.97  4183.4  247.38  4853.1  251.03  4979.3  253.42  4993.9  251.85
  5000.3  249.29  5010.8  253.37  5020.7  254.01  5112.2  253.02  5168.4  254.21
  5285.4  262.48  5517.6   281.7  5544.4  286.86  5549.7  285.69  5576.5  290.73
  5581.7  289.85  5608.6  294.93  5613.8  293.82  5640.6  298.11  5715.3   302.2
    5803  310.04    5856  310.37  5980.2  303.23  6063.7  304.81  6134.6  309.67
#Mann= 9 ,-1 , 0
  3422.5     .05       0  3639.3     .07       0  3645.3     .05       0
  4057.7      .1       0  4183.4     .05       0  4853.1     .16       0
  5112.2      .1       0  5285.4     .16       0    5856     .05       0
Bank Sta=3639.3,3645.3
XS Rating Curve= 0 ,0
Exp/Cntr=0.3,0.1

Chan Stop Cuts=-1
Use User Specified Reach Order=0
Composite Channel Slope=5