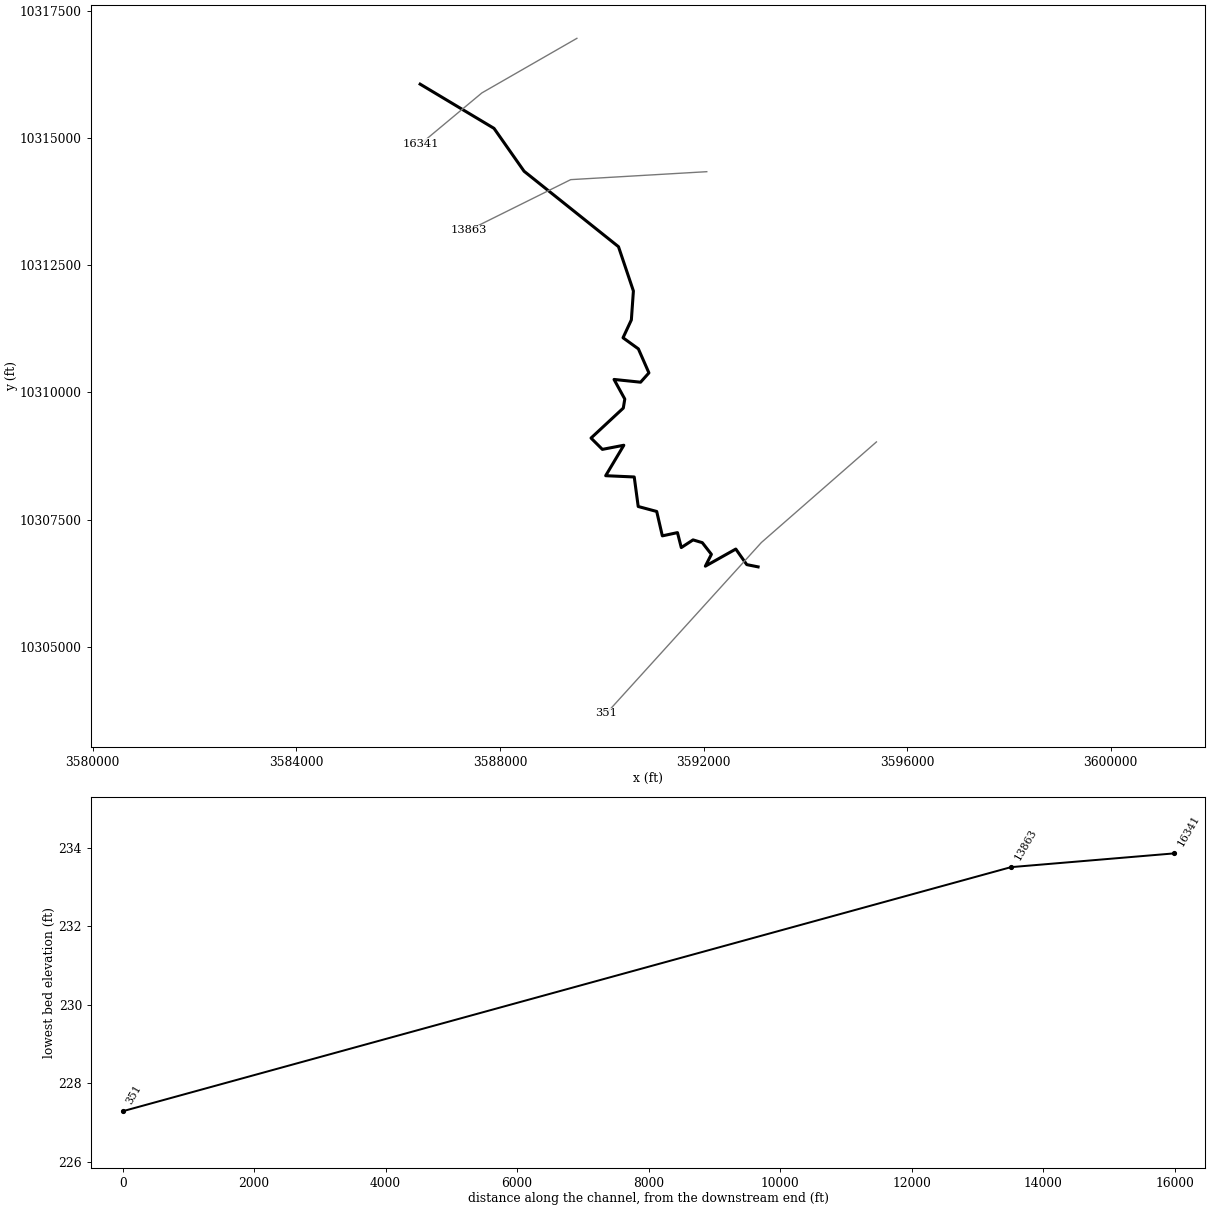
--- NAVASOTA RIVER TRIBUTARY 2.prj (project) ---

Proj Title=NAVASOTA RIVER TRIBUTARY 2 Base Level Engineering
Current Plan=p01
Default Exp/Contr=0.3,0.1
English Units
Geom File=g01
Flow File=f01
Plan File=p01
Y Axis Title=Elevation
X Axis Title(PF)=Main Channel Distance
X Axis Title(XS)=Station
BEGIN DESCRIPTION:
NAVASOTA RIVER TRIBUTARY 2
END DESCRIPTION:
DSS Export Rating Curves= 0
DSS Export Rating Curve Sorted= 0
DSS Export Volume Flow Curves= 0
DXF OffsetX= 0
DXF OffsetY= 0
DXF ScaleX= 1
DXF ScaleY= 10

--- NAVASOTA RIVER TRIBUTARY 2.p01 (plan) ---

Plan Title=Multiple Run
Short Identifier=Multiple
Geom File=g01
Flow File=f01
Subcritical Flow
K Sum by GR= 0
Std Step Tol= 0.01
Critical Tol= 0.01
Num of Std Step Trials= 20
Max Error Tol= 0.3
Flow Tol Ratio= 0.001
Split Flow NTrial= 30
Split Flow Tol= 0.02
Split Flow Ratio= 0.02
Log Output Level= 0
Friction Slope Method= 1
Unsteady Friction Slope Method= 2
Unsteady Bridges Friction Slope Method= 1
Parabolic Critical Depth
Global Vel Dist=  1 , 1 , 1
Global Log Level= 0
CheckData=True
Encroach Param= -1, 0, 0, 0
BEGIN DESCRIPTION:
Multiple Run
END DESCRIPTION:

--- NAVASOTA RIVER TRIBUTARY 2.f01 (steady flow) ---

Flow Title=Multiple
Program Version=4.10
Number of Profiles= 7
Profile Names=10-year,25-year,50-year,1pct_min,100-year,1pct_plu,500-year
River Rch & RM=NAVASOTA RIVER T,Reach-1         ,16341
    2012    2833    3527    3202    4331    5857    6548
River Rch & RM=NAVASOTA RIVER T,Reach-1         ,13863
    2061    2898    3606    3270    4422    5980    6671
River Rch & RM=NAVASOTA RIVER T,Reach-1         ,351
    2351    3311    4123    3740    5058    6840    7634
Boundary for River Rch & Prof#=NAVASOTA RIVER T,Reach-1         , 1
Up Type= 0
Dn Type= 3
Dn Slope=0.001
Boundary for River Rch & Prof#=NAVASOTA RIVER T,Reach-1         , 2
Up Type= 0
Dn Type= 3
Dn Slope=0.001
Boundary for River Rch & Prof#=NAVASOTA RIVER T,Reach-1         , 3
Up Type= 0
Dn Type= 3
Dn Slope=0.001
Boundary for River Rch & Prof#=NAVASOTA RIVER T,Reach-1         , 4
Up Type= 0
Dn Type= 3
Dn Slope=0.001
Boundary for River Rch & Prof#=NAVASOTA RIVER T,Reach-1         , 5
Up Type= 0
Dn Type= 3
Dn Slope=0.001
Boundary for River Rch & Prof#=NAVASOTA RIVER T,Reach-1         , 6
Up Type= 0
Dn Type= 3
Dn Slope=0.001
Boundary for River Rch & Prof#=NAVASOTA RIVER T,Reach-1         , 7
Up Type= 0
Dn Type= 3
Dn Slope=0.001
DSS Import GetInterval= 0
DSS Import GetPeak= 0
DSS Import FillOption= 0

--- NAVASOTA RIVER TRIBUTARY 2.g01 (geometry) ---

Geom Title=Existing Conditions
Program Version=4.10

River Reach=NAVASOTA RIVER T,Reach-1
Reach XY= 30
      3586432.11     10316061.64      3587883.43     10315192.26
      3588474.36     10314349.18      3590328.98     10312865.96
      3590622.09     10311995.73      3590581.95     10311427.16
       3590418.1      10311075.6      3590719.75      10310857.5
        3590927.     10310385.49      3590763.15     10310202.11
      3590241.23     10310256.37      3590452.82     10309871.17
      3590423.53     10309693.22      3589789.85     10309104.02
      3590012.29     10308881.58      3590434.38     10308962.96
      3590077.39     10308364.01      3590638.37     10308339.05
       3590716.5     10307758.54      3591079.99     10307660.88
      3591190.67     10307181.28      3591487.98      10307245.3
      3591562.85     10306951.25      3591793.97     10307102.07
      3591975.83     10307047.64      3592154.45     10306818.43
       3592035.7     10306585.44      3592633.96     10306922.25
      3592849.24       10306616.      3593072.11     10306571.64

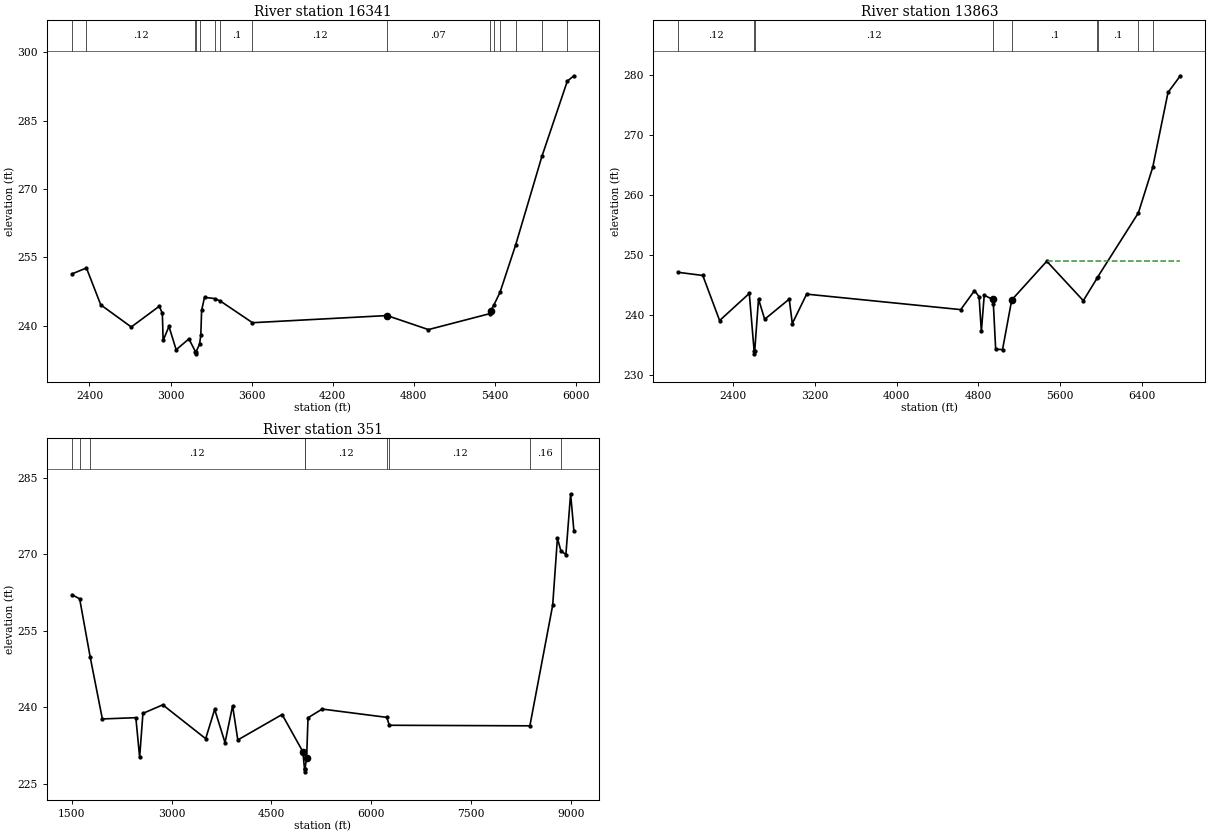
Type RM Length L Ch R = 1 ,16341   ,2478,2478,2478
BEGIN DESCRIPTION:
NAVASOTA RIVER TRIBUTARY 2 28.0
END DESCRIPTION:
XS GIS Cut Line= 3
      3589511.75     10316962.11       3587645.6     10315889.68
      3586446.37     10314890.32
#Sta/Elev= 30
  2271.2  251.41  2377.5   252.7  2483.5  244.61  2709.2  239.75  2916.7  244.31
  2939.2  242.74    2945  236.79  2988.1  239.88  3041.3  234.76  3135.8  237.14
  3183.5  234.36  3186.3  233.86  3189.5  234.36  3214.5  235.97  3223.9  237.96
  3229.7  243.38  3251.2  246.25  3325.9  245.99  3368.9  245.43  3606.2  240.69
    4602  242.26  4907.9  239.18  5362.2  242.68  5368.7  243.31  5391.9  244.54
  5437.8  247.36  5552.9   257.7  5747.5  277.16  5935.8   293.7  5984.6  294.87
#Mann= 15 ,-1 , 0
  2271.2     .16       0  2377.5     .12       0  3183.5     .07       0
  3189.5     .12       0  3214.5      .1       0  3325.9     .12       0
  3368.9      .1       0  3606.2     .12       0    4602     .07       0
  5362.2      .1       0  5391.9     .12       0  5437.8      .1       0
  5552.9     .16       0  5747.5     .05       0  5935.8      .1       0
Bank Sta=4602,5368.7
XS Rating Curve= 0 ,0
Exp/Cntr=0.3,0.1

Type RM Length L Ch R = 1 ,13863   ,13512,13512,13512
BEGIN DESCRIPTION:
NAVASOTA RIVER TRIBUTARY 2 6.0
END DESCRIPTION:
XS GIS Cut Line= 3
      3592063.77     10314340.57       3589390.2     10314184.32
      3587392.14     10313191.66
#Sta/Elev= 30
  1866.1  247.09    2104  246.57  2268.5  239.06  2558.9  243.58    2606  234.01
  2608.8  233.51    2612  234.01  2649.1  242.65  2709.2  239.27  2949.6  242.63
  2979.7  238.56  3119.9  243.46  4627.4  240.88  4761.8  244.05  4806.6  243.04
    4829  237.26    4857  243.27    4941  242.58  4946.6  241.76    4969  234.28
  5036.2  234.22  5125.9  242.49  5468.9  248.94  5826.2  242.37  5964.7  246.22
  5967.6  246.33  6365.2  257.01  6505.6  264.62  6654.9  277.07  6775.3  279.85
#Mann= 9 ,-1 , 0
  1866.1     .12       0    2606     .07       0    2612     .12       0
  4946.6     .05       0  5125.9      .1       0  5964.7     .05       0
  5967.6      .1       0  6365.2     .05       0  6505.6      .1       0
#XS Ineff= 2 , 0
                         5476.14          248.92
Permanent Ineff=
       F       F
Bank Sta=4941,5125.9
XS Rating Curve= 0 ,0
Exp/Cntr=0.3,0.1

Type RM Length L Ch R = 1 ,351     ,0,0,0
BEGIN DESCRIPTION:
NAVASOTA RIVER TRIBUTARY 2 1.0
END DESCRIPTION:
XS GIS Cut Line= 3
      3595397.12     10309028.05      3593136.03     10307050.19
      3590092.08     10303691.62
#Sta/Elev= 30
  1505.8  262.03  1619.7  261.25    1777  249.88  1960.6  237.67  2463.6  237.92
  2520.6  230.14  2569.9  238.76  2867.6  240.44  3512.4   233.8  3647.2  239.55
  3802.8  233.02  3916.7  240.26  3994.6  233.55  4660.1  238.54  4971.7  231.25
  4997.1  227.79  4999.8  227.29  5003.1  227.79  5028.5   230.1  5049.4  237.91
  5262.3  239.61  6232.1  237.98  6270.9  236.43  8381.2  236.32  8723.9  260.01
  8794.9  273.18  8846.1  270.69  8921.9  269.92  8992.9  281.86  9042.6  274.53
#Mann= 9 ,-1 , 0
  1505.8     .05       0  1619.7     .16       0    1777     .12       0
  4997.1     .07       0  5003.1     .12       0  6232.1     .05       0
  6270.9     .12       0  8381.2     .16       0  8846.1     .05       0
Bank Sta=4971.7,5028.5
XS Rating Curve= 0 ,0
Exp/Cntr=0.3,0.1

Chan Stop Cuts=-1
Use User Specified Reach Order=0
Composite Channel Slope=5