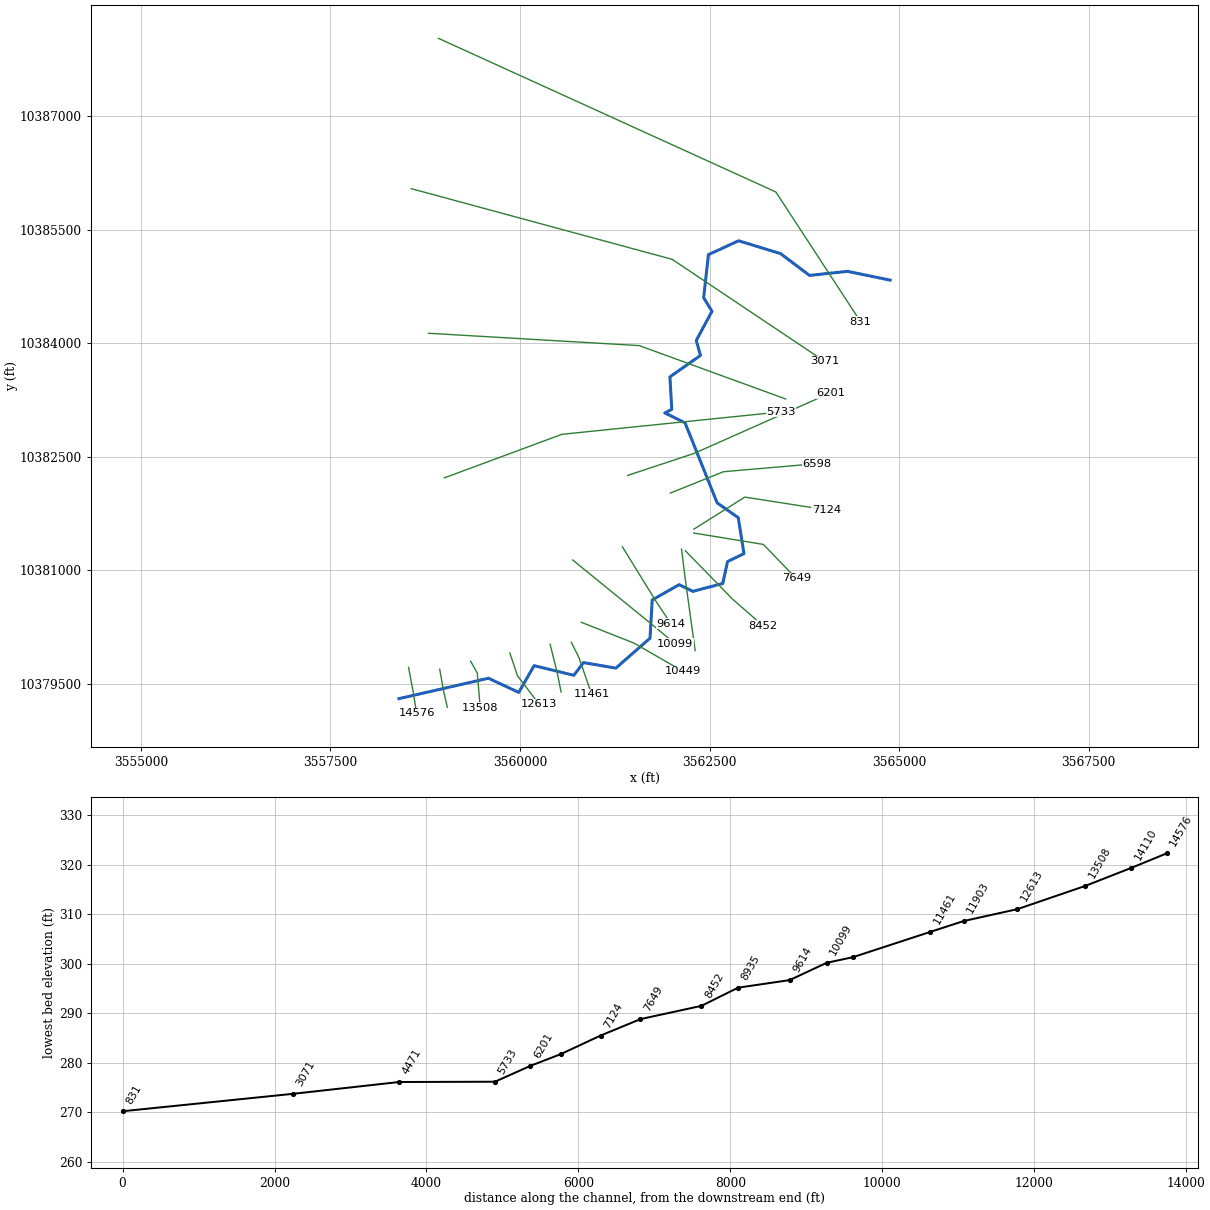
--- NAVASOTA RIVER TRIBUTARY 3 1.prj (project) ---

Proj Title=NAVASOTA RIVER TRIBUTARY 3 1 Base Level Engineering
Current Plan=p01
Default Exp/Contr=0.3,0.1
English Units
Geom File=g01
Flow File=f01
Plan File=p01
BEGIN DESCRIPTION:
NAVASOTA RIVER TRIBUTARY 3 1
END DESCRIPTION:

--- NAVASOTA RIVER TRIBUTARY 3 1.p01 (plan) ---

Plan Title=Multiple Run
Short Identifier=Multiple
Geom File=g01
Flow File=f01
Subcritical Flow
K Sum by GR= 0
Std Step Tol= 0.01
Critical Tol= 0.01
Num of Std Step Trials= 20
Max Error Tol= 0.3
Flow Tol Ratio= 0.001
Split Flow NTrial= 30
Split Flow Tol= 0.02
Split Flow Ratio= 0.02
Log Output Level= 0
Friction Slope Method= 1
Unsteady Friction Slope Method= 2
Unsteady Bridges Friction Slope Method= 1
Parabolic Critical Depth
Global Vel Dist=  1 , 1 , 1
Global Log Level= 0
CheckData=True
Encroach Param= -1, 0, 0, 0
BEGIN DESCRIPTION:
Multiple Run
END DESCRIPTION:

--- NAVASOTA RIVER TRIBUTARY 3 1.f01 (steady flow) ---

Flow Title=Multiple
Number of Profiles=7
Profile Names=10-year,25-year,50-year,1pct_min,100-year,1pct_plu,500-year
River Rch & RM= NAVASOTA RIVER T,Reach-1,14576
     900    1230    1499    1334    1804    2440    2605
River Rch & RM= NAVASOTA RIVER T,Reach-1,13508
    1490    2087    2587    2336    3159    4272    4700
River Rch & RM= NAVASOTA RIVER T,Reach-1,831
    2154    3073    3856    3521    4762    6440    7247
Boundary for River Rch & Prof#=NAVASOTA RIVER T,Reach-1,1
Up Type=0
Dn Type=3
Dn Slope=0.005
Boundary for River Rch & Prof#=NAVASOTA RIVER T,Reach-1,2
Up Type=0
Dn Type=3
Dn Slope=0.005
Boundary for River Rch & Prof#=NAVASOTA RIVER T,Reach-1,3
Up Type=0
Dn Type=3
Dn Slope=0.005
Boundary for River Rch & Prof#=NAVASOTA RIVER T,Reach-1,4
Up Type=0
Dn Type=3
Dn Slope=0.005
Boundary for River Rch & Prof#=NAVASOTA RIVER T,Reach-1,5
Up Type=0
Dn Type=3
Dn Slope=0.005
Boundary for River Rch & Prof#=NAVASOTA RIVER T,Reach-1,6
Up Type=0
Dn Type=3
Dn Slope=0.005
Boundary for River Rch & Prof#=NAVASOTA RIVER T,Reach-1,7
Up Type=0
Dn Type=3
Dn Slope=0.005

--- NAVASOTA RIVER TRIBUTARY 3 1.g01 (geometry) ---

Geom Title=Existing Conditions

River Reach=NAVASOTA RIVER T,Reach-1
Reach XY= 30
      3558404.76     10379304.30      3559584.56     10379573.68
      3559984.56     10379386.53      3560186.57     10379740.10
      3560710.23     10379612.02      3560837.24     10379779.96
      3561264.82     10379707.61      3561714.82     10380102.82
      3561743.57     10380607.24      3562098.67     10380809.76
      3562279.77     10380721.13      3562673.74     10380825.06
      3562737.16     10381114.21      3562953.76     10381219.84
      3562878.04     10381694.81      3562600.13     10381889.64
      3562176.32     10382948.25      3561909.53     10383077.64
      3562001.64     10383125.05      3561977.35     10383554.24
      3562380.18     10383837.39      3562324.66     10384034.57
      3562531.85     10384421.04      3562421.59     10384599.94
      3562485.25     10385168.52      3562883.07     10385351.67
      3563437.07     10385181.54      3563817.77     10384894.09
      3564317.12     10384947.88      3564882.11     10384831.64

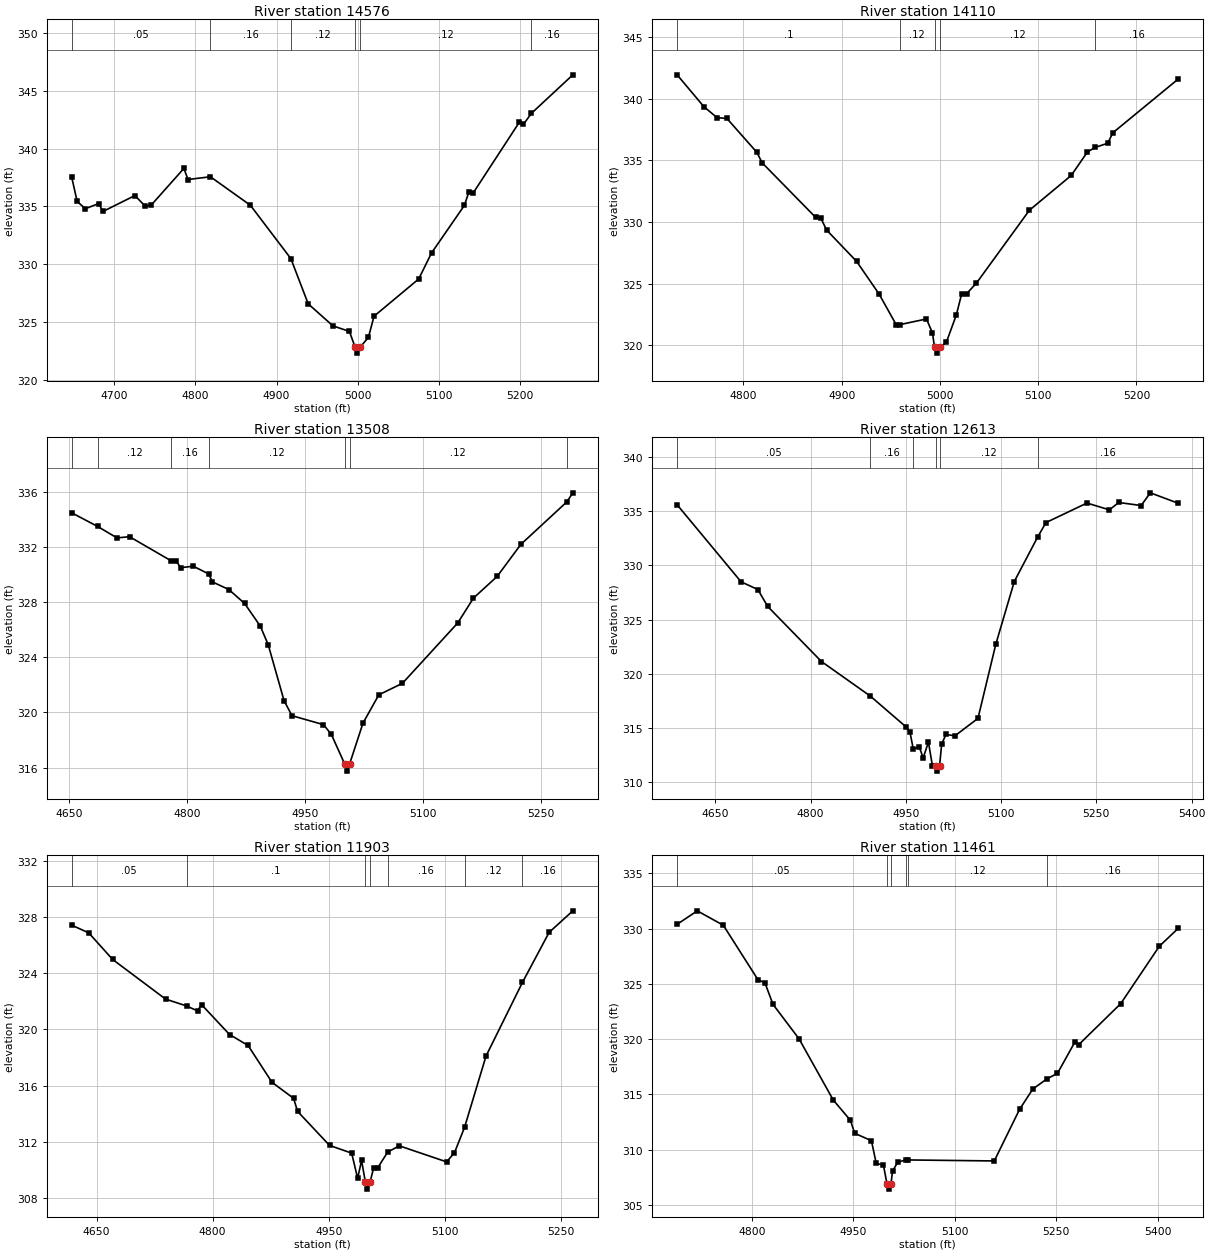
Type RM Length L Ch R = 1,14576,466,466,466
BEGIN DESCRIPTION:
NAVASOTA RIVER TRIBUTARY 3.1 27.0
END DESCRIPTION:
XS GIS Cut Line= 3
      3558530.73     10379718.19      3558592.11     10379391.64
      3558637.25     10379109.60
#Sta/Elev= 30
  4647.4  337.53  4654.1  335.43  4664.2  334.80  4680.7  335.25  4685.8  334.56
  4725.3  335.94  4738.3  335.00  4745.6  335.13  4785.7  338.29  4790.8  337.33
  4818.4  337.57  4867.7  335.10  4917.6  330.48  4939.0  326.56  4969.5  324.65
  4989.8  324.17  4996.9  322.79  4999.7  322.29  5002.9  322.79  5013.2  323.65
  5020.2  325.49  5075.2  328.71  5091.1  330.97  5131.6  335.09  5137.2  336.27
  5142.3  336.15  5199.2  342.28  5204.3  342.10  5214.2  343.06  5265.3  346.40
#Mann=6,-1,0
  4647.4    0.05       0  4818.4    0.16       0  4917.6    0.12       0
  4996.9    0.07       0  5002.9    0.12       0  5214.2    0.16       0
Bank Sta=4996.9,5002.9
Exp/Cntr=0.3,0.1

Type RM Length L Ch R = 1,14110,602,602,602
BEGIN DESCRIPTION:
NAVASOTA RIVER TRIBUTARY 3.1 26.0
END DESCRIPTION:
XS GIS Cut Line= 3
      3558942.11     10379691.62      3558992.11     10379405.93
      3559042.11     10379191.62
#Sta/Elev= 30
  4732.5  341.93  4759.7  339.35  4773.1  338.46  4783.2  338.39  4813.7  335.64
  4819.1  334.79  4873.5  330.37  4878.6  330.33  4884.8  329.33  4915.2  326.80
  4938.1  324.15  4955.8  321.62  4959.1  321.67  4986.3  322.13  4992.4  321.00
  4994.5  319.86  4997.3  319.36  5000.5  319.86  5006.6  320.25  5016.7  322.45
  5022.2  324.19  5027.3  324.19  5037.2  325.04  5091.1  330.95  5133.7  333.77
  5150.2  335.68  5158.3  336.05  5170.7  336.38  5176.2  337.24  5242.6  341.59
#Mann=5,-1,0
  4732.5     0.1       0  4959.1    0.12       0  4994.5    0.07       0
  5000.5    0.12       0  5158.3    0.16       0
Bank Sta=4994.5,5000.5
Exp/Cntr=0.3,0.1

Type RM Length L Ch R = 1,13508,895,895,895
BEGIN DESCRIPTION:
NAVASOTA RIVER TRIBUTARY 3.1 25.0
END DESCRIPTION:
XS GIS Cut Line= 3
      3559349.73     10379798.31      3559437.49     10379641.99
      3559475.51     10379185.75
#Sta/Elev= 30
  4653.8  334.47  4686.8  333.48  4711.4  332.65  4727.3  332.74  4780.5  330.98
  4786.6  330.97  4792.4  330.49  4808.3  330.60  4827.9  330.04  4832.7  329.46
  4853.5  328.91  4873.6  327.90  4893.6  326.25  4903.7  324.89  4923.7  320.86
  4933.8  319.76  4973.9  319.11  4983.9  318.40  5001.0  316.24  5003.8  315.74
  5007.0  316.24  5024.1  319.22  5044.2  321.27  5074.3  322.11  5144.5  326.48
  5164.6  328.29  5194.7  329.86  5224.8  332.18  5283.2  335.26  5290.9  335.92
#Mann=7,-1,0
  4653.8    0.16       0  4686.8    0.12       0  4780.5    0.16       0
  4827.9    0.12       0  5001.0    0.07       0  5007.0    0.12       0
  5283.2    0.16       0
Bank Sta=5001,5007
Exp/Cntr=0.3,0.1

Type RM Length L Ch R = 1,12613,710,710,710
BEGIN DESCRIPTION:
NAVASOTA RIVER TRIBUTARY 3.1 23.0
END DESCRIPTION:
XS GIS Cut Line= 3
      3559866.84     10379906.92      3559966.85     10379606.88
      3560252.79     10379230.56
#Sta/Elev= 30
  4590.0  335.58  4690.7  328.48  4717.1  327.77  4732.6  326.21  4817.2  321.14
  4894.0  317.96  4950.3  315.12  4956.5  314.65  4961.8  313.07  4971.1  313.28
  4977.4  312.26  4985.6  313.72  4991.9  311.54  4997.2  311.54  4999.9  311.04
  5003.2  311.54  5006.5  313.55  5013.3  314.42  5027.3  314.29  5063.6  315.90
  5091.7  322.73  5120.8  328.51  5157.7  332.62  5170.7  333.94  5235.2  335.74
  5270.6  335.11  5285.1  335.79  5320.5  335.51  5335.0  336.68  5378.9  335.72
#Mann=6,-1,0
  4590.0    0.05       0  4894.0    0.16       0  4961.8    0.12       0
  4997.2    0.07       0  5003.2    0.12       0  5157.7    0.16       0
Bank Sta=4997.2,5003.2
Exp/Cntr=0.3,0.1

Type RM Length L Ch R = 1,11903,442,442,442
BEGIN DESCRIPTION:
NAVASOTA RIVER TRIBUTARY 3.1 22.0
END DESCRIPTION:
XS GIS Cut Line= 3
      3560397.60     10380022.96      3560492.11     10379641.64
      3560542.10     10379391.65
#Sta/Elev= 30
  4617.8  327.41  4639.8  326.86  4670.7  324.97  4739.1  322.15  4766.4  321.66
  4780.4  321.31  4785.6  321.76  4821.8  319.63  4845.8  318.85  4876.7  316.23
  4904.6  315.09  4909.8  314.16  4951.1  311.74  4979.7  311.19  4987.4  309.40
  4992.5  310.67  4997.4  309.13  5000.1  308.63  5003.4  309.13  5008.1  310.13
  5013.2  310.13  5026.3  311.27  5041.3  311.71  5102.4  310.57  5112.6  311.22
  5125.6  313.02  5153.4  318.10  5200.5  323.34  5235.0  326.90  5265.6  328.43
#Mann=7,-1,0
  4617.8    0.05       0  4766.4     0.1       0  4997.4    0.07       0
  5003.4     0.1       0  5026.3    0.16       0  5125.6    0.12       0
  5200.5    0.16       0
Bank Sta=4997.4,5003.4
Exp/Cntr=0.3,0.1

Type RM Length L Ch R = 1,11461,1012,1012,1012
BEGIN DESCRIPTION:
NAVASOTA RIVER TRIBUTARY 3.1 21.0
END DESCRIPTION:
XS GIS Cut Line= 3
      3560676.87     10380048.32      3560776.87     10379848.32
      3560946.22     10379360.06
#Sta/Elev= 30
  4689.8  330.38  4719.6  331.60  4758.1  330.29  4809.1  325.38  4819.6  325.08
  4831.4  323.14  4869.9  320.02  4920.5  314.48  4945.8  312.65  4952.2  311.47
  4976.9  310.80  4984.0  308.74  4994.6  308.60  4999.8  306.92  5002.5  306.42
  5005.8  306.92  5008.1  308.05  5015.7  308.85  5028.4  309.08  5031.3  309.06
  5158.4  308.97  5195.7  313.63  5215.4  315.48  5236.1  316.39  5251.8  316.90
  5277.7  319.75  5283.0  319.48  5345.2  323.20  5402.2  328.39  5430.2  330.02
#Mann=6,-1,0
  4689.8    0.05       0  4999.8    0.03       0  5005.8    0.05       0
  5028.4    0.16       0  5031.3    0.12       0  5236.1    0.16       0
Bank Sta=4999.8,5005.8
Exp/Cntr=0.3,0.1

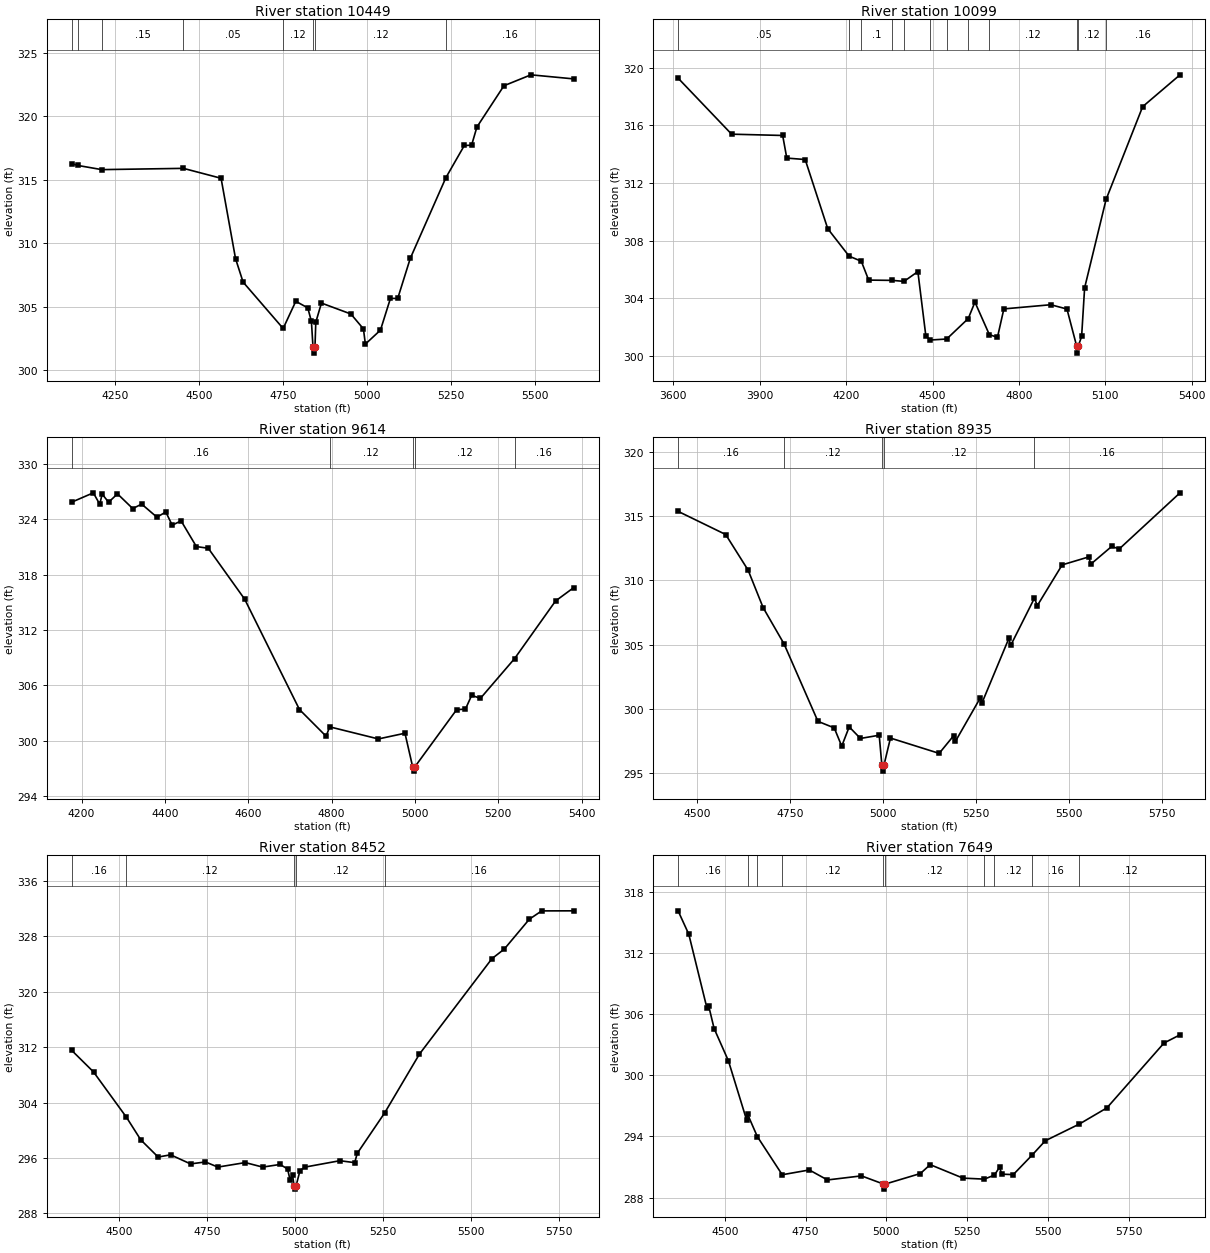
Type RM Length L Ch R = 1,10449,350,350,350
BEGIN DESCRIPTION:
NAVASOTA RIVER TRIBUTARY 3.1 19.0
END DESCRIPTION:
XS GIS Cut Line= 3
      3560809.10     10380312.52      3561502.47     10380038.22
      3562150.19     10379664.83
#Sta/Elev= 30
  4122.0  316.26  4139.8  316.12  4211.2  315.79  4454.1  315.89  4566.2  315.11
  4609.2  308.79  4631.7  306.94  4750.9  303.29  4788.5  305.43  4824.2  304.91
  4835.0  303.84  4839.6  301.85  4842.3  301.35  4845.6  301.85  4848.0  303.78
  4864.8  305.29  4952.4  304.43  4989.7  303.26  4995.5  302.06  5040.4  303.16
  5070.1  305.66  5091.7  305.65  5129.0  308.80  5234.9  315.15  5289.9  317.69
  5311.5  317.71  5327.3  319.14  5407.7  322.39  5488.1  323.25  5615.3  322.93
#Mann=8,-1,0
  4122.0    0.05       0  4139.8     0.1       0  4211.2    0.15       0
  4454.1    0.05       0  4750.9    0.12       0  4839.6    0.07       0
  4845.6    0.12       0  5234.9    0.16       0
Bank Sta=4839.6,4845.6
Exp/Cntr=0.3,0.1

Type RM Length L Ch R = 1,10099,485,485,485
BEGIN DESCRIPTION:
NAVASOTA RIVER TRIBUTARY 3.1 18.0
END DESCRIPTION:
XS GIS Cut Line= 3
      3560694.76     10381135.48      3561792.11     10380241.64
      3562043.45     10380030.62
#Sta/Elev= 30
  3616.2  319.28  3802.1  315.39  3979.5  315.30  3993.8  313.73  4057.7  313.63
  4136.0  308.83  4210.4  306.92  4252.6  306.57  4278.2  305.26  4360.8  305.24
  4400.9  305.17  4449.1  305.85  4476.9  301.37  4492.5  301.10  4549.2  301.17
  4624.1  302.59  4647.3  303.73  4697.5  301.47  4725.6  301.29  4747.8  303.26
  4910.9  303.55  4967.0  303.25  5000.5  300.69  5003.3  300.19  5006.5  300.69
  5017.9  301.35  5028.3  304.72  5102.9  310.86  5229.9  317.30  5359.7  319.51
#Mann=12,-1,0
  3616.2    0.05       0  4210.4    0.07       0  4252.6     0.1       0
  4360.8    0.07       0  4400.9     0.1       0  4492.5    0.12       0
  4549.2    0.07       0  4624.1     0.1       0  4697.5    0.12       0
  5000.5    0.07       0  5006.5    0.12       0  5102.9    0.16       0
Bank Sta=5000.5,5006.5
Exp/Cntr=0.3,0.1

Type RM Length L Ch R = 1,9614,679,679,679
BEGIN DESCRIPTION:
NAVASOTA RIVER TRIBUTARY 3.1 17.0
END DESCRIPTION:
XS GIS Cut Line= 3
      3561350.05     10381310.77      3561792.11     10380591.64
      3561992.11     10380291.63
#Sta/Elev= 30
  4176.4  325.88  4228.1  326.89  4243.5  325.66  4249.4  326.75  4264.8  325.87
  4286.1  326.78  4322.8  325.18  4344.1  325.67  4380.8  324.25  4402.1  324.81
  4417.5  323.38  4438.8  323.85  4475.5  321.06  4504.0  320.88  4591.5  315.35
  4722.9  303.39  4786.7  300.50  4795.6  301.51  4912.3  300.20  4976.1  300.82
  4994.4  297.21  4997.2  296.71  5000.4  297.21  5100.2  303.38  5121.2  303.43
  5136.2  304.93  5157.2  304.60  5239.3  308.92  5337.5  315.16  5381.1  316.61
#Mann=5,-1,0
  4176.4    0.16       0  4795.6    0.12       0  4994.4    0.07       0
  5000.4    0.12       0  5239.3    0.16       0
Bank Sta=4994.4,5000.4
Exp/Cntr=0.3,0.1

Type RM Length L Ch R = 1,8935,483,483,483
BEGIN DESCRIPTION:
NAVASOTA RIVER TRIBUTARY 3.1 16.0
END DESCRIPTION:
XS GIS Cut Line= 3
      3562130.20     10381278.83      3562180.20     10380878.80
      3562310.16     10379939.18
#Sta/Elev= 30
  4447.9  315.37  4576.1  313.57  4636.5  310.80  4676.9  307.89  4733.4  305.06
  4824.5  299.05  4868.4  298.54  4888.6  297.12  4908.7  298.62  4939.0  297.72
  4989.5  297.97  4996.6  295.68  4999.3  295.18  5002.6  295.68  5019.8  297.75
  5151.0  296.56  5189.9  297.93  5194.9  297.50  5261.7  300.87  5266.7  300.51
  5338.6  305.49  5343.6  304.95  5407.3  308.61  5415.4  308.05  5482.2  311.21
  5554.0  311.83  5559.1  311.26  5615.4  312.64  5636.0  312.45  5799.6  316.81
#Mann=5,-1,0
  4447.9    0.16       0  4733.4    0.12       0  4996.6    0.07       0
  5002.6    0.12       0  5407.3    0.16       0
Bank Sta=4996.6,5002.6
Exp/Cntr=0.3,0.1

Type RM Length L Ch R = 1,8452,803,803,803
BEGIN DESCRIPTION:
NAVASOTA RIVER TRIBUTARY 3.1 15.0
END DESCRIPTION:
XS GIS Cut Line= 3
      3562180.62     10381257.41      3562805.46     10380616.39
      3563205.32     10380266.51
#Sta/Elev= 30
  4365.4  311.52  4427.2  308.42  4520.9  301.87  4561.5  298.62  4610.9  296.14
  4646.3  296.46  4702.9  295.15  4745.4  295.43  4780.6  294.69  4858.5  295.34
  4907.9  294.69  4957.5  295.07  4978.7  294.42  4985.8  292.83  4992.8  293.57
  4997.0  292.01  4999.7  291.51  5003.0  292.01  5014.1  294.19  5028.3  294.69
  5127.3  295.61  5169.5  295.33  5176.7  296.67  5254.7  302.51  5353.5  310.99
  5559.5  324.76  5594.6  326.14  5665.8  330.45  5700.9  331.65  5791.9  331.66
#Mann=5,-1,0
  4365.4    0.16       0  4520.9    0.12       0  4997.0    0.07       0
  5003.0    0.12       0  5254.7    0.16       0
Bank Sta=4997,5003
Exp/Cntr=0.3,0.1

Type RM Length L Ch R = 1,7649,525,525,525
BEGIN DESCRIPTION:
NAVASOTA RIVER TRIBUTARY 3.1 13.0
END DESCRIPTION:
XS GIS Cut Line= 3
      3562292.06     10381491.65      3563209.31     10381341.21
      3563642.07     10380891.67
#Sta/Elev= 30
  4355.6  316.12  4388.8  313.82  4445.1  306.56  4450.1  306.82  4467.1  304.58
  4511.4  301.41  4567.6  295.62  4571.0  296.15  4600.9  293.98  4677.9  290.24
  4761.7  290.71  4817.9  289.73  4923.1  290.13  4991.1  289.33  4993.8  288.83
  4997.1  289.33  5105.5  290.36  5135.9  291.23  5237.3  289.91  5303.5  289.81
  5334.8  290.21  5350.5  290.98  5357.4  290.30  5392.9  290.25  5452.0  292.19
  5492.0  293.57  5597.4  295.21  5682.9  296.80  5859.6  303.16  5909.1  303.96
#Mann=10,-1,0
  4355.6    0.16       0  4571.0    0.12       0  4600.9    0.16       0
  4677.9    0.12       0  4991.1    0.07       0  4997.1    0.12       0
  5303.5    0.16       0  5334.8    0.12       0  5452.0    0.16       0
  5597.4    0.12       0
Bank Sta=4991.1,4997.1
Exp/Cntr=0.3,0.1

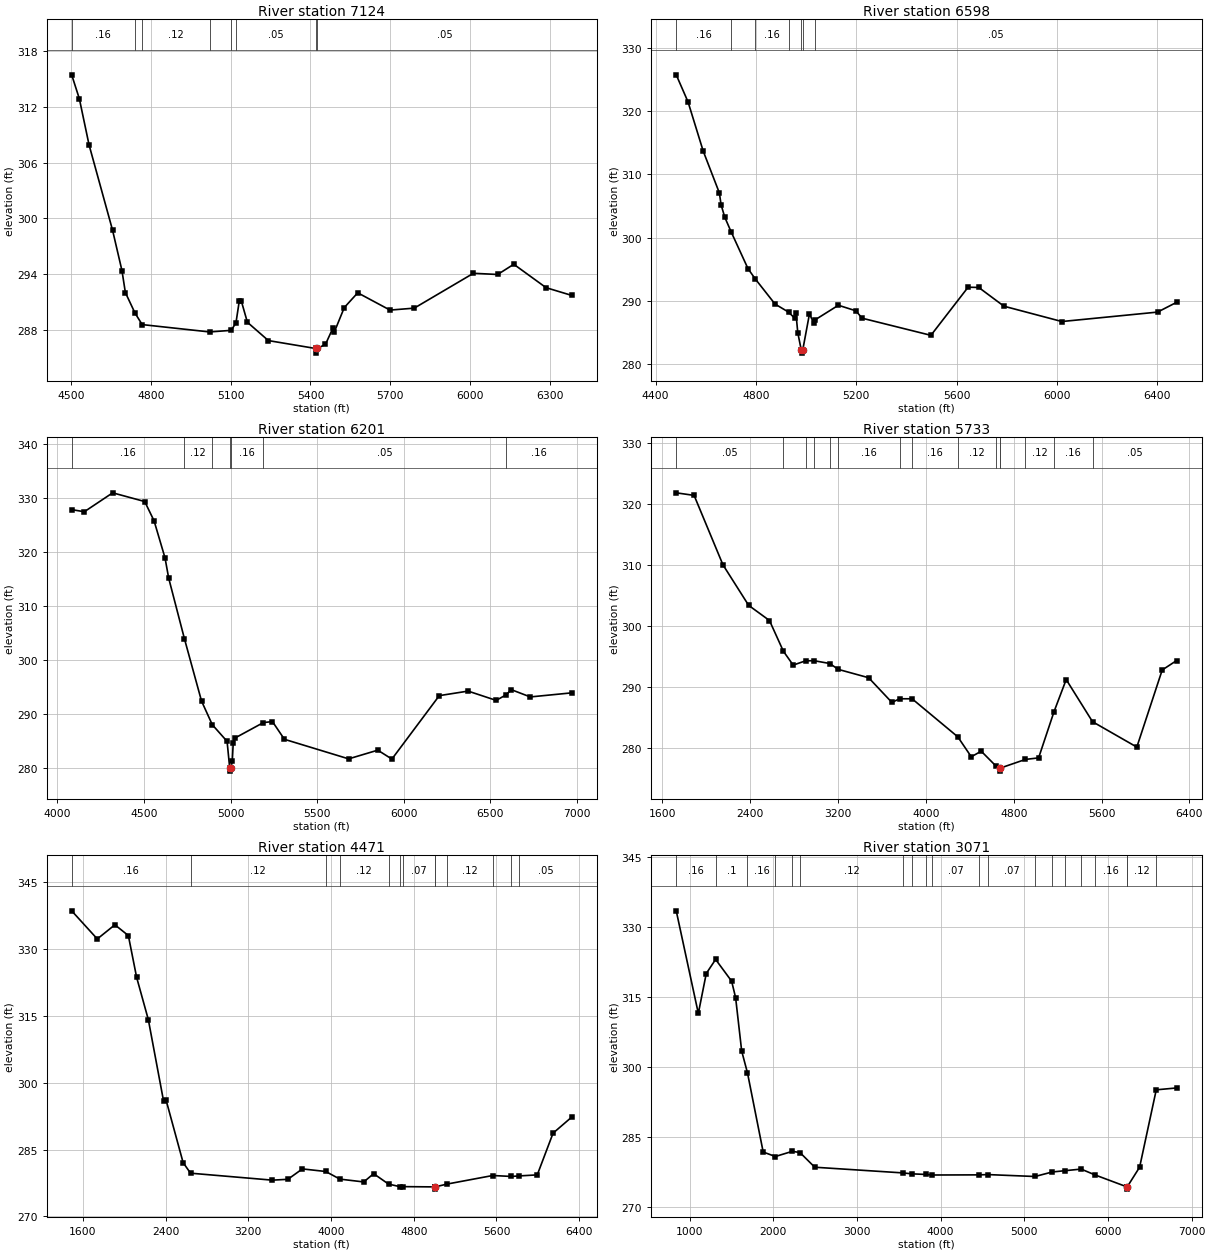
Type RM Length L Ch R = 1,7124,526,526,526
BEGIN DESCRIPTION:
NAVASOTA RIVER TRIBUTARY 3.1 12.0
END DESCRIPTION:
XS GIS Cut Line= 3
      3562292.12     10381541.65      3562965.47     10381966.04
      3564038.46     10381798.62
#Sta/Elev= 30
  4501.8  315.45  4530.6  312.88  4567.1  307.92  4655.4  298.75  4690.9  294.39
  4703.7  292.03  4739.8  289.83  4766.9  288.58  5020.3  287.79  5101.8  287.96
  5119.7  288.77  5132.1  291.10  5140.1  291.09  5162.7  288.83  5241.6  286.86
  5419.2  286.01  5421.9  285.51  5425.2  286.01  5456.3  286.45  5485.0  288.24
  5490.1  287.81  5527.1  290.41  5577.7  292.00  5699.2  290.14  5790.3  290.35
  6012.9  294.10  6104.0  293.97  6164.7  295.07  6286.2  292.55  6383.7  291.71
#Mann=8,-1,0
  4501.8    0.16       0  4739.8     0.1       0  4766.9    0.12       0
  5020.3    0.07       0  5101.8    0.12       0  5119.7    0.05       0
  5419.2    0.07       0  5425.2    0.05       0
Bank Sta=5419.2,5425.2
Exp/Cntr=0.3,0.1

Type RM Length L Ch R = 1,6598,397,397,397
BEGIN DESCRIPTION:
NAVASOTA RIVER TRIBUTARY 3.1 11.0
END DESCRIPTION:
XS GIS Cut Line= 3
      3561982.50     10382019.37      3562683.54     10382301.31
      3563917.53     10382407.95
#Sta/Elev= 30
  4482.2  325.70  4529.4  321.41  4589.6  313.67  4654.2  307.04  4661.0  305.17
  4675.8  303.20  4700.6  300.94  4768.5  295.07  4797.4  293.46  4876.0  289.50
  4929.8  288.23  4954.0  287.28  4959.3  288.02  4966.8  284.95  4980.5  282.25
  4983.3  281.75  4986.5  282.25  5013.1  287.92  5031.5  286.45  5034.6  286.98
  5128.5  289.31  5198.5  288.43  5222.7  287.27  5497.3  284.56  5645.5  292.16
  5688.0  292.12  5788.4  289.16  6019.3  286.74  6400.7  288.23  6476.4  289.77
#Mann=7,-1,0
  4482.2    0.16       0  4700.6    0.12       0  4797.4    0.16       0
  4929.8    0.07       0  4980.5    0.07       0  4986.5    0.07       0
  5034.6    0.05       0
Bank Sta=4980.5,4986.5
Exp/Cntr=0.3,0.1

Type RM Length L Ch R = 1,6201,468,468,468
BEGIN DESCRIPTION:
NAVASOTA RIVER TRIBUTARY 3.1 10.0
END DESCRIPTION:
XS GIS Cut Line= 3
      3561420.80     10382252.72      3562292.11     10382541.64
      3564092.07     10383341.63
#Sta/Elev= 30
  4083.1  327.79  4156.0  327.40  4319.7  330.90  4504.6  329.29  4558.6  325.72
  4621.8  318.86  4642.9  315.12  4733.9  303.89  4832.5  292.37  4894.6  287.99
  4980.0  284.91  4995.4  279.90  4998.2  279.40  5001.4  279.90  5010.0  281.27
  5015.4  284.59  5022.9  285.48  5189.3  288.38  5241.8  288.57  5310.9  285.29
  5681.6  281.67  5849.8  283.28  5931.2  281.63  6204.8  293.37  6371.0  294.21
  6533.1  292.49  6589.9  293.51  6620.7  294.47  6730.1  293.13  6970.8  293.89
#Mann=7,-1,0
  4083.1    0.16       0  4733.9    0.12       0  4894.6    0.16       0
  4995.4    0.07       0  5001.4    0.16       0  5189.3    0.05       0
  6589.9    0.16       0
Bank Sta=4995.4,5001.4
Exp/Cntr=0.3,0.1

Type RM Length L Ch R = 1,5733,1262,1262,1262
BEGIN DESCRIPTION:
NAVASOTA RIVER TRIBUTARY 3.1 9.0
END DESCRIPTION:
XS GIS Cut Line= 3
      3559003.48     10382220.37      3560552.77     10382795.27
      3563442.09     10383091.64
#Sta/Elev= 30
  1726.2  321.81  1889.0  321.39  2151.7  310.01  2386.0  303.36  2575.3  300.88
  2702.2  295.84  2791.4  293.57  2904.0  294.27  2982.3  294.29  3124.9  293.83
  3201.7  292.87  3478.6  291.50  3690.5  287.45  3760.6  288.05  3874.2  288.05
  4290.7  281.81  4413.5  278.54  4503.9  279.46  4641.9  276.96  4671.8  276.69
  4674.6  276.19  4677.8  276.69  4906.8  278.11  5026.7  278.36  5167.0  285.93
  5278.0  291.20  5517.9  284.29  5921.3  280.13  6152.5  292.77  6283.2  294.31
#Mann=15,-1,0
  1726.2    0.05       0  2702.2     0.1       0  2904.0    0.05       0
  2982.3    0.16       0  3124.9    0.05       0  3201.7    0.16       0
  3760.6    0.12       0  3874.2    0.16       0  4290.7    0.12       0
  4641.9    0.07       0  4671.8    0.07       0  4677.8    0.07       0
  4906.8    0.12       0  5167.0    0.16       0  5517.9    0.05       0
Bank Sta=4671.8,4677.8
Exp/Cntr=0.3,0.1

Type RM Length L Ch R = 1,4471,1400,1400,1400
BEGIN DESCRIPTION:
NAVASOTA RIVER TRIBUTARY 3.1 8.0
END DESCRIPTION:
XS GIS Cut Line= 3
      3558794.97     10384129.90      3561572.74     10383967.14
      3563504.16     10383261.85
#Sta/Elev= 30
  1491.8  338.46  1739.4  332.16  1909.6  335.33  2039.9  332.92  2120.0  323.55
  2233.3  314.07  2380.5  295.84  2403.9  296.14  2569.5  282.07  2641.2  279.70
  3432.7  278.14  3582.5  278.33  3722.8  280.66  3948.3  280.08  4086.0  278.37
  4316.2  277.74  4412.1  279.59  4556.0  277.26  4668.6  276.67  4693.7  276.69
  5000.8  276.63  5003.5  276.13  5006.8  276.63  5125.6  277.28  5563.8  279.18
  5744.0  278.97  5821.5  279.09  5994.4  279.32  6147.3  288.67  6330.5  292.32
#Mann=13,-1,0
  1491.8    0.16       0  2641.2    0.12       0  3948.3    0.16       0
  4086.0    0.12       0  4556.0    0.07       0  4668.6    0.12       0
  4693.7    0.07       0  5000.8    0.07       0  5006.8    0.07       0
  5125.6    0.12       0  5563.8    0.16       0  5744.0    0.12       0
  5821.5    0.05       0
Bank Sta=5000.8,5006.8
Exp/Cntr=0.3,0.1

Type RM Length L Ch R = 1,3071,2240,2240,2240
BEGIN DESCRIPTION:
NAVASOTA RIVER TRIBUTARY 3.1 7.0
END DESCRIPTION:
XS GIS Cut Line= 3
      3558567.09     10386039.63      3562006.77     10385106.46
      3564014.14     10383760.98
#Sta/Elev= 30
   839.1  333.46  1103.3  311.44  1198.0  320.01  1309.9  323.03  1501.0  318.37
  1548.9  314.83  1621.4  303.38  1690.9  298.67  1878.5  281.70  2024.1  280.74
  2226.7  281.85  2318.2  281.59  2494.9  278.44  3549.1  277.22  3657.1  277.02
  3822.5  276.89  3900.9  276.77  4459.9  276.80  4564.9  276.86  5127.4  276.45
  5333.6  277.42  5482.6  277.69  5679.1  278.04  5844.6  276.79  6224.4  274.24
  6227.1  273.74  6230.4  274.24  6378.2  278.45  6576.9  295.05  6819.7  295.45
#Mann=20,-1,0
   839.1    0.16       0  1309.9     0.1       0  1690.9    0.16       0
  2024.1    0.12       0  2226.7    0.16       0  2318.2    0.12       0
  3549.1    0.16       0  3657.1    0.07       0  3822.5    0.16       0
  3900.9    0.07       0  4459.9    0.12       0  4564.9    0.07       0
  5127.4    0.12       0  5333.6    0.12       0  5482.6    0.07       0
  5679.1    0.12       0  5844.6    0.16       0  6224.4    0.07       0
  6230.4    0.12       0  6576.9    0.16       0
Bank Sta=6224.4,6230.4
Exp/Cntr=0.3,0.1

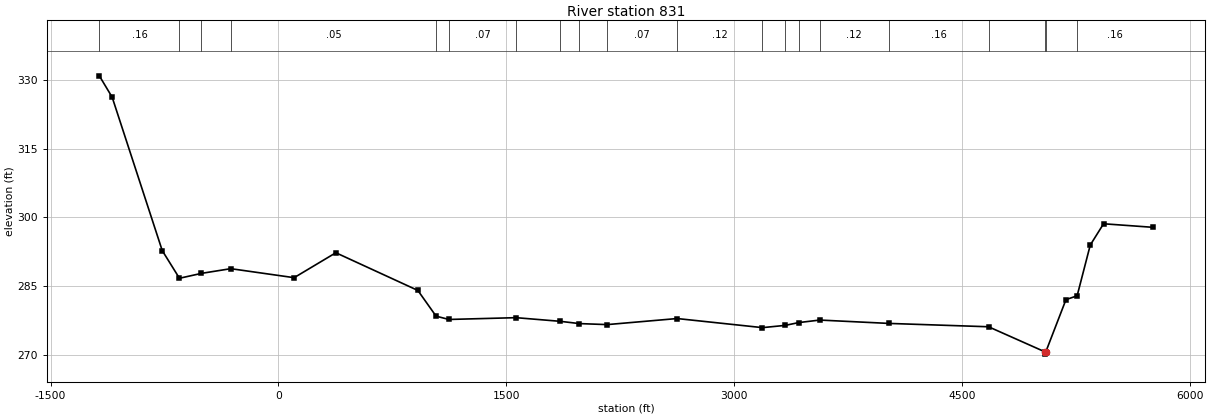
Type RM Length L Ch R = 1,831,0,0,0
BEGIN DESCRIPTION:
NAVASOTA RIVER TRIBUTARY 3.1 1.0
END DESCRIPTION:
XS GIS Cut Line= 3
      3558925.21     10388025.28      3563373.96     10385996.22
      3564491.60     10384281.77
#Sta/Elev= 30
 -1178.7  330.84 -1094.2  326.18  -764.5  292.78  -651.2  286.75  -506.1  287.82
  -313.3  288.84   103.8  286.88   378.6  292.31   918.6  284.10  1038.6  278.50
  1123.1  277.78  1565.4  278.17  1857.5  277.37  1982.3  276.88  2164.8  276.66
  2625.8  277.98  3187.7  276.00  3337.2  276.49  3426.3  277.10  3565.0  277.65
  4019.0  276.92  4676.2  276.19  5047.4  270.73  5050.2  270.23  5053.4  270.73
  5186.1  282.10  5259.6  282.93  5346.1  293.99  5433.7  298.62  5757.5  297.85
#Mann=20,-1,0
 -1178.7    0.16       0  -651.2    0.12       0  -506.1    0.16       0
  -313.3    0.05       0  1038.6    0.16       0  1123.1    0.07       0
  1565.4     0.1       0  1857.5     0.1       0  1982.3    0.16       0
  2164.8    0.07       0  2625.8    0.12       0  3187.7    0.07       0
  3337.2    0.12       0  3426.3    0.07       0  3565.0    0.12       0
  4019.0    0.16       0  4676.2    0.12       0  5047.4    0.07       0
  5053.4    0.12       0  5259.6    0.16       0
Bank Sta=5047.4,5053.4
Exp/Cntr=0.3,0.1

Chan Stop Cuts=-1