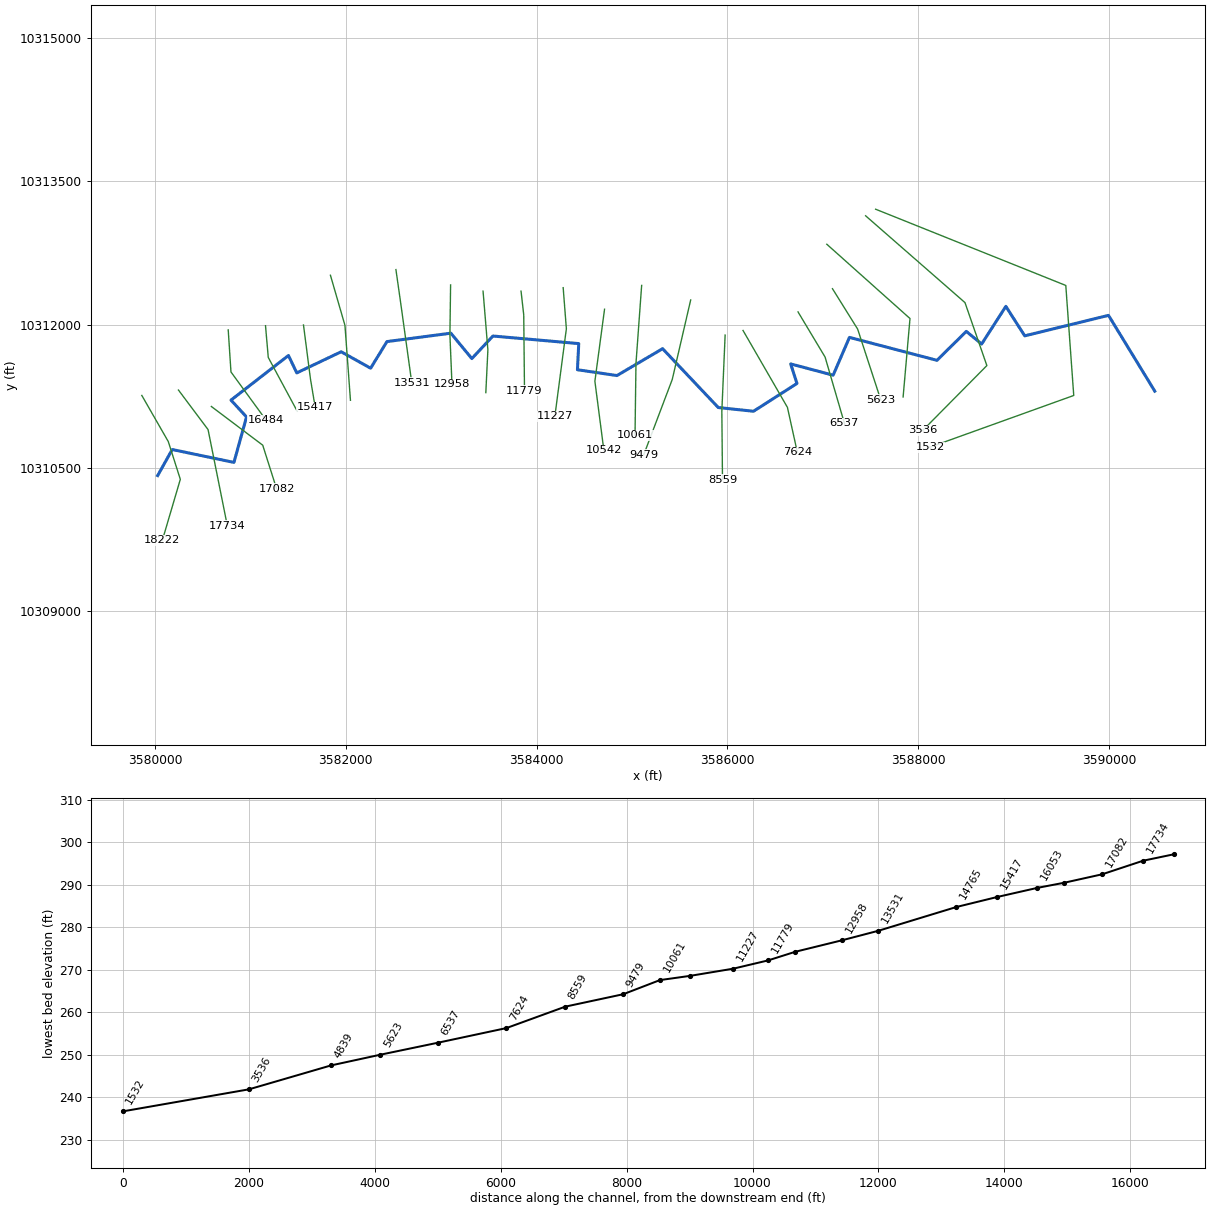
--- NAVASOTA RIVER TRIBUTARY 3.prj (project) ---

Proj Title=NAVASOTA RIVER TRIBUTARY 3 Base Level Engineering
Current Plan=p01
Default Exp/Contr=0.3,0.1
English Units
Geom File=g01
Flow File=f01
Plan File=p01
Y Axis Title=Elevation
X Axis Title(PF)=Main Channel Distance
X Axis Title(XS)=Station
BEGIN DESCRIPTION:
NAVASOTA RIVER TRIBUTARY 3
END DESCRIPTION:
DSS Export Rating Curves= 0
DSS Export Rating Curve Sorted= 0
DSS Export Volume Flow Curves= 0
DXF OffsetX= 0
DXF OffsetY= 0
DXF ScaleX= 1
DXF ScaleY= 10

--- NAVASOTA RIVER TRIBUTARY 3.p01 (plan) ---

Plan Title=Multiple Run
Short Identifier=Multiple
Geom File=g01
Flow File=f01
Subcritical Flow
K Sum by GR= 0
Std Step Tol= 0.01
Critical Tol= 0.01
Num of Std Step Trials= 20
Max Error Tol= 0.3
Flow Tol Ratio= 0.001
Split Flow NTrial= 30
Split Flow Tol= 0.02
Split Flow Ratio= 0.02
Log Output Level= 0
Friction Slope Method= 1
Unsteady Friction Slope Method= 2
Unsteady Bridges Friction Slope Method= 1
Parabolic Critical Depth
Global Vel Dist=  1 , 1 , 1
Global Log Level= 0
CheckData=True
Encroach Param= -1, 0, 0, 0
BEGIN DESCRIPTION:
Multiple Run
END DESCRIPTION:

--- NAVASOTA RIVER TRIBUTARY 3.f01 (steady flow) ---

Flow Title=Multiple
Number of Profiles=7
Profile Names=10-year,25-year,50-year,1pct_min,100-year,1pct_plu,500-year
River Rch & RM= NAVASOTA RIVER T,Reach-1,18222
     635     863    1052     939    1270    1718    1856
River Rch & RM= NAVASOTA RIVER T,Reach-1,13531
     977    1352    1665    1499    2028    2742    3017
Boundary for River Rch & Prof#=NAVASOTA RIVER T,Reach-1,1
Up Type=0
Dn Type=3
Dn Slope=0.005
Boundary for River Rch & Prof#=NAVASOTA RIVER T,Reach-1,2
Up Type=0
Dn Type=3
Dn Slope=0.005
Boundary for River Rch & Prof#=NAVASOTA RIVER T,Reach-1,3
Up Type=0
Dn Type=3
Dn Slope=0.005
Boundary for River Rch & Prof#=NAVASOTA RIVER T,Reach-1,4
Up Type=0
Dn Type=3
Dn Slope=0.005
Boundary for River Rch & Prof#=NAVASOTA RIVER T,Reach-1,5
Up Type=0
Dn Type=3
Dn Slope=0.005
Boundary for River Rch & Prof#=NAVASOTA RIVER T,Reach-1,6
Up Type=0
Dn Type=3
Dn Slope=0.005
Boundary for River Rch & Prof#=NAVASOTA RIVER T,Reach-1,7
Up Type=0
Dn Type=3
Dn Slope=0.005

--- NAVASOTA RIVER TRIBUTARY 3.g01 (geometry) ---

Geom Title=Existing Conditions
Program Version=4.10

River Reach=NAVASOTA RIVER T,Reach-1
Reach XY= 30
      3580029.19     10310417.94      3580181.69     10310690.84
      3580828.54     10310555.91      3580960.49     10311031.79
      3580797.68     10311208.43      3581399.66     10311675.89
      3581487.21     10311493.63      3581952.24     10311714.99
      3582261.23     10311542.72      3582432.11     10311821.64
      3583102.14     10311909.66      3583321.81     10311643.42
      3583542.81     10311879.89      3584442.46     10311800.53
      3584428.78     10311526.57      3584842.94     10311465.76
      3585321.24     10311747.21      3585904.72     10311130.72
      3586274.23     10311091.72      3586729.52     10311382.85
      3586663.62     10311587.67      3587108.62     10311469.53
      3587279.78     10311865.75      3588197.08      10311625.4
      3588504.04     10311928.42      3588665.15     10311796.27
      3588918.77     10312190.79      3589116.58     10311881.93
      3589994.71     10312096.26      3590479.56     10311302.45

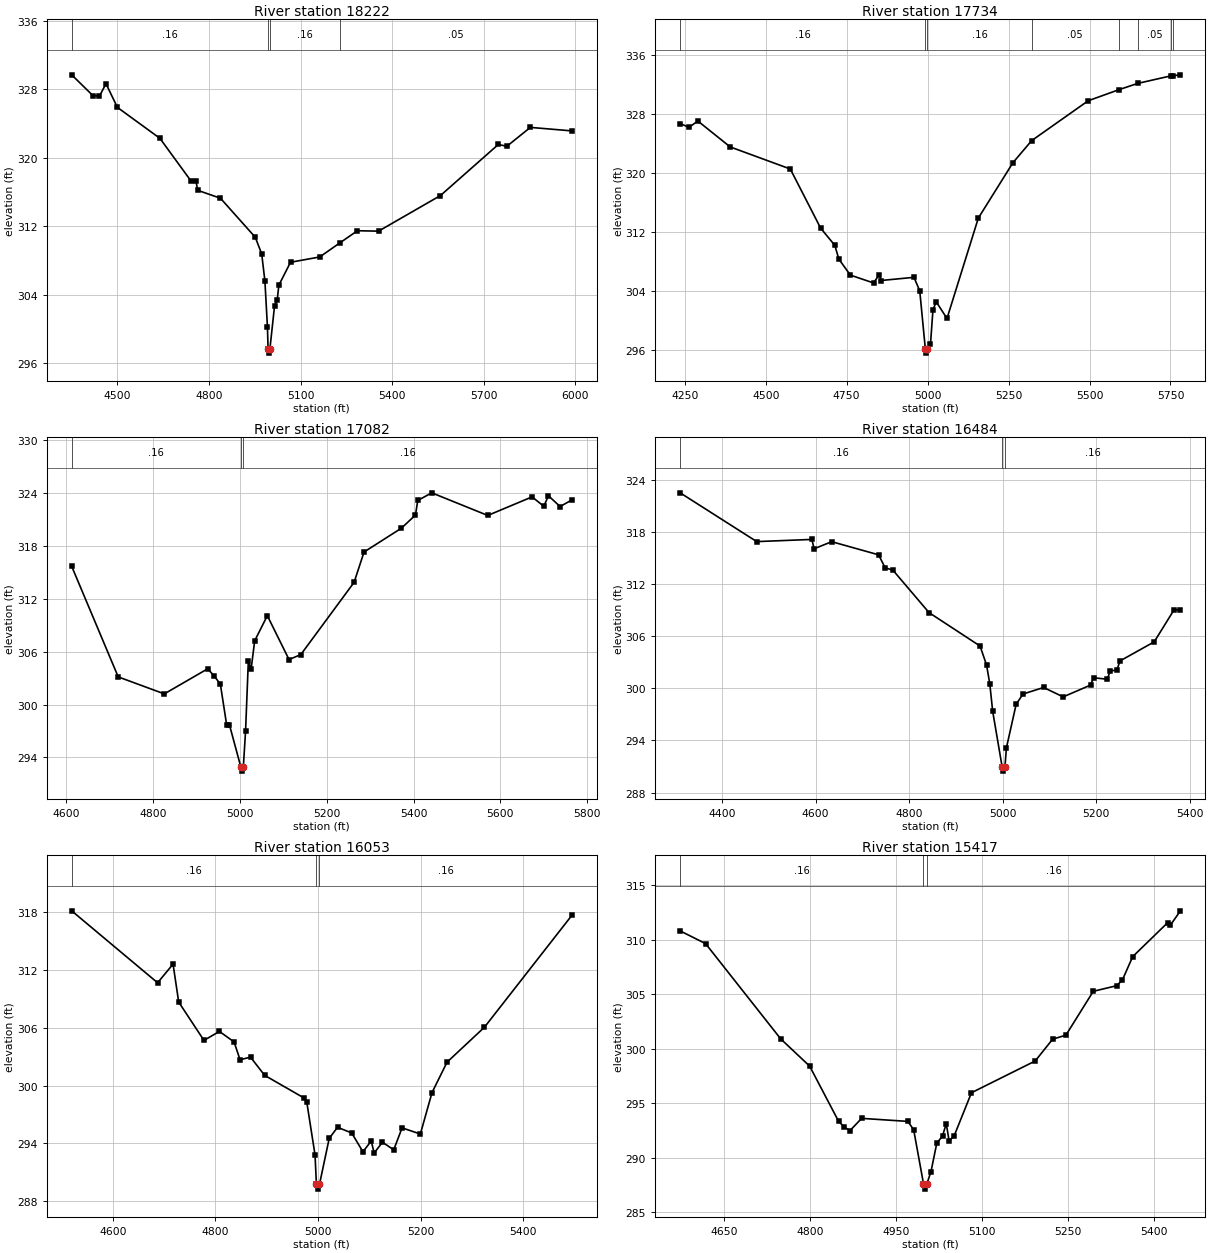
Type RM Length L Ch R = 1 ,18222   ,488,488,488
BEGIN DESCRIPTION:
NAVASOTA RIVER TRIBUTARY 3 8.0
END DESCRIPTION:
XS GIS Cut Line= 4
      3579863.01     10311257.49      3580140.78     10310773.57
      3580266.65     10310378.61      3580077.84     10309738.38
#Sta/Elev= 30
  4349.8  329.71  4419.1  327.29  4440.7  327.21  4462.3  328.67  4499.7   325.9
  4639.1  322.28  4741.2  317.28  4757.1  317.33  4762.8   316.2  4837.6  315.27
  4951.8   310.7  4972.8  308.75  4983.3  305.57  4991.5  300.26  4993.7  297.65
  4996.5  297.15  4999.7  297.65  5014.8  302.66  5023.7   303.4    5029   305.1
  5067.2  307.78    5163   308.4  5227.9  310.02  5286.6  311.47  5355.8  311.42
  5558.9  315.59  5748.4  321.56  5776.5  321.35  5853.5  323.56  5989.8  323.15
#Mann= 4 ,-1 , 0
  4349.8     .16       0  4993.7     .07       0  4999.7     .16       0
  5227.9     .05       0
Bank Sta=4993.7,4999.7
XS Rating Curve= 0 ,0
Exp/Cntr=0.3,0.1

Type RM Length L Ch R = 1 ,17734   ,652,652,652
BEGIN DESCRIPTION:
NAVASOTA RIVER TRIBUTARY 3 7.0
END DESCRIPTION:
XS GIS Cut Line= 3
      3580247.12     10311313.94      3580557.45     10310899.44
      3580759.28     10309892.46
#Sta/Elev= 30
  4235.8  326.71  4263.3   326.2  4290.4  327.06  4390.4  323.55    4576  320.56
  4669.6  312.56  4713.4  310.23  4725.9  308.36  4761.5   306.2  4832.9  305.14
  4850.9  306.27    4856  305.47  4957.9   305.9  4975.7  304.06  4993.1  296.14
  4995.9  295.64  4999.1  296.14  5008.8  296.83  5016.5  301.52  5026.7  302.58
  5059.8  300.33  5156.6  313.92  5263.5  321.42  5321.5  324.41  5495.9   329.8
  5590.2  331.29  5648.9  332.15  5751.3  333.17  5756.5  333.18  5780.6  333.31
#Mann= 8 ,-1 , 0
  4235.8     .16       0  4993.1     .07       0  4999.1     .16       0
  5321.5     .05       0  5590.2     .16       0  5648.9     .05       0
  5751.3     .16       0  5756.5     .05       0
Bank Sta=4993.1,4999.1
XS Rating Curve= 0 ,0
Exp/Cntr=0.3,0.1

Type RM Length L Ch R = 1 ,17082   ,598,598,598
BEGIN DESCRIPTION:
NAVASOTA RIVER TRIBUTARY 3 6.0
END DESCRIPTION:
XS GIS Cut Line= 3
      3580592.12     10311141.63      3581130.43     10310736.16
      3581275.21     10310280.12
#Sta/Elev= 30
  4612.5   315.7  4719.7  303.14  4825.9  301.21  4925.8  304.06  4940.4  303.26
    4955  302.32  4969.6  297.66  4975.8  297.72    5002  292.94  5004.7  292.44
    5008  292.94  5013.1  297.01  5019.5  304.99  5025.8  304.01  5034.1  307.24
  5063.2  310.09  5113.2  305.11  5140.3  305.67  5263.1  313.88    5286  317.32
  5372.2  320.03  5404.5  321.52  5409.7  323.17    5442  324.04    5571  321.47
  5673.1  323.58  5700.1  322.51  5710.8  323.71  5737.6  322.48  5764.9  323.24
#Mann= 3 ,-1 , 0
  4612.5     .16       0    5002     .07       0    5008     .16       0
Bank Sta=5002,5008
XS Rating Curve= 0 ,0
Exp/Cntr=0.3,0.1

Type RM Length L Ch R = 1 ,16484   ,431,431,431
BEGIN DESCRIPTION:
NAVASOTA RIVER TRIBUTARY 3 5.0
END DESCRIPTION:
XS GIS Cut Line= 3
      3580768.51     10311944.95      3580797.46     10311503.43
      3581166.64     10310996.72
#Sta/Elev= 30
  4310.3  322.48    4474  316.87  4591.8  317.12  4596.8  316.05  4634.3  316.86
  4734.5  315.35  4748.4  313.87  4765.2  313.58  4842.4   308.7  4951.4  304.86
  4965.3  302.68  4972.2  300.52  4978.4  297.35  4998.6  290.97  5001.3  290.47
  5004.6  290.97  5007.8  293.16  5028.6  298.16  5043.3  299.34  5087.3  300.09
  5129.1  299.01  5187.8  300.37    5194  301.21  5223.3  301.04  5229.5  301.96
  5244.2  302.13  5250.4  303.14  5323.7  305.34  5365.5  308.97  5379.7  309.06
#Mann= 3 ,-1 , 0
  4310.3     .16       0  4998.6     .07       0  5004.6     .16       0
Bank Sta=4998.6,5004.6
XS Rating Curve= 0 ,0
Exp/Cntr=0.3,0.1

Type RM Length L Ch R = 1 ,16053   ,636,636,636
BEGIN DESCRIPTION:
NAVASOTA RIVER TRIBUTARY 3 4.0
END DESCRIPTION:
XS GIS Cut Line= 3
      3581159.39     10311988.36      3581188.34     10311655.44
       3581492.1     10311091.64
#Sta/Elev= 30
    4520  318.14  4687.4  310.67  4717.5  312.61  4728.5  308.67  4777.7  304.69
  4807.8  305.62  4836.4  304.53    4848  302.68  4868.4  302.95    4896  301.06
  4972.1  298.73  4977.9  298.33  4994.1   292.8  4996.8  289.75  4999.6  289.25
  5002.8  289.75  5021.7  294.51  5037.9  295.67  5065.5  295.08  5087.4  293.13
  5103.6  294.24  5109.3     293  5125.5  294.12  5147.4  293.33  5163.7  295.61
  5199.3  294.97    5222  299.27  5251.3  302.43  5324.2  306.06  5494.6  317.68
#Mann= 3 ,-1 , 0
    4520     .16       0  4996.8     .07       0  5002.8     .16       0
Bank Sta=4996.8,5002.8
XS Rating Curve= 0 ,0
Exp/Cntr=0.3,0.1

Type RM Length L Ch R = 1 ,15417   ,652,652,652
BEGIN DESCRIPTION:
NAVASOTA RIVER TRIBUTARY 3 3.0
END DESCRIPTION:
XS GIS Cut Line= 3
       3581557.5     10311995.64      3581630.31     10311431.73
       3581680.3     10311131.76
#Sta/Elev= 30
  4573.4  310.79  4617.8  309.62  4748.8  300.89  4799.3  298.39  4849.7  293.34
  4859.8  292.79  4869.8  292.48    4890   293.6  4970.7  293.32  4980.8  292.55
  4997.9  287.61  5000.7  287.11  5003.9  287.61    5011  288.72  5021.1  291.32
  5031.2  291.99  5037.6  293.12  5042.6  291.54  5051.3  291.98  5081.6  295.95
  5192.8  298.86  5223.2  300.86  5246.4  301.23  5294.1  305.25  5334.7  305.76
  5344.8  306.28  5362.9  308.43  5423.8  311.54  5428.8  311.33  5446.1  312.63
#Mann= 3 ,-1 , 0
  4573.4     .16       0  4997.9     .07       0  5003.9     .16       0
Bank Sta=4997.9,5003.9
XS Rating Curve= 0 ,0
Exp/Cntr=0.3,0.1

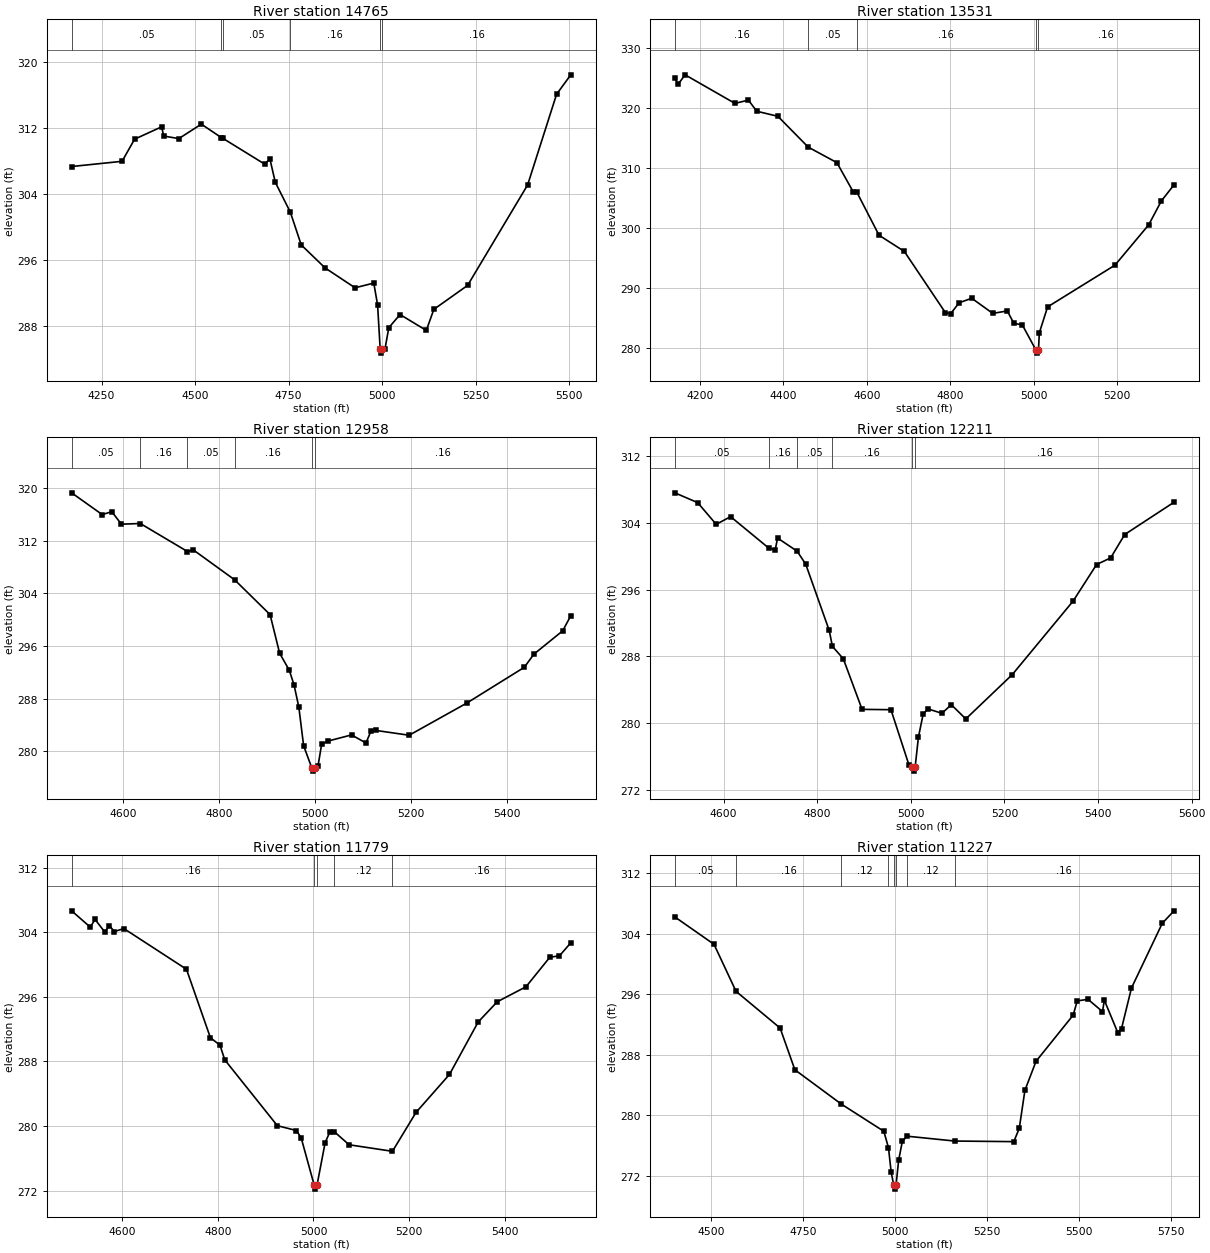
Type RM Length L Ch R = 1 ,14765   ,1234,1234,1234
BEGIN DESCRIPTION:
NAVASOTA RIVER TRIBUTARY 3 1.1
END DESCRIPTION:
XS GIS Cut Line= 3
       3581839.8     10312516.83      3581992.11     10311991.64
      3582049.72     10311206.69
#Sta/Elev= 30
  4170.1  307.33  4304.9  307.96  4338.4  310.64  4410.8  312.14    4416  311.02
  4456.6  310.71  4516.7  312.46  4570.6  310.82    4574  310.75  4685.7  307.63
  4700.1  308.23  4714.3  305.43  4754.6   301.8  4783.7  297.84  4847.3  295.06
  4927.5  292.65  4977.6  293.22  4987.7  290.59  4994.7  285.24  4997.4  284.74
  5000.7  285.24  5007.7  285.29  5017.7  287.82  5047.8  289.41    5118  287.49
  5138.1  290.04  5228.3  292.94  5388.7   305.1  5466.1  316.08    5504  318.43
#Mann= 6 ,-1 , 0
  4170.1     .05       0  4570.6     .16       0    4574     .05       0
  4754.6     .16       0  4994.7     .07       0  5000.7     .16       0
Bank Sta=4994.7,5000.7
XS Rating Curve= 0 ,0
Exp/Cntr=0.3,0.1

Type RM Length L Ch R = 1 ,13531   ,573,573,573
BEGIN DESCRIPTION:
NAVASOTA RIVER TRIBUTARY 3 21.0
END DESCRIPTION:
XS GIS Cut Line= 3
      3582526.29     10312575.95      3582576.29     10312225.95
      3582692.11     10311391.61
#Sta/Elev= 30
  4140.2  324.98  4147.8  323.96  4164.8  325.54  4284.2  320.78  4316.3  321.33
  4336.5  319.47    4387  318.63  4459.6   313.5  4528.4  310.91  4568.1  305.97
  4575.5  306.08  4629.4  298.81  4689.9  296.12  4788.2  285.93    4801  285.74
  4821.2  287.56  4851.5  288.31  4901.9  285.79  4936.7   286.2  4952.4  284.13
  4972.6  283.88  5005.4  279.67  5008.1  279.17  5011.4  279.67  5013.4  282.55
  5033.2  286.87  5194.7  293.83  5275.5  300.55  5305.8  304.53  5336.1  307.21
#Mann= 5 ,-1 , 0
  4140.2     .16       0  4459.6     .05       0  4575.5     .16       0
  5005.4     .07       0  5011.4     .16       0
Bank Sta=5005.4,5011.4
XS Rating Curve= 0 ,0
Exp/Cntr=0.3,0.1

Type RM Length L Ch R = 1 ,12958   ,747,747,747
BEGIN DESCRIPTION:
NAVASOTA RIVER TRIBUTARY 3 20.0
END DESCRIPTION:
XS GIS Cut Line= 3
      3583099.29     10312415.47      3583092.11     10311891.64
       3583113.7     10311374.87
#Sta/Elev= 30
  4491.9   319.3  4555.7  315.99  4575.7  316.43  4595.7  314.53  4635.2  314.63
  4733.5  310.37  4745.8  310.61  4831.8  306.07  4905.8  300.77  4925.8  294.88
  4945.8  292.32  4955.8  290.08  4965.8  286.69  4975.8  280.81  4992.8  277.45
  4995.5  276.95  4998.8  277.45  5005.8  277.72  5013.3  281.01  5025.8  281.51
  5075.8  282.46  5105.9  281.23  5115.9  282.99  5125.9  283.15  5195.9  282.41
    5316   287.3  5436.1  292.75  5456.2  294.76  5516.2   298.3    5533   300.6
#Mann= 6 ,-1 , 0
  4491.9     .05       0  4635.2     .16       0  4733.5     .05       0
  4831.8     .16       0  4992.8     .07       0  4998.8     .16       0
Bank Sta=4992.8,4998.8
XS Rating Curve= 0 ,0
Exp/Cntr=0.3,0.1

Type RM Length L Ch R = 1 ,12211   ,432,432,432
BEGIN DESCRIPTION:
NAVASOTA RIVER TRIBUTARY 3 19.0
END DESCRIPTION:
XS GIS Cut Line= 3
       3583439.5     10312350.33      3583490.17     10311735.06
      3583468.46     10311286.43
#Sta/Elev= 30
  4495.8  307.62  4544.6  306.44  4584.1  303.84  4614.9  304.76  4696.4  300.99
  4710.2  300.78  4715.3  302.19    4757  300.62  4775.4  299.06  4825.6  291.11
  4832.4   289.2  4855.7  287.71  4895.8  281.64  4957.5   281.6  4996.2  274.93
  5003.2  274.73    5006  274.23  5009.2  274.73  5016.2   278.3  5026.3  281.07
  5036.3   281.7  5066.4  281.17  5086.5   282.2  5117.4  280.49  5216.7  285.81
  5346.8  294.64  5396.9  299.02  5426.9  299.81    5457  302.62  5562.3  306.49
#Mann= 6 ,-1 , 0
  4495.8     .05       0  4696.4     .16       0    4757     .05       0
  4832.4     .16       0  5003.2     .07       0  5009.2     .16       0
Bank Sta=5003.2,5009.2
XS Rating Curve= 0 ,0
Exp/Cntr=0.3,0.1

Type RM Length L Ch R = 1 ,11779   ,552,552,552
BEGIN DESCRIPTION:
NAVASOTA RIVER TRIBUTARY 3 18.0
END DESCRIPTION:
XS GIS Cut Line= 3
      3583837.62     10312350.33      3583865.83     10312101.56
      3583873.81     10311307.97
#Sta/Elev= 30
  4494.1  306.64    4533  304.63  4543.1  305.57  4563.2  304.04  4573.3  304.79
  4583.4  304.08  4603.5  304.44  4734.3  299.41  4784.4  290.93  4804.4  290.02
  4814.4   288.2  4924.4  280.05  4964.4  279.45  4974.4  278.51  5001.4   272.7
  5004.1   272.2  5007.4   272.7  5024.4  277.97  5034.4  279.29  5043.8  279.29
  5074.4  277.69  5165.1  276.88  5214.4  281.69  5284.4  286.39  5344.4  292.88
  5384.4  295.39  5444.4  297.24  5494.4   300.9  5514.4  301.07  5538.1  302.68
#Mann= 5 ,-1 , 0
  4494.1     .16       0  5001.4     .07       0  5007.4     .16       0
  5043.8     .12       0  5165.1     .16       0
Bank Sta=5001.4,5007.4
XS Rating Curve= 0 ,0
Exp/Cntr=0.3,0.1

Type RM Length L Ch R = 1 ,11227   ,685,685,685
BEGIN DESCRIPTION:
NAVASOTA RIVER TRIBUTARY 3 17.0
END DESCRIPTION:
XS GIS Cut Line= 3
      3584279.16     10312386.53      3584312.69      10311956.1
      3584192.31     10311040.21
#Sta/Elev= 30
  4402.3   306.2  4508.6  302.59  4568.4  296.38  4688.1  291.53  4728.2  286.02
  4854.3  281.49  4969.7   277.9  4982.4  275.73  4989.8  272.46  4996.9  270.76
  4999.7  270.26  5002.9  270.76    5010  274.08  5020.1  276.58    5033  277.25
  5162.2  276.61  5322.7  276.53  5337.6  278.29  5352.9  283.31  5383.2  287.15
    5484  293.24    5495  295.12  5524.4  295.32  5563.6   293.7  5568.6  295.21
  5605.1  290.93  5615.2  291.45  5642.3  296.82  5726.1  305.38  5757.8  307.01
#Mann= 8 ,-1 , 0
  4402.3     .05       0  4568.4     .16       0  4854.3     .12       0
  4982.4     .16       0  4996.9     .07       0  5002.9     .16       0
    5033     .12       0  5162.2     .16       0
Bank Sta=4996.9,5002.9
XS Rating Curve= 0 ,0
Exp/Cntr=0.3,0.1

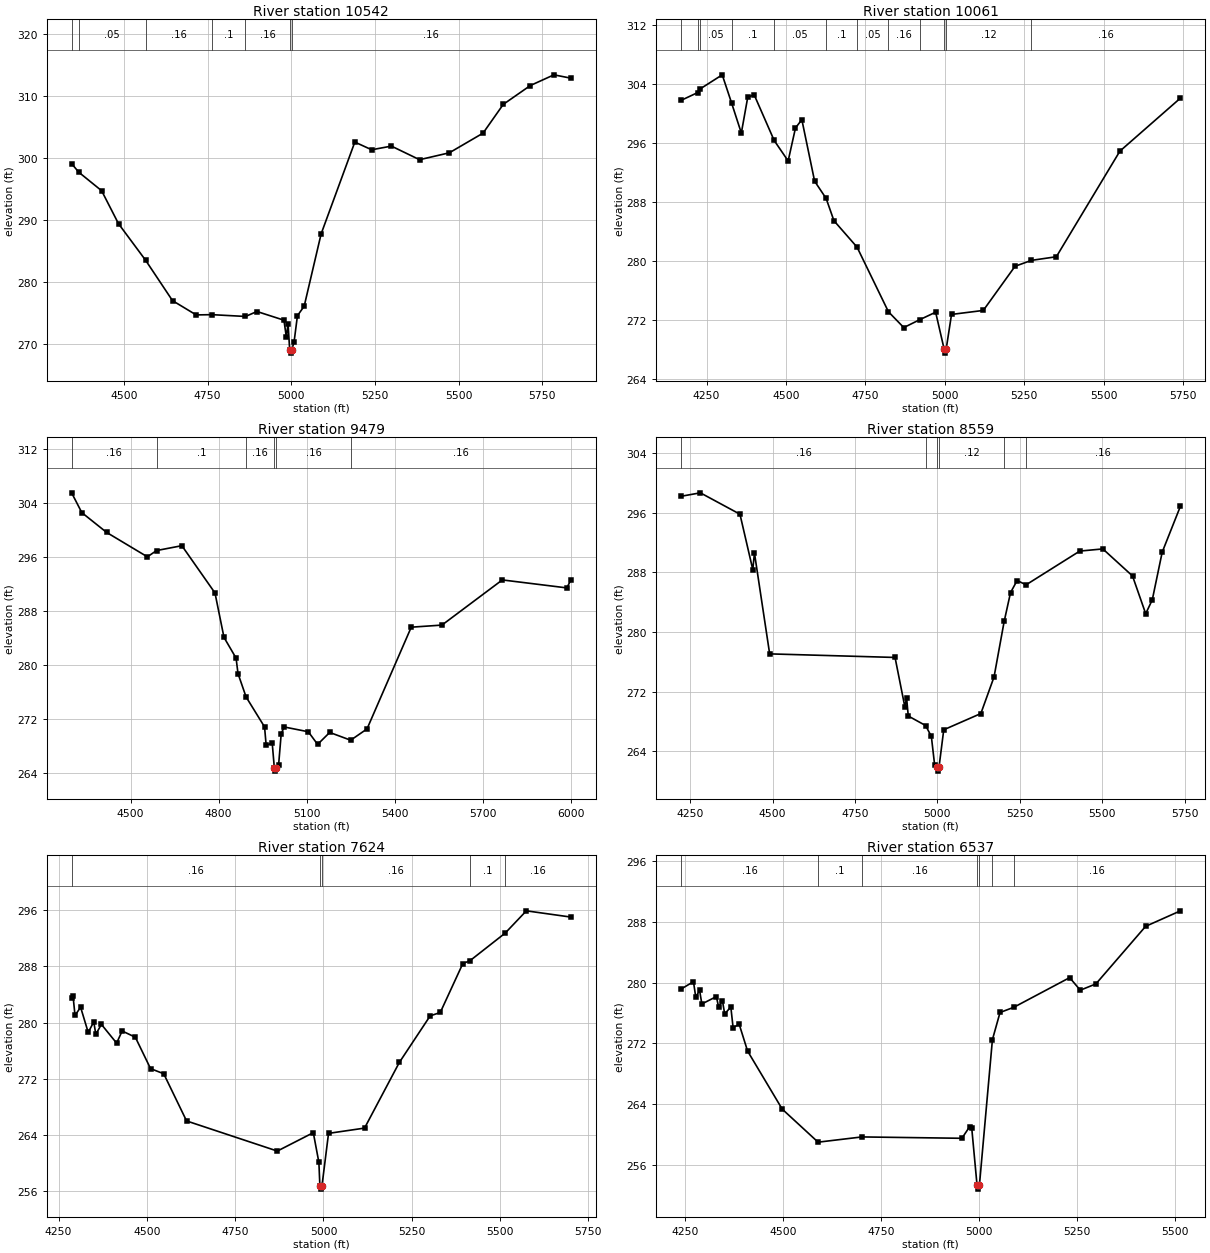
Type RM Length L Ch R = 1 ,10542   ,481,481,481
BEGIN DESCRIPTION:
NAVASOTA RIVER TRIBUTARY 3 16.0
END DESCRIPTION:
XS GIS Cut Line= 3
      3584712.78     10312160.49      3584611.54     10311406.45
      3584705.84     10310681.36
#Sta/Elev= 30
  4343.5  299.11  4365.1  297.72  4433.1  294.75  4483.6  289.43  4564.3  283.56
    4645  277.03  4715.7  274.73  4763.5  274.77  4863.1  274.48  4897.3  275.28
    4978  273.88  4985.2  271.14  4990.2  273.34  4995.2  269.07  4997.9  268.57
  5001.2  269.07  5008.3  270.38  5018.3   274.6  5038.5  276.14    5089  287.77
  5189.8  302.59  5240.2  301.35  5299.1  301.94  5383.3  299.75  5472.2  300.86
    5573  304.03  5633.5  308.67  5714.2   311.7  5784.8  313.43  5835.5  312.89
#Mann= 7 ,-1 , 0
  4343.5     .16       0  4365.1     .05       0  4564.3     .16       0
  4763.5      .1       0  4863.1     .16       0  4995.2     .07       0
  5001.2     .16       0
Bank Sta=4995.2,5001.2
XS Rating Curve= 0 ,0
Exp/Cntr=0.3,0.1

Type RM Length L Ch R = 1 ,10061   ,582,582,582
BEGIN DESCRIPTION:
NAVASOTA RIVER TRIBUTARY 3 14.0
END DESCRIPTION:
XS GIS Cut Line= 3
      3585101.67     10312410.49      3585042.11     10311591.64
      3585032.23     10310841.02
#Sta/Elev= 30
  4170.1   301.8  4222.2  302.85    4230  303.35  4299.3  305.25  4328.7  301.44
  4359.4  297.37  4379.5   302.2  4399.6  302.57  4462.8  296.36  4506.8  293.59
  4529.9  298.06  4549.9  299.18  4590.1  290.85  4626.4  288.51  4650.9   285.5
  4723.7  281.92  4822.5  273.17  4870.8  271.03  4921.2   272.1  4971.1  273.11
  4998.1  268.07  5000.9  267.57  5004.1  268.07  5021.1  272.81  5121.1  273.35
  5221.1  279.33  5272.8  280.13  5351.1  280.62  5551.2  294.92  5741.8   302.1
#Mann= 12 ,-1 , 0
  4170.1     .05       0  4222.2     .16       0    4230     .05       0
  4328.7      .1       0  4462.8     .05       0  4626.4      .1       0
  4723.7     .05       0  4822.5     .16       0  4921.2     .12       0
  4998.1     .07       0  5004.1     .12       0  5272.8     .16       0
Bank Sta=4998.1,5004.1
XS Rating Curve= 0 ,0
Exp/Cntr=0.3,0.1

Type RM Length L Ch R = 1 ,9479    ,920,920,920
BEGIN DESCRIPTION:
NAVASOTA RIVER TRIBUTARY 3 13.0
END DESCRIPTION:
XS GIS Cut Line= 3
      3585615.56     10312257.73      3585422.56     10311425.25
       3585122.5     10310632.71
#Sta/Elev= 30
  4298.7  305.47  4333.4  302.54  4417.9  299.61    4557  295.99  4588.2  296.92
  4674.5  297.64  4787.4  290.64  4818.1  284.06  4859.3  280.99  4865.9   278.7
  4893.4  275.24  4956.4   270.8  4961.9  268.07  4982.5  268.41  4989.7  264.75
  4992.5  264.25  4995.7  264.75  5004.2  265.11  5013.2  269.81  5023.5  270.79
  5105.6  270.08  5137.3  268.21  5178.5  269.98    5250  268.83  5305.7   270.5
  5456.5  285.57  5561.1  285.88  5766.9  292.57  5986.7  291.39  6000.7  292.55
#Mann= 6 ,-1 , 0
  4298.7     .16       0  4588.2      .1       0  4893.4     .16       0
  4989.7     .07       0  4995.7     .16       0    5250     .16       0
Bank Sta=4989.7,4995.7
XS Rating Curve= 0 ,0
Exp/Cntr=0.3,0.1

Type RM Length L Ch R = 1 ,8559    ,935,935,935
BEGIN DESCRIPTION:
NAVASOTA RIVER TRIBUTARY 3 11.0
END DESCRIPTION:
XS GIS Cut Line= 3
      3585976.67     10311889.67      3585942.11     10311091.64
      3585948.89     10310376.25
#Sta/Elev= 30
  4222.9  298.23    4281  298.69  4401.1  295.82    4440  288.39  4445.1   290.6
  4491.2  277.07  4871.5  276.59  4901.3  269.94  4906.4   271.2  4911.6  268.73
  4964.2  267.45  4981.6  265.99  4991.6  262.13  4998.7  261.83  5001.4  261.33
  5004.7  261.83  5019.2  266.88  5131.7  269.06  5171.7  273.97  5202.4  281.42
  5221.7  285.29  5241.7  286.92  5268.9  286.34  5431.7  290.87  5501.7  291.16
  5591.7  287.53  5631.7  282.46  5651.7  284.33  5681.7  290.72  5737.1   296.9
#Mann= 6 ,-1 , 0
  4222.9     .16       0  4964.2     .12       0  4998.7     .07       0
  5004.7     .12       0  5202.4      .1       0  5268.9     .16       0
Bank Sta=4998.7,5004.7
XS Rating Curve= 0 ,0
Exp/Cntr=0.3,0.1

Type RM Length L Ch R = 1 ,7624    ,1087,1087,1087
BEGIN DESCRIPTION:
NAVASOTA RIVER TRIBUTARY 3 9.0
END DESCRIPTION:
XS GIS Cut Line= 3
      3586164.19     10311938.26      3586629.45     10311132.73
      3586733.61     10310660.53
#Sta/Elev= 30
  4286.9  283.47  4290.8  283.84  4296.5  281.02  4312.3   282.2  4333.8  278.61
  4349.6   280.1  4355.4  278.34  4371.2  279.75  4414.3  277.08    4430  278.81
  4467.3  277.92  4510.4  273.45  4547.7  272.72  4612.4     266  4869.4  261.71
  4971.3  264.33  4987.1  260.09  4989.9  256.79  4992.6  256.29  4995.9  256.79
  5014.4  264.23  5116.4  264.98  5214.9  274.33  5302.2  280.96  5330.9  281.45
  5394.7  288.41    5415  288.82  5514.7  292.75  5574.6  295.92  5700.7  295.03
#Mann= 5 ,-1 , 0
  4286.9     .16       0  4989.9     .07       0  4995.9     .16       0
    5415      .1       0  5514.7     .16       0
Bank Sta=4989.9,4995.9
XS Rating Curve= 0 ,0
Exp/Cntr=0.3,0.1

Type RM Length L Ch R = 1 ,6537    ,914,914,914
BEGIN DESCRIPTION:
NAVASOTA RIVER TRIBUTARY 3 7.1
END DESCRIPTION:
XS GIS Cut Line= 3
      3586740.54     10312132.76      3587024.26     10311659.49
       3587226.6     10310966.32
#Sta/Elev= 30
  4240.6  279.15  4271.9  280.11  4277.8  278.06  4287.5  278.98  4293.3  277.18
  4330.3  278.15  4336.1  276.78  4345.8  277.61  4351.6  275.86  4367.2   276.8
    4373  274.08  4388.6  274.51    4410  270.99  4498.4  263.36  4589.9  259.02
  4701.8  259.71  4956.8  259.53  4976.7  261.06  4981.9   260.9  4995.5  253.35
  4998.3  252.85  5001.5  253.35  5034.7  272.49  5054.1  276.06  5089.5  276.75
  5231.8  280.64  5258.9  278.99  5298.8  279.82  5425.6  287.38  5514.5  289.42
#Mann= 7 ,-1 , 0
  4240.6     .16       0  4589.9      .1       0  4701.8     .16       0
  4995.5     .07       0  5001.5     .16       0  5034.7     .12       0
  5089.5     .16       0
Bank Sta=4995.5,5001.5
XS Rating Curve= 0 ,0
Exp/Cntr=0.3,0.1

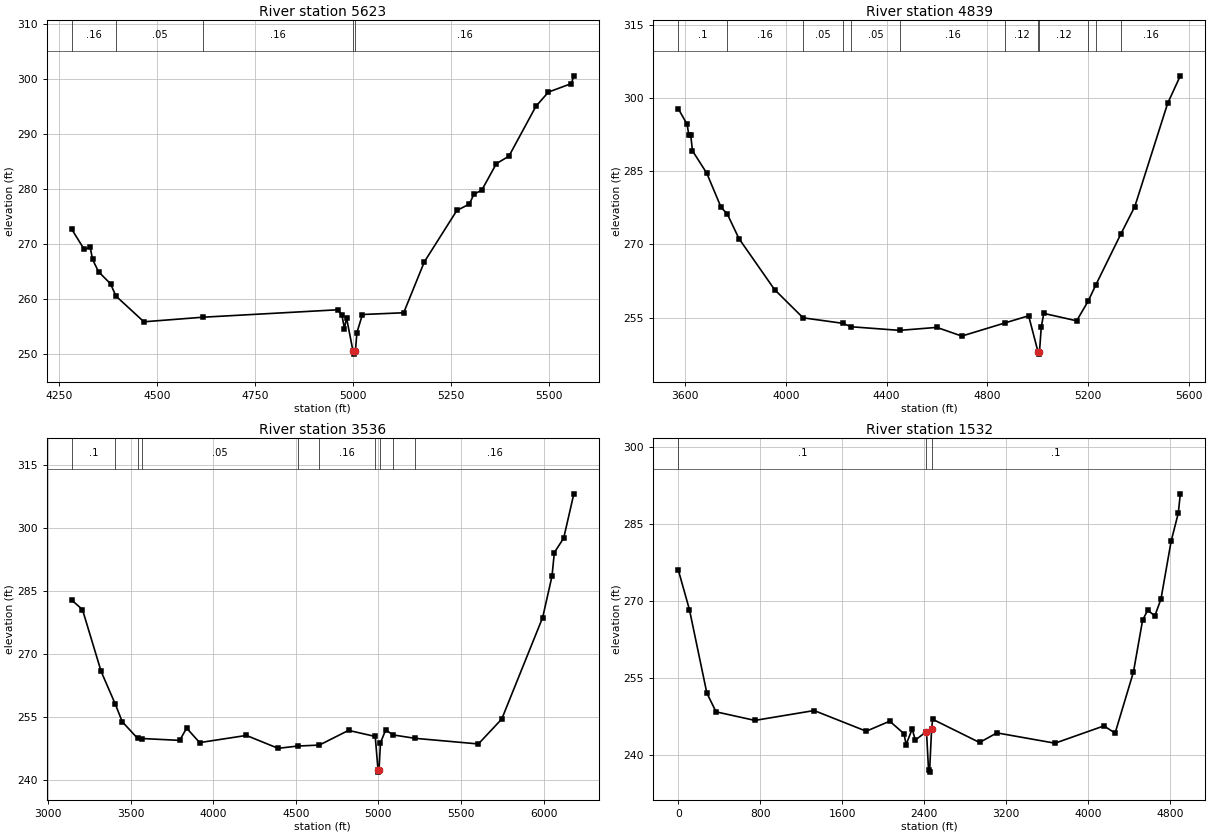
Type RM Length L Ch R = 1 ,5623    ,784,784,784
BEGIN DESCRIPTION:
NAVASOTA RIVER TRIBUTARY 3 6.1
END DESCRIPTION:
XS GIS Cut Line= 3
      3587101.67     10312375.79      3587365.56     10311952.18
      3587608.62      10311209.1
#Sta/Elev= 30
    4282  272.68  4313.8  269.04  4329.1  269.43    4335  267.23  4350.3  264.98
    4381  262.79  4394.5  260.58    4466   255.9  4616.7  256.73  4960.5  258.08
    4971  257.18  4977.7  254.65  4982.9  256.66  4999.6  250.53  5002.3  250.03
  5005.6  250.53  5009.5  253.95  5023.6  257.22  5128.8  257.54  5181.5  266.78
  5264.4   276.1  5296.3  277.26  5307.7  279.03  5328.2  279.81  5365.3  284.61
  5397.2  285.95  5466.2  295.01    5498  297.59  5556.5  299.13  5562.9  300.54
#Mann= 5 ,-1 , 0
    4282     .16       0  4394.5     .05       0  4616.7     .16       0
  4999.6     .07       0  5005.6     .16       0
Bank Sta=4999.6,5005.6
XS Rating Curve= 0 ,0
Exp/Cntr=0.3,0.1

Type RM Length L Ch R = 1 ,4839    ,1303,1303,1303
BEGIN DESCRIPTION:
NAVASOTA RIVER TRIBUTARY 3 4.1
END DESCRIPTION:
XS GIS Cut Line= 3
      3587042.11     10312841.64      3587914.17     10312063.29
      3587842.11     10311241.64
#Sta/Elev= 30
  3572.4  297.83  3607.9  294.59  3614.6  292.33  3622.1   292.4  3628.8   289.2
  3685.7   284.6  3742.5   277.6  3767.3  276.22  3813.6  271.19  3954.9  260.74
  4068.2  254.95  4225.5  253.83  4259.2  253.12  4451.1  252.38  4599.4  252.99
  4698.3  251.21  4871.4  253.93  4963.8  255.37  5000.9  248.01  5003.7  247.51
  5006.9  248.01    5014  253.08    5024  255.86  5154.5  254.34  5200.3  258.39
  5230.6   261.7  5329.5  272.09  5385.4  277.76  5515.9  298.93  5566.1  304.56
#Mann= 12 ,-1 , 0
  3572.4      .1       0  3767.3     .16       0  4068.2     .05       0
  4225.5     .16       0  4259.2     .05       0  4451.1     .16       0
  4871.4     .12       0  5000.9     .07       0  5006.9     .12       0
  5200.3     .16       0  5230.6     .05       0  5329.5     .16       0
Bank Sta=5000.9,5006.9
XS Rating Curve= 0 ,0
Exp/Cntr=0.3,0.1

Type RM Length L Ch R = 1 ,3536    ,2004,2004,2004
BEGIN DESCRIPTION:
NAVASOTA RIVER TRIBUTARY 3 1.0
END DESCRIPTION:
XS GIS Cut Line= 4
       3587448.9     10313139.67      3588490.56     10312229.95
      3588719.73     10311570.23      3588046.63      10310890.2
#Sta/Elev= 30
  3144.5  282.84  3209.2   280.6  3322.2  265.86  3407.8  258.09  3450.3  253.87
  3543.6   249.9  3571.6  249.89  3797.7  249.45  3839.5  252.38  3918.3  248.92
  4201.2  250.63  4392.9  247.56  4512.5   248.1  4642.5  248.33  4819.3  251.83
  4980.9  250.38  4997.7  242.39  5000.4  241.89  5003.7  242.39  5012.7  248.91
  5044.4  251.95  5088.1  250.75  5221.9  249.94    5605   248.6  5746.4  254.53
    5994  278.71  6050.5  288.55  6064.7  294.17  6121.3  297.63  6182.7  308.16
#Mann= 10 ,-1 , 0
  3144.5      .1       0  3407.8     .05       0  3543.6     .07       0
  3571.6     .05       0  4512.5      .1       0  4642.5     .16       0
  4980.9     .05       0  5012.7     .16       0  5088.1     .12       0
  5221.9     .16       0
Bank Sta=4997.7,5003.7
XS Rating Curve= 0 ,0
Exp/Cntr=0.3,0.1

Type RM Length L Ch R = 1 ,1532    ,0,0,0
XS GIS Cut Line= 4
     3587553.993    10313208.457     3589547.049    10312409.846
     3589630.382    10311257.068     3588123.438    10310715.402
#Sta/Elev= 30
       0276.0817109.7554268.2933279.3774252.0903369.1773248.4384748.3323246.7688
1327.043248.68771835.909244.66632065.397246.6194 2205.03244.16182224.957242.0651
2284.739245.0962 2314.63242.9368 2424.23244.59852444.158237.14772454.121236.7042
2474.049245.06012484.012246.99332942.341242.47343111.724244.34133679.093242.3342
4156.602245.69874266.031244.29894445.097256.19344534.629266.2893 4584.37268.2173
4654.007267.11044713.695270.37684813.177281.65814882.813287.08494902.709290.8625
#Mann= 3 ,-1 , 0
       0      .1       0 2424.23     .05       02474.049      .1       0
Bank Sta=2424.23,2474.049
XS Rating Curve= 0 ,0
Exp/Cntr=0.3,0.1

Chan Stop Cuts=-1
Use User Specified Reach Order=0
Composite Channel Slope=5