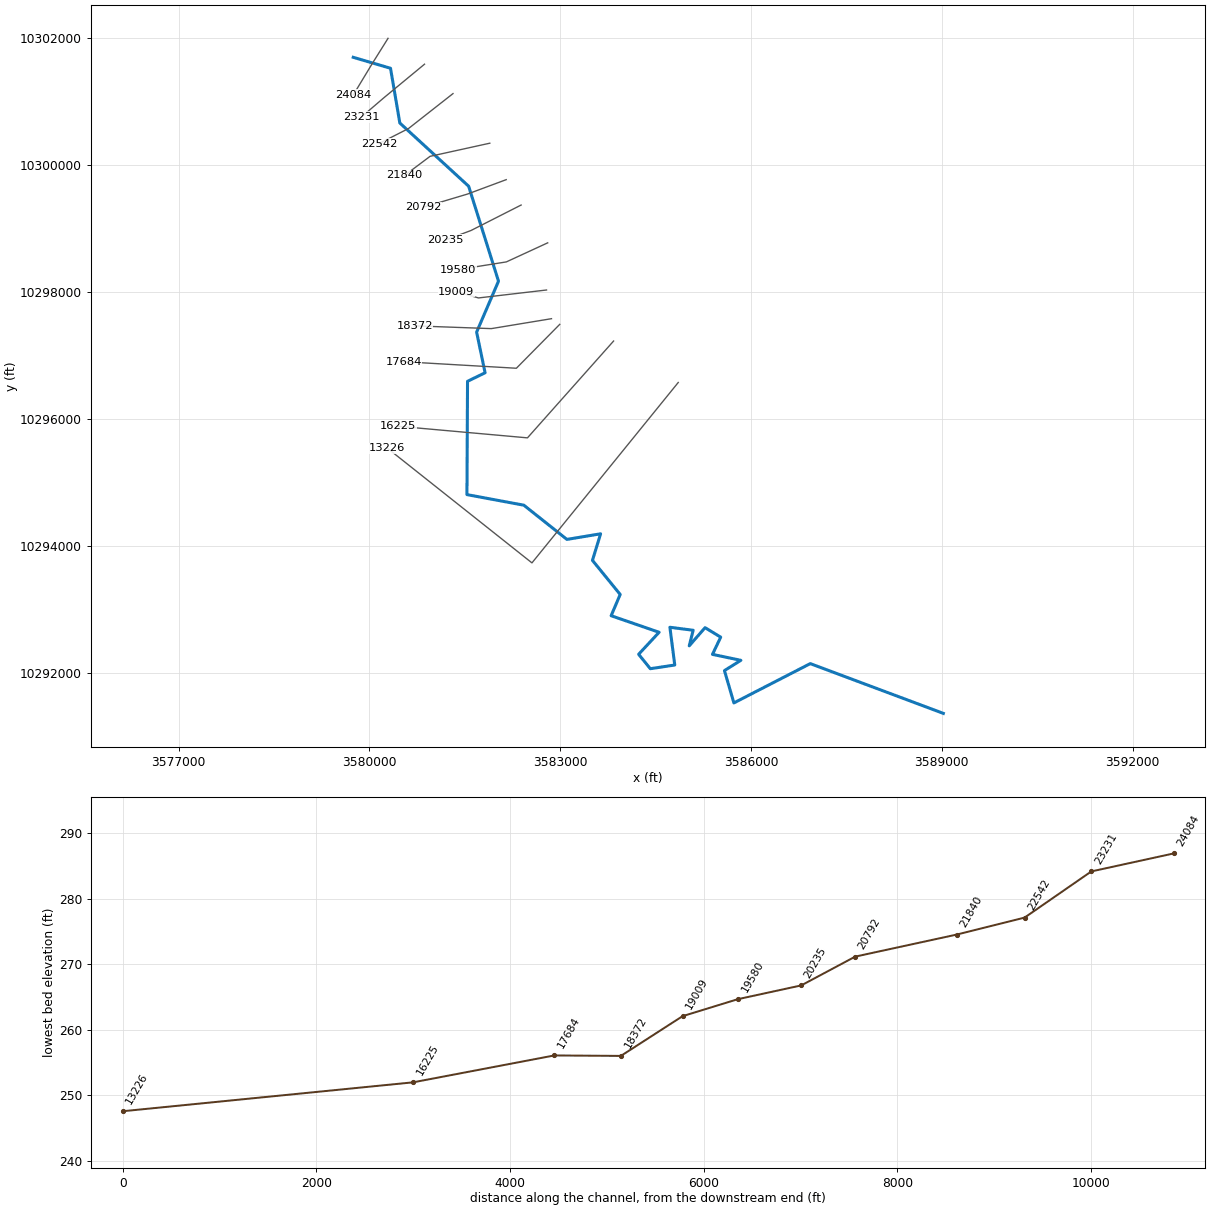
--- OLD CEDAR CREEK.prj (project) ---

Proj Title=OLD CEDAR CREEK Base Level Engineering
Current Plan=p01
Default Exp/Contr=0.3,0.1
English Units
Geom File=g01
Flow File=f01
Plan File=p01
Y Axis Title=Elevation
X Axis Title(PF)=Main Channel Distance
X Axis Title(XS)=Station
BEGIN DESCRIPTION:
OLD CEDAR CREEK
END DESCRIPTION:
DSS Export Rating Curves= 0
DSS Export Rating Curve Sorted= 0
DSS Export Volume Flow Curves= 0
DXF OffsetX= 0
DXF OffsetY= 0
DXF ScaleX= 1
DXF ScaleY= 10

--- OLD CEDAR CREEK.p01 (plan) ---

Plan Title=Multiple Run
Short Identifier=Multiple
Geom File=g01
Flow File=f01
Subcritical Flow
K Sum by GR= 0
Std Step Tol= 0.01
Critical Tol= 0.01
Num of Std Step Trials= 20
Max Error Tol= 0.3
Flow Tol Ratio= 0.001
Split Flow NTrial= 30
Split Flow Tol= 0.02
Split Flow Ratio= 0.02
Log Output Level= 0
Friction Slope Method= 1
Unsteady Friction Slope Method= 2
Unsteady Bridges Friction Slope Method= 1
Parabolic Critical Depth
Global Vel Dist=  1 , 1 , 1
Global Log Level= 0
CheckData=True
Encroach Param= -1, 0, 0, 0
BEGIN DESCRIPTION:
Multiple Run
END DESCRIPTION:

--- OLD CEDAR CREEK.f01 (steady flow) ---

Flow Title=Multiple
Number of Profiles=7
Profile Names=10-year,25-year,50-year,1pct_min,100-year,1pct_plu,500-year
River Rch & RM= OLD CEDAR CREEK,Reach-1,24084
     839    1149    1405    1257    1700    2300    2496
River Rch & RM= OLD CEDAR CREEK,Reach-1,16225
    1026    1417    1742    1566    2118    2864    3138
Boundary for River Rch & Prof#=OLD CEDAR CREEK,Reach-1,1
Up Type=0
Dn Type=3
Dn Slope=0.005
Boundary for River Rch & Prof#=OLD CEDAR CREEK,Reach-1,2
Up Type=0
Dn Type=3
Dn Slope=0.005
Boundary for River Rch & Prof#=OLD CEDAR CREEK,Reach-1,3
Up Type=0
Dn Type=3
Dn Slope=0.005
Boundary for River Rch & Prof#=OLD CEDAR CREEK,Reach-1,4
Up Type=0
Dn Type=3
Dn Slope=0.005
Boundary for River Rch & Prof#=OLD CEDAR CREEK,Reach-1,5
Up Type=0
Dn Type=3
Dn Slope=0.005
Boundary for River Rch & Prof#=OLD CEDAR CREEK,Reach-1,6
Up Type=0
Dn Type=3
Dn Slope=0.005
Boundary for River Rch & Prof#=OLD CEDAR CREEK,Reach-1,7
Up Type=0
Dn Type=3
Dn Slope=0.005

--- OLD CEDAR CREEK.g01 (geometry) ---

Geom Title=Existing Conditions
Program Version=4.10

River Reach=OLD CEDAR CREEK ,Reach-1
Reach XY= 30
      3579745.22     10301693.03      3580331.08     10301520.75
      3580477.59     10300659.47      3581559.76     10299664.48
      3582029.09     10298170.42      3581684.97     10297369.49
      3581818.03     10296729.55      3581542.05     10296595.25
      3581532.95     10294812.45      3582427.66      10294645.9
      3583104.74      10294107.7      3583634.26     10294195.59
      3583506.22     10293777.84       3583942.2     10293241.49
      3583800.27     10292906.85      3584554.18     10292646.44
      3584232.35     10292300.08      3584415.94     10292073.09
      3584800.49     10292131.25       3584724.1       10292725.
      3585089.55     10292678.12      3585027.92     10292433.33
      3585277.05     10292718.92      3585522.71     10292569.61
      3585393.37     10292298.78      3585839.55     10292205.03
      3585581.74     10292043.57      3585730.18     10291534.89
       3586931.2      10292153.3      3589023.23     10291370.38

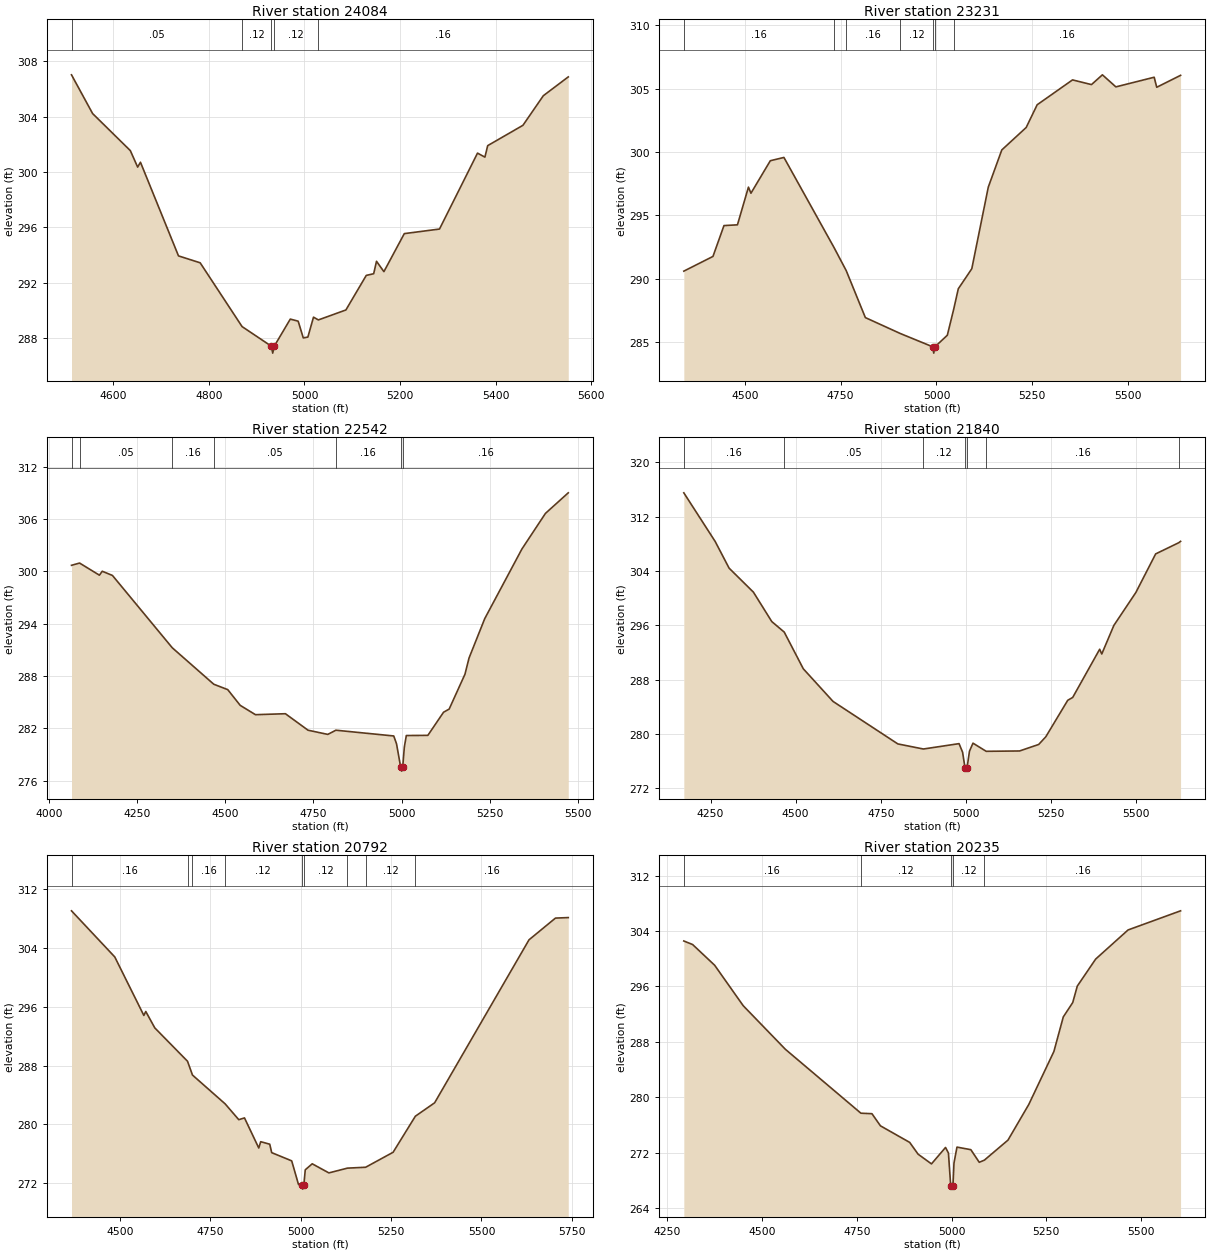
Type RM Length L Ch R = 1 ,24084   ,853,853,853
BEGIN DESCRIPTION:
OLD CEDAR CREEK 25.0
END DESCRIPTION:
XS GIS Cut Line= 3
      3580292.09     10301991.62      3580042.11     10301591.64
      3579748.21     10301105.08
#Sta/Elev= 30
  4512.2  307.02  4556.4  304.22  4635.4  301.54  4650.7  300.35  4656.6   300.7
  4736.2  293.93  4781.6  293.43  4869.3  288.82  4930.7   287.4  4933.5   286.9
  4936.7   287.4  4970.3  289.36  4986.8  289.21  4997.5     288  5007.1  288.06
  5018.9   289.5  5029.1   289.3  5086.7  290.02  5129.4  292.52  5144.9  292.64
  5150.8  293.54  5166.3  292.79    5209  295.54  5282.7  295.87  5362.3  301.36
  5377.8  301.07  5383.6   301.9  5457.4  303.37  5500.1  305.51  5552.3  306.87
#Mann= 5 ,-1 , 0
  4512.2     .05       0  4869.3     .12       0  4930.7     .07       0
  4936.7     .12       0  5029.1     .16       0
Bank Sta=4930.7,4936.7
XS Rating Curve= 0 ,0
Exp/Cntr=0.3,0.1

Type RM Length L Ch R = 1 ,23231   ,689,689,689
BEGIN DESCRIPTION:
OLD CEDAR CREEK 24.0
END DESCRIPTION:
XS GIS Cut Line= 3
      3580865.93     10301584.87      3580223.02     10301053.47
        3579873.     10300753.45
#Sta/Elev= 30
  4341.3  290.61  4417.3  291.77    4446   294.2  4481.1  294.26  4509.8  297.23
  4516.3  296.75  4566.8  299.31  4602.3  299.57  4733.3  292.45  4764.7  290.65
  4814.6  286.95  4905.4   285.7  4990.1  284.65  4992.9  284.15  4996.1  284.65
  5028.3  285.56    5045  287.62  5056.9  289.22  5092.1   290.8  5135.1  297.23
  5170.3  300.16  5233.9  301.93  5262.5  303.72  5354.7  305.68  5404.1  305.31
  5432.6  306.08  5467.7  305.13  5567.6  305.89  5574.2   305.1  5636.4  306.04
#Mann= 7 ,-1 , 0
  4341.3     .16       0  4733.3     .05       0  4764.7     .16       0
  4905.4     .12       0  4990.1     .07       0  4996.1     .12       0
    5045     .16       0
Bank Sta=4990.1,4996.1
XS Rating Curve= 0 ,0
Exp/Cntr=0.3,0.1

Type RM Length L Ch R = 1 ,22542   ,702,702,702
BEGIN DESCRIPTION:
OLD CEDAR CREEK 22.0
END DESCRIPTION:
XS GIS Cut Line= 3
      3581313.66     10301122.22      3580613.63      10300572.2
      3580150.92     10300336.39
#Sta/Elev= 30
  4063.6   300.7  4086.5  300.96  4142.8  299.57  4150.9  300.02  4179.8  299.54
  4349.5  291.25  4467.3  287.07    4507  286.45  4542.3  284.65  4585.6  283.58
  4670.6  283.69  4734.8   281.8  4790.8  281.32  4813.8   281.8    4978  281.14
  4985.9  280.24  4997.5  277.61  5000.2  277.11  5003.5  277.61  5008.1  279.89
  5013.7  281.19  5074.8  281.21  5119.3  283.86  5135.2  284.22  5180.1  288.22
  5191.6  290.07  5236.2  294.59  5341.7  302.57  5408.4  306.65  5473.2  309.01
#Mann= 7 ,-1 , 0
  4063.6     .16       0  4086.5     .05       0  4349.5     .16       0
  4467.3     .05       0  4813.8     .16       0  4997.5     .07       0
  5003.5     .16       0
Bank Sta=4997.5,5003.5
XS Rating Curve= 0 ,0
Exp/Cntr=0.3,0.1

Type RM Length L Ch R = 1 ,21840   ,1048,1048,1048
BEGIN DESCRIPTION:
OLD CEDAR CREEK 20.0
END DESCRIPTION:
XS GIS Cut Line= 3
      3581892.13     10300341.65      3580953.22     10300135.05
      3580554.32     10299835.87
#Sta/Elev= 30
  4171.3  315.53  4263.5  308.36  4304.4  304.43  4375.9  300.89  4429.8  296.56
  4466.4  295.01  4522.5   289.6  4609.9  284.79  4800.3  278.53  4875.5  277.78
  4980.2  278.57  4990.6  277.31  4997.7  275.02  5000.5  274.52  5003.7  275.02
  5010.9  277.46  5021.2  278.64    5060  277.44  5158.1  277.49  5214.3  278.45
  5235.2  279.58  5299.7  284.96  5314.3  285.38  5393.5  292.48  5399.7  291.78
  5435.2  295.99  5499.7  300.83  5558.1  306.53    5626  308.18  5631.3  308.38
#Mann= 7 ,-1 , 0
  4171.3     .16       0  4466.4     .05       0  4875.5     .12       0
  4997.7     .07       0  5003.7     .12       0    5060     .16       0
    5626     .05       0
Bank Sta=4997.7,5003.7
XS Rating Curve= 0 ,0
Exp/Cntr=0.3,0.1

Type RM Length L Ch R = 1 ,20792   ,557,557,557
BEGIN DESCRIPTION:
OLD CEDAR CREEK 18.0
END DESCRIPTION:
XS GIS Cut Line= 3
      3582150.23     10299768.01      3581542.11     10299541.64
       3580848.2       10299334.
#Sta/Elev= 30
  4366.7  309.07  4486.3  302.79  4566.7  294.82    4572  295.36    4597  293.12
  4687.4  288.58  4701.1   286.7  4791.3  282.78  4829.1  280.62  4844.9  280.86
  4884.4  276.76  4889.7  277.62  4914.7  277.28  4920.1  276.13  4975.4  275.01
  4994.2  271.79  5002.8  271.66  5005.5  271.16  5008.8  271.66  5012.9  273.79
  5032.1  274.61  5078.2  273.37  5129.5  274.02  5179.8  274.14  5255.7  276.18
  5317.2  281.09  5370.5  282.92  5631.4  305.12  5704.5  308.08  5739.9  308.15
#Mann= 9 ,-1 , 0
  4366.7     .16       0  4687.4     .12       0  4701.1     .16       0
  4791.3     .12       0  5002.8     .07       0  5008.8     .12       0
  5129.5     .16       0  5179.8     .12       0  5317.2     .16       0
Bank Sta=5002.8,5008.8
XS Rating Curve= 0 ,0
Exp/Cntr=0.3,0.1

Type RM Length L Ch R = 1 ,20235   ,655,655,655
BEGIN DESCRIPTION:
OLD CEDAR CREEK 17.0
END DESCRIPTION:
XS GIS Cut Line= 3
      3582384.69     10299368.74      3581596.62     10298968.03
      3581196.89     10298818.13
#Sta/Elev= 30
  4293.2  302.56  4316.4  302.05  4374.6  299.06  4449.9  293.23  4561.2  286.94
  4760.6  277.72  4789.7  277.65  4812.1   275.9  4889.3  273.51  4911.5  271.81
  4946.8  270.41  4983.9  272.78  4991.6  271.97  4997.5  267.27  5000.3  266.77
  5003.5  267.27  5006.2  270.53  5014.1  272.83  5050.7  272.46  5072.9  270.64
  5086.4  270.95  5148.7  273.84  5203.5  278.97  5269.8  286.61  5294.7  291.61
  5319.6  293.68  5331.6  296.05  5380.1  299.95  5465.6  304.15  5604.2  306.91
#Mann= 5 ,-1 , 0
  4293.2     .16       0  4760.6     .12       0  4997.5     .07       0
  5003.5     .12       0  5086.4     .16       0
Bank Sta=4997.5,5003.5
XS Rating Curve= 0 ,0
Exp/Cntr=0.3,0.1

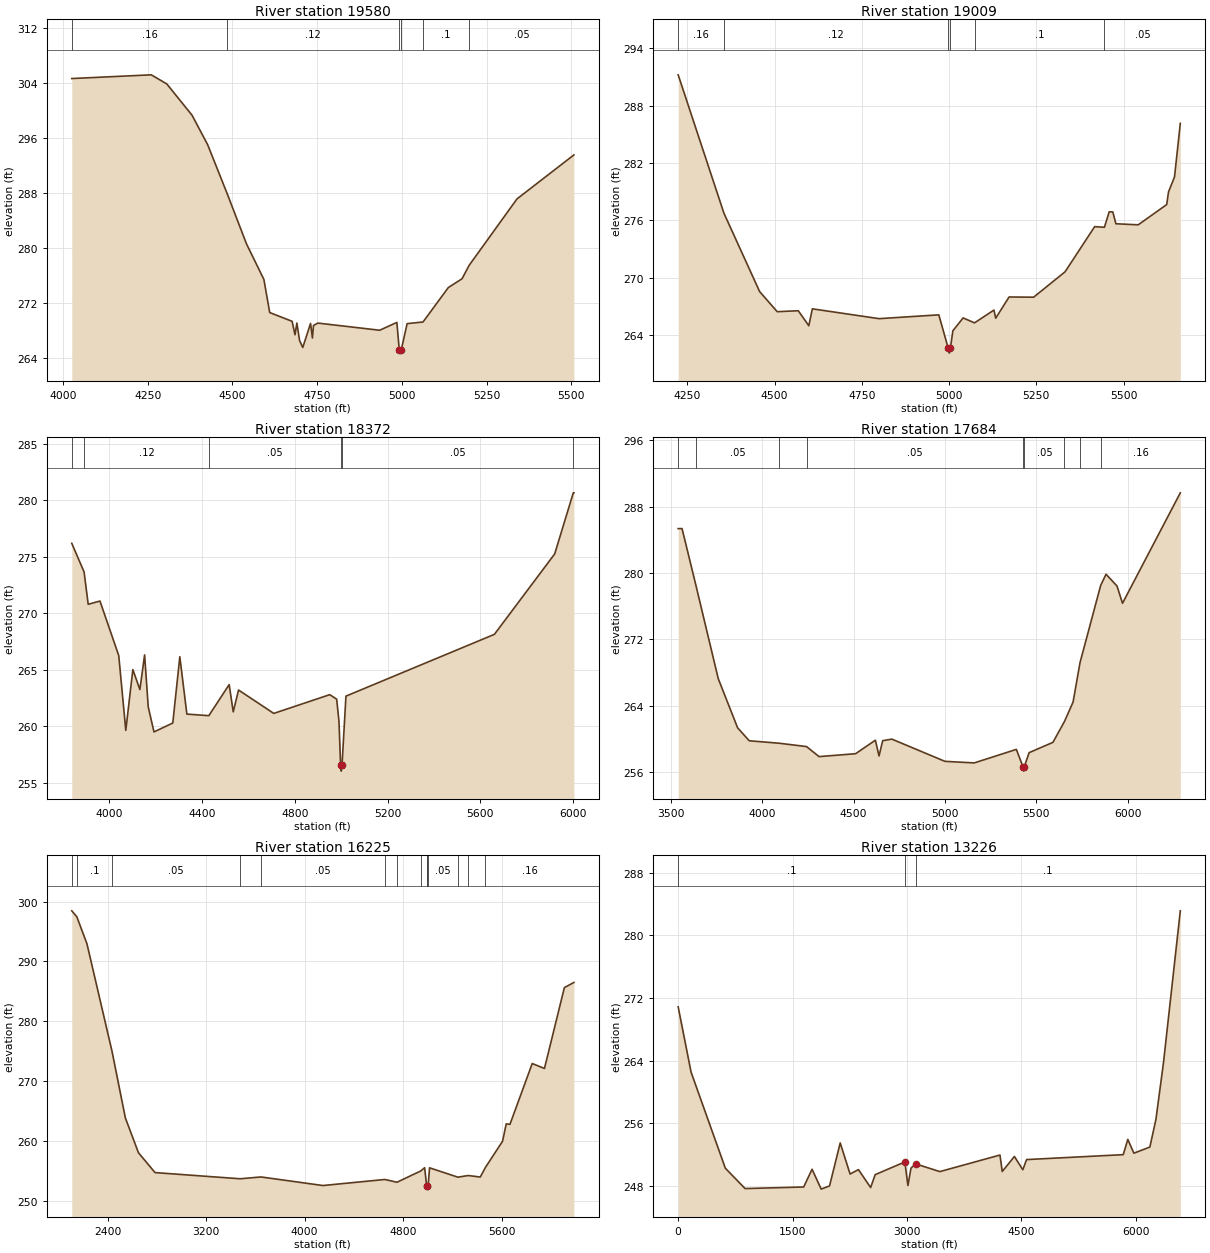
Type RM Length L Ch R = 1 ,19580   ,571,571,571
BEGIN DESCRIPTION:
OLD CEDAR CREEK 15.0
END DESCRIPTION:
XS GIS Cut Line= 3
      3582802.54     10298773.94      3582152.52     10298473.93
       3581396.1     10298353.26
#Sta/Elev= 30
  4025.8  304.62  4260.5  305.16  4306.4  303.83  4380.8  299.28  4426.7  295.01
  4484.8  287.83  4541.4  280.57  4592.8  275.39    4610  270.57  4676.1   269.3
  4684.6  267.34  4690.1  269.05  4698.1  266.51  4707.5  265.49  4730.5  268.99
    4736  266.87  4739.2   268.7  4752.3  269.04  4934.5     268  4985.2  269.14
  4992.3  265.17    4995  264.67  4998.3  265.17  5015.5  268.96  5062.4   269.2
  5137.1  274.21  5177.6  275.49  5198.4  277.43  5339.6   287.1  5507.7  293.51
#Mann= 6 ,-1 , 0
  4025.8     .16       0  4484.8     .12       0  4992.3     .07       0
  4998.3     .12       0  5062.4      .1       0  5198.4     .05       0
Bank Sta=4992.3,4998.3
XS Rating Curve= 0 ,0
Exp/Cntr=0.3,0.1

Type RM Length L Ch R = 1 ,19009   ,637,637,637
BEGIN DESCRIPTION:
OLD CEDAR CREEK 14.0
END DESCRIPTION:
XS GIS Cut Line= 3
      3582783.97     10298031.91      3581714.33     10297906.92
      3581366.18     10298006.39
#Sta/Elev= 30
  4223.6  291.23  4354.7  276.74    4457  268.53  4507.4  266.42  4567.8  266.52
    4598  264.95  4608.1  266.72  4799.4  265.69  4970.5  266.09  4997.7  262.58
  5000.5  262.08  5003.7  262.58  5010.8  264.42  5040.2  265.77  5072.9  265.25
  5128.6  266.59  5133.6  265.74  5171.9  267.96  5242.3  267.94  5332.4   270.6
  5417.2  275.33  5445.1  275.26  5458.8  276.88  5469.2  276.87    5478  275.63
    5542  275.52  5623.6  277.64  5628.8  278.96    5646  280.54  5662.6  286.15
#Mann= 6 ,-1 , 0
  4223.6     .16       0  4354.7     .12       0  4997.7     .07       0
  5003.7     .12       0  5072.9      .1       0  5445.1     .05       0
Bank Sta=4997.7,5003.7
XS Rating Curve= 0 ,0
Exp/Cntr=0.3,0.1

Type RM Length L Ch R = 1 ,18372   ,688,688,688
BEGIN DESCRIPTION:
OLD CEDAR CREEK 13.0
END DESCRIPTION:
XS GIS Cut Line= 3
      3582862.09     10297580.52       3581915.9     10297424.27
      3580709.29     10297467.68
#Sta/Elev= 30
  3837.3  276.19  3890.4  273.66  3908.2  270.79  3958.9  271.08    4040  266.25
  4070.4  259.63  4100.8  265.01  4131.2  263.24  4151.5  266.31  4167.3   261.7
    4192  259.49  4273.1  260.28  4303.5  266.15  4333.9  261.07  4428.6  260.93
  4516.4  263.68  4533.9  261.27  4556.9   263.2  4708.9  261.13  4950.2  262.79
  4980.2  262.39  4990.2  260.41  4997.2  256.52    5000  256.02  5003.2  256.52
  5020.2  262.66  5660.7  268.13  5920.8  275.25  6001.1  280.66  6003.7  280.66
#Mann= 6 ,-1 , 0
  3837.3     .16       0  3890.4     .12       0  4428.6     .05       0
  4997.2     .03       0  5003.2     .05       0  6001.1      .1       0
Bank Sta=4997.2,5003.2
XS Rating Curve= 0 ,0
Exp/Cntr=0.3,0.1

Type RM Length L Ch R = 1 ,17684   ,1459,1459,1459
BEGIN DESCRIPTION:
OLD CEDAR CREEK 11.0
END DESCRIPTION:
XS GIS Cut Line= 3
      3582992.12     10297491.66      3582310.15     10296800.69
      3580536.36      10296903.4
#Sta/Elev= 30
  3540.4  285.33  3561.6  285.34  3635.7  278.66  3759.6  267.25  3865.7  261.31
  3929.4  259.75  4094.5  259.45    4243  259.05  4311.2  257.84  4511.2  258.19
  4619.5  259.82  4639.5  257.92  4659.5  259.76  4709.6  259.95  5000.1  257.27
  5160.4  257.08  5390.8  258.71  5427.8  256.59  5430.6  256.09  5433.8  256.59
  5460.9  258.32  5591.1  259.56    5654  262.07  5701.3  264.42  5739.1  269.16
  5852.3  278.49  5881.6  279.83  5941.7  278.41  5971.7  276.33    6288  289.65
#Mann= 9 ,-1 , 0
  3540.4     .16       0  3635.7     .05       0  4094.5     .12       0
    4243     .05       0  5427.8     .03       0  5433.8     .05       0
    5654     .16       0  5739.1     .05       0  5852.3     .16       0
Bank Sta=5427.8,5433.8
XS Rating Curve= 0 ,0
Exp/Cntr=0.3,0.1

Type RM Length L Ch R = 1 ,16225   ,2999,2999,2999
BEGIN DESCRIPTION:
OLD CEDAR CREEK 1.0
END DESCRIPTION:
XS GIS Cut Line= 3
      3583838.65     10297228.97      3582484.48     10295705.52
      3580455.13     10295887.64
#Sta/Elev= 30
  2109.8  298.46    2151  297.46  2232.9  292.97  2436.8  274.98  2544.8  263.88
    2651  258.07  2785.7  254.75    3476  253.72  3646.3  254.02  4148.1  252.59
    4651   253.6  4749.4  253.14  4943.4  255.03  4973.8  255.57  4990.9  252.49
  4993.6  251.99  4996.9  252.49  5002.5  252.54  5013.9  255.55  5243.5  253.99
  5327.7  254.26  5425.6  254.01  5467.8  255.62  5606.3  259.98  5636.4  262.88
  5666.6  262.81  5847.3  272.96  5946.7  272.14  6108.3  285.64  6185.6   286.5
#Mann= 14 ,-1 , 0
  2109.8     .05       0    2151      .1       0  2436.8     .05       0
    3476     .12       0  3646.3     .05       0    4651      .1       0
  4749.4     .05       0  4943.4      .1       0  4990.9     .07       0
  4996.9      .1       0  5002.5     .05       0  5243.5     .16       0
  5327.7     .05       0  5467.8     .16       0
Bank Sta=4990.9,4996.9
XS Rating Curve= 0 ,0
Exp/Cntr=0.3,0.1

Type RM Length L Ch R = 1 ,13226   ,0,0,0
XS GIS Cut Line= 3
     3584855.257    10296576.813     3582554.909    10293738.271
     3580280.604    10295543.827
#Sta/Elev= 30
       0270.8621169.5519262.5124618.3657250.2571877.6804247.65271645.651247.8561
1755.361250.12331875.044247.58321984.755247.99572124.385253.48522254.043249.5126
2363.753250.07622523.331247.78622583.173249.43432972.145251.0556 3012.04248.0483
 3052.39  250.263111.776250.81123430.932 249.8224218.988251.93684248.917249.8337
4408.537251.75414518.276 250.0584568.157251.35655835.142251.98595894.999253.9322
5974.809252.1741 6184.31252.9574 6264.12 256.5136363.883263.8175 6583.36283.1281
#Mann= 3 , 0 , 0
       0      .1       02972.145     .05       03111.776      .1       0
Bank Sta=2972.145,3111.776
XS Rating Curve= 0 ,0
Exp/Cntr=0.3,0.1

Chan Stop Cuts=-1
Use User Specified Reach Order=0
Composite Channel Slope=5