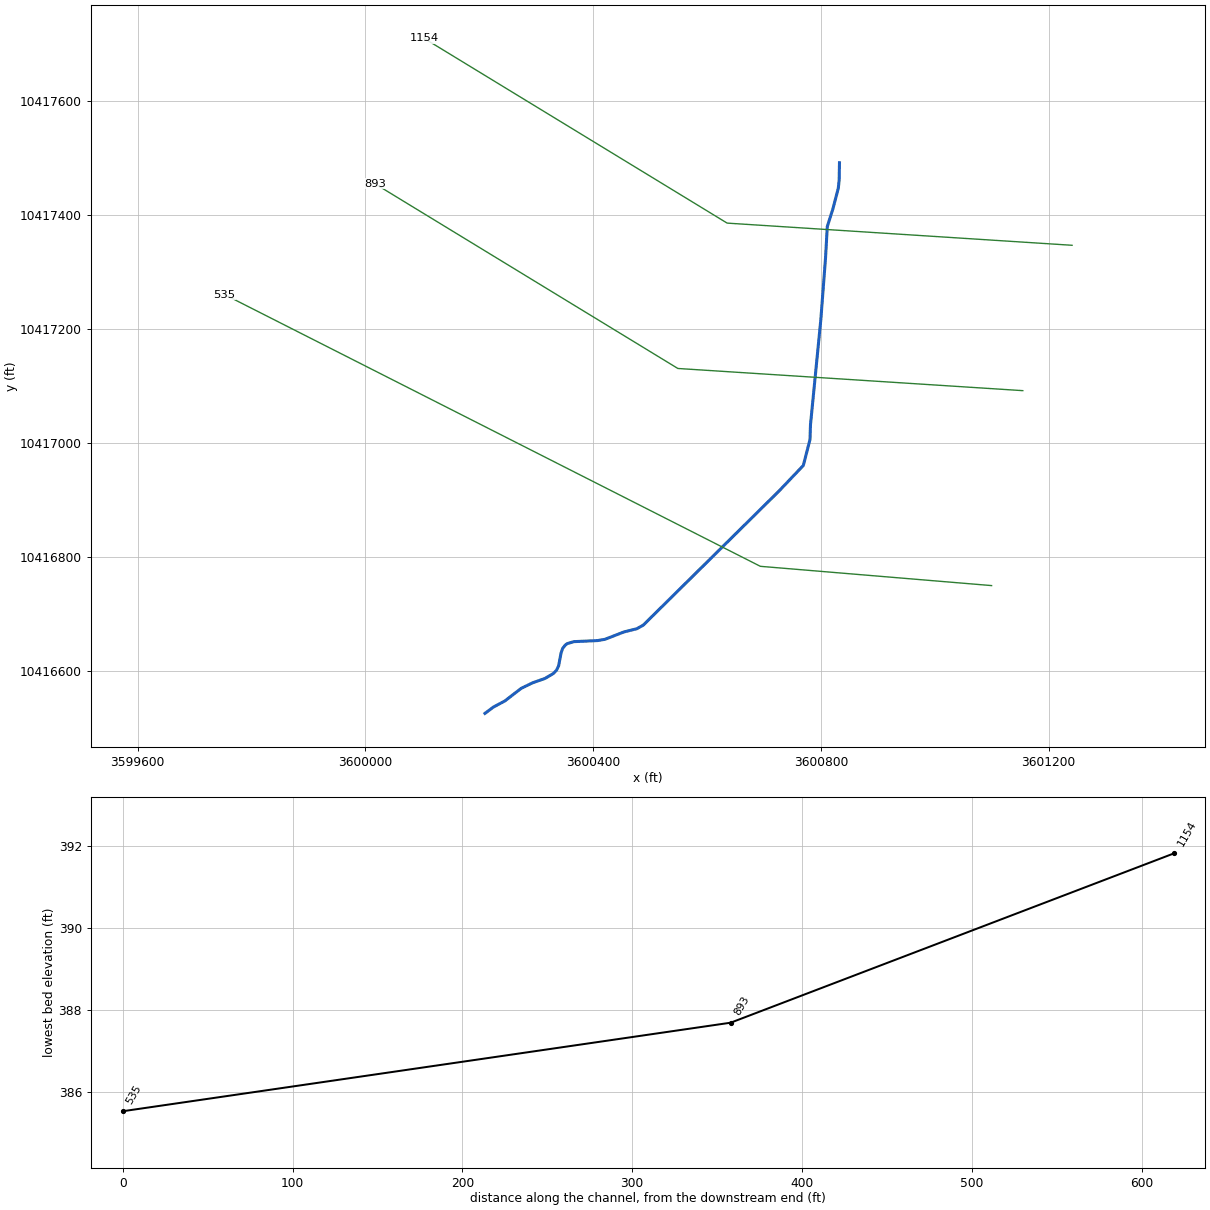
--- ORCHARD BRANCH.prj (project) ---

Proj Title=ORCHARD BRANCH Base Level Engineering
Current Plan=p01
Default Exp/Contr=0.3,0.1
English Units
Geom File=g01
Flow File=f01
Plan File=p01
BEGIN DESCRIPTION:
ORCHARD BRANCH
END DESCRIPTION:

--- ORCHARD BRANCH.p01 (plan) ---

Plan Title=Multiple Run
Short Identifier=Multiple
Geom File=g01
Flow File=f01
Subcritical Flow
K Sum by GR= 0
Std Step Tol= 0.01
Critical Tol= 0.01
Num of Std Step Trials= 20
Max Error Tol= 0.3
Flow Tol Ratio= 0.001
Split Flow NTrial= 30
Split Flow Tol= 0.02
Split Flow Ratio= 0.02
Log Output Level= 0
Friction Slope Method= 1
Unsteady Friction Slope Method= 2
Unsteady Bridges Friction Slope Method= 1
Parabolic Critical Depth
Global Vel Dist=  1 , 1 , 1
Global Log Level= 0
CheckData=True
Encroach Param= -1, 0, 0, 0
BEGIN DESCRIPTION:
Multiple Run
END DESCRIPTION:

--- ORCHARD BRANCH.f01 (steady flow) ---

Flow Title=Multiple
Number of Profiles=7
Profile Names=10-year,25-year,50-year,1pct_min,100-year,1pct_plu,500-year
River Rch & RM= ORCHARD BRANCH,Reach-1,1154
    1287    1807    2246    2038    2756    3728    4138
Boundary for River Rch & Prof#=ORCHARD BRANCH,Reach-1,1
Up Type=0
Dn Type=3
Dn Slope=0.005
Boundary for River Rch & Prof#=ORCHARD BRANCH,Reach-1,2
Up Type=0
Dn Type=3
Dn Slope=0.005
Boundary for River Rch & Prof#=ORCHARD BRANCH,Reach-1,3
Up Type=0
Dn Type=3
Dn Slope=0.005
Boundary for River Rch & Prof#=ORCHARD BRANCH,Reach-1,4
Up Type=0
Dn Type=3
Dn Slope=0.005
Boundary for River Rch & Prof#=ORCHARD BRANCH,Reach-1,5
Up Type=0
Dn Type=3
Dn Slope=0.005
Boundary for River Rch & Prof#=ORCHARD BRANCH,Reach-1,6
Up Type=0
Dn Type=3
Dn Slope=0.005
Boundary for River Rch & Prof#=ORCHARD BRANCH,Reach-1,7
Up Type=0
Dn Type=3
Dn Slope=0.005

--- ORCHARD BRANCH.g01 (geometry) ---

Geom Title=Existing Conditions

River Reach=ORCHARD BRANCH,Reach-1
Reach XY= 30
      3600832.71     10417492.06      3600832.17     10417461.62
      3600830.60     10417447.26      3600821.01     10417410.67
      3600811.29     10417380.06      3600808.26     10417325.80
      3600800.01     10417217.30      3600781.78     10417031.97
      3600780.91     10417005.92      3600769.19     10416960.35
      3600727.09     10416916.08      3600487.88     10416679.74
      3600476.72     10416673.56      3600454.01     10416667.89
      3600420.73     10416654.95      3600407.55     10416652.72
      3600366.33     10416650.87      3600354.58     10416647.43
      3600351.37     10416645.21      3600346.47     10416639.18
      3600343.61     10416630.98      3600339.31     10416608.30
      3600335.62     10416600.70      3600330.06     10416594.84
      3600315.18     10416586.12      3600293.62     10416578.55
      3600273.44     10416568.71      3600244.79     10416546.60
      3600225.00     10416536.07      3600209.88     10416524.84

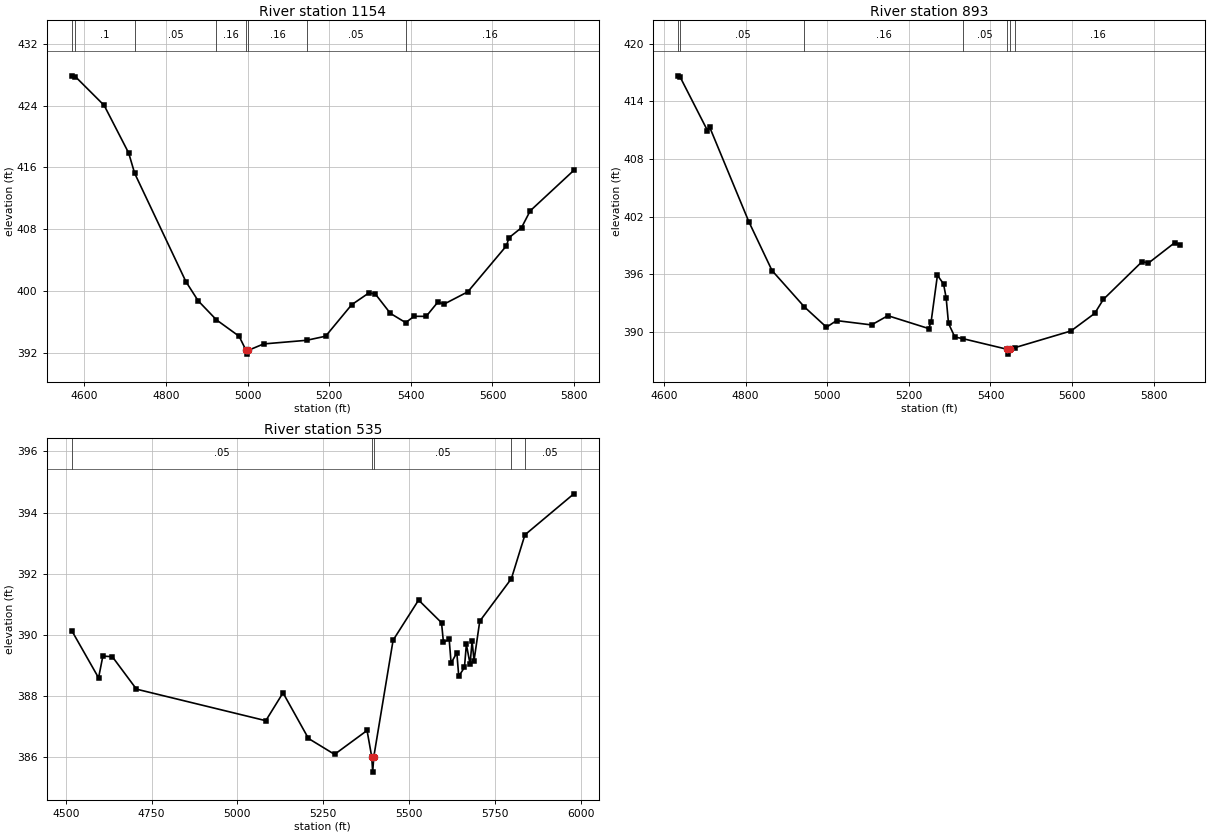
Type RM Length L Ch R = 1,1154,261,261,261
BEGIN DESCRIPTION:
ORCHARD BRANCH 3.0
END DESCRIPTION:
XS GIS Cut Line= 3
      3601241.31     10417347.15      3600635.36     10417386.10
      3600103.02     10417710.70
#Sta/Elev= 30
  4568.8  427.86  4577.9  427.74  4648.2  424.03  4708.3  417.86  4722.9  415.24
  4848.6  401.20  4878.6  398.72  4923.4  396.25  4978.9  394.13  4995.9  392.31
  4998.6  391.81  5001.9  392.31  5039.0  393.13  5144.3  393.60  5191.0  394.13
  5254.9  398.21  5297.5  399.75  5313.0  399.59  5349.8  397.09  5387.2  395.89
  5407.9  396.71  5437.5  396.70  5466.0  398.54  5481.4  398.29  5539.5  399.88
  5634.4  405.85  5640.3  406.88  5671.2  408.19  5692.5  410.37  5799.5  415.62
#Mann=8,-1,0
  4568.8    0.05       0  4577.9     0.1       0  4722.9    0.05       0
  4923.4    0.16       0  4995.9    0.07       0  5001.9    0.16       0
  5144.3    0.05       0  5387.2    0.16       0
Bank Sta=4995.9,5001.9
Exp/Cntr=0.3,0.1

Type RM Length L Ch R = 1,893,358,358,358
BEGIN DESCRIPTION:
ORCHARD BRANCH 2.0
END DESCRIPTION:
XS GIS Cut Line= 3
      3601154.70     10417091.79      3600548.79     10417130.74
      3600016.76     10417455.15
#Sta/Elev= 30
  4634.9  416.64  4640.1  416.47  4706.6  410.94  4711.6  411.33  4807.9  401.46
  4864.7  396.38  4944.1  392.59  4998.2  390.48  5022.8  391.17  5108.5  390.72
  5148.6  391.68  5248.7  390.34  5254.6  391.06  5270.0  395.88  5285.0  394.99
  5291.4  393.54  5297.2  390.87  5312.7  389.46  5332.4  389.29  5441.3  388.18
  5444.1  387.68  5447.3  388.18  5459.4  388.35  5597.3  390.09  5655.4  391.92
  5676.7  393.38  5771.6  397.31  5787.0  397.15  5851.0  399.26  5865.2  399.07
#Mann=7,-1,0
  4634.9     0.1       0  4640.1    0.05       0  4944.1    0.16       0
  5332.4    0.05       0  5441.3    0.07       0  5447.3    0.05       0
  5459.4    0.16       0
Bank Sta=5441.3,5447.3
Exp/Cntr=0.3,0.1

Type RM Length L Ch R = 1,535,0,0,0
BEGIN DESCRIPTION:
ORCHARD BRANCH 1.0
END DESCRIPTION:
XS GIS Cut Line= 3
      3601099.91     10416749.33      3600693.68     10416783.18
      3599752.37     10417260.60
#Sta/Elev= 30
  4517.5  390.14  4595.6  388.60  4608.1  389.31  4635.7  389.29  4706.0  388.23
  5082.9  387.20  5133.1  388.11  5207.2  386.62  5283.3  386.10  5378.0  386.88
  5391.6  386.02  5394.4  385.52  5397.6  386.02  5453.9  389.83  5528.2  391.14
  5595.0  390.40  5600.6  389.76  5617.3  389.86  5622.9  389.08  5639.6  389.42
  5645.2  388.65  5661.8  388.94  5667.4  389.69  5678.2  389.05  5684.1  389.80
  5689.7  389.16  5706.4  390.45  5798.6  391.84  5838.0  393.27  5980.6  394.61
#Mann=5,-1,0
  4517.5    0.05       0  5391.6    0.03       0  5397.6    0.05       0
  5798.6    0.16       0  5838.0    0.05       0
Bank Sta=5391.6,5397.6
Exp/Cntr=0.3,0.1

Chan Stop Cuts=-1