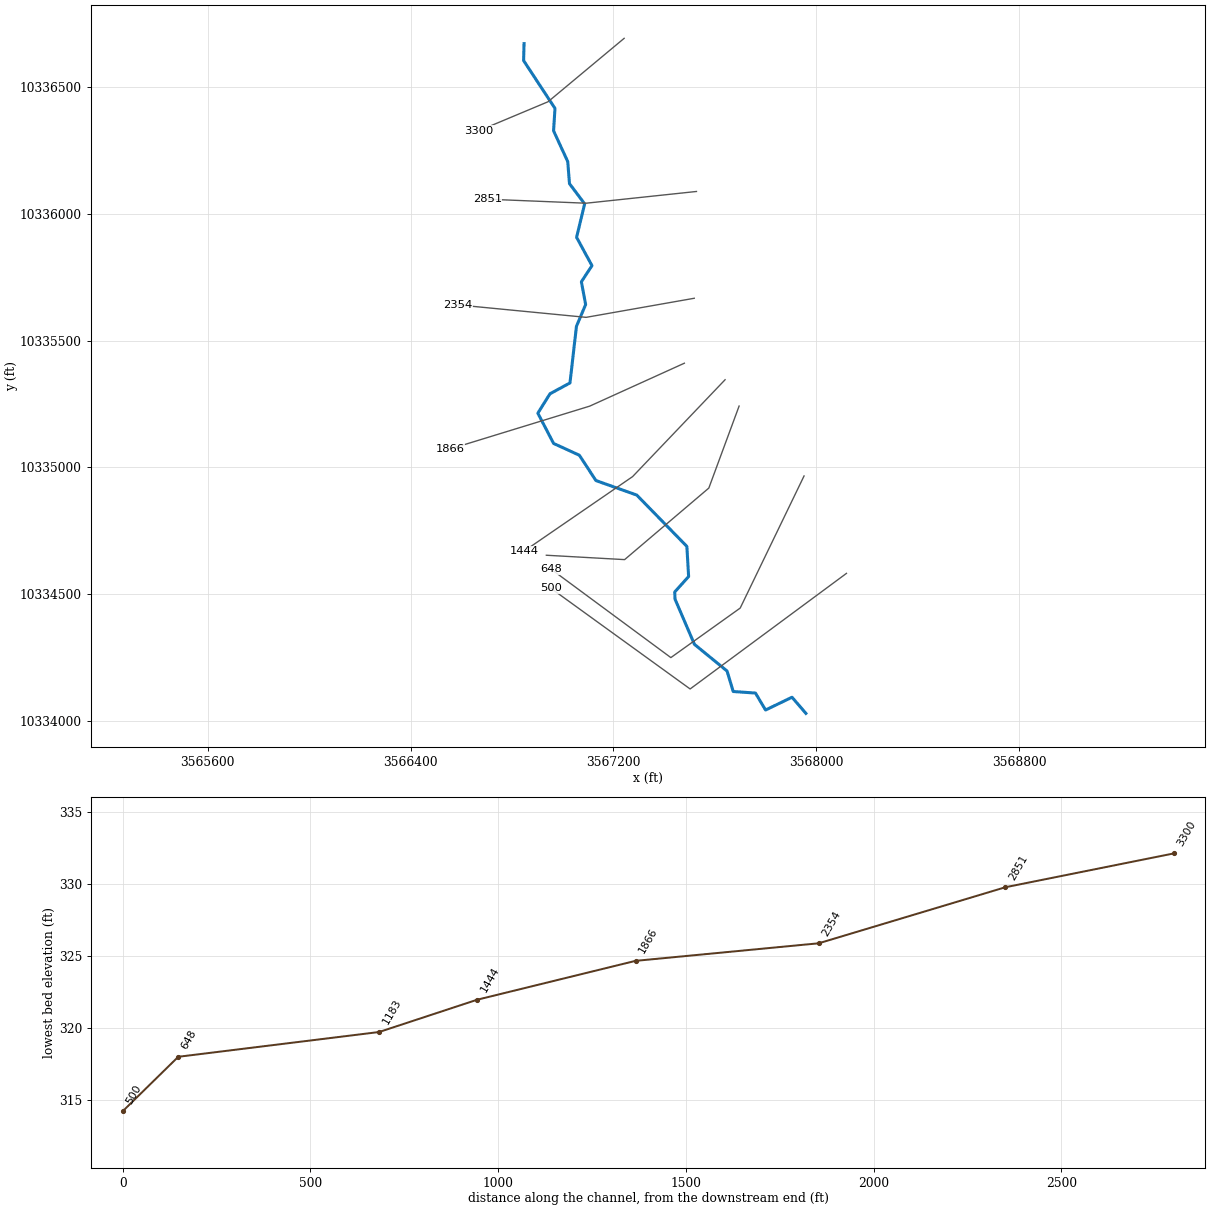
--- PARKER BRANCH.prj (project) ---

Proj Title=PARKER BRANCH Base Level Engineering
Current Plan=p01
Default Exp/Contr=0.3,0.1
English Units
Geom File=g01
Flow File=f01
Plan File=p01
Y Axis Title=Elevation
X Axis Title(PF)=Main Channel Distance
X Axis Title(XS)=Station
BEGIN DESCRIPTION:
PARKER BRANCH
END DESCRIPTION:
DSS Export Rating Curves= 0
DSS Export Rating Curve Sorted= 0
DSS Export Volume Flow Curves= 0
DXF OffsetX= 0
DXF OffsetY= 0
DXF ScaleX= 1
DXF ScaleY= 10

--- PARKER BRANCH.p01 (plan) ---

Plan Title=Multiple Run
Short Identifier=Multiple
Geom File=g01
Flow File=f01
Subcritical Flow
K Sum by GR= 0
Std Step Tol= 0.01
Critical Tol= 0.01
Num of Std Step Trials= 20
Max Error Tol= 0.3
Flow Tol Ratio= 0.001
Split Flow NTrial= 30
Split Flow Tol= 0.02
Split Flow Ratio= 0.02
Log Output Level= 0
Friction Slope Method= 1
Unsteady Friction Slope Method= 2
Unsteady Bridges Friction Slope Method= 1
Parabolic Critical Depth
Global Vel Dist=  1 , 1 , 1
Global Log Level= 0
CheckData=True
Encroach Param= -1, 0, 0, 0
BEGIN DESCRIPTION:
Multiple Run
END DESCRIPTION:

--- PARKER BRANCH.f01 (steady flow) ---

Flow Title=Multiple
Number of Profiles=7
Profile Names=10-year,25-year,50-year,1pct_min,100-year,1pct_plu,500-year
River Rch & RM= PARKER BRANCH,Reach-1,3300
     394     521     622     546     738     998    1039
River Rch & RM= PARKER BRANCH,Reach-1,648
     474     634     764     675     912    1234    1304
Boundary for River Rch & Prof#=PARKER BRANCH,Reach-1,1
Up Type=0
Dn Type=3
Dn Slope=0.005
Boundary for River Rch & Prof#=PARKER BRANCH,Reach-1,2
Up Type=0
Dn Type=3
Dn Slope=0.005
Boundary for River Rch & Prof#=PARKER BRANCH,Reach-1,3
Up Type=0
Dn Type=3
Dn Slope=0.005
Boundary for River Rch & Prof#=PARKER BRANCH,Reach-1,4
Up Type=0
Dn Type=3
Dn Slope=0.005
Boundary for River Rch & Prof#=PARKER BRANCH,Reach-1,5
Up Type=0
Dn Type=3
Dn Slope=0.005
Boundary for River Rch & Prof#=PARKER BRANCH,Reach-1,6
Up Type=0
Dn Type=3
Dn Slope=0.005
Boundary for River Rch & Prof#=PARKER BRANCH,Reach-1,7
Up Type=0
Dn Type=3
Dn Slope=0.005

--- PARKER BRANCH.g01 (geometry) ---

Geom Title=Existing Conditions
Program Version=4.10

River Reach=PARKER BRANCH   ,Reach-1
Reach XY= 30
      3566847.46     10336670.84      3566845.74     10336603.86
      3566969.46     10336415.36      3566963.82     10336327.09
      3567019.73     10336205.66      3567026.58     10336118.69
      3567086.43     10336038.99      3567054.58     10335907.14
      3567115.29     10335795.47      3567073.45     10335731.93
      3567090.34     10335642.11      3567054.06      10335556.3
      3567028.55       10335333.      3566949.72      10335290.3
      3566901.86     10335213.82      3566963.93     10335094.42
      3567065.53     10335048.02      3567130.78     10334948.21
      3567291.79     10334890.98      3567489.36     10334688.58
       3567496.3     10334569.83      3567441.44     10334508.72
      3567442.83     10334480.25      3567519.22     10334302.47
      3567647.82     10334197.15      3567672.13     10334116.42
       3567759.8     10334110.34      3567799.73      10334043.5
       3567903.9     10334093.85      3567958.65     10334030.26

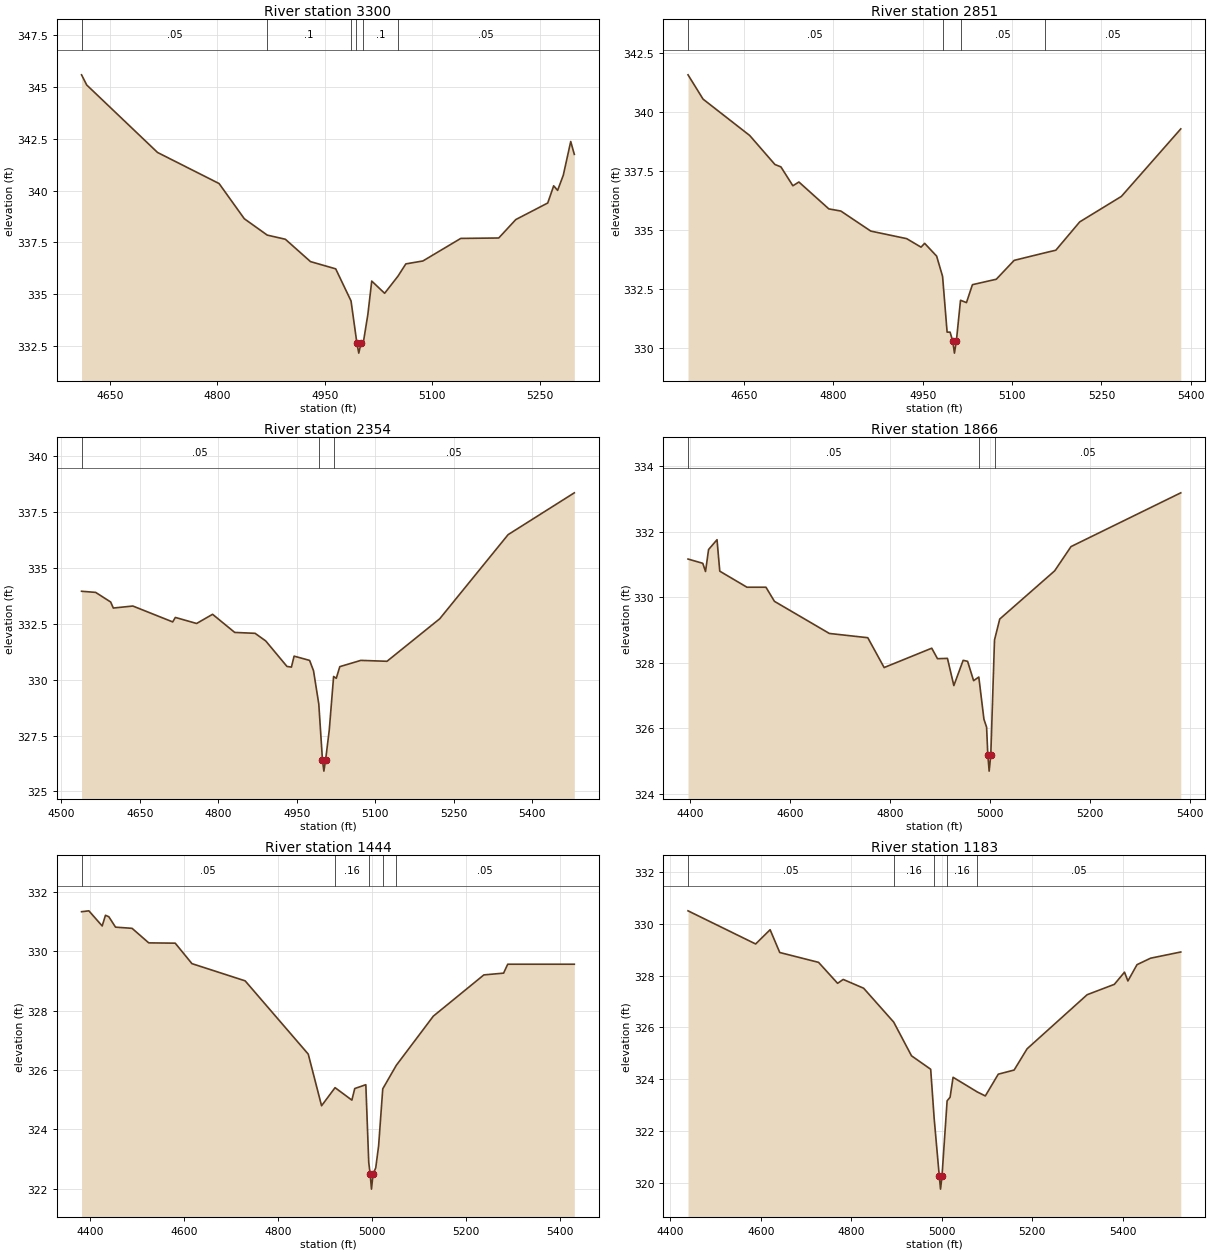
Type RM Length L Ch R = 1 ,3300    ,449,449,449
BEGIN DESCRIPTION:
PARKER BRANCH 6.0
END DESCRIPTION:
XS GIS Cut Line= 3
      3567242.14     10336691.67      3566942.11     10336441.64
       3566667.9     10336326.64
#Sta/Elev= 30
  4610.5  345.59  4617.7   345.1  4716.6  341.84  4802.5  340.34  4837.7  338.64
  4869.7  337.85    4895  337.65  4930.1  336.57  4965.3  336.22  4986.7  334.67
  4993.5  332.98  4994.8  332.65  4997.5  332.15  5000.8  332.65  5003.8  332.65
  5010.2  334.02  5015.6  335.63  5033.6  335.04  5052.3  335.87  5063.2  336.46
    5087   336.6  5139.9  337.69  5192.9  337.71  5216.7   338.6  5261.3   339.4
  5269.6  340.23  5275.1  340.01    5283  340.74  5293.4  342.37  5298.4  341.75
#Mann= 6 ,-1 , 0
  4610.5     .05       0  4869.7      .1       0  4986.7     .05       0
  4993.5     .03       0  5003.8      .1       0  5052.3     .05       0
Bank Sta=4994.8,5000.8
XS Rating Curve= 0 ,0
Exp/Cntr=0.3,0.1

Type RM Length L Ch R = 1 ,2851    ,497,497,497
BEGIN DESCRIPTION:
PARKER BRANCH 5.0
END DESCRIPTION:
XS GIS Cut Line= 3
      3567527.25      10336087.9      3567092.11     10336041.64
      3566702.53     10336057.51
#Sta/Elev= 30
  4555.8  341.59  4581.1  340.56  4659.4  339.02  4701.8  337.79  4711.8  337.69
  4731.9  336.89    4742  337.05  4792.3  335.91  4812.4  335.82  4862.7  334.97
    4923  334.65  4947.1  334.29  4953.2  334.45  4973.3  333.91  4983.3  333.05
  4990.9  330.69  4995.9  330.69  5000.4   330.3  5003.2   329.8  5006.4   330.3
  5013.4  332.04  5023.4  331.94  5033.4   332.7  5073.5  332.93  5103.5  333.73
  5155.1  334.05  5173.5  334.16  5213.6  335.36  5283.6  336.44  5383.3   339.3
#Mann= 4 ,-1 , 0
  4555.8     .05       0  4983.3     .03       0  5013.4     .05       0
  5155.1     .05       0
Bank Sta=5000.4,5006.4
XS Rating Curve= 0 ,0
Exp/Cntr=0.3,0.1

Type RM Length L Ch R = 1 ,2354    ,488,488,488
BEGIN DESCRIPTION:
PARKER BRANCH 4.0
END DESCRIPTION:
XS GIS Cut Line= 3
      3567518.57      10335666.9      3567092.11     10335591.64
      3566586.24     10335640.76
#Sta/Elev= 30
  4538.9  333.95  4565.8   333.9  4594.5  333.47  4599.6   333.2  4636.9  333.29
    4713  332.58  4718.1  332.78  4758.7  332.51  4789.2  332.92  4831.5  332.11
  4870.4  332.07  4890.7  331.73  4931.3  330.59  4939.8  330.56  4944.9  331.05
  4974.5  330.86    4982   330.4  4992.1  328.91  4999.1  326.41  5001.8  325.91
  5005.1  326.41  5012.1  327.75  5020.4  330.14  5025.5  330.06  5032.2  330.58
  5072.4  330.86  5122.4  330.82  5223.1  332.72  5353.7  336.48  5480.2  338.35
#Mann= 3 ,-1 , 0
  4538.9     .05       0  4992.1     .03       0  5020.4     .05       0
Bank Sta=4999.1,5005.1
XS Rating Curve= 0 ,0
Exp/Cntr=0.3,0.1

Type RM Length L Ch R = 1 ,1866    ,422,422,422
BEGIN DESCRIPTION:
PARKER BRANCH 3.0
END DESCRIPTION:
XS GIS Cut Line= 3
       3567479.5     10335410.83       3567106.2     10335241.54
      3566556.05     10335072.59
#Sta/Elev= 30
  4395.8  331.16  4425.3  331.03  4430.8  330.78  4436.9  331.45  4453.8  331.75
  4459.3  330.79  4513.7   330.3  4551.7   330.3  4568.6  329.87  4678.4  328.89
  4755.3  328.76    4788  327.85  4883.2  328.44  4894.7  328.12  4914.6  328.13
  4927.4   327.3    4946  328.07  4954.9  328.04  4966.9  327.45  4977.3  327.56
  4987.6  326.27  4992.9  326.03  4995.3  325.19    4998  324.69  5001.3  325.19
  5008.7  328.69  5019.2  329.33    5129   330.8  5161.7  331.54  5381.2  333.18
#Mann= 3 ,-1 , 0
  4395.8     .05       0  4977.3     .05       0  5008.7     .05       0
Bank Sta=4995.3,5001.3
XS Rating Curve= 0 ,0
Exp/Cntr=0.3,0.1

Type RM Length L Ch R = 1 ,1444    ,261,261,261
BEGIN DESCRIPTION:
PARKER BRANCH 2.0
END DESCRIPTION:
XS GIS Cut Line= 3
      3567640.05      10335345.7      3567275.47     10334963.76
      3566846.44     10334669.07
#Sta/Elev= 30
  4381.5  331.34  4397.1  331.37  4425.4  330.86  4432.4  331.22  4439.6  331.17
  4453.8  330.82    4489  330.78  4524.5  330.29  4580.8  330.28  4616.4  329.59
  4729.6  329.01  4863.9  326.54  4892.2   324.8  4920.9  325.41  4956.7  324.99
  4962.8  325.38  4986.4  325.51  4992.6  322.89  4995.7  322.49  4998.4  321.99
  5001.7  322.49  5007.5  322.71  5013.6  323.45  5022.4  325.37  5051.1  326.16
    5130  327.82  5237.5  329.21  5279.5  329.27  5288.3  329.57    5430  329.57
#Mann= 5 ,-1 , 0
  4381.5     .05       0  4920.9     .16       0  4992.6     .07       0
  5022.4     .16       0  5051.1     .05       0
Bank Sta=4995.7,5001.7
XS Rating Curve= 0 ,0
Exp/Cntr=0.3,0.1

Type RM Length L Ch R = 1 ,1183    ,535,535,535
BEGIN DESCRIPTION:
Mapping XS 215a097d
END DESCRIPTION:
XS GIS Cut Line= 4
      3567695.35     10335241.91        3567576.     10334918.58
      3567243.97     10334636.47      3566935.41     10334653.73
#Sta/Elev= 30
    4439   330.5  4588.5  329.22  4620.5  329.77  4641.8  328.89  4727.6  328.51
  4769.7   327.7  4782.1  327.85  4827.3  327.51  4893.8   326.2  4933.1   324.9
  4975.5  324.38  4983.2  322.48  4994.5  320.25  4997.3  319.75  5000.5  320.25
  5011.8  323.16  5018.4   323.3    5025  324.07  5078.9   323.5  5096.3  323.35
  5124.9  324.19    5160  324.35  5188.6  325.17  5321.4  327.26  5381.5  327.66
    5404  328.13  5411.5  327.79  5431.6  328.42  5461.6  328.67  5528.4  328.91
#Mann= 5 ,-1 , 0
    4439     .05       0  4893.8     .16       0  4983.2     .07       0
  5011.8     .16       0  5078.9     .05       0
Bank Sta=4994.5,5000.5
XS Rating Curve= 0 ,0
Exp/Cntr=0.3,0.1

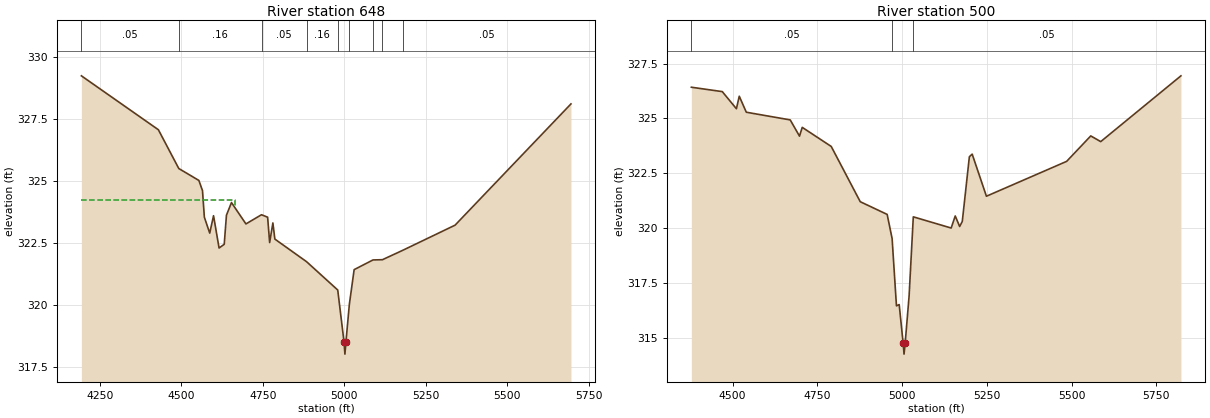
Type RM Length L Ch R = 1 ,648     ,148,148,148
BEGIN DESCRIPTION:
Mapping XS 409437e3
END DESCRIPTION:
XS GIS Cut Line= 4
      3567951.43     10334966.31       3567699.7     10334445.49
      3567426.26     10334250.18      3566953.19     10334599.56
#Sta/Elev= 30
    4193  329.23  4429.3  327.06  4491.9   325.5  4553.6  325.02  4564.7  324.61
  4570.4  323.54  4586.9   322.9  4598.6   323.6  4615.6   322.3  4631.4  322.45
  4638.2  323.62  4653.6  324.13    4698  323.27  4745.8  323.64  4764.6  323.54
  4770.8  322.52  4780.7  323.31  4786.8  322.66  4884.1  321.75  4979.8  320.61
    4999  318.53  5001.8  318.03    5005  318.53  5015.4  320.03  5030.1  321.43
  5087.9  321.82    5117  321.83  5179.6  322.21  5339.9  323.22  5695.6   328.1
#Mann= 9 ,-1 , 0
    4193     .05       0  4491.9     .16       0  4745.8     .05       0
  4884.1     .16       0  4979.8     .07       0  5015.4     .16       0
  5087.9     .05       0    5117     .16       0  5179.6     .05       0
#XS Ineff= 2 , 0
         4664.77  324.25
Permanent Ineff=
       F       F
Bank Sta=4999,5005
XS Rating Curve= 0 ,0
Exp/Cntr=0.3,0.1

Type RM Length L Ch R = 1 ,500     ,0,0,0
BEGIN DESCRIPTION:
PARKER BRANCH 1.0
END DESCRIPTION:
XS GIS Cut Line= 3
      3568118.56     10334582.23      3567502.22     10334126.48
      3566953.14     10334523.64
#Sta/Elev= 30
  4378.5  326.42  4469.7  326.22  4511.4  325.44  4519.8  326.01  4540.6  325.28
  4670.1  324.93  4697.5  324.19  4705.6  324.59  4791.1  323.72  4876.7   321.2
  4956.1  320.62  4970.7  319.52  4983.5  316.45  4991.6  316.51  5003.2  314.75
  5005.9  314.25  5009.2  314.75  5020.8   316.9  5033.2  320.51  5144.9     320
  5156.9  320.55  5169.9  320.07  5177.7   320.3  5198.6  323.25  5206.9  323.37
  5248.9  321.45  5485.6  323.04  5556.7   324.2  5586.1  323.94  5822.7  326.94
#Mann= 3 ,-1 , 0
  4378.5     .05       0  4970.7     .04       0  5033.2     .05       0
Bank Sta=5003.2,5009.2
XS Rating Curve= 0 ,0
Exp/Cntr=0.3,0.1

Chan Stop Cuts=-1
Use User Specified Reach Order=0
Composite Channel Slope=5