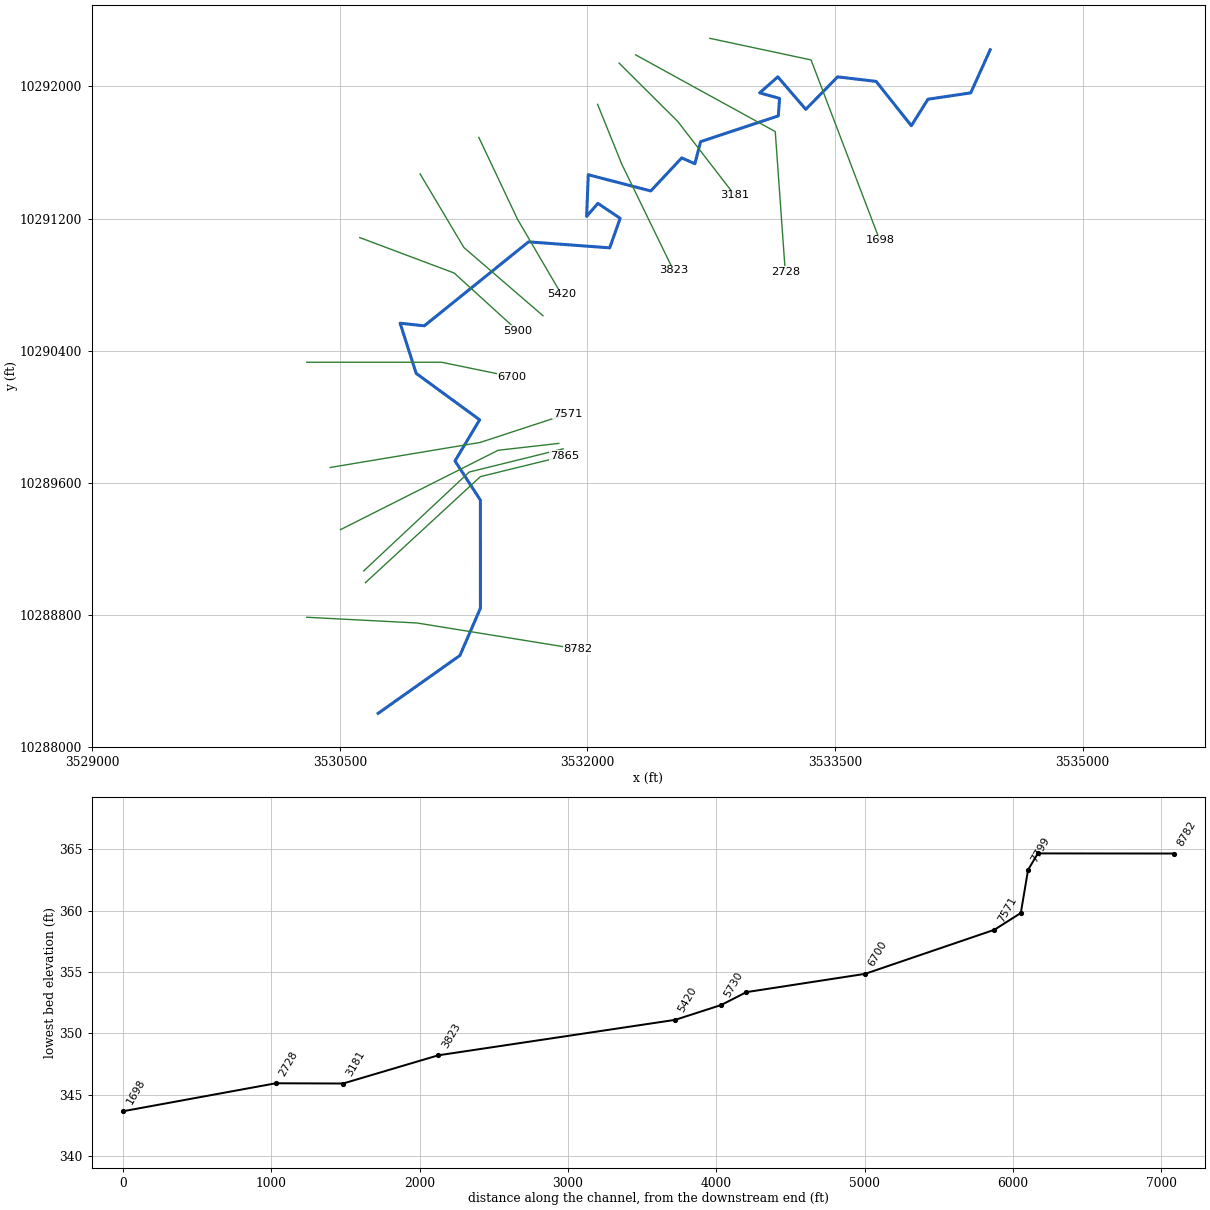
--- PECAN BRANCH.prj (project) ---

Proj Title=PECAN BRANCH Base Level Engineering
Current Plan=p01
Default Exp/Contr=0.3,0.1
English Units
Geom File=g01
Flow File=f01
Plan File=p01
BEGIN DESCRIPTION:
PECAN BRANCH
END DESCRIPTION:

--- PECAN BRANCH.p01 (plan) ---

Plan Title=Multiple Run
Short Identifier=Multiple
Geom File=g01
Flow File=f01
Subcritical Flow
K Sum by GR= 0
Std Step Tol= 0.01
Critical Tol= 0.01
Num of Std Step Trials= 20
Max Error Tol= 0.3
Flow Tol Ratio= 0.001
Split Flow NTrial= 30
Split Flow Tol= 0.02
Split Flow Ratio= 0.02
Log Output Level= 0
Friction Slope Method= 1
Unsteady Friction Slope Method= 2
Unsteady Bridges Friction Slope Method= 1
Parabolic Critical Depth
Global Vel Dist=  1 , 1 , 1
Global Log Level= 0
CheckData=True
Encroach Param= -1, 0, 0, 0
BEGIN DESCRIPTION:
Multiple Run
END DESCRIPTION:

--- PECAN BRANCH.f01 (steady flow) ---

Flow Title=Multiple
Number of Profiles=7
Profile Names=10-year,25-year,50-year,1pct_min,100-year,1pct_plu,500-year
River Rch & RM= PECAN BRANCH,Reach-1,8782
     531     712     857     756    1023    1383    1460
River Rch & RM= PECAN BRANCH,Reach-1,7571
     679     920    1115     990    1338    1810    1933
Boundary for River Rch & Prof#=PECAN BRANCH,Reach-1,1
Up Type=0
Dn Type=3
Dn Slope=0.005
Boundary for River Rch & Prof#=PECAN BRANCH,Reach-1,2
Up Type=0
Dn Type=3
Dn Slope=0.005
Boundary for River Rch & Prof#=PECAN BRANCH,Reach-1,3
Up Type=0
Dn Type=3
Dn Slope=0.005
Boundary for River Rch & Prof#=PECAN BRANCH,Reach-1,4
Up Type=0
Dn Type=3
Dn Slope=0.005
Boundary for River Rch & Prof#=PECAN BRANCH,Reach-1,5
Up Type=0
Dn Type=3
Dn Slope=0.005
Boundary for River Rch & Prof#=PECAN BRANCH,Reach-1,6
Up Type=0
Dn Type=3
Dn Slope=0.005
Boundary for River Rch & Prof#=PECAN BRANCH,Reach-1,7
Up Type=0
Dn Type=3
Dn Slope=0.005

--- PECAN BRANCH.g01 (geometry) ---

Geom Title=Existing Conditions

River Reach=PECAN BRANCH,Reach-1
Reach XY= 30
      3530732.11     10288201.64      3531227.61     10288552.39
      3531352.05     10288839.24      3531351.77     10289493.51
      3531197.93     10289731.06      3531347.43     10289980.39
      3530962.71     10290261.58      3530865.41     10290565.50
      3531011.97     10290549.88      3531643.38     10291058.57
      3532135.23     10291022.20      3532198.57     10291201.11
      3532063.67     10291291.69      3531995.45     10291213.04
      3532005.32     10291465.19      3532384.04     10291366.92
      3532571.49     10291567.21      3532651.17     10291531.79
      3532685.93     10291665.44      3533156.84     10291821.96
      3533164.32     10291927.72      3533043.83     10291961.36
      3533153.75     10292058.14      3533323.14     10291861.39
      3533515.77     10292058.15      3533749.28     10292030.80
      3533962.82     10291762.14      3534063.52     10291922.73
      3534322.54     10291961.14      3534440.60     10292222.41

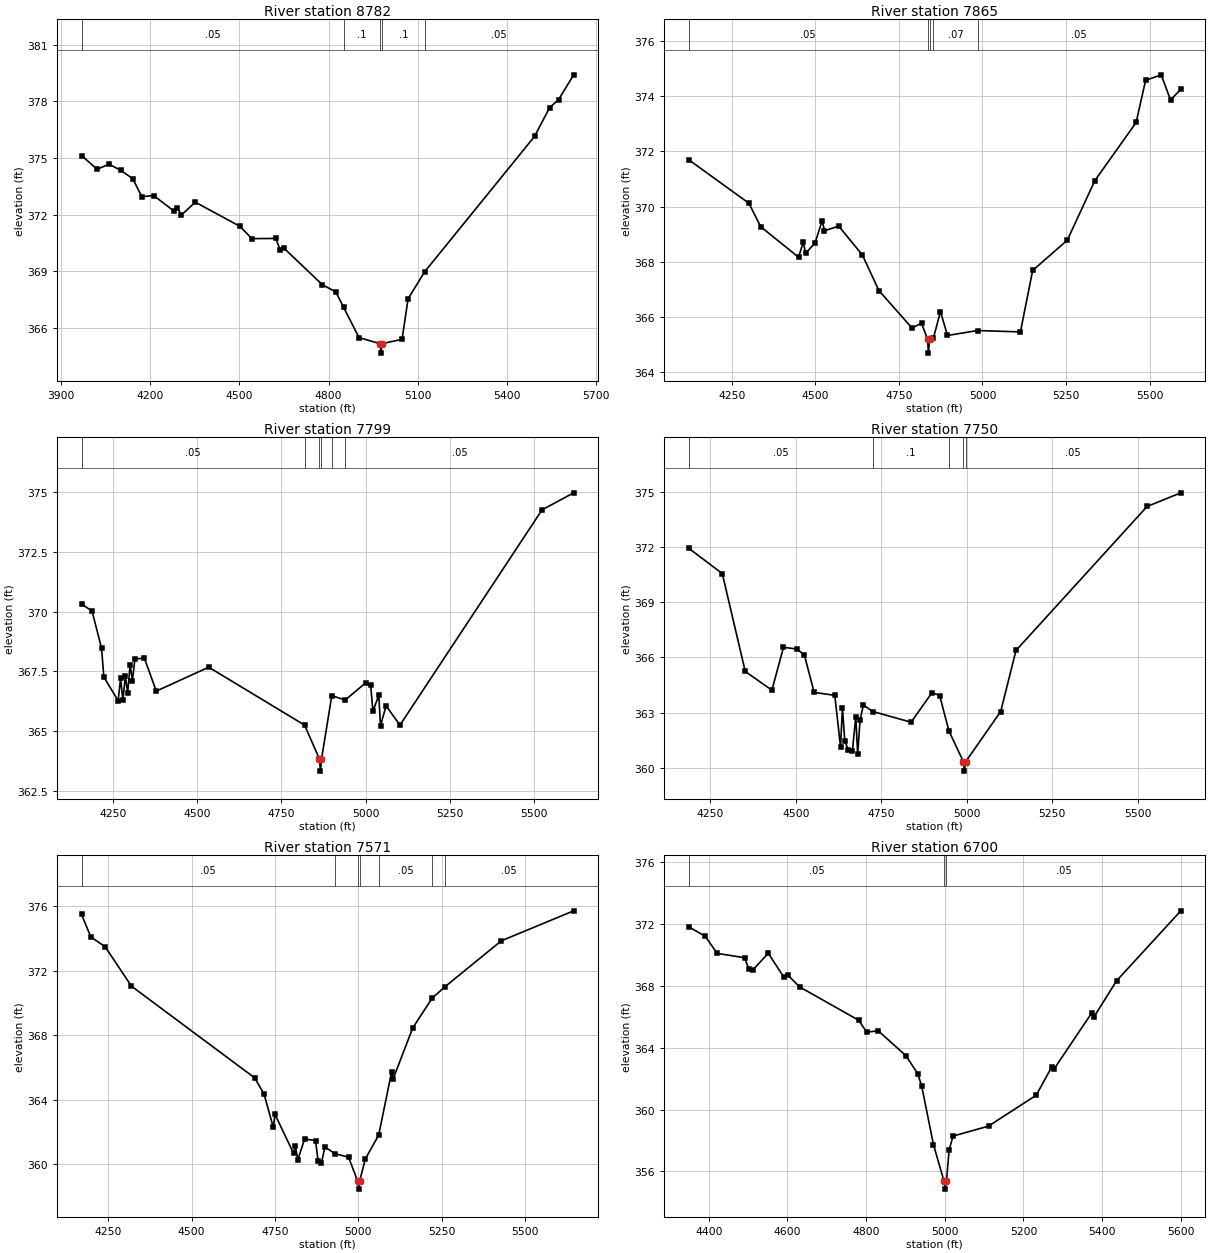
Type RM Length L Ch R = 1,8782,917,917,917
BEGIN DESCRIPTION:
PECAN BRANCH 13.0
END DESCRIPTION:
XS GIS Cut Line= 3
      3530299.70     10288783.98      3530968.09     10288749.26
      3531942.13     10288591.64
#Sta/Elev= 30
  3968.5  375.13  4021.0  374.40  4061.0  374.67  4101.1  374.34  4141.1  373.90
  4171.2  372.95  4211.2  373.01  4281.3  372.17  4291.3  372.35  4304.5  371.98
  4351.4  372.66  4501.6  371.38  4541.7  370.73  4621.8  370.74  4637.3  370.13
  4650.5  370.21  4779.0  368.29  4824.2  367.91  4850.5  367.09  4902.4  365.49
  4973.1  365.17  4975.9  364.67  4979.1  365.17  5047.1  365.40  5067.3  367.55
  5123.8  368.99  5492.8  376.14  5543.4  377.66  5573.8  378.09  5624.5  379.40
#Mann=5,-1,0
  3968.5    0.05       0  4850.5     0.1       0  4973.1    0.07       0
  4979.1     0.1       0  5123.8    0.05       0
Bank Sta=4973.1,4979.1
Exp/Cntr=0.3,0.1

Type RM Length L Ch R = 1,7865,66,66,66
BEGIN DESCRIPTION:
PECAN BRANCH 12.0
END DESCRIPTION:
XS GIS Cut Line= 3
      3530655.35     10288993.69      3531351.56     10289636.08
      3531861.97     10289761.08
#Sta/Elev= 30
  4120.8  371.70  4301.1  370.12  4336.3  369.27  4449.7  368.16  4463.8  368.71
  4470.6  368.30  4499.0  368.68  4520.5  369.49  4527.3  369.12  4569.9  369.29
  4640.8  368.24  4690.1  366.95  4789.3  365.59  4817.7  365.77  4835.7  365.18
  4838.4  364.68  4841.7  365.18  4853.1  365.22  4874.4  366.19  4895.4  365.32
  4985.4  365.50  5113.7  365.45  5150.2  367.68  5254.0  368.78  5336.3  370.94
  5459.9  373.05  5488.2  374.58  5535.0  374.78  5562.8  373.87  5593.6  374.25
#Mann=5,-1,0
  4120.8    0.05       0  4835.7   0.033       0  4841.7    0.05       0
  4853.1    0.07       0  4985.4    0.05       0
Bank Sta=4835.7,4841.7
Exp/Cntr=0.3,0.1

Type RM Length L Ch R = 1,7799,49,49,49
BEGIN DESCRIPTION:
Mapping XS 8d24cd5d
END DESCRIPTION:
XS GIS Cut Line= 3
      3530644.95     10289064.90      3531283.85     10289663.86
      3531853.29     10289804.48
#Sta/Elev= 30
  4156.0  370.31  4187.1  370.03  4215.4  368.48  4222.3  367.27  4264.8  366.28
  4272.1  367.21  4278.9  366.29  4286.2  367.31  4293.1  366.60  4300.4  367.79
  4307.2  367.11  4314.6  368.03  4342.9  368.05  4378.1  366.68  4533.9  367.68
  4818.9  365.26  4863.0  363.84  4865.8  363.34  4869.0  363.84  4899.6  366.49
  4939.5  366.31  5000.8  367.03  5015.0  366.93  5021.9  365.84  5039.2  366.51
  5044.4  365.24  5060.9  366.07  5102.1  365.26  5524.4  374.25  5618.3  374.96
#Mann=6,-1,0
  4156.0    0.05       0  4818.9     0.1       0  4863.0    0.03       0
  4869.0     0.1       0  4899.6    0.07       0  4939.5    0.05       0
Bank Sta=4863,4869
Exp/Cntr=0.3,0.1

Type RM Length L Ch R = 1,7750,179,179,179
BEGIN DESCRIPTION:
Mapping XS a42a7e79
END DESCRIPTION:
XS GIS Cut Line= 3
      3530504.31     10289314.89      3531459.20     10289795.80
      3531827.19     10289837.46
#Sta/Elev= 30
  4186.4  371.94  4284.8  370.56  4351.9  365.24  4429.8  364.22  4463.8  366.55
  4502.3  366.46  4524.6  366.15  4553.4  364.10  4613.9  363.94  4630.6  361.14
  4636.2  363.26  4643.0  361.48  4652.9  360.99  4665.4  360.93  4675.2  362.77
  4680.8  360.75  4687.8  362.62  4697.5  363.41  4725.2  363.06  4837.0  362.48
  4898.3  364.09  4920.6  363.93  4947.6  362.01  4990.2  360.32  4992.9  359.82
  4996.2  360.32  5099.1  363.06  5143.8  366.38  5527.4  374.21  5625.9  374.95
#Mann=5,-1,0
  4186.4    0.05       0  4725.2     0.1       0  4947.6    0.05       0
  4990.2    0.03       0  4996.2    0.05       0
Bank Sta=4990.2,4996.2
Exp/Cntr=0.3,0.1

Type RM Length L Ch R = 1,7571,871,871,871
BEGIN DESCRIPTION:
PECAN BRANCH 11.0
END DESCRIPTION:
XS GIS Cut Line= 3
      3530442.06     10289691.63      3531350.03     10289843.01
      3531878.35     10290016.23
#Sta/Elev= 30
  4169.8  375.49  4197.7  374.09  4240.8  373.48  4319.4  371.04  4689.3  365.35
  4717.3  364.35  4745.1  362.28  4750.2  363.09  4805.9  360.67  4811.0  361.13
  4818.7  360.27  4839.0  361.56  4871.8  361.46  4879.5  360.21  4889.6  360.04
  4899.8  361.07  4930.1  360.65  4970.8  360.43  4998.2  358.95  5000.9  358.45
  5004.2  358.95  5021.4  360.33  5061.3  361.80  5099.9  365.70  5105.1  365.31
  5163.5  368.45  5221.6  370.29  5258.9  370.98  5429.2  373.85  5646.3  375.71
#Mann=7,-1,0
  4169.8    0.05       0  4930.1     0.1       0  4998.2    0.07       0
  5004.2     0.1       0  5061.3    0.05       0  5221.6     0.1       0
  5258.9    0.05       0
Bank Sta=4998.2,5004.2
Exp/Cntr=0.3,0.1

Type RM Length L Ch R = 1,6700,800,800,800
BEGIN DESCRIPTION:
PECAN BRANCH 10.0
END DESCRIPTION:
XS GIS Cut Line= 3
      3530299.69     10290329.12      3531115.66     10290329.12
      3531542.11     10290241.64
#Sta/Elev= 30
  4348.9  371.81  4391.3  371.19  4421.3  370.09  4491.3  369.81  4501.3  369.10
  4511.3  369.00  4551.3  370.10  4591.3  368.54  4601.3  368.68  4631.3  367.92
  4781.3  365.77  4801.3  365.01  4831.3  365.08  4901.3  363.48  4931.3  362.32
  4941.3  361.53  4971.3  357.74  4998.3  355.36  5001.1  354.86  5004.3  355.36
  5011.3  357.42  5021.3  358.29  5111.3  358.93  5232.7  360.93  5272.6  362.78
  5277.7  362.61  5373.4  366.23  5378.5  365.95  5436.9  368.32  5600.2  372.84
#Mann=3,-1,0
  4348.9    0.05       0  4998.3    0.03       0  5004.3    0.05       0
Bank Sta=4998.3,5004.3
Exp/Cntr=0.3,0.1

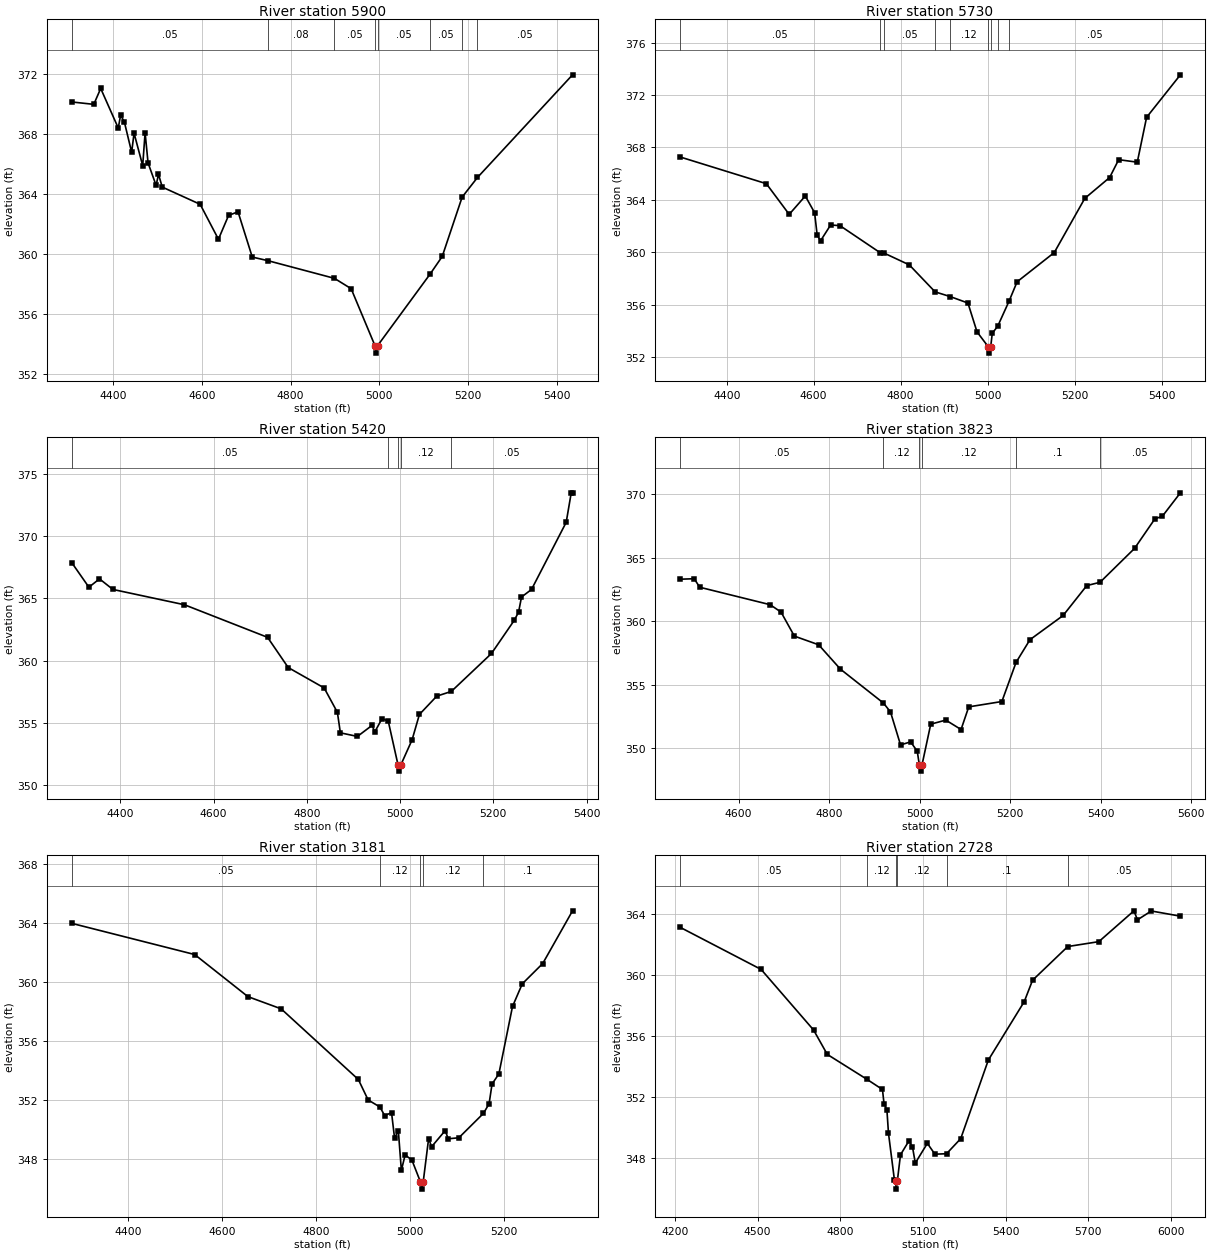
Type RM Length L Ch R = 1,5900,170,170,170
BEGIN DESCRIPTION:
PECAN BRANCH 8.0
END DESCRIPTION:
XS GIS Cut Line= 3
      3530620.89     10291084.31      3531192.82     10290869.59
      3531576.47     10290520.66
#Sta/Elev= 30
  4306.4  370.13  4356.2  369.97  4371.8  371.03  4411.4  368.39  4416.7  369.25
  4425.2  368.79  4441.6  366.77  4447.0  368.05  4466.5  365.88  4471.9  368.08
  4478.6  366.06  4496.8  364.56  4502.1  365.31  4510.6  364.45  4596.1  363.30
  4637.3  360.97  4660.2  362.56  4681.5  362.80  4713.6  359.78  4748.8  359.54
  4898.9  358.36  4936.6  357.67  4990.3  353.87  4993.1  353.37  4996.3  353.87
  5114.8  358.65  5142.0  359.82  5186.9  363.78  5221.5  365.09  5435.9  371.94
#Mann=8,-1,0
  4306.4    0.05       0  4748.8    0.08       0  4898.9    0.05       0
  4990.3    0.07       0  4996.3    0.05       0  5114.8    0.05       0
  5186.9    0.12       0  5221.5    0.05       0
Bank Sta=4990.3,4996.3
Exp/Cntr=0.3,0.1

Type RM Length L Ch R = 1,5730,310,310,310
BEGIN DESCRIPTION:
Mapping XS 17ed9064
END DESCRIPTION:
XS GIS Cut Line= 3
      3530986.24     10291470.25      3531251.85     10291024.10
      3531730.98     10290610.94
#Sta/Elev= 30
  4291.5  367.29  4491.1  365.24  4543.7  362.90  4580.7  364.30  4602.1  363.03
  4608.0  361.33  4615.7  360.88  4639.0  362.09  4660.5  362.04  4752.3  359.99
  4762.4  359.94  4819.9  359.05  4879.3  356.99  4914.2  356.63  4954.8  356.14
  4975.7  353.94  5001.2  352.82  5004.0  352.32  5007.2  352.82  5010.8  353.84
  5023.1  354.36  5049.2  356.27  5067.9  357.76  5153.4  359.99  5223.6  364.12
  5280.7  365.71  5301.5  367.07  5344.3  366.88  5365.7  370.30  5443.4  373.54
#Mann=9,-1,0
  4291.5    0.05       0  4752.3    0.08       0  4762.4    0.05       0
  4879.3    0.08       0  4914.2    0.12       0  5001.2    0.07       0
  5007.2    0.12       0  5023.1    0.08       0  5049.2    0.05       0
Bank Sta=5001.2,5007.2
Exp/Cntr=0.3,0.1

Type RM Length L Ch R = 1,5420,1597,1597,1597
BEGIN DESCRIPTION:
PECAN BRANCH 7.0
END DESCRIPTION:
XS GIS Cut Line= 3
      3531342.12     10291691.62      3531575.72     10291197.17
      3531842.08     10290741.69
#Sta/Elev= 30
  4295.5  367.88  4332.4  365.90  4355.1  366.57  4383.9  365.72  4537.3  364.49
  4715.7  361.87  4760.0  359.44  4837.1  357.80  4865.5  355.84  4871.9  354.19
  4908.5  353.90  4939.9  354.79  4945.7  354.26  4961.4  355.34  4974.7  355.12
  4995.6  351.61  4998.3  351.11  5001.6  351.61  5025.8  353.63  5041.5  355.67
  5078.7  357.14  5110.0  357.52  5196.1  360.57  5244.8  363.23  5254.2  363.89
  5260.5  365.11  5282.0  365.72  5356.4  371.12  5367.2  373.49  5370.0  373.49
#Mann=5,-1,0
  4295.5    0.05       0  4974.7    0.12       0  4995.6    0.07       0
  5001.6    0.12       0  5110.0    0.05       0
Bank Sta=4995.6,5001.6
Exp/Cntr=0.3,0.1

Type RM Length L Ch R = 1,3823,642,642,642
BEGIN DESCRIPTION:
PECAN BRANCH 5.0
END DESCRIPTION:
XS GIS Cut Line= 3
      3532061.83     10291891.63      3532209.41     10291527.03
      3532521.44     10290885.64
#Sta/Elev= 30
  4469.4  363.30  4501.8  363.34  4514.0  362.67  4669.5  361.30  4693.6  360.72
  4723.1  358.83  4776.7  358.15  4825.0  356.23  4919.9  353.57  4935.5  352.87
  4957.7  350.28  4979.9  350.52  4994.6  349.79  4999.2  348.72  5001.9  348.22
  5005.2  348.72  5024.4  351.91  5057.7  352.23  5091.4  351.49  5108.4  353.27
  5181.6  353.69  5213.0  356.77  5243.7  358.55  5316.9  360.45  5369.2  362.80
  5398.5  363.06  5474.7  365.72  5519.8  368.05  5536.0  368.24  5576.0  370.09
#Mann=6,-1,0
  4469.4    0.05       0  4919.9    0.12       0  4999.2    0.07       0
  5005.2    0.12       0  5213.0     0.1       0  5398.5    0.05       0
Bank Sta=4999.2,5005.2
Exp/Cntr=0.3,0.1

Type RM Length L Ch R = 1,3181,453,453,453
BEGIN DESCRIPTION:
PECAN BRANCH 3.0
END DESCRIPTION:
XS GIS Cut Line= 3
      3532192.10     10292141.65      3532547.95     10291787.45
      3532892.12     10291341.63
#Sta/Elev= 30
  4280.3  363.98  4541.9  361.86  4655.1  359.00  4725.8  358.17  4890.0  353.37
  4910.8  351.98  4935.9  351.50  4946.1  350.91  4960.6  351.12  4967.0  349.40
  4975.1  349.87  4981.5  347.20  4989.6  348.25  5004.1  347.88  5022.0  346.42
  5024.7  345.92  5028.0  346.42  5039.5  349.36  5045.8  348.80  5074.8  349.90
  5081.1  349.34  5103.8  349.41  5156.2  351.07  5168.1  351.72  5174.4  353.06
  5188.9  353.75  5217.9  358.33  5238.7  359.87  5282.2  361.25  5345.6  364.83
#Mann=5,-1,0
  4280.3    0.05       0  4935.9    0.12       0  5022.0    0.07       0
  5028.0    0.12       0  5156.2     0.1       0
Bank Sta=5022,5028
Exp/Cntr=0.3,0.1

Type RM Length L Ch R = 1,2728,1030,1030,1030
BEGIN DESCRIPTION:
PECAN BRANCH 2.0
END DESCRIPTION:
XS GIS Cut Line= 3
      3532292.06     10292191.67      3533138.22     10291726.69
      3533198.96     10290876.36
#Sta/Elev= 30
  4216.6  363.12  4512.7  360.34  4703.1  356.37  4752.9  354.77  4897.5  353.13
  4953.2  352.47  4958.9  351.53  4969.3  351.14  4975.0  349.61  4996.8  346.51
  5001.0  346.44  5003.7  345.94  5007.0  346.44  5018.6  348.19  5049.6  349.11
  5062.2  348.70  5072.4  347.65  5116.1  348.94  5143.6  348.23  5185.8  348.26
  5237.3  349.25  5337.5  354.40  5467.9  358.23  5498.0  359.63  5625.9  361.84
  5738.6  362.16  5866.0  364.18  5878.9  363.59  5929.0  364.17  6034.6  363.83
#Mann=6,-1,0
  4216.6    0.05       0  4897.5    0.12       0  5001.0    0.07       0
  5007.0    0.12       0  5185.8     0.1       0  5625.9    0.05       0
Bank Sta=5001,5007
Exp/Cntr=0.3,0.1

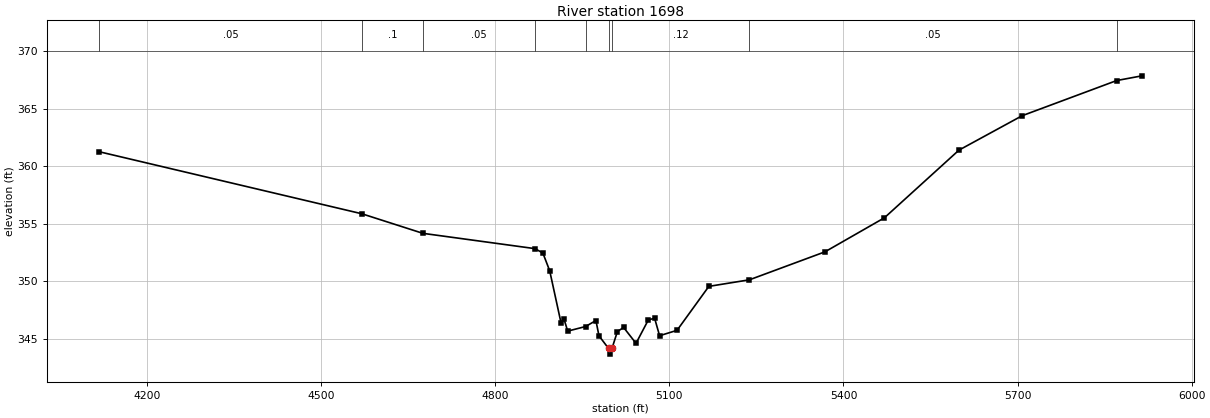
Type RM Length L Ch R = 1,1698,0,0,0
BEGIN DESCRIPTION:
PECAN BRANCH 1.0
END DESCRIPTION:
XS GIS Cut Line= 3
      3532742.11     10292291.64      3533355.24     10292160.71
      3533771.91     10291066.94
#Sta/Elev= 30
  4117.0  361.26  4570.2  355.86  4675.3  354.16  4868.4  352.83  4882.1  352.45
  4893.9  350.90  4913.3  346.40  4918.6  346.69  4924.9  345.66  4955.7  346.06
  4973.5  346.58  4978.8  345.25  4995.2  344.16  4998.0  343.66  5001.2  344.16
  5010.5  345.62  5021.2  345.98  5042.6  344.60  5064.0  346.65  5074.7  346.77
  5083.2  345.26  5113.3  345.73  5168.1  349.55  5238.0  350.12  5368.1  352.55
  5470.6  355.51  5599.0  361.39  5707.8  364.38  5870.8  367.44  5914.4  367.85
#Mann=9,-1,0
  4117.0    0.05       0  4570.2     0.1       0  4675.3    0.05       0
  4868.4     0.1       0  4955.7    0.12       0  4995.2    0.07       0
  5001.2    0.12       0  5238.0    0.05       0  5870.8     0.1       0
Bank Sta=4995.2,5001.2
Exp/Cntr=0.3,0.1

Chan Stop Cuts=-1