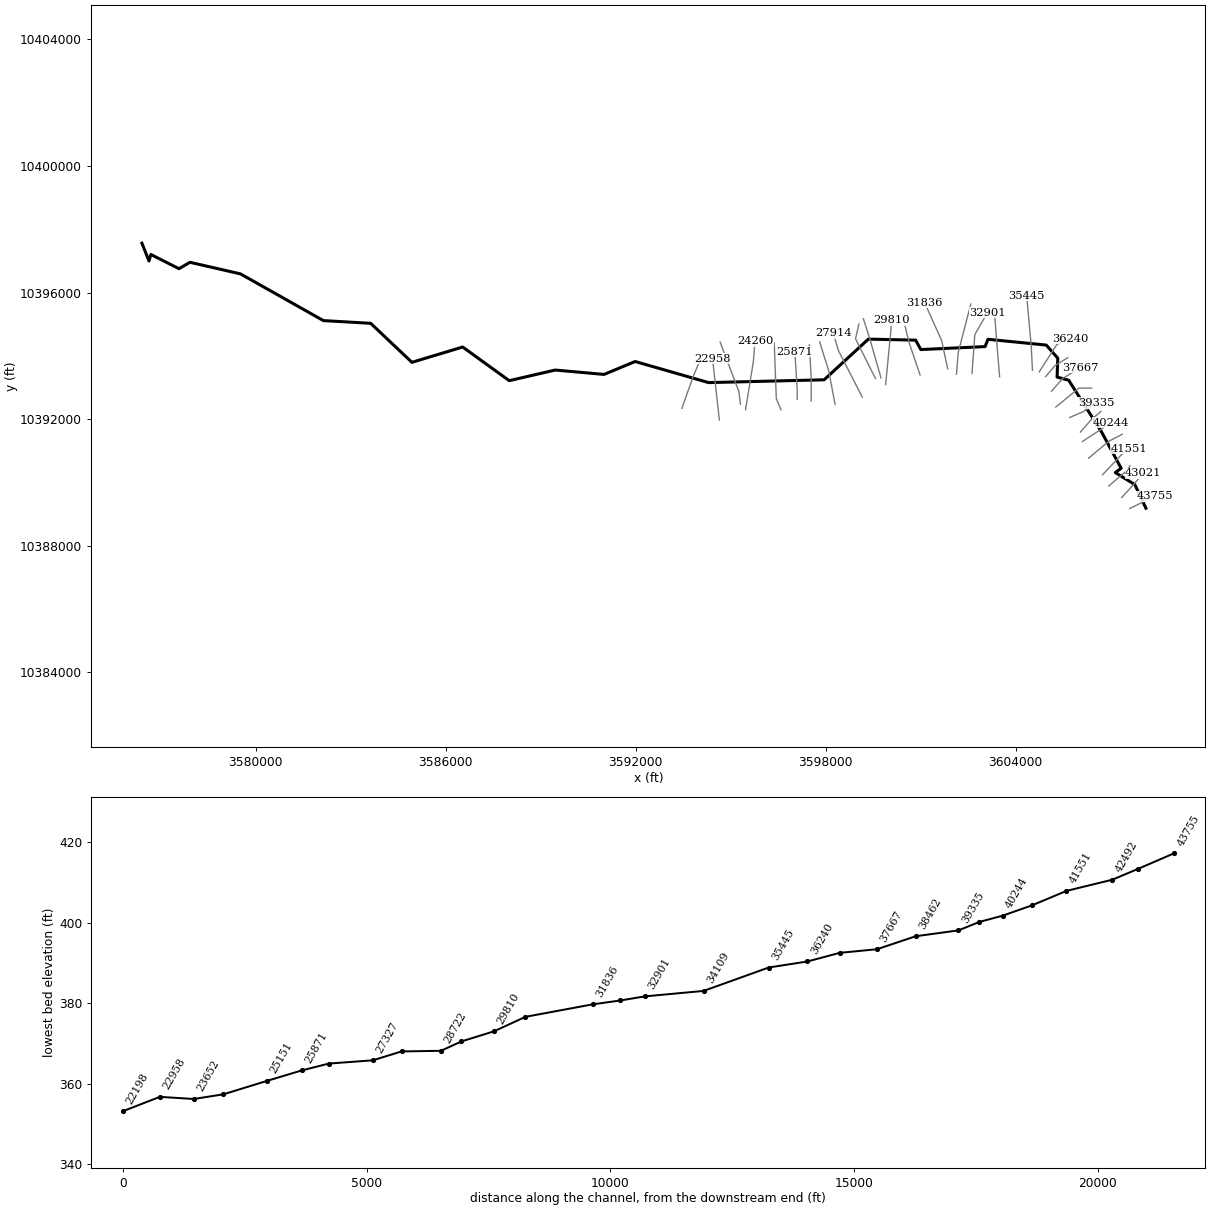
--- PIGEON ROOST CREEK.prj (project) ---

Proj Title=PIGEON ROOST CREEK Base Level Engineering
Current Plan=p01
Default Exp/Contr=0.3,0.1
English Units
Geom File=g01
Flow File=f01
Plan File=p01
Y Axis Title=Elevation
X Axis Title(PF)=Main Channel Distance
X Axis Title(XS)=Station
BEGIN DESCRIPTION:
PIGEON ROOST CREEK
END DESCRIPTION:
DSS Export Rating Curves= 0
DSS Export Rating Curve Sorted= 0
DSS Export Volume Flow Curves= 0
DXF OffsetX= 0
DXF OffsetY= 0
DXF ScaleX= 1
DXF ScaleY= 10

--- PIGEON ROOST CREEK.p01 (plan) ---

Plan Title=Multiple Run
Short Identifier=Multiple
Geom File=g01
Flow File=f01
Subcritical Flow
K Sum by GR= 0
Std Step Tol= 0.01
Critical Tol= 0.01
Num of Std Step Trials= 20
Max Error Tol= 0.3
Flow Tol Ratio= 0.001
Split Flow NTrial= 30
Split Flow Tol= 0.02
Split Flow Ratio= 0.02
Log Output Level= 0
Friction Slope Method= 1
Unsteady Friction Slope Method= 2
Unsteady Bridges Friction Slope Method= 1
Parabolic Critical Depth
Global Vel Dist=  1 , 1 , 1
Global Log Level= 0
CheckData=True
Encroach Param= -1, 0, 0, 0
BEGIN DESCRIPTION:
Multiple Run
END DESCRIPTION:

--- PIGEON ROOST CREEK.f01 (steady flow) ---

Flow Title=Multiple
Program Version=4.10
Number of Profiles= 7
Profile Names=10-year,25-year,50-year,1pct_min,100-year,1pct_plu,500-year
River Rch & RM=PIGEON ROOST CRE,Reach-1         ,43755
    2166    3100    3902    3578    4838    6543    7418
River Rch & RM=PIGEON ROOST CRE,Reach-1         ,35445
    3526    5165    6602    6137    8299   11223   13085
River Rch & RM=PIGEON ROOST CRE,Reach-1         ,34109
    3526    5165    6602    6137    8299   11223   13085
River Rch & RM=PIGEON ROOST CRE,Reach-1         ,31836
    5220    7770   10042    9426   12748   17240   20499
River Rch & RM=PIGEON ROOST CRE,Reach-1         ,30456
    5220    7770   10042    9426   12748   17240   20499
River Rch & RM=PIGEON ROOST CRE,Reach-1         ,26424
    5537    8249   10666   10015   13544   18317   21793
River Rch & RM=PIGEON ROOST CRE,Reach-1         ,23652
    5784    8620   11149   10468   14156   19145   22777
River Rch & RM=PIGEON ROOST CRE,Reach-1         ,20903
    6069    9049   11705   10990   14862   20099   23911
River Rch & RM=PIGEON ROOST CRE,Reach-1         ,16828
    7867   11814   15359   14481   19584   26485   31772
River Rch & RM=PIGEON ROOST CRE,Reach-1         ,15790
    7867   11814   15359   14481   19584   26485   31772
River Rch & RM=PIGEON ROOST CRE,Reach-1         ,10018
    8105   12176   15833   14930   20192   27307   32766
River Rch & RM=PIGEON ROOST CRE,Reach-1         ,6180
    8666   13022   16935   15969   21596   29206   35036
Boundary for River Rch & Prof#=PIGEON ROOST CRE,Reach-1         , 1
Up Type= 0
Dn Type= 3
Dn Slope=0.00205
Boundary for River Rch & Prof#=PIGEON ROOST CRE,Reach-1         , 2
Up Type= 0
Dn Type= 3
Dn Slope=0.00205
Boundary for River Rch & Prof#=PIGEON ROOST CRE,Reach-1         , 3
Up Type= 0
Dn Type= 3
Dn Slope=0.00205
Boundary for River Rch & Prof#=PIGEON ROOST CRE,Reach-1         , 4
Up Type= 0
Dn Type= 3
Dn Slope=0.00205
Boundary for River Rch & Prof#=PIGEON ROOST CRE,Reach-1         , 5
Up Type= 0
Dn Type= 3
Dn Slope=0.00205
Boundary for River Rch & Prof#=PIGEON ROOST CRE,Reach-1         , 6
Up Type= 0
Dn Type= 3
Dn Slope=0.00205
Boundary for River Rch & Prof#=PIGEON ROOST CRE,Reach-1         , 7
Up Type= 0
Dn Type= 3
Dn Slope=0.00205
DSS Import GetInterval= 0
DSS Import GetPeak= 0
DSS Import FillOption= 0

--- PIGEON ROOST CREEK.g01 (geometry) ---

Geom Title=Existing Conditions
Program Version=4.10

River Reach=PIGEON ROOST CRE,Reach-1
Reach XY= 30
      3608111.87     10389184.56       3607761.4     10389931.05
      3607143.95     10390312.85      3607330.14     10390446.23
      3606706.53     10391603.84      3605674.13     10393228.12
      3605307.22     10393329.07       3605328.5     10393925.18
      3604966.15     10394339.97      3603125.17     10394523.25
      3603032.29     10394291.91      3601004.08      10394198.6
      3600839.68     10394495.74      3599347.66     10394528.77
      3597949.82     10393242.81      3594302.62      10393154.4
      3591982.09     10393821.06      3591001.61     10393412.98
      3589457.19     10393551.03      3588007.01     10393215.33
        3586537.     10394278.46      3584933.52     10393794.96
      3583630.37     10395028.13      3582137.79     10395113.37
      3579520.87      10396589.2      3577924.23     10396956.03
      3577577.88     10396753.77      3576690.69     10397202.97
      3576630.07      10396996.8      3576408.01     10397559.88

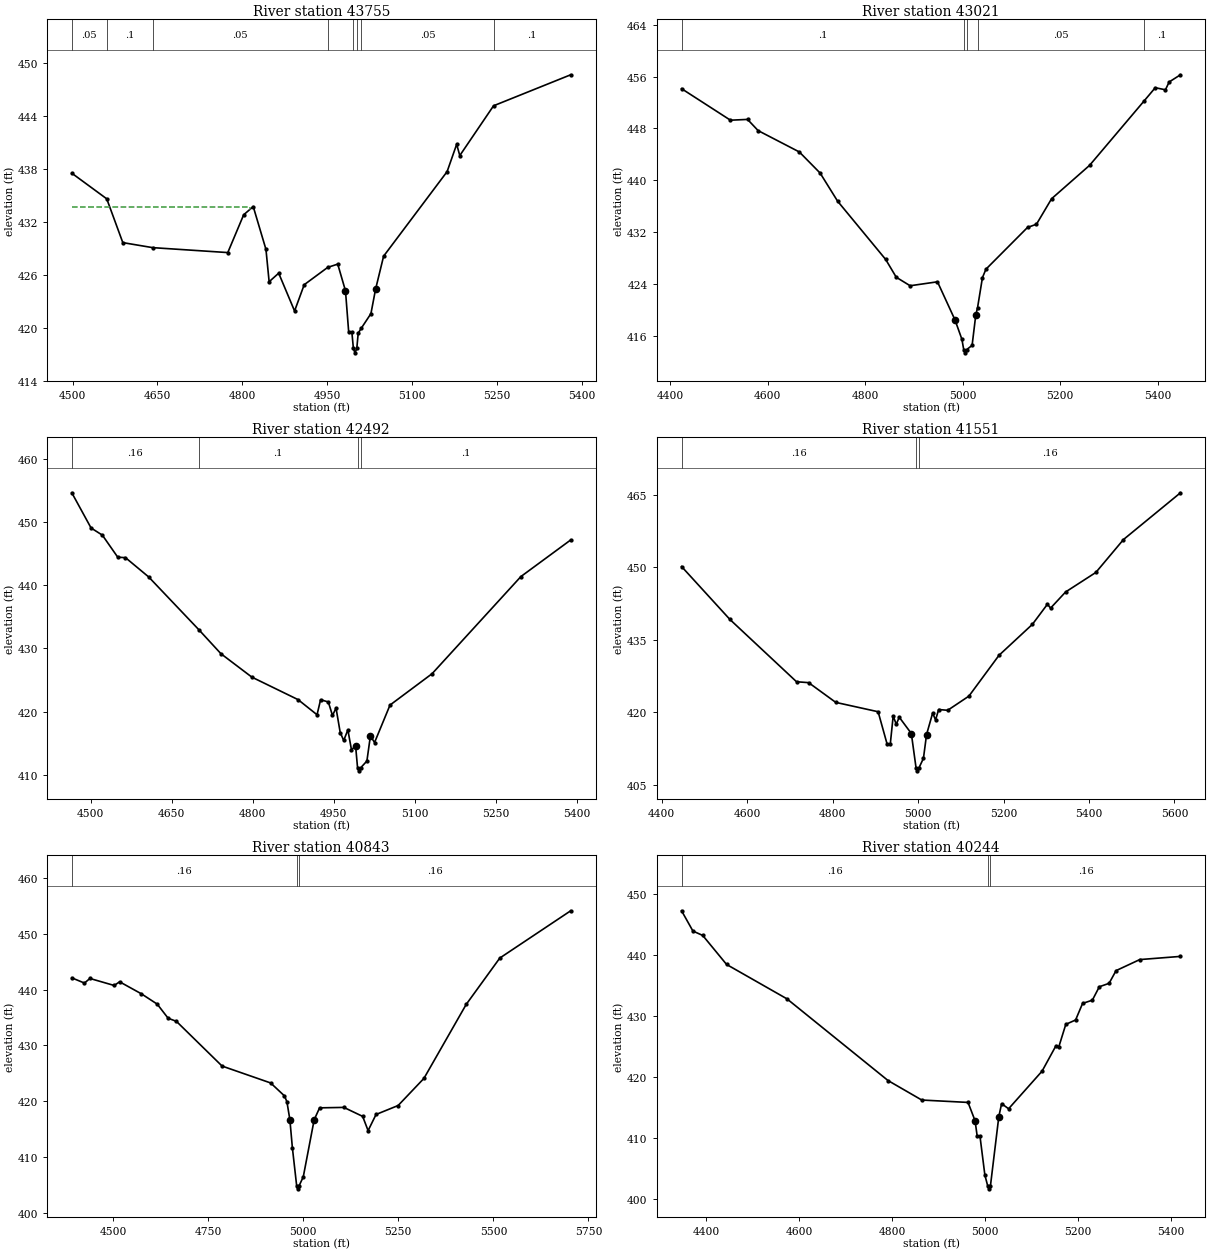
Type RM Length L Ch R = 1 ,43755   ,734,734,734
BEGIN DESCRIPTION:
PIGEON ROOST CREEK 75.0
END DESCRIPTION:
XS GIS Cut Line= 3
      3607599.82     10389175.18      3608042.11     10389391.64
      3608391.55      10389564.1
#Sta/Elev= 30
  4498.6  437.54  4560.4  434.63  4588.8  429.66  4641.6  429.09  4774.4  428.53
  4802.5  432.82  4819.4  433.75  4841.9  428.89  4847.5  425.22  4864.4  426.19
  4892.5   421.9  4909.5  424.88  4951.1  426.85  4968.8  427.22  4982.5  424.19
  4988.2  419.48  4993.8  419.48  4996.5  417.65  4999.2  417.15  5002.5  417.65
    5005  419.38  5010.4  419.94  5027.5   421.6  5035.6  424.34  5049.9  428.12
  5162.2  437.72  5179.1  440.82  5184.6  439.54  5244.3  445.19  5380.7  448.71
#Mann= 8 ,-1 , 0
  4498.6     .05       0  4560.4      .1       0  4641.6     .05       0
  4951.1      .1       0  4996.5     .07       0  5002.5      .1       0
  5010.4     .05       0  5244.3      .1       0
#XS Ineff= 2 , 0
         4813.07  433.75
Permanent Ineff=
       F       F
Bank Sta=4982.5,5035.6
XS Rating Curve= 0 ,0
Exp/Cntr=0.3,0.1

Type RM Length L Ch R = 1 ,43021   ,529,529,529
BEGIN DESCRIPTION:
PIGEON ROOST CREEK 73.0
END DESCRIPTION:
XS GIS Cut Line= 3
      3607349.86     10389522.43      3607835.97     10390064.09
      3608030.43     10390286.33
#Sta/Elev= 30
  4423.6  454.15  4523.8  449.28  4558.9   449.4  4580.6  447.67  4665.1  444.37
  4707.7  441.11  4743.6  436.76  4842.2  427.75  4863.9     425  4892.3  423.69
  4948.4   424.3  4984.3  418.41  4998.5  415.41  5002.2  413.82    5005  413.32
  5008.2  413.82  5019.4  414.47  5026.9  419.16  5030.6  420.31  5040.6  424.95
  5047.8  426.25    5133   432.7  5151.4   433.2  5182.4  437.14  5260.3   442.3
  5371.4  452.19    5395   454.3  5415.9  453.98  5423.5  455.19  5446.7   456.3
#Mann= 5 ,-1 , 0
  4423.6      .1       0  5002.2     .07       0  5008.2      .1       0
  5030.6     .05       0  5371.4      .1       0
Bank Sta=4984.3,5026.9
XS Rating Curve= 0 ,0
Exp/Cntr=0.3,0.1

Type RM Length L Ch R = 1 ,42492   ,941,941,941
BEGIN DESCRIPTION:
PIGEON ROOST CREEK 72.0
END DESCRIPTION:
XS GIS Cut Line= 3
      3606942.09     10389891.63      3607508.77     10390374.98
      3607607.94     10390523.73
#Sta/Elev= 30
  4465.2  454.59  4500.9  449.02  4521.8  447.89  4550.3   444.4  4564.6  444.33
  4607.4  441.29  4700.8   432.9  4741.3  429.14  4798.5  425.44  4884.1  421.88
  4919.2  419.49  4925.8  421.87  4940.1  421.51  4947.8  419.38  4954.4  420.54
  4962.1  416.68  4968.6  415.42  4976.3   417.1  4982.9  413.97  4990.6  414.54
  4994.2  411.12  4996.9  410.62  5000.2  411.12  5011.5  412.17    5018  416.14
  5025.7   415.1  5054.3  421.02  5132.2  425.98  5296.6  441.34  5388.8  447.13
#Mann= 4 ,-1 , 0
  4465.2     .16       0  4700.8      .1       0  4994.2     .07       0
  5000.2      .1       0
Bank Sta=4990.6,5018
XS Rating Curve= 0 ,0
Exp/Cntr=0.3,0.1

Type RM Length L Ch R = 1 ,41551   ,708,708,708
BEGIN DESCRIPTION:
PIGEON ROOST CREEK 71.0
END DESCRIPTION:
XS GIS Cut Line= 3
      3606742.09     10390241.63      3607419.88     10390961.09
      3607568.53     10391060.19
#Sta/Elev= 30
  4446.9  450.19    4560  439.22  4715.8  426.31  4744.1  426.12  4807.6  422.03
  4906.7  420.09  4927.8  413.36  4935.1  413.35  4941.9  419.19  4949.2  417.49
  4956.1  418.96  4984.4  415.58  4995.6  408.34  4998.3  407.84  5001.6  408.34
  5012.7  410.42    5020  415.36  5034.2   419.8  5041.1   418.4  5048.3  420.55
  5069.4  420.39  5119.1  423.33  5189.5  431.79  5267.6  438.21  5302.8  442.38
  5310.1  441.57  5345.3  444.92  5416.1  448.97  5480.7  455.79    5614  465.48
#Mann= 3 ,-1 , 0
  4446.9     .16       0  4995.6     .07       0  5001.6     .16       0
Bank Sta=4984.4,5020
XS Rating Curve= 0 ,0
Exp/Cntr=0.3,0.1

Type RM Length L Ch R = 1 ,40843   ,599,599,599
BEGIN DESCRIPTION:
PIGEON ROOST CREEK 69.0
END DESCRIPTION:
XS GIS Cut Line= 3
      3606301.26     10390765.49      3606940.13      10391300.2
      3607363.76     10391522.43
#Sta/Elev= 30
  4391.7  442.13    4425  441.19  4439.3  442.02  4503.1  440.76  4517.4  441.42
  4574.7  439.26  4616.3  437.41  4644.9  434.88  4666.7  434.32  4786.8  426.29
  4914.4  423.26  4950.7  420.94  4957.2  419.89    4965  416.65  4971.5  411.67
  4982.9  404.75  4985.6  404.25  4988.9  404.75  5000.2   406.4  5028.8  416.64
  5043.1  418.79  5106.9  418.87  5156.3  417.26  5170.6   414.7  5191.5   417.6
  5249.6  419.21  5317.4  424.08  5428.5  437.36  5516.8  445.68  5703.2  454.17
#Mann= 3 ,-1 , 0
  4391.7     .16       0  4982.9     .07       0  4988.9     .16       0
Bank Sta=4965,5028.8
XS Rating Curve= 0 ,0
Exp/Cntr=0.3,0.1

Type RM Length L Ch R = 1 ,40244   ,477,477,477
BEGIN DESCRIPTION:
PIGEON ROOST CREEK 68.0
END DESCRIPTION:
XS GIS Cut Line= 3
       3606106.8     10391293.25      3606642.11     10391641.64
      3607002.59     10391883.51
#Sta/Elev= 30
  4346.9  447.23  4371.3  443.91  4392.4  443.19  4443.7  438.44  4573.5  432.81
  4790.9  419.43  4863.4  416.24  4962.9  415.85    4978  412.85  4982.6  410.31
  4988.6  410.31  4999.1  403.95  5005.1   402.2  5007.8   401.7  5011.1   402.2
  5029.1  413.54  5035.1  415.65  5050.1  414.81  5122.1  420.97  5152.1  425.15
  5158.2  424.98  5173.1  428.63  5194.2  429.35  5209.2  432.06  5230.2  432.59
  5245.2  434.79  5266.2  435.35  5281.2  437.43  5332.2  439.24  5419.7  439.76
#Mann= 3 ,-1 , 0
  4346.9     .16       0  5005.1     .07       0  5011.1     .16       0
Bank Sta=4978,5029.1
XS Rating Curve= 0 ,0
Exp/Cntr=0.3,0.1

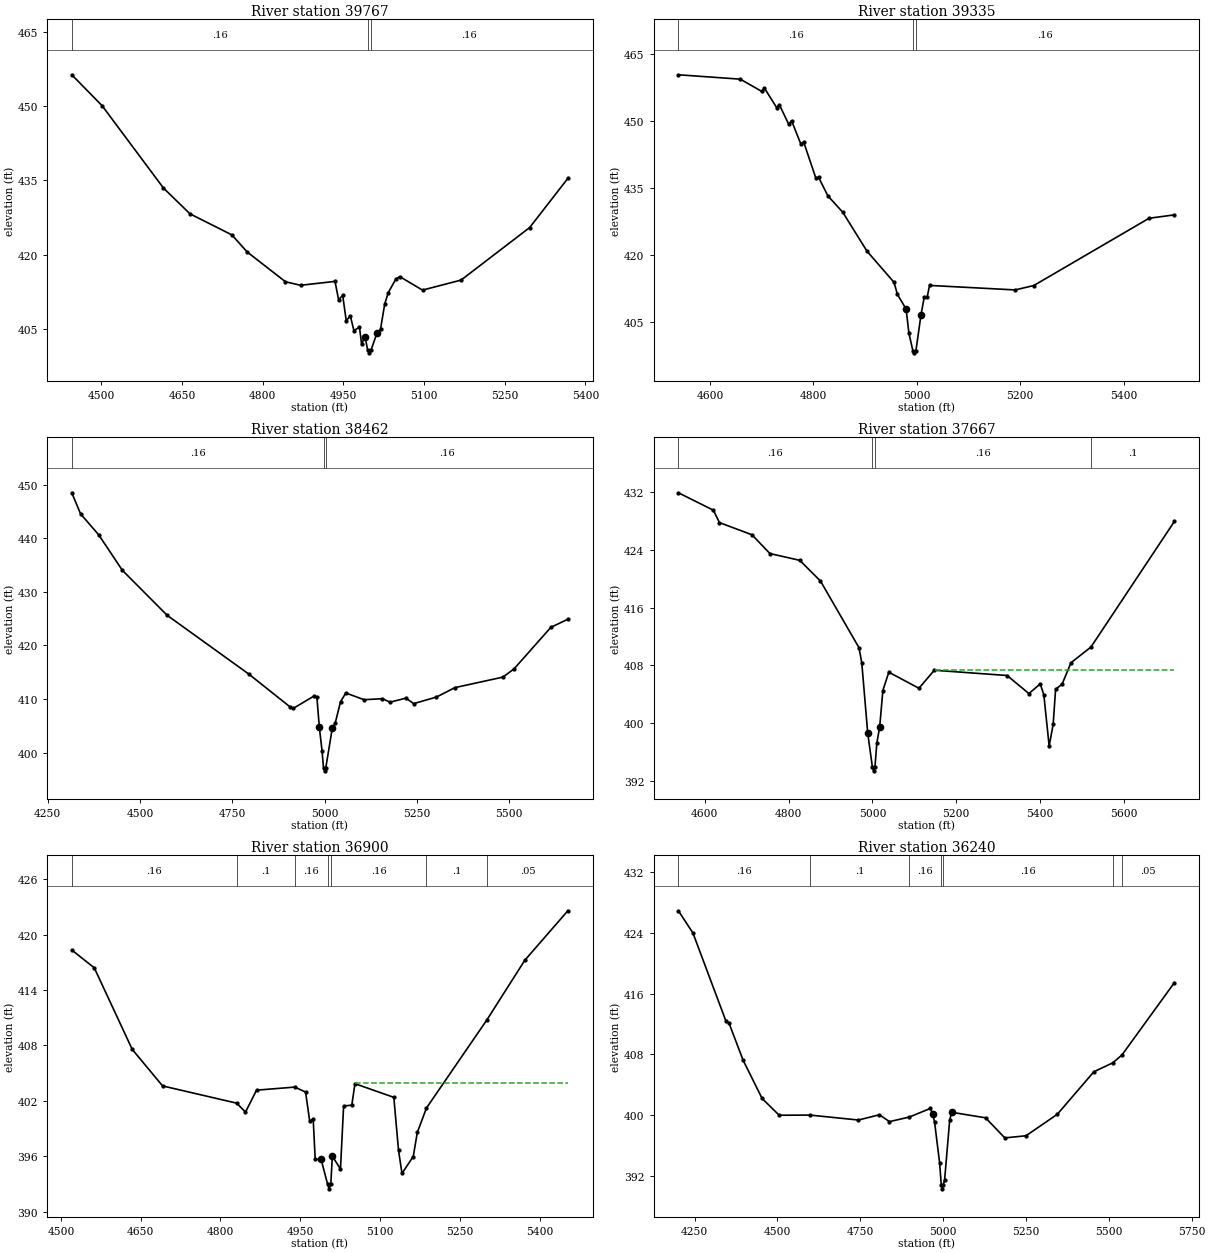
Type RM Length L Ch R = 1 ,39767   ,432,432,432
BEGIN DESCRIPTION:
PIGEON ROOST CREEK 67.0
END DESCRIPTION:
XS GIS Cut Line= 3
      3606042.12     10391591.66      3606392.11     10391991.64
      3606692.11     10392241.65
#Sta/Elev= 30
  4445.2   456.3  4501.6  450.05  4615.5  433.44  4664.9  428.22  4742.7  423.97
  4771.2  420.52  4842.4   414.5  4870.4  413.79  4934.4  414.58  4941.1  410.88
  4948.7  411.75  4955.3  406.64  4962.9  407.62  4969.6  404.63  4979.9  405.35
  4983.8  401.94  4990.4   403.4  4995.2  400.65  4997.9  400.15  5001.2  400.65
  5012.5  404.16    5019  404.92  5026.8  409.99  5033.3  412.29  5047.6  415.06
  5054.8  415.54  5097.1  412.82  5168.7  414.84  5296.3  425.46  5367.2  435.38
#Mann= 3 ,-1 , 0
  4445.2     .16       0  4995.2     .07       0  5001.2     .16       0
Bank Sta=4990.4,5012.5
XS Rating Curve= 0 ,0
Exp/Cntr=0.3,0.1

Type RM Length L Ch R = 1 ,39335   ,873,873,873
BEGIN DESCRIPTION:
PIGEON ROOST CREEK 66.0
END DESCRIPTION:
XS GIS Cut Line= 3
      3605704.02      10392050.2      3606142.11     10392241.64
       3606542.9      10392507.6
#Sta/Elev= 30
    4539  460.27  4658.7  459.29    4700  456.56  4705.5  457.27  4728.9  452.94
  4734.4  453.54  4752.3  449.19  4757.8  449.99  4775.7  444.79  4781.2  445.24
  4804.6  437.21    4810  437.34    4828  433.18  4856.8  429.51  4903.6   420.8
  4955.9  413.83  4962.5  411.11  4979.3  407.84  4984.7  402.45  4992.3  398.54
    4995  398.04  4998.3  398.54  5008.1  406.57  5014.4  410.56  5020.1  410.56
  5024.6  413.13    5190  412.12  5226.1   413.1  5449.1  428.16  5498.1  428.92
#Mann= 3 ,-1 , 0
    4539     .16       0  4992.3     .07       0  4998.3     .16       0
Bank Sta=4979.3,5008.1
XS Rating Curve= 0 ,0
Exp/Cntr=0.3,0.1

Type RM Length L Ch R = 1 ,38462   ,795,795,795
BEGIN DESCRIPTION:
PIGEON ROOST CREEK 64.0
END DESCRIPTION:
XS GIS Cut Line= 3
      3605266.49     10392383.51      3605999.05     10392980.53
      3606398.12     10392980.53
#Sta/Elev= 30
  4315.1  448.49  4338.8  444.57  4388.3  440.62  4452.2  434.02  4573.6  425.62
  4794.1  414.69  4907.5  408.48  4915.4  408.26  4971.4  410.56  4979.3   410.3
  4985.8  404.76  4993.2  400.34  4997.2   397.1  4999.9   396.6  5003.2   397.1
    5021  404.58  5028.9  405.52  5043.3   409.5  5057.6  411.13  5107.2  409.87
  5156.7  410.07  5177.5  409.41  5220.6  410.17  5241.4  409.14  5303.2  410.37
  5353.2  412.13  5483.2  414.09  5513.2  415.61  5613.2  423.38  5659.2  424.89
#Mann= 3 ,-1 , 0
  4315.1     .16       0  4997.2     .07       0  5003.2     .16       0
Bank Sta=4985.8,5021
XS Rating Curve= 0 ,0
Exp/Cntr=0.3,0.1

Type RM Length L Ch R = 1 ,37667   ,767,767,767
BEGIN DESCRIPTION:
PIGEON ROOST CREEK 63.0
END DESCRIPTION:
XS GIS Cut Line= 3
      3605132.37     10392883.29      3605482.38     10393283.31
      3606037.19     10393626.49
#Sta/Elev= 30
    4537   431.9  4620.7  429.48  4634.9  427.77  4712.7  426.08  4755.4  423.48
  4826.6  422.54    4876  419.68    4968  410.44  4974.7  408.34  4988.9  398.58
  5000.1  393.87  5002.9  393.37  5006.1  393.87  5010.7  397.27  5017.4  399.42
    5025   404.5  5039.2  407.04  5111.1  404.81  5147.8  407.31  5321.5  406.58
  5373.5  404.08  5400.7  405.42  5409.2   403.9  5421.9   396.8  5431.4   399.8
  5437.3  404.68  5452.7  405.37    5474  408.35  5521.6  410.52  5720.9  427.94
#Mann= 4 ,-1 , 0
    4537     .16       0  5000.1     .07       0  5006.1     .16       0
  5521.6      .1       0
#XS Ineff= 2 , 0
                         5149.32           407.4
Permanent Ineff=
       F       F
Bank Sta=4988.9,5017.4
XS Rating Curve= 0 ,0
Exp/Cntr=0.3,0.1

Type RM Length L Ch R = 1 ,36900   ,660,660,660
BEGIN DESCRIPTION:
PIGEON ROOST CREEK 61.0
END DESCRIPTION:
XS GIS Cut Line= 3
      3604942.07      10393341.6      3605242.11     10393691.64
      3605642.08     10393941.63
#Sta/Elev= 30
  4520.5  418.34  4562.8  416.41  4634.1  407.58  4691.2  403.62  4830.6  401.75
  4847.1  400.78  4867.9  403.16  4939.8  403.49  4960.1  402.95  4967.8  399.81
  4974.4  400.01  4978.2  395.65  4989.2  395.67  5001.5  392.97  5004.3  392.47
  5007.5  392.97  5010.4     396  5025.7  394.62  5031.6  401.45    5047  401.53
  5052.9  403.86    5126  402.38  5134.8  396.66  5141.3  394.14  5162.5  395.97
  5170.2  398.58  5187.4  401.23  5301.2  410.79  5372.4  417.24  5453.2  422.59
#Mann= 7 ,-1 , 0
  4520.5     .16       0  4830.6      .1       0  4939.8     .16       0
  5001.5     .07       0  5007.5     .16       0  5187.4      .1       0
  5301.2     .05       0
#XS Ineff= 2 , 0
                         5055.23          403.89
Permanent Ineff=
       F       F
Bank Sta=4989.2,5010.4
XS Rating Curve= 0 ,0
Exp/Cntr=0.3,0.1

Type RM Length L Ch R = 1 ,36240   ,795,795,795
BEGIN DESCRIPTION:
PIGEON ROOST CREEK 60.0
END DESCRIPTION:
XS GIS Cut Line= 3
      3604742.11     10393491.65      3605301.24     10394361.83
       3605726.6     10394544.12
#Sta/Elev= 30
    4201   426.9  4244.9  423.98  4344.6  412.38  4353.9  412.11  4396.2  407.26
  4453.6  402.22  4505.2  400.01  4598.2  400.03  4744.3  399.38  4807.7  400.07
  4838.1  399.17  4897.9  399.77  4961.7  400.91  4968.2  400.18  4974.1  399.14
  4989.3  393.79  4994.4  390.83  4997.1  390.33  5000.4  390.83  5004.5  391.51
  5019.7  399.33  5025.6   400.4  5128.1  399.67  5186.1  397.03  5250.1  397.31
  5344.4  400.13    5455  405.73  5511.5  406.89  5539.5  407.92  5698.1  417.46
#Mann= 7 ,-1 , 0
    4201     .16       0  4598.2      .1       0  4897.9     .16       0
  4994.4     .07       0  5000.4     .16       0  5511.5      .1       0
  5539.5     .05       0
Bank Sta=4968.2,5025.6
XS Rating Curve= 0 ,0
Exp/Cntr=0.3,0.1

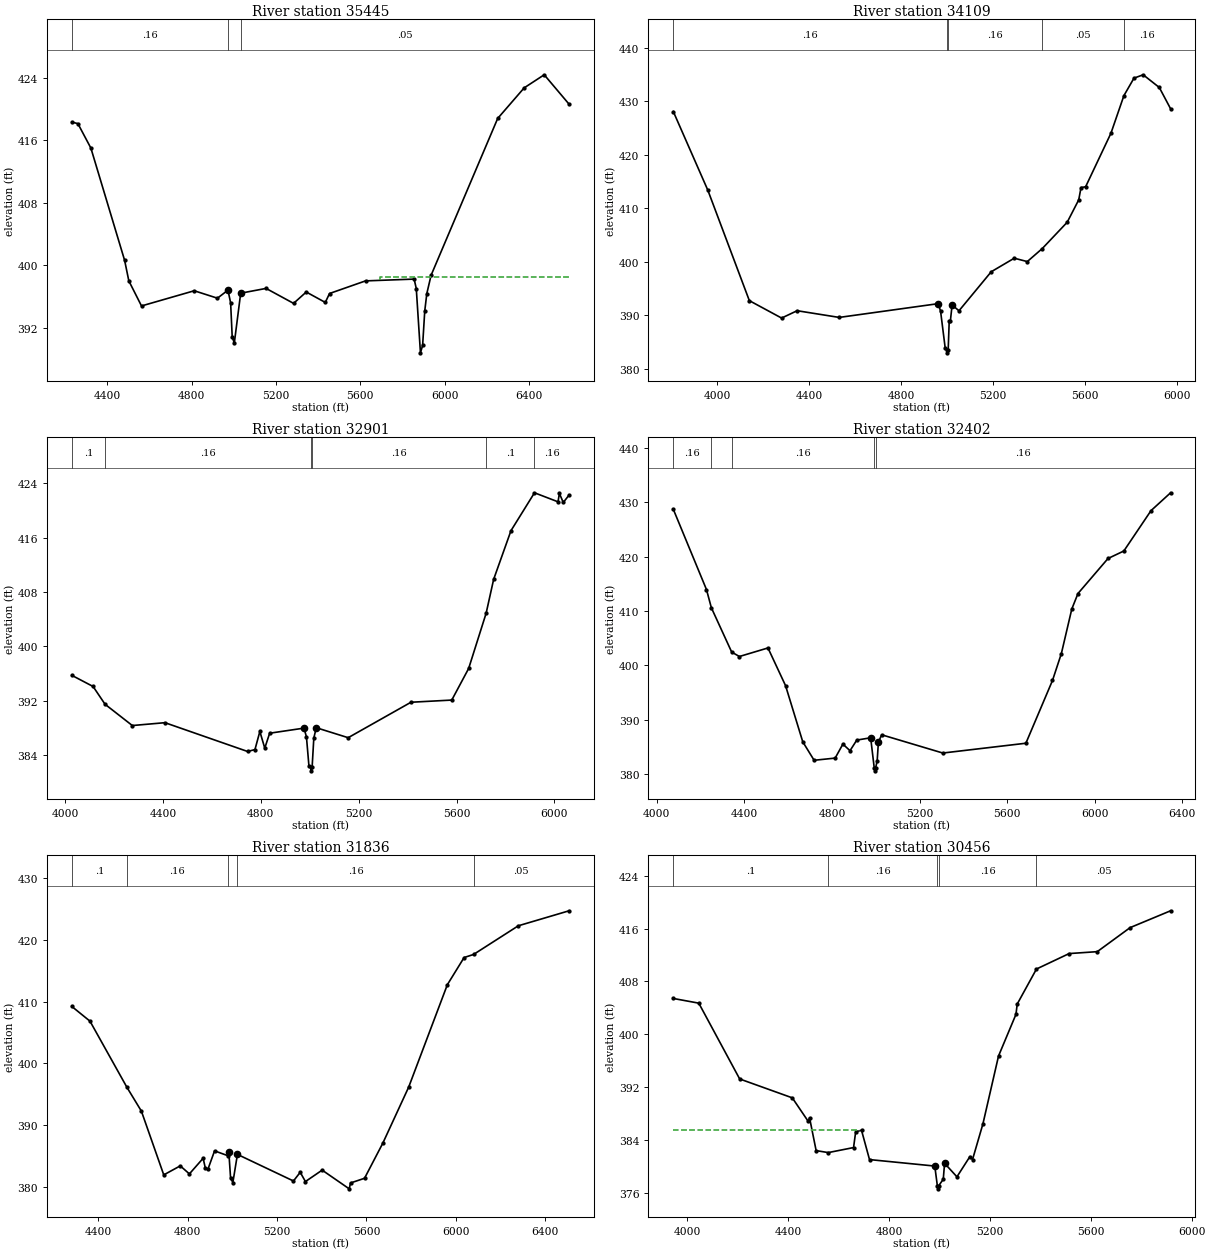
Type RM Length L Ch R = 1 ,35445   ,1336,1336,1336
BEGIN DESCRIPTION:
PIGEON ROOST CREEK 58.0
END DESCRIPTION:
XS GIS Cut Line= 3
      3604528.68     10393541.48      3604492.11     10394291.64
      3604346.38     10395893.97
#Sta/Elev= 30
  4231.2  418.31  4259.9  418.11  4321.5  414.99  4481.7  400.64  4501.7  398.02
  4561.8  394.82  4812.1  396.76  4922.2  395.81  4972.2  396.84  4984.8  395.21
  4992.3  390.86  5002.3  390.08  5032.5  396.45    5153  397.06  5283.5  395.15
  5343.7   396.6  5434.1  395.27  5454.2  396.41  5624.9  398.02  5855.8  398.25
  5865.9  397.04  5885.7  388.83    5896  389.78  5906.1  394.18  5915.9   396.4
  5936.2  398.74  6252.2  418.77    6378  422.68  6473.1  424.35  6591.2  420.59
#Mann= 3 , 0 , 0
  4231.2     .16       0  4972.2     .07       0  5032.5     .05       0
#XS Ineff= 2 , 0
                         5692.61          398.47
Permanent Ineff=
       F       F
Bank Sta=4972.2,5032.5
XS Rating Curve= 0 ,0
Exp/Cntr=0.3,0.1

Type RM Length L Ch R = 1 ,34109   ,1208,1208,1208
BEGIN DESCRIPTION:
PIGEON ROOST CREEK 57.0
END DESCRIPTION:
XS GIS Cut Line= 3
       3603492.1     10393341.66      3603392.11     10394541.64
      3603321.21     10395500.69
#Sta/Elev= 30
    3808  428.04  3958.5  413.35  4139.1  392.76  4279.6  389.51  4347.3  390.88
  4530.5  389.63    4962   392.2    4972  390.79  4992.1  383.93  4999.1  383.52
  5001.9  383.02  5005.1  383.52  5009.6  388.94  5014.6  388.94  5022.2  391.95
  5052.2  390.87  5192.6  398.15  5292.9  400.68  5349.7  400.05  5414.9  402.48
  5523.5  407.39  5573.7  411.57  5583.7  413.86  5603.7  414.01    5714     424
  5770.5  431.02  5814.3  434.28  5854.4  434.91  5924.6  432.54  5973.8  428.57
#Mann= 5 ,-1 , 0
    3808     .16       0  4999.1     .07       0  5005.1     .16       0
  5414.9     .05       0  5770.5     .16       0
Bank Sta=4962,5022.2
XS Rating Curve= 0 ,0
Exp/Cntr=0.3,0.1

Type RM Length L Ch R = 1 ,32901   ,499,499,499
BEGIN DESCRIPTION:
PIGEON ROOST CREEK 56.0
END DESCRIPTION:
XS GIS Cut Line= 3
      3602619.82     10393445.12      3602708.36     10394670.86
      3603108.77     10395367.67
#Sta/Elev= 30
  4027.4  395.72  4114.2  394.08  4163.2  391.46  4274.6  388.33    4408  388.75
  4745.8  384.51  4775.9  384.79  4795.9  387.46    4816     385    4836   387.2
  4976.4  387.95  4986.4  386.65  4996.4  382.43  5003.5  382.16  5006.2  381.66
  5009.5  382.16  5016.5  386.48  5026.5  388.01  5156.9  386.54  5413.7  391.76
  5580.4  392.08  5649.4  396.73  5720.9  404.87  5751.5  409.85  5822.4  417.02
  5918.5   422.6  6014.6  421.27  6020.4   422.5  6036.2  421.17    6060  422.27
#Mann= 6 ,-1 , 0
  4027.4      .1       0  4163.2     .16       0  5003.5     .07       0
  5009.5     .16       0  5720.9      .1       0  5918.5     .16       0
Bank Sta=4976.4,5026.5
XS Rating Curve= 0 ,0
Exp/Cntr=0.3,0.1

Type RM Length L Ch R = 1 ,32402   ,566,566,566
BEGIN DESCRIPTION:
PIGEON ROOST CREEK 54.0
END DESCRIPTION:
XS GIS Cut Line= 3
      3602130.24     10393420.86       3602184.5     10394106.85
      3602582.98     10395638.12
#Sta/Elev= 30
  4075.6  428.68  4226.9  413.95  4249.3   410.6  4342.1  402.46  4377.3  401.65
  4507.7  403.22    4588   396.3  4666.6  385.98  4718.4  382.59  4814.5  382.99
  4849.8  385.56  4882.3  384.35  4913.3   386.3  4976.6  386.72    4993  381.15
  4995.8  380.65    4999  381.15  5006.3  382.44  5011.9  385.93    5027  387.27
    5306  383.92  5685.3  385.72  5806.8  397.25  5847.3  402.19    5895  410.38
  5923.2  413.22  6060.3  419.65  6132.6  421.03  6256.6  428.44    6346  431.72
#Mann= 5 ,-1 , 0
  4075.6     .16       0  4249.3      .1       0  4342.1     .16       0
    4993     .07       0    4999     .16       0
Bank Sta=4976.6,5011.9
XS Rating Curve= 0 ,0
Exp/Cntr=0.3,0.1

Type RM Length L Ch R = 1 ,31836   ,1380,1380,1380
BEGIN DESCRIPTION:
PIGEON ROOST CREEK 53.0
END DESCRIPTION:
XS GIS Cut Line= 3
      3601854.19     10393587.56      3601661.49     10394483.36
      3601125.02     10395676.08
#Sta/Elev= 30
  4282.1  409.23  4363.2  406.85  4528.7  396.12  4593.1  392.28  4693.2  381.95
    4767  383.41  4807.9  382.11  4869.3  384.64  4879.5     383  4890.6  382.85
  4920.5  385.84  4979.1  385.07  4984.2  385.65  4992.1  381.45  5002.3  380.71
  5022.7  385.27  5273.3  380.96  5303.6  382.37  5326.8  380.87  5401.7  382.72
  5522.7  379.69  5528.5  380.64  5591.2   381.4  5672.9  387.08  5788.6  396.16
  5961.7  412.76  6036.6  417.16  6078.6  417.65  6279.1   422.3  6506.2  424.73
#Mann= 5 ,-1 , 0
  4282.1      .1       0  4528.7     .16       0  4979.1     .07       0
  5022.7     .16       0  6078.6     .05       0
Bank Sta=4984.2,5022.7
XS Rating Curve= 0 ,0
Exp/Cntr=0.3,0.1

Type RM Length L Ch R = 1 ,30456   ,646,646,646
BEGIN DESCRIPTION:
PIGEON ROOST CREEK 52.0
END DESCRIPTION:
XS GIS Cut Line= 3
      3600980.93     10393394.82      3600642.11     10394391.64
      3600418.43     10395283.69
#Sta/Elev= 30
  3943.9  405.42  4044.9  404.71  4207.1  393.23  4415.8  390.37    4479  386.81
  4484.3  387.35  4510.4  382.38  4558.5  382.08  4658.8  382.84  4667.3  385.24
  4690.4  385.46  4722.1  381.02    4981  380.04  4991.1  377.09  4993.8  376.59
  4997.1  377.09  5014.7  378.04  5019.9  380.46  5068.9  378.41  5120.4  381.48
  5130.8  381.03    5172  386.43  5233.9  396.71    5303  403.01  5308.1  404.58
  5384.4  409.88    5514  412.22  5625.6  412.51  5755.9  416.15  5916.4   418.7
#Mann= 5 ,-1 , 0
  3943.9      .1       0  4558.5     .16       0  4991.1     .07       0
  4997.1     .16       0  5384.4     .05       0
#XS Ineff= 2 , 0
         4681.82  385.52
Permanent Ineff=
       F       F
Bank Sta=4981,5019.9
XS Rating Curve= 0 ,0
Exp/Cntr=0.3,0.1

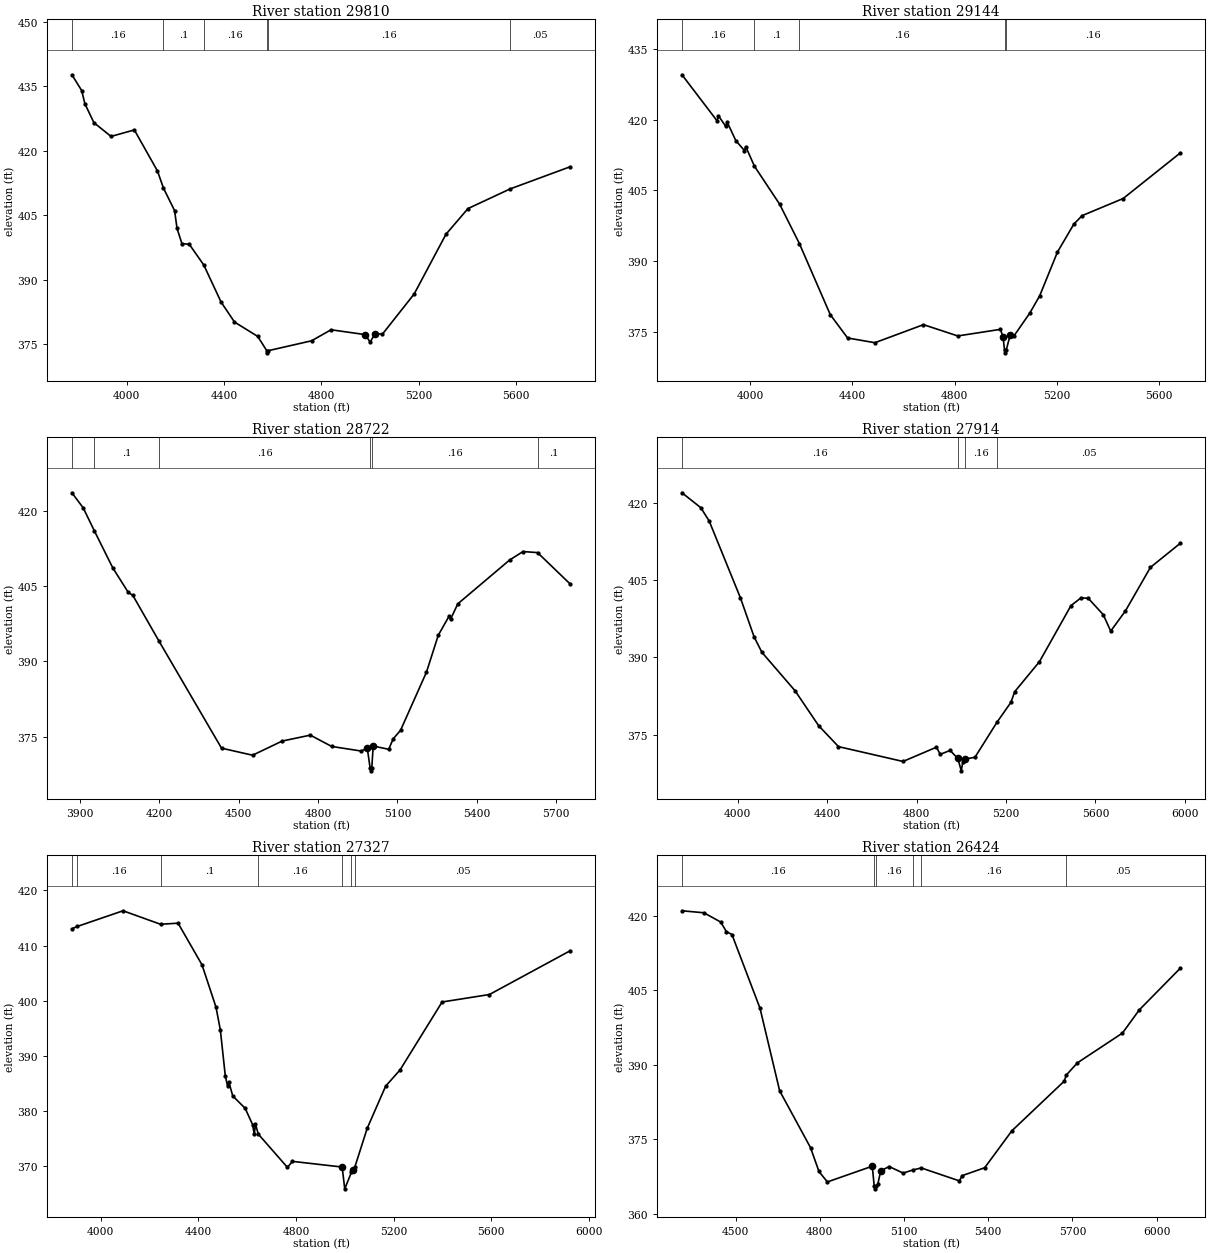
Type RM Length L Ch R = 1 ,29810   ,666,666,666
BEGIN DESCRIPTION:
PIGEON ROOST CREEK 51.0
END DESCRIPTION:
XS GIS Cut Line= 3
      3599892.11     10393091.64      3600067.11     10394881.92
      3600067.11     10395131.91
#Sta/Elev= 30
  3774.4  437.72  3814.6  434.05  3827.7  430.98  3864.8  426.58  3935.2  423.37
    4031  424.88  4126.1  415.32  4150.5  411.36  4196.4   406.1  4206.5  401.95
  4226.5  398.42  4256.7  398.27  4316.4  393.44  4387.3  384.83  4442.6  380.16
    4538  376.82  4575.2  373.49    4578  372.99  4581.2  373.49  4759.1  375.79
  4839.5  378.36  4980.1  377.23  5000.2  375.46  5020.3  377.49  5050.5  377.33
  5181.1   386.7  5311.7  400.59  5402.1  406.57    5575  411.14  5823.2  416.33
#Mann= 6 ,-1 , 0
  3774.4     .16       0  4150.5      .1       0  4316.4     .16       0
  4575.2     .07       0  4581.2     .16       0    5575     .05       0
Bank Sta=4980.1,5020.3
XS Rating Curve= 0 ,0
Exp/Cntr=0.3,0.1

Type RM Length L Ch R = 1 ,29144   ,422,422,422
BEGIN DESCRIPTION:
PIGEON ROOST CREEK 49.0
END DESCRIPTION:
XS GIS Cut Line= 3
      3599744.83     10393304.49      3599392.11     10394541.64
      3599189.27     10395172.59
#Sta/Elev= 30
  3734.2  429.59  3871.7  419.78  3876.9  420.87  3905.5  418.61  3910.7  419.56
  3944.6  415.61  3978.4  413.48  3983.6  414.32  4017.4  410.17    4116  402.09
  4193.4   393.7  4314.1   378.6  4381.8  373.65  4488.5  372.64  4678.4  376.48
  4812.7  374.08  4979.1  375.48  4989.5  373.95  4995.5  370.99  4998.3  370.49
  5001.5  370.99  5018.1  374.38  5031.2     374  5094.2  378.94    5133  382.63
  5202.4  391.92  5266.6  397.86  5298.7  399.65  5459.2  403.29  5683.4  413.01
#Mann= 5 ,-1 , 0
  3734.2     .16       0  4017.4      .1       0  4193.4     .16       0
  4995.5     .07       0  5001.5     .16       0
Bank Sta=4989.5,5018.1
XS Rating Curve= 0 ,0
Exp/Cntr=0.3,0.1

Type RM Length L Ch R = 1 ,28722   ,808,808,808
BEGIN DESCRIPTION:
PIGEON ROOST CREEK 48.0
END DESCRIPTION:
XS GIS Cut Line= 3
      3599571.23     10393283.67      3598942.11     10394541.64
      3599050.39     10395005.97
#Sta/Elev= 30
  3870.3   423.7  3912.8   420.7  3955.1   416.1  4024.6  408.71  4083.4  403.79
  4100.2  403.23  4199.1  394.09  4435.5  372.69  4552.9  371.28  4664.7  374.11
  4770.9  375.29  4851.9  373.03  4963.8  372.11  4986.1   372.7  4997.1  368.66
  4999.9  368.16  5003.1  368.66  5008.5  373.12  5067.2  372.46    5084  374.55
  5111.9  376.26  5209.7  387.86  5254.5  395.26  5295.5  399.08  5300.7  398.44
  5328.2  401.52  5523.7  410.26  5574.6  411.96  5629.5  411.75  5753.6  405.43
#Mann= 6 ,-1 , 0
  3870.3     .16       0  3955.1      .1       0  4199.1     .16       0
  4997.1     .07       0  5003.1     .16       0  5629.5      .1       0
Bank Sta=4986.1,5008.5
XS Rating Curve= 0 ,0
Exp/Cntr=0.3,0.1

Type RM Length L Ch R = 1 ,27914   ,587,587,587
BEGIN DESCRIPTION:
PIGEON ROOST CREEK 47.0
END DESCRIPTION:
XS GIS Cut Line= 3
      3599156.29     10392693.41      3598401.07     10394167.39
      3598240.03     10394718.03
#Sta/Elev= 30
  3750.8  421.97  3834.9  419.08  3872.4   416.5  4012.5  401.55  4073.5  393.99
  4108.4     391  4256.7  383.54  4362.1  376.77  4450.9   372.7  4739.5  369.82
  4889.3  372.59  4905.9   371.2  4950.3  371.96  4984.8   370.4  5000.1     368
  5007.3  369.75  5016.9  370.29  5061.3  370.63    5160  377.44  5222.3   381.3
  5238.9  383.35  5349.9  389.19    5491  400.08  5536.5   401.6  5568.3  401.48
  5635.2  398.31  5668.6  395.12  5734.4  399.04  5846.2  407.49  5980.7   412.2
#Mann= 4 ,-1 , 0
  3750.8     .16       0  4984.8     .07       0  5016.9     .16       0
    5160     .05       0
Bank Sta=4984.8,5016.9
XS Rating Curve= 0 ,0
Exp/Cntr=0.3,0.1

Type RM Length L Ch R = 1 ,27327   ,903,903,903
BEGIN DESCRIPTION:
PIGEON ROOST CREEK 45.0
END DESCRIPTION:
XS GIS Cut Line= 3
       3598296.9     10392464.27      3598092.11     10393541.64
      3597807.33     10394443.38
#Sta/Elev= 30
  3882.4  413.04  3904.3  413.46  4091.9  416.31  4245.6  413.86  4317.4  414.06
  4415.5  406.48  4472.8  398.79  4490.5  394.67  4510.8  386.33  4519.9  384.51
    4525  385.27  4541.4  382.67  4592.3  380.42  4622.8  377.45  4629.4  375.72
  4634.5  377.54    4646  375.74  4765.3   369.7  4785.7  370.79  4989.5  369.76
  5000.2   365.8  5027.6  368.81  5032.8  369.19  5041.8   369.8  5092.2   376.8
  5167.8  384.46  5226.8   387.4    5399  399.74    5593   401.1  5924.7  409.07
#Mann= 7 ,-1 , 0
  3882.4      .1       0  3904.3     .16       0  4245.6      .1       0
    4646     .16       0  4989.5     .07       0  5027.6     .16       0
  5041.8     .05       0
Bank Sta=4989.5,5032.8
XS Rating Curve= 0 ,0
Exp/Cntr=0.3,0.1

Type RM Length L Ch R = 1 ,26424   ,553,553,553
BEGIN DESCRIPTION:
PIGEON ROOST CREEK 44.0
END DESCRIPTION:
XS GIS Cut Line= 3
       3597541.7     10392573.64      3597542.11     10393291.64
      3597484.49     10394348.17
#Sta/Elev= 30
    4309  420.99    4387  420.59    4447  418.72    4467  416.81    4487  416.21
    4587  401.36    4657  384.73    4767  373.29    4797  368.49    4827  366.38
    4987  369.55    4994  365.49  4996.7  364.99    5000  365.49    5007     366
    5017   368.6    5047  369.48  5097.1  368.16  5131.7  368.79  5161.4   369.2
  5297.4  366.59  5307.4  367.65  5387.5  369.24  5484.4  376.68  5671.3   386.7
  5677.8  387.88    5718  390.37  5878.3  396.36  5938.4  401.03  6085.1  409.46
#Mann= 6 ,-1 , 0
    4309     .16       0    4994     .07       0    5000     .16       0
  5131.7     .05       0  5161.4     .16       0  5677.8     .05       0
Bank Sta=4987,5017
XS Rating Curve= 0 ,0
Exp/Cntr=0.3,0.1

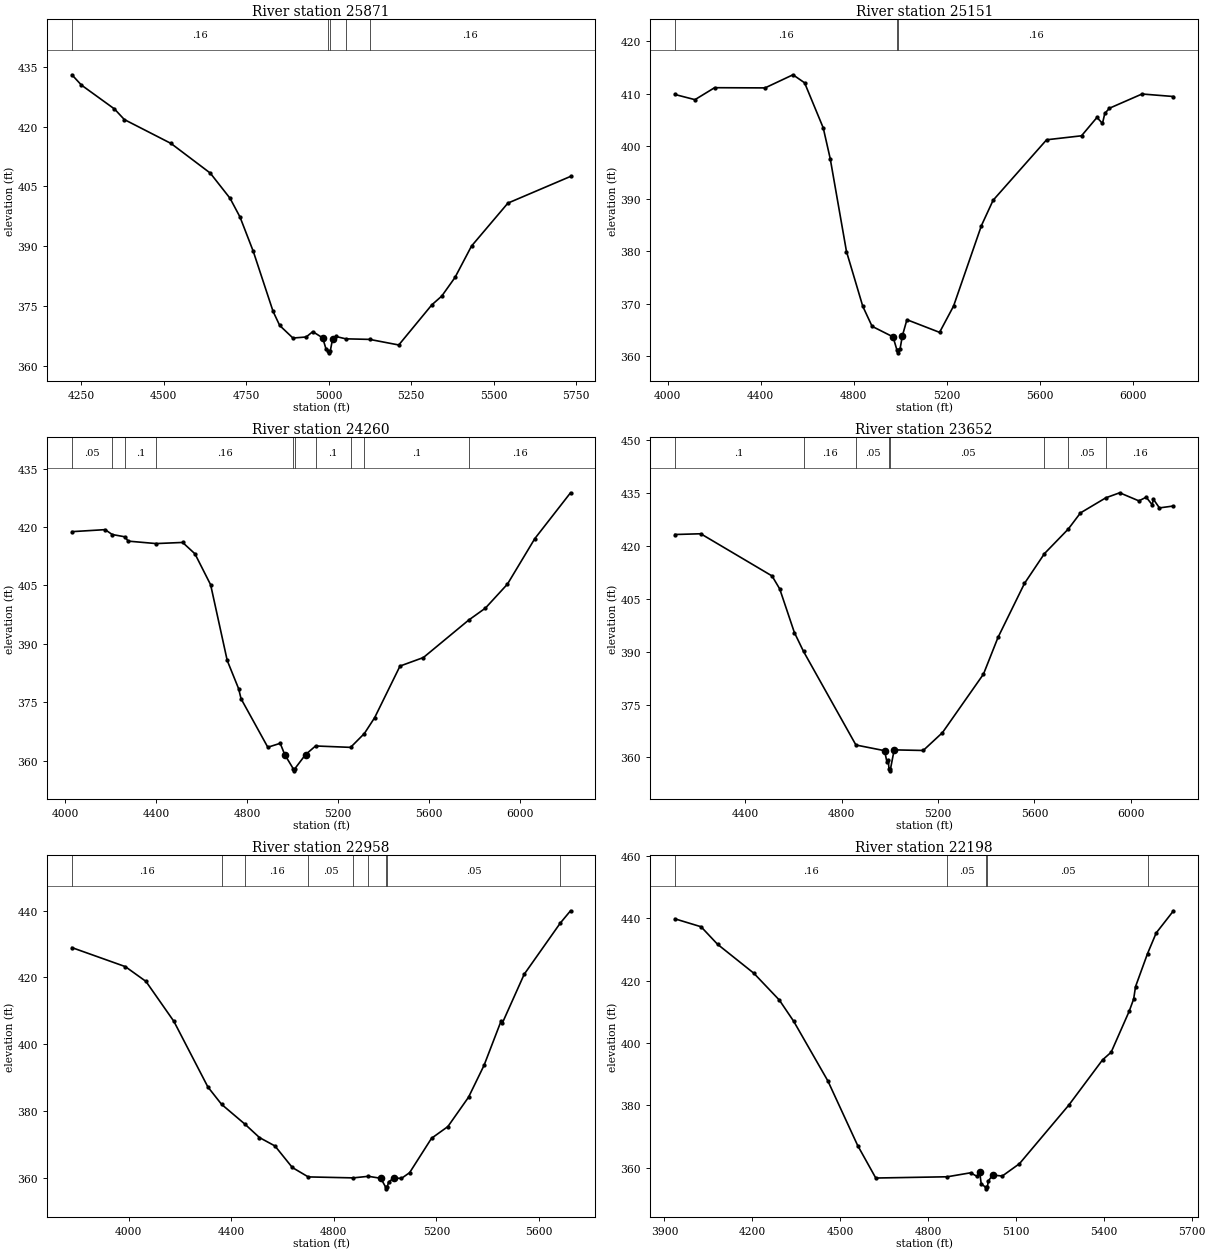
Type RM Length L Ch R = 1 ,25871   ,720,720,720
BEGIN DESCRIPTION:
PIGEON ROOST CREEK 43.0
END DESCRIPTION:
XS GIS Cut Line= 3
      3597100.44     10392622.86      3597100.44     10392922.89
      3597026.07     10394130.97
#Sta/Elev= 30
  4221.9  432.98  4250.7   430.4  4350.7  424.42  4380.7  421.76  4521.9  415.78
  4640.9  408.35    4701  402.02  4731.1  397.33  4771.2  388.75  4831.3  373.68
  4851.3  370.16  4891.4  367.01  4931.5  367.27  4951.5  368.61  4981.5  367.05
  4991.6  364.27  4998.6   363.8  5001.3   363.3  5004.6   363.8  5011.6  366.78
  5021.6   367.4  5051.5  366.81  5123.7  366.67    5212  365.27  5312.2  375.33
  5342.2  377.52  5382.3  382.18  5432.4  390.06  5542.6  400.82  5732.3  407.51
#Mann= 5 ,-1 , 0
  4221.9     .16       0  4998.6     .07       0  5004.6     .16       0
  5051.5      .1       0  5123.7     .16       0
Bank Sta=4981.5,5011.6
XS Rating Curve= 0 ,0
Exp/Cntr=0.3,0.1

Type RM Length L Ch R = 1 ,25151   ,891,891,891
BEGIN DESCRIPTION:
PIGEON ROOST CREEK 41.0
END DESCRIPTION:
XS GIS Cut Line= 3
      3596590.03     10392294.74      3596440.02     10392644.77
      3596375.03     10394406.85
#Sta/Elev= 30
  4030.9  409.89  4117.3   408.9  4201.6  411.18  4418.6  411.14  4538.7  413.64
  4588.7  412.11  4668.8  403.53  4698.8  397.68  4768.8  379.98  4838.9  369.54
  4878.9  365.73    4969  363.72    4986  361.18  4988.7  360.68    4992  361.18
    4999  361.37    5009   363.9  5028.7  366.99  5169.1  364.58  5229.2  369.58
  5349.2  384.93  5399.3  389.74  5629.4  401.26  5779.5  402.02    5846  405.52
  5869.6  404.37  5879.6  406.28  5899.6  407.27  6039.7  409.98    6175   409.5
#Mann= 3 ,-1 , 0
  4030.9     .16       0    4986     .07       0    4992     .16       0
Bank Sta=4969,5009
XS Rating Curve= 0 ,0
Exp/Cntr=0.3,0.1

Type RM Length L Ch R = 1 ,24260   ,608,608,608
BEGIN DESCRIPTION:
PIGEON ROOST CREEK 40.0
END DESCRIPTION:
XS GIS Cut Line= 3
      3595468.78     10392297.61      3595716.06     10393819.77
      3595765.95     10394468.24
#Sta/Elev= 30
  4029.7  418.81  4175.6  419.33  4206.9  418.08  4263.2  417.48  4276.9  416.38
  4399.9  415.75  4516.6  416.04  4570.7  413.12  4639.7  405.16  4712.6  385.72
  4762.9  378.44  4773.4  375.89  4891.1  363.42  4945.6  364.43  4965.8   361.5
  5003.4  357.86  5006.1  357.36  5009.4  357.86    5057  361.53  5101.1  363.75
  5255.1  363.39  5315.7  366.95    5361  371.03  5472.4  384.28  5575.3  386.47
  5773.7  396.06  5847.8  399.16  5944.8  405.33  6065.1  417.02  6222.2   428.8
#Mann= 10 ,-1 , 0
  4029.7     .05       0  4206.9     .16       0  4263.2      .1       0
  4399.9     .16       0  5003.4     .07       0  5009.4     .16       0
  5101.1      .1       0  5255.1     .05       0  5315.7      .1       0
  5773.7     .16       0
Bank Sta=4965.8,5057
XS Rating Curve= 0 ,0
Exp/Cntr=0.3,0.1

Type RM Length L Ch R = 1 ,23652   ,694,694,694
BEGIN DESCRIPTION:
PIGEON ROOST CREEK 39.0
END DESCRIPTION:
XS GIS Cut Line= 3
      3595307.72     10392475.03      3595257.73     10392874.98
      3594666.88     10394432.51
#Sta/Elev= 30
  4108.3  423.26  4215.7  423.47  4511.4   411.5  4543.3  407.82  4604.1  395.45
  4642.1  390.08  4859.5  363.53  4978.4  361.92  4988.1  358.72  4993.4  359.37
  4996.8   356.7  4999.5   356.2  5002.8   356.7  5018.2  362.15  5138.8  361.98
  5218.5  367.04  5388.7  383.64    5449  394.05  5558.8  409.37  5641.8  417.84
  5740.6  424.81  5791.2  429.39  5896.6  433.68    5954   435.1  6033.7   432.8
  6063.9  433.85  6088.7  431.71    6094  433.24  6118.8  430.81  6177.2  431.35
#Mann= 8 ,-1 , 0
  4108.3      .1       0  4642.1     .16       0  4859.5     .05       0
  4996.8    .035       0  5002.8     .05       0  5641.8     .16       0
  5740.6     .05       0  5896.6     .16       0
Bank Sta=4978.4,5018.2
XS Rating Curve= 0 ,0
Exp/Cntr=0.3,0.1

Type RM Length L Ch R = 1 ,22958   ,760,760,760
BEGIN DESCRIPTION:
PIGEON ROOST CREEK 38.0
END DESCRIPTION:
XS GIS Cut Line= 3
      3594640.65     10391974.67      3594540.02     10392895.81
      3594427.13      10393906.8
#Sta/Elev= 30
  3779.2  428.93  3987.4  423.24  4067.9  418.81  4176.9  406.84  4309.3  387.22
  4362.7  382.02  4453.3  376.12  4510.5  372.07  4570.9  369.56  4638.4  363.12
  4700.6   360.3  4875.6  360.01  4935.1  360.48  4983.4  359.88  5002.5  357.23
  5005.2  356.73  5008.5  357.23  5013.6  358.73  5033.7  359.98  5063.9  359.85
  5095.8  361.57  5181.1  371.85    5245  375.37  5325.5  384.16  5385.9  393.68
  5452.1   406.9  5457.2  406.33  5542.5  420.95  5683.4  436.29  5723.1  439.95
#Mann= 9 ,-1 , 0
  3779.2     .16       0  4362.7     .05       0  4453.3     .16       0
  4700.6     .05       0  4875.6     .16       0  4935.1     .05       0
  5002.5     .03       0  5008.5     .05       0  5683.4      .1       0
Bank Sta=4983.4,5033.7
XS Rating Curve= 0 ,0
Exp/Cntr=0.3,0.1

Type RM Length L Ch R = 1 ,22198   ,661,661,661
BEGIN DESCRIPTION:
PIGEON ROOST CREEK 36.0
END DESCRIPTION:
XS GIS Cut Line= 3
      3593458.36     10392339.27      3593809.81     10393331.23
      3594059.82     10393931.25
#Sta/Elev= 30
  3935.6  439.81    4025  437.26  4081.4  431.63    4205  422.36  4292.3  413.73
  4341.3  406.92    4458  387.78  4559.7  367.06  4621.5  356.63  4865.6  357.03
  4945.3  358.31  4967.2  357.15  4976.2  358.41  4981.5  354.82  4996.3  353.66
    4999  353.16  5002.3  353.66  5005.8   355.7  5020.9  357.57  5053.4  357.27
    5112  361.22  5280.9  380.07  5395.8  394.55  5425.1  396.99  5486.8  410.17
    5502  414.08  5508.4  418.06  5549.4  428.66  5578.9  435.27    5638  442.39
#Mann= 5 ,-1 , 0
  3935.6     .16       0  4865.6     .05       0  4996.3     .03       0
  5002.3     .05       0  5549.4     .16       0
Bank Sta=4976.2,5020.9
XS Rating Curve= 0 ,0
Exp/Cntr=0.3,0.1