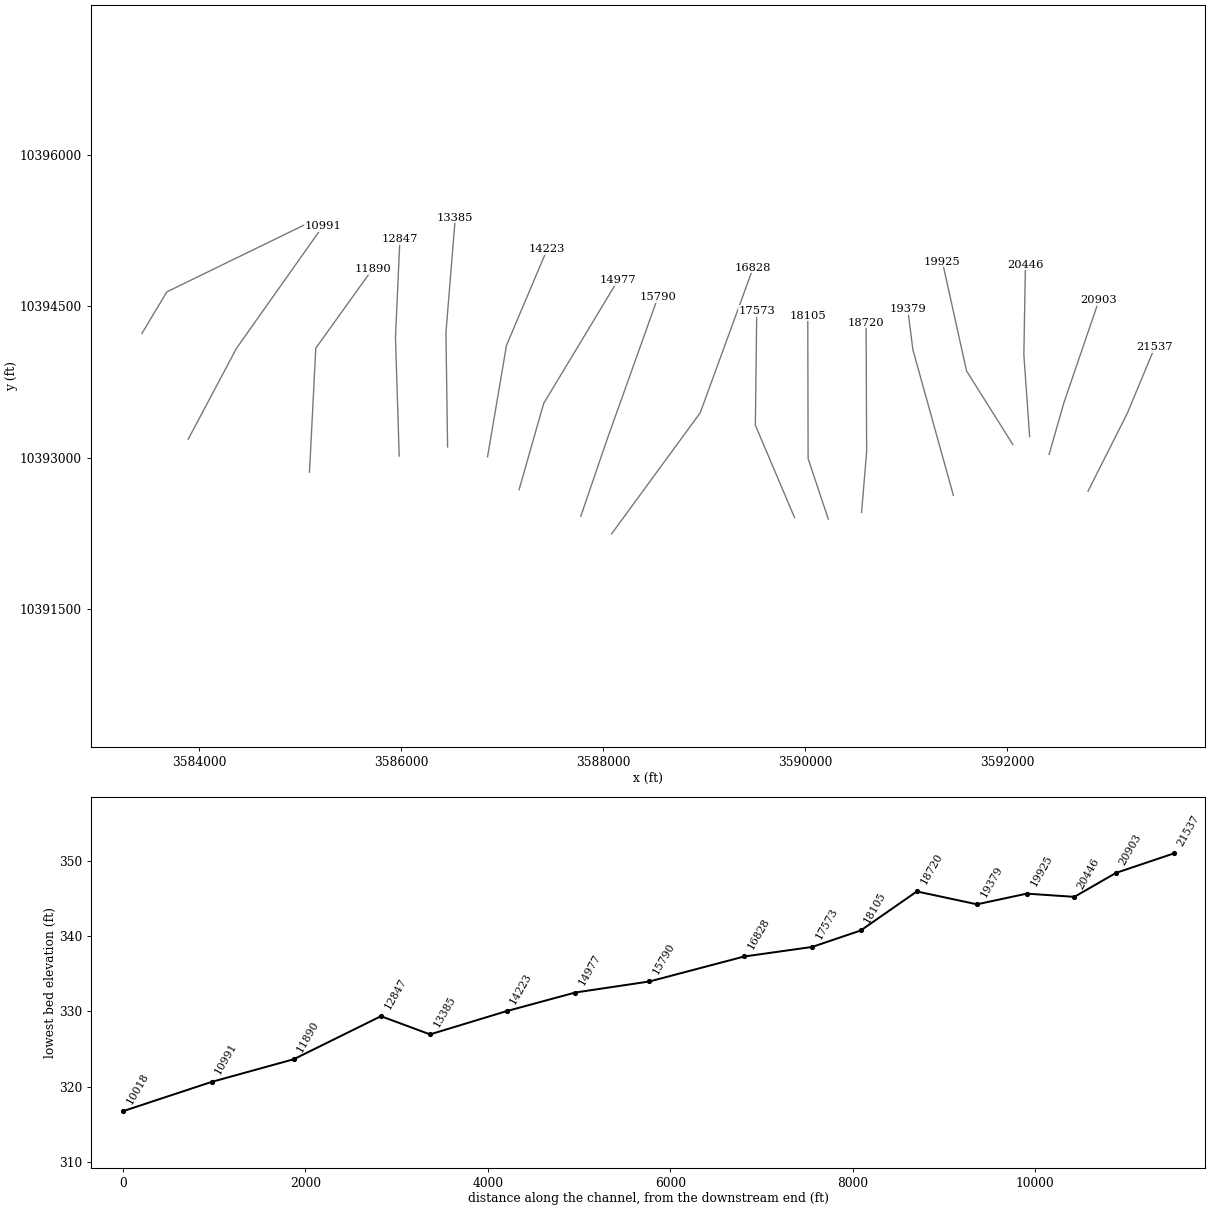
HEC-RAS study PIGEON ROOST CREEK.prj: PIGEON ROOST CREEK Base Level Engineering

--- PIGEON ROOST CREEK.g01 (geometry) --- (continued)

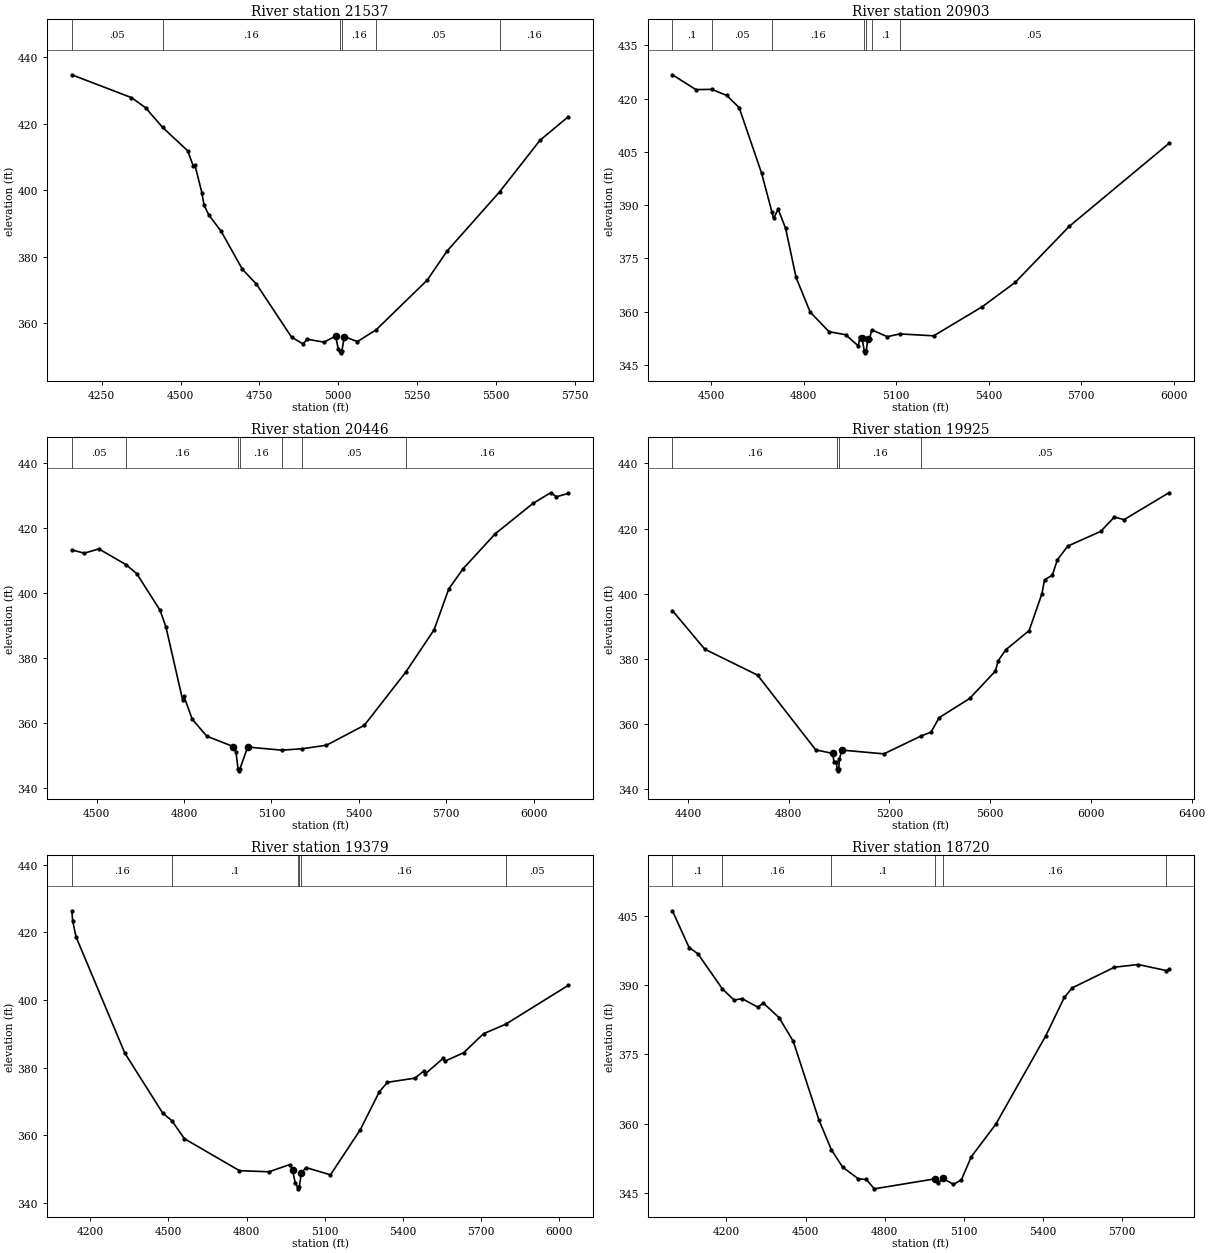
Type RM Length L Ch R = 1 ,21537   ,634,634,634
BEGIN DESCRIPTION:
PIGEON ROOST CREEK 35.0
END DESCRIPTION:
XS GIS Cut Line= 3
      3592802.12      10392667.4      3593192.11     10393441.64
      3593463.56     10394094.44
#Sta/Elev= 30
  4155.4  434.75  4344.6  427.87  4389.2  424.83  4443.2  418.92  4523.1  411.82
  4539.8   407.4  4545.4  407.66  4567.7  399.27  4574.4  395.53    4590  392.51
  4629.1  387.57    4696  376.21  4740.6  371.72  4852.2  355.72  4887.9  353.72
  4902.4   355.1  4955.1  354.22  4991.6  356.08  4999.9  352.28  5005.4  351.51
  5008.1  351.01  5011.4  351.51  5019.5  355.92  5060.8  354.39  5120.5  357.97
  5282.2  372.91  5344.8  381.63  5511.4  399.47  5639.7  415.02  5729.3  422.12
#Mann= 6 ,-1 , 0
  4155.4     .05       0  4443.2     .16       0  5005.4     .07       0
  5011.4     .16       0  5120.5     .05       0  5511.4     .16       0
Bank Sta=4991.6,5019.5
XS Rating Curve= 0 ,0
Exp/Cntr=0.3,0.1

Type RM Length L Ch R = 1 ,20903   ,457,457,457
BEGIN DESCRIPTION:
PIGEON ROOST CREEK 34.0
END DESCRIPTION:
XS GIS Cut Line= 3
      3592416.71     10393032.01      3592562.53     10393542.39
      3592911.48     10394563.19
#Sta/Elev= 30
  4374.5   426.7  4450.4  422.53  4502.1  422.59  4550.9  420.87  4590.8  417.46
  4663.6  399.01  4697.5  387.94  4702.6  386.25  4717.3  388.88  4741.6  383.45
  4775.4  369.64  4821.3  359.88    4882  354.39  4936.2  353.51  4977.2  350.37
  4982.5  352.94  4989.1  352.65  4996.6  348.92  4999.4  348.42  5002.6  348.92
  5008.6  352.35  5013.8   352.3  5020.5   354.9  5071.2  352.96  5111.7  353.75
  5221.6  353.21    5379   361.4  5485.8  368.25  5660.8  384.01  5984.1  407.37
#Mann= 7 ,-1 , 0
  4374.5      .1       0  4502.1     .05       0  4697.5     .16       0
  4996.6     .07       0  5002.6     .16       0  5020.5      .1       0
  5111.7     .05       0
Bank Sta=4989.1,5008.6
XS Rating Curve= 0 ,0
Exp/Cntr=0.3,0.1

Type RM Length L Ch R = 1 ,20446   ,521,521,521
BEGIN DESCRIPTION:
PIGEON ROOST CREEK 33.0
END DESCRIPTION:
XS GIS Cut Line= 3
      3592223.99     10393209.01       3592166.7     10394021.55
      3592182.32     10394912.16
#Sta/Elev= 30
  4414.1  413.36  4456.8  412.35    4507  413.66    4600  408.84  4637.3  406.01
  4717.5   394.7  4737.5  389.58  4794.5  367.19  4799.5  368.18  4827.8  361.13
  4877.9  355.91  4968.1  352.73  4978.1     351  4985.2  345.73  4987.9  345.23
  4991.2  345.73  5018.2  352.57    5136   351.6    5206  352.05  5288.8  353.13
  5418.8  359.26  5561.2  375.67  5658.8  388.77  5708.8  401.31  5758.8  407.61
  5868.8  418.35  5998.9  427.74  6058.9  430.97  6078.9  429.75  6119.4  430.77
#Mann= 7 ,-1 , 0
  4414.1     .05       0    4600     .16       0  4985.2     .07       0
  4991.2     .16       0    5136      .1       0    5206     .05       0
  5561.2     .16       0
Bank Sta=4968.1,5018.2
XS Rating Curve= 0 ,0
Exp/Cntr=0.3,0.1

Type RM Length L Ch R = 1 ,19925   ,546,546,546
BEGIN DESCRIPTION:
PIGEON ROOST CREEK 32.0
END DESCRIPTION:
XS GIS Cut Line= 3
      3592057.32     10393130.93      3591598.99     10393860.09
      3591359.39     10394943.47
#Sta/Elev= 30
  4338.5  394.84  4466.9     383  4676.6  375.03  4907.4  352.09  4974.5  351.02
  4980.4  348.23    4989  348.48  4992.7  346.16  4995.5  345.66  4998.7  346.16
  5001.6   349.3    5011  352.03    5178  350.87  5324.5  356.32  5365.2  357.56
  5397.4  361.98  5518.8  367.89  5620.7   376.3  5631.5  379.44  5662.2  382.84
  5754.4  388.69  5805.5  400.05  5815.8  404.29  5846.6  405.72    5867  410.49
  5908.1  414.64    6039  419.16  6092.9  423.56  6131.4  422.75  6309.3     431
#Mann= 4 ,-1 , 0
  4338.5     .16       0  4992.7     .07       0  4998.7     .16       0
  5324.5     .05       0
Bank Sta=4974.5,5011
XS Rating Curve= 0 ,0
Exp/Cntr=0.3,0.1

Type RM Length L Ch R = 1 ,19379   ,659,659,659
BEGIN DESCRIPTION:
PIGEON ROOST CREEK 31.0
END DESCRIPTION:
XS GIS Cut Line= 3
      3591468.78     10392625.73      3591067.11     10394071.85
       3591017.1     10394471.87
#Sta/Elev= 30
  4129.9  426.39  4133.5  423.27  4146.4  418.63  4333.2  384.35  4478.5  366.62
  4513.8  364.37  4561.6  359.06  4772.8  349.61    4886  349.28  4966.3  351.42
  4976.7  349.67  4987.1  345.89  4996.1  344.74  4998.8  344.24  5002.1  344.74
  5010.5  349.01  5028.2  350.52    5122  348.38  5236.2   361.7  5308.8  372.85
    5340  375.71  5446.4  376.95  5480.7  379.13  5485.9  378.23  5554.4  382.82
  5559.6  381.91  5633.2  384.48  5708.8  390.07  5793.8  392.87  6033.9  404.36
#Mann= 6 ,-1 , 0
  4129.9     .16       0  4513.8      .1       0  4996.1     .07       0
  5002.1      .1       0  5010.5     .16       0  5793.8     .05       0
Bank Sta=4976.7,5010.5
XS Rating Curve= 0 ,0
Exp/Cntr=0.3,0.1

Type RM Length L Ch R = 1 ,18720   ,615,615,615
BEGIN DESCRIPTION:
PIGEON ROOST CREEK 30.0
END DESCRIPTION:
XS GIS Cut Line= 3
      3590559.19     10392458.65      3590609.18     10393058.61
       3590604.2     10394337.96
#Sta/Elev= 30
  3995.5  406.06  4058.7  398.12  4092.3  396.75  4184.6  389.19  4229.3  386.76
  4259.4  387.07  4319.6  385.22  4339.7  386.13  4399.9  382.95  4453.6  377.82
  4550.4   360.9  4597.5  354.44  4640.6  350.64  4700.6  348.09  4730.6  347.99
  4760.3  345.95  4990.6  348.11  5000.6  347.12  5020.6   348.2  5060.6  346.92
  5090.6   347.9  5128.2   352.9  5220.6  359.88  5410.6  379.06  5480.6  387.33
  5510.6  389.39  5670.6  393.86  5760.6  394.44  5867.1  393.14  5876.9   393.4
#Mann= 6 ,-1 , 0
  3995.5      .1       0  4184.6     .16       0  4597.5      .1       0
  4990.6     .07       0  5020.6     .16       0  5867.1     .05       0
Bank Sta=4990.6,5020.6
XS Rating Curve= 0 ,0
Exp/Cntr=0.3,0.1

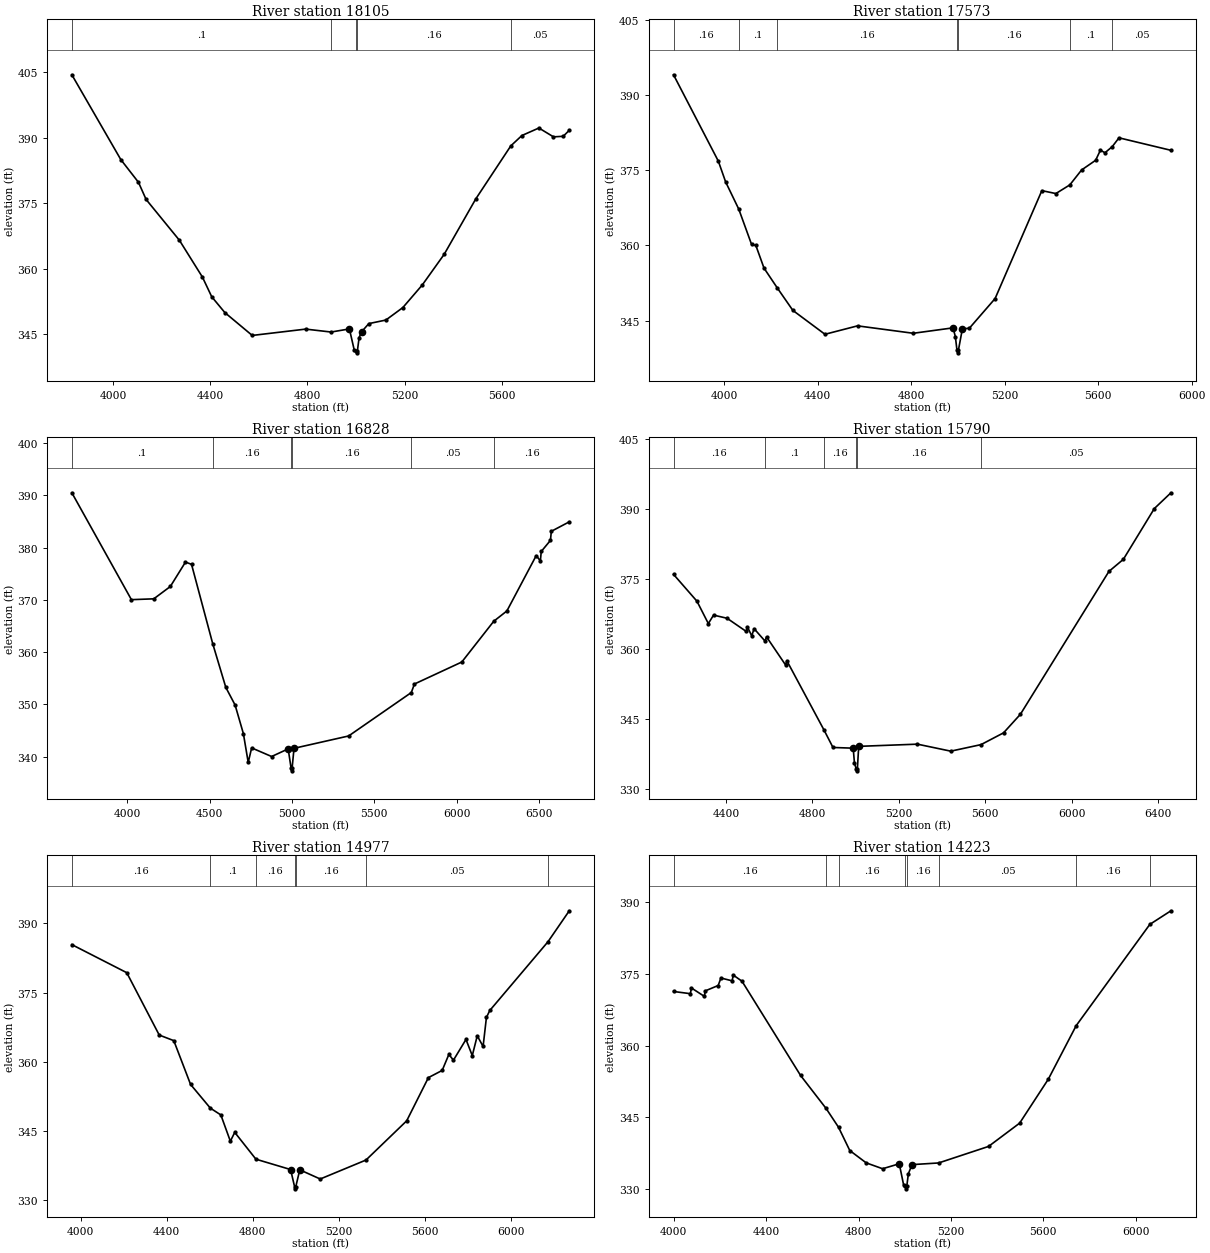
Type RM Length L Ch R = 1 ,18105   ,532,532,532
BEGIN DESCRIPTION:
PIGEON ROOST CREEK 29.0
END DESCRIPTION:
XS GIS Cut Line= 3
      3590229.61     10392391.64      3590029.61     10392991.64
      3590026.07     10394406.78
#Sta/Elev= 30
  3830.6  404.38  4032.2  384.97  4104.7  379.79  4136.3  375.85  4273.3  366.52
  4368.2  358.08  4406.4  353.59  4460.4  349.97  4573.1  344.74  4793.1  346.19
  4897.7  345.52  4973.1  346.23  4993.1  341.38  5000.1  341.26  5002.8  340.76
  5006.1  341.26  5013.1  344.24  5023.1  345.57  5053.1  347.45  5123.1  348.26
  5193.1  351.12  5273.1  356.29  5363.1  363.29  5493.1  375.96  5637.5  388.11
  5683.1  390.48  5753.1   392.2  5813.1  390.18  5853.1   390.3  5878.2  391.68
#Mann= 5 ,-1 , 0
  3830.6      .1       0  4897.7     .16       0  5000.1     .07       0
  5006.1     .16       0  5637.5     .05       0
Bank Sta=4973.1,5023.1
XS Rating Curve= 0 ,0
Exp/Cntr=0.3,0.1

Type RM Length L Ch R = 1 ,17573   ,745,745,745
BEGIN DESCRIPTION:
PIGEON ROOST CREEK 28.0
END DESCRIPTION:
XS GIS Cut Line= 3
      3589895.85     10392405.27      3589506.97      10393321.9
      3589520.86     10394453.81
#Sta/Elev= 30
  3783.7  394.01  3975.3   376.8  4006.7  372.64  4062.9  367.21  4117.6  360.18
  4135.9  359.98  4170.8  355.46  4227.7   351.5  4294.2  347.03  4431.5  342.27
  4570.8  343.95  4809.2  342.47  4979.2  343.55  4989.2  341.82  4996.2  339.07
  4998.9  338.57  5002.2  339.07  5019.2  343.34  5049.2  343.48  5159.2  349.39
  5359.2  370.91  5419.2  370.33  5478.7  372.05  5529.2  375.03  5589.2  376.96
  5609.7  378.98  5629.2  378.46  5660.4  379.69  5689.2  381.44  5911.4  378.95
#Mann= 7 ,-1 , 0
  3783.7     .16       0  4062.9      .1       0  4227.7     .16       0
  4996.2     .07       0  5002.2     .16       0  5478.7      .1       0
  5660.4     .05       0
Bank Sta=4979.2,5019.2
XS Rating Curve= 0 ,0
Exp/Cntr=0.3,0.1

Type RM Length L Ch R = 1 ,16828   ,1038,1038,1038
BEGIN DESCRIPTION:
PIGEON ROOST CREEK 27.0
END DESCRIPTION:
XS GIS Cut Line= 3
      3588083.37     10392245.53      3588961.14     10393445.51
      3589486.13     10394884.37
#Sta/Elev= 30
  3664.7   390.5  4026.1  370.05  4161.9  370.21  4262.3  372.57  4354.2  377.24
  4390.9  376.81  4519.3  361.65    4599  353.26  4655.3  349.89  4705.5  344.43
  4734.9  338.91  4755.7  341.69  4876.9  340.04  4977.3   341.5  4995.2   337.8
  4997.9   337.3  5001.2   337.8  5012.8  341.61  5344.1  343.97  5724.6  352.28
  5743.4  353.91  6030.9  358.12  6224.8  365.92  6304.5  367.89  6482.5  378.48
  6507.7  377.46    6513  379.27  6568.8  381.39  6574.2  383.13  6683.1  384.94
#Mann= 6 ,-1 , 0
  3664.7      .1       0  4519.3     .16       0  4995.2     .07       0
  5001.2     .16       0  5724.6     .05       0  6224.8     .16       0
Bank Sta=4977.3,5012.8
XS Rating Curve= 0 ,0
Exp/Cntr=0.3,0.1

Type RM Length L Ch R = 1 ,15790   ,813,813,813
BEGIN DESCRIPTION:
PIGEON ROOST CREEK 26.0
END DESCRIPTION:
XS GIS Cut Line= 3
      3587777.79     10392419.09      3588042.11     10393191.64
       3588542.1     10394591.62
#Sta/Elev= 30
  4156.6  376.03    4265  370.29  4317.8   365.5    4342  367.31  4404.6  366.63
  4493.3  363.81  4498.5   364.8  4518.6  362.88  4529.8   364.4  4580.1  361.76
  4587.2  362.65  4675.8  356.61  4681.1  357.56  4853.9  342.67  4894.9  338.98
  4988.5  338.83  4994.4   335.6    5002  334.48  5004.7  333.98    5008  334.48
    5014  339.22  5285.8  339.69  5440.3  338.19  5580.3  339.59  5684.6  342.11
  5762.6  346.08  6172.5  376.66  6239.4  379.25  6382.7  390.11  6459.7  393.49
#Mann= 6 ,-1 , 0
  4156.6     .16       0  4580.1      .1       0  4853.9     .16       0
    5002     .07       0    5008     .16       0  5580.3     .05       0
Bank Sta=4988.5,5014
XS Rating Curve= 0 ,0
Exp/Cntr=0.3,0.1

Type RM Length L Ch R = 1 ,14977   ,754,754,754
BEGIN DESCRIPTION:
PIGEON ROOST CREEK 25.0
END DESCRIPTION:
XS GIS Cut Line= 3
      3587166.69     10392682.99      3587409.75     10393537.18
      3588145.05     10394758.06
#Sta/Elev= 30
  3959.7  385.41    4215  379.33  4366.1  365.82  4433.8  364.61  4511.9  355.12
  4603.8  349.99  4652.6  348.52  4696.8  342.83  4717.3  344.74  4815.8  338.93
    4977  336.69  4995.3  333.01  4998.1  332.51  5001.3  333.01  5019.7  336.63
  5114.8  334.64  5327.6  338.75  5516.8  347.24  5617.8   356.6  5681.9  358.16
    5713  361.62  5734.3  360.38  5792.6  364.87  5821.9  361.37    5845  365.66
  5872.2  363.35  5887.7  369.64  5903.3  371.14  6174.1  386.04    6273  392.74
#Mann= 7 ,-1 , 0
  3959.7     .16       0  4603.8      .1       0  4815.8     .16       0
  4995.3     .07       0  5001.3     .16       0  5327.6     .05       0
  6174.1     .16       0
Bank Sta=4977,5019.7
XS Rating Curve= 0 ,0
Exp/Cntr=0.3,0.1

Type RM Length L Ch R = 1 ,14223   ,838,838,838
BEGIN DESCRIPTION:
PIGEON ROOST CREEK 23.0
END DESCRIPTION:
XS GIS Cut Line= 3
      3586854.19     10393009.39       3587041.7     10394113.57
      3587444.46     10395064.93
#Sta/Elev= 30
  3999.2  371.36  4071.9   370.9  4076.9  372.09  4132.2  370.35  4137.2   371.5
  4192.5  372.61  4204.4  374.18  4252.8  373.59  4257.8  374.79  4295.6  373.51
  4549.2  353.77  4659.5  346.87  4713.4  342.93  4762.2  338.05  4833.2  335.47
  4904.2  334.24  4976.3  335.28  4995.5  330.77  5002.7  330.53  5005.4  330.03
  5008.7  330.53  5015.8  333.19  5031.5   335.1  5146.6  335.45  5362.7  338.91
  5497.4  343.79  5621.2  352.97  5742.2  364.21  6060.9  385.41  6152.3  388.26
#Mann= 8 ,-1 , 0
  3999.2     .16       0  4659.5      .1       0  4713.4     .16       0
  5002.7     .07       0  5008.7     .16       0  5146.6     .05       0
  5742.2     .16       0  6060.9     .05       0
Bank Sta=4976.3,5031.5
XS Rating Curve= 0 ,0
Exp/Cntr=0.3,0.1

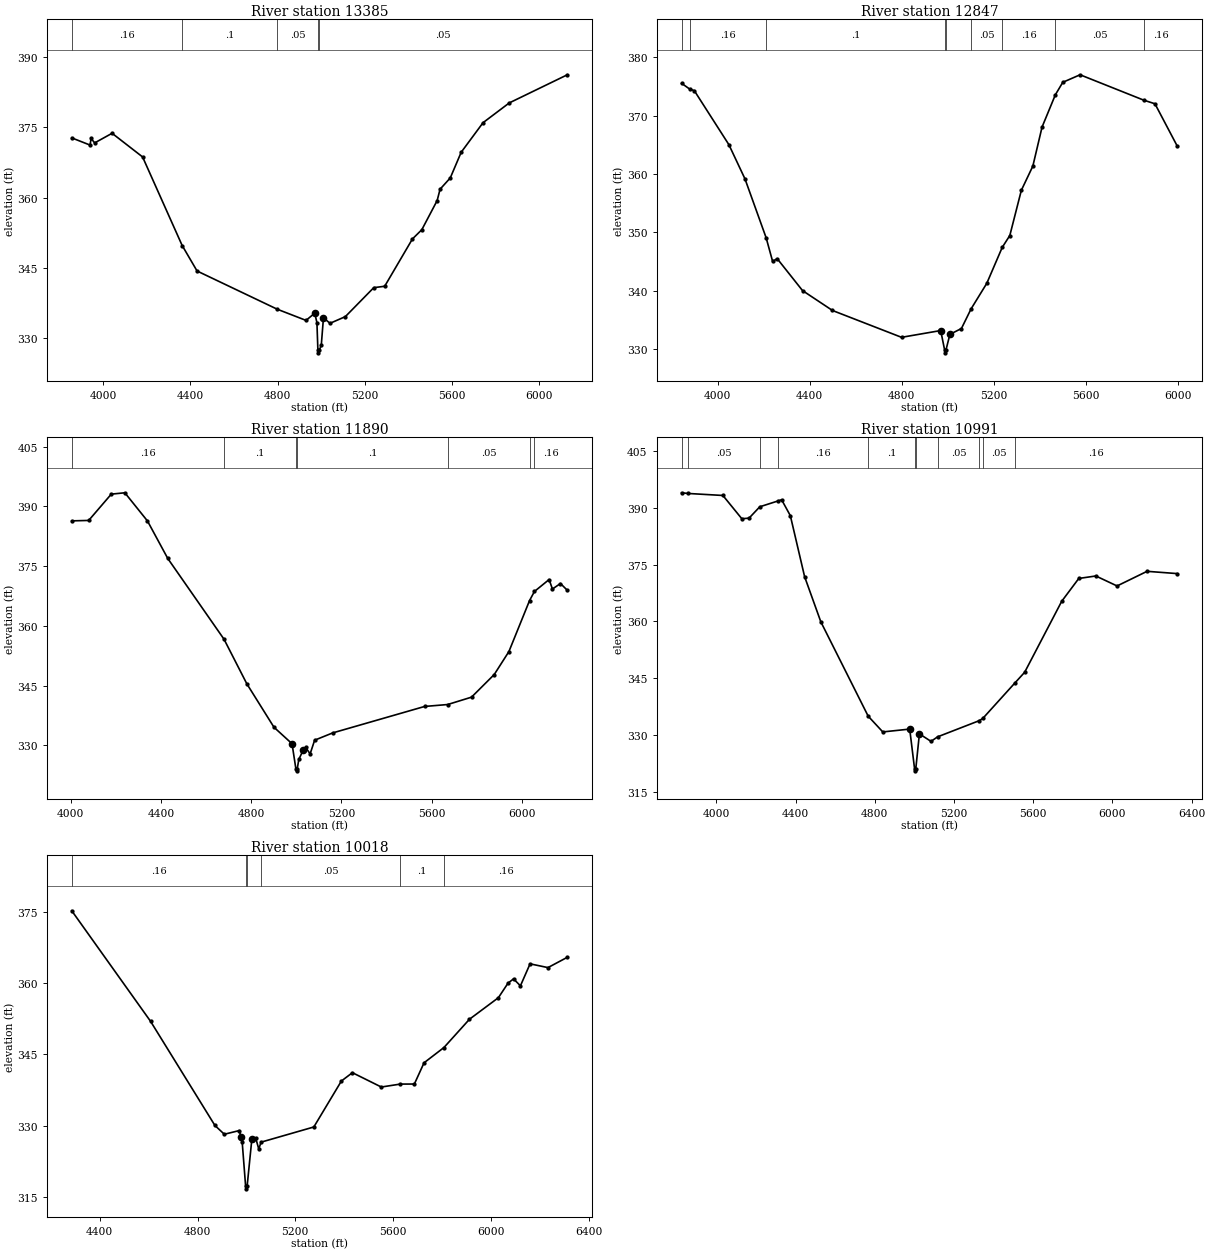
Type RM Length L Ch R = 1 ,13385   ,538,538,538
BEGIN DESCRIPTION:
PIGEON ROOST CREEK 22.0
END DESCRIPTION:
XS GIS Cut Line= 3
      3586458.36     10393106.58      3586442.11     10394241.64
      3586534.72     10395377.09
#Sta/Elev= 30
  3855.2  372.72  3939.1  371.19  3944.1   372.6  3960.3  371.65  4040.3   373.7
  4180.3  368.66  4361.9   349.8  4430.3  344.37  4798.3  336.23  4930.4  333.85
  4970.4  335.39  4980.4  333.38  4984.9  327.44  4987.6  326.94  4990.9  327.44
  5000.4  328.56  5010.4  334.41  5040.5  333.23  5110.8  334.65  5241.2  340.82
  5291.4  341.12  5418.8   351.2  5461.9  353.17  5532.2  359.37  5545.6  361.79
  5592.4  364.19  5642.5  369.66  5742.9  375.96  5863.3  380.17  6129.6  386.16
#Mann= 5 ,-1 , 0
  3855.2     .16       0  4361.9      .1       0  4798.3     .05       0
  4984.9     .03       0  4990.9     .05       0
Bank Sta=4970.4,5010.4
XS Rating Curve= 0 ,0
Exp/Cntr=0.3,0.1

Type RM Length L Ch R = 1 ,12847   ,957,957,957
BEGIN DESCRIPTION:
PIGEON ROOST CREEK 21.0
END DESCRIPTION:
XS GIS Cut Line= 3
      3585979.19     10393016.38      3585942.11     10394191.64
      3585986.08     10395167.91
#Sta/Elev= 30
  3843.1  375.56  3878.7  374.56  3898.4   374.3  4048.5  365.05  4118.5  359.18
  4210.5  349.08  4238.6  345.04  4258.6   345.5  4368.6  340.03  4498.7  336.62
  4798.8  332.02  4968.9  333.18  4985.9  329.86  4988.7  329.36  4991.9  329.86
  5008.9  332.53    5059  333.53    5101   336.9  5169.1  341.27  5236.3  347.44
  5269.2  349.47  5319.3  357.22  5369.3  361.37  5409.3  368.06  5467.2   373.6
  5499.4  375.73  5574.5  377.02  5851.1  372.67  5899.8  372.05  5996.2  364.83
#Mann= 9 ,-1 , 0
  3843.1      .1       0  3878.7     .16       0  4210.5      .1       0
  4985.9     .07       0  4991.9      .1       0    5101     .05       0
  5236.3     .16       0  5467.2     .05       0  5851.1     .16       0
Bank Sta=4968.9,5008.9
XS Rating Curve= 0 ,0
Exp/Cntr=0.3,0.1

Type RM Length L Ch R = 1 ,11890   ,899,899,899
BEGIN DESCRIPTION:
PIGEON ROOST CREEK 20.0
END DESCRIPTION:
XS GIS Cut Line= 3
      3585090.31     10392856.62      3585152.81     10394085.79
      3585715.33     10394870.54
#Sta/Elev= 30
  4004.7  386.36  4079.8  386.47  4179.9  393.07    4240  393.41  4340.3  386.33
  4430.3  376.92  4679.6  356.65  4780.7  345.46  4900.9  334.57    4981  330.43
    4998  324.13  5000.8  323.63    5004  324.13    5011   326.5    5031   328.9
  5041.1  329.54  5061.1  327.88  5081.1  331.32  5161.2  333.15  5568.8  339.79
  5670.6  340.27  5776.4  342.12  5877.1   347.8  5942.2  353.57  6033.6  366.36
  6055.2  368.64  6120.3  371.64    6135  369.26  6170.7  370.64    6201  368.94
#Mann= 7 ,-1 , 0
  4004.7     .16       0  4679.6      .1       0    4998     .07       0
    5004      .1       0  5670.6     .05       0  6033.6      .1       0
  6055.2     .16       0
Bank Sta=4981,5031
XS Rating Curve= 0 ,0
Exp/Cntr=0.3,0.1

Type RM Length L Ch R = 1 ,10991   ,973,973,973
BEGIN DESCRIPTION:
PIGEON ROOST CREEK 19.0
END DESCRIPTION:
XS GIS Cut Line= 3
      3583888.93     10393183.03      3584368.08     10394085.79
      3585222.26     10395294.13
#Sta/Elev= 30
  3824.7  393.94  3857.2  393.76  4033.3  393.23  4128.8   387.1  4165.3  387.25
  4219.6  390.25  4311.2  391.78  4329.8   392.1  4373.8   387.9  4445.8  371.82
  4527.7  359.91  4766.8  335.03  4840.5  330.88  4976.4  331.63    5001  321.12
  5003.7  320.62    5007  321.12  5025.3  330.37    5084  328.39  5116.9  329.58
  5327.5  333.85  5345.6  334.45  5508.6  343.86  5556.7  346.61  5743.8  365.33
    5830  371.35  5916.2     372  6023.2  369.37  6174.7  373.23  6326.5  372.63
#Mann= 11 ,-1 , 0
  3824.7     .16       0  3857.2     .05       0  4219.6      .1       0
  4311.2     .16       0  4766.8      .1       0    5001     .07       0
    5007      .1       0  5116.9     .05       0  5327.5      .1       0
  5345.6     .05       0  5508.6     .16       0
Bank Sta=4976.4,5025.3
XS Rating Curve= 0 ,0
Exp/Cntr=0.3,0.1

Type RM Length L Ch R = 1 ,10018   ,595,595,595
BEGIN DESCRIPTION:
PIGEON ROOST CREEK 17.0
END DESCRIPTION:
XS GIS Cut Line= 3
       3583430.6     10394231.65      3583677.68     10394643.99
       3585068.3     10395321.33
#Sta/Elev= 30
  4285.4  375.25  4607.7  351.99  4871.1  330.06  4909.6  328.21  4971.2  328.99
  4977.2   327.7  4982.8  326.51  4996.8  317.22  4999.5  316.72  5002.8  317.22
  5022.3  327.23    5038  327.42  5050.4  325.12  5060.2  326.55  5275.8  329.74
  5388.5  339.41  5433.6  341.17  5551.9  338.15  5629.4  338.77  5687.1  338.78
  5726.7  343.25  5808.2  346.47  5912.6  352.42  6030.8  356.95  6070.4  360.02
  6092.9  360.92    6121  359.45  6160.5  364.08  6233.7  363.29  6312.9  365.46
#Mann= 6 ,-1 , 0
  4285.4     .16       0  4996.8     .07       0  5002.8     .16       0
  5060.2     .05       0  5629.4      .1       0  5808.2     .16       0
Bank Sta=4977.2,5022.3
XS Rating Curve= 0 ,0
Exp/Cntr=0.3,0.1