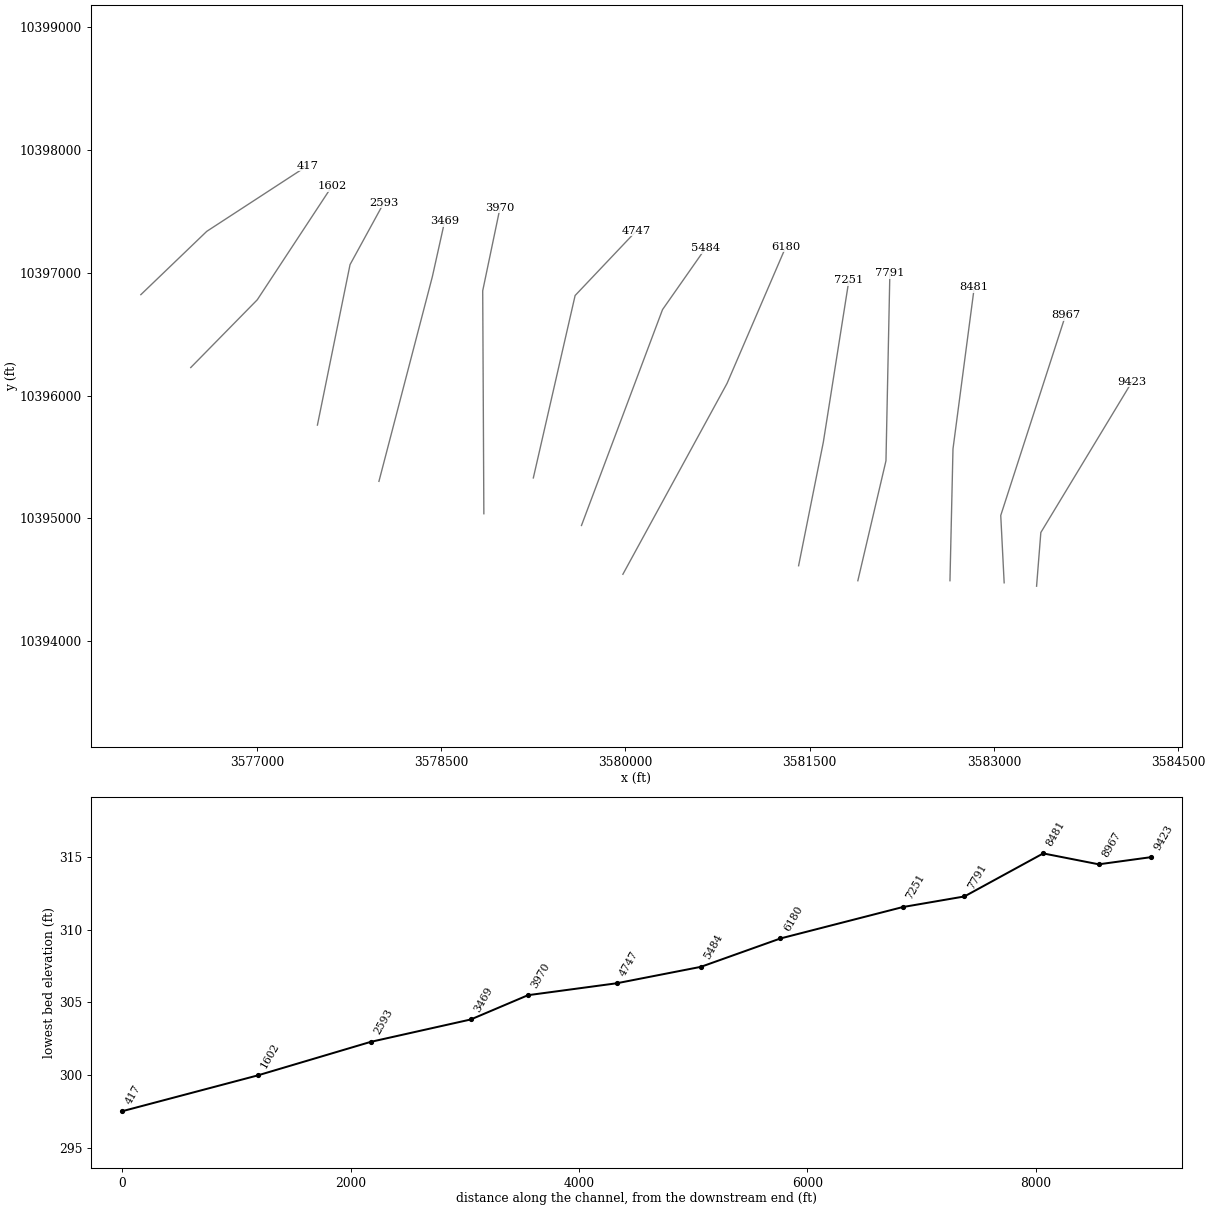
HEC-RAS study PIGEON ROOST CREEK.prj: PIGEON ROOST CREEK Base Level Engineering

--- PIGEON ROOST CREEK.g01 (geometry) --- (continued)

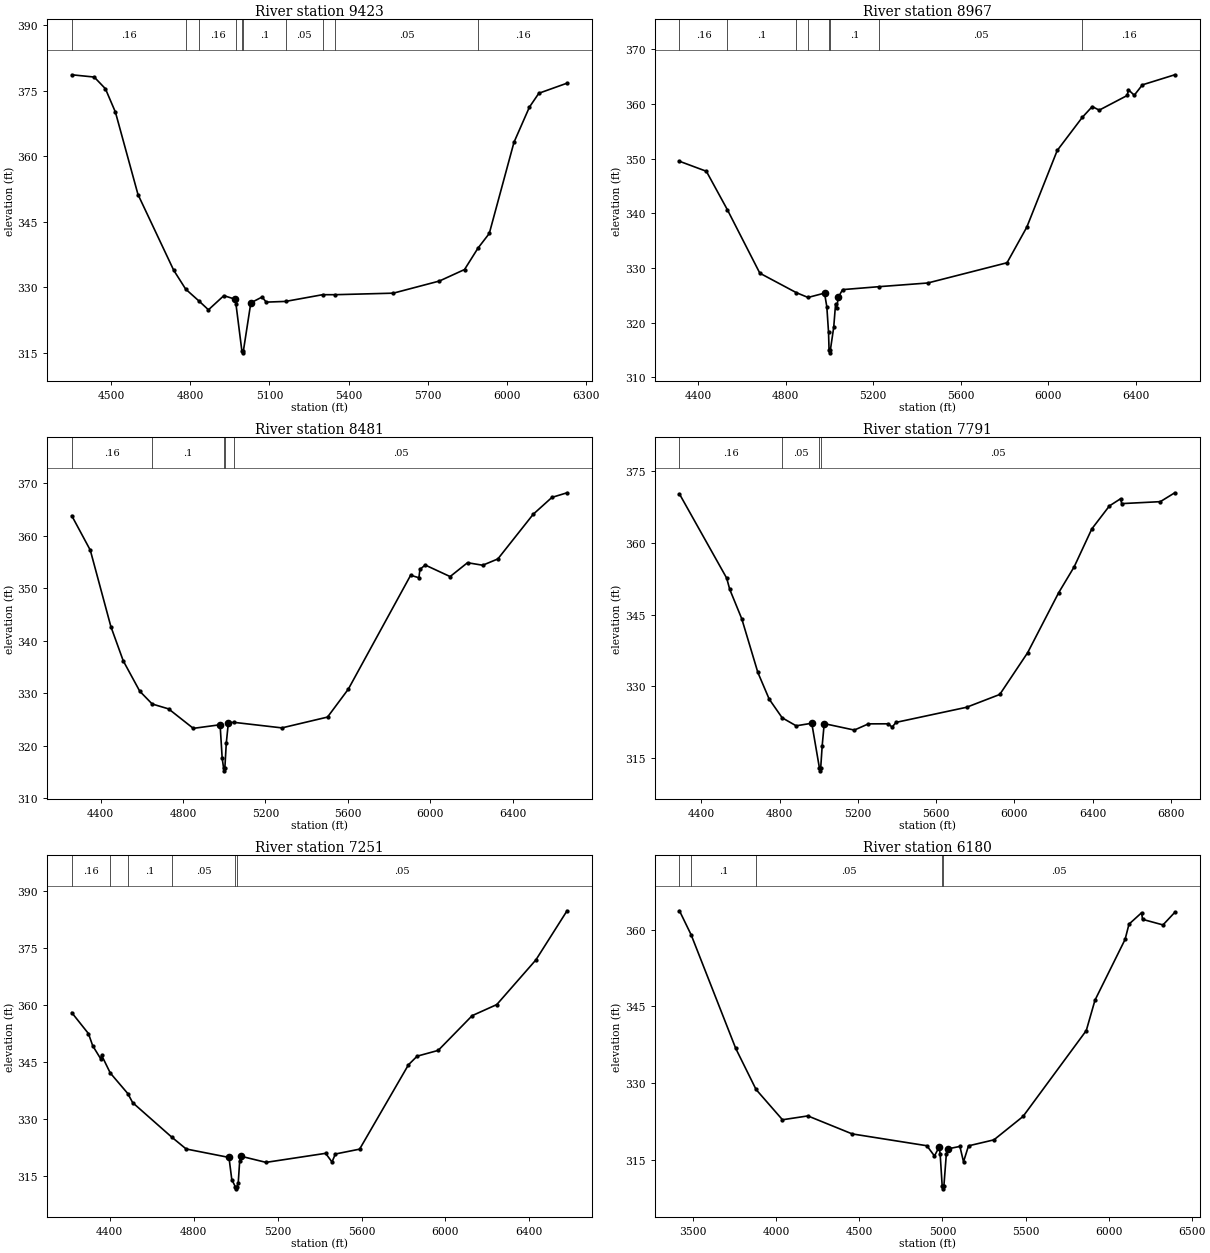
Type RM Length L Ch R = 1 ,9423    ,456,456,456
BEGIN DESCRIPTION:
PIGEON ROOST CREEK 16.0
END DESCRIPTION:
XS GIS Cut Line= 3
      3583347.25     10394446.86      3583381.97      10394884.4
      3584125.02     10396113.55
#Sta/Elev= 30
  4351.4  378.64  4436.4  378.12  4478.8  375.45  4516.7   370.1  4602.2  351.23
  4737.4   333.9  4782.8  329.57    4835  326.75  4868.9  324.84  4927.3  328.08
  4971.2  327.24  4973.2  326.13  4995.4  315.49  4998.2  314.99  5001.4  315.49
  5029.4  326.44  5072.1  327.77  5087.6   326.6  5160.9  326.76  5301.3   328.3
  5349.4   328.3  5568.8  328.65  5743.4  331.43  5838.5  334.06  5889.3  338.95
  5932.2  342.32  6025.7  363.19  6084.2  371.25  6119.9  374.41  6226.6  376.72
#Mann= 10 ,-1 , 0
  4351.4     .16       0  4782.8      .1       0    4835     .16       0
  4973.2      .1       0  4995.4     .07       0  5001.4      .1       0
  5160.9     .05       0  5301.3      .1       0  5349.4     .05       0
  5889.3     .16       0
Bank Sta=4971.2,5029.4
XS Rating Curve= 0 ,0
Exp/Cntr=0.3,0.1

Type RM Length L Ch R = 1 ,8967    ,486,486,486
BEGIN DESCRIPTION:
PIGEON ROOST CREEK 15.0
END DESCRIPTION:
XS GIS Cut Line= 3
      3583083.36     10394474.64      3583055.58     10395023.29
      3583583.36     10396655.22
#Sta/Elev= 30
  4313.9   349.5  4436.9  347.67  4533.4  340.61  4681.4  329.05  4848.5  325.49
  4901.7  324.62  4977.1  325.41  4987.6  322.93  4995.5  318.23  4997.8     315
  5000.5   314.5  5003.8     315  5019.2  319.19  5027.6  323.43  5032.8  322.71
  5040.2  324.66  5059.6  326.05  5227.1  326.59    5449  327.26  5811.6  330.96
    5902  337.47    6041  351.47  6155.8  357.53  6201.1  359.49  6233.1  358.84
  6361.1  361.52  6366.4  362.57  6393.2  361.56  6430.4  363.46  6578.4   365.3
#Mann= 8 ,-1 , 0
  4313.9     .16       0  4533.4      .1       0  4848.5     .16       0
  4901.7      .1       0  4997.8     .07       0  5003.8      .1       0
  5227.1     .05       0  6155.8     .16       0
Bank Sta=4977.1,5040.2
XS Rating Curve= 0 ,0
Exp/Cntr=0.3,0.1

Type RM Length L Ch R = 1 ,8481    ,690,690,690
BEGIN DESCRIPTION:
PIGEON ROOST CREEK 14.0
END DESCRIPTION:
XS GIS Cut Line= 3
      3582642.11     10394491.66       3582666.7     10395564.96
      3582840.31     10396884.41
#Sta/Elev= 30
  4259.6  363.85  4349.6  357.28  4449.6  342.72  4509.6   336.2  4589.7  330.42
  4650.1  327.98  4729.7  327.05  4849.7  323.34  4979.8  324.03  4989.8  317.69
  4996.8  315.75  4999.5  315.25  5002.8  315.75  5009.8  320.52  5019.8  324.39
  5046.2  324.49  5279.8  323.43  5501.3  325.49  5602.2  330.81  5904.7   352.5
  5944.8  352.03  5949.9  353.62  5975.4  354.45  6096.4  352.25  6180.8  354.89
  6254.5  354.41  6328.1  355.61  6499.8  364.12  6590.6  367.33    6664  368.21
#Mann= 5 ,-1 , 0
  4259.6     .16       0  4650.1      .1       0  4996.8     .07       0
  5002.8      .1       0  5046.2     .05       0
Bank Sta=4979.8,5019.8
XS Rating Curve= 0 ,0
Exp/Cntr=0.3,0.1

Type RM Length L Ch R = 1 ,7791    ,540,540,540
BEGIN DESCRIPTION:
PIGEON ROOST CREEK 13.0
END DESCRIPTION:
XS GIS Cut Line= 3
       3581892.1      10394491.6      3582121.03     10395468.37
      3582152.81      10396995.5
#Sta/Elev= 30
  4288.5  370.28  4529.7  352.66  4545.3  350.31  4606.9  344.13  4689.1  332.89
  4747.1   327.3  4813.3   323.4  4884.8  321.72  4964.5  322.26    5004  312.79
  5006.8  312.29    5010  312.79  5017.8  317.58  5028.1  322.18  5181.9  320.83
    5254  322.13    5355  322.14    5375  321.45    5395  322.44  5755.1   325.6
  5925.1  328.29  6067.4  337.03  6225.2  349.54  6305.2  355.02  6395.3  362.96
  6485.3  367.78  6542.8  369.29  6547.8  368.26  6745.3  368.67  6819.2  370.53
#Mann= 4 ,-1 , 0
  4288.5     .16       0  4813.3     .05       0    5004     .03       0
    5010     .05       0
Bank Sta=4964.5,5028.1
XS Rating Curve= 0 ,0
Exp/Cntr=0.3,0.1

Type RM Length L Ch R = 1 ,7251    ,1071,1071,1071
BEGIN DESCRIPTION:
PIGEON ROOST CREEK 12.0
END DESCRIPTION:
XS GIS Cut Line= 3
      3581409.75     10394613.59      3581611.14     10395620.51
      3581819.21     10396938.32
#Sta/Elev= 30
  4218.8  357.91  4298.4  352.39  4318.8  349.18  4356.4   345.8  4361.5  346.65
  4402.5  342.02  4486.1  336.61  4509.3  334.22  4695.2  325.17  4764.3  322.04
  4968.3  319.82  4981.7     314  4999.1  312.06  5001.8  311.56  5005.1  312.06
  5012.3  313.01  5019.2   318.8  5024.3  320.15  5144.8  318.52    5429   320.9
  5459.4  318.61  5475.4  320.72    5591     322  5823.9  344.19  5865.2  346.45
  5965.6  347.97  6127.6  357.11  6244.8  360.02  6431.3  371.77  6579.8  384.69
#Mann= 6 ,-1 , 0
  4218.8     .16       0  4402.5     .05       0  4486.1      .1       0
  4695.2     .05       0  4999.1     .03       0  5005.1     .05       0
Bank Sta=4968.3,5024.3
XS Rating Curve= 0 ,0
Exp/Cntr=0.3,0.1

Type RM Length L Ch R = 1 ,6180    ,696,696,696
BEGIN DESCRIPTION:
PIGEON ROOST CREEK 10.0
END DESCRIPTION:
XS GIS Cut Line= 3
       3579979.2     10394544.13      3580827.28     10396099.08
      3581305.57     10397210.76
#Sta/Elev= 30
    3417  363.66  3487.6  358.95  3755.9  336.79    3878  328.79  4037.1  322.88
  4189.9  323.63  4456.6  320.12  4906.3  317.81  4951.9  315.81  4979.7  317.54
  4986.1  316.26  4998.5   309.9  5001.3   309.4  5004.5   309.9  5008.9  310.05
  5023.3  316.15  5031.6  317.19    5105  317.68  5126.8  314.68  5156.9  317.79
  5309.8  318.96  5484.9  323.52  5865.7  340.28  5918.2  346.22  6099.3  358.07
  6122.9  361.05  6198.9  363.28  6204.4  361.99  6327.5   360.9  6398.4  363.35
#Mann= 5 ,-1 , 0
    3417     .16       0  3487.6      .1       0    3878     .05       0
  4998.5     .03       0  5004.5     .05       0
Bank Sta=4979.7,5031.6
XS Rating Curve= 0 ,0
Exp/Cntr=0.3,0.1

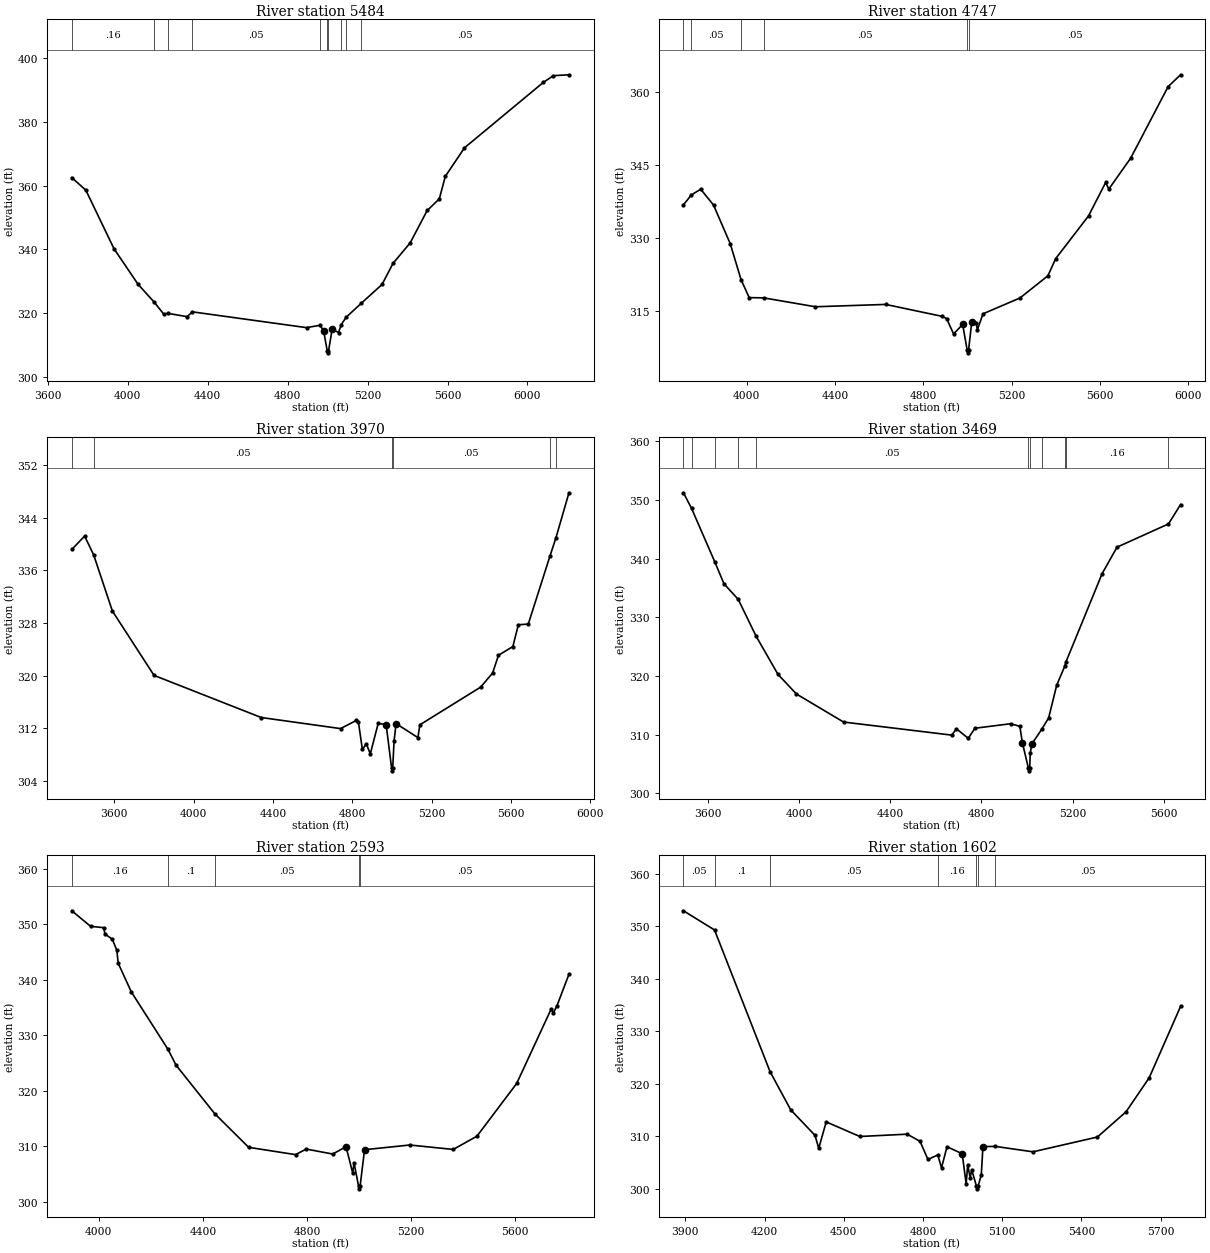
Type RM Length L Ch R = 1 ,5484    ,737,737,737
BEGIN DESCRIPTION:
PIGEON ROOST CREEK 8.0
END DESCRIPTION:
XS GIS Cut Line= 3
       3579642.1     10394941.63      3580301.83     10396699.98
      3580651.85     10397200.01
#Sta/Elev= 30
  3719.5  362.51  3789.8  358.56  3930.4  340.18  4051.4  328.95  4132.5  323.33
  4178.8  319.66  4201.7  319.84  4296.3  318.82  4323.1  320.33  4894.4  315.37
  4961.6  316.11  4979.8   314.4  4998.2  307.95  5000.9  307.45  5004.2  307.95
  5022.6  314.88  5054.6  313.84    5068   316.3  5092.6  318.64  5168.1  323.01
  5272.3  328.94  5327.4  335.59  5412.8  341.98  5498.3  352.19  5558.8  355.81
    5589  362.92    5685  371.89  6079.6  392.45  6130.2  394.56  6207.9  394.84
#Mann= 10 ,-1 , 0
  3719.5     .16       0  4132.5      .1       0  4201.7     .16       0
  4323.1     .05       0  4961.6     .16       0  4998.2     .07       0
  5004.2     .16       0    5068     .05       0  5092.6     .16       0
  5168.1     .05       0
Bank Sta=4979.8,5022.6
XS Rating Curve= 0 ,0
Exp/Cntr=0.3,0.1

Type RM Length L Ch R = 1 ,4747    ,777,777,777
BEGIN DESCRIPTION:
PIGEON ROOST CREEK 7.0
END DESCRIPTION:
XS GIS Cut Line= 3
      3579250.03     10395328.87      3579590.31     10396814.96
      3580090.34     10397342.76
#Sta/Elev= 30
  3712.8  336.76  3748.6   338.8  3790.9  339.98    3849  336.73  3924.8  328.77
    3974  321.34  4010.7  317.68  4075.6  317.63  4310.7   315.8  4628.7  316.28
  4885.1  313.82    4905  313.35  4936.4   310.2  4977.5  312.16  4998.1  306.82
  5000.8  306.32  5004.1  306.82  5018.5  312.64  5038.8  312.42    5044  311.07
  5069.8  314.35  5237.3  317.61  5363.6  322.17  5398.8   325.7  5547.6  334.49
  5625.3  341.37  5639.5  340.01  5738.6  346.38  5908.1  361.08  5964.4  363.52
#Mann= 6 ,-1 , 0
  3712.8     .16       0  3748.6     .05       0    3974     .08       0
  4075.6     .05       0  4998.1    .035       0  5004.1     .05       0
Bank Sta=4977.5,5018.5
XS Rating Curve= 0 ,0
Exp/Cntr=0.3,0.1

Type RM Length L Ch R = 1 ,3970    ,501,501,501
BEGIN DESCRIPTION:
PIGEON ROOST CREEK 6.0
END DESCRIPTION:
XS GIS Cut Line= 3
      3578847.25     10395037.23      3578837.93     10396853.63
      3578978.82     10397528.45
#Sta/Elev= 30
  3386.5   339.2  3450.9  341.24  3496.5  338.38  3590.9  329.83  3800.9  320.03
  4340.9  313.62  4740.9  311.93  4820.9  313.18  4830.9  312.96  4850.9  308.77
  4870.9  309.61  4890.9  308.08  4930.9  312.74  4970.9  312.53  4997.9     306
  5000.7   305.5  5003.9     306  5010.9  310.08  5020.9  312.69  5130.9  310.56
  5140.9  312.51  5447.4  318.25  5507.4  320.39  5537.1   323.1  5609.5  324.42
  5637.2  327.74  5687.2  327.84  5796.7  338.21  5826.7  340.98  5892.3  347.83
#Mann= 6 ,-1 , 0
  3386.5     .08       0  3496.5     .05       0  4997.9    .035       0
  5003.9     .05       0  5796.7     .16       0  5826.7     .05       0
Bank Sta=4970.9,5020.9
XS Rating Curve= 0 ,0
Exp/Cntr=0.3,0.1

Type RM Length L Ch R = 1 ,3469    ,876,876,876
BEGIN DESCRIPTION:
PIGEON ROOST CREEK 5.0
END DESCRIPTION:
XS GIS Cut Line= 3
      3577993.09     10395301.08      3578428.22     10396969.42
      3578527.91     10397418.03
#Sta/Elev= 30
  3490.9  351.23  3526.7  348.56  3629.2   339.4  3668.8  335.73  3731.7  333.05
  3810.2  326.77  3906.5  320.26  3987.5  316.92  4194.2  312.15  4669.6  309.92
  4690.3  310.99    4742  309.37  4771.3  311.09    4928  311.86  4968.5  311.42
  4979.6  308.66    5006  304.33  5008.8  303.83    5012  304.33  5014.2  306.81
    5021  308.38  5064.3  310.89  5095.1  312.84  5130.4  318.41  5166.8  321.75
    5171  322.38    5330  337.44  5395.5  341.96  5621.5  345.92  5674.6  349.22
#Mann= 11 ,-1 , 0
  3490.9     .16       0  3526.7      .1       0  3629.2     .05       0
  3731.7      .1       0  3810.2     .05       0    5006     .03       0
    5012     .05       0  5064.3     .16       0  5166.8     .05       0
    5171     .16       0  5621.5     .05       0
Bank Sta=4979.6,5021
XS Rating Curve= 0 ,0
Exp/Cntr=0.3,0.1

Type RM Length L Ch R = 1 ,2593    ,991,991,991
BEGIN DESCRIPTION:
PIGEON ROOST CREEK 4.0
END DESCRIPTION:
XS GIS Cut Line= 3
      3577492.22      10395759.4      3577757.84     10397066.69
      3578033.88     10397571.89
#Sta/Elev= 30
  3896.5  352.47  3968.2  349.67  4018.8  349.42  4023.9  348.27  4051.9  347.34
  4069.4  345.32  4074.5  343.01  4125.2  337.81  4265.3  327.51  4296.8  324.61
  4444.9  315.88  4575.7  309.78    4756  308.46  4796.8  309.47  4898.8  308.57
  4949.8   309.9  4975.5  305.14  4980.6     307  4997.9  302.79  5000.6  302.29
  5003.9  302.79    5021  309.35  5194.7   310.2  5361.5   309.4  5452.7  311.79
  5605.4  321.31  5737.5   334.7  5746.8  334.07  5760.3  335.35  5806.2  341.02
#Mann= 5 ,-1 , 0
  3896.5     .16       0  4265.3      .1       0  4444.9     .05       0
  4997.9     .03       0  5003.9     .05       0
Bank Sta=4949.8,5021
XS Rating Curve= 0 ,0
Exp/Cntr=0.3,0.1

Type RM Length L Ch R = 1 ,1602    ,1185,1185,1185
BEGIN DESCRIPTION:
PIGEON ROOST CREEK 3.0
END DESCRIPTION:
XS GIS Cut Line= 3
      3576460.99     10396228.18      3577002.63     10396780.23
      3577611.78     10397706.97
#Sta/Elev= 30
  3892.8  352.94  4010.5  349.29  4220.6  322.32  4299.1  315.02    4391  310.17
  4405.1  307.69  4433.4  312.73  4560.7  309.95  4739.7  310.39  4788.6  309.04
  4818.7  305.57  4855.8  306.43    4870     304    4891     308  4948.3  306.67
  4963.3  300.96  4969.3  304.56  4978.4  302.08  4984.4  303.59  5002.5  300.48
  5005.2  299.98  5008.5  300.48  5020.6  302.62  5026.9  308.03  5074.3  308.06
  5216.4  307.03  5460.4  309.85  5568.9  314.66  5656.3  321.12  5775.2  334.72
#Mann= 7 ,-1 , 0
  3892.8     .05       0  4010.5      .1       0  4220.6     .05       0
  4855.8     .16       0  5002.5     .07       0  5008.5     .16       0
  5074.3     .05       0
Bank Sta=4948.3,5026.9
XS Rating Curve= 0 ,0
Exp/Cntr=0.3,0.1

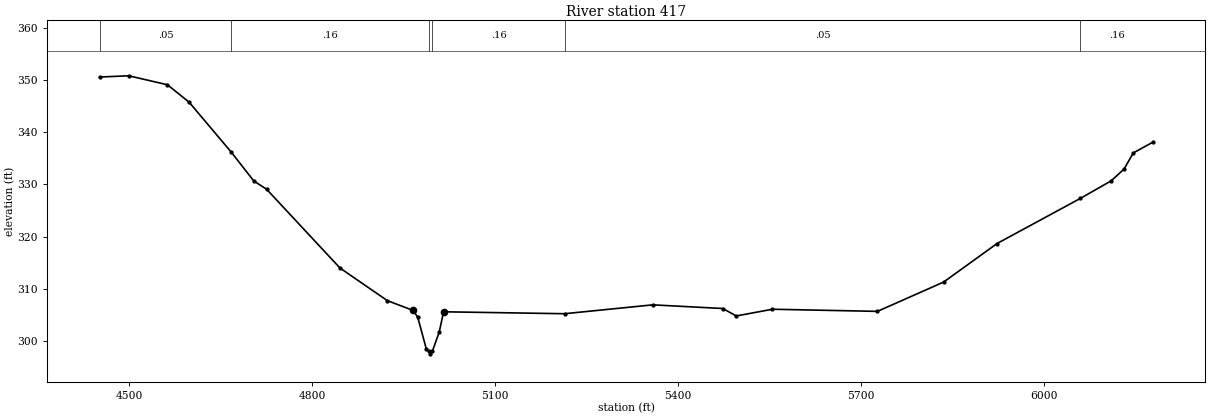
Type RM Length L Ch R = 1 ,417     ,0,0,0
BEGIN DESCRIPTION:
PIGEON ROOST CREEK 1.0
END DESCRIPTION:
XS GIS Cut Line= 3
      3576054.69     10396821.88      3576591.17     10397337.52
      3577414.05     10397873.96
#Sta/Elev= 30
    4452  350.58  4499.6  350.82  4563.1   349.1  4598.6  345.77    4668  336.15
  4704.6  330.67  4725.8  329.06  4846.1  313.96  4923.8  307.71  4966.2  305.83
  4973.5  304.52  4987.6  298.43  4991.5  298.02  4994.3  297.52  4997.5  298.02
  5008.7  301.71  5015.9  305.58  5214.1  305.21  5358.8  306.91  5473.5  306.21
  5495.7  304.78    5555  306.07    5727  305.66  5835.6  311.28  5923.2  318.67
  6059.5   327.3  6110.2  330.68  6131.3  332.93  6146.5  336.03  6178.4  338.08
#Mann= 6 ,-1 , 0
    4452     .05       0    4668     .16       0  4991.5     .07       0
  4997.5     .16       0  5214.1     .05       0  6059.5     .16       0
Bank Sta=4966.2,5015.9
XS Rating Curve= 0 ,0
Exp/Cntr=0.3,0.1

Chan Stop Cuts=-1
Use User Specified Reach Order=0
Composite Channel Slope=5