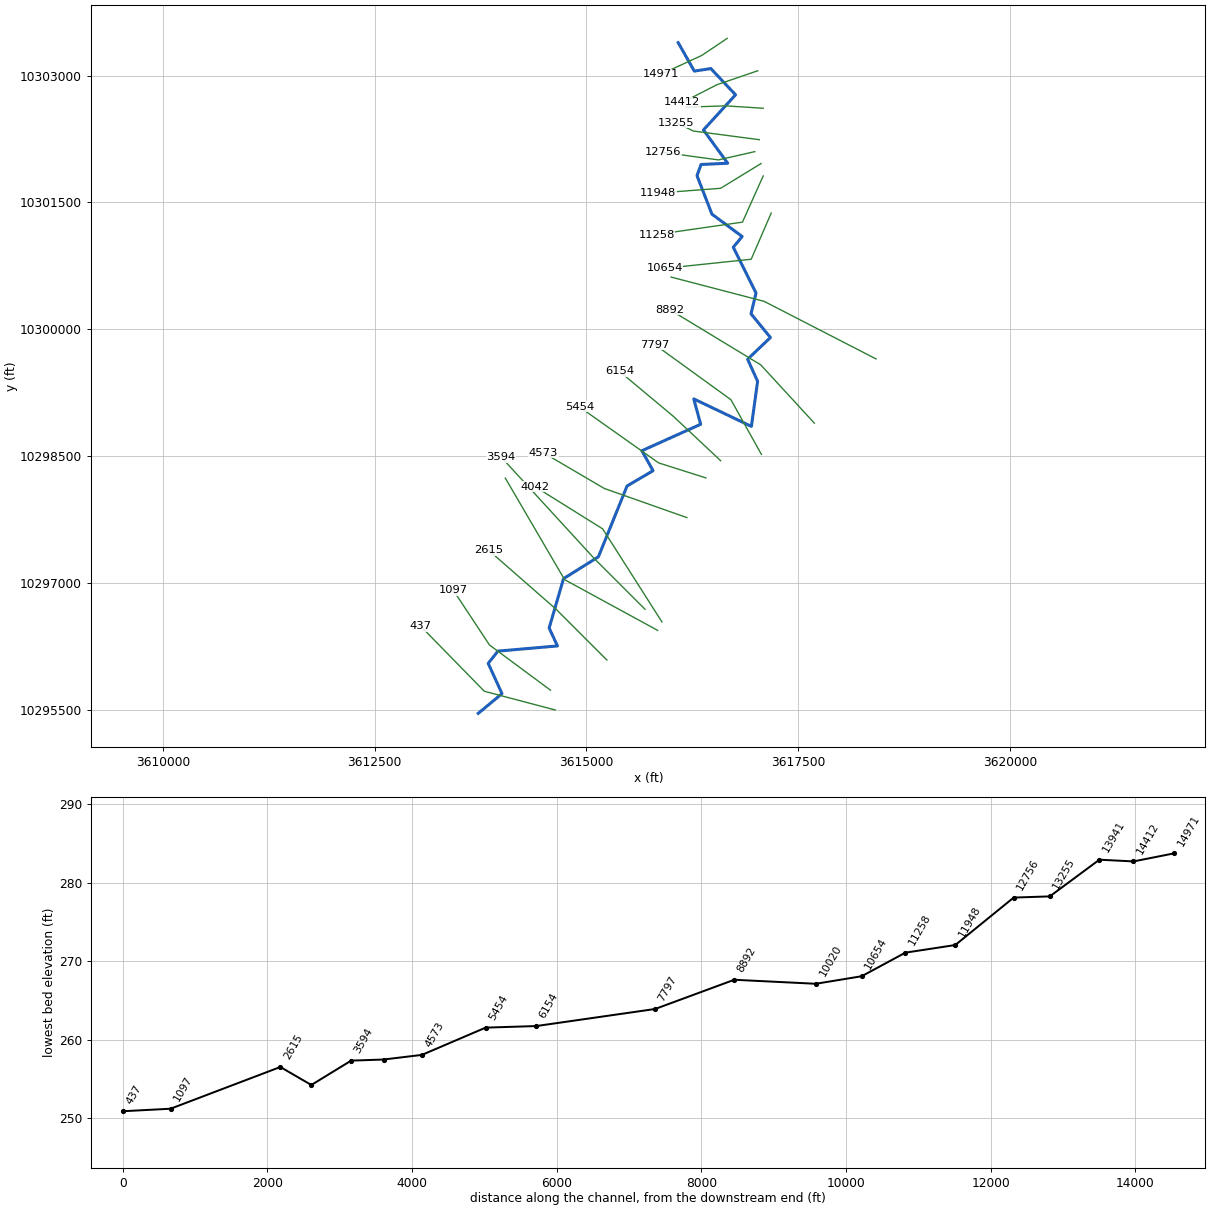
--- RAYLEIGH BRANCH.prj (project) ---

Proj Title=RAYLEIGH BRANCH Base Level Engineering
Current Plan=p01
Default Exp/Contr=0.3,0.1
English Units
Geom File=g01
Flow File=f01
Plan File=p01
Y Axis Title=Elevation
X Axis Title(PF)=Main Channel Distance
X Axis Title(XS)=Station
BEGIN DESCRIPTION:
RAYLEIGH BRANCH
END DESCRIPTION:
DSS Export Rating Curves= 0
DSS Export Rating Curve Sorted= 0
DSS Export Volume Flow Curves= 0
DXF OffsetX= 0
DXF OffsetY= 0
DXF ScaleX= 1
DXF ScaleY= 10

--- RAYLEIGH BRANCH.p01 (plan) ---

Plan Title=Multiple Run
Short Identifier=Multiple
Geom File=g01
Flow File=f01
Subcritical Flow
K Sum by GR= 0
Std Step Tol= 0.01
Critical Tol= 0.01
Num of Std Step Trials= 20
Max Error Tol= 0.3
Flow Tol Ratio= 0.001
Split Flow NTrial= 30
Split Flow Tol= 0.02
Split Flow Ratio= 0.02
Log Output Level= 0
Friction Slope Method= 1
Unsteady Friction Slope Method= 2
Unsteady Bridges Friction Slope Method= 1
Parabolic Critical Depth
Global Vel Dist=  1 , 1 , 1
Global Log Level= 0
CheckData=True
Encroach Param= -1, 0, 0, 0
BEGIN DESCRIPTION:
Multiple Run
END DESCRIPTION:

--- RAYLEIGH BRANCH.f01 (steady flow) ---

Flow Title=Multiple
Program Version=4.10
Number of Profiles= 7
Profile Names=10-year,25-year,50-year,1pct_min,100-year,1pct_plu,500-year
River Rch & RM=RAYLEIGH BRANCH,Reach-1         ,14971
     617     826     996     879    1189    1608    1697
River Rch & RM=RAYLEIGH BRANCH,Reach-1         ,10020
    1691    2363    2928    2648    3581    4842    5369
River Rch & RM=RAYLEIGH BRANCH,Reach-1         ,8892
    1691    2363    2928    2648    3581    4842    5369
Boundary for River Rch & Prof#=RAYLEIGH BRANCH,Reach-1         , 1
Up Type= 0
Dn Type= 3
Dn Slope=0.005
Boundary for River Rch & Prof#=RAYLEIGH BRANCH,Reach-1         , 2
Up Type= 0
Dn Type= 3
Dn Slope=0.005
Boundary for River Rch & Prof#=RAYLEIGH BRANCH,Reach-1         , 3
Up Type= 0
Dn Type= 3
Dn Slope=0.005
Boundary for River Rch & Prof#=RAYLEIGH BRANCH,Reach-1         , 4
Up Type= 0
Dn Type= 3
Dn Slope=0.005
Boundary for River Rch & Prof#=RAYLEIGH BRANCH,Reach-1         , 5
Up Type= 0
Dn Type= 3
Dn Slope=0.005
Boundary for River Rch & Prof#=RAYLEIGH BRANCH,Reach-1         , 6
Up Type= 0
Dn Type= 3
Dn Slope=0.005
Boundary for River Rch & Prof#=RAYLEIGH BRANCH,Reach-1         , 7
Up Type= 0
Dn Type= 3
Dn Slope=0.005
DSS Import GetInterval= 0
DSS Import GetPeak= 0
DSS Import FillOption= 0

--- RAYLEIGH BRANCH.g01 (geometry) ---

Geom Title=Existing Conditions
Program Version=4.10

River Reach=RAYLEIGH BRANCH ,Reach-1
Reach XY= 30
      3616083.91     10303388.64      3616274.37      10303052.5
      3616469.68     10303082.02      3616761.61     10302772.12
      3616382.38     10302356.59      3616668.82     10301963.31
      3616353.37     10301948.43      3616306.25     10301816.58
       3616482.6     10301361.68      3616839.64     10301097.33
       3616734.6     10300970.16      3617003.27     10300429.36
      3616944.06     10300183.52      3617173.28     10299903.33
      3616904.07     10299646.44      3617021.97     10299386.01
      3616948.66      10298852.8      3616267.64     10299178.01
      3616349.64     10298877.87      3615655.05     10298565.07
      3615787.14     10298329.29      3615479.89     10298147.98
      3615141.65      10297311.5      3614729.56     10297053.08
      3614559.77     10296469.75      3614658.21     10296257.77
      3613955.08     10296196.83      3613839.98     10296052.04
      3614002.82     10295694.23      3613722.68     10295460.95

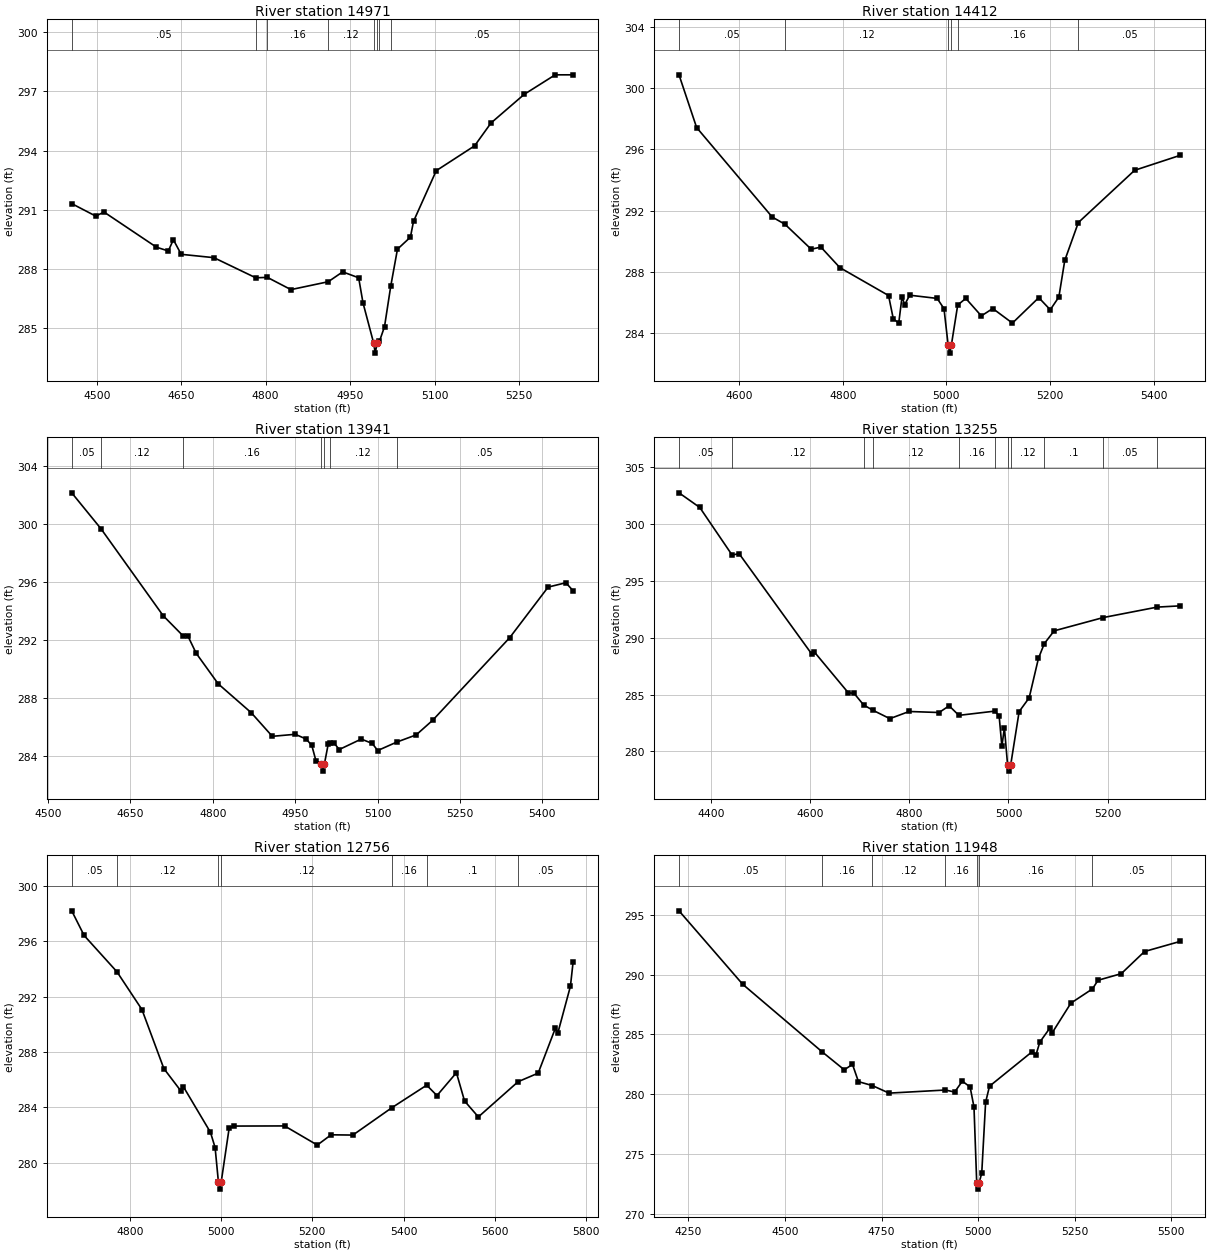
Type RM Length L Ch R = 1 ,14971   ,559,559,559
BEGIN DESCRIPTION:
RAYLEIGH BRANCH 24.0
END DESCRIPTION:
XS GIS Cut Line= 3
      3616663.52     10303439.59      3616361.41     10303236.76
      3615883.24     10303016.36
#Sta/Elev= 30
  4455.6  291.31  4498.1  290.68  4513.1  290.88  4606.1   289.1  4627.1  288.91
  4636.1  289.48    4650  288.74  4708.1  288.57  4782.4  287.55  4803.1  287.57
  4844.9  286.95  4911.2  287.35  4936.8  287.85  4965.2  287.55  4972.9  286.28
  4991.9  284.23  4994.6  283.73  4997.9  284.23    5002  284.32  5011.1  285.07
  5022.2  287.13  5034.1     289  5057.1  289.61  5062.6  290.41    5103  292.98
  5171.1  294.24  5200.3   295.4  5259.2  296.85  5314.2  297.84    5346  297.84
#Mann= 8 ,-1 , 0
  4455.6     .05       0  4782.4     .12       0  4803.1     .16       0
  4911.2     .12       0  4991.9     .07       0  4997.9     .12       0
    5002     .16       0  5022.2     .05       0
Bank Sta=4991.9,4997.9
XS Rating Curve= 0 ,0
Exp/Cntr=0.3,0.1

Type RM Length L Ch R = 1 ,14412   ,471,471,471
BEGIN DESCRIPTION:
RAYLEIGH BRANCH 23.0
END DESCRIPTION:
XS GIS Cut Line= 3
      3617023.67     10303056.14      3616542.11     10302891.64
      3616133.53     10302682.03
#Sta/Elev= 30
  4483.7  300.87  4517.7  297.43  4663.7  291.59  4688.3  291.12    4739  289.49
  4757.7  289.63  4794.3  288.29  4888.3  286.47  4897.5  284.95    4908  284.67
  4914.3  286.37  4919.6  285.88  4929.2  286.49  4982.2  286.28  4995.4  285.61
  5003.5  283.21  5006.2  282.71  5009.5  283.21  5021.9  285.85  5037.5  286.28
  5067.5  285.14  5089.6  285.62  5127.5  284.67  5178.4  286.33  5200.6  285.54
  5217.2  286.37  5228.6  288.76  5254.8  291.23  5363.5  294.64  5451.8  295.62
#Mann= 6 ,-1 , 0
  4483.7     .05       0  4688.3     .12       0  5003.5     .07       0
  5009.5     .12       0  5021.9     .16       0  5254.8     .05       0
Bank Sta=5003.5,5009.5
XS Rating Curve= 0 ,0
Exp/Cntr=0.3,0.1

Type RM Length L Ch R = 1 ,13941   ,686,686,686
BEGIN DESCRIPTION:
RAYLEIGH BRANCH 22.0
END DESCRIPTION:
XS GIS Cut Line= 3
      3617088.19      10302613.2      3616642.11     10302641.64
      3616176.75     10302626.12
#Sta/Elev= 30
  4543.3  302.12  4596.6  299.64  4709.7  293.65  4745.9  292.26  4754.7  292.25
  4769.8  291.06  4809.9  288.95    4870  286.96  4908.4  285.33  4950.2  285.47
  4970.2  285.14  4980.3   284.7  4987.8  283.65  4997.3  283.43    5000  282.93
  5003.3  283.43  5010.3  284.82  5013.5  284.84  5020.3  284.89  5030.3  284.42
  5070.3  285.14  5090.3  284.84  5100.3  284.35  5134.8  284.93  5170.4  285.43
  5200.4  286.44  5340.5  292.13  5410.5  295.62  5442.8  295.92  5455.9  295.37
#Mann= 7 ,-1 , 0
  4543.3     .05       0  4596.6     .12       0  4745.9     .16       0
  4997.3     .07       0  5003.3     .16       0  5013.5     .12       0
  5134.8     .05       0
Bank Sta=4997.3,5003.3
XS Rating Curve= 0 ,0
Exp/Cntr=0.3,0.1

Type RM Length L Ch R = 1 ,13255   ,499,499,499
BEGIN DESCRIPTION:
RAYLEIGH BRANCH 21.0
END DESCRIPTION:
XS GIS Cut Line= 3
      3617042.13     10302241.64      3616261.49     10302344.34
      3616061.46     10302444.35
#Sta/Elev= 30
  4335.6  302.76  4377.5  301.47  4442.7  297.28  4456.7  297.41  4603.4  288.56
  4608.5  288.75  4677.1  285.15  4688.6  285.11  4707.8  284.09  4726.1  283.63
  4760.8  282.88  4799.6  283.51  4860.1  283.42  4880.3  284.01    4900  283.17
    4972  283.54  4981.1  283.15  4986.7  280.45  4991.8  282.08  4998.3  278.76
  5001.1  278.26  5004.3  278.76  5021.5   283.5  5041.7  284.71  5060.4  288.18
  5072.2  289.48  5092.1  290.61  5191.2  291.78  5299.9   292.7  5346.6  292.81
#Mann= 11 ,-1 , 0
  4335.6     .05       0  4442.7     .12       0  4707.8     .16       0
  4726.1     .12       0    4900     .16       0    4972     .12       0
  4998.3     .07       0  5004.3     .12       0  5072.2      .1       0
  5191.2     .05       0  5299.9     .16       0
Bank Sta=4998.3,5004.3
XS Rating Curve= 0 ,0
Exp/Cntr=0.3,0.1

Type RM Length L Ch R = 1 ,12756   ,808,808,808
BEGIN DESCRIPTION:
RAYLEIGH BRANCH 20.0
END DESCRIPTION:
XS GIS Cut Line= 3
      3616988.66     10302100.53      3616559.23     10302002.56
      3615906.33     10302091.54
#Sta/Elev= 30
  4672.3  298.19  4699.5  296.41  4771.5  293.79  4826.2  291.07  4874.3  286.81
  4912.2  285.17  4917.3  285.49  4976.5  282.21  4986.7  281.11    4994  278.61
  4996.7  278.11    5000  278.61  5017.5  282.51  5027.8  282.66  5139.1  282.67
  5210.8  281.29  5241.1  282.03  5288.8  282.01  5374.1  283.98  5450.7  285.61
  5473.2  284.86  5515.9  286.51  5533.7  284.47    5564  283.32  5651.1  285.86
  5695.2  286.48    5733  289.73    5738  289.34  5765.9  292.75  5771.7  294.48
#Mann= 7 ,-1 , 0
  4672.3     .05       0  4771.5     .12       0    4994     .07       0
    5000     .12       0  5374.1     .16       0  5450.7      .1       0
  5651.1     .05       0
Bank Sta=4994,5000
XS Rating Curve= 0 ,0
Exp/Cntr=0.3,0.1

Type RM Length L Ch R = 1 ,11948   ,690,690,690
BEGIN DESCRIPTION:
RAYLEIGH BRANCH 19.0
END DESCRIPTION:
XS GIS Cut Line= 3
       3617062.4     10301959.57      3616585.03     10301667.13
      3615849.68     10301611.23
#Sta/Elev= 30
    4226  295.32  4390.6  289.19    4596  283.55  4653.6  282.04  4674.9  282.49
  4690.3  281.05  4726.4  280.72  4769.6  280.09  4915.5  280.35  4939.2  280.18
  4959.2  281.09  4979.3   280.6  4989.3  278.93  4996.4  272.57  4999.1  272.07
  5002.4  272.57  5009.4  273.42  5019.4  279.33  5029.5  280.67  5139.8  283.55
  5149.8   283.3  5159.8  284.36  5186.5  285.56  5191.5  285.12  5240.1  287.61
  5295.9   288.8  5310.3  289.52  5370.4  290.07  5430.6  291.92  5523.3  292.77
#Mann= 7 ,-1 , 0
    4226     .05       0    4596     .16       0  4726.4     .12       0
  4915.5     .16       0  4996.4     .07       0  5002.4     .16       0
  5295.9     .05       0
Bank Sta=4996.4,5002.4
XS Rating Curve= 0 ,0
Exp/Cntr=0.3,0.1

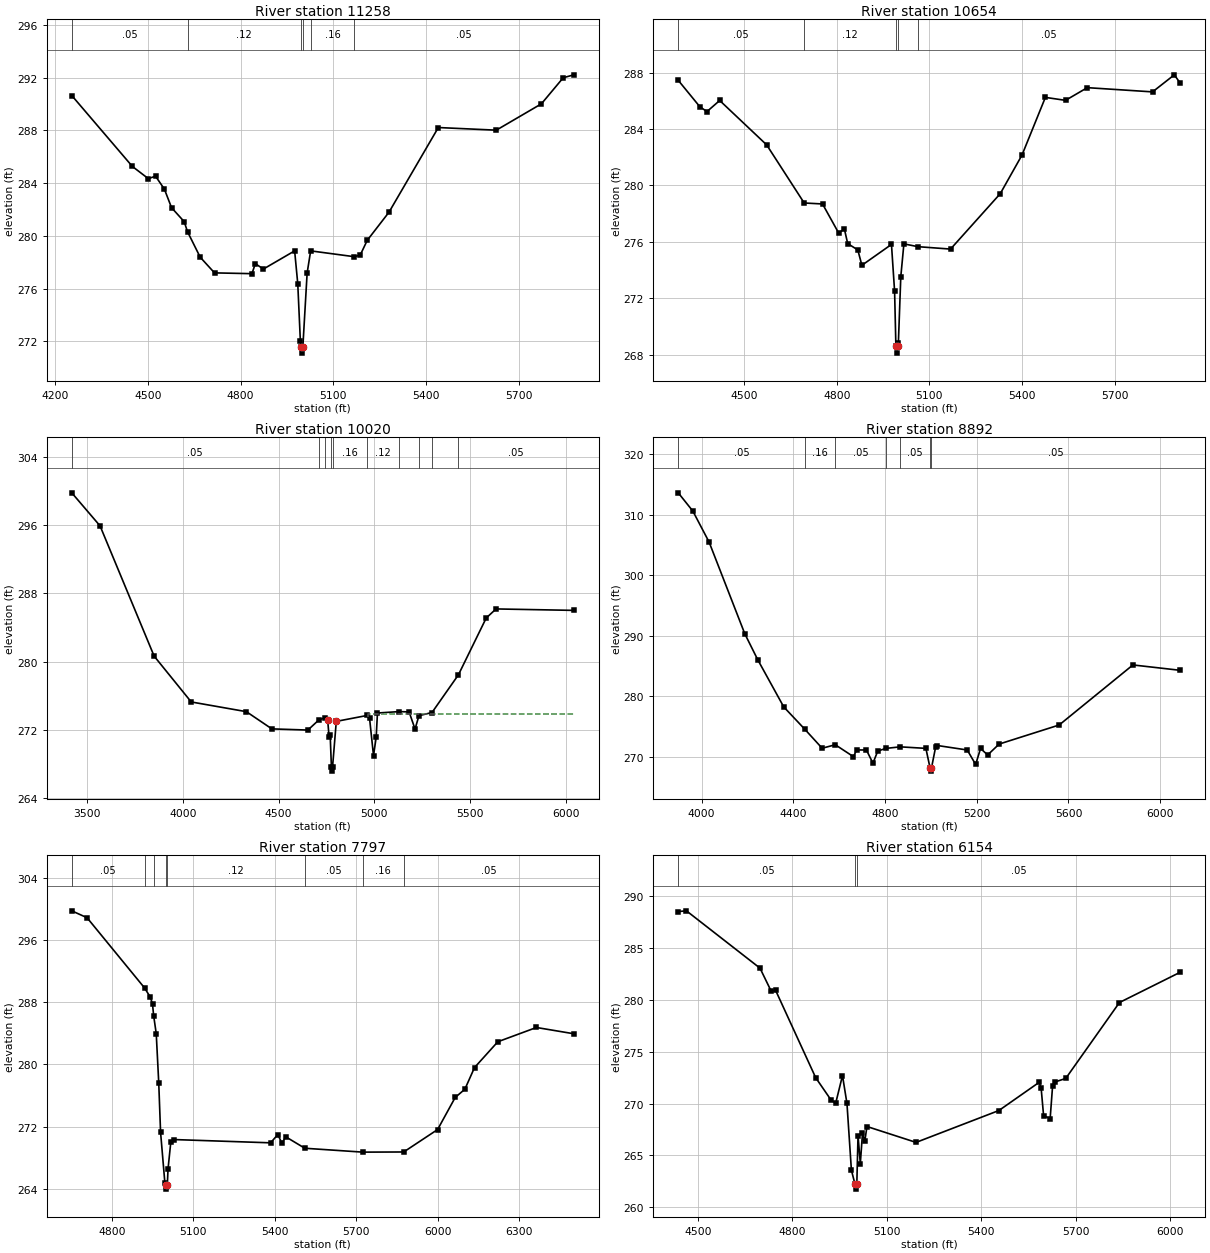
Type RM Length L Ch R = 1 ,11258   ,604,604,604
BEGIN DESCRIPTION:
RAYLEIGH BRANCH 18.0
END DESCRIPTION:
XS GIS Cut Line= 3
      3617088.18     10301813.37      3616843.05      10301267.2
      3615828.19     10301120.99
#Sta/Elev= 30
    4254  290.65  4449.9  285.27  4501.7  284.34  4524.9  284.53  4553.5  283.55
  4576.7  282.14  4617.5  281.08  4628.5  280.31  4669.4  278.38  4715.7  277.19
  4836.8  277.13  4847.7  277.89  4873.8  277.48  4974.9  278.86    4985  276.36
  4993.4  272.02  4995.5   271.6  4998.2   271.1  5001.5   271.6  5015.3  277.18
  5026.7  278.86  5167.2  278.42    5187  278.54  5209.7  279.66  5280.2   281.8
  5439.6  288.22  5627.2  288.02  5773.1  290.02  5843.7     292    5878  292.22
#Mann= 6 ,-1 , 0
    4254     .05       0  4628.5     .12       0  4995.5     .07       0
  5001.5     .12       0  5026.7     .16       0  5167.2     .05       0
Bank Sta=4995.5,5001.5
XS Rating Curve= 0 ,0
Exp/Cntr=0.3,0.1

Type RM Length L Ch R = 1 ,10654   ,634,634,634
BEGIN DESCRIPTION:
RAYLEIGH BRANCH 17.0
END DESCRIPTION:
XS GIS Cut Line= 3
      3617182.77     10301374.69      3616946.26     10300828.56
      3615922.82     10300721.06
#Sta/Elev= 30
  4287.4  287.45  4356.8  285.59  4380.2  285.23  4421.5  286.02  4573.5  282.87
  4694.8  278.75  4754.2  278.68  4806.6  276.61  4824.7  276.92  4835.6  275.87
  4868.3  275.42  4881.5  274.33  4977.2  275.81  4987.3  272.49  4991.5   268.6
  4994.2   268.1  4997.5   268.6  4999.5   268.8  5007.4  273.53  5017.4  275.85
    5063  275.65  5168.3  275.48  5329.1  279.41  5399.5  282.15  5475.1  286.24
  5540.3  286.03  5610.7  286.93  5821.8  286.63  5892.2  287.84  5911.6  287.24
#Mann= 5 ,-1 , 0
  4287.4     .05       0  4694.8     .12       0  4991.5     .07       0
  4997.5     .12       0    5063     .05       0
Bank Sta=4991.5,4997.5
XS Rating Curve= 0 ,0
Exp/Cntr=0.3,0.1

Type RM Length L Ch R = 1 ,10020   ,1128,1128,1128
BEGIN DESCRIPTION:
RAYLEIGH BRANCH 15.0
END DESCRIPTION:
XS GIS Cut Line= 3
      3618421.06     10299650.27      3617100.08     10300330.47
      3615999.17     10300618.15
#Sta/Elev= 30
  3419.4  299.81  3567.2  295.93  3849.8  280.64  4043.7  275.26  4331.9  274.12
  4464.9   272.1  4653.2  271.96  4709.7  273.13  4740.5   273.4  4756.7  273.13
  4764.1  271.15  4769.7  271.41  4776.2  267.64    4779  267.14  4782.2  267.64
  4801.7  272.98    4964  273.68  4975.5  273.36  4996.2  268.96  5010.2  271.12
  5016.8  273.96  5130.6  274.13  5182.2  274.09  5213.2  272.08  5233.7  273.65
  5301.8  274.02    5440  278.45  5585.3  285.12  5636.7  286.18  6043.1  286.01
#Mann= 10 ,-1 , 0
  3419.4     .05       0  4709.7     .12       0  4740.5     .16       0
  4776.2     .07       0  4782.2     .16       0    4964     .12       0
  5130.6     .16       0  5233.7     .05       0  5301.8     .16       0
    5440     .05       0
#XS Ineff= 2 , 0
                         4968.75           273.8
Permanent Ineff=
       F       F
Bank Sta=4756.7,4801.7
XS Rating Curve= 0 ,0
Exp/Cntr=0.3,0.1

Type RM Length L Ch R = 1 ,8892    ,1095,1095,1095
BEGIN DESCRIPTION:
RAYLEIGH BRANCH 14.0
END DESCRIPTION:
XS GIS Cut Line= 3
      3617692.12     10298891.63      3617058.21     10299580.83
      3615986.62     10300231.59
#Sta/Elev= 30
  3897.9  313.62  3961.7   310.6  4032.6  305.48    4188  290.36  4244.7  286.05
  4358.1  278.26  4448.7  274.62  4525.7  271.43  4582.9  272.01  4662.1  270.04
  4676.3  271.15  4718.8  271.14  4747.2  268.96  4768.2  270.96  4802.8   271.4
  4865.9  271.66  4978.2  271.41  4996.5  268.15  4999.2  267.65  5002.5  268.15
  5020.8  271.66  5028.6  271.88  5158.5  271.14  5195.3  268.75  5216.6  271.39
  5247.6  270.32  5297.7  272.12  5559.6  275.27  5881.3  285.19    6088   284.3
#Mann= 7 ,-1 , 0
  3897.9     .05       0  4448.7     .16       0  4582.9     .05       0
  4802.8     .12       0  4865.9     .05       0  4996.5     .03       0
  5002.5     .05       0
Bank Sta=4996.5,5002.5
XS Rating Curve= 0 ,0
Exp/Cntr=0.3,0.1

Type RM Length L Ch R = 1 ,7797    ,1643,1643,1643
BEGIN DESCRIPTION:
RAYLEIGH BRANCH 13.0
END DESCRIPTION:
XS GIS Cut Line= 3
      3617066.91     10298521.77      3616706.65      10299168.5
      3615808.23     10299819.53
#Sta/Elev= 30
  4652.1  299.81  4708.4  298.92  4920.2  289.87  4941.6  288.68  4949.6  287.78
  4953.7  286.31  4963.3  283.98  4972.5  277.66  4979.3  271.25  4995.3  264.66
  4998.1  264.43  5000.8  263.93  5004.1  264.43  5006.8  266.55  5017.1  270.04
  5029.7  270.32  5384.5   269.9  5411.4  270.97  5426.1  269.85  5440.8  270.67
  5510.8   269.2  5723.9   268.7  5875.1  268.72  5999.9  271.61  6064.8  275.75
  6100.4  276.81  6135.9   279.6  6221.8  282.93    6364  284.77  6501.9  283.96
#Mann= 8 ,-1 , 0
  4652.1     .05       0  4920.2     .16       0  4953.7     .12       0
  4998.1     .07       0  5004.1     .12       0  5510.8     .05       0
  5723.9     .16       0  5875.1     .05       0
Bank Sta=4998.1,5004.1
XS Rating Curve= 0 ,0
Exp/Cntr=0.3,0.1

Type RM Length L Ch R = 1 ,6154    ,700,700,700
BEGIN DESCRIPTION:
RAYLEIGH BRANCH 11.0
END DESCRIPTION:
XS GIS Cut Line= 3
      3616585.15     10298447.98      3616025.23     10298973.19
      3615391.54     10299502.71
#Sta/Elev= 30
  4438.2  288.49  4464.2  288.56  4697.7  283.04  4732.9  280.84    4747  280.92
  4874.5  272.49  4923.9  270.31    4938  270.04  4959.5   272.7  4973.7  270.01
  4987.8  263.58    4999  262.26  5001.7  261.76    5005  262.26  5008.8  266.91
  5016.1  264.22    5023  267.15  5030.3  266.39  5037.2  267.79    5193  266.26
  5455.9  269.33  5583.5  272.04    5590  271.48  5597.8  268.83  5618.6  268.56
  5626.4  271.72  5632.9  272.07  5668.1  272.42  5838.5  279.73  6031.7  282.65
#Mann= 3 ,-1 , 0
  4438.2     .05       0    4999     .03       0    5005     .05       0
Bank Sta=4999,5005
XS Rating Curve= 0 ,0
Exp/Cntr=0.3,0.1

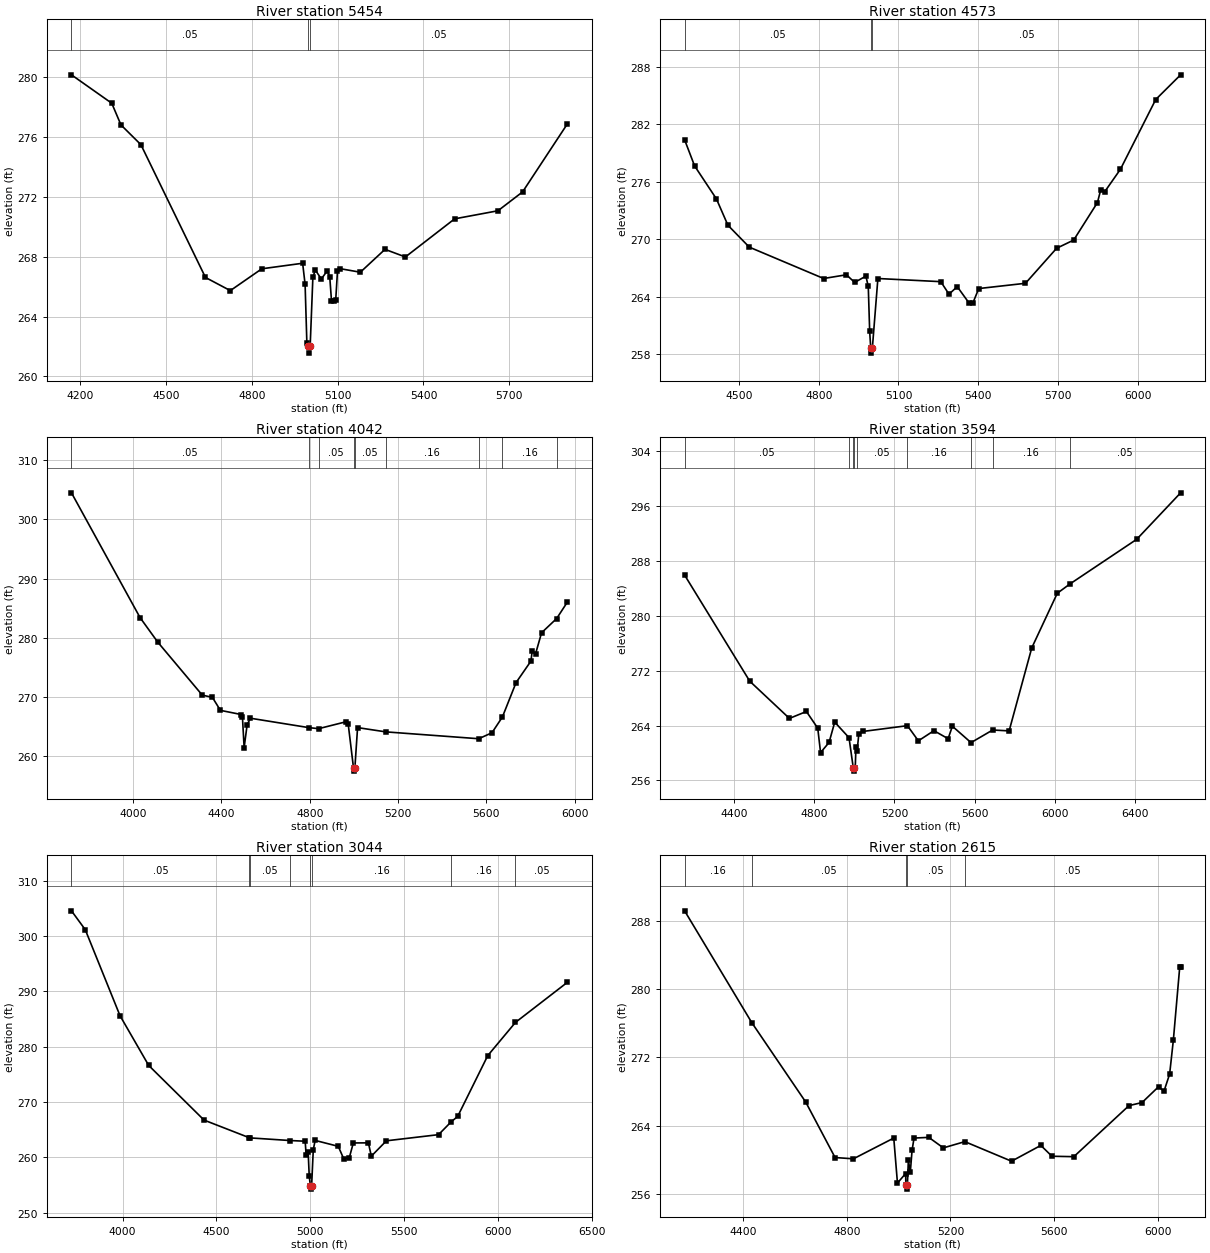
Type RM Length L Ch R = 1 ,5454    ,881,881,881
BEGIN DESCRIPTION:
RAYLEIGH BRANCH 10.0
END DESCRIPTION:
XS GIS Cut Line= 3
       3616411.5     10298244.02      3615851.61     10298421.97
      3614915.62     10299084.97
#Sta/Elev= 30
  4169.1  280.17    4310  278.27  4342.2  276.82  4411.9   275.5  4637.7  266.62
  4724.6  265.74  4834.8   267.2  4977.5  267.57  4986.1  266.16  4992.3  262.22
  4997.9  262.06  5000.7  261.56  5003.9  262.06  5013.3  266.63  5021.8  267.12
  5042.7  266.52  5063.6  267.06  5072.3  266.66  5078.4  265.06  5086.9  265.03
  5093.2  265.12  5099.3  267.02    5108  267.21  5179.3  266.97  5265.5   268.5
  5336.8  267.99  5509.1  270.54  5660.5  271.08  5746.6  272.34  5903.6   276.9
#Mann= 3 ,-1 , 0
  4169.1     .05       0  4997.9     .03       0  5003.9     .05       0
Bank Sta=4997.9,5003.9
XS Rating Curve= 0 ,0
Exp/Cntr=0.3,0.1

Type RM Length L Ch R = 1 ,4573    ,531,531,531
BEGIN DESCRIPTION:
RAYLEIGH BRANCH 9.0
END DESCRIPTION:
XS GIS Cut Line= 3
      3616185.79     10297775.28      3615211.34     10298119.26
      3614492.08     10298541.66
#Sta/Elev= 30
  4294.8  280.39  4332.4  277.66  4414.6  274.21  4457.8  271.46  4538.3  269.17
  4818.3  265.89  4904.1  266.28    4935  265.48  4977.4  266.14  4986.3  265.06
  4991.6  260.36  4995.6  258.59  4998.4  258.09  5001.6  258.59  5022.5  265.89
  5259.3  265.56  5290.3  264.25  5321.2  265.04  5365.2  263.35  5380.9  263.38
  5402.3  264.84  5578.2  265.39  5695.4  269.05  5759.8  269.91  5849.2  273.83
  5861.4  275.15    5877  274.98  5935.7  277.31  6068.6   284.6  6162.3  287.18
#Mann= 3 ,-1 , 0
  4294.8     .05       0  4995.6     .03       0  5001.6     .05       0
Bank Sta=4995.6,5001.6
XS Rating Curve= 0 ,0
Exp/Cntr=0.3,0.1

Type RM Length L Ch R = 1 ,4042    ,448,448,448
BEGIN DESCRIPTION:
RAYLEIGH BRANCH 7.0
END DESCRIPTION:
XS GIS Cut Line= 3
      3615892.12     10296541.61      3615192.11     10297641.64
      3614392.08     10298141.66
#Sta/Elev= 30
  3720.4  304.49  4031.2  283.42  4111.6  279.27  4313.1  270.33  4358.8  269.96
  4395.2  267.76  4489.2  267.06  4495.1  266.62  4502.7  261.46  4516.3  265.34
  4531.5  266.43  4796.8  264.84  4840.3  264.67    4965  265.84  4974.3  265.42
  4998.4     258  5001.2   257.5  5004.4     258  5016.7  264.85    5144  264.13
  5565.6  262.97  5625.7  263.98    5673  266.65  5734.8  272.45    5802  276.07
  5807.9  277.75  5823.2  277.31  5850.3  280.86  5918.8  283.27  5967.7  286.07
#Mann= 9 ,-1 , 0
  3720.4     .05       0  4796.8     .16       0  4840.3     .05       0
  4998.4     .03       0  5004.4     .05       0    5144     .16       0
  5565.6     .05       0    5673     .16       0  5918.8     .05       0
Bank Sta=4998.4,5004.4
XS Rating Curve= 0 ,0
Exp/Cntr=0.3,0.1

Type RM Length L Ch R = 1 ,3594    ,550,550,550
BEGIN DESCRIPTION:
RAYLEIGH BRANCH 6.0
END DESCRIPTION:
XS GIS Cut Line= 3
      3615692.12     10296691.63      3615092.11     10297291.64
      3613992.12     10298491.62
#Sta/Elev= 30
  4152.3  285.96  4477.6  270.48  4675.6  265.05  4760.4  266.06    4817  263.63
  4831.1  260.06  4873.6  261.55  4901.8  264.51  4973.1  262.24  4994.3  257.86
  4997.1  257.36  5000.3  257.86  5004.2  257.86  5007.9   260.9  5013.3  260.26
  5022.1  262.78  5043.1  263.15  5264.7  263.99  5319.3  261.78    5397  263.26
  5467.9  262.09  5489.2  263.91  5582.3  261.52  5690.5  263.36  5772.5  263.23
  5885.4  275.33    6013  283.31  6075.9  284.66  6409.5  291.18  6628.7  297.96
#Mann= 9 ,-1 , 0
  4152.3     .05       0  4973.1      .1       0  4994.3     .07       0
  5000.3      .1       0  5013.3     .05       0  5264.7     .16       0
  5582.3     .05       0  5690.5     .16       0  6075.9     .05       0
Bank Sta=4994.3,5000.3
XS Rating Curve= 0 ,0
Exp/Cntr=0.3,0.1

Type RM Length L Ch R = 1 ,3044    ,429,429,429
BEGIN DESCRIPTION:
RAYLEIGH BRANCH 5.0
END DESCRIPTION:
XS GIS Cut Line= 3
      3615842.14     10296441.62      3614742.11     10297041.64
       3614042.1     10298241.66
#Sta/Elev= 30
  3727.7  304.53  3801.3  301.12  3986.4  285.58  4139.2   276.6    4434  266.73
  4674.8  263.55  4680.9  263.51  4891.9  263.04  4972.7  262.91  4977.9   260.4
  4988.6  260.95  4994.4  256.56  5000.9  254.76  5003.6  254.26  5006.9  254.76
  5015.9  261.39  5025.8  263.06    5149  261.99  5177.5  259.77  5207.7  259.94
  5229.2   262.6  5309.4  262.62  5325.2  260.22  5405.4  262.99  5683.2   264.1
  5751.4  266.45  5784.9  267.38  5945.4  278.38  6093.1  284.38    6370  291.63
#Mann= 8 ,-1 , 0
  3727.7     .05       0  4674.8      .1       0  4680.9     .05       0
  4891.9     .16       0  5000.9     .07       0  5006.9     .16       0
  5751.4     .16       0  6093.1     .05       0
Bank Sta=5000.9,5006.9
XS Rating Curve= 0 ,0
Exp/Cntr=0.3,0.1

Type RM Length L Ch R = 1 ,2615    ,1518,1518,1518
BEGIN DESCRIPTION:
RAYLEIGH BRANCH 4.0
END DESCRIPTION:
XS GIS Cut Line= 3
      3615242.13     10296091.62      3614642.11     10296691.64
      3613842.09     10297391.66
#Sta/Elev= 30
  4175.3  289.14  4433.9  276.06    4642  266.75  4755.2  260.25  4825.9   260.1
  4981.4  262.53  4995.6  257.26  5027.2  258.38    5028  257.05  5030.7  256.55
    5034  257.05  5037.6  259.93  5045.2  258.55  5051.9  261.09  5059.5  262.53
  5116.4  262.61  5172.4  261.38  5255.3  262.11  5435.3  259.82  5548.2  261.67
    5591   260.4  5675.4  260.35    5888  266.33  5938.3  266.69  6001.9  268.54
  6022.8  268.01  6044.6  270.03  6058.9     274  6083.6   282.6  6086.9   282.6
#Mann= 5 ,-1 , 0
  4175.3     .16       0  4433.9     .05       0    5028     .03       0
    5034     .05       0  5255.3     .05       0
Bank Sta=5028,5034
XS Rating Curve= 0 ,0
Exp/Cntr=0.3,0.1

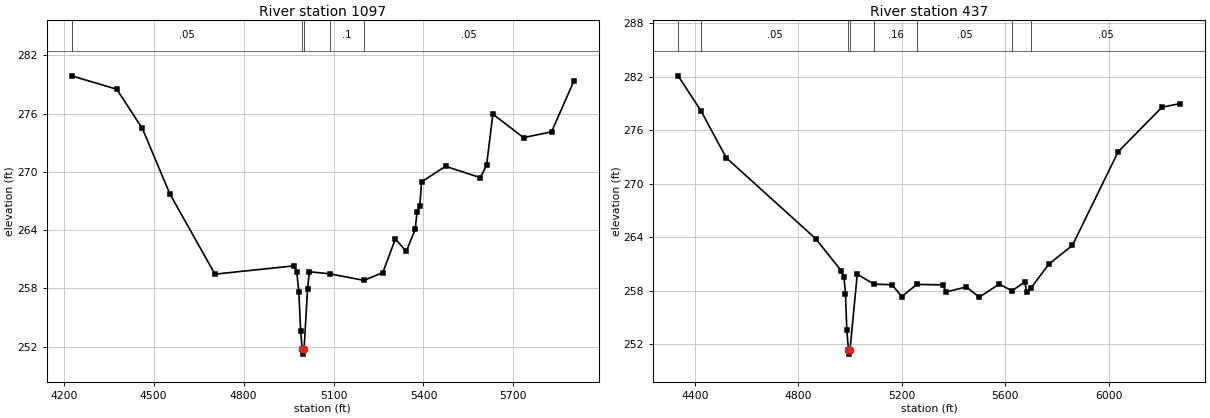
Type RM Length L Ch R = 1 ,1097    ,660,660,660
BEGIN DESCRIPTION:
RAYLEIGH BRANCH 3.0
END DESCRIPTION:
XS GIS Cut Line= 3
      3614575.57     10295735.34      3613855.09     10296269.19
      3613426.26     10296918.93
#Sta/Elev= 30
  4226.4  279.88  4376.8   278.5  4462.3  274.46  4554.3  267.71  4704.4  259.47
  4969.4  260.33  4977.5  259.69  4984.1  257.68  4990.3  253.59  4995.7  251.74
  4998.4  251.24  5001.7  251.74  5013.3  257.94  5019.5  259.72  5088.4   259.5
  5201.4  258.83  5264.3  259.63  5306.4   263.1  5342.5  261.81  5372.6  264.09
  5378.6  265.91  5387.7  266.46  5393.7  268.97  5473.5  270.57  5589.4   269.4
  5610.4  270.66  5631.5  275.94  5733.9  273.52  5827.2  274.12  5901.6  279.33
#Mann= 5 ,-1 , 0
  4226.4     .05       0  4995.7     .03       0  5001.7     .05       0
  5088.4      .1       0  5201.4     .05       0
Bank Sta=4995.7,5001.7
XS Rating Curve= 0 ,0
Exp/Cntr=0.3,0.1

Type RM Length L Ch R = 1 ,437     ,0,0,0
BEGIN DESCRIPTION:
RAYLEIGH BRANCH 1.0
END DESCRIPTION:
XS GIS Cut Line= 3
        3614632.     10295500.96      3613794.32     10295722.32
       3613042.1     10296491.65
#Sta/Elev= 30
  4334.7   282.1  4424.5  278.11  4520.8  272.92  4866.5  263.86  4965.5  260.27
  4975.9  259.59  4982.1   257.7  4987.3  253.59  4993.6  251.42  4996.3  250.92
  4999.6  251.42  5027.6  259.88  5092.3  258.76    5162   258.7  5199.7  257.37
  5257.9  258.73  5357.8  258.68  5371.9  257.89  5449.8  258.45  5499.2   257.3
  5577.1  258.77  5625.7  258.01  5675.9  259.01  5683.1  257.84  5700.4  258.35
    5768  260.99  5859.8   263.1  6036.7  273.59  6206.4  278.59  6277.1  278.99
#Mann= 8 ,-1 , 0
  4334.7     .12       0  4424.5     .05       0  4993.6     .03       0
  4999.6     .05       0  5092.3     .16       0  5257.9     .05       0
  5625.7     .16       0  5700.4     .05       0
Bank Sta=4993.6,4999.6
XS Rating Curve= 0 ,0
Exp/Cntr=0.3,0.1

Chan Stop Cuts=-1
Use User Specified Reach Order=0
Composite Channel Slope=5