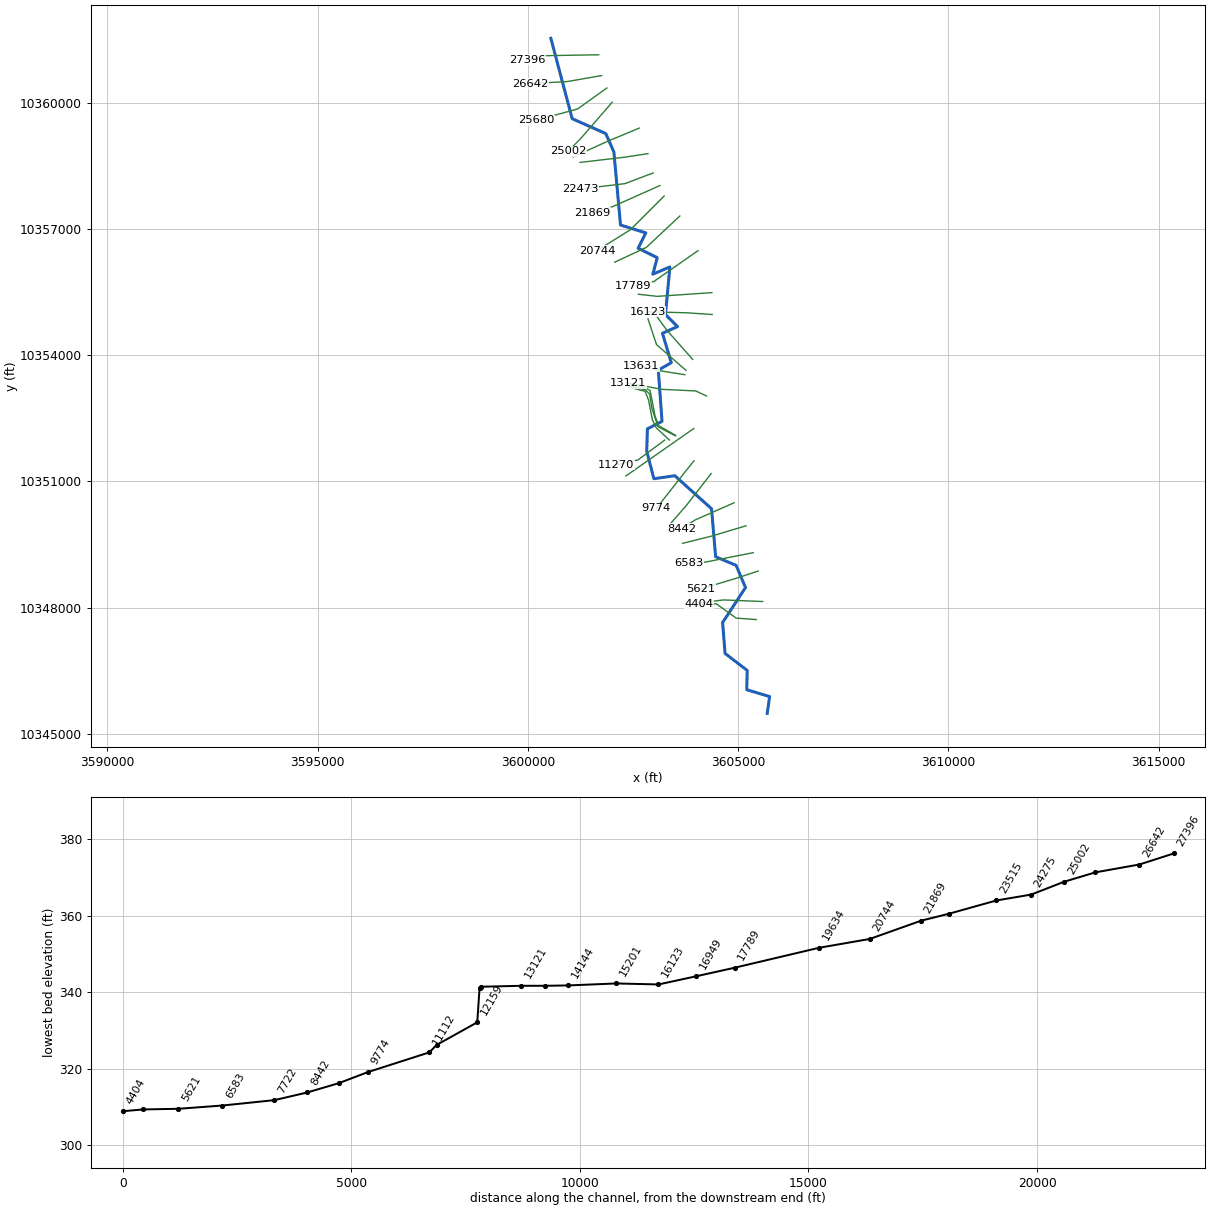
--- RED BANK CREEK.prj (project) ---

Proj Title=RED BANK CREEK Base Level Engineering
Current Plan=p01
Default Exp/Contr=0.3,0.1
English Units
Geom File=g01
Flow File=f01
Plan File=p01
Y Axis Title=Elevation
X Axis Title(PF)=Main Channel Distance
X Axis Title(XS)=Station
BEGIN DESCRIPTION:
RED BANK CREEK
END DESCRIPTION:
DSS Export Rating Curves= 0
DSS Export Rating Curve Sorted= 0
DSS Export Volume Flow Curves= 0
DXF OffsetX= 0
DXF OffsetY= 0
DXF ScaleX= 1
DXF ScaleY= 10

--- RED BANK CREEK.p01 (plan) ---

Plan Title=Multiple Run
Short Identifier=Multiple
Geom File=g01
Flow File=f01
Subcritical Flow
K Sum by GR= 0
Std Step Tol= 0.01
Critical Tol= 0.01
Num of Std Step Trials= 20
Max Error Tol= 0.3
Flow Tol Ratio= 0.001
Split Flow NTrial= 30
Split Flow Tol= 0.02
Split Flow Ratio= 0.02
Log Output Level= 0
Friction Slope Method= 1
Unsteady Friction Slope Method= 2
Unsteady Bridges Friction Slope Method= 1
Parabolic Critical Depth
Global Vel Dist=  1 , 1 , 1
Global Log Level= 0
CheckData=True
Encroach Param= -1, 0, 0, 0
BEGIN DESCRIPTION:
Multiple Run
END DESCRIPTION:

--- RED BANK CREEK.f01 (steady flow) ---

Flow Title=Multiple
Number of Profiles=7
Profile Names=10-year,25-year,50-year,1pct_min,100-year,1pct_plu,500-year
River Rch & RM= RED BANK CREEK,Reach-1,27396
    1820    2564    3192    2894    3913    5292    5867
River Rch & RM= RED BANK CREEK,Reach-1,22473
    2122    2997    3737    3390    4584    6199    6882
River Rch & RM= RED BANK CREEK,Reach-1,12159
    2245    3183    3980    3621    4897    6623    7400
Boundary for River Rch & Prof#=RED BANK CREEK,Reach-1,1
Up Type=0
Dn Type=3
Dn Slope=0.005
Boundary for River Rch & Prof#=RED BANK CREEK,Reach-1,2
Up Type=0
Dn Type=3
Dn Slope=0.005
Boundary for River Rch & Prof#=RED BANK CREEK,Reach-1,3
Up Type=0
Dn Type=3
Dn Slope=0.005
Boundary for River Rch & Prof#=RED BANK CREEK,Reach-1,4
Up Type=0
Dn Type=3
Dn Slope=0.005
Boundary for River Rch & Prof#=RED BANK CREEK,Reach-1,5
Up Type=0
Dn Type=3
Dn Slope=0.005
Boundary for River Rch & Prof#=RED BANK CREEK,Reach-1,6
Up Type=0
Dn Type=3
Dn Slope=0.005
Boundary for River Rch & Prof#=RED BANK CREEK,Reach-1,7
Up Type=0
Dn Type=3
Dn Slope=0.005

--- RED BANK CREEK.g01 (geometry) ---

Geom Title=Existing Conditions
Program Version=4.10

River Reach=RED BANK CREEK  ,Reach-1
Reach XY= 30
      3600548.31     10361544.43      3601054.55     10359632.68
      3601854.66      10359277.3      3602046.86     10358840.38
      3602204.19      10357102.5      3602806.85     10356914.52
      3602622.89     10356551.11      3603077.74     10356325.58
      3602973.82      10355933.6      3603378.36     10356104.93
      3603273.19     10354971.85      3603560.46     10354685.43
      3603201.54     10354525.56      3603411.83     10353826.56
      3603103.23     10353650.65      3603191.38     10352431.58
       3602843.4     10352251.17      3602828.09     10351718.14
      3602998.04     10351065.16      3603494.83     10351136.37
      3604369.45     10350349.95       3604466.1     10349208.97
      3604953.47     10349003.16      3605177.07     10348476.78
      3604632.34       10347643.      3604690.99     10346907.15
      3605217.19     10346503.86       3605206.1       10346045.
      3605750.37     10345881.37      3605692.34     10345481.58

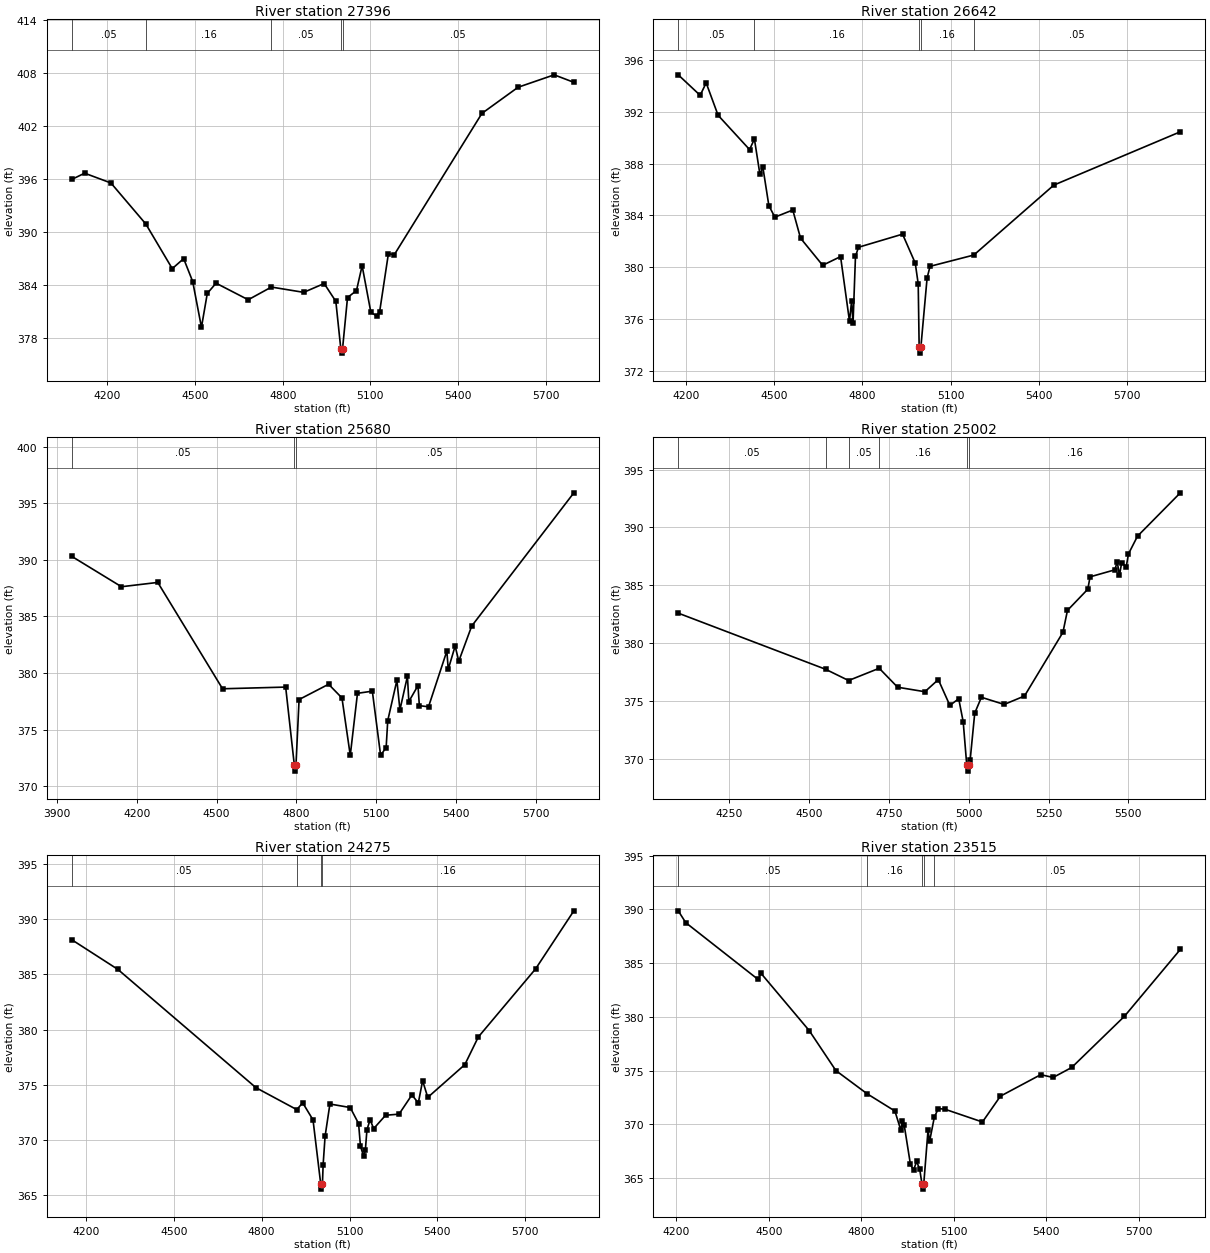
Type RM Length L Ch R = 1 ,27396   ,754,754,754
BEGIN DESCRIPTION:
RED BANK CREEK 50.0
END DESCRIPTION:
XS GIS Cut Line= 3
      3601686.07     10361153.28      3600379.61     10361130.88
      3599979.57     10361030.87
#Sta/Elev= 30
  4077.8  395.98  4121.8  396.69  4211.8  395.58  4331.3  390.93  4421.8  385.87
  4460.9     387  4491.8  384.41  4521.8  379.22  4541.8  383.06  4571.8  384.22
  4681.9  382.34  4761.3  383.78  4871.9  383.18  4941.9  384.18  4981.9  382.16
  4998.9  376.79  5001.7  376.29  5004.9  376.79  5021.9  382.59  5052.6  383.38
  5071.9   386.2  5101.9   380.9  5121.9  380.51  5131.9  380.99  5161.9  387.57
  5181.9  387.44  5482.1  403.47  5605.8  406.43  5729.5  407.84  5796.8  406.99
#Mann= 5 ,-1 , 0
  4077.8     .05       0  4331.3     .16       0  4761.3     .05       0
  4998.9     .03       0  5004.9     .05       0
Bank Sta=4998.9,5004.9
XS Rating Curve= 0 ,0
Exp/Cntr=0.3,0.1

Type RM Length L Ch R = 1 ,26642   ,962,962,962
BEGIN DESCRIPTION:
RED BANK CREEK 48.0
END DESCRIPTION:
XS GIS Cut Line= 3
      3601755.54     10360658.49       3600941.8      10360516.1
      3600062.84     10360467.52
#Sta/Elev= 30
  4173.9  394.84  4248.4  393.26  4268.8  394.22  4309.4  391.72  4416.3  389.08
  4432.8  389.89  4451.5  387.17  4461.6  387.71  4481.9  384.76  4502.2  383.87
  4563.2  384.42  4589.6  382.25  4664.7  380.16  4725.6  380.83    4756  375.84
    4763   377.4    4768  375.69  4776.3  380.85  4786.5  381.55  4936.3  382.56
  4979.4  380.33  4989.5  378.73  4992.7  373.89  4995.5  373.39  4998.7  373.89
  5019.7  379.18  5029.7  380.08  5178.5  380.95  5450.4  386.34  5880.3  390.45
#Mann= 5 ,-1 , 0
  4173.9     .05       0  4432.8     .16       0  4992.7     .07       0
  4998.7     .16       0  5178.5     .05       0
Bank Sta=4992.7,4998.7
XS Rating Curve= 0 ,0
Exp/Cntr=0.3,0.1

Type RM Length L Ch R = 1 ,25680   ,678,678,678
BEGIN DESCRIPTION:
RED BANK CREEK 47.0
END DESCRIPTION:
XS GIS Cut Line= 3
      3601881.47     10360363.44      3601181.44     10359863.41
      3600192.07     10359591.63
#Sta/Elev= 30
  3955.8   390.3  4142.5  387.62  4278.9     388  4522.3  378.61  4759.4  378.76
  4792.1  371.84  4794.8  371.34  4798.1  371.84  4809.8  377.66  4920.7  379.01
  4970.9   377.8  5002.1  372.73  5029.2  378.21    5085   378.4  5116.1  372.74
  5136.9  373.42  5142.9   375.8  5177.3  379.36  5188.7  376.75  5216.9  379.72
  5222.1  377.48  5256.5  378.89  5261.7  377.12  5296.1  377.02    5365  381.94
  5370.2  380.33  5396.1  382.38  5409.8  381.05  5458.4  384.15  5842.1  395.91
#Mann= 3 ,-1 , 0
  3955.8     .05       0  4792.1     .03       0  4798.1     .05       0
Bank Sta=4792.1,4798.1
XS Rating Curve= 0 ,0
Exp/Cntr=0.3,0.1

Type RM Length L Ch R = 1 ,25002   ,727,727,727
BEGIN DESCRIPTION:
RED BANK CREEK 45.0
END DESCRIPTION:
XS GIS Cut Line= 3
      3602007.29     10360024.84       3601255.3     10359157.27
       3600956.2     10358858.17
#Sta/Elev= 30
  4091.3  382.58  4552.7  377.72  4624.4  376.75  4720.2  377.81  4777.8  376.17
  4863.1  375.78  4905.1  376.83  4941.2   374.6    4969  375.17    4983  373.18
  4994.2  369.41    4997  368.91  5000.2  369.41  5004.8  369.88  5019.1  373.93
    5040   375.3  5111.2  374.68  5174.8  375.41  5295.1  380.92  5309.3  382.82
  5372.9  384.65    5380  385.72  5457.8  386.33  5464.9  387.04  5471.9  385.87
    5479  386.94  5493.1  386.58  5500.2  387.71  5528.5  389.24  5662.4  392.99
#Mann= 6 ,-1 , 0
  4091.3     .05       0  4552.7      .1       0  4624.4     .05       0
  4720.2     .16       0  4994.2     .07       0  5000.2     .16       0
Bank Sta=4994.2,5000.2
XS Rating Curve= 0 ,0
Exp/Cntr=0.3,0.1

Type RM Length L Ch R = 1 ,24275   ,760,760,760
BEGIN DESCRIPTION:
RED BANK CREEK 43.0
END DESCRIPTION:
XS GIS Cut Line= 3
      3602649.58     10359408.47      3601892.11     10359091.64
       3601078.4      10358722.7
#Sta/Elev= 30
  4151.6  388.15  4308.9  385.46  4780.6  374.73    4920  372.74  4940.1  373.36
  4975.4  371.81  5001.6  366.03  5004.3  365.53  5007.6  366.03    5010  367.76
  5016.6  370.32  5033.1  373.25  5102.4  372.93    5131  371.48  5137.4  369.43
  5148.3  368.51  5154.1  369.06  5159.6  370.92  5170.3  371.82  5182.6  371.02
  5223.3  372.23  5269.1  372.33    5313  374.07    5335  373.35  5349.7  375.36
  5367.3  373.85  5493.8  376.82  5539.9  379.33  5735.6  385.51  5866.1  390.77
#Mann= 4 ,-1 , 0
  4151.6     .05       0    4920     .16       0  5001.6     .07       0
  5007.6     .16       0
Bank Sta=5001.6,5007.6
XS Rating Curve= 0 ,0
Exp/Cntr=0.3,0.1

Type RM Length L Ch R = 1 ,23515   ,1042,1042,1042
BEGIN DESCRIPTION:
RED BANK CREEK 42.0
END DESCRIPTION:
XS GIS Cut Line= 3
      3602857.92     10358800.84       3602301.7     10358715.68
      3601242.13     10358591.65
#Sta/Elev= 30
  4205.9  389.86  4230.3  388.76  4464.7  383.49  4474.8  384.04  4630.9  378.73
  4717.6  375.01  4818.6  372.86  4909.1  371.25  4928.3  369.47  4933.3  370.33
  4939.3  369.94  4959.5  366.29  4969.6  365.76  4979.6  366.56  4989.7  365.83
  4996.8  364.49  4999.5  363.99  5002.8  364.49  5016.6  369.48  5021.6  368.42
  5037.2   370.7  5050.1  371.47  5070.2  371.43  5193.2  370.23  5251.5  372.63
  5382.4  374.63  5422.6  374.37    5483   375.3  5654.2  380.06  5835.4  386.27
#Mann= 5 ,-1 , 0
  4205.9     .05       0  4818.6     .16       0  4996.8     .07       0
  5002.8     .16       0  5037.2     .05       0
Bank Sta=4996.8,5002.8
XS Rating Curve= 0 ,0
Exp/Cntr=0.3,0.1

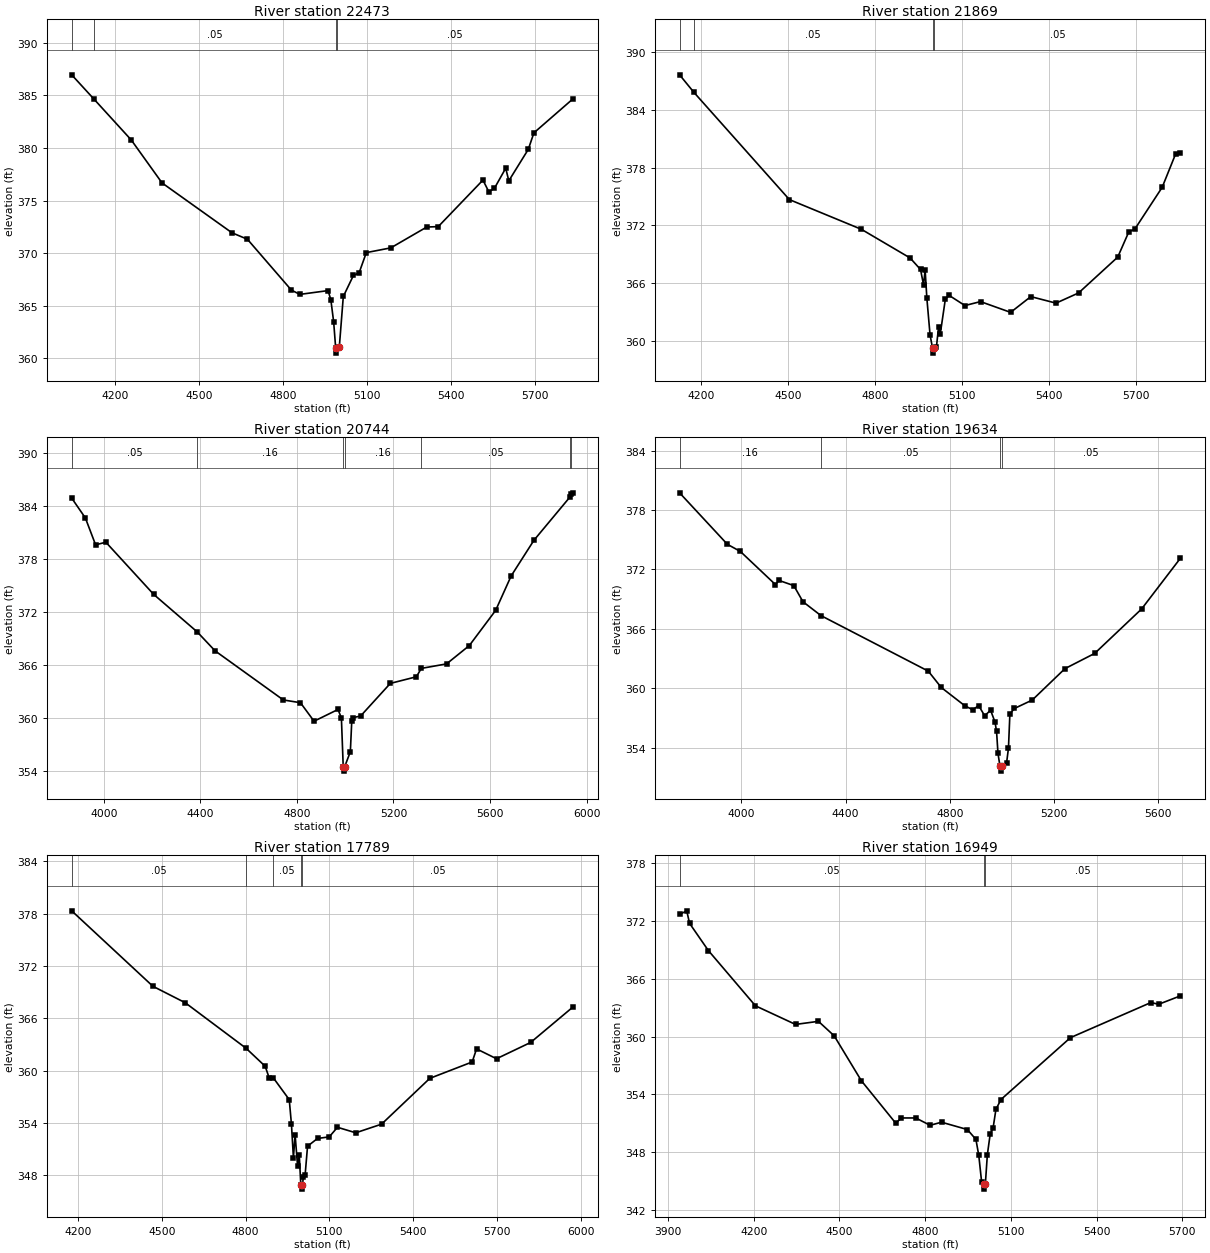
Type RM Length L Ch R = 1 ,22473   ,604,604,604
BEGIN DESCRIPTION:
RED BANK CREEK 40.0
END DESCRIPTION:
XS GIS Cut Line= 3
      3602979.49     10358340.78      3602309.73     10358086.73
      3601245.29     10357959.06
#Sta/Elev= 30
  4046.4  386.95    4126  384.64  4259.1  380.76    4369  376.68  4618.9  371.94
  4673.8  371.33  4830.8   366.5  4861.1  366.09  4961.8  366.45  4971.8  365.58
  4981.9  363.47    4989  361.01  4991.7  360.51    4995  361.01  5002.1  361.12
  5016.3  365.89  5052.4  367.89  5072.6  368.13  5098.5  370.06  5185.9  370.51
  5314.3  372.49  5355.4  372.53    5515  376.95  5535.9  375.84    5556  376.17
  5596.3  378.08  5607.3  376.88  5676.9  379.87    5697  381.44  5834.8  384.63
#Mann= 4 ,-1 , 0
  4046.4     .16       0    4126     .05       0    4989     .03       0
    4995     .05       0
Bank Sta=4989,5002.1
XS Rating Curve= 0 ,0
Exp/Cntr=0.3,0.1

Type RM Length L Ch R = 1 ,21869   ,1125,1125,1125
BEGIN DESCRIPTION:
RED BANK CREEK 39.0
END DESCRIPTION:
XS GIS Cut Line= 3
      3603142.07     10358041.63      3602016.15     10357539.78
      3601542.15     10357391.66
#Sta/Elev= 30
  4125.6  387.66  4174.7  385.85  4504.8  374.68  4753.5  371.59  4921.6  368.61
  4957.6  367.41  4968.1  365.81  4973.5  367.37  4979.5  364.42  4990.5  360.61
  4999.2  359.21    5002  358.71  5005.2  359.21  5012.4  359.32    5020  361.44
  5025.5  360.65  5043.2   364.3  5056.2  364.72  5110.9  363.66  5164.8  364.07
  5268.7  362.95  5338.4  364.59  5425.4  363.91  5503.4  364.97  5638.6   368.7
  5676.8  371.32  5697.8  371.62  5792.1  375.96  5838.7  379.45  5854.9  379.53
#Mann= 4 ,-1 , 0
  4125.6     .16       0  4174.7     .05       0  4999.2     .03       0
  5005.2     .05       0
Bank Sta=4999.2,5005.2
XS Rating Curve= 0 ,0
Exp/Cntr=0.3,0.1

Type RM Length L Ch R = 1 ,20744   ,1110,1110,1110
BEGIN DESCRIPTION:
RED BANK CREEK 37.0
END DESCRIPTION:
XS GIS Cut Line= 3
      3603242.13     10357791.67      3602442.11     10356991.64
      3601642.11     10356491.65
#Sta/Elev= 30
  3866.9  384.89  3923.5  382.64  3965.9  379.59  4008.4  379.89  4206.3  373.98
  4386.8  369.72  4460.9  367.57  4743.7     362  4814.5  361.69    4871  359.59
    4970  360.92  4984.2  359.97  4991.8  354.43  4994.5  353.93  4997.8  354.43
  5021.3  356.13  5027.2  359.63  5033.7     360  5063.8  360.18    5187  363.88
  5294.9  364.63  5315.2  365.58  5419.9  366.09  5514.2  368.17  5623.3  372.16
  5687.6  376.07  5781.9  380.11    5931  385.01  5937.3  385.41  5941.7  385.49
#Mann= 7 ,-1 , 0
  3866.9     .05       0  4386.8     .16       0  4991.8     .07       0
  4997.8     .16       0  5315.2     .05       0    5931     .08       0
  5937.3     .05       0
Bank Sta=4991.8,4997.8
XS Rating Curve= 0 ,0
Exp/Cntr=0.3,0.1

Type RM Length L Ch R = 1 ,19634   ,1845,1845,1845
BEGIN DESCRIPTION:
RED BANK CREEK 35.0
END DESCRIPTION:
XS GIS Cut Line= 3
      3603615.75     10357317.72      3602815.72     10356567.68
      3602067.28      10356218.3
#Sta/Elev= 30
  3762.9  379.73  3946.4  374.53  3996.2  373.81  4130.6  370.47  4144.7  370.88
  4201.4  370.36  4236.6  368.73  4305.6  367.33  4717.7  361.72  4767.5  360.07
  4858.6  358.21  4888.4  357.82  4911.2  358.24  4934.1  357.21  4956.9  357.77
  4973.9  356.57  4979.8  355.63  4985.3  353.41  4992.9  352.12  4995.7  351.62
  4998.9  352.12    5018   352.4  5025.5  353.93    5031   357.4  5048.4  357.95
  5116.9   358.8  5242.3  361.97  5356.5  363.51  5536.7     368  5685.5  373.12
#Mann= 4 ,-1 , 0
  3762.9     .16       0  4305.6     .05       0  4992.9     .03       0
  4998.9     .05       0
Bank Sta=4992.9,4998.9
XS Rating Curve= 0 ,0
Exp/Cntr=0.3,0.1

Type RM Length L Ch R = 1 ,17789   ,840,840,840
BEGIN DESCRIPTION:
RED BANK CREEK 33.0
END DESCRIPTION:
XS GIS Cut Line= 3
      3604047.22     10356491.84      3602993.26      10355755.7
      3602495.21     10355656.09
#Sta/Elev= 30
  4177.2  378.32  4467.9  369.67  4583.9  367.78  4801.7  362.56    4870   360.5
  4884.8  359.13    4899  359.18  4956.3  356.67  4964.1  353.86  4971.2  350.03
  4977.3  352.65    4986  349.09  4992.1  350.34  4997.7  346.91  5000.4  346.41
  5003.7  346.91  5006.9  347.85    5013  347.99  5021.8  351.33  5057.5  352.22
  5099.4   352.4    5129   353.5  5194.5  352.87  5286.9  353.86  5459.6  359.11
  5611.4  360.99  5627.1  362.49  5698.5  361.36  5820.9  363.23  5970.7  367.25
#Mann= 5 ,-1 , 0
  4177.2     .05       0  4801.7     .12       0    4899     .05       0
  4997.7     .03       0  5003.7     .05       0
Bank Sta=4997.7,5003.7
XS Rating Curve= 0 ,0
Exp/Cntr=0.3,0.1

Type RM Length L Ch R = 1 ,16949   ,826,826,826
BEGIN DESCRIPTION:
RED BANK CREEK 31.0
END DESCRIPTION:
XS GIS Cut Line= 3
      3604377.06     10355493.56      3603079.61     10355404.84
      3602629.65     10355454.83
#Sta/Elev= 30
  3940.4  372.66  3965.4  373.04  3975.4  371.74  4041.2  368.92    4206  363.19
  4346.3  361.26  4426.5  361.58  4481.6  360.08  4576.8  355.42  4697.1  351.02
  4717.2  351.56  4767.3  351.56  4817.4   350.8  4857.5  351.12  4947.7  350.36
  4977.8  349.34  4987.8  347.69  4997.8  344.92  5004.8  344.68  5007.6  344.18
  5010.8  344.68  5017.9  347.76  5027.9  349.91  5037.9  350.51  5047.9  352.45
  5065.4  353.47  5308.8  359.89  5590.5  363.53  5617.6  363.35  5693.6  364.22
#Mann= 3 ,-1 , 0
  3940.4     .05       0  5004.8     .03       0  5010.8     .05       0
Bank Sta=5004.8,5010.8
XS Rating Curve= 0 ,0
Exp/Cntr=0.3,0.1

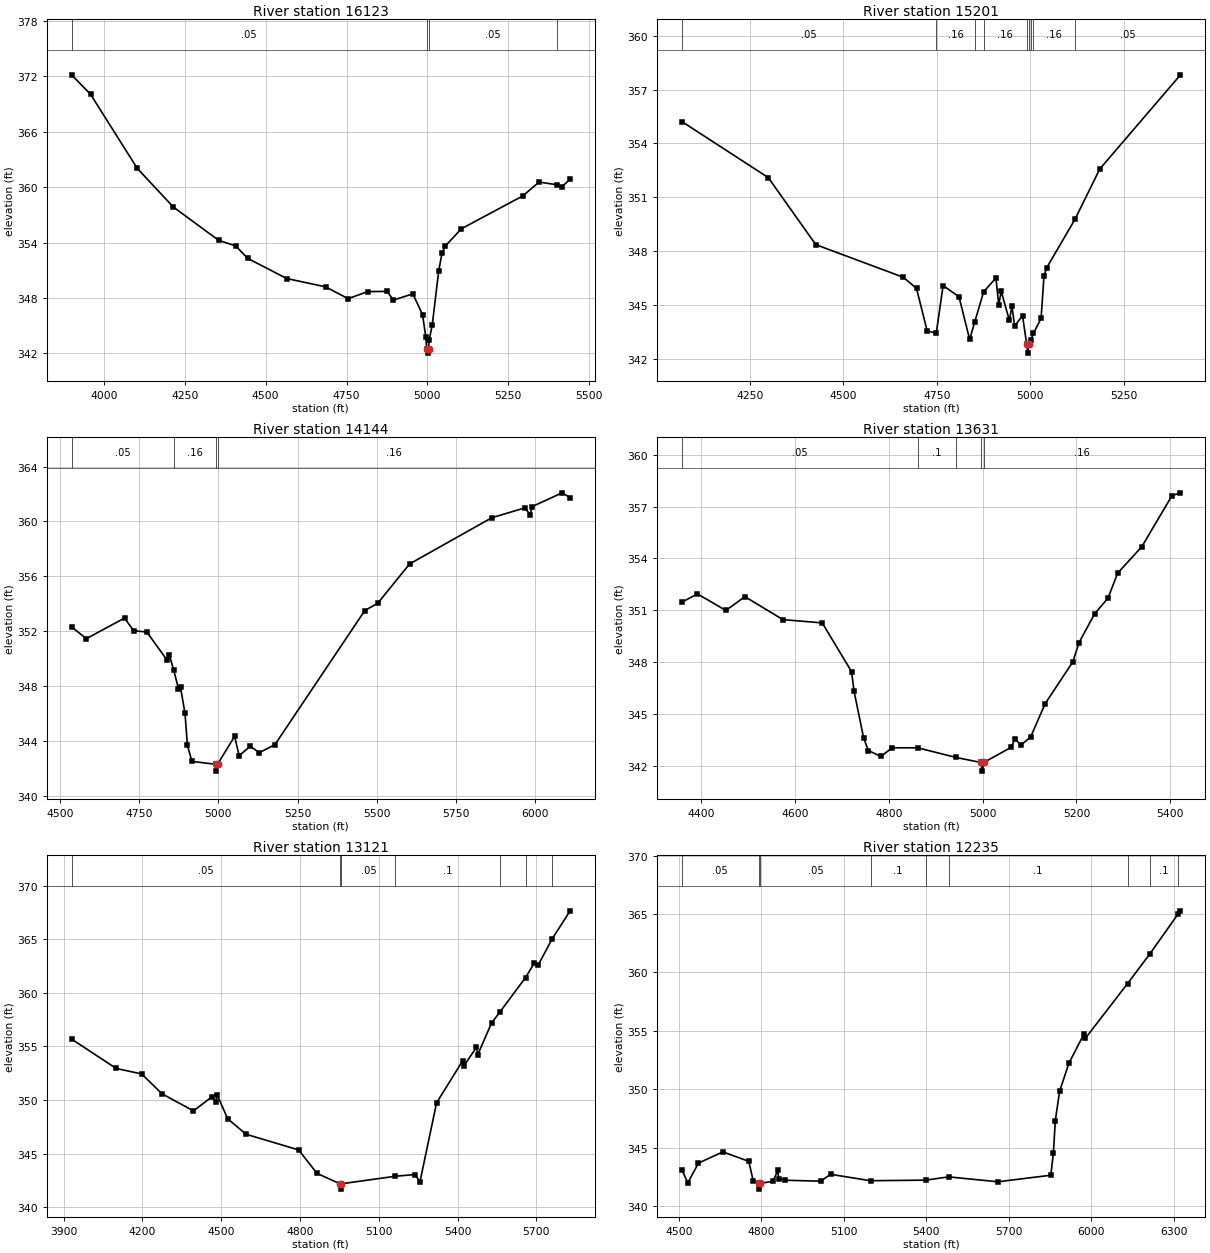
Type RM Length L Ch R = 1 ,16123   ,922,922,922
BEGIN DESCRIPTION:
RED BANK CREEK 29.0
END DESCRIPTION:
XS GIS Cut Line= 3
      3604385.74     10354972.72      3603771.95     10355014.07
      3602846.04     10355038.02
#Sta/Elev= 30
    3900  372.14  3958.5  370.04  4103.1  362.02  4214.3  357.85  4354.7  354.24
  4407.2  353.64  4444.9  352.28    4565  350.11  4685.1  349.21  4755.1  347.93
  4815.1  348.69  4875.1  348.72  4895.2  347.78  4955.2  348.45  4985.2  346.19
  4995.2  343.75  4997.8  342.54  5000.5  342.04  5003.8  342.54  5005.8  343.48
  5015.2  345.11  5035.2  350.97  5045.2  352.84  5055.2  353.61  5105.2  355.49
  5295.3  359.05  5345.3  360.54  5401.1  360.25  5415.3  360.01  5441.4  360.86
#Mann= 4 ,-1 , 0
    3900     .05       0  4997.8     .03       0  5003.8     .05       0
  5401.1     .08       0
Bank Sta=4997.8,5003.8
XS Rating Curve= 0 ,0
Exp/Cntr=0.3,0.1

Type RM Length L Ch R = 1 ,15201   ,1057,1057,1057
BEGIN DESCRIPTION:
RED BANK CREEK 28.0
END DESCRIPTION:
XS GIS Cut Line= 3
      3603920.82     10353904.63      3603303.08      10354602.1
      3603067.65     10354927.45
#Sta/Elev= 30
  4068.3  355.21  4299.1  352.09  4426.2  348.35  4660.4  346.53  4695.6  345.91
    4724  343.55  4748.4   343.4  4766.7  346.07  4809.3  345.44  4837.8  343.06
  4851.2  344.03  4875.1  345.72    4908  346.49  4915.5  344.99  4922.2  345.75
    4944  344.12  4950.7  344.92  4958.2  343.81  4979.1  344.39  4990.3   342.8
  4993.1   342.3  4996.3   342.8  5001.2  343.02  5008.1   343.4  5028.8  344.24
  5036.5  346.59  5043.5  347.05  5119.6  349.77  5185.8  352.57  5401.6  357.82
#Mann= 9 ,-1 , 0
  4068.3     .05       0  4748.4     .16       0  4851.2     .08       0
  4875.1     .16       0  4990.3     .07       0  4996.3     .16       0
  5001.2     .05       0  5008.1     .16       0  5119.6     .05       0
Bank Sta=4990.3,4996.3
XS Rating Curve= 0 ,0
Exp/Cntr=0.3,0.1

Type RM Length L Ch R = 1 ,14144   ,513,513,513
BEGIN DESCRIPTION:
RED BANK CREEK 27.0
END DESCRIPTION:
XS GIS Cut Line= 3
      3603760.76     10353644.58      3603059.22     10354258.37
      3602858.27     10354867.63
#Sta/Elev= 30
  4536.7   352.3  4583.4  351.45  4703.9  352.95  4732.4  352.03  4774.2  351.93
  4838.7  349.86  4845.4  350.24  4859.1  349.15  4873.8  347.81  4880.5   347.9
  4894.7     346  4902.3  343.66  4916.6  342.49  4991.4  342.28  4994.1  341.78
  4997.4  342.28  5051.3  344.32  5065.6  342.91  5100.7  343.59  5129.2  343.13
  5178.5  343.71  5462.3   353.5  5503.1  354.03  5603.6   356.9  5862.9  360.27
  5967.2  360.99  5984.7   360.5    5990  361.08  6085.2  362.09  6110.4  361.74
#Mann= 4 ,-1 , 0
  4536.7     .05       0  4859.1     .16       0  4991.4     .07       0
  4997.4     .16       0
Bank Sta=4991.4,4997.4
XS Rating Curve= 0 ,0
Exp/Cntr=0.3,0.1

Type RM Length L Ch R = 1 ,13631   ,510,510,510
BEGIN DESCRIPTION:
RED BANK CREEK 25.0
END DESCRIPTION:
XS GIS Cut Line= 3
      3603734.66     10353540.44      3603092.11     10353641.64
      3602692.09     10353741.65
#Sta/Elev= 30
  4359.1  351.47  4392.1  351.95  4452.8  350.99  4493.3  351.79  4574.3  350.46
  4658.2  350.27  4720.7  347.45  4726.1   346.3  4746.4  343.61  4756.5  342.88
  4783.2  342.54  4807.1  343.04  4861.5  343.04  4943.7  342.48  4996.5  342.19
  4999.2  341.69  5002.5  342.19  5061.1  343.07  5068.8  343.56  5081.7   343.2
  5102.3  343.66  5133.3  345.59  5192.5  348.02  5205.4  349.12  5238.9   350.8
  5267.3   351.7  5287.9  353.15  5339.4  354.68  5403.8  357.64  5421.9   357.8
#Mann= 5 ,-1 , 0
  4359.1     .05       0  4861.5      .1       0  4943.7     .16       0
  4996.5     .07       0  5002.5     .16       0
Bank Sta=4996.5,5002.5
XS Rating Curve= 0 ,0
Exp/Cntr=0.3,0.1

Type RM Length L Ch R = 1 ,13121   ,886,886,886
BEGIN DESCRIPTION:
RED BANK CREEK 24.0
END DESCRIPTION:
XS GIS Cut Line= 4
      3604249.18     10353033.44      3603992.28     10353154.25
      3603192.11     10353191.64      3602392.08     10353341.65
#Sta/Elev= 30
  3930.1  355.69  4100.1  352.95  4196.9  352.44  4274.2  350.59  4394.4  348.99
  4464.4   350.3  4479.5  349.81  4484.5  350.49  4524.5  348.26  4594.6  346.81
  4794.8  345.35  4864.9  343.16    4952  342.19  4954.7  341.69    4958  342.19
  5162.9  342.89  5238.9  343.05  5256.7  342.34  5320.3  349.74  5419.5  353.66
  5424.5  353.21    5472  354.91  5477.1  354.24  5529.7  357.19  5562.5  358.25
  5659.2  361.43  5692.5  362.79  5706.9  362.58  5760.5  365.04    5829  367.66
#Mann= 7 ,-1 , 0
  3930.1     .05       0    4952     .03       0    4958     .05       0
  5162.9      .1       0  5562.5     .16       0  5659.2      .1       0
  5760.5     .05       0
Bank Sta=4952,4958
XS Rating Curve= 0 ,0
Exp/Cntr=0.3,0.1

Type RM Length L Ch R = 1 ,12235   ,26,26,26
BEGIN DESCRIPTION:
RED BANK CREEK 23.02
END DESCRIPTION:
XS GIS Cut Line= 6
       3603515.7     10352096.72      3603112.13     10352327.03
      3603025.76     10352555.33      3602907.92     10353164.27
      3602784.23     10353230.46      3602451.15     10353298.81
#Sta/Elev= 30
    4511  343.09  4532.3  341.98    4571  343.67  4659.8  344.63  4754.1  343.82
  4770.7   342.1  4789.8  341.94  4792.6  341.44  4795.8  341.94  4842.8  342.11
  4859.4  343.06  4862.7  342.33  4887.6   342.2    5016  342.12  5051.5  342.71
  5197.1  342.16  5396.9  342.21  5481.2  342.49    5660  342.07  5852.7  342.63
    5862   344.5    5869   347.3  5884.7  349.82  5918.7  352.24    5973  354.71
  5978.7  354.37  6131.9  359.05    6213  361.59  6314.7  364.98  6324.4  365.28
#Mann= 9 ,-1 , 0
    4511     .05       0  4789.8     .03       0  4795.8     .05       0
  5197.1      .1       0  5396.9     .05       0  5481.2      .1       0
  6131.9     .16       0    6213      .1       0  6314.7     .05       0
Bank Sta=4789.8,4795.8
XS Rating Curve= 0 ,0
Exp/Cntr=0.3,0.1

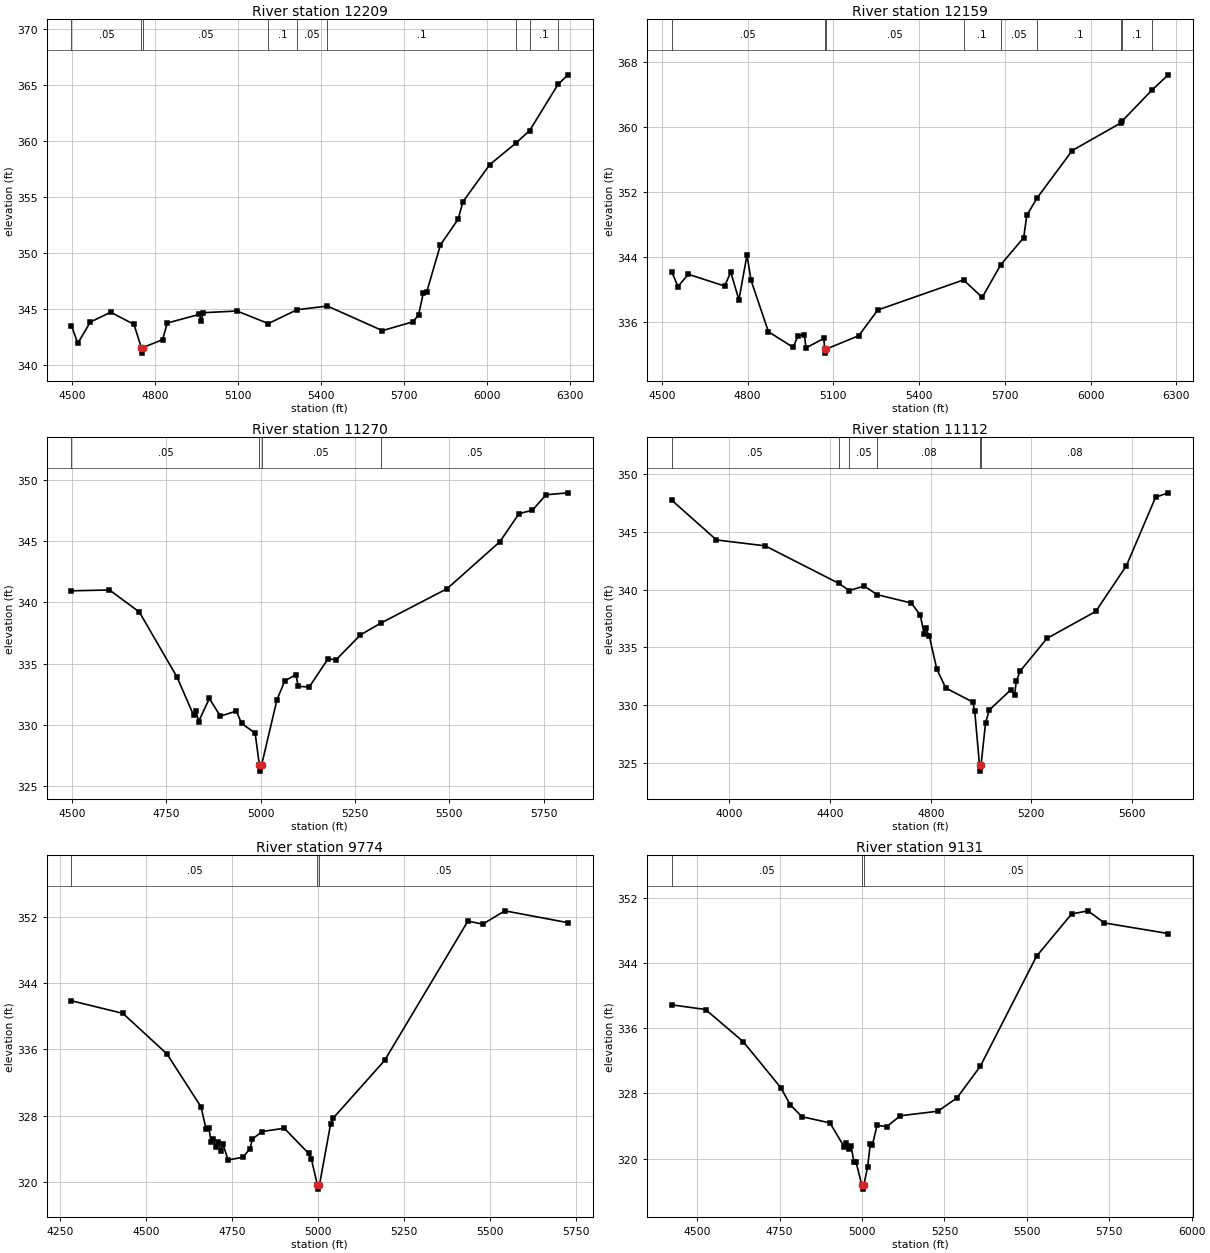
Type RM Length L Ch R = 1 ,12209   ,50,50,50
BEGIN DESCRIPTION:
RED BANK CREEK 23.01
END DESCRIPTION:
XS GIS Cut Line= 6
      3603506.19     10352086.29      3603096.39     10352302.26
      3602951.25     10352740.46       3602895.7     10353080.04
        3602795.     10353181.43      3602427.07      10353268.9
#Sta/Elev= 30
  4498.5  343.51  4521.1  341.92  4566.6  343.83  4640.3   344.7  4724.4  343.62
  4750.9  341.55  4753.7  341.05  4756.9  341.55  4827.7  342.25  4844.9  343.74
  4960.7  344.51  4967.4   343.9  4975.3  344.66  5096.8  344.81  5210.3  343.69
  5314.3  344.93    5424  345.25  5622.6  343.06  5733.7  343.85  5753.8  344.49
  5770.7  346.44  5783.2  346.54  5832.6  350.72  5896.3     353  5913.8  354.57
  6010.8  357.88  6104.6  359.79    6155  360.92  6257.5  365.04  6293.5   365.9
#Mann= 9 ,-1 , 0
  4498.5     .05       0  4750.9     .03       0  4756.9     .05       0
  5210.3      .1       0  5314.3     .05       0    5424      .1       0
  6104.6     .16       0    6155      .1       0  6257.5     .05       0
Bank Sta=4750.9,4756.9
XS Rating Curve= 0 ,0
Exp/Cntr=0.3,0.1

Type RM Length L Ch R = 1 ,12159   ,889,889,889
BEGIN DESCRIPTION:
RED BANK CREEK 23.0
END DESCRIPTION:
XS GIS Cut Line= 6
      3603368.13     10351986.49      3603054.21     10352275.35
      3602963.06     10352465.46      3602870.61     10352936.81
      3602787.28     10353146.45      3602407.07      10353244.1
#Sta/Elev= 30
  4535.1  342.14  4556.8  340.33  4592.7  341.85  4719.8   340.4  4741.4  342.11
  4769.8   338.7  4798.2  344.23  4812.3   341.1  4873.1  334.78  4959.8  332.84
  4976.3   334.3  4998.9  334.36  5004.5  332.79  5066.9  333.95  5069.4  332.64
  5072.2  332.14  5075.4  332.64  5189.1  334.29  5255.4  337.45  5555.3  341.15
  5620.7     339  5685.4  343.02  5765.6  346.35  5776.5  349.09  5812.3  351.23
  5935.5  357.08  6104.5  360.46    6110  360.71    6213  364.48  6271.1   366.4
#Mann= 9 ,-1 , 0
  4535.1     .05       0  5069.4     .03       0  5075.4     .05       0
  5555.3      .1       0  5685.4     .05       0  5812.3      .1       0
  6104.5     .16       0    6110      .1       0    6213     .05       0
Bank Sta=5069.4,5075.4
XS Rating Curve= 0 ,0
Exp/Cntr=0.3,0.1

Type RM Length L Ch R = 1 ,11270   ,158,158,158
BEGIN DESCRIPTION:
RED BANK CREEK 21.0
END DESCRIPTION:
XS GIS Cut Line= 3
      3603252.47     10351983.23      3602620.64      10351512.6
      3602105.58     10351395.73
#Sta/Elev= 30
  4498.3  340.95  4598.9  341.02  4678.1  339.22  4778.2   333.9  4822.1  330.78
  4828.3  331.13  4835.4  330.28  4863.7  332.16  4892.9  330.72  4935.2  331.13
  4949.2  330.12  4985.1  329.34  4996.3  326.73    4999  326.23  5002.3  326.73
  5043.1  332.07  5063.9   333.6  5093.1  334.11  5099.4  333.15  5128.6   333.1
  5178.6  335.41  5199.5  335.31  5264.1  337.35  5318.6  338.32  5494.3  341.13
  5633.9  344.96  5684.6  347.25  5720.1  347.53  5756.3  348.79  5814.3  348.95
#Mann= 4 ,-1 , 0
  4498.3     .05       0  4996.3     .03       0  5002.3     .05       0
  5318.6     .05       0
Bank Sta=4996.3,5002.3
XS Rating Curve= 0 ,0
Exp/Cntr=0.3,0.1

Type RM Length L Ch R = 1 ,11112   ,1338,1338,1338
BEGIN DESCRIPTION:
RED BANK CREEK 20.0
END DESCRIPTION:
XS GIS Cut Line= 2
      3603948.73     10352261.27      3602332.04     10351130.67
#Sta/Elev= 30
  3771.1  347.74  3948.8   344.3  4142.4  343.79  4434.2  340.55  4476.6  339.92
  4535.7  340.31  4587.9  339.56  4723.2  338.84  4758.9  337.77  4773.7  336.18
  4779.8  336.66  4794.7  335.95  4824.3  333.12  4860.1  331.48  4967.3  330.27
    4975  329.49    4994  324.79  4996.7  324.29    5000  324.79  5017.9  328.44
  5032.7  329.58  5119.1  331.34  5133.7  330.91    5140  332.05  5154.8  332.93
  5262.1  335.78  5455.7  338.11  5577.8  342.07  5693.7     348  5743.9  348.38
#Mann= 6 ,-1 , 0
  3771.1     .05       0  4434.2     .08       0  4476.6     .05       0
  4587.9     .08       0    4994     .07       0    5000     .08       0
Bank Sta=4994,5000
XS Rating Curve= 0 ,0
Exp/Cntr=0.3,0.1

Type RM Length L Ch R = 1 ,9774    ,643,643,643
BEGIN DESCRIPTION:
RED BANK CREEK 18.0
END DESCRIPTION:
XS GIS Cut Line= 3
      3603951.74     10351491.86      3603704.12     10351182.21
      3603056.85     10350358.34
#Sta/Elev= 30
  4282.1  341.86  4431.6  340.34  4559.7  335.46  4658.9  329.08  4673.4  326.44
  4682.1  326.49  4687.8  324.88  4694.2  325.19  4702.3  324.22  4708.6  324.86
  4716.7  323.81  4723.1  324.55  4737.5  322.67  4780.9     323  4801.7  324.05
    4808  325.19  4836.9   326.1  4901.1   326.5  4971.8  323.47  4979.7  322.82
  4997.5  319.66  5000.3  319.16  5003.5  319.66  5035.8     327  5043.9  327.74
    5193  334.67  5435.2  351.46  5478.6   351.1  5542.8   352.7  5726.3  351.27
#Mann= 3 ,-1 , 0
  4282.1     .05       0  4997.5     .03       0  5003.5     .05       0
Bank Sta=4997.5,5003.5
XS Rating Curve= 0 ,0
Exp/Cntr=0.3,0.1

Type RM Length L Ch R = 1 ,9131    ,689,689,689
BEGIN DESCRIPTION:
RED BANK CREEK 17.0
END DESCRIPTION:
XS GIS Cut Line= 3
      3604359.69       10351188.       3603761.9     10350418.38
      3603411.91     10350018.39
#Sta/Elev= 30
  4422.9  338.89  4525.4  338.32  4639.5  334.37  4753.5  328.72  4782.5   326.6
  4817.8  325.14  4902.8  324.38  4946.3  321.41  4952.6  321.87  4960.8  321.17
  4967.1   321.5  4975.2  319.62  4981.6  319.61  4999.4  316.74  5002.1  316.24
  5005.4  316.74  5016.9  318.93    5025  321.78  5031.3  321.64  5045.8  324.09
  5074.8  323.92  5116.4  325.26  5230.5  325.82  5288.4  327.47    5359  331.35
  5529.4  344.87  5635.7  350.06  5685.4  350.45  5735.3  348.96  5928.9  347.66
#Mann= 3 ,-1 , 0
  4422.9     .05       0  4999.4     .03       0  5005.4     .05       0
Bank Sta=4999.4,5005.4
XS Rating Curve= 0 ,0
Exp/Cntr=0.3,0.1

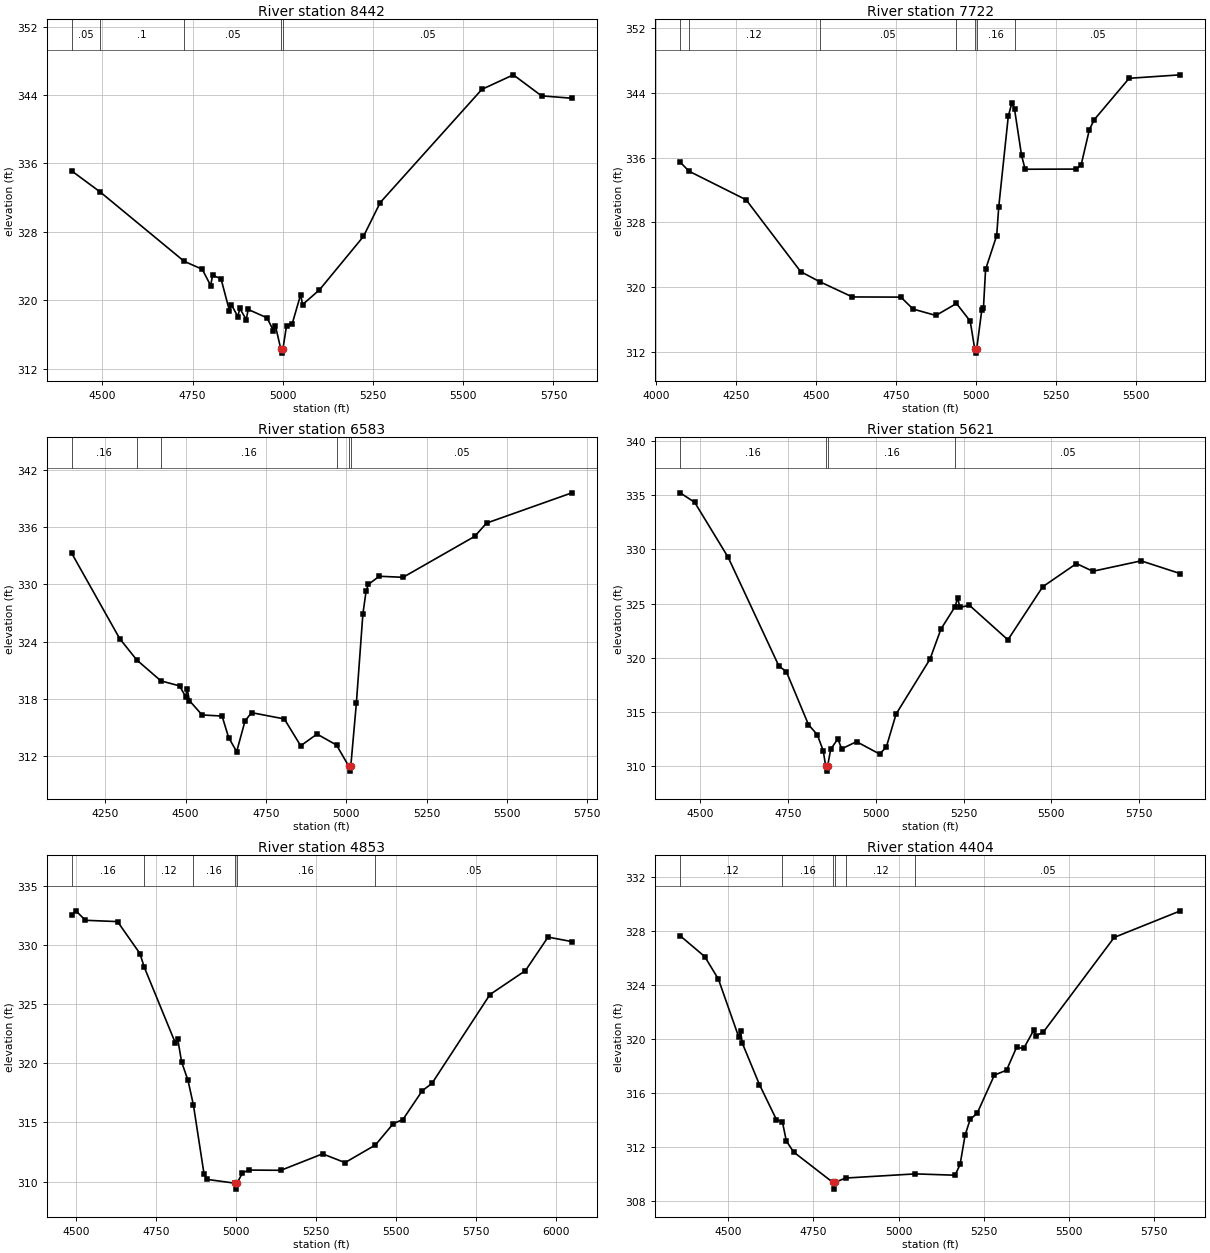
Type RM Length L Ch R = 1 ,8442    ,720,720,720
BEGIN DESCRIPTION:
RED BANK CREEK 15.0
END DESCRIPTION:
XS GIS Cut Line= 3
      3604906.53     10350493.54      3603968.84      10350078.8
      3603668.82     10349878.78
#Sta/Elev= 30
  4415.2  335.13  4494.6  332.65  4726.6  324.56  4776.9  323.62  4800.2  321.72
  4805.6  322.91  4828.9  322.52  4852.2  318.78  4857.7  319.47  4875.5  318.09
    4881  319.04  4898.8  317.74  4904.3  318.92  4956.4  317.94  4974.2  316.44
  4979.6  317.01  4994.5  314.31  4997.2  313.81  5000.5  314.31  5010.5  317.03
  5026.2  317.25  5049.5  320.64    5055  319.49  5101.6  321.21  5223.5  327.46
  5270.1  331.43  5551.7  344.67  5638.8  346.37  5716.9  343.91  5801.1  343.63
#Mann= 5 ,-1 , 0
  4415.2     .05       0  4494.6      .1       0  4726.6     .05       0
  4994.5     .03       0  5000.5     .05       0
Bank Sta=4994.5,5000.5
XS Rating Curve= 0 ,0
Exp/Cntr=0.3,0.1

Type RM Length L Ch R = 1 ,7722    ,1139,1139,1139
BEGIN DESCRIPTION:
RED BANK CREEK 14.0
END DESCRIPTION:
XS GIS Cut Line= 3
      3605187.83     10349944.95      3604357.38     10349695.81
      3603680.84     10349528.27
#Sta/Elev= 30
    4075  335.42    4103   334.3  4281.2  330.77  4451.8  321.88  4510.7  320.65
  4613.4  318.75    4765  318.73  4803.2  317.25  4874.6  316.46  4938.9  317.94
  4981.8  315.76    4996   312.3  4998.7   311.8    5002   312.3  5018.1  317.15
  5023.2  317.38  5029.9  322.16  5064.6  326.34  5071.1  329.93  5100.9  341.11
  5112.3  342.77  5120.4  341.98  5142.3  336.28  5153.5  334.55  5313.1  334.57
  5328.6  335.08  5354.5  339.46  5369.8  340.69  5478.7   345.8    5639  346.23
#Mann= 7 ,-1 , 0
    4075     .16       0    4103     .12       0  4510.7     .05       0
  4938.9     .16       0    4996     .07       0    5002     .16       0
  5120.4     .05       0
Bank Sta=4996,5002
XS Rating Curve= 0 ,0
Exp/Cntr=0.3,0.1

Type RM Length L Ch R = 1 ,6583    ,962,962,962
BEGIN DESCRIPTION:
RED BANK CREEK 12.0
END DESCRIPTION:
XS GIS Cut Line= 3
      3605361.47     10349306.06      3604236.43     10349083.83
      3603826.95     10349056.07
#Sta/Elev= 30
  4145.2  333.27  4294.7   324.3  4347.9  322.06  4422.8  319.87  4480.9  319.34
  4499.8  318.22  4504.9  319.02  4511.5   317.8  4551.1  316.29  4613.4  316.17
  4633.8  313.91  4658.8  312.44  4684.8  315.65    4705  316.53  4807.1  315.87
  4858.1  313.05    4909  314.28  4969.6  313.13    5008  310.89  5010.7  310.39
    5014  310.89  5031.4  317.51  5051.7  326.89  5061.9  329.34  5069.1     330
  5102.7  330.85  5176.7  330.74  5399.9  335.04  5436.6  336.43  5702.4  339.61
#Mann= 6 ,-1 , 0
  4145.2     .16       0  4347.9     .12       0  4422.8     .16       0
  4969.6     .05       0    5008     .03       0    5014     .05       0
Bank Sta=5008,5014
XS Rating Curve= 0 ,0
Exp/Cntr=0.3,0.1

Type RM Length L Ch R = 1 ,5621    ,768,768,768
BEGIN DESCRIPTION:
RED BANK CREEK 10.0
END DESCRIPTION:
XS GIS Cut Line= 3
      3605479.51     10348868.56      3604942.11     10348691.64
      3604118.33     10348444.93
#Sta/Elev= 30
  4442.3  335.23  4483.7  334.35    4579  329.28  4723.8  319.23  4744.9  318.73
    4808  313.83  4833.3  312.89  4850.2   311.4  4856.8  310.04  4859.5  309.54
  4862.8  310.04  4871.2  311.55  4891.6  312.51  4902.8   311.6  4944.9  312.26
  5010.7  311.12  5029.8  311.76  5057.7  314.81  5154.2  319.87  5185.5  322.65
  5225.7  324.72  5233.6  325.56  5238.8  324.65  5266.7  324.85  5376.4  321.66
  5475.6  326.56  5571.8   328.7  5618.4  327.99    5756  328.95    5868  327.77
#Mann= 4 ,-1 , 0
  4442.3     .16       0  4856.8     .07       0  4862.8     .16       0
  5225.7     .05       0
Bank Sta=4856.8,4862.8
XS Rating Curve= 0 ,0
Exp/Cntr=0.3,0.1

Type RM Length L Ch R = 1 ,4853    ,449,449,449
BEGIN DESCRIPTION:
RED BANK CREEK 9.0
END DESCRIPTION:
XS GIS Cut Line= 3
      3605585.18     10348143.03       3604653.1     10348181.06
       3604028.1     10348104.67
#Sta/Elev= 30
  4486.1  332.51  4499.2  332.88  4529.2  332.08  4629.3  331.97  4699.3  329.27
  4712.5  328.14  4809.4  321.75  4817.2  322.07  4829.5  320.11  4849.5  318.55
  4866.4  316.47  4899.5  310.65  4909.5  310.19  4996.6  309.87  4999.3  309.37
  5002.6  309.87  5019.6  310.74  5039.6  310.98  5139.7  310.96  5269.8  312.35
  5339.9  311.61  5434.9   313.1  5490.5   314.9  5520.7  315.25  5581.1  317.68
  5611.4   318.3  5792.7  325.81  5903.5  327.83    5974  330.66  6048.6  330.28
#Mann= 6 ,-1 , 0
  4486.1     .16       0  4712.5     .12       0  4866.4     .16       0
  4996.6     .07       0  5002.6     .16       0  5434.9     .05       0
Bank Sta=4996.6,5002.6
XS Rating Curve= 0 ,0
Exp/Cntr=0.3,0.1

Type RM Length L Ch R = 1 ,4404    ,54,54,54
BEGIN DESCRIPTION:
Mapping XS b8da9a95
END DESCRIPTION:
XS GIS Cut Line= 4
      3605433.92     10347713.88      3604954.74      10347748.6
      3604482.52     10348088.88      3604078.03     10348083.67
#Sta/Elev= 30
  4359.4  327.67  4431.4  326.13  4471.5  324.46  4531.3  320.16  4536.4   320.6
  4541.7  319.71  4591.8  316.65  4641.9  314.04  4659.1   313.9  4670.7  312.47
  4692.1  311.65  4807.1   309.4  4809.8   308.9  4813.1   309.4  4844.4  309.72
  5049.2  310.03  5165.6  309.93  5180.3  310.73    5195   312.9  5209.7  314.06
  5230.6  314.53  5280.9  317.35  5316.5  317.71    5346  319.41  5366.8  319.32
  5396.3  320.68  5402.4  320.25  5424.6  320.54  5632.3  327.55  5826.4  329.52
#Mann= 6 ,-1 , 0
  4359.4     .12       0  4659.1     .16       0  4807.1     .07       0
  4813.1     .16       0  4844.4     .12       0  5049.2     .05       0
Bank Sta=4807.1,4813.1
XS Rating Curve= 0 ,0
Exp/Cntr=0.3,0.1