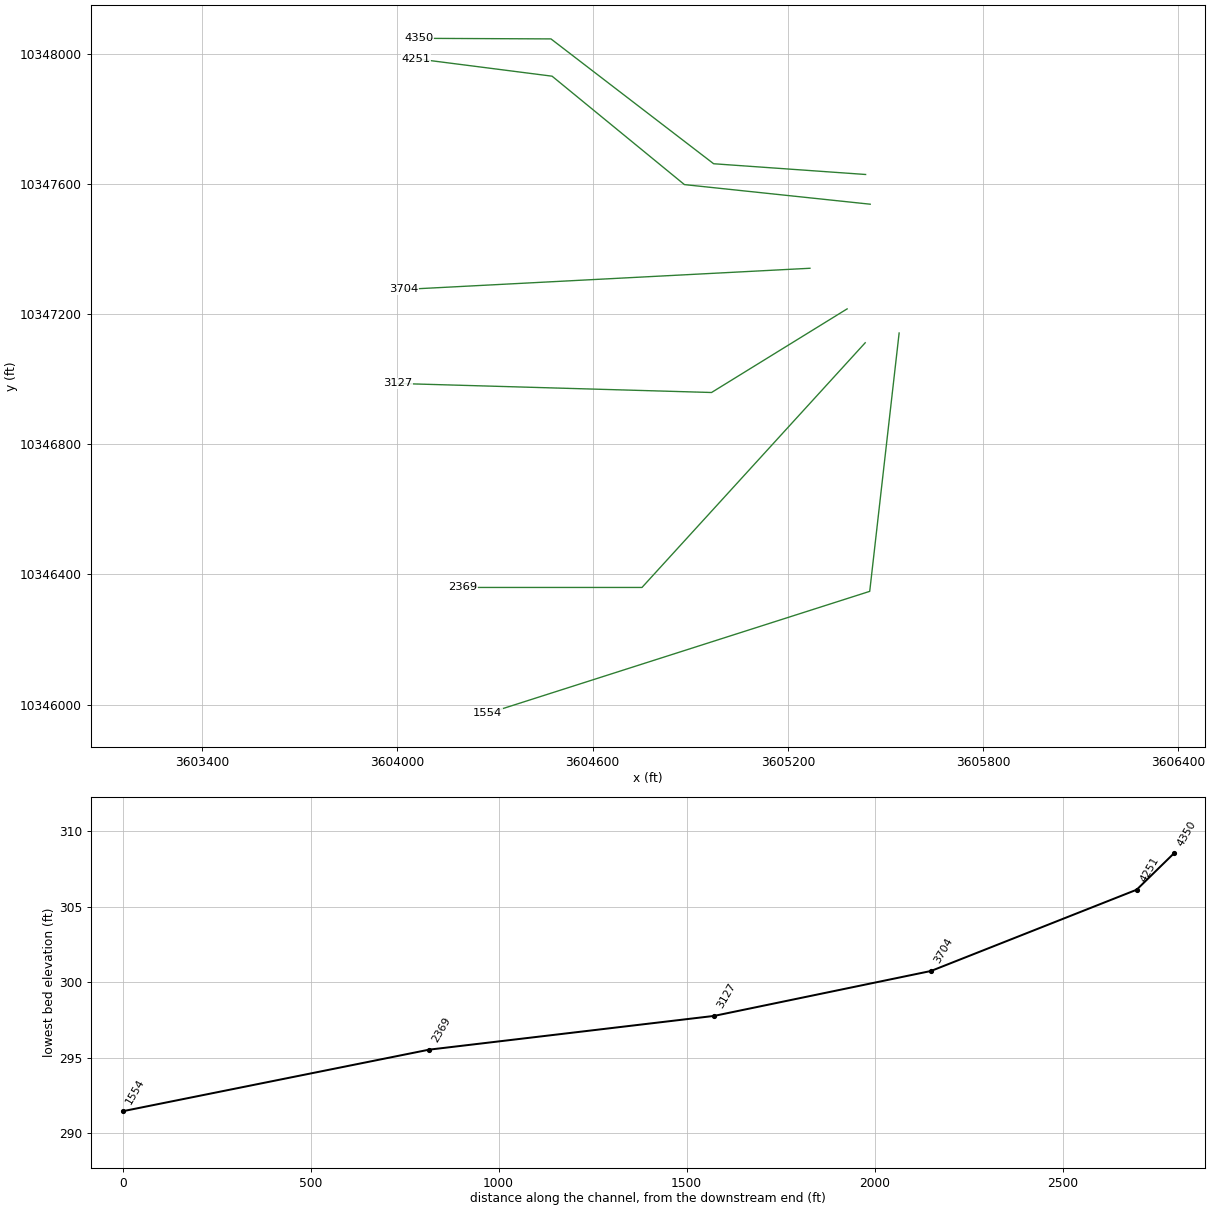
HEC-RAS study RED BANK CREEK.prj: RED BANK CREEK Base Level Engineering

--- RED BANK CREEK.g01 (geometry) --- (continued)

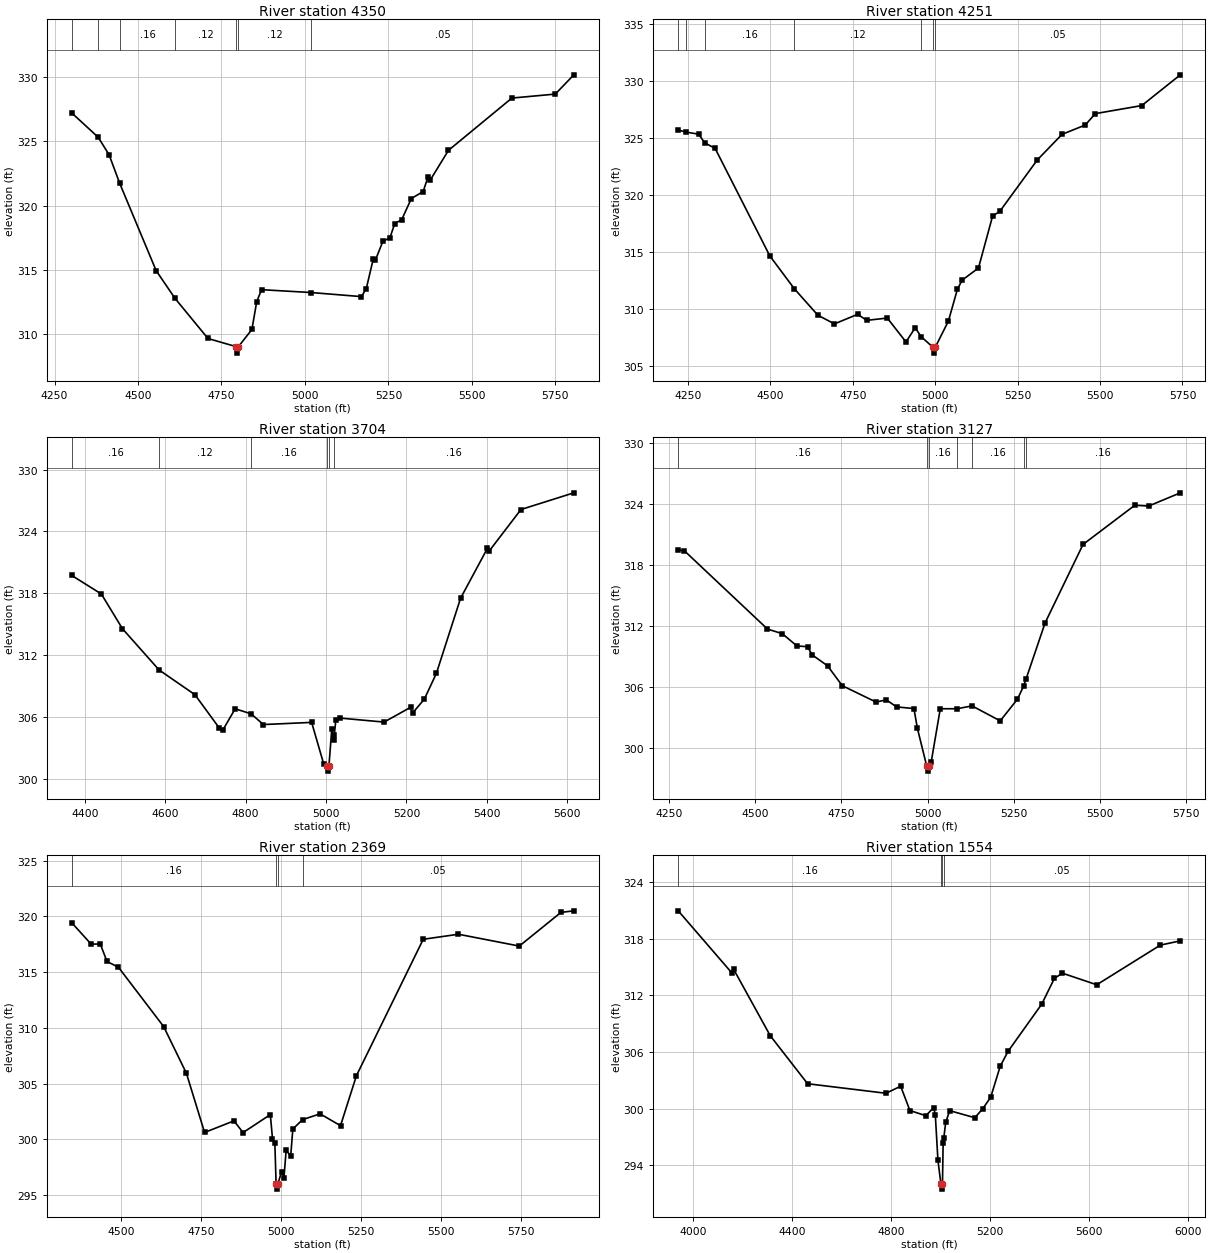
Type RM Length L Ch R = 1 ,4350    ,99,99,99
BEGIN DESCRIPTION:
Mapping XS 981d1d73
END DESCRIPTION:
XS GIS Cut Line= 4
      3605439.08     10347628.81      3604972.11     10347661.79
      3604472.11     10348045.47      3604066.49     10348047.21
#Sta/Elev= 30
  4301.5  327.21  4380.6  325.32  4413.2  323.96  4445.1  321.73  4554.3  314.93
  4610.9  312.77  4709.5  309.65  4794.6  309.01  4797.3  308.51  4800.6  309.01
  4841.1  310.35  4855.6  312.53  4870.2  313.45  5017.6  313.23  5169.3  312.91
  5183.8  313.54  5204.6  315.84  5210.9  315.74  5233.6  317.23  5254.4  317.48
    5269   318.6  5289.8   318.9  5318.8  320.55  5354.1  321.09  5368.7  322.24
    5375  321.97  5429.9   324.3  5619.9  328.37  5749.9  328.68  5805.5  330.18
#Mann= 7 ,-1 , 0
  4301.5     .16       0  4380.6     .12       0  4445.1     .16       0
  4610.9     .12       0  4794.6     .07       0  4800.6     .12       0
  5017.6     .05       0
Bank Sta=4794.6,4800.6
XS Rating Curve= 0 ,0
Exp/Cntr=0.3,0.1

Type RM Length L Ch R = 1 ,4251    ,547,547,547
BEGIN DESCRIPTION:
RED BANK CREEK 7.0
END DESCRIPTION:
XS GIS Cut Line= 4
      3605453.25     10347537.47      3604882.27     10347597.72
      3604475.58     10347930.89      3604056.29      10347984.6
#Sta/Elev= 30
  4220.9  325.71  4244.1  325.53  4282.4  325.35  4301.5  324.58  4332.7   324.1
  4498.7  314.65  4573.1  311.76  4644.4  309.44  4694.7  308.68    4765  309.52
  4792.6  308.99  4854.9  309.19  4911.6  307.09  4939.6  308.35  4956.9  307.57
  4994.1  306.61  4996.8  306.11  5000.1  306.61  5040.1  308.92  5067.4  311.71
  5081.8  312.52  5131.4  313.59  5174.3  318.16    5196  318.56    5310  323.09
  5384.8  325.33  5455.3  326.15  5485.6  327.15  5626.7  327.86  5743.5  330.56
#Mann= 7 ,-1 , 0
  4220.9     .16       0  4244.1     .12       0  4301.5     .16       0
  4573.1     .12       0  4956.9     .05       0  4994.1    .035       0
  5000.1     .05       0
Bank Sta=4994.1,5000.1
XS Rating Curve= 0 ,0
Exp/Cntr=0.3,0.1

Type RM Length L Ch R = 1 ,3704    ,577,577,577
BEGIN DESCRIPTION:
Mapping XS 0ae0ddc1
END DESCRIPTION:
XS GIS Cut Line= 2
      3605268.07     10347340.61      3604020.67     10347275.51
#Sta/Elev= 30
  4367.4  319.73    4441  317.93  4493.5  314.56  4584.6  310.56  4673.8  308.16
  4733.9  304.95  4743.9  304.77  4773.9  306.79  4813.7   306.3    4844  305.26
  4964.2  305.47  4994.2  301.43  5001.2  301.24    5004  300.74  5007.2  301.24
  5014.2  304.79  5019.2  303.75  5020.5  304.24  5024.3  305.67  5034.3  305.89
  5144.4   305.5  5210.2  306.93  5215.2  306.37  5244.6  307.73  5274.6  310.24
  5334.7  317.52  5401.3  322.35  5406.3  322.12  5484.9  326.13  5616.5  327.75
#Mann= 6 ,-1 , 0
  4367.4     .16       0  4584.6     .12       0  4813.7     .16       0
  5001.2     .07       0  5007.2     .16       0  5020.5     .16       0
Bank Sta=5001.2,5007.2
XS Rating Curve= 0 ,0
Exp/Cntr=0.3,0.1

Type RM Length L Ch R = 1 ,3127    ,758,758,758
BEGIN DESCRIPTION:
RED BANK CREEK 5.0
END DESCRIPTION:
XS GIS Cut Line= 3
      3605382.27     10347215.78       3604965.6     10346958.83
      3604000.33     10346986.61
#Sta/Elev= 30
  4277.4  319.51    4295  319.43  4536.1  311.73  4578.9  311.28  4621.4  310.07
  4652.2     310  4665.3   309.2  4710.2  308.12  4752.7  306.17  4850.5  304.56
  4880.5  304.77  4910.5  304.08  4960.5  303.92  4970.5  301.99  4997.5  298.27
  5000.3  297.77  5003.5  298.27  5010.5  298.65  5036.9   303.9  5085.5   303.9
    5129  304.18  5210.6  302.71  5260.6  304.84  5278.1  306.11  5285.3   306.8
  5340.7  312.34  5450.7  320.05  5600.8   323.9  5640.8  323.82  5732.6  325.12
#Mann= 7 ,-1 , 0
  4277.4     .16       0  4997.5     .07       0  5003.5     .16       0
  5085.5     .12       0    5129     .16       0  5278.1     .12       0
  5285.3     .16       0
Bank Sta=4997.5,5003.5
XS Rating Curve= 0 ,0
Exp/Cntr=0.3,0.1

Type RM Length L Ch R = 1 ,2369    ,815,815,815
BEGIN DESCRIPTION:
RED BANK CREEK 2.0
END DESCRIPTION:
XS GIS Cut Line= 3
      3605437.82     10347111.61      3604751.83      10346359.7
      3604201.84      10346359.7
#Sta/Elev= 30
  4346.2  319.42  4406.8   317.5  4435.2  317.52  4456.2  315.95    4492  315.43
  4633.2  310.11  4704.1  305.93  4760.9  300.62  4852.7  301.66  4881.1  300.61
  4966.2  302.22    4973  300.07  4980.4  299.64  4984.2  296.04  4986.9  295.54
  4990.2  296.04  5001.4  297.12  5008.8  296.58  5015.6  299.02  5029.8  298.51
  5036.5  300.93  5066.9  301.77  5121.6  302.29  5185.4  301.23  5235.1  305.71
  5443.7  317.94  5553.7  318.39  5743.7  317.33  5873.7  320.35    5914  320.49
#Mann= 4 ,-1 , 0
  4346.2     .16       0  4984.2     .07       0  4990.2     .16       0
  5066.9     .05       0
Bank Sta=4984.2,4990.2
XS Rating Curve= 0 ,0
Exp/Cntr=0.3,0.1

Type RM Length L Ch R = 1 ,1554    ,0,0,0
BEGIN DESCRIPTION:
RED BANK CREEK 1.0
END DESCRIPTION:
XS GIS Cut Line= 3
      3605542.11     10347141.65      3605451.71     10346347.72
      3604278.12     10345972.73
#Sta/Elev= 30
  3939.3  320.94    4158  314.31    4163  314.77  4311.7  307.71  4462.7  302.63
    4780  301.62  4839.1  302.37  4876.5  299.79  4940.8  299.25    4973   300.1
  4979.4  299.27  4989.9  294.52  5002.2  291.97  5004.9  291.47  5008.2  291.97
  5010.9  296.32  5013.6  296.89  5021.4  298.55  5037.4  299.78  5139.1  299.03
  5171.3  299.99  5203.5  301.21  5241.8  304.48  5273.3  306.05  5409.8  311.06
  5460.9  313.78  5493.1  314.34  5632.3  313.11  5889.7  317.31  5970.4  317.76
#Mann= 4 ,-1 , 0
  3939.3     .16       0  5002.2     .07       0  5008.2     .16       0
  5013.6     .05       0
Bank Sta=5002.2,5008.2
XS Rating Curve= 0 ,0
Exp/Cntr=0.3,0.1

Chan Stop Cuts=-1
Use User Specified Reach Order=0
Composite Channel Slope=5