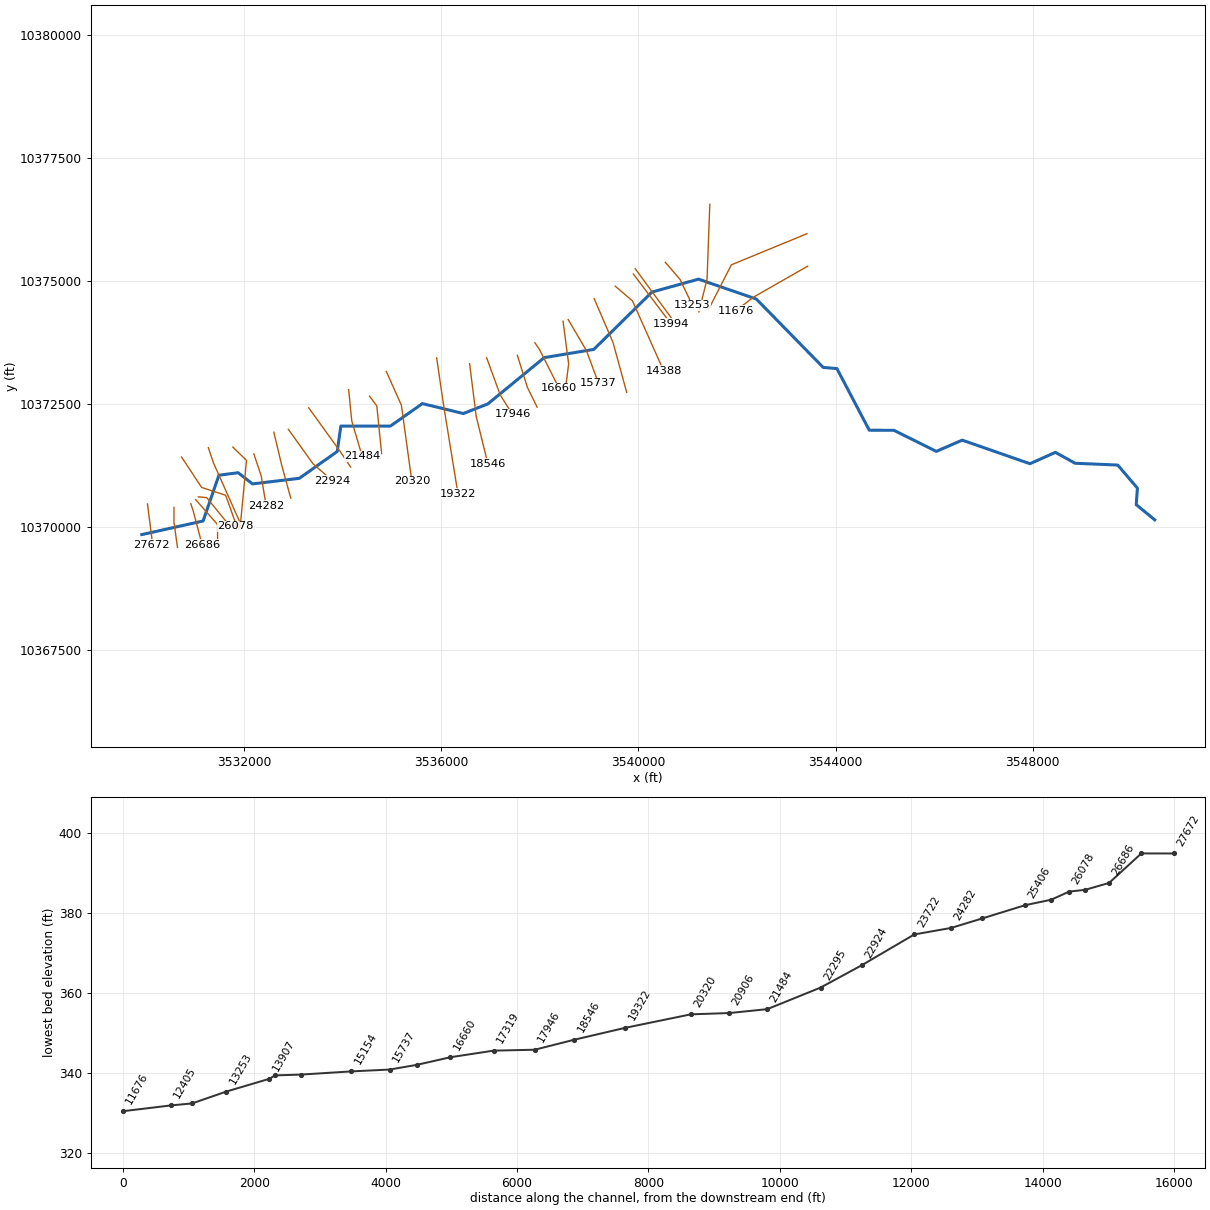
--- REISS CREEK.prj (project) ---

Proj Title=REISS CREEK Base Level Engineering
Current Plan=p01
Default Exp/Contr=0.3,0.1
English Units
Geom File=g01
Flow File=f01
Plan File=p01
Y Axis Title=Elevation
X Axis Title(PF)=Main Channel Distance
X Axis Title(XS)=Station
BEGIN DESCRIPTION:
REISS CREEK
END DESCRIPTION:
DSS Export Rating Curves= 0
DSS Export Rating Curve Sorted= 0
DSS Export Volume Flow Curves= 0
DXF OffsetX= 0
DXF OffsetY= 0
DXF ScaleX= 1
DXF ScaleY= 10

--- REISS CREEK.p01 (plan) ---

Plan Title=Multiple Run
Short Identifier=Multiple
Geom File=g01
Flow File=f01
Subcritical Flow
K Sum by GR= 0
Std Step Tol= 0.01
Critical Tol= 0.01
Num of Std Step Trials= 20
Max Error Tol= 0.3
Flow Tol Ratio= 0.001
Split Flow NTrial= 30
Split Flow Tol= 0.02
Split Flow Ratio= 0.02
Log Output Level= 0
Friction Slope Method= 1
Unsteady Friction Slope Method= 2
Unsteady Bridges Friction Slope Method= 1
Parabolic Critical Depth
Global Vel Dist=  1 , 1 , 1
Global Log Level= 0
CheckData=True
Encroach Param= -1, 0, 0, 0
BEGIN DESCRIPTION:
Multiple Run
END DESCRIPTION:

--- REISS CREEK.f01 (steady flow) ---

Flow Title=Multiple
Program Version=4.10
Number of Profiles= 7
Profile Names=10-year,25-year,50-year,1pct_min,100-year,1pct_plu,500-year
River Rch & RM=REISS CREEK,Reach-1         ,27672
    1067    1490    1844    1666    2254    3048    3358
River Rch & RM=REISS CREEK,Reach-1         ,23722
    1560    2215    2773    2531    3422    4628    5201
River Rch & RM=REISS CREEK,Reach-1         ,18546
    1627    2315    2902    2650    3584    4847    5457
River Rch & RM=REISS CREEK,Reach-1         ,17319
    1772    2526    3169    2896    3917    5297    5973
River Rch & RM=REISS CREEK,Reach-1         ,14388
    1931    2761    3471    3177    4297    5811    6574
River Rch & RM=REISS CREEK,Reach-1         ,12732
    3402    4963    6323    5851    7912   10701   12376
River Rch & RM=REISS CREEK,Reach-1         ,12405
    3675    5372    6852    6346    8583   11607   13452
River Rch & RM=REISS CREEK,Reach-1         ,11676
    3675    5372    6852    6346    8583   11607   13452
River Rch & RM=REISS CREEK,Reach-1         ,8608
    3755    5491    7005    6490    8777   11870   13762
River Rch & RM=REISS CREEK,Reach-1         ,7600
    3931    5758    7355    6821    9225   12475   14493
River Rch & RM=REISS CREEK,Reach-1         ,5985
    4009    5863    7480    6927    9368   12669   14677
River Rch & RM=REISS CREEK,Reach-1         ,1573
    4161    6088    7770    7198    9734   13164   15256
Boundary for River Rch & Prof#=REISS CREEK,Reach-1         , 1
Up Type= 0
Dn Type= 3
Dn Slope=0.00143
Boundary for River Rch & Prof#=REISS CREEK,Reach-1         , 2
Up Type= 0
Dn Type= 3
Dn Slope=0.00143
Boundary for River Rch & Prof#=REISS CREEK,Reach-1         , 3
Up Type= 0
Dn Type= 3
Dn Slope=0.00143
Boundary for River Rch & Prof#=REISS CREEK,Reach-1         , 4
Up Type= 0
Dn Type= 3
Dn Slope=0.00143
Boundary for River Rch & Prof#=REISS CREEK,Reach-1         , 5
Up Type= 0
Dn Type= 3
Dn Slope=0.00143
Boundary for River Rch & Prof#=REISS CREEK,Reach-1         , 6
Up Type= 0
Dn Type= 3
Dn Slope=0.00143
Boundary for River Rch & Prof#=REISS CREEK,Reach-1         , 7
Up Type= 0
Dn Type= 3
Dn Slope=0.00143
DSS Import GetInterval= 0
DSS Import GetPeak= 0
DSS Import FillOption= 0

--- REISS CREEK.g01 (geometry) ---

Geom Title=Existing Conditions
Program Version=4.10

River Reach=REISS CREEK     ,Reach-1
Reach XY= 30
      3529918.19     10369852.14      3531161.39     10370127.36
      3531483.36     10371057.81      3531873.19     10371108.71
      3532164.77     10370881.32      3533115.89     10370995.15
       3533885.9     10371540.41      3533957.36     10372055.15
      3534965.32     10372056.73      3535613.93     10372512.46
      3536444.92     10372310.91      3536940.47     10372505.48
      3538086.79     10373446.68      3539093.27     10373613.28
      3540272.96     10374778.21      3541218.82     10375040.47
      3542392.43     10374636.45      3543750.14     10373247.16
      3544027.91     10373224.24      3544684.89     10371972.16
      3545186.05     10371969.53      3546046.34     10371542.05
      3546571.69     10371770.44      3547946.75     10371291.63
      3548463.42     10371522.18      3548864.94      10371300.7
       3549728.7     10371264.07      3550128.43      10370795.4
      3550104.13     10370460.33      3550480.47     10370150.31

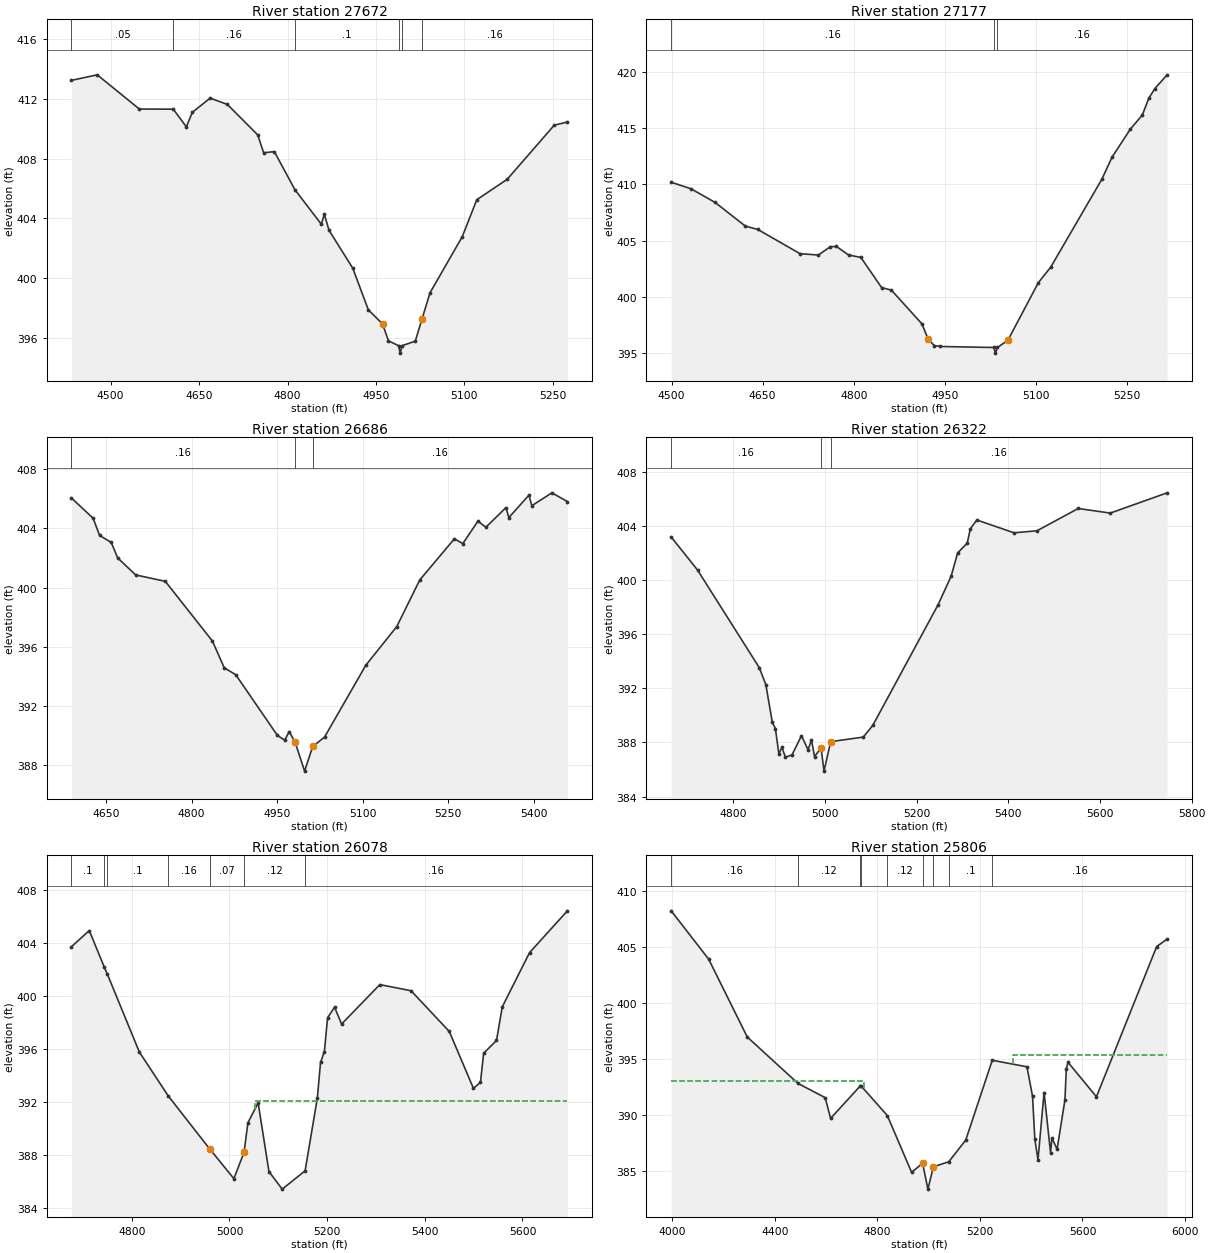
Type RM Length L Ch R = 1 ,27672   ,495,495,495
BEGIN DESCRIPTION:
REISS CREEK 54.0
END DESCRIPTION:
XS GIS Cut Line= 3
      3530033.01     10370474.96       3530120.8     10369789.34
       3530120.8     10369639.35
#Sta/Elev= 30
  4433.5  413.24  4477.2  413.61  4548.6  411.32  4606.2  411.31  4628.4  410.13
  4638.5   411.1  4668.7  412.05  4697.9  411.63  4749.4  409.59  4759.5  408.39
  4777.6  408.47  4812.7  405.91  4857.3  403.61  4862.4  404.28  4870.4   403.2
  4910.7  400.66    4937  397.88  4961.1  396.94  4971.2   395.8  4988.3  395.48
  4991.1  394.98  4994.3  395.48  5016.7  395.78  5028.1  397.27  5041.7  399.02
  5096.4  402.78    5121  405.25  5172.4  406.61  5252.4  410.24  5274.7  410.45
#Mann= 6 ,-1 , 0
  4433.5     .05       0  4606.2     .16       0  4812.7      .1       0
  4988.3     .07       0  4994.3      .1       0  5028.1     .16       0
Bank Sta=4961.1,5028.1
XS Rating Curve= 0 ,0
Exp/Cntr=0.3,0.1

Type RM Length L Ch R = 1 ,27177   ,491,491,491
BEGIN DESCRIPTION:
REISS CREEK 53.0
END DESCRIPTION:
XS GIS Cut Line= 3
       3530570.8     10370404.07       3530570.8     10370104.11
      3530642.11     10369591.61
#Sta/Elev= 30
  4499.2  410.17  4531.6   409.6  4571.6  408.38  4621.6  406.27  4641.6  405.99
  4711.6  403.83  4741.6  403.71  4761.6  404.45  4771.6  404.47  4791.6  403.71
  4811.8   403.5    4846  400.82  4862.2  400.59  4912.6  397.59  4922.8  396.22
  4932.9  395.67    4943  395.59  5030.9   395.5  5033.6     395  5036.9   395.5
  5054.1  396.14  5104.5  401.27  5124.7  402.63  5209.1  410.45  5225.7  412.39
    5256  414.89  5275.7  416.14  5286.3  417.62  5296.4  418.49  5316.6  419.71
#Mann= 3 ,-1 , 0
  4499.2     .16       0  5030.9     .07       0  5036.9     .16       0
Bank Sta=4922.8,5054.1
XS Rating Curve= 0 ,0
Exp/Cntr=0.3,0.1

Type RM Length L Ch R = 1 ,26686   ,364,364,364
BEGIN DESCRIPTION:
REISS CREEK 52.0
END DESCRIPTION:
XS GIS Cut Line= 3
      3530912.92     10370477.73      3530962.93     10370327.72
       3531143.9     10369639.96
#Sta/Elev= 30
  4589.6  406.06  4627.6  404.69  4638.9  403.53  4659.3  403.06  4670.6  402.01
  4702.2  400.86    4754  400.43  4836.7  396.39  4857.4  394.58  4877.5  394.12
  4950.5  390.02  4963.3  389.69  4971.2  390.27  4981.5  389.57  4998.2   387.6
  5012.5  389.27  5033.2   389.9  5105.6  394.76  5159.8  397.37  5200.1  400.52
  5260.7   403.3  5275.6  402.98  5302.1   404.5  5315.9  404.08  5351.1  405.41
  5356.3  404.74  5391.4  406.25  5396.6  405.54  5431.7  406.41  5458.9  405.82
#Mann= 3 , 0 , 0
  4589.6     .16       0  4981.5     .07       0  5012.5     .16       0
Bank Sta=4981.5,5012.5
XS Rating Curve= 0 ,0
Exp/Cntr=0.3,0.1

Type RM Length L Ch R = 1 ,26322   ,244,244,244
BEGIN DESCRIPTION:
REISS CREEK 51.01
END DESCRIPTION:
XS GIS Cut Line= 3
      3531011.09     10370561.85      3531456.39     10370054.05
      3531456.39     10369647.75
#Sta/Elev= 30
  4664.8  403.21  4722.2  400.77  4856.9  393.54  4871.2  392.29  4885.4  389.49
  4892.1  389.03  4899.6  387.16  4906.3  387.64  4913.9  386.92  4928.1  387.07
    4949   388.5  4963.2  387.47  4970.8  388.18  4977.5  386.96  4991.7   387.6
  4998.1  385.88  5012.6  388.06  5083.7   388.4  5104.6  389.27    5247   398.2
  5275.4  400.31  5289.7  402.04  5310.5  402.75  5317.2  403.81  5331.4  404.47
  5412.6  403.52  5462.6  403.67  5552.6  405.32  5622.6  404.98  5746.5  406.48
#Mann= 3 , 0 , 0
  4664.8     .16       0  4991.7     .07       0  5012.6     .16       0
Bank Sta=4991.7,5012.6
XS Rating Curve= 0 ,0
Exp/Cntr=0.3,0.1

Type RM Length L Ch R = 1 ,26078   ,272,272,272
BEGIN DESCRIPTION:
REISS CREEK 51.0
END DESCRIPTION:
XS GIS Cut Line= 4
      3531065.81     10370619.15      3531235.04     10370603.53
        3531677.     10370060.28      3531816.59     10370020.21
#Sta/Elev= 30
  4676.5   403.7    4713  404.91    4744  402.13    4750  401.63  4815.5  395.76
  4874.7  392.45  4959.5  388.46  5009.1  386.22  5029.9  388.21  5037.8  390.43
  5058.7  391.93  5080.9  386.75    5108  385.43  5154.9  386.81    5180   392.3
  5186.5  394.98  5194.4  395.79  5200.9  398.34  5215.2  399.14  5229.6  397.87
  5307.9  400.84  5371.8  400.38  5450.1  397.31  5499.6  393.02    5514  393.48
  5520.5  395.67  5546.8  396.63  5558.6  399.16  5614.5  403.25    5692   406.4
#Mann= 7 ,-1 , 0
  4676.5      .1       0    4744     .16       0    4750      .1       0
  4874.7     .16       0  4959.5     .07       0  5029.9     .12       0
  5154.9     .16       0
#XS Ineff= 2 , 0
                         5052.73          392.07
Permanent Ineff=
       F       F
Bank Sta=4959.5,5029.9
XS Rating Curve= 0 ,0
Exp/Cntr=0.3,0.1

Type RM Length L Ch R = 1 ,25806   ,400,400,400
BEGIN DESCRIPTION:
REISS CREEK 50.0
END DESCRIPTION:
XS GIS Cut Line= 4
      3530725.49     10371427.14      3531132.42     10370809.68
      3531619.24     10370650.84      3531850.65     10370007.46
#Sta/Elev= 30
  3995.2  408.26  4141.5  403.94    4292  396.99  4490.1  392.84  4596.2  391.57
  4617.3  389.72  4733.5  392.63  4735.8  392.63  4838.7  389.97  4933.4   384.9
  4976.3  385.71    4997   383.4  5018.4   385.4  5078.1  385.84  5144.6  387.78
  5248.1  394.91  5383.5  394.33  5405.3  391.69  5414.2  387.86  5426.6  386.03
  5450.2  392.03  5475.6  386.66  5480.9  387.98    5501  386.96  5531.7  391.37
    5537  394.11  5543.5  394.74  5654.6  391.65  5889.7  405.07  5930.5  405.74
#Mann= 9 ,-1 , 0
  3995.2     .16       0  4490.1     .12       0  4733.5     .16       0
  4735.8      .1       0  4838.7     .12       0  4976.3     .07       0
  5018.4     .12       0  5078.1      .1       0  5248.1     .16       0
#XS Ineff= 2 , 0
         4745.74   393.1 5330.97          395.39
Permanent Ineff=
       F       F
Bank Sta=4976.3,5018.4
XS Rating Curve= 0 ,0
Exp/Cntr=0.3,0.1

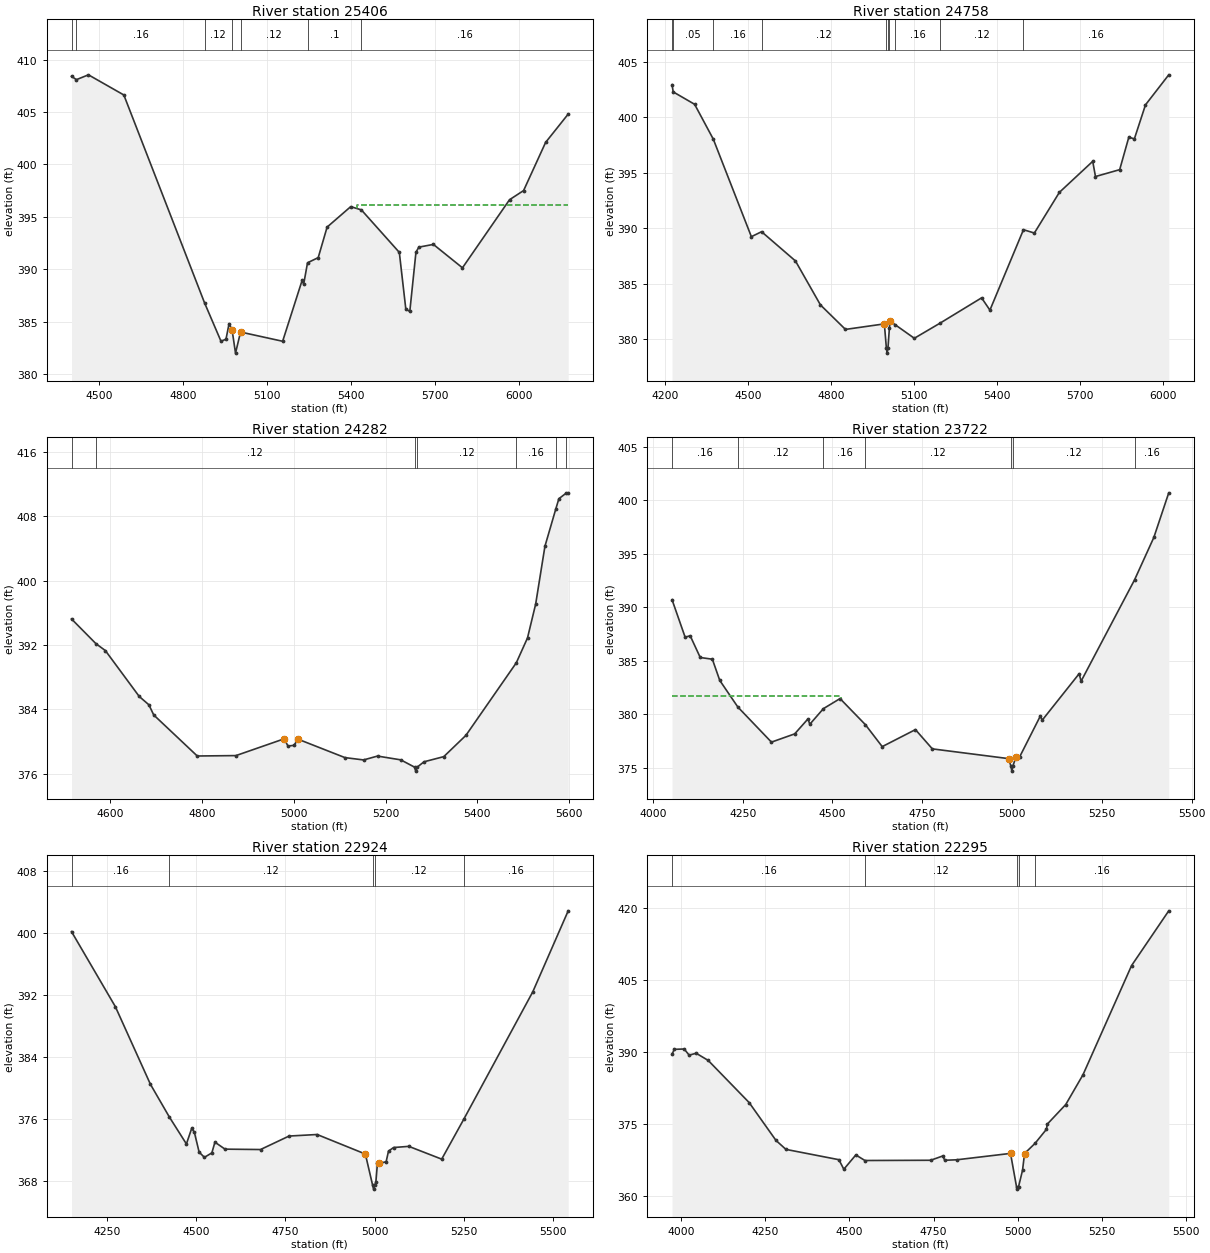
Type RM Length L Ch R = 1 ,25406   ,648,648,648
BEGIN DESCRIPTION:
REISS CREEK 49.0
END DESCRIPTION:
XS GIS Cut Line= 4
      3531268.99     10371617.06      3531368.98     10371317.06
      3531897.54     10370129.82      3531892.34     10369971.01
#Sta/Elev= 30
  4400.3   408.4  4417.9  408.08  4460.8  408.54  4587.3  406.62  4875.7  386.81
  4934.5  383.15  4952.3  383.35  4963.3  384.83  4974.2  384.21  4986.3  382.02
  5004.3  384.03  5154.7  383.15  5224.4  388.96  5229.8  388.58  5243.6  390.63
  5281.8  391.12  5313.6  394.03    5398  395.98    5436  395.67  5571.6  391.62
  5594.9   386.2  5609.1     386    5631  391.63  5641.3  392.12  5693.3  392.38
  5797.2  390.15  5965.4  396.64  6015.6  397.51  6094.3   402.1    6175   404.8
#Mann= 7 ,-1 , 0
  4400.3     .05       0  4417.9     .16       0  4875.7     .12       0
  4974.2     .07       0  5004.3     .12       0  5243.6      .1       0
    5436     .16       0
#XS Ineff= 2 , 0
                         5421.88          396.11
Permanent Ineff=
       F       F
Bank Sta=4974.2,5004.3
XS Rating Curve= 0 ,0
Exp/Cntr=0.3,0.1

Type RM Length L Ch R = 1 ,24758   ,476,476,476
BEGIN DESCRIPTION:
REISS CREEK 48.0
END DESCRIPTION:
XS GIS Cut Line= 3
      3531764.75      10371629.8      3532043.38     10371358.98
      3531910.56     10369957.92
#Sta/Elev= 30
  4223.8  402.95  4227.9   402.3  4305.4  401.18    4373  398.03  4510.6  389.23
  4547.5  389.68    4670  387.04  4760.4  383.07  4850.8  380.86  4991.4  381.36
  4998.6  379.22  5001.3  378.72  5004.6  379.22  5009.6  380.97  5011.5  381.63
  5031.3  381.27  5099.8  380.06  5193.1  381.43    5343  383.71  5373.1   382.6
  5494.4  389.86  5533.8  389.56  5624.2  393.23  5744.8  396.03  5754.8  394.66
  5842.3  395.28  5875.3  398.21  5895.4  398.06  5935.6  401.13  6019.7  403.84
#Mann= 10 ,-1 , 0
  4223.8     .16       0  4227.9     .05       0    4373     .16       0
  4547.5     .12       0  4998.6     .07       0  5004.6     .12       0
  5009.6      .1       0  5031.3     .16       0  5193.1     .12       0
  5494.4     .16       0
Bank Sta=4991.4,5011.5
XS Rating Curve= 0 ,0
Exp/Cntr=0.3,0.1

Type RM Length L Ch R = 1 ,24282   ,560,560,560
BEGIN DESCRIPTION:
REISS CREEK 47.0
END DESCRIPTION:
XS GIS Cut Line= 3
      3532192.11     10371491.64      3532342.11     10371041.64
       3532442.1     10370441.66
#Sta/Elev= 30
  4515.3  395.24  4568.7  392.16  4589.1  391.31  4662.9  385.61    4684  384.57
  4694.5  383.31  4789.4  378.21  4873.7  378.26  4979.1  380.35    4987  379.45
  4999.8  379.53  5009.9  380.28  5111.3  378.01  5151.8  377.72  5182.3   378.2
    5233  377.73  5262.9  376.83  5265.6  376.33  5268.9  376.83  5283.6  377.49
  5326.7  378.13  5374.9  380.77  5484.8  389.79  5509.2  392.88    5527  397.09
  5547.2  404.27    5571  408.93  5577.6  410.18  5593.7  410.88  5597.9  410.91
#Mann= 7 ,-1 , 0
  4515.3     .16       0  4568.7     .12       0  5262.9     .07       0
  5268.9     .12       0  5484.8     .16       0    5571     .07       0
  5593.7     .05       0
Bank Sta=4979.1,5009.9
XS Rating Curve= 0 ,0
Exp/Cntr=0.3,0.1

Type RM Length L Ch R = 1 ,23722   ,798,798,798
BEGIN DESCRIPTION:
REISS CREEK 46.0
END DESCRIPTION:
XS GIS Cut Line= 3
      3532598.34     10371930.77       3532763.6     10371238.28
      3532942.12      10370591.6
#Sta/Elev= 30
  4053.4  390.72  4089.8  387.22  4103.9  387.35  4131.9  385.32  4165.6  385.16
  4186.2  383.18  4236.6  380.69  4330.1  377.41  4394.8  378.18  4431.8  379.58
  4436.9  379.08  4474.8  380.54  4521.1  381.48  4591.7  379.04  4638.5  376.99
    4731  378.58    4778  376.78  4990.1  375.87  4996.6   375.2  4999.4   374.7
  5002.6   375.2  5010.8  376.04  5021.2  376.04  5078.7  379.85  5083.9  379.46
  5186.9  383.81  5192.1   383.1  5340.9  392.57  5394.7  396.54  5436.2  400.71
#Mann= 7 ,-1 , 0
  4053.4     .16       0  4236.6     .12       0  4474.8     .16       0
  4591.7     .12       0  4996.6     .07       0  5002.6     .12       0
  5340.9     .16       0
#XS Ineff= 2 , 0
         4522.73   381.7
Permanent Ineff=
       F       F
Bank Sta=4990.1,5010.8
XS Rating Curve= 0 ,0
Exp/Cntr=0.3,0.1

Type RM Length L Ch R = 1 ,22924   ,629,629,629
BEGIN DESCRIPTION:
REISS CREEK 44.0
END DESCRIPTION:
XS GIS Cut Line= 3
      3532892.08     10371991.67      3533392.11     10371291.64
      3533792.12     10370941.63
#Sta/Elev= 30
  4150.8  400.24  4273.7  390.55    4372  380.53  4424.7  376.33  4472.8  372.83
  4487.6  374.84  4494.9  374.37  4508.4  371.78  4523.2   371.1  4544.1  371.68
  4552.7  373.06    4581  372.16  4680.5  372.11  4760.4  373.85    4839  374.05
  4974.2  371.53  4994.6   367.5  4997.3     367  5000.6   367.5  5003.7  367.91
    5008  370.31  5011.1  370.31  5032.4  370.53  5039.1  371.91  5053.3  372.37
    5096  372.52  5188.1  370.87  5250.1  376.03  5443.4  392.47  5542.6  402.92
#Mann= 5 ,-1 , 0
  4150.8     .16       0  4424.7     .12       0  4994.6     .07       0
  5000.6     .12       0  5250.1     .16       0
Bank Sta=4974.2,5011.1
XS Rating Curve= 0 ,0
Exp/Cntr=0.3,0.1

Type RM Length L Ch R = 1 ,22295   ,811,811,811
BEGIN DESCRIPTION:
REISS CREEK 43.0
END DESCRIPTION:
XS GIS Cut Line= 3
      3533306.55     10372426.54      3533957.36     10371523.12
      3534157.25     10371223.27
#Sta/Elev= 30
  3974.2  389.51  3980.8  390.54  4010.2  390.61  4024.9  389.33  4045.8  389.72
  4081.4  388.23  4202.9  379.44  4282.6  371.54  4312.1  369.67  4469.2  367.52
  4483.9  365.53  4519.5  368.51  4546.5  367.35  4741.6   367.4  4777.2  368.29
  4783.4   367.4    4819   367.5  4978.5  368.83  4996.3  361.88  4999.1  361.38
  5002.3  361.88  5014.1   365.3  5020.2  368.81  5051.2  370.92  5085.2  373.87
  5087.4  374.92  5142.4  379.03  5193.5  385.23  5337.7  408.01    5448  419.43
#Mann= 5 ,-1 , 0
  3974.2     .16       0  4546.5     .12       0  4996.3     .07       0
  5002.3     .12       0  5051.2     .16       0
Bank Sta=4978.5,5020.2
XS Rating Curve= 0 ,0
Exp/Cntr=0.3,0.1

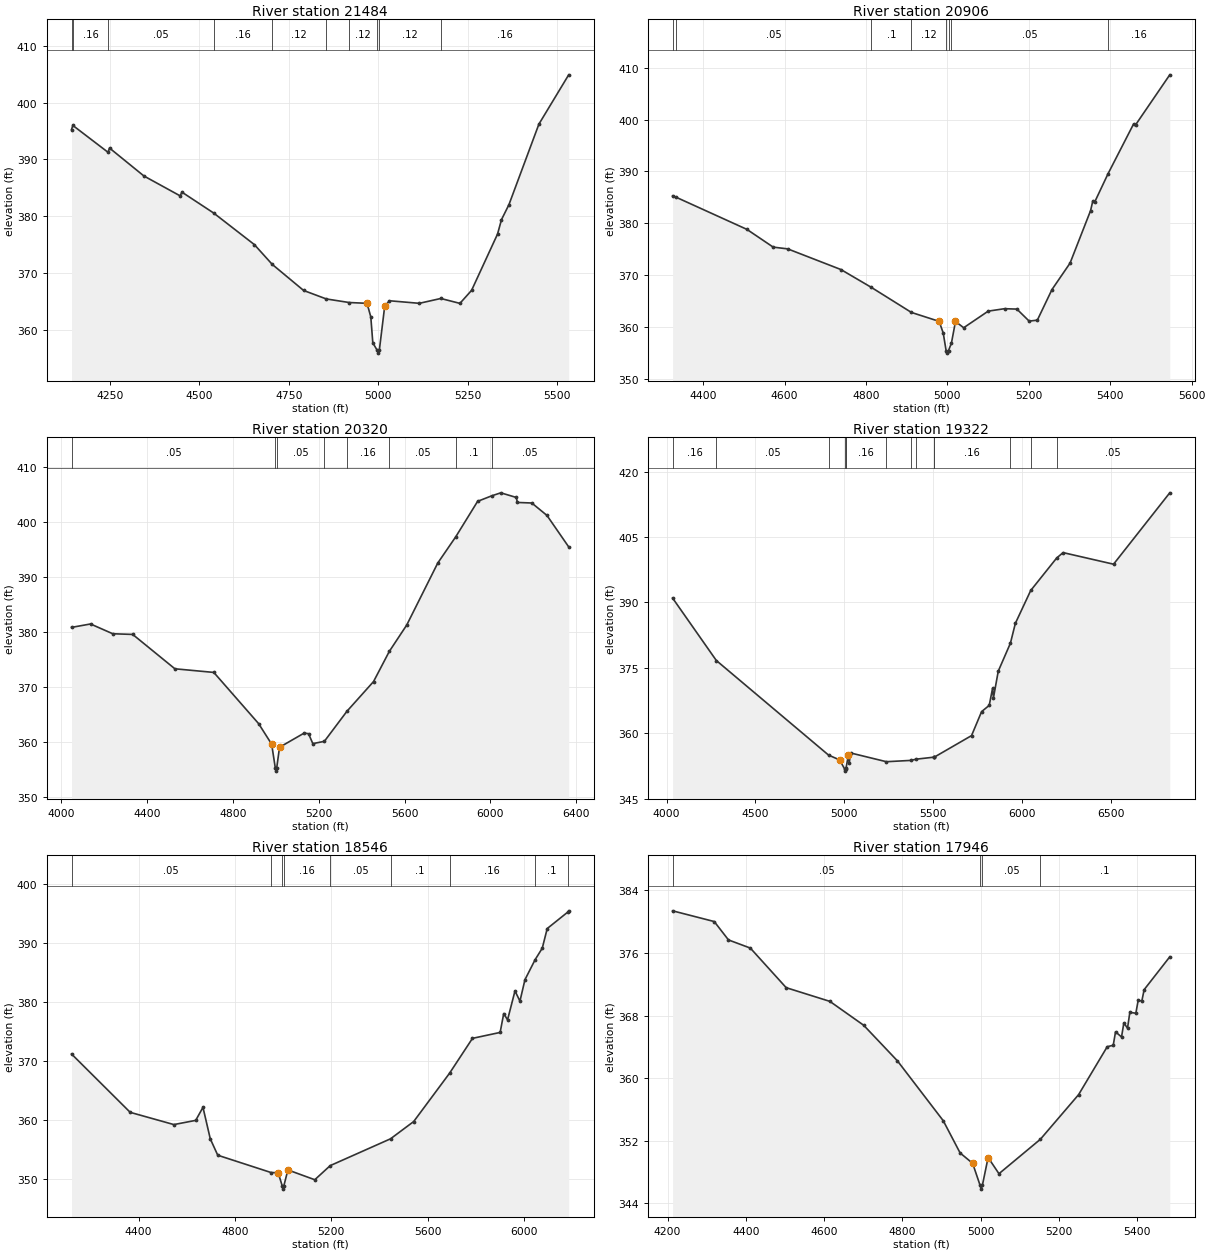
Type RM Length L Ch R = 1 ,21484   ,578,578,578
BEGIN DESCRIPTION:
REISS CREEK 42.0
END DESCRIPTION:
XS GIS Cut Line= 3
      3534117.09      10372796.4      3534180.04     10372158.97
      3534392.12      10371441.6
#Sta/Elev= 30
    4143  395.26  4146.7  395.98    4245  391.26  4249.1  392.01  4345.2   387.1
  4446.3  383.61  4451.4  384.26  4539.8   380.6  4653.6  375.05  4703.6  371.57
  4791.2  366.99  4854.5   365.5  4918.5  364.87  4968.4  364.73  4978.9  362.34
  4984.5  357.79  4996.7  356.48  4999.5  355.98  5002.7  356.48  5017.7  364.21
    5031  365.18  5114.4  364.73  5174.4  365.58  5227.8  364.72  5260.4  367.01
  5332.9   376.9  5343.9  379.43  5364.7  382.06  5448.4  396.21  5531.6  404.87
#Mann= 10 ,-1 , 0
    4143      .1       0  4146.7     .16       0    4245     .05       0
  4539.8     .16       0  4703.6     .12       0  4854.5     .16       0
  4918.5     .12       0  4996.7     .07       0  5002.7     .12       0
  5174.4     .16       0
Bank Sta=4968.4,5017.7
XS Rating Curve= 0 ,0
Exp/Cntr=0.3,0.1

Type RM Length L Ch R = 1 ,20906   ,586,586,586
BEGIN DESCRIPTION:
REISS CREEK 40.0
END DESCRIPTION:
XS GIS Cut Line= 3
       3534538.8     10372664.32      3534688.83     10372464.28
      3534785.96     10371497.99
#Sta/Elev= 30
    4325  385.31  4334.2  385.02  4507.5  378.85  4572.1  375.43  4607.8  375.09
  4738.5  371.11  4813.3  367.67  4911.6  362.85  4979.7  361.13  4989.8  358.88
  4996.8  355.51  4999.6  355.01  5002.8  355.51  5009.9  356.94  5019.9  361.11
    5040   359.9  5100.3   363.1  5140.5  363.57  5170.7  363.49  5200.8  361.18
  5220.9  361.36  5256.9  367.26  5301.3  372.35  5351.6  382.44  5357.1  384.27
  5362.2  384.18  5394.5  389.55  5457.4  399.16  5462.4     399  5546.2  408.62
#Mann= 8 ,-1 , 0
    4325     .16       0  4334.2     .05       0  4813.3      .1       0
  4911.6     .12       0  4996.8     .07       0  5002.8     .12       0
  5009.9     .05       0  5394.5     .16       0
Bank Sta=4979.7,5019.9
XS Rating Curve= 0 ,0
Exp/Cntr=0.3,0.1

Type RM Length L Ch R = 1 ,20320   ,998,998,998
BEGIN DESCRIPTION:
REISS CREEK 38.0
END DESCRIPTION:
XS GIS Cut Line= 3
       3534880.4     10373166.19      3535187.29      10372481.6
      3535399.75     10370931.42
#Sta/Elev= 30
  4049.2  380.82  4137.7  381.44  4241.3  379.66  4334.1  379.54  4530.5  373.29
  4711.7  372.63  4920.5  363.31  4981.1  359.58  4998.3  355.18    5001  354.68
  5004.3  355.18  5017.7  359.02  5132.5   361.6  5152.7  361.49  5172.8  359.68
  5226.5   360.1  5331.7  365.57  5455.5  370.97  5528.8  376.45    5610  381.25
  5754.3  392.51  5838.8  397.33    5940  403.74  6005.3  404.74    6048  405.29
  6120.1  404.45  6125.2  403.54  6192.3  403.44  6262.9  401.18  6364.1  395.46
#Mann= 8 ,-1 , 0
  4049.2     .05       0  4998.3     .03       0  5004.3     .05       0
  5226.5      .1       0  5331.7     .16       0  5528.8     .05       0
  5838.8      .1       0  6005.3     .05       0
Bank Sta=4981.1,5017.7
XS Rating Curve= 0 ,0
Exp/Cntr=0.3,0.1

Type RM Length L Ch R = 1 ,19322   ,776,776,776
BEGIN DESCRIPTION:
REISS CREEK 36.0
END DESCRIPTION:
XS GIS Cut Line= 3
      3535903.38     10373441.62      3536042.11     10372491.64
      3536336.18      10370679.6
#Sta/Elev= 30
    4034  390.99    4280  376.67    4911  354.98  4973.8  353.86  5001.2   351.8
  5003.9   351.3  5007.2   351.8  5009.7  352.05  5022.3  354.94  5027.4  353.17
  5034.6  355.47  5236.3  353.46    5374  353.76  5403.4  354.04  5501.3  354.49
  5503.8  354.48  5504.5  354.48  5715.2  359.45  5771.7  364.95  5814.6  366.38
  5833.3  370.28  5838.4  368.11  5865.3  374.22  5933.8  380.65  5961.6   385.2
  6047.9  392.73  6194.1  400.19    6230  401.42  6513.7  398.76  6829.8  415.13
#Mann= 15 ,-1 , 0
    4034     .16       0    4280     .05       0    4911      .1       0
  5001.2     .07       0  5007.2      .1       0  5009.7     .16       0
  5236.3     .07       0    5374     .16       0  5403.4     .05       0
  5501.3     .07       0  5503.8     .05       0  5504.5     .16       0
  5933.8     .05       0  6047.9     .16       0  6194.1     .05       0
Bank Sta=4973.8,5022.3
XS Rating Curve= 0 ,0
Exp/Cntr=0.3,0.1

Type RM Length L Ch R = 1 ,18546   ,600,600,600
BEGIN DESCRIPTION:
REISS CREEK 35.0
END DESCRIPTION:
XS GIS Cut Line= 3
      3536572.26     10373323.55      3536706.03      10372253.4
       3536941.7     10371295.03
#Sta/Elev= 30
    4121   371.2  4364.8  361.32  4546.2  359.25  4636.9  359.96  4667.1  362.17
  4697.4  356.84  4728.5  354.06  4949.9  351.13  4979.5   351.1  4996.7  348.82
  4999.4  348.32  5002.7  348.82  5019.9  351.57  5131.6  349.91  5195.7   352.3
  5446.3  356.84  5542.6  359.77  5691.4  367.94  5786.7  373.85  5901.6  374.85
  5916.5  378.05  5932.4  376.98  5963.3  381.88  5983.9  380.15  6004.7  383.78
  6047.1  387.18  6076.6  389.11  6097.2  392.44  6184.5  395.29  6186.4  395.44
#Mann= 9 ,-1 , 0
    4121     .05       0  4949.9     .16       0  4996.7     .07       0
  5002.7     .16       0  5195.7     .05       0  5446.3      .1       0
  5691.4     .16       0  6047.1      .1       0  6184.5     .05       0
Bank Sta=4979.5,5019.9
XS Rating Curve= 0 ,0
Exp/Cntr=0.3,0.1

Type RM Length L Ch R = 1 ,17946   ,627,627,627
BEGIN DESCRIPTION:
REISS CREEK 34.0
END DESCRIPTION:
XS GIS Cut Line= 3
       3536918.5     10373441.64      3537192.11     10372691.64
      3537442.08     10372291.68
#Sta/Elev= 30
    4213  381.38  4319.4  380.01  4355.8  377.66  4411.6  376.62  4503.2  371.56
  4614.8  369.81  4701.1  366.76  4787.5   362.2  4904.4  354.56  4947.5  350.44
  4979.4  349.12  4998.4  346.32  5001.1  345.82  5004.4  346.32    5019  349.86
  5046.7  347.79  5152.5  352.19  5250.1  357.89  5323.3  364.02  5338.6   364.2
  5344.5  365.92  5359.8  365.26  5365.7  367.05  5375.1  366.39    5381   368.4
  5396.4   368.3  5402.3  369.94  5411.7  369.86  5417.6  371.31    5483   375.5
#Mann= 4 ,-1 , 0
    4213     .05       0  4998.4     .03       0  5004.4     .05       0
  5152.5      .1       0
Bank Sta=4979.4,5019
XS Rating Curve= 0 ,0
Exp/Cntr=0.3,0.1

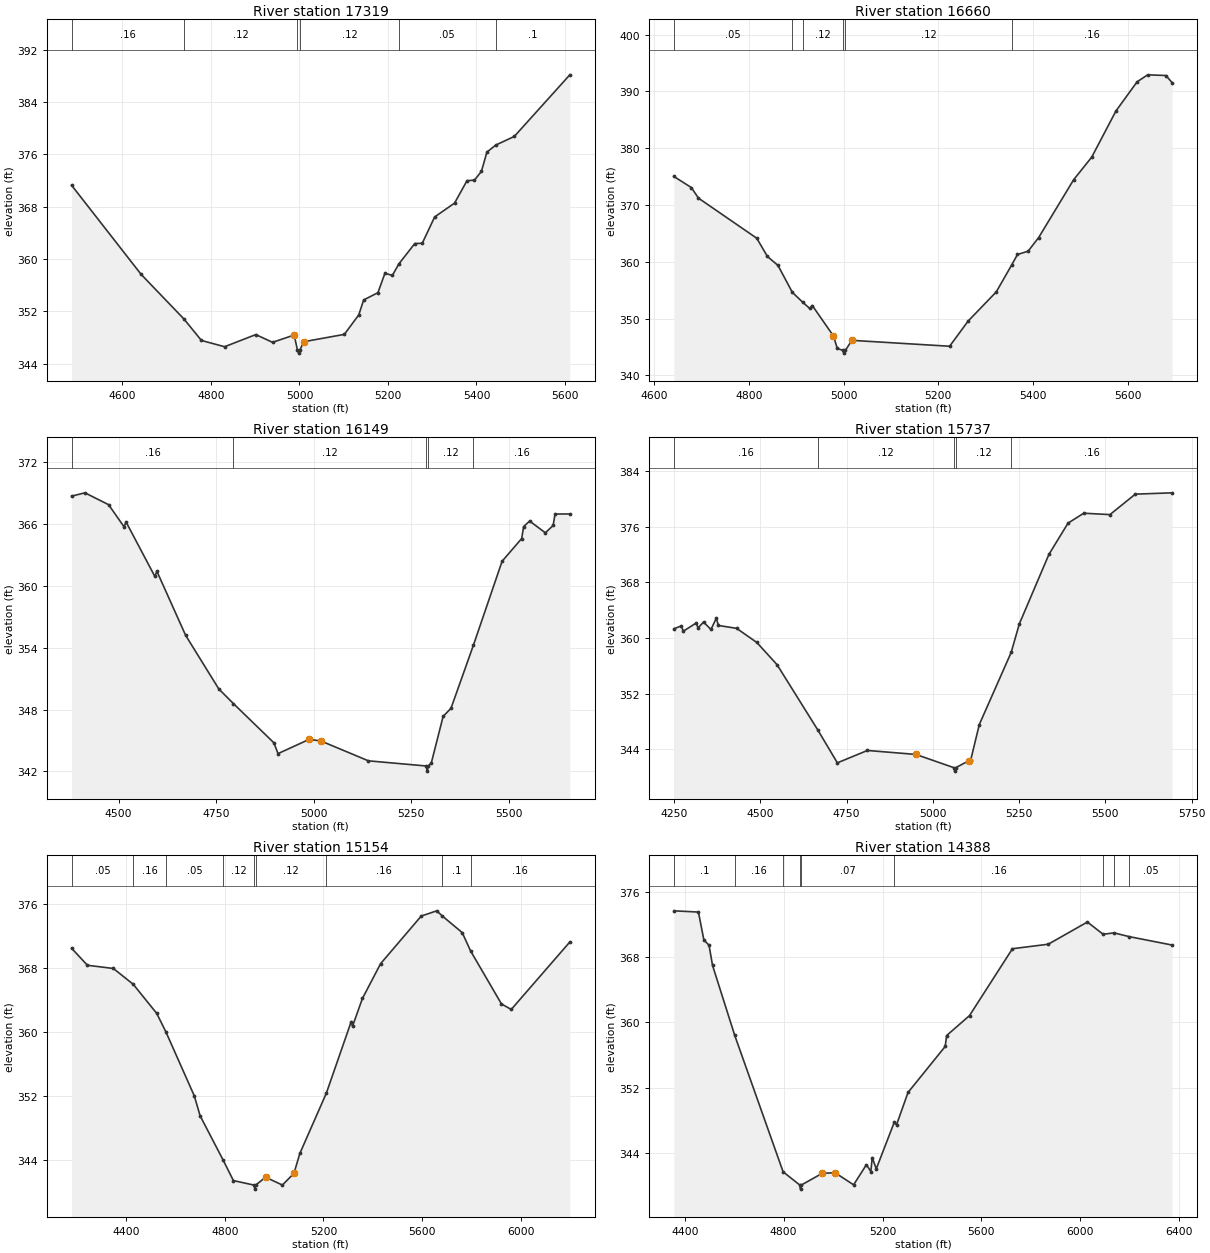
Type RM Length L Ch R = 1 ,17319   ,659,659,659
BEGIN DESCRIPTION:
REISS CREEK 32.0
END DESCRIPTION:
XS GIS Cut Line= 3
       3537542.1     10373491.67      3537744.76     10372843.58
      3537941.49     10372442.24
#Sta/Elev= 30
    4485  371.28  4642.2  357.64    4739  350.81  4778.4  347.53  4830.8  346.57
  4901.4  348.43  4939.1  347.24    4988  348.36  4995.4  346.09  4998.2  345.59
  5001.4  346.09  5009.3  347.33  5101.4  348.46  5133.9  351.43  5145.1  353.73
  5177.3  354.84  5193.1   357.8    5210  357.49  5224.6  359.24  5260.6  362.36
  5277.5   362.4  5305.5  366.43  5350.5  368.55  5378.6  371.98  5395.5  372.07
  5411.2   373.4  5423.6  376.35  5443.6  377.43  5485.5  378.75    5611  388.18
#Mann= 6 ,-1 , 0
    4485     .16       0    4739     .12       0  4995.4     .07       0
  5001.4     .12       0  5224.6     .05       0  5443.6      .1       0
Bank Sta=4988,5009.3
XS Rating Curve= 0 ,0
Exp/Cntr=0.3,0.1

Type RM Length L Ch R = 1 ,16660   ,511,511,511
BEGIN DESCRIPTION:
REISS CREEK 31.0
END DESCRIPTION:
XS GIS Cut Line= 3
      3537897.66     10373749.05      3537997.68     10373599.02
      3538390.04     10372819.95
#Sta/Elev= 30
  4641.5  375.03  4678.5  373.07  4693.5  371.21  4816.7  364.15  4839.2  360.94
  4861.5  359.37  4891.9  354.62  4913.7  352.89  4928.5   351.8  4934.1   352.3
  4978.7  346.95  4986.8  344.76    4998  344.43  5000.8  343.93    5004  344.43
  5017.7  346.18  5224.1  345.14  5263.2  349.57  5322.7  354.71  5354.9   359.4
  5367.5  361.29  5389.9  361.87  5412.3  364.28  5486.3  374.47  5524.3  378.42
  5575.5  386.55  5620.2  391.68  5642.5  392.91    5681  392.79  5694.1  391.54
#Mann= 6 ,-1 , 0
  4641.5     .05       0  4891.9     .16       0  4913.7     .12       0
    4998     .07       0    5004     .12       0  5354.9     .16       0
Bank Sta=4978.7,5017.7
XS Rating Curve= 0 ,0
Exp/Cntr=0.3,0.1

Type RM Length L Ch R = 1 ,16149   ,412,412,412
BEGIN DESCRIPTION:
REISS CREEK 30.0
END DESCRIPTION:
XS GIS Cut Line= 3
      3538469.09     10374185.66      3538582.38     10373319.42
      3538532.39     10372919.45
#Sta/Elev= 30
  4379.7  368.72    4414  369.04  4474.5  367.89  4514.2  365.74  4519.3  366.21
  4593.1  360.92  4598.2  361.43    4672   355.2  4756.9     350  4794.3  348.58
  4898.1  344.77  4908.7  343.72  4988.9  345.11  5019.1  344.94  5140.3  343.02
  5288.1  342.52  5290.9  342.02  5294.1  342.52  5301.5  342.82  5331.7  347.33
  5351.9  348.12  5409.2  354.23  5482.9   362.4    5533   364.6    5538  365.76
  5553.4   366.3  5593.7  365.16  5613.6  365.87  5618.6  366.98  5656.4  366.99
#Mann= 5 ,-1 , 0
  4379.7     .16       0  4794.3     .12       0  5288.1     .07       0
  5294.1     .12       0  5409.2     .16       0
Bank Sta=4988.9,5019.1
XS Rating Curve= 0 ,0
Exp/Cntr=0.3,0.1

Type RM Length L Ch R = 1 ,15737   ,583,583,583
BEGIN DESCRIPTION:
REISS CREEK 29.0
END DESCRIPTION:
XS GIS Cut Line= 3
      3538573.28     10374220.31      3538942.11     10373591.64
       3539191.3     10372921.77
#Sta/Elev= 30
  4249.7   361.3  4271.3  361.72  4277.1  360.96  4314.2  362.12    4320  361.44
  4335.7  362.27  4357.2  361.21  4372.9  362.83  4378.7  361.78  4431.5  361.37
  4490.1  359.34  4548.7  356.15  4666.6  346.78  4723.5  342.04  4810.5  343.82
 4950.91  343.25  5060.9  341.35  5063.7  340.85  5066.9  341.35  5104.5  342.35
  5109.8  342.44  5134.8  347.55    5227   357.9  5250.8  362.02  5336.5     372
  5391.9  376.49  5437.4  377.91  5513.3  377.71  5586.7  380.65  5693.3  380.84
#Mann= 5 ,-1 , 0
  4249.7     .16       0  4666.6     .12       0  5060.9     .07       0
  5066.9     .12       0    5227     .16       0
Bank Sta=4950.91,5104.5
XS Rating Curve= 0 ,0
Exp/Cntr=0.3,0.1

Type RM Length L Ch R = 1 ,15154   ,766,766,766
BEGIN DESCRIPTION:
REISS CREEK 28.0
END DESCRIPTION:
XS GIS Cut Line= 3
      3539101.03     10374643.98      3539482.98     10373755.06
      3539760.77     10372741.13
#Sta/Elev= 30
  4179.6  370.48  4243.8  368.35  4348.9  367.95  4429.6  365.97  4524.6  362.34
  4562.2     360  4676.8  352.04  4700.4  349.55  4794.3  343.98  4835.2  341.46
  4919.3  340.89    4922  340.39  4925.3  340.89  4965.8  341.88  5033.7   340.9
  5080.8  342.37  5104.4  344.84  5211.8  352.37  5312.7  361.32  5317.9  360.73
    5358   364.2  5431.7  368.55  5596.5   374.5  5659.3  375.15  5681.9   374.5
  5762.4  372.43  5796.3  370.14  5921.4  363.52    5961  362.83  6198.4  371.26
#Mann= 9 ,-1 , 0
  4179.6     .05       0  4429.6     .16       0  4562.2     .05       0
  4794.3     .12       0  4919.3     .07       0  4925.3     .12       0
  5211.8     .16       0  5681.9      .1       0  5796.3     .16       0
Bank Sta=4965.8,5080.8
XS Rating Curve= 0 ,0
Exp/Cntr=0.3,0.1

Type RM Length L Ch R = 1 ,14388   ,394,394,394
BEGIN DESCRIPTION:
REISS CREEK 26.0
END DESCRIPTION:
XS GIS Cut Line= 3
      3539528.22     10374898.58      3539878.22     10374598.59
      3540510.76     10373178.68
#Sta/Elev= 30
  4355.9  373.67  4455.4  373.52  4477.4   370.1  4498.2  369.46  4512.5  366.98
  4602.3  358.41  4797.9  341.71  4865.5  340.09  4868.3  339.59  4871.5  340.09
  4955.8  341.52  5007.9   341.6  5083.1  340.12    5135  342.59  5152.8  341.74
  5158.3  343.45  5174.8  342.08  5247.3  347.76  5256.7  347.47  5303.2  351.43
  5453.5  357.06  5459.4   358.4  5551.9  360.84  5725.5  369.03  5870.4  369.58
  6028.7   372.3  6092.2   370.8  6136.5  370.97  6197.9  370.51  6371.3  369.48
#Mann= 9 ,-1 , 0
  4355.9      .1       0  4602.3     .16       0  4797.9     .07       0
  4865.5     .07       0  4871.5     .07       0  5247.3     .16       0
  6092.2     .05       0  6136.5     .16       0  6197.9     .05       0
Bank Sta=4955.8,5007.9
XS Rating Curve= 0 ,0
Exp/Cntr=0.3,0.1

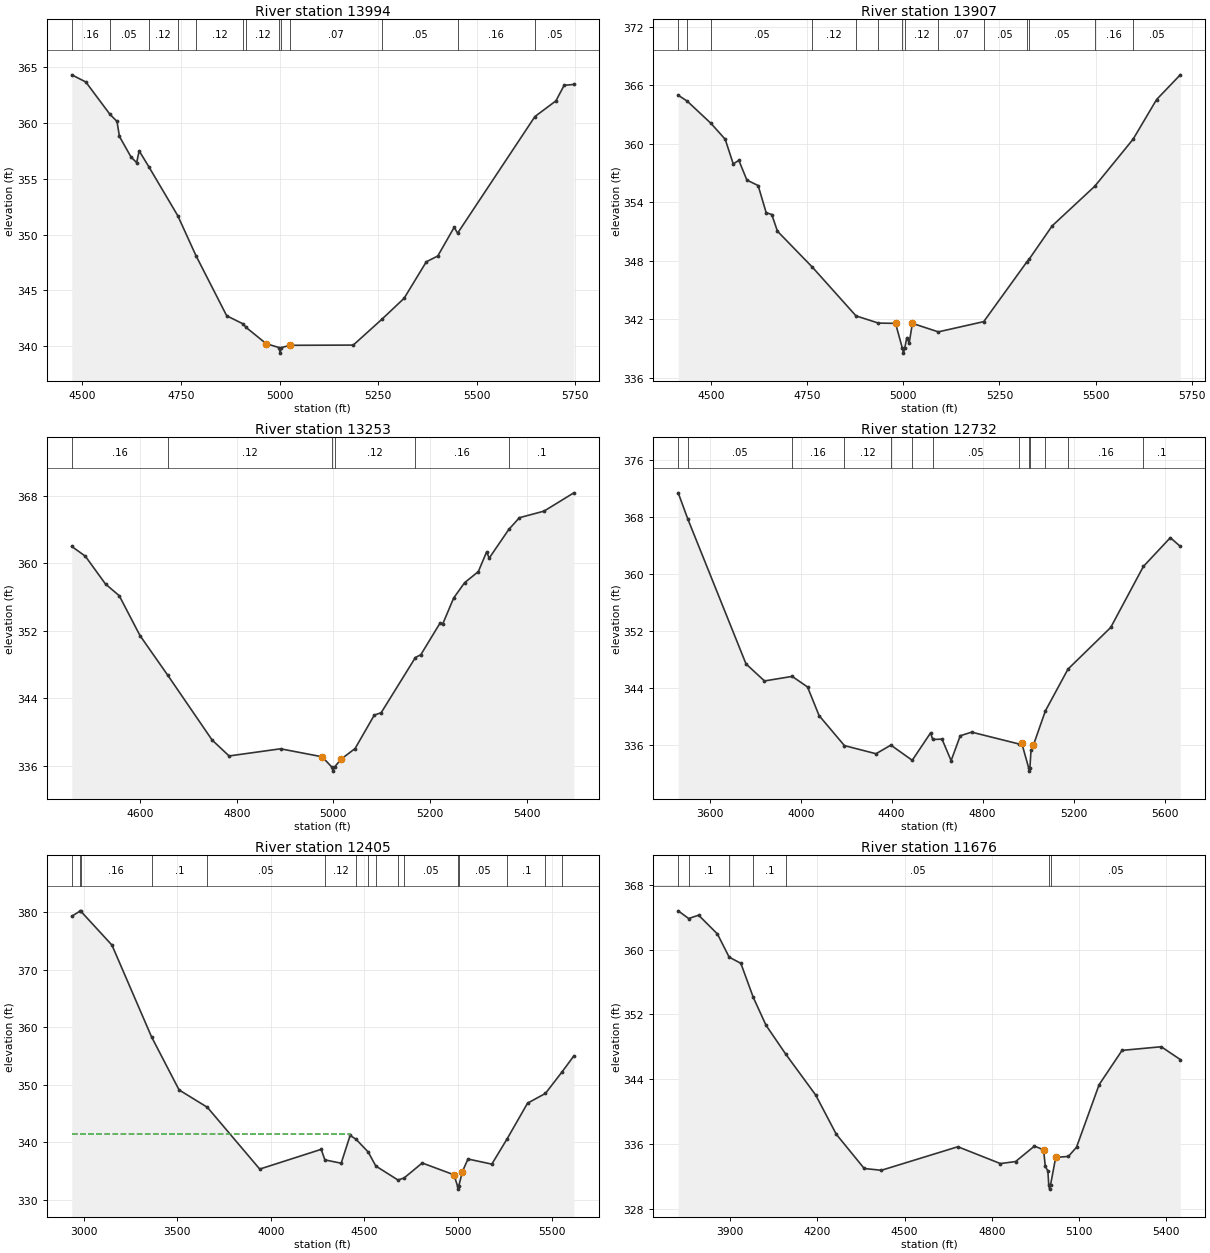
Type RM Length L Ch R = 1 ,13994   ,87,87,87
BEGIN DESCRIPTION:
Mapping XS d59bb826
END DESCRIPTION:
XS GIS Cut Line= 2
      3539895.66      10375145.1      3540663.86     10374129.52
#Sta/Elev= 30
    4473  364.29  4508.6  363.65  4569.3  360.78  4587.7  360.12  4593.9  358.78
  4623.1  356.95  4637.6  356.43  4643.9  357.49  4668.4  356.07  4742.1  351.67
  4787.9  348.12    4866  342.73  4907.4  342.01  4914.9   341.7  4966.3  340.23
  4998.8  339.89  5001.5  339.39  5004.8  339.89    5027  340.09    5187  340.11
  5260.5  342.45    5316   344.3  5372.2  347.56  5401.3  348.08    5443  350.65
  5451.6  350.12  5647.8  360.56    5701  361.96  5721.8  363.35  5746.4  363.43
#Mann= 13 ,-1 , 0
    4473     .16       0  4569.3     .05       0  4668.4     .12       0
  4742.1     .05       0  4787.9     .12       0  4907.4     .16       0
  4914.9     .12       0  4998.8     .07       0  5004.8     .12       0
    5027     .07       0  5260.5     .05       0  5451.6     .16       0
  5647.8     .05       0
Bank Sta=4966.3,5027
XS Rating Curve= 0 ,0
Exp/Cntr=0.3,0.1

Type RM Length L Ch R = 1 ,13907   ,654,654,654
BEGIN DESCRIPTION:
REISS CREEK 25.0
END DESCRIPTION:
XS GIS Cut Line= 2
      3539933.42     10375253.39      3540705.23     10374199.48
#Sta/Elev= 30
  4414.1  364.97  4437.3  364.37  4499.5  362.08  4536.4  360.45  4557.3  357.93
  4571.9  358.29  4592.8  356.27  4622.1  355.71    4643  352.93  4657.6  352.74
  4672.3  351.03  4763.5  347.33  4876.7  342.35    4935  341.61  4979.6  341.58
  4997.4  339.03  5000.2  338.53  5003.4  339.03  5008.9   340.1  5015.1  339.57
  5023.5  341.58  5090.9  340.71  5209.1  341.76  5321.2  347.88  5327.4  348.17
  5387.2  351.58    5498  355.64  5597.7  360.46  5658.9  364.53  5720.4  367.06
#Mann= 14 ,-1 , 0
  4414.1     .05       0  4437.3     .16       0  4499.5     .05       0
  4763.5     .12       0  4876.7     .05       0    4935     .12       0
  4997.4     .07       0  5003.4     .12       0  5090.9     .07       0
  5209.1     .05       0  5321.2     .12       0  5327.4     .05       0
    5498     .16       0  5597.7     .05       0
Bank Sta=4979.6,5023.5
XS Rating Curve= 0 ,0
Exp/Cntr=0.3,0.1

Type RM Length L Ch R = 1 ,13253   ,521,521,521
BEGIN DESCRIPTION:
REISS CREEK 23.0
END DESCRIPTION:
XS GIS Cut Line= 3
      3540544.88     10375383.31      3540844.88     10375033.31
       3541094.1       10374512.
#Sta/Elev= 30
  4458.7     362  4486.8  360.84  4528.5  357.54    4557  356.15  4599.8  351.43
  4656.8  346.76  4749.1  339.03  4784.2  337.14  4890.7  337.99  4976.9  337.04
  4996.5  335.84  4999.3  335.34  5002.5  335.84  5016.7  336.79  5044.9  338.02
  5084.7  341.99  5098.9  342.27  5169.7  348.82  5180.9  349.15  5220.8  352.91
  5226.3  352.81    5249  355.89  5271.6   357.7  5299.9  359.01    5317  361.34
  5322.5  360.62    5363  364.02    5385  365.41  5435.9  366.19  5497.5  368.36
#Mann= 6 ,-1 , 0
  4458.7     .16       0  4656.8     .12       0  4996.5     .07       0
  5002.5     .12       0  5169.7     .16       0    5363      .1       0
Bank Sta=4976.9,5016.7
XS Rating Curve= 0 ,0
Exp/Cntr=0.3,0.1

Type RM Length L Ch R = 1 ,12732   ,327,327,327
BEGIN DESCRIPTION:
REISS CREEK 22.0
END DESCRIPTION:
XS GIS Cut Line= 3
      3541448.26     10376560.65      3541392.11     10375041.64
      3541226.47     10374374.85
#Sta/Elev= 30
  3461.5  371.41  3503.6  367.75  3759.6  347.41  3840.8  345.02  3962.5  345.66
    4030  344.18  4080.9  340.16  4192.3  335.95  4331.1  334.81  4396.5  336.02
  4490.3  333.89  4570.9  337.73  4580.4  336.81  4621.3  336.86  4661.3  333.84
  4701.4  337.33  4751.4  337.84  4958.2  336.19  4971.5  336.33  5001.8  332.87
  5004.5  332.37  5007.8  332.87  5012.5  335.29  5022.8     336  5075.7  340.82
    5175  346.68  5362.8  352.52  5506.5  361.08    5625  365.12  5668.6   363.9
#Mann= 13 ,-1 , 0
  3461.5     .16       0  3503.6     .05       0  3962.5     .16       0
  4192.3     .12       0  4396.5     .05       0  4490.3     .12       0
  4580.4     .05       0  4958.2     .12       0  5001.8     .07       0
  5007.8     .12       0  5075.7     .05       0    5175     .16       0
  5506.5      .1       0
Bank Sta=4971.5,5022.8
XS Rating Curve= 0 ,0
Exp/Cntr=0.3,0.1

Type RM Length L Ch R = 1 ,12405   ,729,729,729
BEGIN DESCRIPTION:
REISS CREEK 21.0
END DESCRIPTION:
XS GIS Cut Line= 3
      3543420.52     10375963.41      3541885.76     10375331.45
      3541420.47      10374421.7
#Sta/Elev= 30
    2937  379.25  2983.4  380.19  2984.7  380.14  3151.6  374.24  3363.2   358.3
  3510.1  349.09  3661.3  346.07    3941  335.34  4269.4  338.77  4288.9  336.94
    4376  336.36  4423.9  341.19  4455.8  340.51  4520.3  338.31    4561  335.87
  4679.1  333.45  4711.9  333.79  4808.9   336.4  4978.4  334.35  4997.9  332.36
  5000.7  331.86  5003.9  332.36  5023.4   334.9  5053.2  337.09  5180.6   336.2
  5262.3  340.59  5371.6  346.79    5467  348.48  5554.4  352.16  5618.6  354.99
#Mann= 16 ,-1 , 0
    2937     .16       0  2983.4     .05       0  2984.7     .16       0
  3363.2      .1       0  3661.3     .05       0  4288.9     .12       0
  4455.8     .16       0  4520.3     .12       0    4561     .05       0
  4679.1     .12       0  4711.9     .05       0  4997.9     .03       0
  5003.9     .05       0  5262.3      .1       0    5467     .16       0
  5554.4      .1       0
#XS Ineff= 2 , 0
            4425  341.41
Permanent Ineff=
       F       F
Bank Sta=4978.4,5023.4
XS Rating Curve= 0 ,0
Exp/Cntr=0.3,0.1

Type RM Length L Ch R = 1 ,11676   ,180,180,180
BEGIN DESCRIPTION:
REISS CREEK 20.0
END DESCRIPTION:
XS GIS Cut Line= 3
      3543434.37     10375303.67      3542330.21     10374671.73
       3541969.1     10374393.95
#Sta/Elev= 30
  3720.9  364.81  3756.8  363.86  3791.2  364.27  3855.9  361.95  3896.2  359.09
  3936.5  358.32  3979.4   354.1  4023.1  350.67  4091.7  347.06  4194.1  342.04
    4265  337.19  4361.1  332.96  4420.1  332.74  4683.4  335.65  4829.6  333.57
    4882  333.82  4946.8  335.73  4978.4  335.27  4984.2  333.22  4993.1  332.66
  4996.2  330.91    4999  330.41  5002.2  330.91  5020.1  334.34  5063.6  334.45
  5091.7  335.59  5169.6  343.33  5248.4  347.56  5383.4  348.01  5448.7  346.43
#Mann= 7 ,-1 , 0
  3720.9     .05       0  3756.8      .1       0  3896.2     .05       0
  3979.4      .1       0  4091.7     .05       0  4996.2     .03       0
  5002.2     .05       0
Bank Sta=4978.4,5020.1
XS Rating Curve= 0 ,0
Exp/Cntr=0.3,0.1