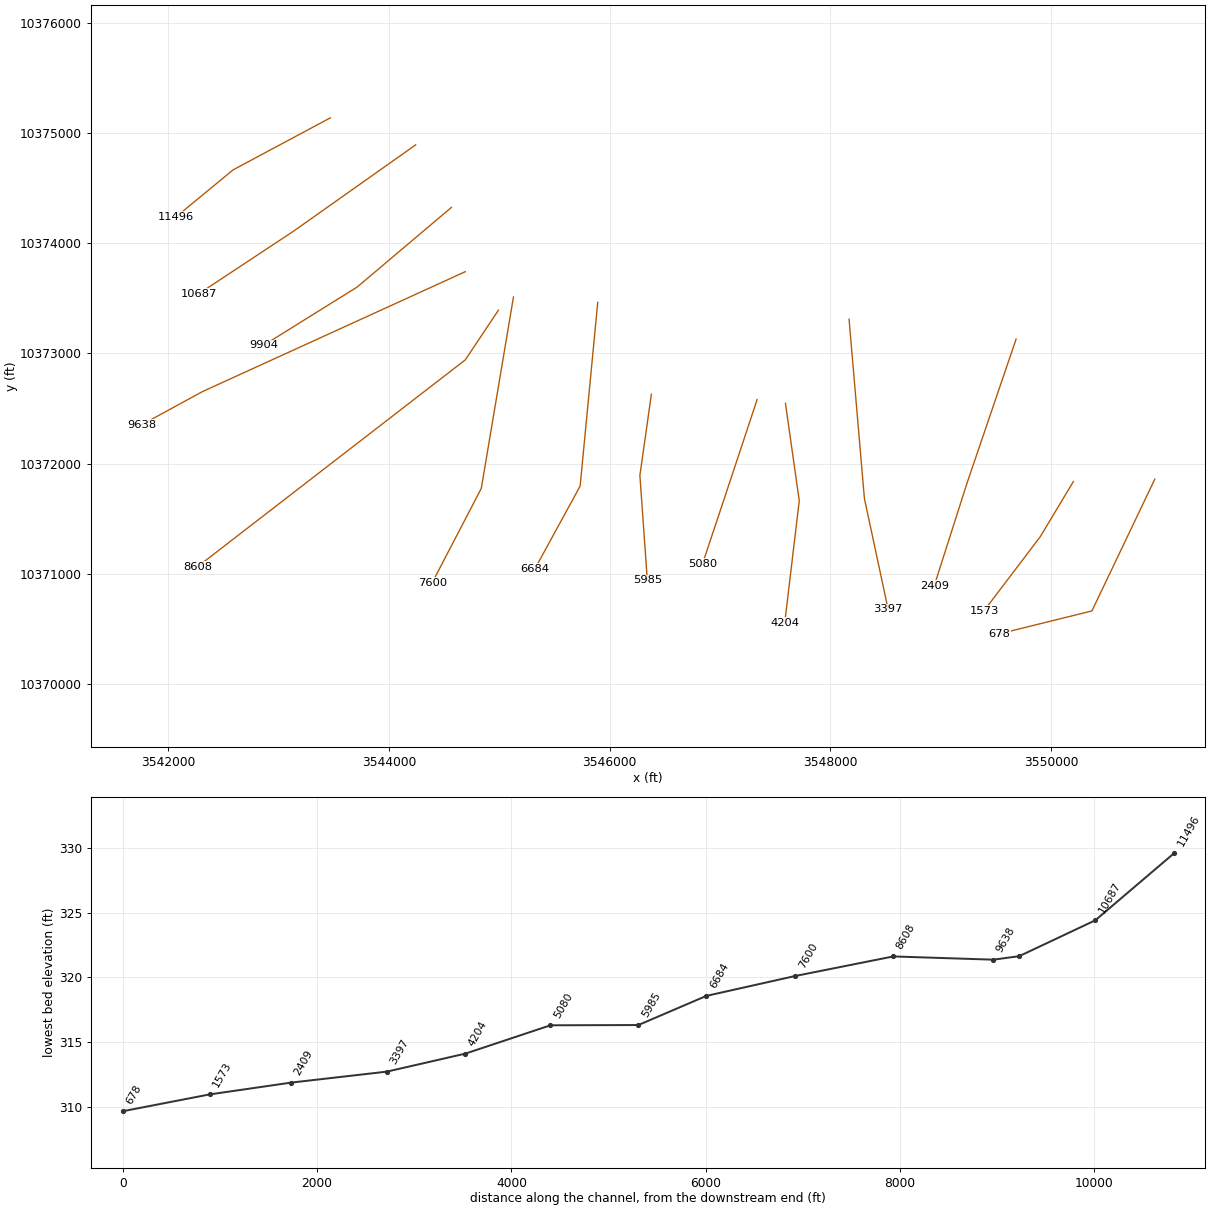
HEC-RAS study REISS CREEK.prj: REISS CREEK Base Level Engineering

--- REISS CREEK.g01 (geometry) --- (continued)

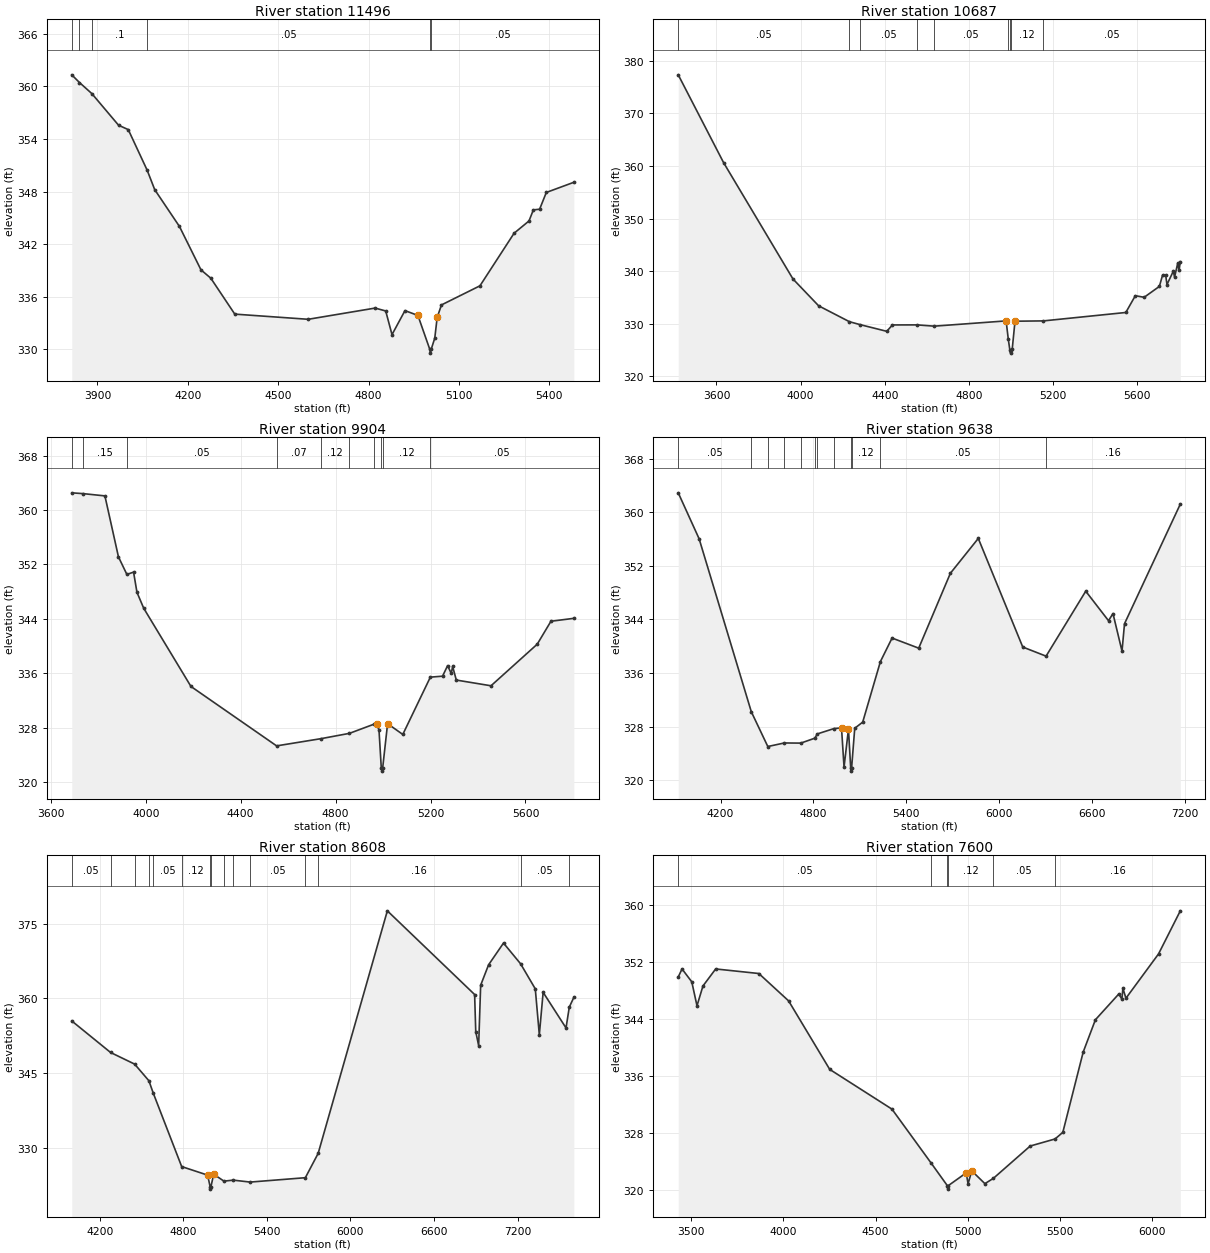
Type RM Length L Ch R = 1 ,11496   ,809,809,809
BEGIN DESCRIPTION:
REISS CREEK 19.0
END DESCRIPTION:
XS GIS Cut Line= 3
      3543469.05     10375136.98      3542587.15     10374664.78
      3542073.29     10374241.19
#Sta/Elev= 30
    3815  361.33  3840.6  360.45  3881.6  359.19  3970.3  355.58  4002.5  355.08
  4065.2  350.45  4090.3  348.23  4172.4  344.03  4243.8  339.08  4276.4  338.13
    4356  334.03  4599.7  333.44  4821.8  334.72  4856.9  334.39  4877.8  331.69
  4920.8  334.43  4963.8  333.88  5002.5  330.08  5005.2  329.58  5008.5  330.08
  5019.8   331.3  5027.7  333.65    5042  335.08  5169.7  337.26    5283  343.26
  5332.5  344.66  5346.9  345.92  5367.7     346  5389.9  347.91  5481.3  349.07
#Mann= 6 ,-1 , 0
    3815      .1       0  3840.6     .05       0  3881.6      .1       0
  4065.2     .05       0  5002.5     .03       0  5008.5     .05       0
Bank Sta=4963.8,5027.7
XS Rating Curve= 0 ,0
Exp/Cntr=0.3,0.1

Type RM Length L Ch R = 1 ,10687   ,783,783,783
BEGIN DESCRIPTION:
REISS CREEK 18.0
END DESCRIPTION:
XS GIS Cut Line= 3
      3544242.14     10374891.67      3543135.76     10374109.23
      3542275.87     10373540.59
#Sta/Elev= 30
  3418.4  377.34  3633.9  360.64  3963.7  338.51  4085.6  333.41  4231.8  330.39
  4281.6  329.84  4409.3  328.56  4436.4  329.77  4553.8  329.78  4634.8  329.54
  4976.6  330.54    4987  327.04  4994.7  324.91  4997.5  324.41  5000.7  324.91
  5005.7  325.22  5018.8  330.48  5153.9  330.54  5545.4  332.14  5590.6  335.33
  5632.7  335.03  5704.9   337.1    5720  339.24    5735  339.19    5741  337.45
  5771.1  339.99  5777.1  338.88  5792.2  341.51  5798.2  340.14  5804.4   341.8
#Mann= 9 ,-1 , 0
  3418.4     .05       0  4231.8     .12       0  4281.6     .05       0
  4553.8     .12       0  4634.8     .05       0    4987     .12       0
  4994.7     .07       0  5000.7     .12       0  5153.9     .05       0
Bank Sta=4976.6,5018.8
XS Rating Curve= 0 ,0
Exp/Cntr=0.3,0.1

Type RM Length L Ch R = 1 ,9904    ,266,266,266
BEGIN DESCRIPTION:
REISS CREEK 17.0
END DESCRIPTION:
XS GIS Cut Line= 3
      3544566.33     10374324.51      3543712.15     10373602.28
      3542865.99     10373075.17
#Sta/Elev= 30
  3688.3  362.53  3736.8  362.41  3827.9  362.08    3885  353.12  3920.5  350.54
  3948.7  350.88    3963  347.91  3991.6  345.56  4190.5  334.08  4551.4  325.35
  4738.4  326.41  4858.3  327.19  4961.9  328.54  4973.3  328.57  4982.8  327.69
  4992.4  322.14  4995.2  321.64  4998.4  322.14    5019  328.61  5083.1  327.03
  5199.2  335.45  5250.6  335.59  5271.9  337.14  5287.2     336  5293.1  337.02
  5308.5  335.02  5454.8  334.18  5649.5  340.29  5707.3  343.66  5803.8  344.09
#Mann= 10 ,-1 , 0
  3688.3      .1       0  3736.8     .15       0  3920.5     .05       0
  4551.4     .07       0  4738.4     .12       0  4858.3     .05       0
  4961.9     .12       0  4992.4     .07       0  4998.4     .12       0
  5199.2     .05       0
Bank Sta=4973.3,5019
XS Rating Curve= 0 ,0
Exp/Cntr=0.3,0.1

Type RM Length L Ch R = 1 ,9638    ,1030,1030,1030
BEGIN DESCRIPTION:
REISS CREEK 16.0
END DESCRIPTION:
XS GIS Cut Line= 3
      3544692.06     10373741.62      3542310.16     10372654.14
      3541760.17     10372354.14
#Sta/Elev= 30
  3926.4  362.88  4061.3  356.03  4398.6  330.23  4505.3  325.04    4612  325.57
  4718.7  325.55  4808.8  326.28  4825.4  326.92  4932.1  327.71  4981.7  327.82
    4998  321.97  5026.5  327.62    5041  321.87  5043.8  321.37    5047  321.87
  5067.1  327.76  5118.6  328.68    5233  337.71  5308.4  341.22  5480.6  339.71
  5685.2  350.88  5865.6  356.08    6153  339.88  6303.7  338.52  6560.1  348.21
  6707.2  343.81  6736.2  344.87  6794.5  339.27  6810.7  343.36  7171.3   361.2
#Mann= 12 ,-1 , 0
  3926.4     .05       0  4398.6     .12       0  4505.3     .05       0
    4612     .12       0  4718.7     .05       0  4808.8     .12       0
  4825.4     .05       0  4932.1     .12       0    5041     .07       0
    5047     .12       0    5233     .05       0  6303.7     .16       0
Bank Sta=4981.7,5026.5
XS Rating Curve= 0 ,0
Exp/Cntr=0.3,0.1

Type RM Length L Ch R = 1 ,8608    ,1008,1008,1008
BEGIN DESCRIPTION:
REISS CREEK 14.0
END DESCRIPTION:
XS GIS Cut Line= 3
      3544992.12     10373391.66      3544692.11     10372941.64
      3542267.67     10371067.53
#Sta/Elev= 30
  3999.3  355.48  4278.1  349.13  4450.7  346.79  4553.1  343.44  4584.4  340.95
  4788.5  326.16  4974.8  324.44  4992.7  322.12  4995.4  321.62  4998.7  322.12
  5018.3  324.62  5091.9  323.23    5159  323.43  5280.2  323.04  5676.6  323.92
  5768.6  328.82  6265.3  377.65    6892   360.8  6900.1  353.35  6920.9  350.52
  6935.4  362.67  6992.2  366.78  7099.4  371.16    7222  366.99  7327.6  361.94
  7356.6  352.71    7384  361.24  7548.3  354.07  7571.9  358.27  7604.5  360.23
#Mann= 15 ,-1 , 0
  3999.3     .05       0  4278.1     .16       0  4450.7     .05       0
  4553.1     .16       0  4584.4     .05       0  4788.5     .12       0
  4992.7     .07       0  4998.7     .12       0  5091.9     .05       0
    5159     .16       0  5280.2     .05       0  5676.6     .12       0
  5768.6     .16       0    7222     .05       0  7571.9     .16       0
Bank Sta=4974.8,5018.3
XS Rating Curve= 0 ,0
Exp/Cntr=0.3,0.1

Type RM Length L Ch R = 1 ,7600    ,916,916,916
BEGIN DESCRIPTION:
REISS CREEK 13.0
END DESCRIPTION:
XS GIS Cut Line= 3
      3545128.81     10373511.98      3544837.15     10371775.89
      3544392.71     10370921.72
#Sta/Elev= 30
    3430  349.89  3450.6  351.02  3503.5  349.21  3531.7  345.85  3564.1  348.63
  3633.1  351.02  3867.1  350.38  4028.6  346.54  4251.7  336.92  4589.3  331.34
  4803.4  323.71  4889.3  320.61    4892  320.11  4895.3  320.61  4991.9  322.39
  5002.1  320.86  5022.3  322.67  5093.3  320.88  5139.2  321.62  5339.1  326.16
  5473.7  327.15    5516  328.08  5626.5  339.35  5692.8  343.89  5819.8  347.51
  5836.3  346.78  5841.9   348.3  5858.4  346.91  6035.2  353.13  6153.3  359.18
#Mann= 6 ,-1 , 0
    3430     .05       0  4803.4     .12       0  4889.3     .07       0
  4895.3     .12       0  5139.2     .05       0  5473.7     .16       0
Bank Sta=4991.9,5022.3
XS Rating Curve= 0 ,0
Exp/Cntr=0.3,0.1

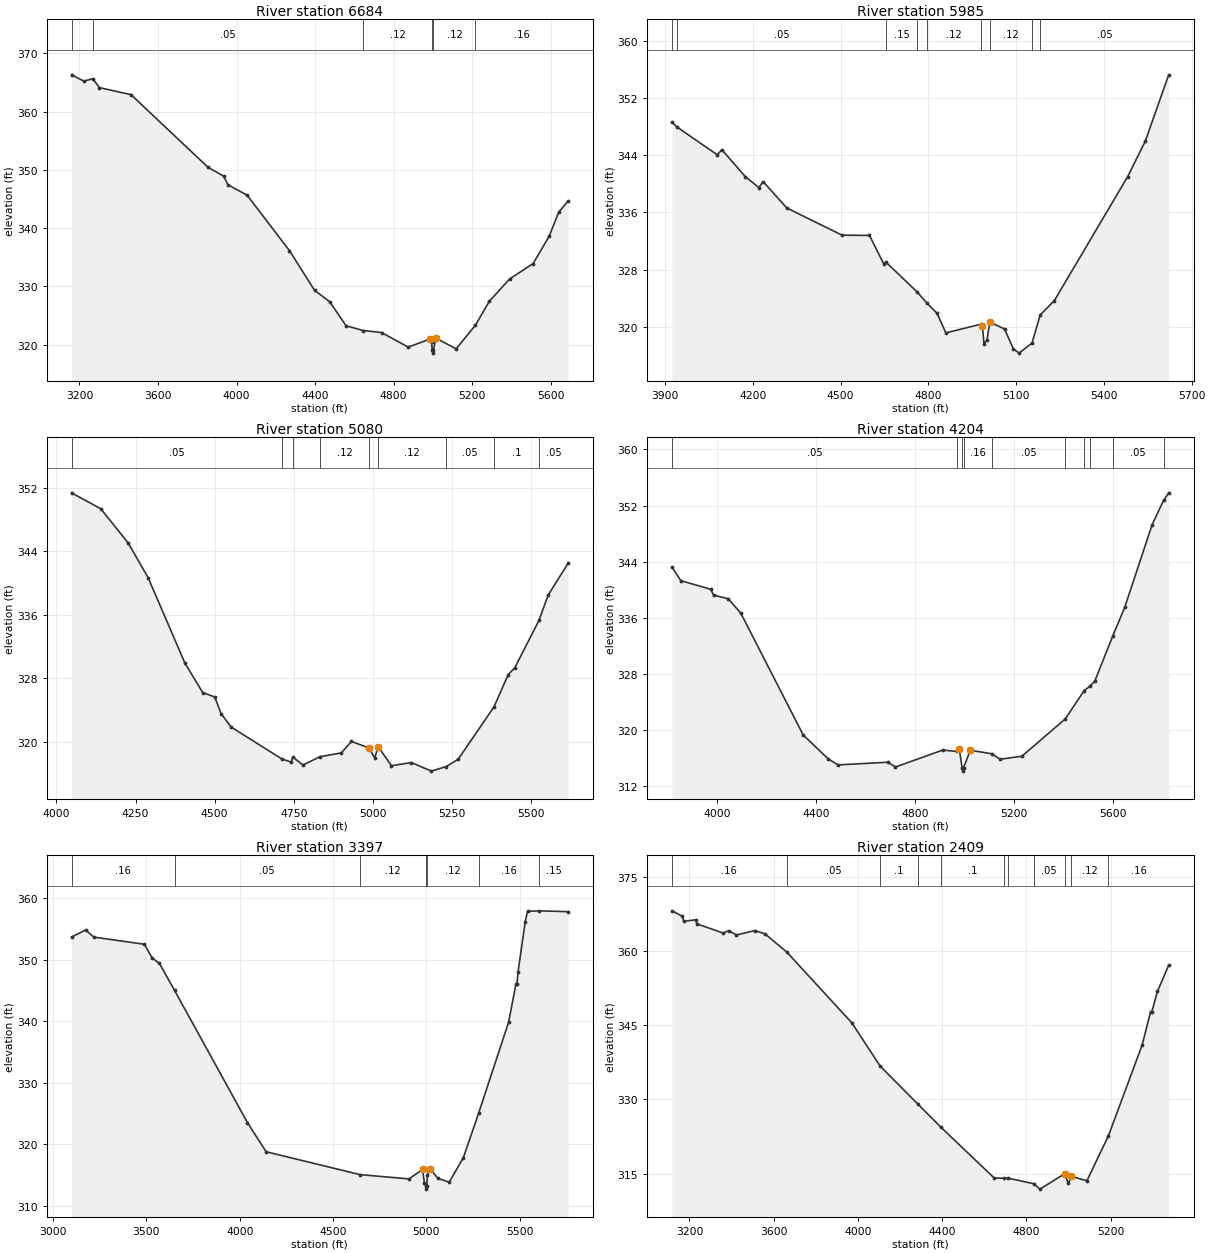
Type RM Length L Ch R = 1 ,6684    ,699,699,699
BEGIN DESCRIPTION:
REISS CREEK 12.0
END DESCRIPTION:
XS GIS Cut Line= 3
      3545892.71      10373463.4      3545732.98     10371796.73
      3545323.27     10371046.75
#Sta/Elev= 30
  3159.6  366.31  3222.5  365.23  3267.8  365.64    3302  364.11  3462.7  362.91
  3854.5  350.45  3934.9  348.92  3956.1  347.45  4053.7  345.67    4269  336.17
    4397  329.35  4474.3  327.39  4557.7  323.26  4644.5  322.45  4738.6   322.1
  4873.9   319.6  4987.2  321.02  4992.9  320.51  4996.2  319.07    4999  318.57
  5002.2  319.07  5014.7  321.14  5118.1  319.31  5216.6  323.37    5287  327.46
  5390.4  331.29    5510  333.94  5591.6  338.61  5640.9  342.79  5688.5  344.67
#Mann= 6 ,-1 , 0
  3159.6     .16       0  3267.8     .05       0  4644.5     .12       0
  4996.2     .07       0  5002.2     .12       0  5216.6     .16       0
Bank Sta=4987.2,5014.7
XS Rating Curve= 0 ,0
Exp/Cntr=0.3,0.1

Type RM Length L Ch R = 1 ,5985    ,905,905,905
BEGIN DESCRIPTION:
REISS CREEK 11.0
END DESCRIPTION:
XS GIS Cut Line= 3
      3546378.81     10372630.02      3546274.65     10371893.95
      3546342.11     10370941.64
#Sta/Elev= 30
  3923.4  348.61  3940.4  347.94  4078.3  344.05  4093.5  344.78  4174.3  340.99
  4220.4  339.47  4234.9  340.31  4315.7  336.62  4504.5  332.82  4598.4  332.78
  4646.6  328.85  4655.4  329.02  4760.4  324.92  4795.3   323.3  4829.5  321.89
  4859.6  319.15  4979.7  320.37  4984.8  320.12  4989.9  317.64  4999.9  318.12
    5010  320.65  5060.1   319.7  5090.2  316.93    5110  316.32  5154.4  317.75
  5182.1  321.66  5230.5  323.66  5481.1     341  5541.3  345.95  5621.5  355.24
#Mann= 9 ,-1 , 0
  3923.4     .16       0  3940.4     .05       0  4655.4     .15       0
  4760.4     .05       0  4795.3     .12       0  4979.7     .07       0
    5010     .12       0  5154.4     .16       0  5182.1     .05       0
Bank Sta=4984.8,5010
XS Rating Curve= 0 ,0
Exp/Cntr=0.3,0.1

Type RM Length L Ch R = 1 ,5080    ,876,876,876
BEGIN DESCRIPTION:
REISS CREEK 9.0
END DESCRIPTION:
XS GIS Cut Line= 3
      3547337.15     10372581.46      3547042.11     10371691.64
      3546842.11     10371091.65
#Sta/Elev= 30
  4047.5  351.38  4139.9  349.38  4226.4  345.07  4289.6  340.69  4405.5  329.96
  4462.1  326.21  4500.3  325.64  4520.2  323.56  4551.9  321.86  4711.4  317.86
    4742  317.43  4746.9  318.09    4779  317.07  4833.1  318.12  4900.5   318.6
  4932.2  320.04  4987.6  319.23    5006  317.98  5016.6   319.4  5058.7  316.98
    5122  317.38    5185   316.3  5231.9  316.88  5269.6  317.79    5383   324.4
  5427.7  328.45  5448.8  329.34  5525.1   335.3  5554.2  338.49  5617.4  342.52
#Mann= 9 ,-1 , 0
  4047.5     .05       0  4711.4     .12       0  4746.9     .05       0
  4833.1     .12       0  4987.6     .07       0  5016.6     .12       0
  5231.9     .05       0    5383      .1       0  5525.1     .05       0
Bank Sta=4987.6,5016.6
XS Rating Curve= 0 ,0
Exp/Cntr=0.3,0.1

Type RM Length L Ch R = 1 ,4204    ,807,807,807
BEGIN DESCRIPTION:
REISS CREEK 7.0
END DESCRIPTION:
XS GIS Cut Line= 3
      3547594.09     10372546.74       3547719.1     10371664.78
      3547587.33     10370555.15
#Sta/Elev= 30
  3816.7  343.22  3852.2  341.28  3973.3  340.05  3984.6  339.22    4044   338.7
  4094.5  336.66    4347  319.27    4448  315.86  4488.4     315  4689.3  315.38
    4720   314.7    4912  317.12    4969  316.91  4978.1  317.26  4989.6  314.61
  4992.4  314.11  4995.6  314.61  5022.8  317.09  5108.7  316.59  5143.5  315.81
  5231.2  316.23  5406.7  321.56  5482.6  325.57  5507.6  326.27  5526.3  326.97
  5598.2  333.34  5647.2  337.49  5757.9  349.26    5804  352.72  5824.9  353.81
#Mann= 10 ,-1 , 0
  3816.7     .05       0    4969     .16       0  4989.6     .07       0
  4995.6     .16       0  5108.7     .05       0  5406.7     .16       0
  5482.6     .05       0  5507.6     .16       0  5598.2     .05       0
    5804     .16       0
Bank Sta=4978.1,5022.8
XS Rating Curve= 0 ,0
Exp/Cntr=0.3,0.1

Type RM Length L Ch R = 1 ,3397    ,988,988,988
BEGIN DESCRIPTION:
REISS CREEK 5.0
END DESCRIPTION:
XS GIS Cut Line= 3
      3548170.49     10373310.58      3548309.37     10371685.61
      3548524.65     10370678.66
#Sta/Elev= 30
  3098.9  353.68  3174.9  354.83  3218.3  353.67  3489.3  352.51  3531.6  350.25
  3569.5  349.42  3650.9  345.01  4041.3  323.54  4141.6  318.79  4644.4  315.08
  4906.4  314.38  4979.3  315.91  4989.5   313.7  4996.7  313.22  4999.5  312.72
  5002.7  313.22  5005.4  315.08  5020.2  316.06  5061.1  314.46  5122.4  313.86
  5198.2  317.84  5279.8  325.06  5440.5  339.85  5479.7  346.06  5484.8  345.97
  5490.6  347.92  5529.2  356.15  5541.7  357.85  5603.4  357.94  5759.5   357.8
#Mann= 7 ,-1 , 0
  3098.9     .16       0  3650.9     .05       0  4644.4     .12       0
  4996.7     .07       0  5002.7     .12       0  5279.8     .16       0
  5603.4     .15       0
Bank Sta=4979.3,5020.2
XS Rating Curve= 0 ,0
Exp/Cntr=0.3,0.1

Type RM Length L Ch R = 1 ,2409    ,836,836,836
BEGIN DESCRIPTION:
REISS CREEK 4.0
END DESCRIPTION:
XS GIS Cut Line= 3
      3549684.37     10373130.06      3549239.93      10371824.5
       3548942.1     10370891.62
#Sta/Elev= 30
  3117.1  368.12  3166.8  367.01  3172.1  365.99  3229.5  366.31  3234.8  365.49
  3360.3  363.63  3386.3  364.12    3423  363.24  3511.8  364.14  3559.1  363.44
    3661  359.83  3971.1  345.47  4105.1  336.75  4284.2  329.07  4393.5   324.4
  4646.2  314.15  4695.6  314.05  4710.7  314.11  4834.7  312.96    4864  311.87
  4982.1  314.99  4998.3  313.02  5013.6  314.44  5087.1  313.56  5189.3  322.65
  5349.5     341  5389.8  347.77    5395  347.65    5422  351.84  5475.5  357.13
#Mann= 11 ,-1 , 0
  3117.1     .16       0    3661     .05       0  4105.1      .1       0
  4284.2     .05       0  4393.5      .1       0  4695.6     .05       0
  4710.7     .12       0  4834.7     .05       0  4982.1     .07       0
  5013.6     .12       0  5189.3     .16       0
Bank Sta=4982.1,5013.6
XS Rating Curve= 0 ,0
Exp/Cntr=0.3,0.1

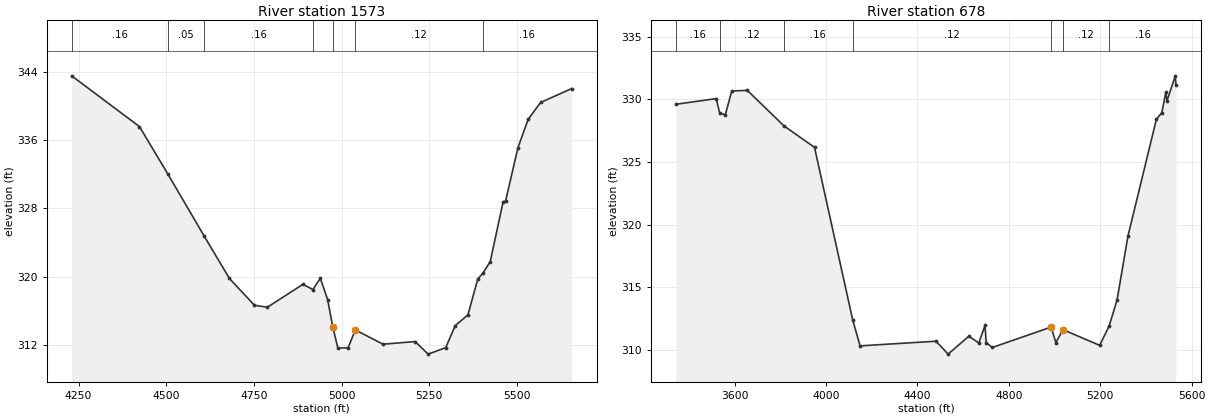
Type RM Length L Ch R = 1 ,1573    ,895,895,895
BEGIN DESCRIPTION:
REISS CREEK 3.0
END DESCRIPTION:
XS GIS Cut Line= 3
      3550203.22     10371837.48      3549903.22     10371337.48
      3549393.41     10370665.71
#Sta/Elev= 30
  4230.2  343.52  4423.6  337.58  4504.9  332.01  4608.8  324.73  4680.2  319.81
  4751.7  316.67  4788.6  316.45  4889.6  319.12  4918.4  318.52  4939.5  319.83
  4960.4  317.33  4974.9  314.16  4989.5  311.68  5018.6  311.69  5039.4  313.79
  5118.4  312.12    5210  312.43  5247.1  310.96  5297.2  311.72  5324.3   314.3
  5360.4  315.54  5388.8  319.76    5403  320.41  5424.2  321.78  5460.9  328.78
  5467.8  328.84  5503.2  335.11  5532.3  338.42  5567.7   340.4  5656.6  342.03
#Mann= 7 ,-1 , 0
  4230.2     .16       0  4504.9     .05       0  4608.8     .16       0
  4918.4     .12       0  4974.9     .07       0  5039.4     .12       0
    5403     .16       0
Bank Sta=4974.9,5039.4
XS Rating Curve= 0 ,0
Exp/Cntr=0.3,0.1

Type RM Length L Ch R = 1 ,678     ,0,0,0
BEGIN DESCRIPTION:
REISS CREEK 1.0
END DESCRIPTION:
XS GIS Cut Line= 3
      3550941.34     10371859.27      3550371.87     10370664.78
      3549531.99     10370456.54
#Sta/Elev= 30
  3342.7   329.6    3519  330.05  3533.9  328.92  3558.9  328.75  3587.1  330.66
  3655.2  330.71    3816  327.87  3949.4  326.16  4116.4   312.4  4148.8  310.32
  4481.1  310.69  4534.1  309.66  4625.1  311.09  4668.4  310.55  4695.7  311.96
  4700.8  310.58  4727.6  310.19  4985.1  311.82  5005.7  310.58    5037  311.61
  5197.4  310.36  5238.8   311.9  5273.6  313.99  5321.5   319.1  5445.7   328.4
  5469.4  328.93  5487.1  330.56  5492.2  329.88  5528.5  331.87  5531.3  331.11
#Mann= 7 ,-1 , 0
  3342.7     .16       0  3533.9     .12       0    3816     .16       0
  4116.4     .12       0  4985.1     .07       0    5037     .12       0
  5238.8     .16       0
Bank Sta=4985.1,5037
XS Rating Curve= 0 ,0
Exp/Cntr=0.3,0.1

Chan Stop Cuts=-1
Use User Specified Reach Order=0
Composite Channel Slope=5