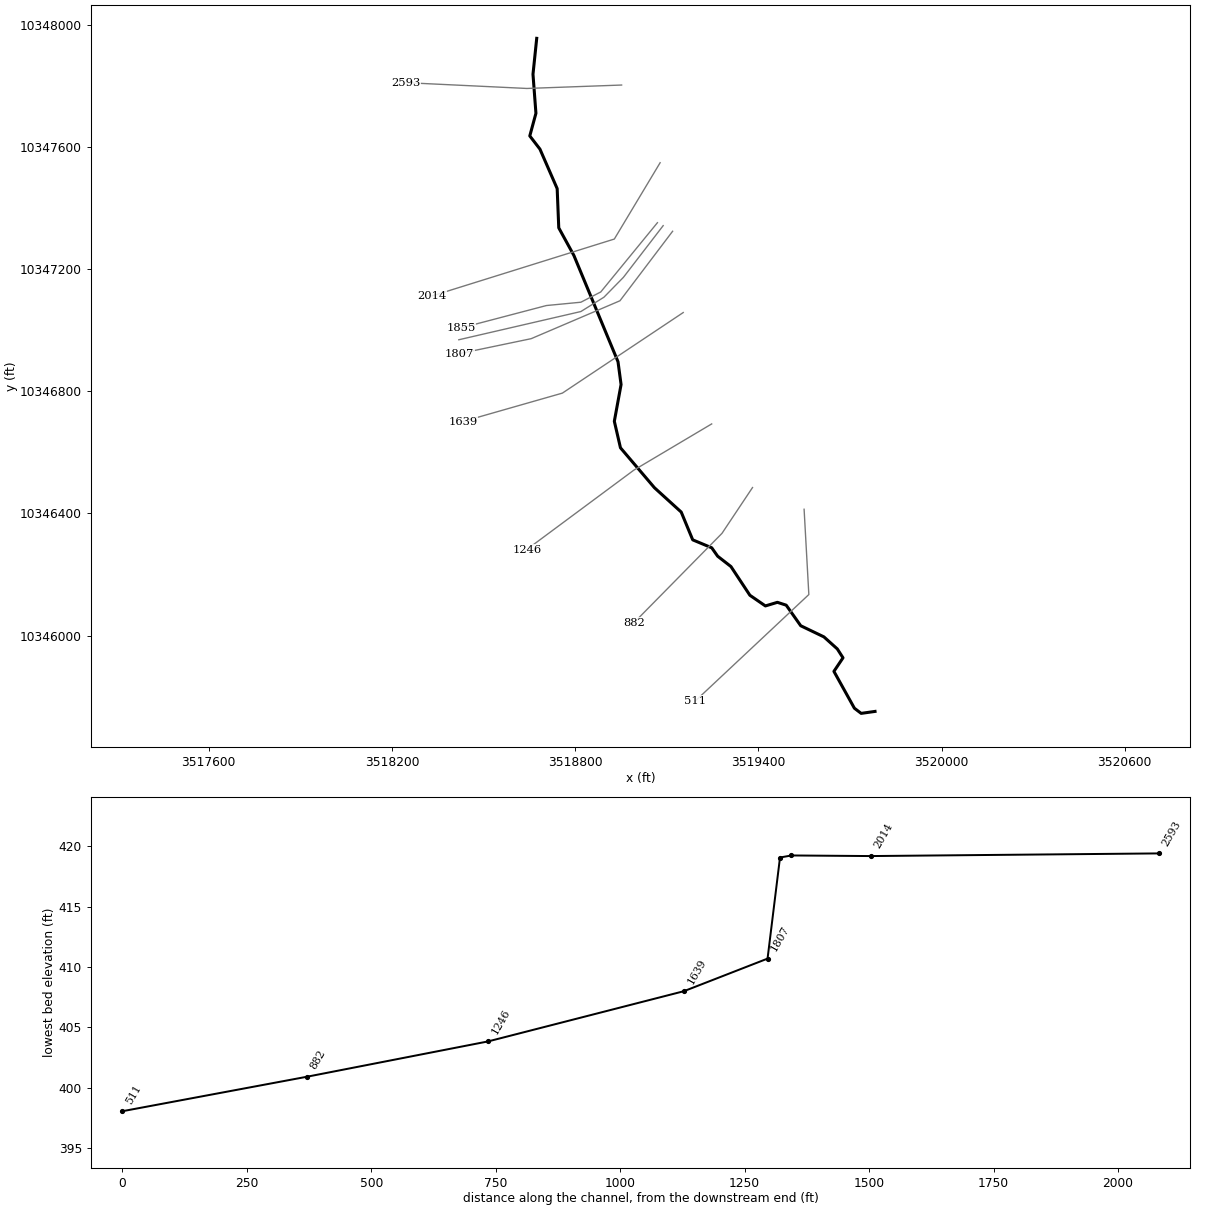
--- ROCKY BRANCH TRIBUTARY 1.prj (project) ---

Proj Title=ROCKY BRANCH TRIBUTARY 1 Base Level Engineering
Current Plan=p01
Default Exp/Contr=0.3,0.1
English Units
Geom File=g01
Flow File=f01
Plan File=p01
BEGIN DESCRIPTION:
ROCKY BRANCH TRIBUTARY 1
END DESCRIPTION:

--- ROCKY BRANCH TRIBUTARY 1.p01 (plan) ---

Plan Title=Multiple Run
Short Identifier=Multiple
Geom File=g01
Flow File=f01
Subcritical Flow
K Sum by GR= 0
Std Step Tol= 0.01
Critical Tol= 0.01
Num of Std Step Trials= 20
Max Error Tol= 0.3
Flow Tol Ratio= 0.001
Split Flow NTrial= 30
Split Flow Tol= 0.02
Split Flow Ratio= 0.02
Log Output Level= 0
Friction Slope Method= 1
Unsteady Friction Slope Method= 2
Unsteady Bridges Friction Slope Method= 1
Parabolic Critical Depth
Global Vel Dist=  1 , 1 , 1
Global Log Level= 0
CheckData=True
Encroach Param= -1, 0, 0, 0
BEGIN DESCRIPTION:
Multiple Run
END DESCRIPTION:

--- ROCKY BRANCH TRIBUTARY 1.f01 (steady flow) ---

Flow Title=Multiple
Number of Profiles=7
Profile Names=10-year,25-year,50-year,1pct_min,100-year,1pct_plu,500-year
River Rch & RM= ROCKY BRANCH TRI,Reach-1,2593
     245     316     372     323     436     590     599
Boundary for River Rch & Prof#=ROCKY BRANCH TRI,Reach-1,1
Up Type=0
Dn Type=3
Dn Slope=0.005
Boundary for River Rch & Prof#=ROCKY BRANCH TRI,Reach-1,2
Up Type=0
Dn Type=3
Dn Slope=0.005
Boundary for River Rch & Prof#=ROCKY BRANCH TRI,Reach-1,3
Up Type=0
Dn Type=3
Dn Slope=0.005
Boundary for River Rch & Prof#=ROCKY BRANCH TRI,Reach-1,4
Up Type=0
Dn Type=3
Dn Slope=0.005
Boundary for River Rch & Prof#=ROCKY BRANCH TRI,Reach-1,5
Up Type=0
Dn Type=3
Dn Slope=0.005
Boundary for River Rch & Prof#=ROCKY BRANCH TRI,Reach-1,6
Up Type=0
Dn Type=3
Dn Slope=0.005
Boundary for River Rch & Prof#=ROCKY BRANCH TRI,Reach-1,7
Up Type=0
Dn Type=3
Dn Slope=0.005

--- ROCKY BRANCH TRIBUTARY 1.g01 (geometry) ---

Geom Title=Existing Conditions

River Reach=ROCKY BRANCH TRI,Reach-1
Reach XY= 30
      3518674.21     10347955.80      3518662.00     10347838.14
      3518671.64     10347710.36      3518651.52     10347636.20
      3518684.77     10347593.01      3518741.19     10347463.67
      3518746.40     10347335.20      3518795.88     10347244.92
      3518940.43     10346896.71      3518950.44     10346822.03
      3518928.37     10346701.78      3518948.44     10346614.96
      3519059.75     10346484.15      3519147.42     10346404.43
      3519185.03     10346313.51      3519247.35     10346287.46
      3519266.68     10346259.94      3519310.24     10346226.04
      3519372.32     10346131.98      3519423.05     10346097.08
      3519462.35     10346108.89      3519491.23     10346099.55
      3519538.75     10346032.21      3519614.72     10345995.71
      3519658.56     10345956.29      3519677.21     10345927.17
      3519647.46     10345882.78      3519714.52     10345762.13
      3519736.66     10345745.23      3519782.11     10345751.64

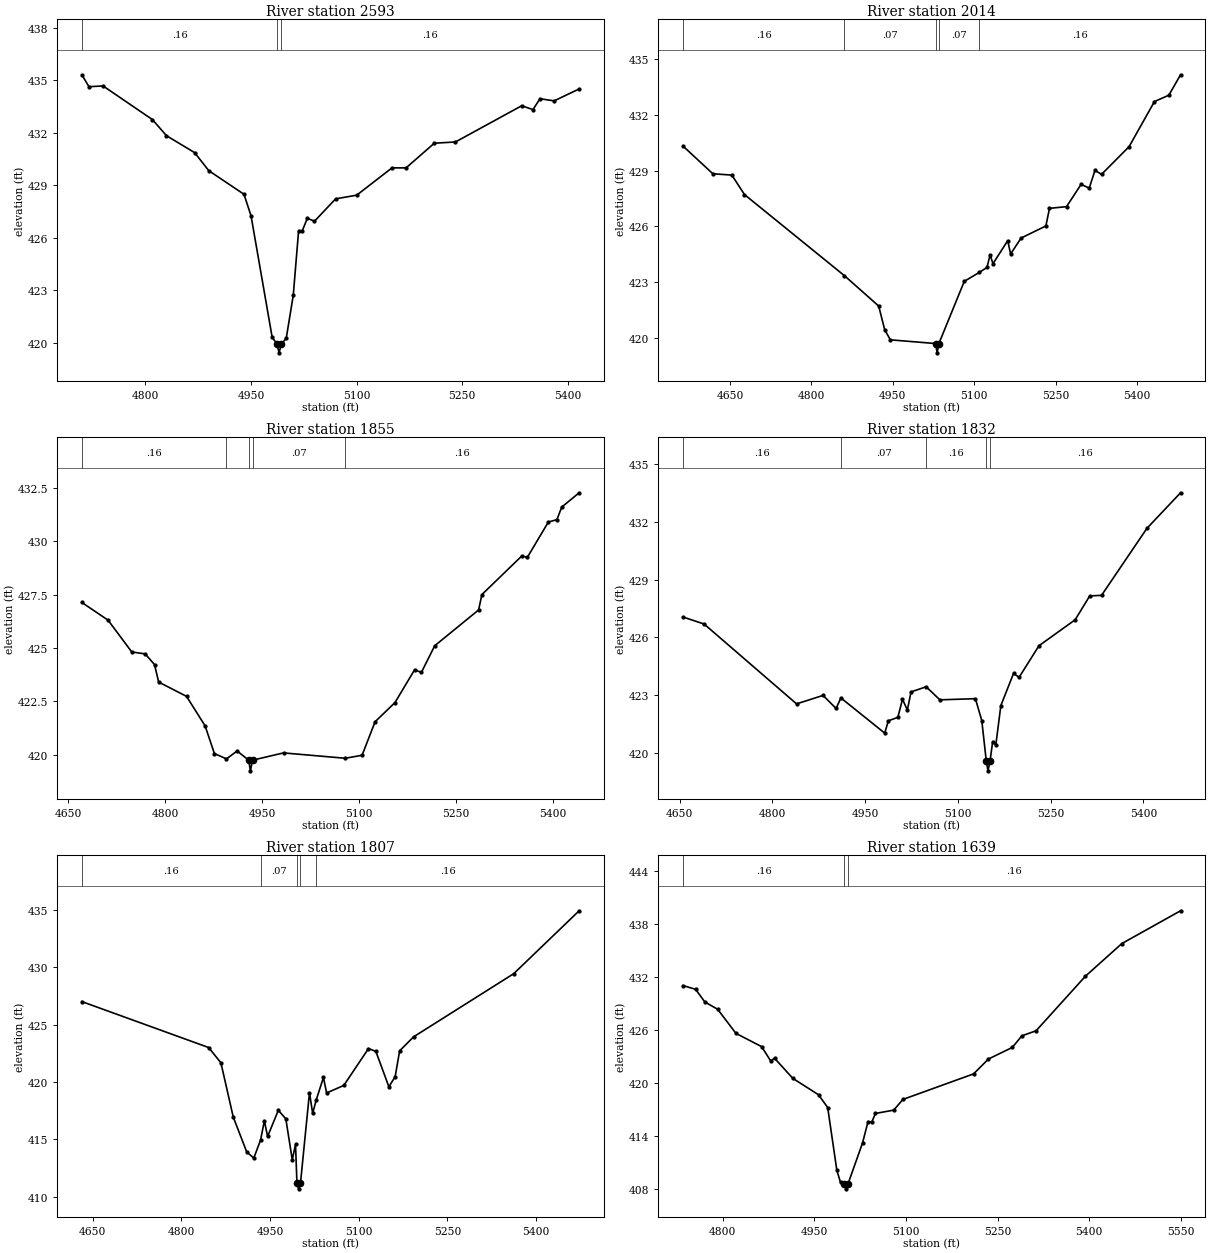
Type RM Length L Ch R = 1,2593,579,579,579
BEGIN DESCRIPTION:
ROCKY BRANCH TRIBUTARY 1 6.0
END DESCRIPTION:
XS GIS Cut Line= 3
      3518952.24     10347802.86      3518642.11     10347791.64
      3518246.60     10347810.59
#Sta/Elev= 30
  4709.7  435.30  4719.8  434.62  4739.9  434.66  4809.9  432.74  4829.9  431.82
  4869.9  430.85  4890.0  429.82  4940.0  428.47  4950.0  427.24  4980.0  420.30
  4987.0  419.91  4989.8  419.41  4993.0  419.91  5000.0  420.24  5010.0  422.71
  5017.5  426.36  5022.5  426.36  5030.0  427.10  5040.1  426.93  5070.1  428.21
  5100.1  428.42  5150.2  429.98  5170.2  429.98  5210.3  431.39  5240.3  431.46
  5334.4  433.53  5350.4  433.31  5360.4  433.93  5380.5  433.81  5416.0  434.49
#Mann=3,-1,0
  4709.7    0.16       0  4987.0    0.07       0  4993.0    0.16       0
Bank Sta=4987,4993
Exp/Cntr=0.3,0.1

Type RM Length L Ch R = 1,2014,159,159,159
BEGIN DESCRIPTION:
ROCKY BRANCH TRIBUTARY 1 5.0
END DESCRIPTION:
XS GIS Cut Line= 3
      3519078.34     10347548.49      3518928.36     10347298.52
      3518331.48     10347112.20
#Sta/Elev= 30
  4563.7  430.31  4618.3  428.83  4653.3  428.76  4676.6  427.71  4860.6  423.35
  4924.0  421.71  4935.1  420.43  4945.6  419.89  5029.0  419.69  5031.7  419.19
  5035.0  419.69  5081.8  423.04  5109.5  423.52  5123.7  423.79  5129.4  424.47
  5134.7  423.99  5161.9  425.23  5167.2  424.51  5186.5  425.37  5232.2  426.02
  5238.9  426.97  5270.3  427.06  5297.1  428.26  5312.2  428.06  5322.7  429.01
  5334.9  428.80  5385.6  430.29  5432.4  432.72  5458.9  433.06  5480.5  434.16
#Mann=5,-1,0
  4563.7    0.16       0  4860.6    0.07       0  5029.0    0.07       0
  5035.0    0.07       0  5109.5    0.16       0
Bank Sta=5029,5035
Exp/Cntr=0.3,0.1

Type RM Length L Ch R = 1,1855,23,23,23
BEGIN DESCRIPTION:
ROCKY BRANCH TRIBUTARY 1 4.03
END DESCRIPTION:
XS GIS Cut Line= 5
      3519069.51     10347352.08      3518883.95     10347125.28
      3518818.85     10347091.65      3518706.00     10347080.80
      3518426.07     10347007.30
#Sta/Elev= 30
  4671.1  427.13  4711.7  426.30  4748.3  424.81  4769.1  424.72  4783.5  424.22
  4789.9  423.40  4833.0  422.73  4861.7  421.35  4876.1  420.05  4894.8  419.80
  4911.2  420.17  4929.1  419.74  4931.8  419.24  4935.1  419.74  4983.0  420.08
  5078.4  419.83  5104.5  419.97  5124.6  421.54  5155.4  422.44  5185.8  423.98
  5196.2  423.85  5216.8  425.10  5284.7  426.78  5289.8  427.50  5351.2  429.30
  5360.2  429.25  5392.6  430.90  5405.8  431.01  5413.3  431.60  5440.2  432.27
#Mann=5,-1,0
  4671.1    0.16       0  4894.8    0.07       0  4929.1    0.07       0
  4935.1    0.07       0  5078.4    0.16       0
Bank Sta=4929.1,4935.1
Exp/Cntr=0.3,0.1

Type RM Length L Ch R = 1,1832,25,25,25
BEGIN DESCRIPTION:
ROCKY BRANCH TRIBUTARY 1 4.01
END DESCRIPTION:
XS GIS Cut Line= 5
      3519088.34     10347342.42      3518958.12     10347173.13
      3518894.32     10347108.02      3518818.80     10347061.15
      3518419.07     10346968.70
#Sta/Elev= 30
  4656.0  427.06  4689.7  426.70  4839.2  422.55  4882.0  422.99  4903.1  422.31
  4910.8  422.86  4981.7  421.03  4987.5  421.67  5002.9  421.85  5010.4  422.79
  5018.3  422.23  5024.2  423.17  5048.7  423.44  5070.8  422.76  5128.3  422.82
  5138.6  421.68  5145.9  419.57  5148.6  419.07  5151.9  419.57  5156.2  420.59
  5161.3  420.42  5169.4  422.46  5189.9  424.13  5198.9  423.93  5231.0  425.57
  5289.5  426.92  5313.1  428.16  5332.2  428.19  5405.5  431.67  5459.9  433.52
#Mann=5,-1,0
  4656.0    0.16       0  4910.8    0.07       0  5048.7    0.16       0
  5145.9    0.07       0  5151.9    0.16       0
Bank Sta=5145.9,5151.9
Exp/Cntr=0.3,0.1

Type RM Length L Ch R = 1,1807,168,168,168
BEGIN DESCRIPTION:
ROCKY BRANCH TRIBUTARY 1 4.02
END DESCRIPTION:
XS GIS Cut Line= 4
      3519119.23     10347324.04      3518946.83     10347096.42
      3518656.08     10346972.29      3518421.69     10346923.46
#Sta/Elev= 30
  4631.6  427.00  4846.0  423.00  4866.8  421.67  4887.7  416.94  4910.5  413.90
  4922.4  413.37  4933.9  414.94  4940.3  416.62  4945.8  415.25  4963.9  417.53
  4976.6  416.79  4987.5  413.22  4993.0  414.57  4995.4  411.19  4998.2  410.69
  5001.4  411.19  5016.6  419.07  5022.0  417.26  5028.0  418.43  5040.2  420.39
  5045.6  419.04  5074.7  419.70  5116.4  422.91  5128.9  422.66  5150.9  419.58
  5161.5  420.46  5169.1  422.71  5192.7  423.93  5362.0  429.43  5472.7  434.91
#Mann=5,-1,0
  4631.6    0.16       0  4933.9    0.07       0  4995.4    0.07       0
  5001.4    0.07       0  5028.0    0.16       0
Bank Sta=4995.4,5001.4
Exp/Cntr=0.3,0.1

Type RM Length L Ch R = 1,1639,393,393,393
BEGIN DESCRIPTION:
ROCKY BRANCH TRIBUTARY 1 4.0
END DESCRIPTION:
XS GIS Cut Line= 3
      3519154.01     10347057.84      3518758.26     10346794.01
      3518432.34     10346700.88
#Sta/Elev= 30
  4735.1  431.04  4755.4  430.62  4770.4  429.19  4791.4  428.36  4821.5  425.62
  4863.5  424.12  4878.5  422.48  4884.6  422.81  4914.6  420.52  4956.7  418.66
  4971.7  417.21  4986.7  410.09  4992.7  408.72  4998.7  408.49  5001.5  407.99
  5004.7  408.49  5028.8  413.20  5037.8  415.62  5043.8  415.54  5049.9  416.54
  5079.9  416.92  5094.9  418.13  5210.7  421.03  5235.1  422.72  5274.1  424.03
  5289.9  425.35  5313.1  425.92  5393.9  432.11  5453.5  435.81  5549.7  439.53
#Mann=3,-1,0
  4735.1    0.16       0  4998.7    0.07       0  5004.7    0.16       0
Bank Sta=4998.7,5004.7
Exp/Cntr=0.3,0.1

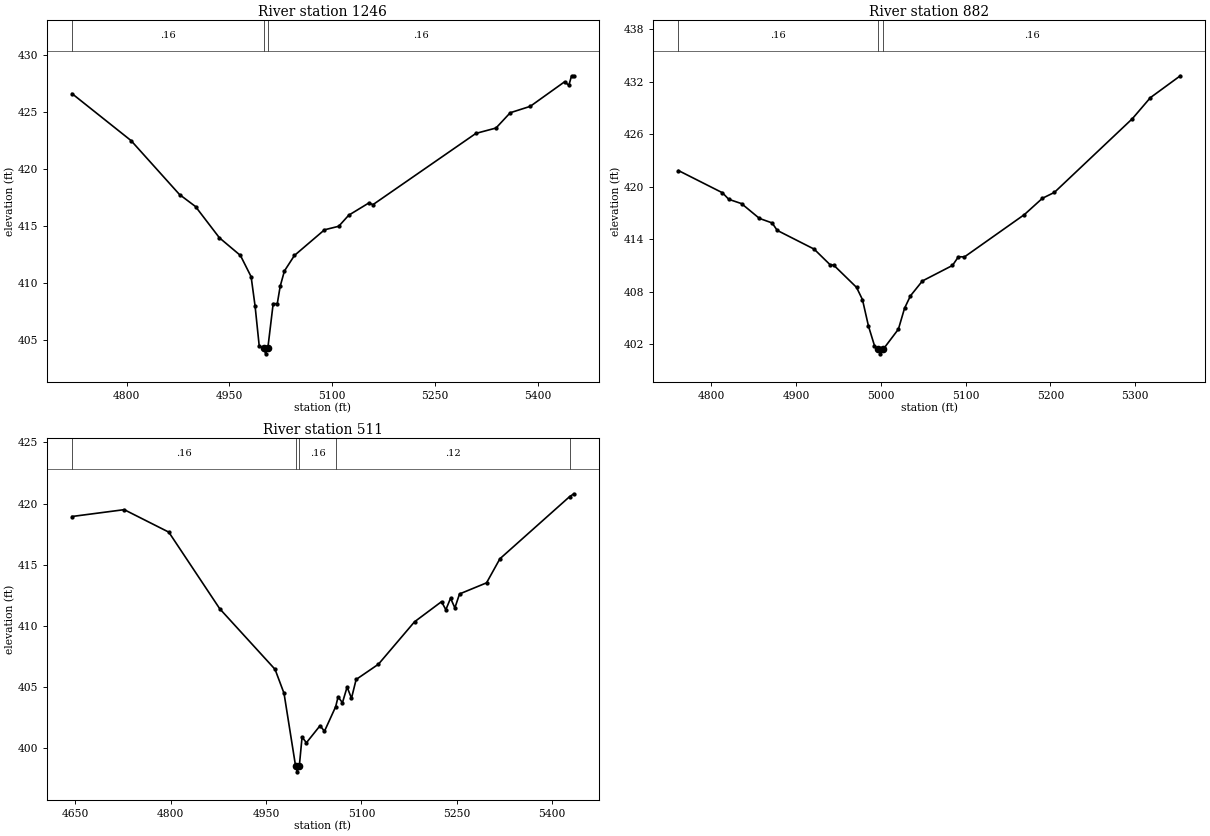
Type RM Length L Ch R = 1,1246,364,364,364
BEGIN DESCRIPTION:
ROCKY BRANCH TRIBUTARY 1 3.0
END DESCRIPTION:
XS GIS Cut Line= 3
      3519247.18     10346693.13      3518992.11     10346541.64
      3518641.83     10346281.80
#Sta/Elev= 30
  4720.0  426.64  4806.3  422.52  4877.1  417.79  4900.4  416.74  4935.3  414.00
  4966.0  412.45  4981.6  410.59  4987.4  408.01  4993.4  404.53  5000.0  404.33
  5002.8  403.83  5006.0  404.33  5013.8  408.23  5019.8  408.23  5024.0  409.74
  5030.2  411.09  5044.8  412.45  5088.7  414.70  5109.5  415.01  5124.1  415.98
  5153.4  417.05  5159.6  416.91  5309.8  423.15  5339.1  423.62  5359.9  424.96
  5389.1  425.52  5439.2  427.67  5445.5  427.37  5449.5  428.20  5452.8  428.20
#Mann=3,-1,0
  4720.0    0.16       0  5000.0    0.07       0  5006.0    0.16       0
Bank Sta=5000,5006
Exp/Cntr=0.3,0.1

Type RM Length L Ch R = 1,882,371,371,371
BEGIN DESCRIPTION:
ROCKY BRANCH TRIBUTARY 1 2.0
END DESCRIPTION:
XS GIS Cut Line= 3
      3519380.93     10346484.80      3519280.91     10346334.77
      3518992.11     10346041.65
#Sta/Elev= 30
  4761.3  421.85  4813.2  419.31  4820.7  418.56  4835.7  418.07  4856.8  416.38
  4871.8  415.86  4877.8  415.01  4921.3  412.87  4940.5  411.05  4944.3  411.05
  4971.3  408.50  4978.3  407.10  4985.4  404.07  4992.5  401.83  4996.6  401.40
  4999.3  400.90  5002.6  401.40  5020.7  403.72  5027.9  406.10  5034.9  407.53
  5049.0  409.23  5084.4  411.00  5091.5  412.00  5098.6  411.98  5169.3  416.82
  5190.5  418.68  5204.6  419.35  5296.6  427.78  5317.8  430.18  5353.1  432.68
#Mann=3,-1,0
  4761.3    0.16       0  4996.6    0.07       0  5002.6    0.16       0
Bank Sta=4996.6,5002.6
Exp/Cntr=0.3,0.1

Type RM Length L Ch R = 1,511,0,0,0
BEGIN DESCRIPTION:
ROCKY BRANCH TRIBUTARY 1 1.0
END DESCRIPTION:
XS GIS Cut Line= 3
      3519549.82     10346413.70      3519565.34     10346134.37
      3519193.61     10345785.88
#Sta/Elev= 30
  4644.7  418.94  4726.9  419.50  4797.0  417.66  4877.1  411.39  4964.1  406.43
  4978.2  404.47  4996.3  398.54  4999.0  398.04  5002.3  398.54  5006.6  400.89
  5013.4  400.42  5034.9  401.82  5041.8  401.36  5059.4  403.37  5063.2  404.17
  5070.1  403.70  5077.4  404.98  5084.3  404.06  5091.6  405.60  5126.7  406.85
  5183.4  410.32  5225.9  411.97  5232.7  411.31  5240.1  412.25  5246.9  411.46
  5254.2  412.60  5296.7  413.51  5317.7  415.48  5427.4  420.57  5434.0  420.80
#Mann=5,-1,0
  4644.7    0.16       0  4996.3    0.07       0  5002.3    0.16       0
  5059.4    0.12       0  5427.4    0.16       0
Bank Sta=4996.3,5002.3
Exp/Cntr=0.3,0.1

Chan Stop Cuts=-1