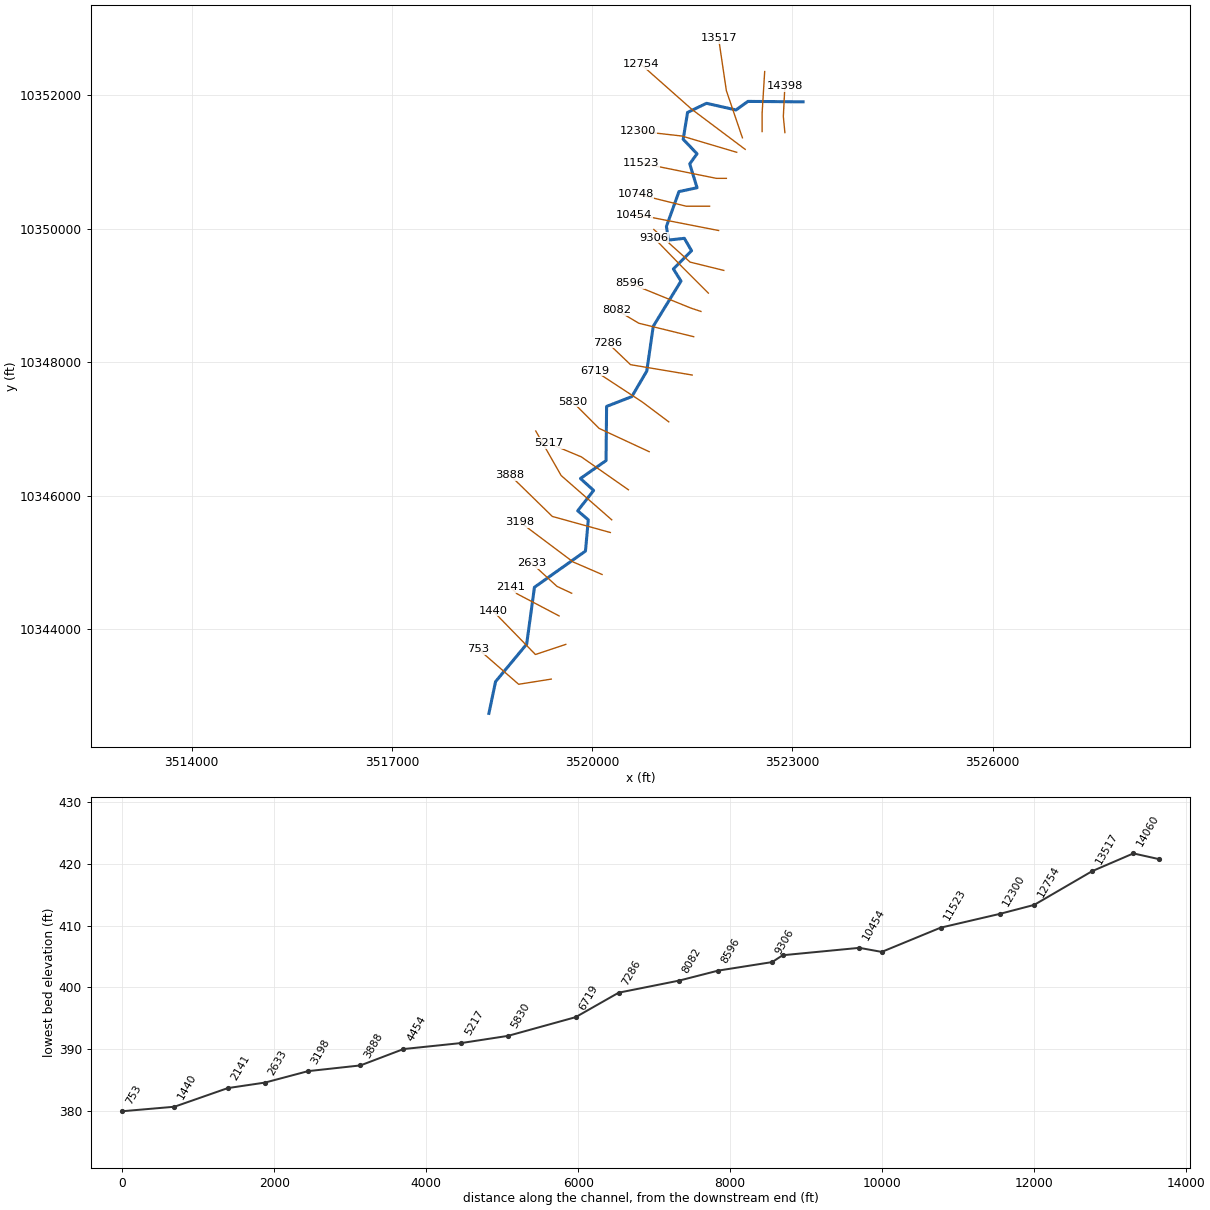
--- ROCKY BRANCH.prj (project) ---

Proj Title=ROCKY BRANCH Base Level Engineering
Current Plan=p01
Default Exp/Contr=0.3,0.1
English Units
Geom File=g01
Flow File=f01
Plan File=p01
BEGIN DESCRIPTION:
ROCKY BRANCH
END DESCRIPTION:

--- ROCKY BRANCH.p01 (plan) ---

Plan Title=Multiple Run
Short Identifier=Multiple
Geom File=g01
Flow File=f01
Subcritical Flow
K Sum by GR= 0
Std Step Tol= 0.01
Critical Tol= 0.01
Num of Std Step Trials= 20
Max Error Tol= 0.3
Flow Tol Ratio= 0.001
Split Flow NTrial= 30
Split Flow Tol= 0.02
Split Flow Ratio= 0.02
Log Output Level= 0
Friction Slope Method= 1
Unsteady Friction Slope Method= 2
Unsteady Bridges Friction Slope Method= 1
Parabolic Critical Depth
Global Vel Dist=  1 , 1 , 1
Global Log Level= 0
CheckData=True
Encroach Param= -1, 0, 0, 0
BEGIN DESCRIPTION:
Multiple Run
END DESCRIPTION:

--- ROCKY BRANCH.f01 (steady flow) ---

Flow Title=Multiple
Number of Profiles=7
Profile Names=10-year,25-year,50-year,1pct_min,100-year,1pct_plu,500-year
River Rch & RM= ROCKY BRANCH,Reach-1,14398
     779    1071    1311    1173    1587    2146    2318
River Rch & RM= ROCKY BRANCH,Reach-1,14060
    1782    2560    3227    2964    4009    5422    6178
River Rch & RM= ROCKY BRANCH,Reach-1,10748
    1859    2666    3358    3080    4165    5633    6408
River Rch & RM= ROCKY BRANCH,Reach-1,3888
    1847    2640    3319    3038    4109    5557    6299
Boundary for River Rch & Prof#=ROCKY BRANCH,Reach-1,1
Up Type=0
Dn Type=3
Dn Slope=0.005
Boundary for River Rch & Prof#=ROCKY BRANCH,Reach-1,2
Up Type=0
Dn Type=3
Dn Slope=0.005
Boundary for River Rch & Prof#=ROCKY BRANCH,Reach-1,3
Up Type=0
Dn Type=3
Dn Slope=0.005
Boundary for River Rch & Prof#=ROCKY BRANCH,Reach-1,4
Up Type=0
Dn Type=3
Dn Slope=0.005
Boundary for River Rch & Prof#=ROCKY BRANCH,Reach-1,5
Up Type=0
Dn Type=3
Dn Slope=0.005
Boundary for River Rch & Prof#=ROCKY BRANCH,Reach-1,6
Up Type=0
Dn Type=3
Dn Slope=0.005
Boundary for River Rch & Prof#=ROCKY BRANCH,Reach-1,7
Up Type=0
Dn Type=3
Dn Slope=0.005

--- ROCKY BRANCH.g01 (geometry) ---

Geom Title=Existing Conditions

River Reach=ROCKY BRANCH,Reach-1
Reach XY= 30
      3523159.19     10351903.41      3522332.56     10351910.28
      3522154.35     10351781.85      3521712.11     10351881.64
      3521428.31     10351744.68      3521363.04     10351342.03
      3521570.62     10351125.71      3521461.19     10350973.96
      3521570.69     10350616.87      3521299.65     10350558.77
      3521111.88     10350036.87      3521143.03     10349832.73
      3521380.43     10349858.63      3521488.34     10349672.79
      3521215.79     10349400.06      3521330.13     10349218.11
      3520914.36     10348540.63      3520817.31     10347869.31
      3520593.02     10347487.21      3520215.44     10347340.46
      3520207.13     10346528.96      3519823.69     10346260.58
      3520021.27     10346081.45      3519782.62     10345776.64
      3519941.13     10345641.38      3519898.96     10345172.96
      3519134.35     10344631.03      3519017.77     10343778.76
      3518551.68     10343216.91      3518452.11     10342741.64

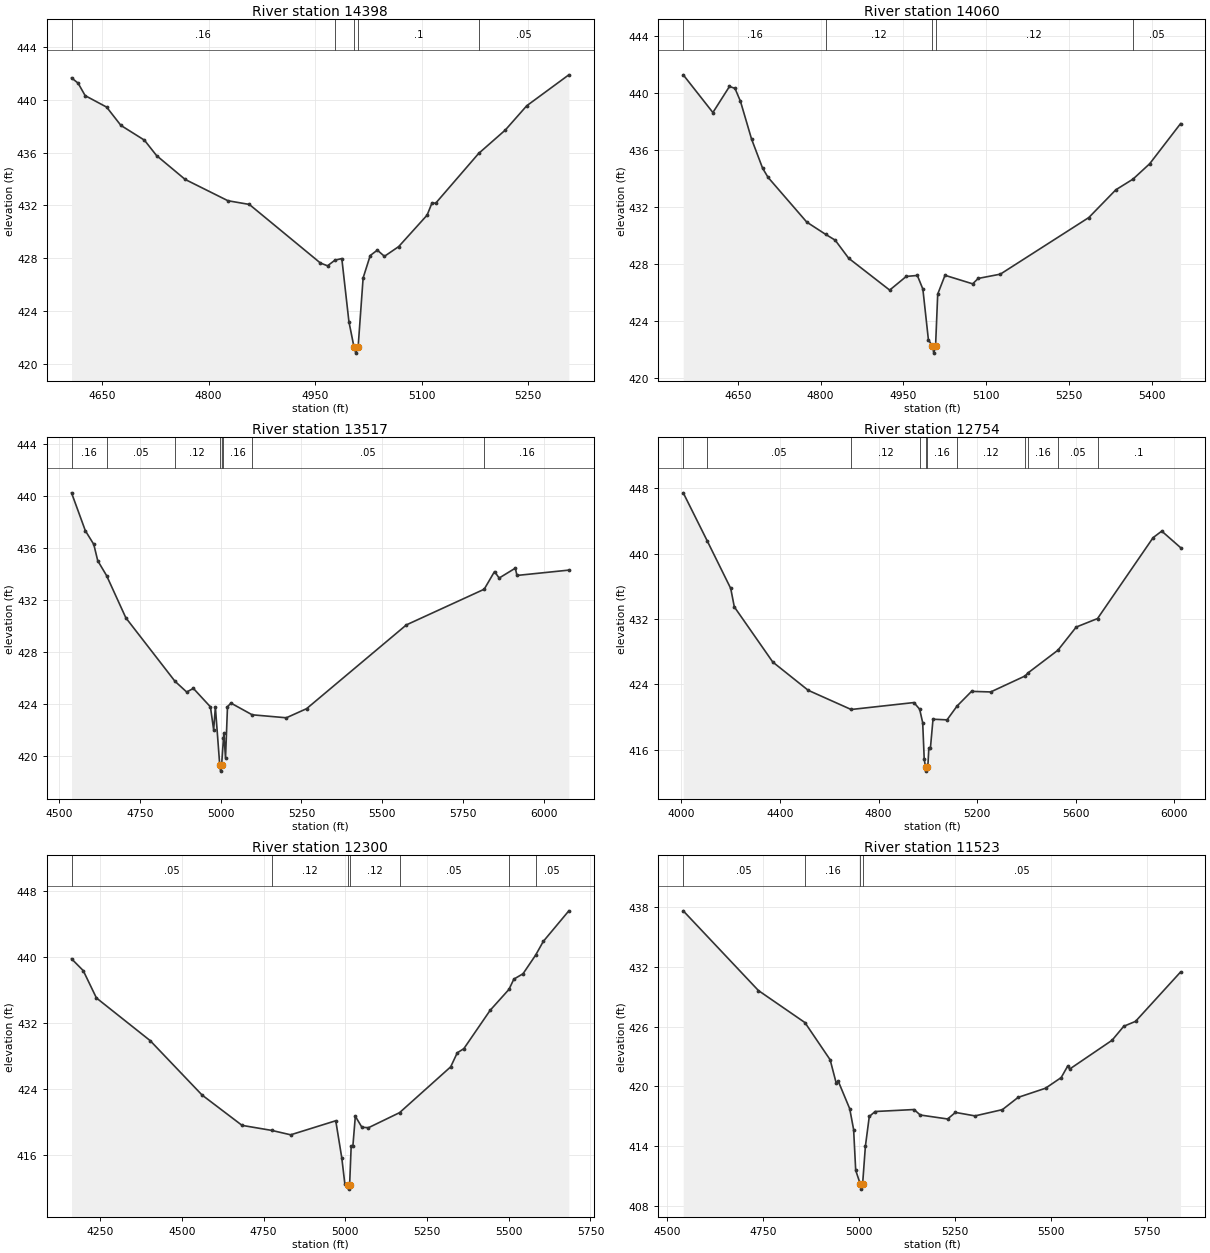
Type RM Length L Ch R = 1,14398,338,338,338
BEGIN DESCRIPTION:
ROCKY BRANCH 28.0
END DESCRIPTION:
XS GIS Cut Line= 3
      3522886.79     10351442.49      3522863.51     10351683.06
      3522886.79     10352140.88
#Sta/Elev= 30
  4607.0  441.69  4616.2  441.29  4626.2  440.34  4656.4  439.47  4676.5  438.08
  4709.6  436.96  4726.7  435.79  4766.9  433.98  4827.2  432.36  4857.3  432.08
  4957.4  427.63  4967.4  427.42  4977.9  427.85  4987.5  427.97  4997.5  423.18
  5004.5  421.29  5007.2  420.79  5010.5  421.29  5017.5  426.50  5027.5  428.20
  5037.5  428.61  5047.5  428.14  5067.6  428.88  5107.6  431.27  5114.5  432.20
  5119.6  432.17  5180.1  435.95  5217.7  437.73  5247.8  439.57  5307.1  441.92
#Mann=5,-1,0
  4607.0    0.16       0  4977.9     0.1       0  5004.5    0.07       0
  5010.5     0.1       0  5180.1    0.05       0
Bank Sta=5004.5,5010.5
Exp/Cntr=0.3,0.1

Type RM Length L Ch R = 1,14060,543,543,543
BEGIN DESCRIPTION:
ROCKY BRANCH 27.0
END DESCRIPTION:
XS GIS Cut Line= 3
      3522545.33     10351457.96      3522545.33     10351729.62
      3522584.09     10352357.47
#Sta/Elev= 30
  4551.1  441.28  4604.8  438.63  4634.8  440.46  4644.8  440.33  4654.8  439.41
  4674.8  436.77  4694.8  434.72  4704.8  434.07  4774.8  430.93  4809.3  430.06
  4826.3  429.66  4850.7  428.39  4925.0  426.15  4955.0  427.11  4975.1  427.18
  4985.1  426.22  4995.1  422.67  5002.1  422.22  5004.9  421.72  5008.1  422.22
  5012.0  425.87  5025.2  427.19  5075.3  426.59  5085.3  426.97  5125.4  427.27
  5285.7  431.25  5334.6  433.20  5365.7  433.95  5395.9  435.03  5451.8  437.85
#Mann=5,-1,0
  4551.1    0.16       0  4809.3    0.12       0  5002.1    0.07       0
  5008.1    0.12       0  5365.7    0.05       0
Bank Sta=5002.1,5008.1
Exp/Cntr=0.3,0.1

Type RM Length L Ch R = 1,13517,763,763,763
BEGIN DESCRIPTION:
ROCKY BRANCH 25.0
END DESCRIPTION:
XS GIS Cut Line= 3
      3522250.44     10351364.87      3522009.86     10352071.08
      3521893.45     10352854.92
#Sta/Elev= 30
  4538.9  440.23  4581.6  437.32  4607.7  436.27  4620.0  435.01  4647.3  433.87
  4707.0  430.62  4858.8  425.75  4895.2  424.92  4915.8  425.20  4968.6  423.78
  4978.6  422.01  4983.9  423.76  4997.3  419.34  5000.1  418.84  5003.3  419.34
  5008.9  421.35  5010.0  421.74  5015.3  419.86  5021.4  423.79  5032.0  424.07
  5097.7  423.17  5203.4  422.94  5266.1  423.64  5574.8  430.08  5815.5  432.82
  5847.5  434.18  5861.8  433.68  5911.8  434.44  5916.9  433.88  6077.4  434.29
#Mann=8,-1,0
  4538.9    0.16       0  4647.3    0.05       0  4858.8    0.12       0
  4997.3    0.07       0  5003.3    0.12       0  5008.9    0.16       0
  5097.7    0.05       0  5815.5    0.16       0
Bank Sta=4997.3,5003.3
Exp/Cntr=0.3,0.1

Type RM Length L Ch R = 1,12754,454,454,454
BEGIN DESCRIPTION:
ROCKY BRANCH 24.0
END DESCRIPTION:
XS GIS Cut Line= 3
      3522292.09     10351191.65      3521492.11     10351791.64
      3520729.49     10352466.77
#Sta/Elev= 30
  4007.3  447.46  4104.7  441.57  4200.0  435.75  4214.6  433.49  4370.8  426.73
  4514.6  423.27  4688.8  420.92  4943.7  421.77  4966.9  420.95  4979.2  419.30
  4985.4  414.84  4990.7  413.87  4993.5  413.37  4996.7  413.87  5000.0  413.87
  5004.2  416.21  5010.6  416.21  5021.1  419.73  5078.0  419.65  5118.9  421.35
  5177.5  423.14  5255.3  423.07  5395.8  425.04  5405.3  425.37  5528.0  428.18
  5602.4  431.02  5688.9  432.06  5914.4  441.97  5949.5  442.77  6025.8  440.75
#Mann=11,-1,0
  4007.3    0.16       0  4104.7    0.05       0  4688.8    0.12       0
  4966.9    0.16       0  4990.7    0.07       0  4996.7    0.16       0
  5118.9    0.12       0  5395.8    0.05       0  5405.3    0.16       0
  5528.0    0.05       0  5688.9     0.1       0
Bank Sta=4990.7,4996.7
Exp/Cntr=0.3,0.1

Type RM Length L Ch R = 1,12300,777,777,777
BEGIN DESCRIPTION:
ROCKY BRANCH 23.0
END DESCRIPTION:
XS GIS Cut Line= 3
      3522165.11     10351147.58      3521342.11     10351391.64
      3520682.79     10351465.77
#Sta/Elev= 30
  4162.0  439.77  4197.8  438.34  4238.2  435.03  4402.4  429.88  4561.5  423.29
  4683.9  419.62  4774.9  419.01  4832.7  418.48  4970.6  420.18  4989.1  415.68
  4998.6  412.47  5007.0  412.41  5009.8  411.91  5013.0  412.41  5017.8  417.11
  5023.0  417.11  5030.5  420.73  5050.6  419.39  5070.8  419.34  5165.9  421.16
  5322.3  426.70  5342.5  428.40  5362.6  428.90  5443.1  433.54  5500.7  436.07
  5515.6  437.31  5543.7  437.96  5582.2  440.21  5605.7  441.87  5683.9  445.57
#Mann=7,-1,0
  4162.0    0.05       0  4774.9    0.12       0  5007.0    0.07       0
  5013.0    0.12       0  5165.9    0.05       0  5500.7     0.1       0
  5582.2    0.05       0
Bank Sta=5007,5013
Exp/Cntr=0.3,0.1

Type RM Length L Ch R = 1,11523,775,775,775
BEGIN DESCRIPTION:
ROCKY BRANCH 22.0
END DESCRIPTION:
XS GIS Cut Line= 3
      3522010.29     10350757.16      3521860.28     10350757.16
      3520737.19     10350984.61
#Sta/Elev= 30
  4542.6  437.65  4738.5  429.64  4859.7  426.42  4925.4  422.68  4941.3  420.32
  4946.4  420.54  4976.4  417.76  4986.6  415.66  4992.0  411.57  5004.0  410.18
  5006.8  409.68  5010.0  410.18  5017.2  413.97  5027.4  416.98  5042.7  417.48
  5144.1  417.68  5160.1  417.13  5231.5  416.73  5251.9  417.39  5302.9  417.04
  5374.3  417.67  5415.2  418.90  5486.6  419.82  5527.4  420.89  5544.6  422.06
  5549.7  421.75  5660.0  424.64  5690.6  426.05  5721.2  426.54  5838.5  431.50
#Mann=4,-1,0
  4542.6    0.05       0  4859.7    0.16       0  5004.0    0.07       0
  5010.0    0.05       0
Bank Sta=5004,5010
Exp/Cntr=0.3,0.1

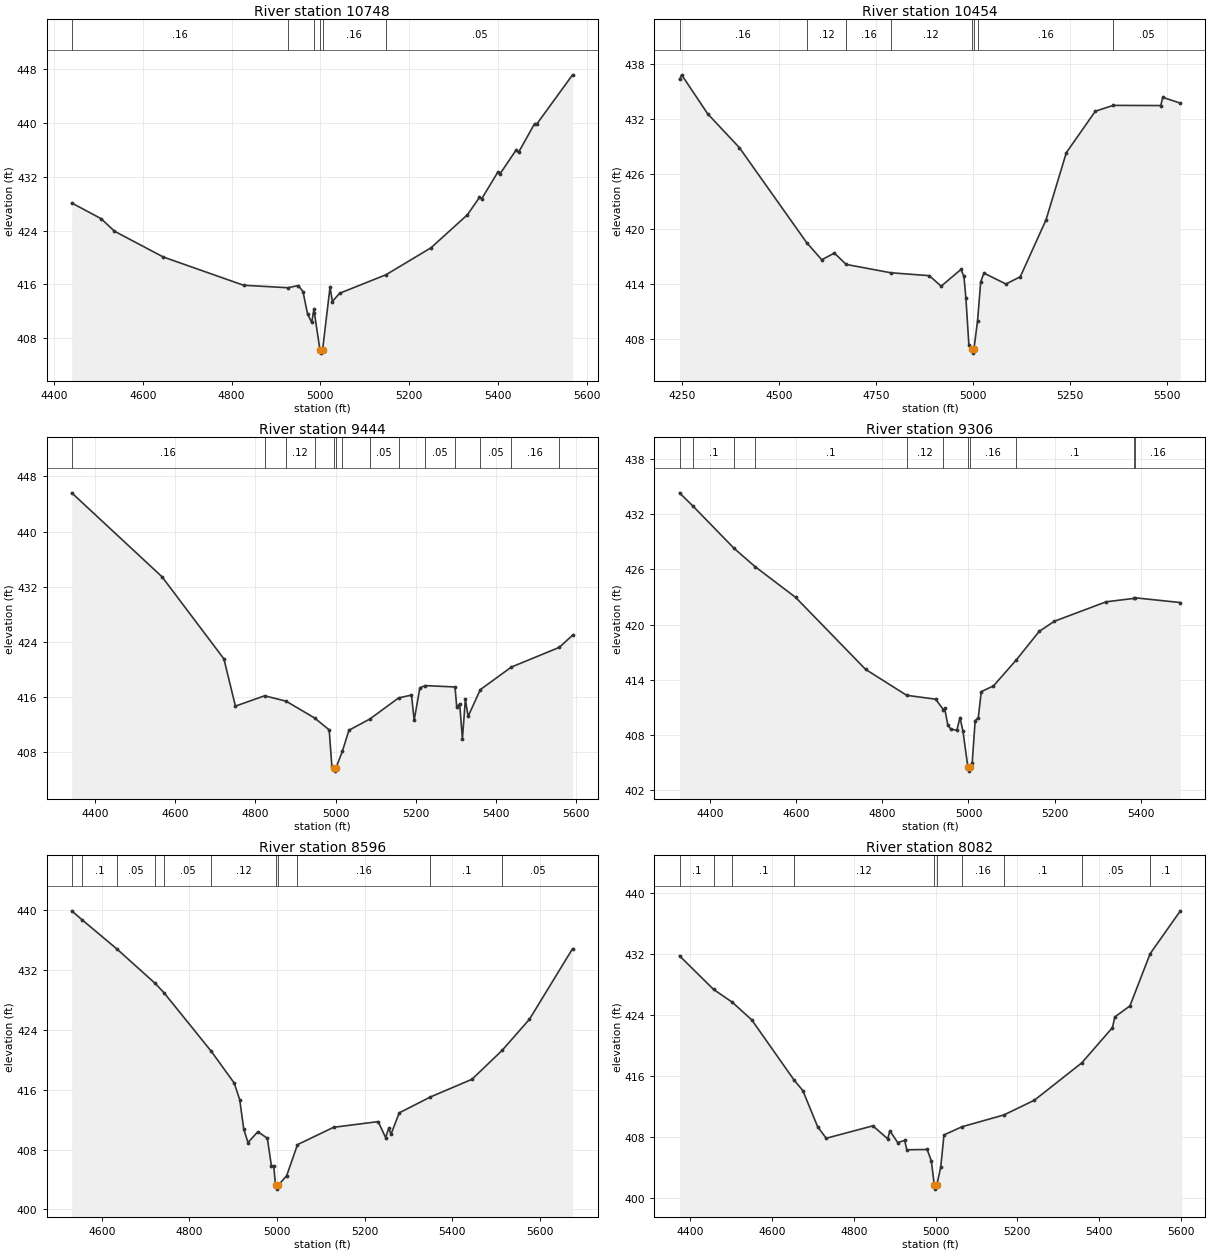
Type RM Length L Ch R = 1,10748,294,294,294
BEGIN DESCRIPTION:
ROCKY BRANCH 21.0
END DESCRIPTION:
XS GIS Cut Line= 3
      3521758.51     10350339.87      3521408.51     10350339.87
      3520652.04     10350526.70
#Sta/Elev= 30
  4439.4  428.12  4505.8  425.77  4535.8  423.91  4645.8  420.07  4826.9  415.86
  4926.8  415.49  4950.5  415.82  4960.8  414.91  4971.1  411.60  4980.4  410.32
  4985.5  412.26  4986.6  411.72  4999.0  406.25  5001.8  405.75  5005.0  406.25
  5021.8  415.60  5027.0  413.43  5043.2  414.66  5148.1  417.43  5249.2  421.43
  5331.6  426.36  5358.6  428.94  5363.8  428.75  5400.1  432.71  5405.2  432.47
  5441.5  436.02  5446.7  435.64  5483.0  439.93  5488.1  439.89  5568.6  447.20
#Mann=6,-1,0
  4439.4    0.16       0  4926.8    0.12       0  4986.6    0.16       0
  4999.0    0.07       0  5005.0    0.16       0  5148.1    0.05       0
Bank Sta=4999,5005
Exp/Cntr=0.3,0.1

Type RM Length L Ch R = 1,10454,1010,1010,1010
BEGIN DESCRIPTION:
ROCKY BRANCH 20.0
END DESCRIPTION:
XS GIS Cut Line= 3
      3521893.46     10349975.77      3520924.81     10350164.92
      3520625.98     10350214.73
#Sta/Elev= 30
  4243.7  436.33  4249.2  436.84  4316.4  432.57  4397.9  428.88  4571.4  418.48
  4610.1  416.62  4642.5  417.35  4673.0  416.11  4787.4  415.20  4887.0  414.88
  4917.6  413.73  4968.5  415.56  4976.2  414.80  4981.3  412.43  4988.9  407.32
  4996.1  406.91  4998.8  406.41  5002.1  406.91  5011.3  409.95  5019.4  414.21
  5027.7  415.16  5084.4  413.97  5121.3  414.76  5187.5  420.97  5239.8  428.32
  5314.5  432.86  5360.8  433.50  5483.1  433.48  5488.2  434.38  5533.6  433.74
#Mann=8,-1,0
  4243.7    0.16       0  4571.4    0.12       0  4673.0    0.16       0
  4787.4    0.12       0  4996.1    0.07       0  5002.1    0.12       0
  5011.3    0.16       0  5360.8    0.05       0
Bank Sta=4996.1,5002.1
Exp/Cntr=0.3,0.1

Type RM Length L Ch R = 1,9444,138,138,138
BEGIN DESCRIPTION:
ROCKY BRANCH 19.0
END DESCRIPTION:
XS GIS Cut Line= 3
      3521971.04     10349378.22      3521466.64     10349502.38
      3520923.41     10349991.29
#Sta/Elev= 30
  4341.4  445.62  4566.9  433.43  4721.3  421.51  4750.1  414.65  4823.0  416.15
  4876.5  415.37  4947.9  412.92  4984.1  411.20  4990.8  405.96  4995.3  405.71
  4998.0  405.21  5001.3  405.71  5017.1  408.10  5033.4  411.15  5085.7  412.78
  5157.7  415.85  5189.6  416.25  5196.3  412.60  5210.5  417.30  5223.5  417.63
  5298.3  417.43  5302.5  414.52  5309.9  414.98  5316.7  409.88  5324.1  415.64
  5330.9  413.15  5361.3  417.04  5438.9  420.32  5558.5  423.18  5591.7  424.95
#Mann=14,-1,0
  4341.4    0.16       0  4823.0    0.05       0  4876.5    0.12       0
  4947.9    0.05       0  4995.3    0.04       0  5001.3    0.05       0
  5017.1    0.12       0  5085.7    0.05       0  5157.7    0.12       0
  5223.5    0.05       0  5298.3    0.12       0  5361.3    0.05       0
  5438.9    0.16       0  5558.5    0.05       0
Bank Sta=4995.3,5001.3
Exp/Cntr=0.3,0.1

Type RM Length L Ch R = 1,9306,710,710,710
BEGIN DESCRIPTION:
ROCKY BRANCH 18.0
END DESCRIPTION:
XS GIS Cut Line= 3
      3521739.58     10349038.17      3521339.55     10349438.20
      3520923.65     10349866.87
#Sta/Elev= 30
  4329.1  434.31  4359.3  432.92  4455.9  428.28  4504.8  426.29  4598.5  422.97
  4761.1  415.15  4856.6  412.33  4923.8  411.91  4942.0  410.76  4944.9  410.90
  4952.1  409.11  4959.1  408.65  4973.2  408.54  4980.4  409.92  4987.3  408.43
  4998.5  404.60  5001.2  404.10  5004.5  404.60  5008.7  404.97  5015.6  409.58
  5022.8  409.89  5029.8  412.73  5058.1  413.35  5111.1  416.17  5164.3  419.27
  5199.6  420.37  5319.7  422.48  5384.1  422.85  5385.8  422.92  5492.1  422.40
#Mann=11,-1,0
  4329.1    0.16       0  4359.3     0.1       0  4455.9    0.16       0
  4504.8     0.1       0  4856.6    0.12       0  4942.0    0.16       0
  4998.5    0.07       0  5004.5    0.16       0  5111.1     0.1       0
  5384.1    0.05       0  5385.8    0.16       0
Bank Sta=4998.5,5004.5
Exp/Cntr=0.3,0.1

Type RM Length L Ch R = 1,8596,514,514,514
BEGIN DESCRIPTION:
ROCKY BRANCH 17.0
END DESCRIPTION:
XS GIS Cut Line= 3
      3521629.28     10348763.14      3521479.24     10348813.15
      3520566.81     10349184.05
#Sta/Elev= 30
  4531.5  439.94  4555.0  438.75  4635.0  434.82  4721.9  430.24  4741.9  429.00
  4850.3  421.13  4902.5  416.90  4915.0  414.66  4924.0  410.79  4933.7  408.95
  4956.4  410.40  4978.0  409.52  4987.2  405.85  4992.6  405.86  4996.6  403.22
  4999.4  402.72  5002.6  403.22  5022.1  404.52  5046.8  408.67  5129.2  410.99
  5230.9  411.75  5247.9  409.62  5254.9  410.84  5260.3  410.08  5279.0  412.92
  5350.3  415.05  5445.0  417.41  5513.7  421.27  5576.2  425.44  5674.6  434.88
#Mann=11,-1,0
  4531.5    0.05       0  4555.0     0.1       0  4635.0    0.05       0
  4721.9     0.1       0  4741.9    0.05       0  4850.3    0.12       0
  4996.6    0.07       0  5002.6    0.12       0  5046.8    0.16       0
  5350.3     0.1       0  5513.7    0.05       0
Bank Sta=4996.6,5002.6
Exp/Cntr=0.3,0.1

Type RM Length L Ch R = 1,8082,796,796,796
BEGIN DESCRIPTION:
ROCKY BRANCH 16.0
END DESCRIPTION:
XS GIS Cut Line= 3
      3521520.97     10348384.88      3520698.36     10348586.66
      3520372.42     10348780.67
#Sta/Elev= 30
  4373.2  431.70  4456.5  427.30  4502.9  425.59  4550.4  423.28  4653.9  415.39
  4675.1  414.03  4711.5  409.28  4732.4  407.77  4846.6  409.40  4883.0  407.70
  4888.2  408.75  4907.4  407.21  4924.6  407.49  4929.7  406.26  4979.5  406.30
  4989.8  404.80  4997.1  401.60  4999.9  401.10  5003.1  401.60  5012.9  404.04
  5020.7  408.21  5064.8  409.28  5167.5  410.83  5242.3  412.77  5358.1  417.66
  5433.2  422.28  5439.0  423.68  5476.0  425.13  5525.5  431.98  5599.5  437.60
#Mann=10,-1,0
  4373.2     0.1       0  4456.5    0.05       0  4502.9     0.1       0
  4653.9    0.12       0  4997.1    0.07       0  5003.1    0.12       0
  5064.8    0.16       0  5167.5     0.1       0  5358.1    0.05       0
  5525.5     0.1       0
Bank Sta=4997.1,5003.1
Exp/Cntr=0.3,0.1

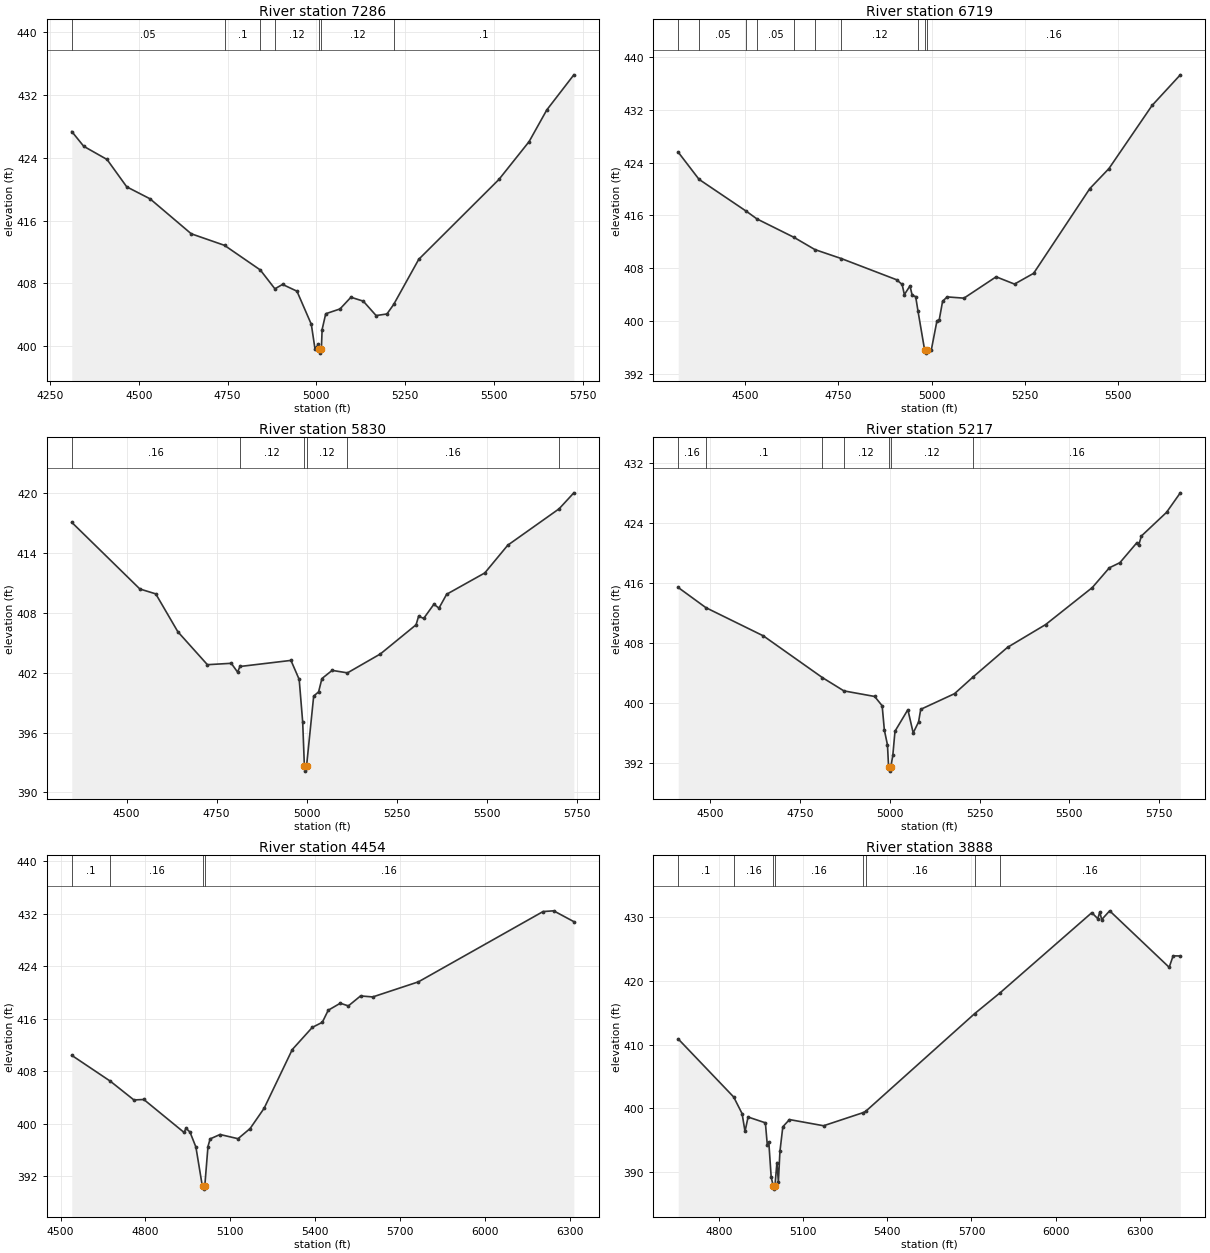
Type RM Length L Ch R = 1,7286,567,567,567
BEGIN DESCRIPTION:
ROCKY BRANCH 14.0
END DESCRIPTION:
XS GIS Cut Line= 3
      3521497.70     10347810.61      3520574.19     10347965.83
      3520228.49     10348296.00
#Sta/Elev= 30
  4310.8  427.33  4344.5  425.45  4410.2  423.77  4465.7  420.29  4531.3  418.77
  4647.4  414.32  4741.1  412.85  4841.9  409.72  4883.1  407.32  4904.6  407.88
  4945.2  407.02  4985.7  402.80  4995.9  399.72  5005.9  400.24  5008.0  399.64
  5010.7  399.14  5014.0  399.64  5016.1  402.14  5026.3  404.15  5066.5  404.76
  5097.3  406.25  5132.1  405.75  5168.2  403.92  5198.7  404.12  5217.7  405.33
  5288.3  411.07  5514.4  421.24  5599.3  426.05  5649.0  430.07  5725.3  434.54
#Mann=7,-1,0
  4310.8    0.05       0  4741.1     0.1       0  4841.9    0.05       0
  4883.1    0.12       0  5008.0    0.07       0  5014.0    0.12       0
  5217.7     0.1       0
Bank Sta=5008,5014
Exp/Cntr=0.3,0.1

Type RM Length L Ch R = 1,6719,889,889,889
BEGIN DESCRIPTION:
ROCKY BRANCH 13.0
END DESCRIPTION:
XS GIS Cut Line= 3
      3521147.28     10347108.86      3520747.31     10347408.83
      3520038.71     10347872.71
#Sta/Elev= 30
  4320.2  425.58  4376.0  421.47  4503.2  416.63  4531.4  415.48  4630.5  412.70
  4686.9  410.84  4757.8  409.48  4905.8  406.28  4920.9  405.56  4926.8  404.03
  4941.9  405.34  4947.9  403.91  4957.1  403.73  4963.5  401.50  4981.1  395.67
  4983.9  395.17  4987.1  395.67  4999.2  395.68  5014.3  400.07  5020.3  400.19
  5029.4  403.02  5041.5  403.68  5086.7  403.49  5173.0  406.72  5222.3  405.62
  5273.6  407.25  5424.3  420.07  5475.6  423.10  5591.3  432.65  5667.1  437.29
#Mann=10,-1,0
  4320.2    0.16       0  4376.0    0.05       0  4503.2     0.1       0
  4531.4    0.05       0  4630.5    0.12       0  4686.9    0.16       0
  4757.8    0.12       0  4963.5    0.16       0  4981.1    0.07       0
  4987.1    0.16       0
Bank Sta=4981.1,4987.1
Exp/Cntr=0.3,0.1

Type RM Length L Ch R = 1,5830,613,613,613
BEGIN DESCRIPTION:
ROCKY BRANCH 11.0
END DESCRIPTION:
XS GIS Cut Line= 3
      3520853.53     10346662.10      3520102.42     10347011.49
      3519702.40     10347411.50
#Sta/Elev= 30
  4348.0  417.08  4537.1  410.40  4581.2  409.91  4642.6  406.11  4724.6  402.81
  4790.9  402.95  4808.3  402.07  4815.0  402.63  4956.6  403.24  4979.5  401.33
  4989.2  397.05  4993.9  392.64  4996.6  392.14  4999.9  392.64  5019.7  399.66
  5033.4  400.09  5042.6  401.42  5071.0  402.24  5113.5  401.99  5205.0  403.89
  5304.0  406.81  5311.1  407.67  5325.2  407.45  5353.5  408.87  5367.6  408.48
  5388.9  409.87  5494.9  412.01  5558.6  414.79  5701.2  418.44  5742.1  420.04
#Mann=6,-1,0
  4348.0    0.16       0  4815.0    0.12       0  4993.9    0.07       0
  4999.9    0.12       0  5113.5    0.16       0  5701.2     0.1       0
Bank Sta=4993.9,4999.9
Exp/Cntr=0.3,0.1

Type RM Length L Ch R = 1,5217,763,763,763
BEGIN DESCRIPTION:
ROCKY BRANCH 10.0
END DESCRIPTION:
XS GIS Cut Line= 3
      3520542.07     10346091.67      3519836.95     10346584.47
      3519342.13     10346791.63
#Sta/Elev= 30
  4411.8  415.40  4488.7  412.72  4648.5  408.97  4813.1  403.41  4872.7  401.65
  4958.2  400.91  4979.1  399.67  4985.2  396.44  4993.9  394.46  4997.0  391.48
  4999.8  390.98  5003.0  391.48  5008.7  393.07  5014.8  396.29  5050.6  399.15
  5065.4  396.06  5080.3  397.51  5086.4  399.20  5180.4  401.28  5231.5  403.48
  5327.8  407.44  5433.8  410.47  5563.6  415.39  5611.1  418.02  5640.4  418.70
  5687.9  421.37  5693.3  421.11  5700.1  422.24  5770.1  425.39  5808.5  427.99
#Mann=7,-1,0
  4411.8    0.16       0  4488.7     0.1       0  4813.1    0.16       0
  4872.7    0.12       0  4997.0    0.07       0  5003.0    0.12       0
  5231.5    0.16       0
Bank Sta=4997,5003
Exp/Cntr=0.3,0.1

Type RM Length L Ch R = 1,4454,566,566,566
BEGIN DESCRIPTION:
ROCKY BRANCH 8.0
END DESCRIPTION:
XS GIS Cut Line= 3
      3520292.09     10345641.66      3519534.30     10346305.10
      3519154.03     10346972.50
#Sta/Elev= 30
  4539.8  410.40  4676.1  406.46  4759.5  403.60  4794.6  403.67  4937.0  398.64
  4943.6  399.29  4957.8  398.70  4978.7  396.42  5000.6  390.69  5004.2  390.50
  5006.9  390.00  5010.2  390.50  5021.4  396.50  5029.0  397.66  5064.1  398.33
  5127.7  397.69  5170.4  399.24  5219.8  402.32  5319.4  411.28  5390.4  414.67
  5425.7  415.44  5446.6  417.28  5489.3  418.35  5517.8  417.94  5560.9  419.46
  5604.1  419.31  5765.5  421.61  6206.3  432.33  6243.8  432.44  6315.1  430.79
#Mann=4,-1,0
  4539.8     0.1       0  4676.1    0.16       0  5004.2    0.07       0
  5010.2    0.16       0
Bank Sta=5004.2,5010.2
Exp/Cntr=0.3,0.1

Type RM Length L Ch R = 1,3888,690,690,690
BEGIN DESCRIPTION:
ROCKY BRANCH 7.0
END DESCRIPTION:
XS GIS Cut Line= 3
      3520271.54     10345451.45      3519402.37     10345692.03
      3518766.58     10346312.31
#Sta/Elev= 30
  4654.5  410.90  4852.2  401.80  4882.2  399.19  4892.6  396.39  4903.5  398.66
  4965.2  397.75  4972.1  394.26  4977.3  394.77  4985.9  389.23  4993.3  387.85
  4996.1  387.35  4999.3  387.85  5006.4  391.52  5011.6  388.52  5017.1  393.27
  5027.4  397.13  5051.1  398.26  5172.7  397.29  5313.9  399.35  5322.3  399.53
  5711.5  414.88  5802.5  418.16  6129.1  430.71  6150.3  429.77  6157.4  430.80
  6164.4  429.63  6192.7  431.00  6404.9  422.14  6419.0  423.94  6444.6  423.92
#Mann=8,-1,0
  4654.5     0.1       0  4852.2    0.16       0  4993.3    0.07       0
  4999.3    0.16       0  5313.9     0.1       0  5322.3    0.16       0
  5711.5    0.12       0  5802.5    0.16       0
Bank Sta=4993.3,4999.3
Exp/Cntr=0.3,0.1

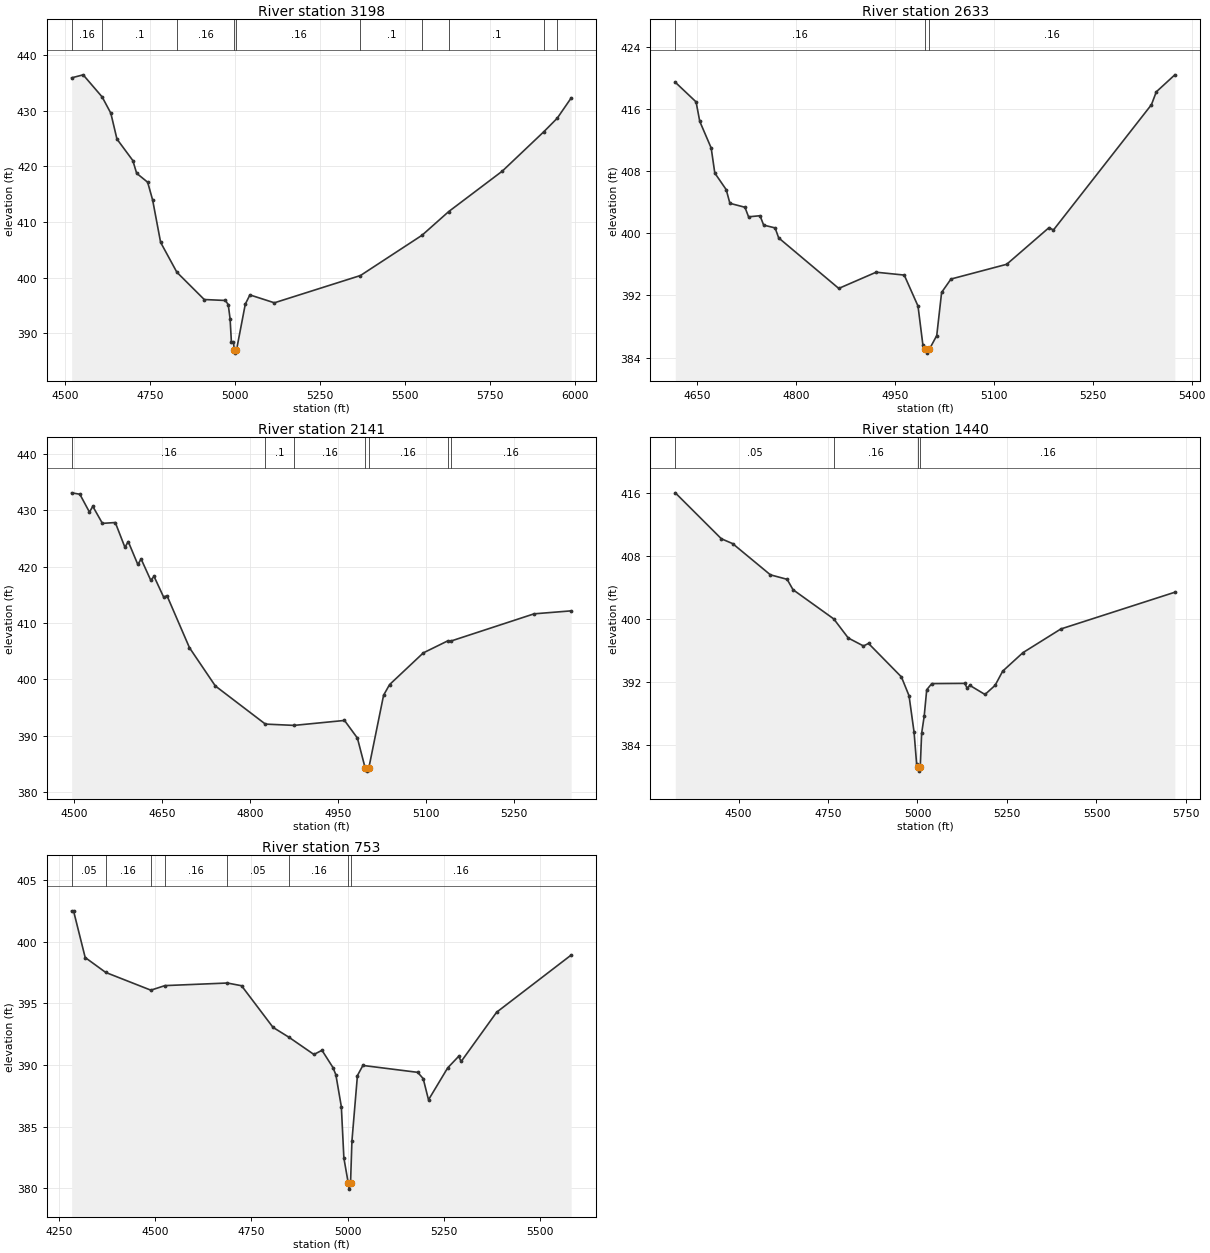
Type RM Length L Ch R = 1,3198,565,565,565
BEGIN DESCRIPTION:
ROCKY BRANCH 6.0
END DESCRIPTION:
XS GIS Cut Line= 3
      3520147.37     10344822.86      3519714.50     10345009.72
      3518915.84     10345608.71
#Sta/Elev= 30
  4518.7  435.93  4552.6  436.47  4608.5  432.49  4634.0  429.57  4652.0  424.92
  4698.7  421.06  4710.0  418.76  4742.3  417.16  4757.0  413.96  4780.5  406.34
  4828.3  400.97  4908.9  396.06  4971.0  395.89  4979.4  395.16  4984.9  392.60
  4988.8  388.39  4994.8  388.39  4997.6  386.92  5000.3  386.42  5003.6  386.92
  5029.7  395.24  5043.2  396.89  5115.2  395.47  5368.6  400.38  5549.7  407.62
  5628.0  411.87  5786.0  419.16  5908.6  426.27  5947.5  428.67  5988.5  432.31
#Mann=10,-1,0
  4518.7    0.16       0  4608.5     0.1       0  4828.3    0.16       0
  4997.6    0.07       0  5003.6    0.16       0  5368.6     0.1       0
  5549.7    0.16       0  5628.0     0.1       0  5908.6    0.16       0
  5947.5     0.1       0
Bank Sta=4997.6,5003.6
Exp/Cntr=0.3,0.1

Type RM Length L Ch R = 1,2633,492,492,492
BEGIN DESCRIPTION:
ROCKY BRANCH 5.0
END DESCRIPTION:
XS GIS Cut Line= 3
      3519692.13     10344541.63      3519472.21     10344644.37
      3519092.10     10344991.65
#Sta/Elev= 30
  4616.9  419.48  4648.4  416.95  4654.0  414.44  4671.3  411.01  4676.8  407.78
  4694.1  405.64  4699.7  403.88  4722.5  403.37  4728.0  402.14  4745.4  402.28
  4750.9  401.07  4768.2  400.71  4773.7  399.42  4864.8  392.91  4921.5  395.00
  4964.1  394.63  4985.0  390.63  4992.4  385.61  4996.2  385.07  4999.0  384.57
  5002.2  385.07  5013.4  386.83  5020.8  392.40  5035.0  394.12  5119.5  396.02
  5183.6  400.74  5190.4  400.44  5339.0  416.59  5346.4  418.25  5374.5  420.44
#Mann=3,-1,0
  4616.9    0.16       0  4996.2    0.07       0  5002.2    0.16       0
Bank Sta=4996.2,5002.2
Exp/Cntr=0.3,0.1

Type RM Length L Ch R = 1,2141,701,701,701
BEGIN DESCRIPTION:
ROCKY BRANCH 4.0
END DESCRIPTION:
XS GIS Cut Line= 3
      3519503.23     10344202.05      3518873.93     10344533.00
      3518773.96     10344632.97
#Sta/Elev= 30
  4495.7  433.14  4509.7  432.89  4526.1  429.71  4531.8  430.74  4548.2  427.71
  4570.2  427.86  4586.6  423.46  4592.3  424.47  4608.6  420.41  4614.3  421.37
  4630.7  417.60  4636.3  418.29  4652.7  414.60  4658.4  414.86  4696.8  405.60
  4740.9  398.81  4826.3  392.03  4875.2  391.80  4961.3  392.68  4983.3  389.55
  4996.7  384.17  4999.5  383.67  5002.7  384.17  5028.0  397.16  5038.2  399.05
  5095.8  404.69  5137.4  406.82  5142.9  406.79  5284.8  411.63  5348.1  412.16
#Mann=7,-1,0
  4495.7    0.16       0  4826.3     0.1       0  4875.2    0.16       0
  4996.7    0.07       0  5002.7    0.16       0  5137.4     0.1       0
  5142.9    0.16       0
Bank Sta=4996.7,5002.7
Exp/Cntr=0.3,0.1

Type RM Length L Ch R = 1,1440,687,687,687
BEGIN DESCRIPTION:
ROCKY BRANCH 2.0
END DESCRIPTION:
XS GIS Cut Line= 3
      3519604.15     10343775.21      3519149.08     10343623.57
      3518509.93     10344279.63
#Sta/Elev= 30
  4323.4  415.98  4452.0  410.15  4483.7  409.53  4589.1  405.57  4635.8  405.00
  4652.3  403.68  4766.2  399.97  4806.6  397.55  4849.1  396.54  4863.2  396.86
  4955.1  392.61  4976.4  390.22  4990.5  385.58  4997.5  381.60  5001.7  381.15
  5004.4  380.65  5007.7  381.15  5011.6  385.44  5018.8  387.65  5025.8  390.98
  5039.9  391.76  5132.0  391.79  5139.0  391.17  5146.1  391.54  5188.6  390.38
  5216.9  391.54  5238.0  393.34  5294.6  395.69  5400.7  398.70  5719.0  403.36
#Mann=4,-1,0
  4323.4    0.05       0  4766.2    0.16       0  5001.7    0.07       0
  5007.7    0.16       0
Bank Sta=5001.7,5007.7
Exp/Cntr=0.3,0.1

Type RM Length L Ch R = 1,753,0,0,0
BEGIN DESCRIPTION:
ROCKY BRANCH 1.0
END DESCRIPTION:
XS GIS Cut Line= 3
      3519386.83     10343255.26      3518897.94     10343177.66
      3518292.67     10343705.34
#Sta/Elev= 30
  4282.7  402.51  4287.6  402.51  4317.9  398.72  4371.2  397.51  4488.5  396.07
  4525.2  396.44  4687.3  396.65  4724.2  396.43  4806.0  393.05  4847.3  392.25
  4912.3  390.85  4933.2  391.19  4961.7  389.79  4969.3  389.20  4983.5  386.61
  4990.1  382.44  5001.4  380.42  5004.1  379.92  5007.4  380.42  5011.0  383.82
  5025.3  389.14  5039.5  389.96  5181.9  389.40  5196.2  388.89  5210.0  387.17
  5259.8  389.76  5288.3  390.70  5294.9  390.28  5387.0  394.28  5580.7  398.92
#Mann=8,-1,0
  4282.7    0.05       0  4371.2    0.16       0  4488.5    0.05       0
  4525.2    0.16       0  4687.3    0.05       0  4847.3    0.16       0
  5001.4    0.07       0  5007.4    0.16       0
Bank Sta=5001.4,5007.4
Exp/Cntr=0.3,0.1

Chan Stop Cuts=-1