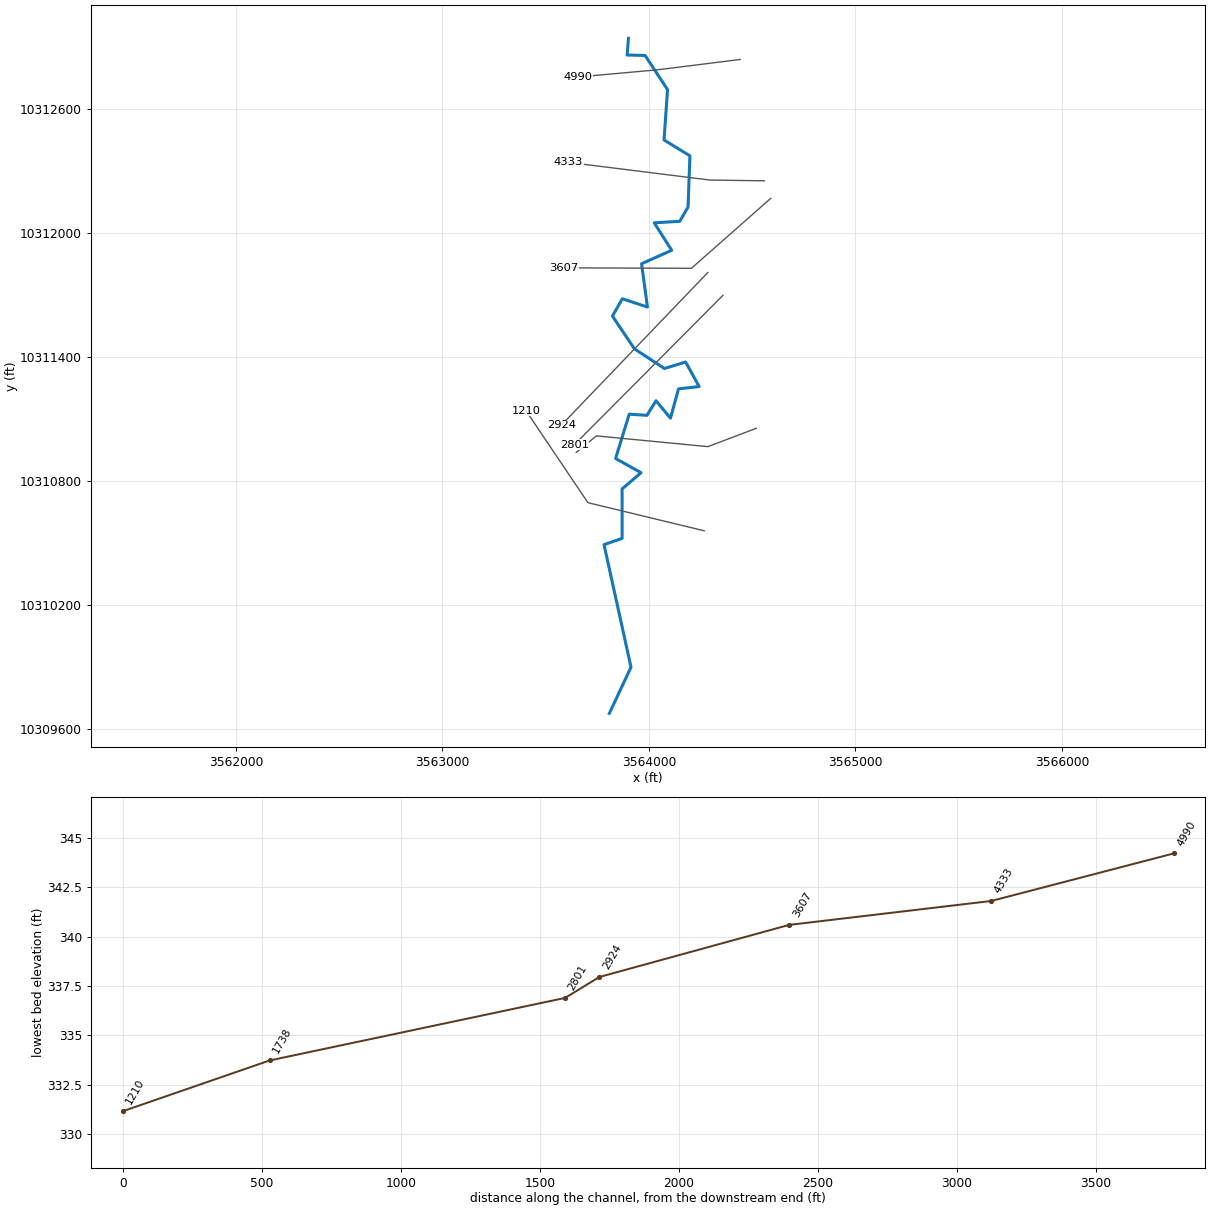
--- ROCKY CREEK TRIBUTARY 1.prj (project) ---

Proj Title=ROCKY CREEK TRIBUTARY 1 Base Level Engineering
Current Plan=p01
Default Exp/Contr=0.3,0.1
English Units
Geom File=g01
Flow File=f01
Plan File=p01
Y Axis Title=Elevation
X Axis Title(PF)=Main Channel Distance
X Axis Title(XS)=Station
BEGIN DESCRIPTION:
ROCKY CREEK TRIBUTARY 1
END DESCRIPTION:
DSS Export Rating Curves= 0
DSS Export Rating Curve Sorted= 0
DSS Export Volume Flow Curves= 0
DXF OffsetX= 0
DXF OffsetY= 0
DXF ScaleX= 1
DXF ScaleY= 10

--- ROCKY CREEK TRIBUTARY 1.p01 (plan) ---

Plan Title=Multiple Run
Short Identifier=Multiple
Geom File=g01
Flow File=f01
Subcritical Flow
K Sum by GR= 0
Std Step Tol= 0.01
Critical Tol= 0.01
Num of Std Step Trials= 20
Max Error Tol= 0.3
Flow Tol Ratio= 0.001
Split Flow NTrial= 30
Split Flow Tol= 0.02
Split Flow Ratio= 0.02
Log Output Level= 0
Friction Slope Method= 1
Unsteady Friction Slope Method= 2
Unsteady Bridges Friction Slope Method= 1
Parabolic Critical Depth
Global Vel Dist=  1 , 1 , 1
Global Log Level= 0
CheckData=True
Encroach Param= -1, 0, 0, 0
BEGIN DESCRIPTION:
Multiple Run
END DESCRIPTION:

--- ROCKY CREEK TRIBUTARY 1.f01 (steady flow) ---

Flow Title=Multiple
Number of Profiles=7
Profile Names=10-year,25-year,50-year,1pct_min,100-year,1pct_plu,500-year
River Rch & RM= ROCKY CREEK TRIB,Reach-1,4990
     253     322     374     319     431     584     575
Boundary for River Rch & Prof#=ROCKY CREEK TRIB,Reach-1,1
Up Type=0
Dn Type=3
Dn Slope=0.005
Boundary for River Rch & Prof#=ROCKY CREEK TRIB,Reach-1,2
Up Type=0
Dn Type=3
Dn Slope=0.005
Boundary for River Rch & Prof#=ROCKY CREEK TRIB,Reach-1,3
Up Type=0
Dn Type=3
Dn Slope=0.005
Boundary for River Rch & Prof#=ROCKY CREEK TRIB,Reach-1,4
Up Type=0
Dn Type=3
Dn Slope=0.005
Boundary for River Rch & Prof#=ROCKY CREEK TRIB,Reach-1,5
Up Type=0
Dn Type=3
Dn Slope=0.005
Boundary for River Rch & Prof#=ROCKY CREEK TRIB,Reach-1,6
Up Type=0
Dn Type=3
Dn Slope=0.005
Boundary for River Rch & Prof#=ROCKY CREEK TRIB,Reach-1,7
Up Type=0
Dn Type=3
Dn Slope=0.005

--- ROCKY CREEK TRIBUTARY 1.g01 (geometry) ---

Geom Title=Existing Conditions

River Reach=ROCKY CREEK TRIB,Reach-1
Reach XY= 30
      3563900.69     10312943.99      3563894.36     10312863.12
      3563981.25     10312861.10      3564090.16     10312695.80
      3564073.10     10312451.84      3564198.43     10312375.07
      3564189.49     10312126.99      3564149.20     10312057.70
      3564025.52     10312050.71      3564110.13     10311917.57
      3563964.30     10311852.29      3563992.77     10311642.57
      3563871.24     10311682.85      3563823.33     10311598.82
      3563929.58     10311440.49      3564074.71     10311345.07
      3564177.84     10311376.32      3564243.12     10311257.57
      3564143.23     10311246.52      3564104.20     10311104.33
      3564034.41     10311188.70      3563989.96     10311118.22
      3563904.55     10311123.77      3563838.57     10310909.19
      3563961.84     10310840.44      3563869.82     10310761.62
      3563870.17     10310522.30      3563782.50     10310491.92
      3563913.14     10309898.60      3563808.36     10309674.80

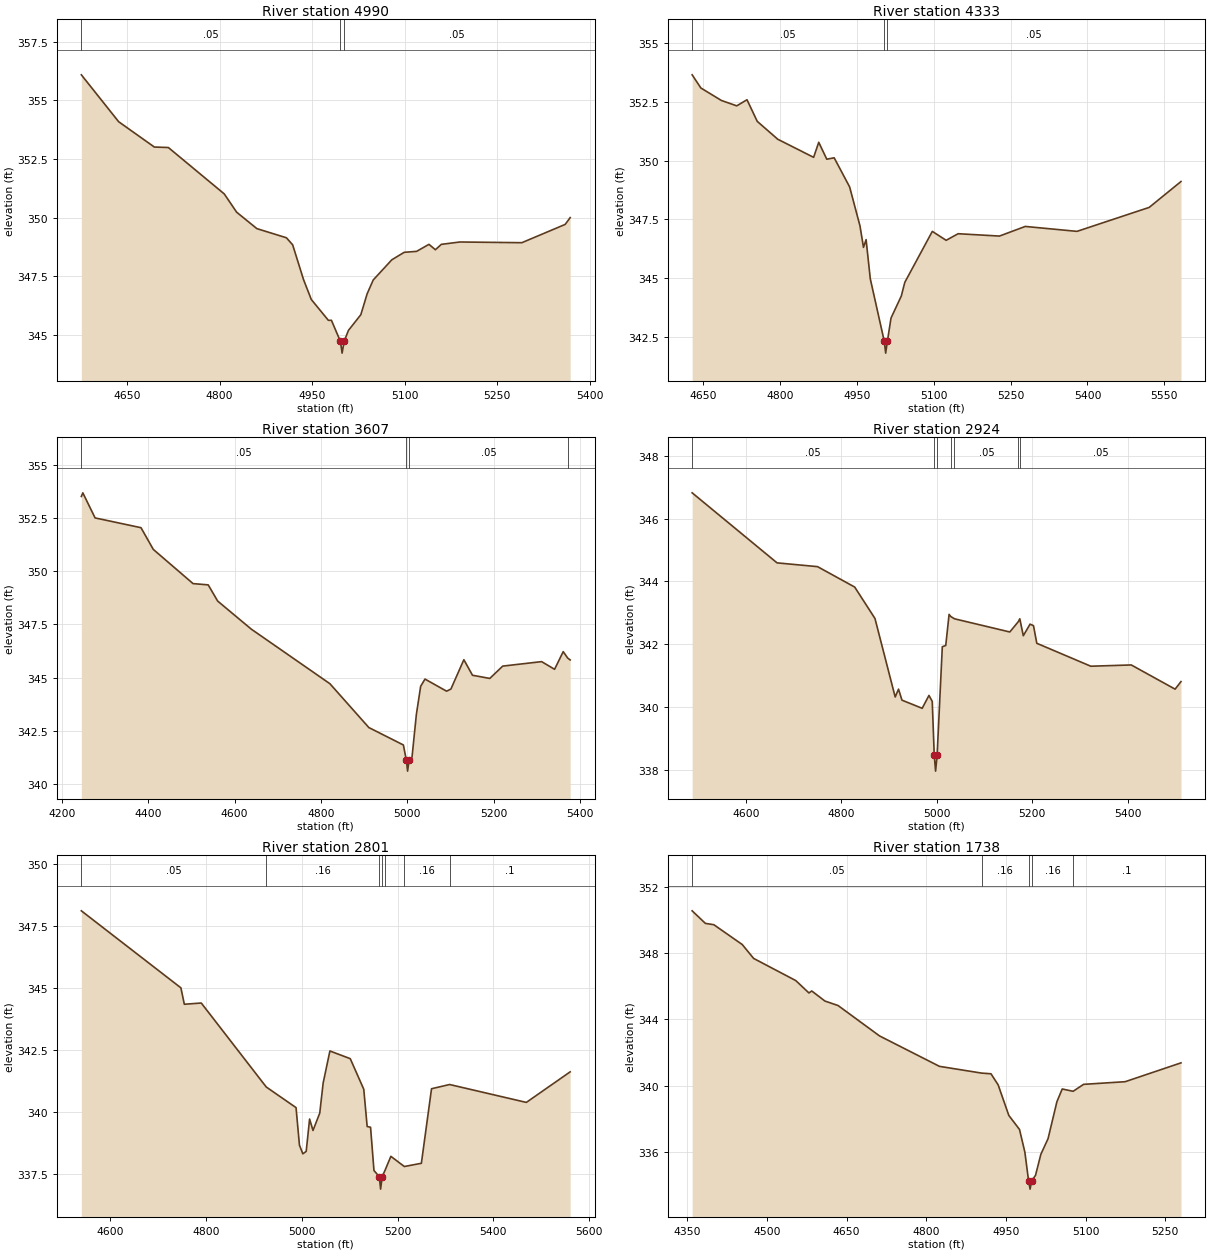
Type RM Length L Ch R = 1,4990,657,657,657
BEGIN DESCRIPTION:
ROCKY CREEK TRIBUTARY 1 6.0
END DESCRIPTION:
XS GIS Cut Line= 3
      3564442.11     10312841.64      3564042.11     10312791.64
      3563654.01     10312756.55
#Sta/Elev= 30
  4575.8  356.09  4636.3  354.09  4694.2  353.01  4716.9  352.99  4807.6  351.01
  4827.7  350.23  4860.5  349.53  4908.4  349.14  4918.5  348.84  4936.1  347.36
  4948.7  346.51  4976.4  345.62  4981.4  345.62  4996.0  344.72  4998.7  344.22
  5002.0  344.72  5009.0  345.19  5029.1  345.86  5039.3  346.75  5049.2  347.34
  5079.3  348.20  5099.4  348.52  5119.5  348.56  5139.6  348.86  5150.0  348.63
  5159.7  348.86  5189.8  348.96  5290.2  348.93  5360.5  349.71  5368.6  350.00
#Mann=3,-1,0
  4575.8    0.05       0  4996.0    0.03       0  5002.0    0.05       0
Bank Sta=4996,5002
Exp/Cntr=0.3,0.1

Type RM Length L Ch R = 1,4333,726,726,726
BEGIN DESCRIPTION:
ROCKY CREEK TRIBUTARY 1 5.0
END DESCRIPTION:
XS GIS Cut Line= 3
      3564559.07     10312254.04      3564295.65     10312257.63
      3563610.63     10312343.26
#Sta/Elev= 30
  4628.6  353.65  4645.6  353.09  4685.6  352.56  4715.6  352.33  4735.6  352.59
  4755.6  351.67  4795.6  350.91  4865.6  350.14  4875.6  350.78  4891.3  350.06
  4905.7  350.12  4935.9  348.88  4956.1  347.22  4962.9  346.31  4968.0  346.64
  4976.2  344.97  5003.5  342.31  5006.2  341.81  5009.5  342.31  5016.6  343.30
  5036.7  344.24  5043.5  344.82  5097.2  346.99  5124.2  346.61  5147.6  346.89
  5228.2  346.79  5278.6  347.20  5379.4  346.99  5520.4  348.01  5582.4  349.11
#Mann=3,-1,0
  4628.6    0.05       0  5003.5    0.03       0  5009.5    0.05       0
Bank Sta=5003.5,5009.5
Exp/Cntr=0.3,0.1

Type RM Length L Ch R = 1,3607,683,683,683
BEGIN DESCRIPTION:
Mapping XS a651a993
END DESCRIPTION:
XS GIS Cut Line= 3
      3564589.71     10312168.83      3564205.60     10311830.30
      3563586.00     10311832.47
#Sta/Elev= 30
  4245.3  353.52  4248.7  353.69  4277.1  352.51  4383.4  352.05  4411.8  351.03
  4503.9  349.42  4539.0  349.36  4560.8  348.60  4638.6  347.28  4820.8  344.71
  4910.8  342.65  4990.8  341.83  4997.8  341.10  5000.5  340.60  5003.8  341.10
  5010.8  341.26  5020.8  343.26  5030.8  344.59  5040.8  344.93  5090.8  344.36
  5100.8  344.46  5130.8  345.84  5150.8  345.11  5190.8  344.96  5220.8  345.54
  5310.8  345.75  5340.8  345.39  5360.8  346.22  5371.1  345.92  5376.9  345.83
#Mann=4,-1,0
  4245.3    0.05       0  4997.8    0.03       0  5003.8    0.05       0
  5371.1     0.1       0
Bank Sta=4997.8,5003.8
Exp/Cntr=0.3,0.1

Type RM Length L Ch R = 1,2924,123,123,123
BEGIN DESCRIPTION:
Mapping XS 6c519ce6
END DESCRIPTION:
XS GIS Cut Line= 2
      3564285.45     10311810.10      3563575.84     10311070.60
#Sta/Elev= 30
  4487.1  346.82  4665.1  344.59  4750.0  344.47  4827.9  343.82  4870.4  342.82
  4912.8  340.32  4919.8  340.57  4927.0  340.22  4969.4  339.96  4983.6  340.37
  4990.5  340.18  4994.7  338.46  4997.5  337.96  5000.7  338.46  5011.6  341.92
  5018.8  341.96  5025.8  342.95  5029.5  342.88  5037.1  342.81  5153.1  342.39
  5171.0  342.72  5174.1  342.81  5181.4  342.27  5195.6  342.64  5202.8  342.59
  5209.7  342.03  5322.9  341.30  5407.8  341.34  5499.7  340.57  5512.0  340.81
#Mann=7,-1,0
  4487.1    0.05       0  4994.7    0.04       0  5000.7    0.05       0
  5029.5    0.16       0  5037.1    0.05       0  5171.0     0.1       0
  5174.1    0.05       0
Bank Sta=4994.7,5000.7
Exp/Cntr=0.3,0.1

Type RM Length L Ch R = 1,2801,1063,1063,1063
BEGIN DESCRIPTION:
ROCKY CREEK TRIBUTARY 1 3.0
END DESCRIPTION:
XS GIS Cut Line= 2
      3564358.36     10311699.42      3563638.60     10310975.70
#Sta/Elev= 30
  4539.7  348.10  4747.6  345.00  4754.7  344.34  4790.1  344.39  4925.8  341.01
  4988.0  340.18  4995.1  338.67  5002.2  338.32  5009.2  338.42  5016.3  339.72
  5023.4  339.26  5037.5  339.96  5044.6  341.17  5058.7  342.46  5101.2  342.15
  5129.4  340.92  5136.5  339.42  5143.6  339.39  5150.7  337.65  5161.8  337.40
  5164.6  336.90  5167.8  337.40  5173.9  337.66  5186.0  338.22  5214.1  337.81
  5249.7  337.94  5270.9  340.94  5308.7  341.11  5468.9  340.39  5560.4  341.62
#Mann=7,-1,0
  4539.7    0.05       0  4925.8    0.16       0  5161.8    0.07       0
  5167.8    0.16       0  5173.9     0.1       0  5214.1    0.16       0
  5308.7     0.1       0
Bank Sta=5161.8,5167.8
Exp/Cntr=0.3,0.1

Type RM Length L Ch R = 1,1738,528,528,528
BEGIN DESCRIPTION:
ROCKY CREEK TRIBUTARY 1 4.0
END DESCRIPTION:
XS GIS Cut Line= 4
      3564520.24     10311055.55      3564285.90     10310966.59
      3563745.53     10311018.67      3563647.84     10310938.34
#Sta/Elev= 30
  4359.4  350.57  4384.3  349.81  4400.2  349.73  4453.7  348.53  4475.1  347.69
  4554.4  346.35  4579.2  345.60  4584.5  345.72  4609.3  345.11  4634.0  344.84
  4712.1  343.00  4824.8  341.16  4904.3  340.75  4921.8  340.71  4935.3  340.04
  4955.4  338.19  4975.5  337.34  4985.6  335.97  4992.6  334.23  4995.4  333.73
  4998.6  334.23  5005.7  334.57  5015.7  335.84  5029.2  336.78  5045.9  339.02
  5055.9  339.79  5076.4  339.65  5096.1  340.07  5174.3  340.23  5279.4  341.37
#Mann=5,-1,0
  4359.4    0.05       0  4904.3    0.16       0  4992.6    0.07       0
  4998.6    0.16       0  5076.4     0.1       0
Bank Sta=4992.6,4998.6
Exp/Cntr=0.3,0.1

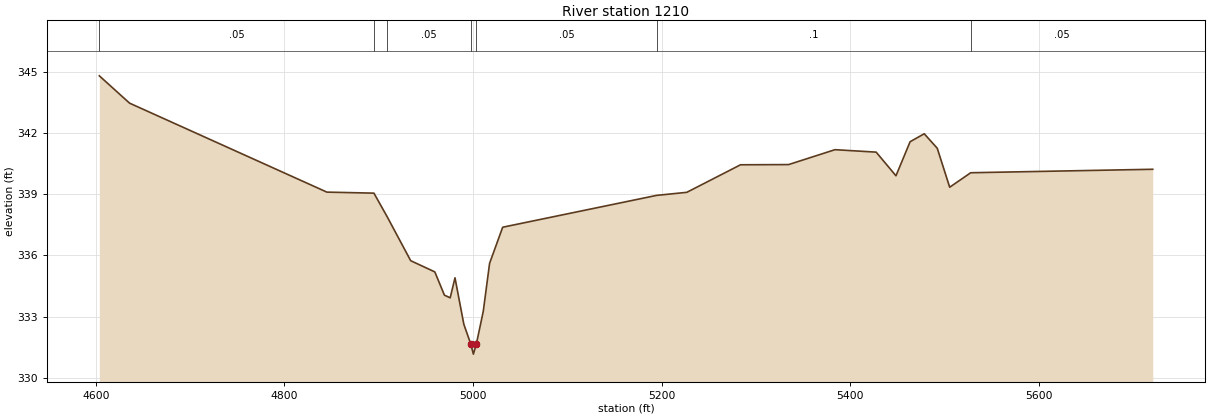
Type RM Length L Ch R = 1,1210,0,0,0
BEGIN DESCRIPTION:
ROCKY CREEK TRIBUTARY 1 1.0
END DESCRIPTION:
XS GIS Cut Line= 3
      3564268.00     10310559.02      3563704.54     10310695.19
      3563404.05     10311141.23
#Sta/Elev= 30
  4603.6  344.80  4635.7  343.46  4845.0  339.10  4894.9  339.05  4909.0  337.89
  4933.9  335.74  4959.5  335.19  4969.7  334.05  4975.8  333.92  4980.9  334.90
  4990.3  332.62  4997.6  331.66  5000.4  331.16  5003.6  331.66  5010.9  333.26
  5017.6  335.61  5031.5  337.38  5194.8  338.94  5226.8  339.09  5283.8  340.44
  5334.8  340.45  5384.0  341.18  5427.7  341.06  5448.7  339.90  5463.7  341.57
  5478.7  341.96  5492.5  341.25  5505.7  339.34  5528.0  340.05  5721.1  340.22
#Mann=7,-1,0
  4603.6    0.05       0  4894.9    0.16       0  4909.0    0.05       0
  4997.6    0.03       0  5003.6    0.05       0  5194.8     0.1       0
  5528.0    0.05       0
Bank Sta=4997.6,5003.6
Exp/Cntr=0.3,0.1

Chan Stop Cuts=-1