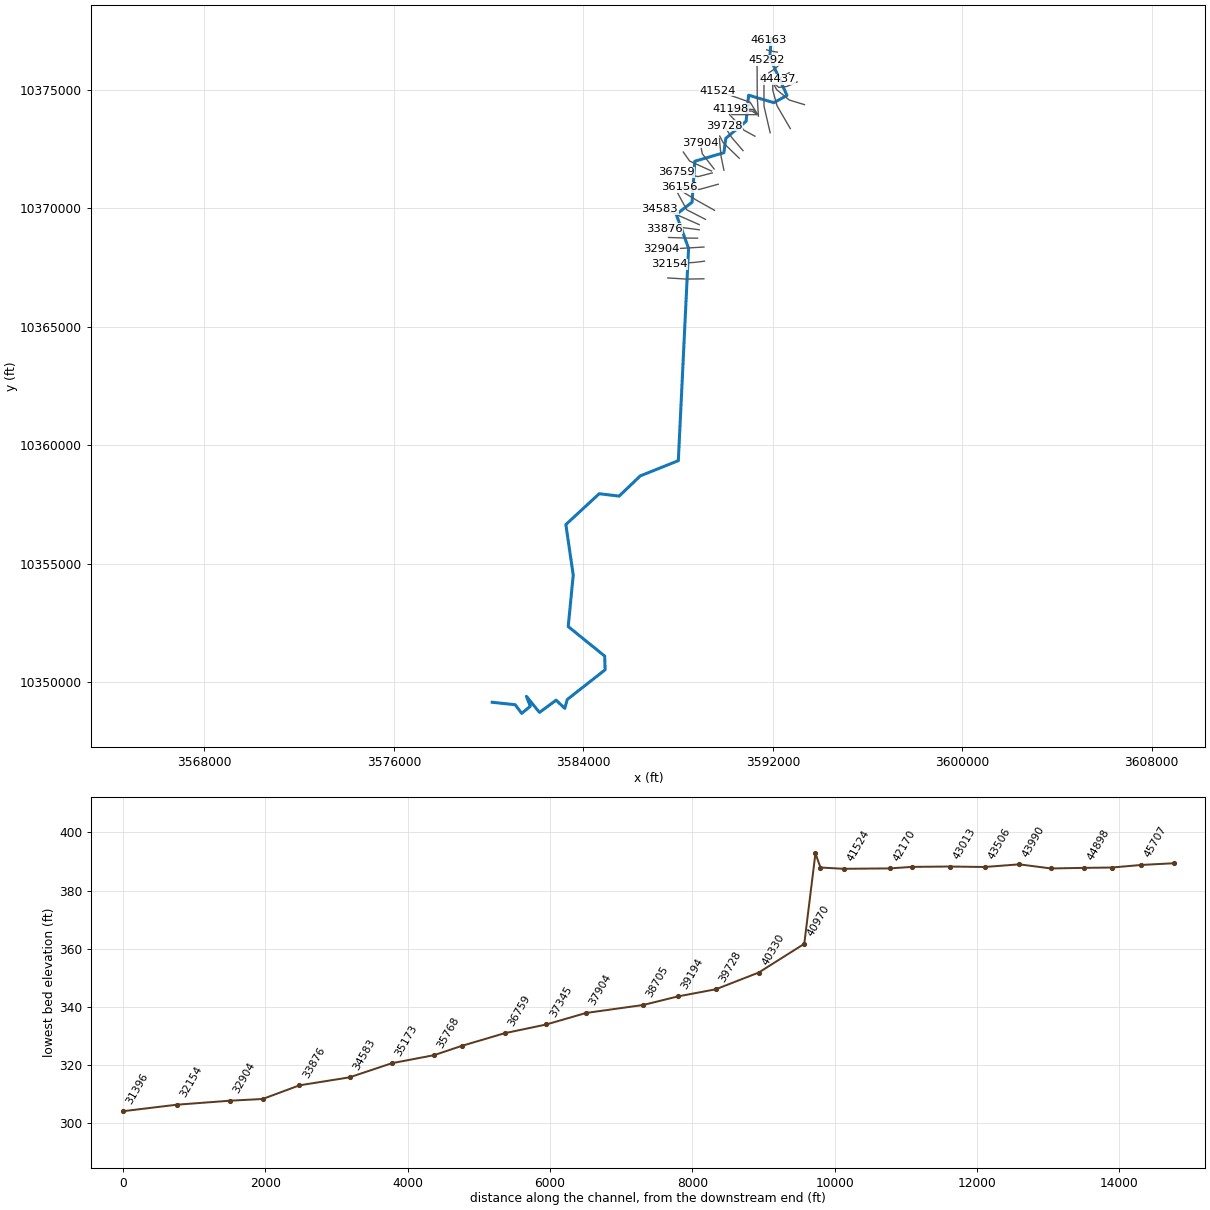
--- RUNNING CREEK.prj (project) ---

Proj Title=RUNNING CREEK Base Level Engineering
Current Plan=p01
Default Exp/Contr=0.3,0.1
English Units
Geom File=g01
Flow File=f01
Plan File=p01
Y Axis Title=Elevation
X Axis Title(PF)=Main Channel Distance
X Axis Title(XS)=Station
BEGIN DESCRIPTION:
RUNNING CREEK
END DESCRIPTION:
DSS Export Rating Curves= 0
DSS Export Rating Curve Sorted= 0
DSS Export Volume Flow Curves= 0
DXF OffsetX= 0
DXF OffsetY= 0
DXF ScaleX= 1
DXF ScaleY= 10

--- RUNNING CREEK.p01 (plan) ---

Plan Title=Multiple Run
Short Identifier=Multiple
Geom File=g01
Flow File=f01
Subcritical Flow
K Sum by GR= 0
Std Step Tol= 0.01
Critical Tol= 0.01
Num of Std Step Trials= 20
Max Error Tol= 0.3
Flow Tol Ratio= 0.001
Split Flow NTrial= 30
Split Flow Tol= 0.02
Split Flow Ratio= 0.02
Log Output Level= 0
Friction Slope Method= 1
Unsteady Friction Slope Method= 2
Unsteady Bridges Friction Slope Method= 1
Parabolic Critical Depth
Global Vel Dist=  1 , 1 , 1
Global Log Level= 0
CheckData=True
Encroach Param= -1, 0, 0, 0
BEGIN DESCRIPTION:
Multiple Run
END DESCRIPTION:

--- RUNNING CREEK.f01 (steady flow) ---

Flow Title=Multiple
Program Version=4.10
Number of Profiles= 7
Profile Names=10-year,25-year,50-year,1pct_min,100-year,1pct_plu,500-year
River Rch & RM=RUNNING CREEK,Reach-1         ,46163
     868    1180    1434    1274    1722    2329    2474
River Rch & RM=RUNNING CREEK,Reach-1         ,43506
    1716    2412    2999    2714    3671    4964    5487
River Rch & RM=RUNNING CREEK,Reach-1         ,40970
    2078    2972    3738    3425    4631    6264    7093
River Rch & RM=RUNNING CREEK,Reach-1         ,37904
    3224    4701    5990    5550    7506   10151   11762
River Rch & RM=RUNNING CREEK,Reach-1         ,30501
    3361    4892    6226    5760    7789   10534   12166
River Rch & RM=RUNNING CREEK,Reach-1         ,25786
    6158    9246   12019   11344   15341   20747   24944
River Rch & RM=RUNNING CREEK,Reach-1         ,23921
    6158    9246   12019   11344   15341   20747   24944
River Rch & RM=RUNNING CREEK,Reach-1         ,22148
    6313    9455   12269   11556   15628   21136   25307
River Rch & RM=RUNNING CREEK,Reach-1         ,11871
    8072   12117   15747   14841   20071   27144   32539
Boundary for River Rch & Prof#=RUNNING CREEK,Reach-1         , 1
Up Type= 0
Dn Type= 3
Dn Slope=0.001
Boundary for River Rch & Prof#=RUNNING CREEK,Reach-1         , 2
Up Type= 0
Dn Type= 3
Dn Slope=0.001
Boundary for River Rch & Prof#=RUNNING CREEK,Reach-1         , 3
Up Type= 0
Dn Type= 3
Dn Slope=0.001
Boundary for River Rch & Prof#=RUNNING CREEK,Reach-1         , 4
Up Type= 0
Dn Type= 3
Dn Slope=0.001
Boundary for River Rch & Prof#=RUNNING CREEK,Reach-1         , 5
Up Type= 0
Dn Type= 3
Dn Slope=0.001
Boundary for River Rch & Prof#=RUNNING CREEK,Reach-1         , 6
Up Type= 0
Dn Type= 3
Dn Slope=0.001
Boundary for River Rch & Prof#=RUNNING CREEK,Reach-1         , 7
Up Type= 0
Dn Type= 3
Dn Slope=0.001
DSS Import GetInterval= 0
DSS Import GetPeak= 0
DSS Import FillOption= 0

--- RUNNING CREEK.g01 (geometry) ---

Geom Title=Existing Conditions
Program Version=4.10

River Reach=RUNNING CREEK   ,Reach-1
Reach XY= 30
       3591935.2     10377174.57      3591870.05     10376371.61
      3592597.91      10374764.4      3592044.29     10374458.31
      3590977.74     10374772.82      3590872.17     10373673.87
      3590014.59     10372953.55      3589934.59      10372345.2
      3588705.76     10371983.94      3588589.59     10370258.07
      3587923.88      10369736.2      3588442.85      10368311.6
      3588010.19     10359342.84       3586403.7     10358699.99
       3585512.1     10357847.04      3584669.64     10357946.21
      3583261.55     10356646.07      3583572.49     10354511.59
      3583361.27       10352338.      3584901.17     10351091.71
      3584918.38     10350513.17      3583319.64     10349258.46
       3583216.6     10348883.51      3582852.08     10349230.67
      3582147.82     10348713.73      3581596.97     10349391.64
      3581759.21     10348972.95      3581396.18     10348672.96
      3581125.09     10349037.22      3580152.11     10349141.64

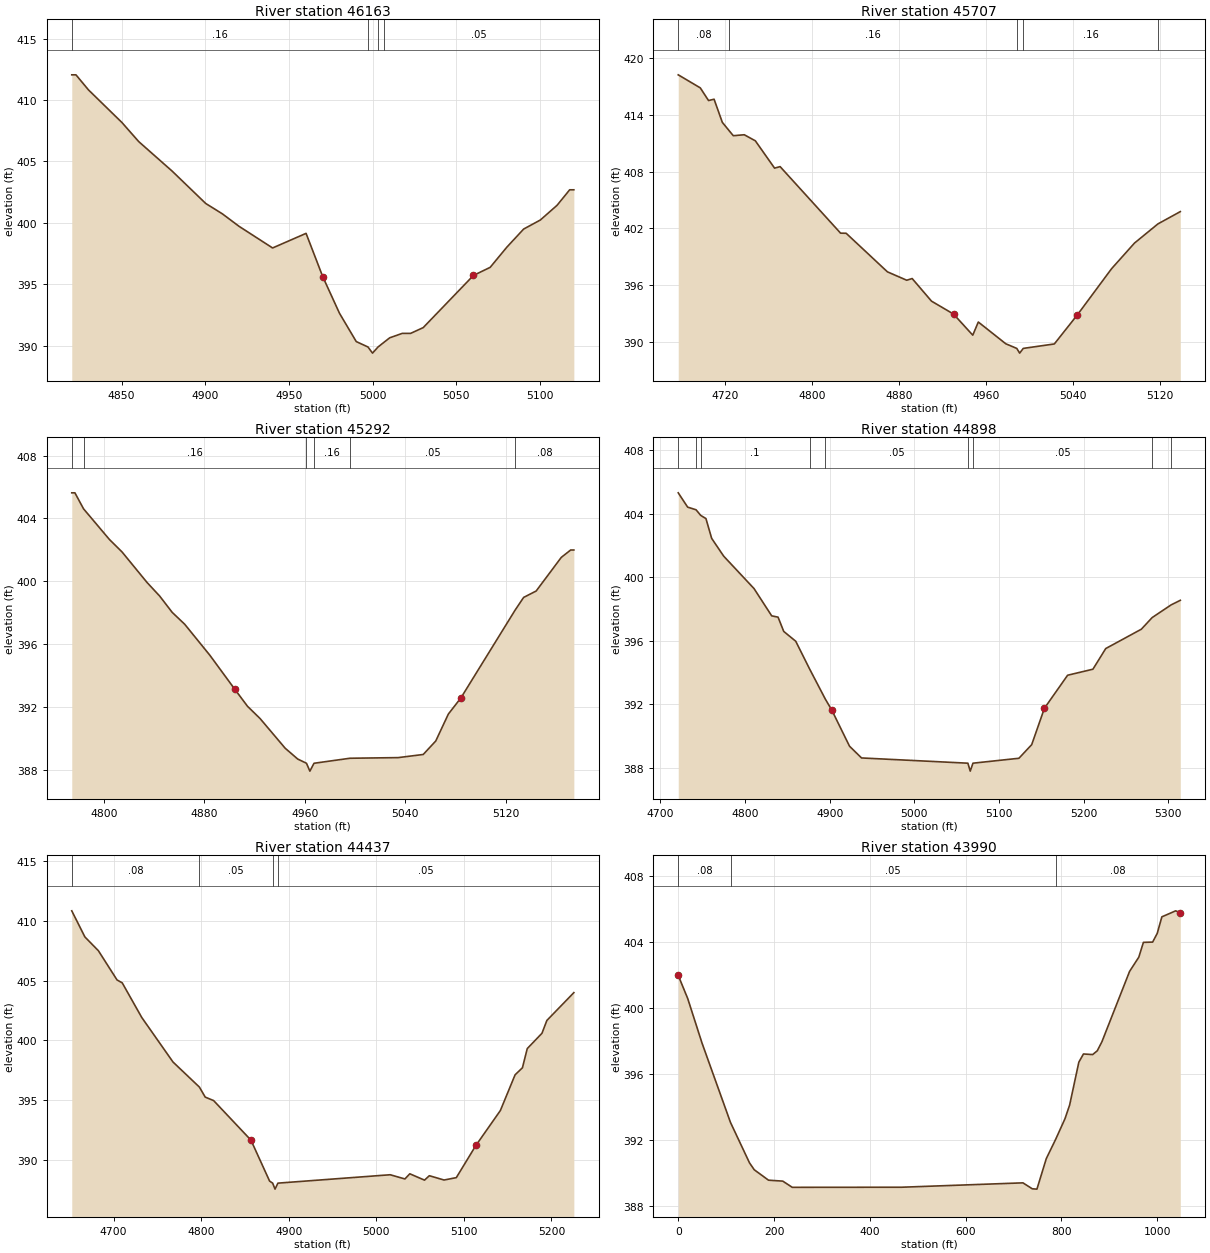
Type RM Length L Ch R = 1 ,46163   ,456,456,456
BEGIN DESCRIPTION:
RUNNING CREEK 68.0
END DESCRIPTION:
XS GIS Cut Line= 3
      3592142.06     10377091.64      3591942.11     10377091.64
      3591842.06     10377091.64
#Sta/Elev= 30
  4820.2  412.06  4822.7  412.06  4830.2  410.83  4850.2  408.17  4860.2  406.62
  4880.2  404.21  4900.2  401.58  4910.2  400.73  4920.2  399.71  4940.2  397.95
  4960.2  399.14  4970.2   395.6  4980.2  392.62  4990.2  390.32  4997.2  389.88
  4999.9  389.38  5003.2  389.88    5007  390.29  5010.2  390.63  5017.7  390.99
  5022.7  390.99  5030.2  391.46  5060.2  395.71  5070.2  396.37  5080.2  398.02
  5090.2  399.49  5100.2  400.23  5110.2  401.43  5117.7  402.69  5120.2  402.69
#Mann= 4 ,-1 , 0
  4820.2     .16       0  4997.2     .07       0  5003.2     .16       0
    5007     .05       0
Bank Sta=4970.2,5060.2
XS Rating Curve= 0 ,0
Exp/Cntr=0.3,0.1

Type RM Length L Ch R = 1 ,45707   ,415,415,415
BEGIN DESCRIPTION:
RUNNING CREEK 67.0
END DESCRIPTION:
XS GIS Cut Line= 3
      3592192.12     10376591.64      3591892.11     10376641.64
      3591742.07     10376691.65
#Sta/Elev= 30
  4676.8  418.24  4697.1  416.86  4704.7  415.52  4709.8  415.66  4717.4  413.21
  4723.9   412.3  4727.5   411.8  4737.6   411.9  4747.8  411.26  4765.5  408.37
  4770.6  408.53  4826.3  401.49  4831.4  401.48  4869.4   397.4  4887.2  396.51
  4892.2  396.69    4910   394.3  4930.3  392.93    4948   390.7  4953.1  392.09
  4978.4  389.79  4988.5   389.3  4991.2   388.8  4994.5   389.3  5023.1  389.77
  5044.2  392.83  5075.8  397.73  5096.9  400.44  5118.5  402.47  5139.1  403.77
#Mann= 5 ,-1 , 0
  4676.8     .08       0  4723.9     .16       0  4988.5     .07       0
  4994.5     .16       0  5118.5     .05       0
Bank Sta=4930.3,5044.2
XS Rating Curve= 0 ,0
Exp/Cntr=0.3,0.1

Type RM Length L Ch R = 1 ,45292   ,394,394,394
BEGIN DESCRIPTION:
RUNNING CREEK 66.0
END DESCRIPTION:
XS GIS Cut Line= 3
      3592142.09     10376241.64      3591942.11     10376241.64
      3591742.09     10376241.64
#Sta/Elev= 30
  4774.3  405.63  4776.8  405.63  4783.7  404.61  4804.3  402.66  4814.3  401.87
  4834.3  399.92  4844.3  399.06  4854.3  398.02  4864.3  397.26  4884.3  395.29
  4904.3  393.11  4914.3  392.04  4924.3  391.26  4944.3  389.37  4954.3  388.68
  4961.3  388.41    4964  387.91  4967.3  388.41  4995.9  388.73  5034.3  388.77
  5054.3  388.97  5064.3  389.83  5074.3  391.54  5084.3  392.57  5127.5  398.16
  5134.3  398.97  5144.3  399.38  5164.3  401.52  5171.8  401.99  5174.3  401.99
#Mann= 6 ,-1 , 0
  4774.3     .08       0  4783.7     .16       0  4961.3     .04       0
  4967.3     .16       0  4995.9     .05       0  5127.5     .08       0
Bank Sta=4904.3,5084.3
XS Rating Curve= 0 ,0
Exp/Cntr=0.3,0.1

Type RM Length L Ch R = 1 ,44898   ,461,461,461
BEGIN DESCRIPTION:
RUNNING CREEK 65.0
END DESCRIPTION:
XS GIS Cut Line= 3
      3592299.65     10376080.16      3592092.11     10375891.64
      3591830.88     10375719.91
#Sta/Elev= 30
  4721.1  405.32  4732.2  404.42  4742.2  404.25  4747.6   403.9  4753.8   403.7
  4760.6  402.45  4774.8  401.33  4810.6  399.29  4831.5  397.57    4839  397.49
  4845.7  396.59  4859.9  395.97  4876.4  394.21  4894.8  392.33  4902.5  391.63
  4923.4  389.36  4937.6  388.62  5063.2  388.29    5066  387.79  5069.2  388.29
  5123.5   388.6  5138.6  389.46  5153.6  391.75    5181  393.83  5210.9  394.21
    5226  395.51  5268.1  396.73  5280.8  397.46  5303.2  398.26  5314.1  398.55
#Mann= 9 ,-1 , 0
  4721.1      .1       0  4742.2     .08       0  4747.6      .1       0
  4876.4     .16       0  4894.8     .05       0  5063.2    .033       0
  5069.2     .05       0  5280.8     .08       0  5303.2     .05       0
Bank Sta=4902.5,5153.6
XS Rating Curve= 0 ,0
Exp/Cntr=0.3,0.1

Type RM Length L Ch R = 1 ,44437   ,447,447,447
BEGIN DESCRIPTION:
RUNNING CREEK 64.0
END DESCRIPTION:
XS GIS Cut Line= 3
      3592690.27     10375724.26      3592392.11     10375541.64
      3592192.06     10375441.62
#Sta/Elev= 30
  4652.3  410.82  4667.3  408.64  4682.7  407.49    4704  405.05  4709.9  404.81
  4732.2  401.92  4767.9   398.2    4798  396.11  4804.7  395.27  4814.3  394.98
  4856.9  391.68  4878.2  388.26  4881.7  388.09  4884.4  387.59  4887.7  388.09
  5015.9  388.79  5032.7  388.44  5038.3  388.87  5055.1  388.34  5060.6  388.71
  5077.4  388.35  5091.4  388.55  5113.8  391.24  5141.7  394.15  5158.5  397.13
  5166.9  397.72  5172.4  399.32  5189.2   400.6  5194.8  401.67  5225.6  403.99
#Mann= 4 ,-1 , 0
  4652.3     .08       0    4798     .05       0  4881.7    .033       0
  4887.7     .05       0
Bank Sta=4856.9,5113.8
XS Rating Curve= 0 ,0
Exp/Cntr=0.3,0.1

Type RM Length L Ch R = 1 ,43990   ,484,484,484
BEGIN DESCRIPTION:
RUNNING CREEK 63.0
END DESCRIPTION:
XS GIS Cut Line= 4
      3593024.54     10375333.67      3592592.11     10375141.64
     3592250.977    10375102.744     3592063.512      10375263.9
#Sta/Elev= 30
       0401.955219.83723 400.54949.59308397.8584109.1048393.0413148.7792390.5934
158.6978390.1746188.4537389.5428218.2095389.4862238.0468389.1097466.1749389.1158
719.5721389.3812739.0643389.0215748.8103 389.001768.3024390.8496787.7945392.0121
807.2866393.2653817.0327394.0938836.2883396.6975845.9161397.1919865.1717397.1563
874.7995397.3875884.4273397.9328942.1942402.1965961.4498403.0596971.0776403.9567
990.3333403.9738999.9611404.50391009.589405.50361038.472405.8683  1048.1405.7463
#Mann= 3 ,-1 , 0
       0     .08       0109.1048     .05       0787.7945     .08       0
Bank Sta=0,1048.1
XS Rating Curve= 0 ,0
Exp/Cntr=0.3,0.1

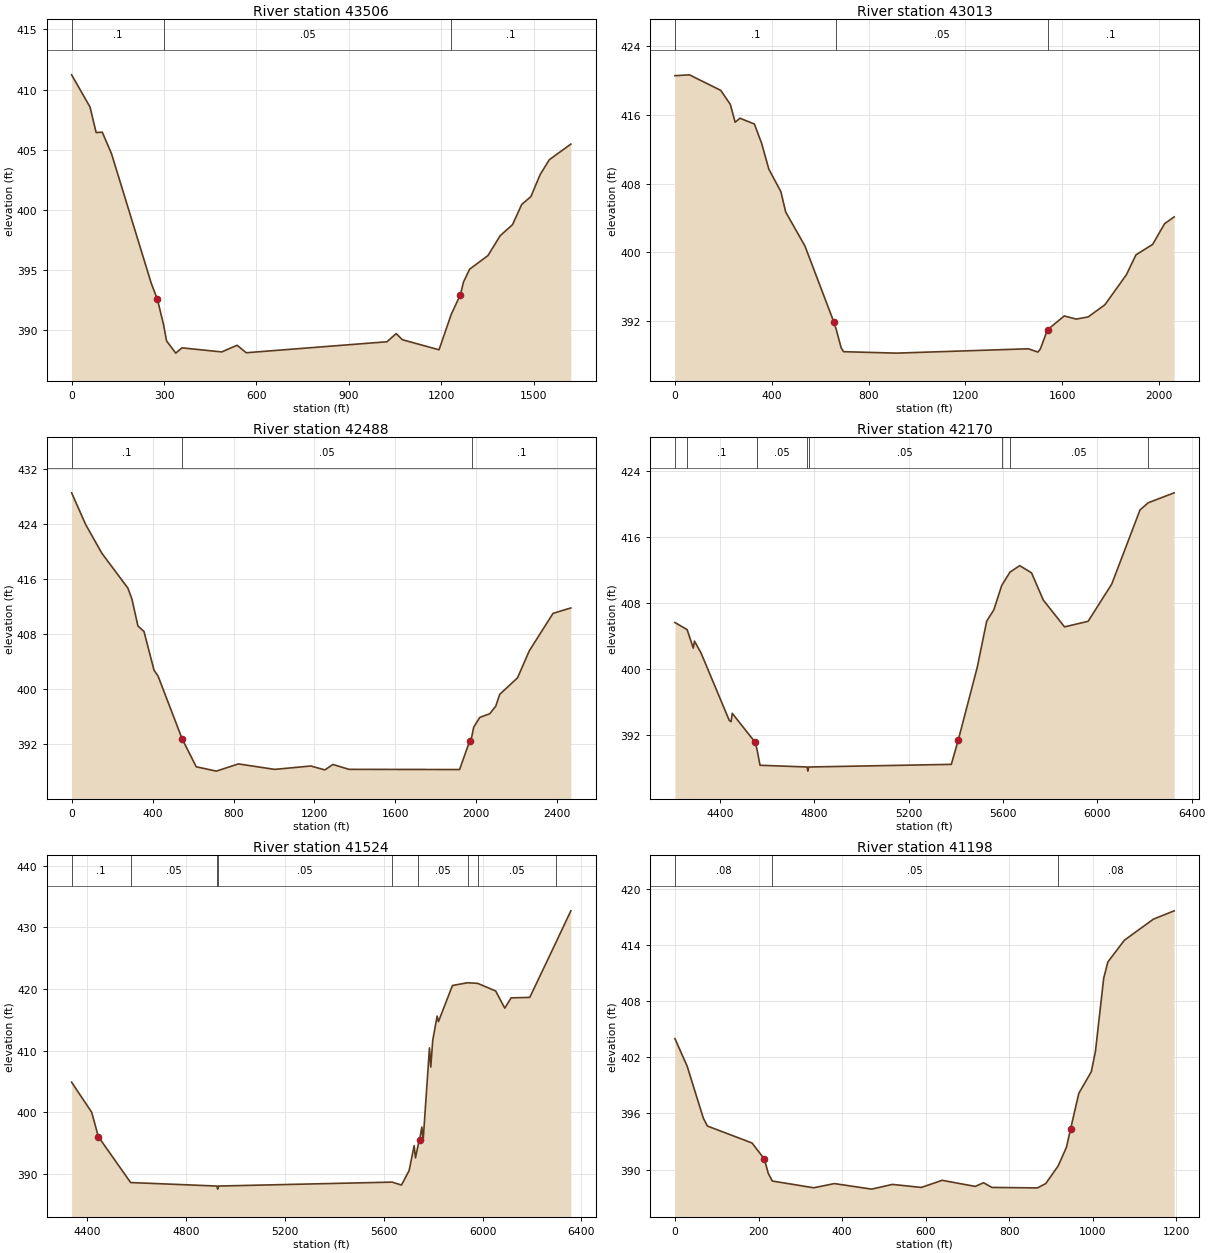
Type RM Length L Ch R = 1 ,43506   ,493,493,493
BEGIN DESCRIPTION:
RUNNING CREEK 62.0
END DESCRIPTION:
XS GIS Cut Line= 4
      3593337.04     10374374.43      3592694.64     10374569.76
      3592157.36    10375010.548     3592040.942    10375239.595
#Sta/Elev= 30
       0411.222259.68555408.551379.58073406.427299.47591406.4543129.3187404.6836
258.6374393.8919278.5326392.5711298.4277390.4627308.3753389.1042338.2181388.0939
358.1133 388.533 487.432388.1937537.1699388.7477567.0127388.12581024.079389.0385
1053.879389.71941073.745 389.2091192.942388.37151232.674 391.3171262.473392.9574
1272.406     3941292.273395.06921351.871396.20121391.676397.85721431.555398.7674
1461.463400.45011491.372401.10291521.281402.93471551.189404.16791620.976405.4647
#Mann= 3 ,-1 , 0
       0      .1       0298.4277     .05       01232.674      .1       0
Bank Sta=278.5326,1262.473
XS Rating Curve= 0 ,0
Exp/Cntr=0.3,0.1

Type RM Length L Ch R = 1 ,43013   ,525,525,525
BEGIN DESCRIPTION:
RUNNING CREEK 61.0
END DESCRIPTION:
XS GIS Cut Line= 4
      3592738.05     10373363.15      3592178.14      10374326.7
     3591998.024    10374985.781     3591995.803    10375262.164
#Sta/Elev= 30
       0420.592559.69012420.6947189.0187418.8871228.8121417.2469248.7088415.1667
268.6055415.6377328.2956414.9583358.1407412.7044387.9857409.6997437.7275407.0664
457.6242404.7011537.2111400.7298656.5912391.8738666.5396390.9966686.4363388.8989
696.3847388.4208915.2485388.25241460.098 388.7591499.627388.37431509.509388.7302
1539.156390.97051608.333392.58631657.745392.21951707.156392.47221776.333393.8918
1865.173397.39541904.621399.71131973.656400.92922022.966403.34652062.414 404.133
#Mann= 3 ,-1 , 0
       0      .1       0666.5396     .05       01539.156      .1       0
Bank Sta=656.5912,1539.156
XS Rating Curve= 0 ,0
Exp/Cntr=0.3,0.1

Type RM Length L Ch R = 1 ,42488   ,318,318,318
BEGIN DESCRIPTION:
RUNNING CREEK 60.0
END DESCRIPTION:
XS GIS Cut Line= 4
      3591887.35     10373189.52      3591626.93     10374313.68
      3591626.01      10375239.6     3591468.026    10375597.234
#Sta/Elev= 30
       0428.514269.52661423.9051148.9856419.7699278.1064414.6849297.9712413.0982
327.7683409.1941357.5655   408.4407.2273402.7821427.0921401.9352546.2805 392.806
615.8071 388.764715.1309388.1331 824.387389.1823 1003.17388.38431181.966388.8763
1251.523388.3114 1291.27389.09861370.764388.39181917.284388.36391966.968392.4928
1976.905393.06361986.842394.49522016.652395.92562066.335396.46252095.972397.5583
2115.498399.27112203.365 401.6682261.944405.6079  2379.1411.02592466.968411.8101
#Mann= 3 ,-1 , 0
       0      .1       0546.2805     .05       01976.905      .1       0
Bank Sta=546.2805,1966.968
XS Rating Curve= 0 ,0
Exp/Cntr=0.3,0.1

Type RM Length L Ch R = 1 ,42170   ,646,646,646
BEGIN DESCRIPTION:
RUNNING CREEK 59.0
END DESCRIPTION:
XS GIS Cut Line= 3
      3591392.11     10373891.64      3591342.11     10374691.64
      3591336.13     10376006.36
#Sta/Elev= 30
  4209.6  405.61  4261.3  404.75  4287.3  402.51  4292.3  403.36  4319.8  401.95
  4440.1  393.74  4447.6   393.6  4452.6  394.61  4550.3  391.08  4557.4  390.26
  4570.3  388.32  4770.2  388.11    4773  387.61  4776.2  388.11  5381.2  388.43
  5411.2  391.43  5491.2  400.19  5531.2  405.78  5561.2  407.13  5594.9   410.1
  5629.7  411.71  5671.2   412.5  5721.2  411.63  5771.2  408.33  5861.2  405.08
  5961.2  405.76  6061.2  410.26  6181.2  419.25  6216.2  420.12  6325.9  421.32
#Mann= 8 ,-1 , 0
  4209.6     .05       0  4261.3      .1       0  4557.4     .05       0
  4770.2    .033       0  4776.2     .05       0  5594.9     .08       0
  5629.7     .05       0  6216.2     .16       0
Bank Sta=4550.3,5411.2
XS Rating Curve= 0 ,0
Exp/Cntr=0.3,0.1

Type RM Length L Ch R = 1 ,41524   ,326,326,326
BEGIN DESCRIPTION:
RUNNING CREEK 58.0
END DESCRIPTION:
XS GIS Cut Line= 3
      3591342.11     10373991.64      3591045.76      10374473.2
      3589675.49     10374955.45
#Sta/Elev= 30
  4338.9  404.85    4420  399.96  4447.2  395.98  4577.5  388.54  4926.4  387.97
  4929.2  387.47  4932.4  387.97  5634.6  388.61  5672.3  388.13  5703.3  390.49
  5723.6  394.54  5728.9  392.56  5740.8  394.84  5745.7  395.49  5754.6  397.56
  5759.9  395.39  5785.5  410.44  5790.8  407.32  5798.7  411.67  5816.5   415.6
  5821.8   414.7  5878.4  420.57  5939.4  421.02  5980.4  420.92  6053.2  419.68
  6089.9  416.89  6115.5  418.56    6191  418.64    6299  427.76    6357  432.71
#Mann= 9 ,-1 , 0
  4338.9      .1       0  4577.5     .05       0  4926.4    .033       0
  4932.4     .05       0  5634.6     .16       0  5740.8     .05       0
  5939.4     .16       0  5980.4     .05       0    6299     .16       0
Bank Sta=4447.2,5745.7
XS Rating Curve= 0 ,0
Exp/Cntr=0.3,0.1

Type RM Length L Ch R = 1 ,41198   ,71,71,71
BEGIN DESCRIPTION:
RUNNING CREEK 57.0
END DESCRIPTION:
XS GIS Cut Line= 3
     3591319.132    10373987.851      3591164.44     10374170.87
      3590207.69     10374205.18
#Sta/Elev= 30
       0403.9876 29.1287401.062767.96696395.492677.67652394.6542184.4817 392.844
  214.09  391.13  223.32 389.602233.0296388.7817331.9854388.0604381.5667388.5075
 470.813387.9153520.3943388.4196589.8081 388.096639.3893 388.857718.7194388.2052
738.5519388.5992758.3845388.0984867.4633388.0447887.2958388.5067917.0445390.3891
 936.877392.3825946.7933394.3353966.6258398.1554996.3746400.45091006.291402.6176
1026.123410.4551 1036.04  412.181075.705414.50711145.118416.7552  1194.7417.6421
#Mann= 3 ,-1 , 0
       0     .08       0233.0296     .05       0917.0445     .08       0
Bank Sta=214.09,946.7933
XS Rating Curve= 0 ,0
Exp/Cntr=0.3,0.1

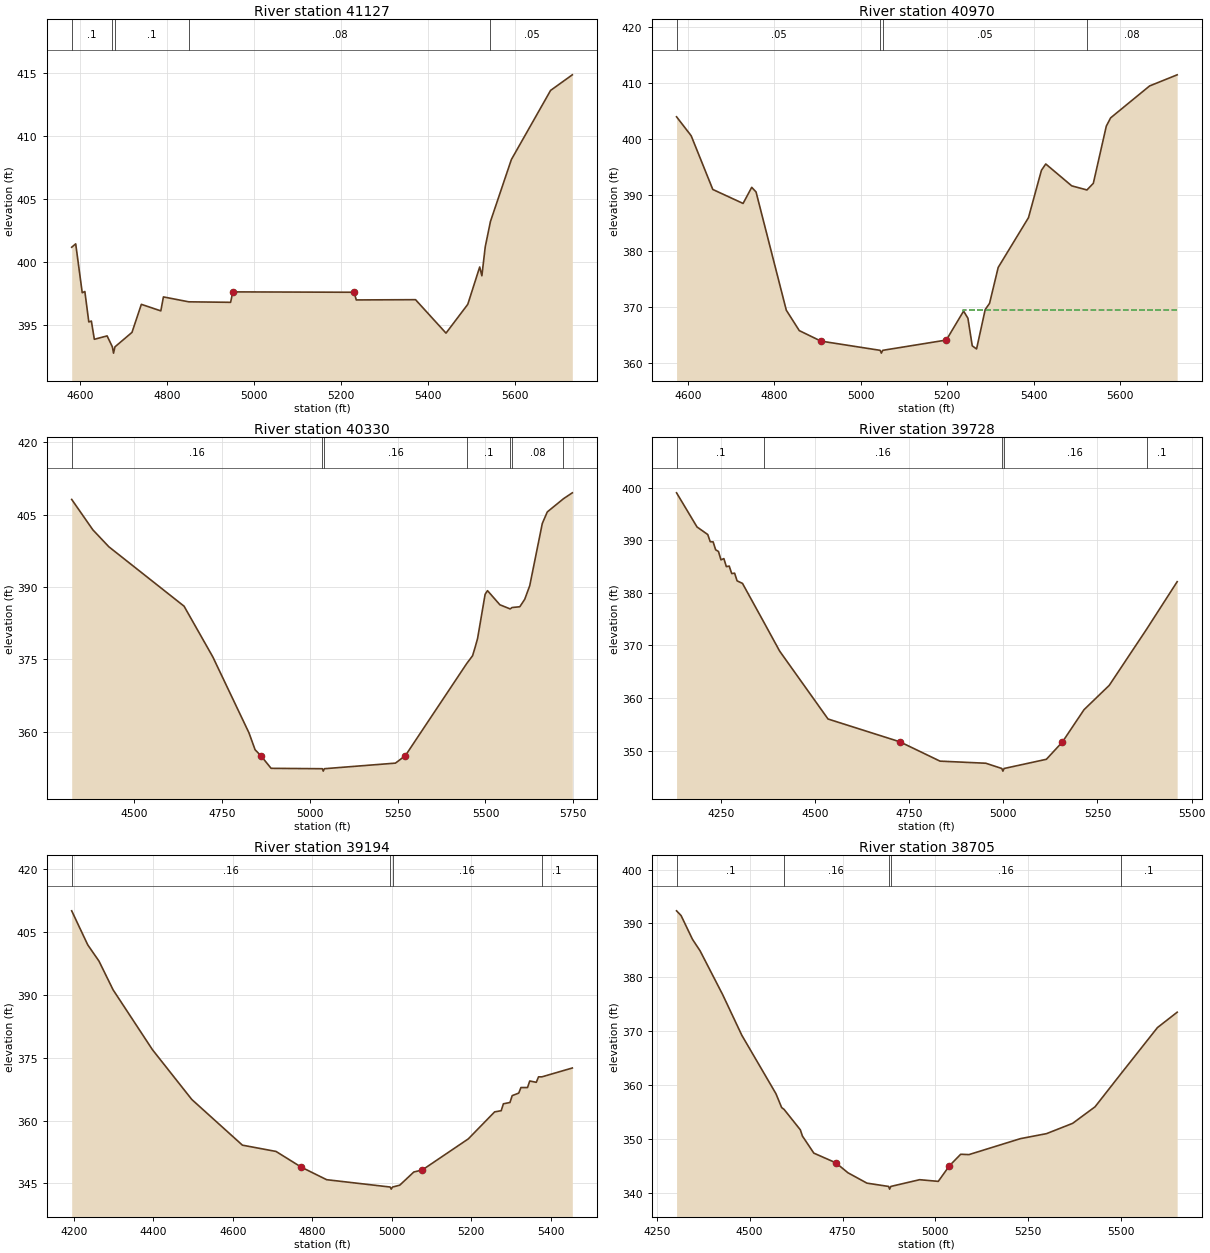
Type RM Length L Ch R = 1 ,41127   ,157,157,157
BEGIN DESCRIPTION:
Mapping XS b9e13fba
END DESCRIPTION:
XS GIS Cut Line= 3
      3591305.48     10373982.08      3591125.38     10374101.43
       3590192.2     10374133.98
#Sta/Elev= 30
  4581.1  401.18  4590.3  401.45  4605.3  397.56  4611.3  397.66  4620.4  395.24
  4626.3  395.31  4633.1  393.86  4662.4  394.13  4674.5  393.26  4677.2  392.76
  4680.5  393.26  4719.6  394.41  4741.1  396.64  4785.8  396.12  4791.8  397.23
    4850  396.84  4946.1   396.8  4951.2  397.63  5229.7   397.6  5234.7  396.99
  5370.8  397.01  5440.8  394.35  5490.8  396.64  5518.2  399.61  5523.2  398.91
  5530.9  401.21  5542.9  403.23  5590.9  408.15    5681  413.65  5730.9  414.89
#Mann= 5 ,-1 , 0
  4581.1      .1       0  4674.5     .07       0  4680.5      .1       0
    4850     .08       0  5542.9     .05       0
Bank Sta=4951.2,5229.7
XS Rating Curve= 0 ,0
Exp/Cntr=0.3,0.1

Type RM Length L Ch R = 1 ,40970   ,640,640,640
BEGIN DESCRIPTION:
RUNNING CREEK 56.0
END DESCRIPTION:
XS GIS Cut Line= 3
      3591335.92     10373951.69       3590287.7     10373953.86
      3590203.07      10374023.3
#Sta/Elev= 30
  4573.8  403.98  4607.6  400.59  4657.6  390.98  4727.6  388.48  4747.6  391.36
  4757.6  390.54  4827.6  369.38  4857.6  365.73  4907.6  363.85  5044.6   362.2
  5047.4   361.7  5050.6   362.2  5197.6  364.04  5237.6  369.22  5247.6  367.94
  5257.6     363  5267.6  362.45  5287.6   369.5  5297.6   370.6  5317.6  377.03
  5387.6  385.93  5417.6  394.41  5427.6  395.54  5487.6  391.63  5522.8  390.89
  5537.6  392.08  5567.6  402.31  5577.6  403.79  5667.7   409.5  5731.5  411.49
#Mann= 4 ,-1 , 0
  4573.8     .05       0  5044.6     .04       0  5050.6     .05       0
  5522.8     .08       0
#XS Ineff= 2 , 0
                         5236.82          369.46
Permanent Ineff=
       F       F
Bank Sta=4907.6,5197.6
XS Rating Curve= 0 ,0
Exp/Cntr=0.3,0.1

Type RM Length L Ch R = 1 ,40330   ,602,602,602
BEGIN DESCRIPTION:
RUNNING CREEK 55.0
END DESCRIPTION:
XS GIS Cut Line= 3
      3591244.95       10373042.      3590786.51     10373291.98
      3590172.93     10373953.45
#Sta/Elev= 30
  4322.7  408.16  4382.9  401.86  4428.5  398.34  4642.4  386.03  4724.1  375.53
  4827.1  359.77  4844.5  356.27  4861.8  354.95  4890.1  352.41  5035.7  352.33
  5038.4  351.83  5041.7  352.33  5243.9  353.49  5272.2  355.05  5446.5  374.12
  5463.3  375.75  5470.6  377.51  5477.5  379.31    5499  388.49  5505.8  389.25
    5541  386.32  5570.3  385.46  5575.7  385.75  5597.7  385.91  5611.8  387.47
    5626  390.29  5661.7  403.18  5675.9  405.57    5722  408.31  5747.1  409.53
#Mann= 7 ,-1 , 0
  4322.7     .16       0  5035.7     .07       0  5041.7     .16       0
  5446.5      .1       0  5570.3     .05       0  5575.7     .08       0
    5722     .05       0
Bank Sta=4861.8,5272.2
XS Rating Curve= 0 ,0
Exp/Cntr=0.3,0.1

Type RM Length L Ch R = 1 ,39728   ,534,534,534
BEGIN DESCRIPTION:
RUNNING CREEK 54.0
END DESCRIPTION:
XS GIS Cut Line= 3
      3590741.52     10372434.33       3590255.4     10372998.58
      3589942.13      10373491.6
#Sta/Elev= 30
  4132.7  399.01    4187  392.52  4215.5  391.08  4222.1  389.71  4229.8  389.68
  4236.4  388.19    4244  387.85  4250.6  386.27  4258.3   386.5  4264.9  384.98
  4272.5  385.08  4279.1  383.66  4286.8  383.73  4293.4  382.27  4307.7  381.79
  4365.2  374.31  4406.4  368.91  4534.8     356  4725.7  351.66  4832.1  347.99
  4953.5  347.59  4996.2  346.59    4999  346.09  5002.2  346.59  5114.4  348.34
  5156.8  351.62  5214.3  357.77  5281.3   362.4  5380.5  373.08  5461.6  382.11
#Mann= 5 ,-1 , 0
  4132.7      .1       0  4365.2     .16       0  4996.2     .07       0
  5002.2     .16       0  5380.5      .1       0
Bank Sta=4725.7,5156.8
XS Rating Curve= 0 ,0
Exp/Cntr=0.3,0.1

Type RM Length L Ch R = 1 ,39194   ,489,489,489
BEGIN DESCRIPTION:
RUNNING CREEK 53.0
END DESCRIPTION:
XS GIS Cut Line= 3
      3590580.92     10372113.17      3589902.27     10372770.76
      3589756.67     10373049.89
#Sta/Elev= 30
  4194.3  410.03  4234.7  401.91    4263  398.03  4298.5  391.18  4397.5   376.9
  4496.5  365.02  4623.9  354.12  4708.5  352.62  4772.3  348.86  4835.9  345.88
  4995.7  344.13  4998.4  343.63  5001.7  344.13  5019.8  344.57  5055.3  347.72
  5076.4  348.19  5192.4  355.62  5258.6  362.06  5275.1  362.34  5280.7  363.99
  5297.2   364.3  5302.8  365.94  5319.3  366.54  5324.9  367.87  5341.4  367.87
    5347  369.43  5363.4  369.11  5369.1  370.42  5377.6  370.42  5454.1  372.53
#Mann= 4 ,-1 , 0
  4194.3     .16       0  4995.7     .07       0  5001.7     .16       0
  5377.6      .1       0
Bank Sta=4772.3,5076.4
XS Rating Curve= 0 ,0
Exp/Cntr=0.3,0.1

Type RM Length L Ch R = 1 ,38705   ,801,801,801
BEGIN DESCRIPTION:
RUNNING CREEK 52.0
END DESCRIPTION:
XS GIS Cut Line= 3
      3589934.22     10371609.69      3589817.03     10372178.27
       3589742.1     10372941.67
#Sta/Elev= 30
  4303.2  392.34  4315.4  391.46    4346  387.06  4366.5  384.92  4427.7  376.73
  4478.8  369.25  4570.7   358.4  4586.1  355.82  4592.6  355.48  4636.4  351.69
  4642.1  350.52  4672.8  347.36  4731.8  345.57  4764.7  343.71  4815.7  341.79
    4874  341.18  4876.7  340.68    4880  341.18  4957.5  342.43  5007.7  342.12
  5037.8  345.02    5068  347.15  5090.4  347.09  5228.8  350.05  5299.1  350.98
  5369.4  352.89  5429.7  355.96  5499.7  362.12  5597.6  370.66  5650.8  373.52
#Mann= 5 ,-1 , 0
  4303.2      .1       0  4592.6     .16       0    4874     .07       0
    4880     .16       0  5499.7      .1       0
Bank Sta=4731.8,5037.8
XS Rating Curve= 0 ,0
Exp/Cntr=0.3,0.1

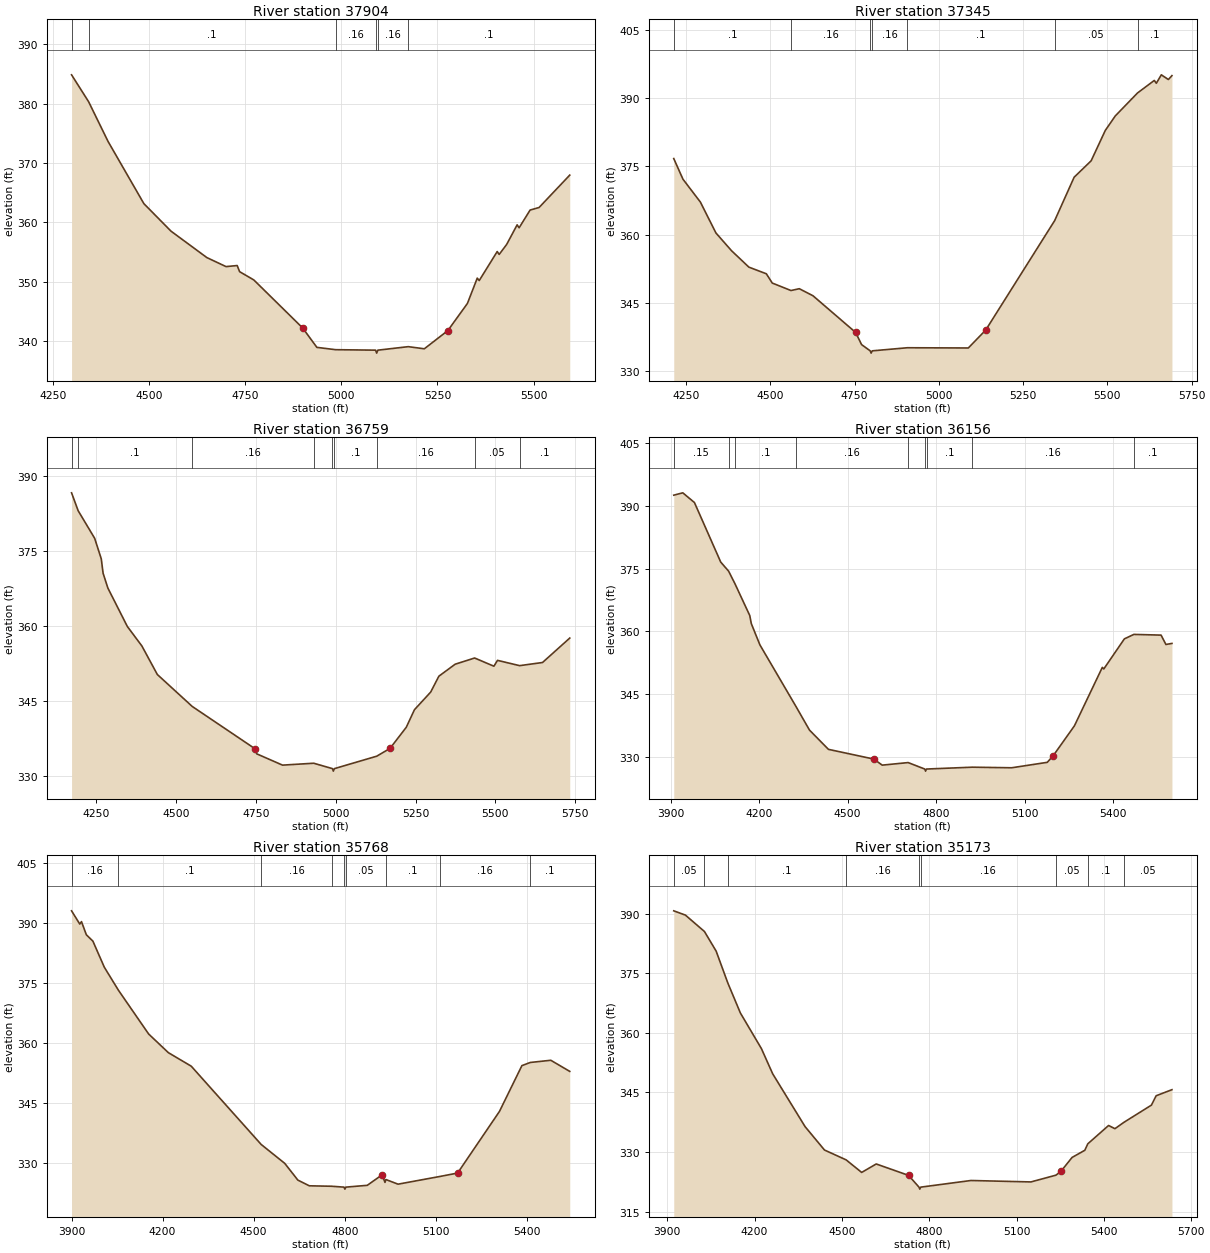
Type RM Length L Ch R = 1 ,37904   ,559,559,559
BEGIN DESCRIPTION:
RUNNING CREEK 51.0
END DESCRIPTION:
XS GIS Cut Line= 3
       3589521.9     10371657.42      3589022.76     10372299.79
      3588931.61      10372772.9
#Sta/Elev= 30
  4298.7  384.85    4343  380.32  4393.5  373.63  4486.7  363.14  4557.3   358.5
  4650.5  354.05  4700.3  352.53  4729.3  352.71  4735.6  351.68  4772.6  350.28
  4899.4   342.2  4936.5  338.92  4985.2  338.53  5089.2  338.45  5091.9  337.95
  5095.2  338.45  5174.1  339.04  5215.9  338.68    5277  341.75  5327.9  346.32
  5353.5  350.59  5358.6  350.18  5405.4  355.07  5410.5  354.58  5429.8  356.25
  5457.2  359.57  5462.3  359.07  5490.9  362.06  5514.2  362.49    5594  367.95
#Mann= 6 ,-1 , 0
  4298.7     .16       0    4343      .1       0  4985.2     .16       0
  5089.2     .07       0  5095.2     .16       0  5174.1      .1       0
Bank Sta=4899.4,5277
XS Rating Curve= 0 ,0
Exp/Cntr=0.3,0.1

Type RM Length L Ch R = 1 ,37345   ,586,586,586
BEGIN DESCRIPTION:
RUNNING CREEK 50.0
END DESCRIPTION:
XS GIS Cut Line= 3
      3589409.73     10371574.37      3588488.91     10371991.63
      3588219.79      10372373.6
#Sta/Elev= 30
  4213.3   376.7  4240.6  372.17  4292.3  367.15  4338.4  360.37  4384.6  356.48
  4436.3  352.86    4488  351.41  4505.6  349.37  4561.1  347.73  4585.8  348.13
  4626.5  346.58    4753  338.53  4770.6  335.86  4796.2  334.49  4798.9  333.99
  4802.2  334.49  4906.4  335.17  5087.3  335.12  5138.9  339.05  5343.7   363.1
  5401.3   372.6  5451.8  376.21  5493.7  382.87  5523.3  386.05  5589.3  391.09
  5639.1  393.85  5645.2  393.23    5660  395.08  5680.9  394.05  5691.5   394.9
#Mann= 7 ,-1 , 0
  4213.3      .1       0  4561.1     .16       0  4796.2     .07       0
  4802.2     .16       0  4906.4      .1       0  5343.7     .05       0
  5589.3      .1       0
Bank Sta=4753,5138.9
XS Rating Curve= 0 ,0
Exp/Cntr=0.3,0.1

Type RM Length L Ch R = 1 ,36759   ,603,603,603
BEGIN DESCRIPTION:
RUNNING CREEK 48.0
END DESCRIPTION:
XS GIS Cut Line= 3
       3589442.1     10371491.64      3588844.81     10371336.25
      3587920.33     10371522.89
#Sta/Elev= 30
  4172.8  386.68  4193.4   383.1  4245.1  377.58  4265.8  373.47  4271.5  370.59
  4286.5  367.62  4347.4  359.94  4393.1  356.02  4441.4  350.32  4550.6  343.93
  4747.5  335.45  4752.7  334.44  4833.5  332.18  4931.2  332.56  4989.9  331.48
  4992.6  330.98  4995.9  331.48  5128.6  333.97  5170.2  335.53  5221.2  339.77
  5246.7  343.27  5297.5   346.8  5323.2  349.98  5374.2  352.38  5435.2  353.62
  5495.5  351.98  5506.8  353.15    5576  352.09  5647.8  352.72  5733.1  357.61
#Mann= 9 ,-1 , 0
  4172.8     .05       0  4193.4      .1       0  4550.6     .16       0
  4931.2      .1       0  4989.9     .07       0  4995.9      .1       0
  5128.6     .16       0  5435.2     .05       0    5576      .1       0
Bank Sta=4747.5,5170.2
XS Rating Curve= 0 ,0
Exp/Cntr=0.3,0.1

Type RM Length L Ch R = 1 ,36156   ,388,388,388
BEGIN DESCRIPTION:
RUNNING CREEK 47.0
END DESCRIPTION:
XS GIS Cut Line= 3
      3589695.48     10371015.06      3588892.55     10370793.72
      3588041.84     10370880.53
#Sta/Elev= 30
    3911  392.53  3941.6  393.09  3981.1  390.77  4070.1  376.56  4096.9  374.38
  4118.4  371.38  4168.5  363.79  4173.8  361.85  4202.9  356.78  4325.5  342.02
  4370.9  336.43  4435.1  331.83  4588.7  329.51  4617.3  328.06  4705.2  328.67
  4761.4  327.13  4764.2  326.63  4767.4  327.13  4922.3  327.57  5055.9  327.43
  5176.6  328.73  5196.7  330.31  5268.6  337.45  5363.1  351.41  5368.1  351.03
  5437.9  358.22  5470.1  359.28  5562.2  359.11  5578.6  356.87    5599  357.13
#Mann= 9 ,-1 , 0
    3911     .15       0  4096.9     .05       0  4118.4      .1       0
  4325.5     .16       0  4705.2      .1       0  4761.4     .07       0
  4767.4      .1       0  4922.3     .16       0  5470.1      .1       0
Bank Sta=4588.7,5196.7
XS Rating Curve= 0 ,0
Exp/Cntr=0.3,0.1

Type RM Length L Ch R = 1 ,35768   ,595,595,595
BEGIN DESCRIPTION:
RUNNING CREEK 46.0
END DESCRIPTION:
XS GIS Cut Line= 3
      3589539.23     10369912.65      3588805.75     10370324.97
      3588120.51     10370736.98
#Sta/Elev= 30
  3900.2  393.06  3927.2  389.75  3932.9  390.36  3948.8  387.08  3970.5  385.47
  4008.1  378.95  4054.7  373.18  4154.1  362.25  4219.1  357.58  4294.4   354.2
  4524.8  334.62  4602.3   329.9  4645.7   325.7  4683.3  324.28  4756.7  324.17
  4797.7  323.95  4800.5  323.45  4803.7  323.95  4874.2   324.4  4923.1  327.03
  4932.6  325.13  4935.5  325.85  4975.6  324.69  5114.4  326.63  5171.8  327.47
  5309.7  342.89  5383.6  354.34  5411.1  355.13  5478.7  355.68  5541.2   352.9
#Mann= 9 ,-1 , 0
  3900.2     .16       0  4054.7      .1       0  4524.8     .16       0
  4756.7     .05       0  4797.7     .07       0  4803.7     .05       0
  4935.5      .1       0  5114.4     .16       0  5411.1      .1       0
Bank Sta=4923.1,5171.8
XS Rating Curve= 0 ,0
Exp/Cntr=0.3,0.1

Type RM Length L Ch R = 1 ,35173   ,590,590,590
BEGIN DESCRIPTION:
RUNNING CREEK 45.0
END DESCRIPTION:
XS GIS Cut Line= 3
       3589157.3      10369530.7      3588367.38     10369934.34
       3587973.1     10370657.91
#Sta/Elev= 30
  3922.3  390.69  3962.4  389.61  4027.8  385.48  4067.9  380.55  4107.8  372.57
  4151.1  364.99  4223.4  356.02  4262.2  349.67  4373.3   336.4    4440  330.51
  4514.4  328.03  4567.7  324.87  4617.7     327  4728.8  324.13  4764.6  321.17
  4767.4  320.67  4770.6  321.17    4943  322.84    5149  322.48  5234.9  324.18
  5252.5  325.18  5290.5  328.65  5334.1  330.44  5344.4  332.07  5415.8  336.68
  5437.6  335.88  5468.3  337.47    5563  341.81  5579.1  344.16  5633.4  345.69
#Mann= 9 ,-1 , 0
  3922.3     .05       0  4027.8     .16       0  4107.8      .1       0
  4514.4     .16       0  4764.6     .07       0  4770.6     .16       0
  5234.9     .05       0  5344.4      .1       0  5468.3     .05       0
Bank Sta=4728.8,5252.5
XS Rating Curve= 0 ,0
Exp/Cntr=0.3,0.1

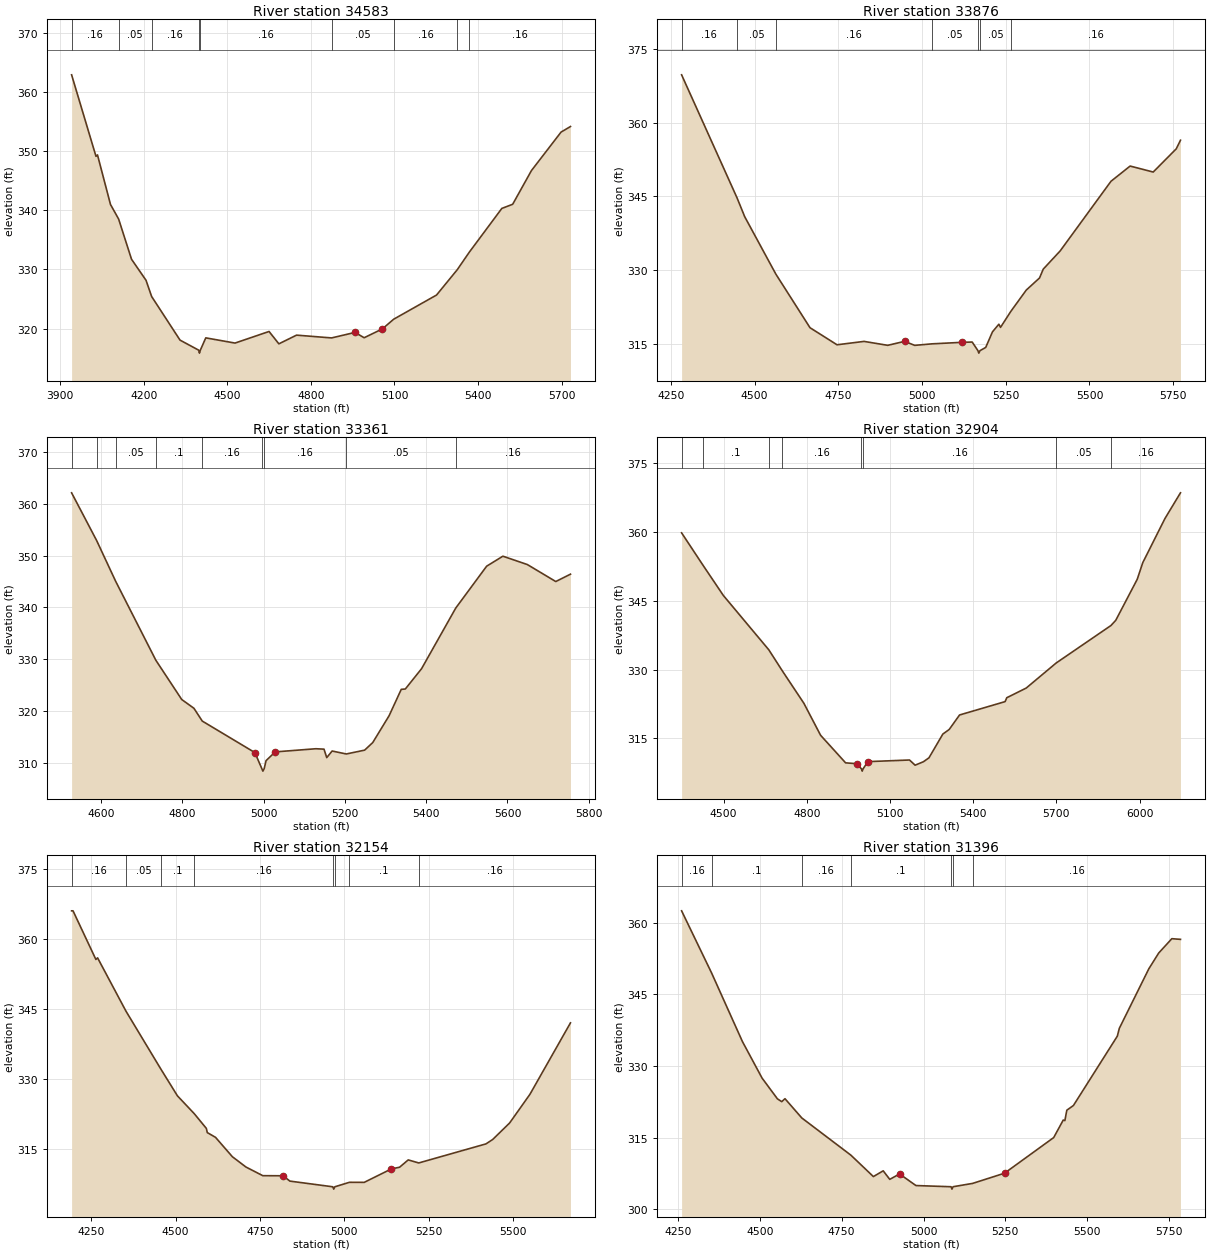
Type RM Length L Ch R = 1 ,34583   ,707,707,707
BEGIN DESCRIPTION:
RUNNING CREEK 44.0
END DESCRIPTION:
XS GIS Cut Line= 3
       3588892.6     10369309.32      3587740.37     10369817.86
      3587230.25     10369964.72
#Sta/Elev= 30
  3941.3  362.88  4028.8   349.1  4034.2  349.34  4080.9  340.96  4110.1   338.5
  4156.3  331.71  4208.4  328.15  4228.5  325.41  4330.4  318.04  4397.3  316.34
  4400.1  315.84  4403.3  316.34  4422.8  318.42  4527.8  317.54  4649.9   319.5
  4685.1  317.41  4748.6  318.88  4874.3  318.41  4958.4  319.34  4991.2  318.44
  5056.8  319.94  5097.1  321.57    5251  325.66  5325.3  329.94  5368.5   332.9
  5485.3   340.3  5524.2     341  5591.6   346.7  5697.8   353.2  5731.6  354.14
#Mann= 9 ,-1 , 0
  3941.3     .16       0  4110.1     .05       0  4228.5     .16       0
  4397.3     .04       0  4403.3     .16       0  4874.3     .05       0
  5097.1     .16       0  5325.3      .1       0  5368.5     .16       0
Bank Sta=4958.4,5056.8
XS Rating Curve= 0 ,0
Exp/Cntr=0.3,0.1

Type RM Length L Ch R = 1 ,33876   ,515,515,515
BEGIN DESCRIPTION:
RUNNING CREEK 43.0
END DESCRIPTION:
XS GIS Cut Line= 3
      3588892.09     10369091.64      3587920.47     10369220.47
        3587417.     10369144.43
#Sta/Elev= 30
  4282.3  369.79    4448  344.69  4470.7  340.88  4563.5   329.2  4665.6  318.26
  4746.3  314.78    4827  315.47  4897.6  314.67  4948.1  315.48  4978.3  314.66
  5029.4  314.97  5119.5  315.28  5149.8  315.34    5167  313.58  5169.7  313.08
    5173  313.58  5190.2  314.24  5210.3  317.41  5229.4  318.97  5234.4  318.33
  5265.4  321.61  5311.3  325.93  5350.9   328.4  5361.9  330.19  5412.5  333.91
  5564.2   348.1  5621.3   351.2  5690.2  349.98  5759.1  354.72  5771.6  356.46
#Mann= 7 ,-1 , 0
  4282.3     .16       0    4448     .05       0  4563.5     .16       0
  5029.4     .05       0    5167     .07       0    5173     .05       0
  5265.4     .16       0
Bank Sta=4948.1,5119.5
XS Rating Curve= 0 ,0
Exp/Cntr=0.3,0.1

Type RM Length L Ch R = 1 ,33361   ,457,457,457
BEGIN DESCRIPTION:
RUNNING CREEK 41.0
END DESCRIPTION:
XS GIS Cut Line= 3
      3588823.07     10368736.43      3588342.11     10368741.64
      3587595.92     10368766.77
#Sta/Elev= 30
  4527.5  362.11  4589.2  352.89  4635.9  345.04  4734.8   329.8  4798.5  322.22
  4828.5  320.53    4849  318.06  4978.5  311.98  4995.5   308.9  4998.2   308.4
  5001.5   308.9    5006  310.42  5028.5  312.11  5128.6  312.72  5148.6  312.64
  5155.3  311.01  5168.6  312.28  5203.5  311.71  5248.6  312.45  5268.6  313.92
  5308.7  319.08  5338.7  324.18  5348.7  324.25  5388.7  328.17  5472.8  339.87
  5548.8  347.95  5588.8  349.88  5648.9  348.27  5718.9  344.99  5755.1  346.41
#Mann= 9 ,-1 , 0
  4527.5     .16       0  4589.2      .1       0  4635.9     .05       0
  4734.8      .1       0    4849     .16       0  4995.5     .07       0
  5001.5     .16       0  5203.5     .05       0  5472.8     .16       0
Bank Sta=4978.5,5028.5
XS Rating Curve= 0 ,0
Exp/Cntr=0.3,0.1

Type RM Length L Ch R = 1 ,32904   ,750,750,750
BEGIN DESCRIPTION:
RUNNING CREEK 40.0
END DESCRIPTION:
XS GIS Cut Line= 3
      3589092.21     10368363.16      3587985.44     10368298.06
      3587296.24     10368280.72
#Sta/Elev= 30
    4349  359.85  4425.1  352.87  4499.4  346.18  4663.4   334.3  4711.6  329.75
  4789.9  322.61    4850  315.64  4940.1  309.62  4980.2  309.43  4997.2  308.31
    5000  307.81  5003.2  308.31  5020.3  309.88  5170.5  310.24  5190.6  309.11
  5220.6  309.86  5240.6  310.72  5290.7  315.91  5313.6  316.91  5350.8  320.07
    5515  322.99    5521  323.84  5591.1  325.95    5699  331.42  5896.5  339.61
  5913.9  340.75  5991.2   349.7  6011.2  353.34  6091.2  362.98  6147.1  368.59
#Mann= 8 ,-1 , 0
    4349     .05       0  4425.1      .1       0  4663.4     .05       0
  4711.6     .16       0  4997.2     .07       0  5003.2     .16       0
    5699     .05       0  5896.5     .16       0
Bank Sta=4980.2,5020.3
XS Rating Curve= 0 ,0
Exp/Cntr=0.3,0.1

Type RM Length L Ch R = 1 ,32154   ,758,758,758
BEGIN DESCRIPTION:
RUNNING CREEK 39.0
END DESCRIPTION:
XS GIS Cut Line= 3
      3589115.53     10367765.95      3588715.54     10367715.95
      3587642.11     10367641.64
#Sta/Elev= 30
  4191.5  366.05  4195.7  366.05  4263.5  355.63  4268.5  355.98  4352.8  344.54
  4456.1  332.15  4505.3  326.41  4555.2  322.59    4591  319.44  4593.8  318.54
  4618.1  317.53  4668.2  313.37  4708.3  311.17  4758.4  309.31  4818.6  309.29
  4838.6  308.15  4965.9  306.93  4968.7  306.43  4971.9  306.93  5015.2  307.89
  5059.1  307.88  5139.3  310.75  5164.1  311.13  5189.5  312.69  5220.8  312.04
    5420  316.12  5440.1  317.07  5490.2   320.6  5550.3  326.73  5670.6  342.05
#Mann= 8 ,-1 , 0
  4191.5     .16       0  4352.8     .05       0  4456.1      .1       0
  4555.2     .16       0  4965.9     .07       0  4971.9     .16       0
  5015.2      .1       0  5220.8     .16       0
Bank Sta=4818.6,5139.3
XS Rating Curve= 0 ,0
Exp/Cntr=0.3,0.1

Type RM Length L Ch R = 1 ,31396   ,450,450,450
BEGIN DESCRIPTION:
RUNNING CREEK 37.0
END DESCRIPTION:
XS GIS Cut Line= 3
      3589087.83     10367022.02      3588364.35     10367008.82
      3587565.71     10367058.73
#Sta/Elev= 30
  4261.1  362.54  4352.7  349.51  4446.9  335.13  4506.9  327.47  4553.8  323.12
  4566.9  322.53  4576.9  323.15  4628.1  319.12  4778.2  311.31  4846.9  306.82
  4876.9  308.03  4896.9  306.24  4926.9  307.37  4976.9  304.94  5084.1  304.69
  5086.9  304.19  5090.1  304.69  5150.1  305.39  5247.5  307.53  5397.7     315
  5426.8  318.67  5431.8  318.56  5437.8  320.74  5457.9  321.72  5592.1  336.27
  5598.1   337.9  5688.3  350.39  5718.4  353.69  5758.5   356.7  5784.9  356.56
#Mann= 7 ,-1 , 0
  4261.1     .16       0  4352.7      .1       0  4628.1     .16       0
  4778.2      .1       0  5084.1     .07       0  5090.1      .1       0
  5150.1     .16       0
Bank Sta=4926.9,5247.5
XS Rating Curve= 0 ,0
Exp/Cntr=0.3,0.1