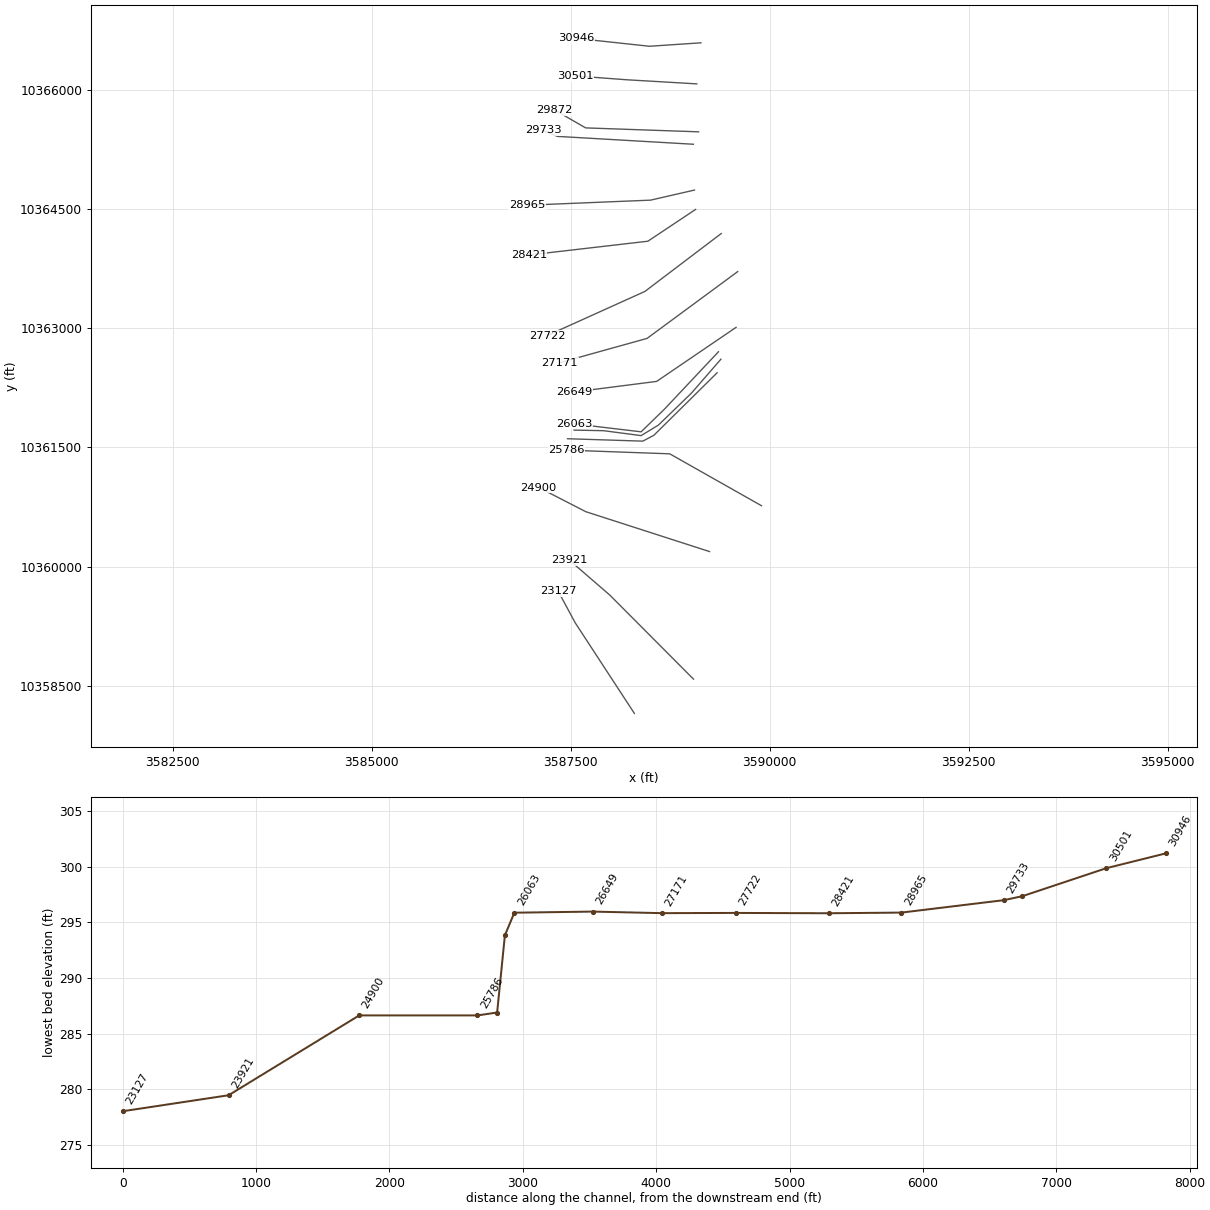
HEC-RAS study RUNNING CREEK.prj: RUNNING CREEK Base Level Engineering

--- RUNNING CREEK.g01 (geometry) --- (continued)

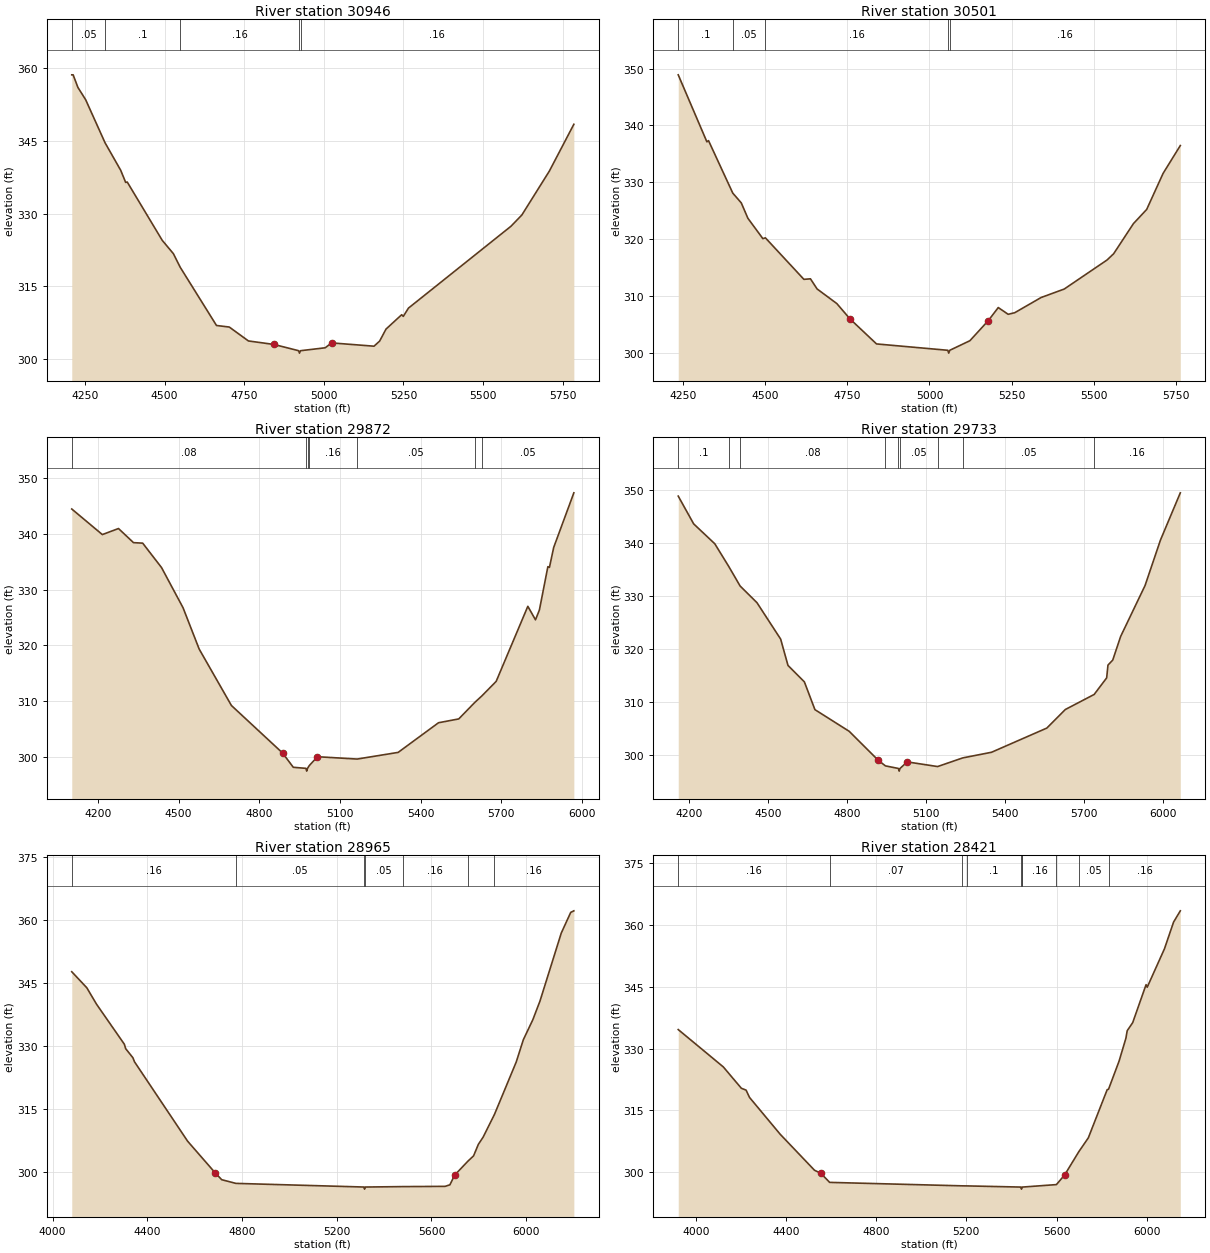
Type RM Length L Ch R = 1 ,30946   ,445,445,445
BEGIN DESCRIPTION:
RUNNING CREEK 36.0
END DESCRIPTION:
XS GIS Cut Line= 3
      3589135.62     10366587.99      3588488.91     10366544.59
      3587565.74     10366644.27
#Sta/Elev= 30
  4208.3  358.61  4212.6  358.61  4227.6  356.01  4251.9  353.48  4312.9  344.59
  4362.2   338.9  4377.5  336.43  4382.5   336.5  4492.5  324.47  4527.3  321.74
  4549.1   318.9  4662.8  306.92  4702.9   306.6  4763.1  303.73  4843.2  303.01
  4920.7  301.72  4923.4  301.22  4926.7  301.72  5004.1  302.32  5024.2  303.33
  5157.5  302.65  5175.1   303.7  5195.2  306.18  5244.3  309.14  5249.4   308.8
  5265.6   310.5  5587.5  327.38  5621.7   329.7  5708.2  338.77    5785  348.41
#Mann= 5 ,-1 , 0
  4208.3     .05       0  4312.9      .1       0  4549.1     .16       0
  4920.7     .07       0  4926.7     .16       0
Bank Sta=4843.2,5024.2
XS Rating Curve= 0 ,0
Exp/Cntr=0.3,0.1

Type RM Length L Ch R = 1 ,30501   ,629,629,629
BEGIN DESCRIPTION:
RUNNING CREEK 35.0
END DESCRIPTION:
XS GIS Cut Line= 3
      3589083.53      10366071.5      3588198.11     10366123.58
      3587560.04     10366171.33
#Sta/Elev= 30
  4236.1  348.92  4323.2  337.12  4328.2  337.33    4402  328.08  4427.9  326.35
  4447.9  323.65  4493.5  320.06  4501.2   320.2  4618.2  312.89  4638.2  312.98
  4658.3   311.2  4718.4  308.62  4758.4  305.92  4839.1  301.51  5055.9  300.39
  5058.7  299.89  5061.9  300.39  5123.1  302.08  5179.2  305.63  5209.3  307.92
  5239.4  306.73  5259.4  307.01  5339.7  309.69  5409.9  311.18  5540.2   316.3
  5560.3  317.41  5620.4  322.71  5660.6   325.2  5710.7  331.57  5762.9  336.46
#Mann= 5 ,-1 , 0
  4236.1      .1       0    4402     .05       0  4501.2     .16       0
  5055.9     .07       0  5061.9     .16       0
Bank Sta=4758.4,5179.2
XS Rating Curve= 0 ,0
Exp/Cntr=0.3,0.1

Type RM Length L Ch R = 1 ,29872   ,139,139,139
BEGIN DESCRIPTION:
RUNNING CREEK 34.0
END DESCRIPTION:
XS GIS Cut Line= 3
      3589105.87     10365468.61      3587686.58     10365518.09
      3587298.53     10365742.06
#Sta/Elev= 30
  4102.2  344.51    4216  339.91  4276.1     341  4331.9  338.46  4366.1  338.37
  4436.2  333.98  4516.2  326.76  4576.3  319.32  4696.3  309.17  4886.4  300.64
  4926.5  298.06  4973.5  297.87  4976.3  297.37  4979.5  297.87  4986.2  298.38
  5016.5  299.96  5164.1  299.54  5316.7  300.74  5466.8  306.07  5542.2  306.76
  5601.3   309.7    5628  310.89  5681.4  313.51  5799.2  327.01  5827.7  324.58
  5842.3  326.36  5873.8  334.14  5879.6  334.01  5895.4  337.59  5970.4  347.42
#Mann= 7 ,-1 , 0
  4102.2     .08       0  4973.5     .07       0  4979.5     .08       0
  4986.2     .16       0  5164.1     .05       0  5601.3     .16       0
    5628     .05       0
Bank Sta=4886.4,5016.5
XS Rating Curve= 0 ,0
Exp/Cntr=0.3,0.1

Type RM Length L Ch R = 1 ,29733   ,768,768,768
BEGIN DESCRIPTION:
RUNNING CREEK 33.0
END DESCRIPTION:
XS GIS Cut Line= 3
      3589040.73     10365312.36      3587332.41     10365411.32
      3587150.39     10365486.73
#Sta/Elev= 30
  4157.4   348.8  4216.1  343.57  4296.3  339.83  4349.6  335.54  4392.6  331.87
  4456.5  328.74  4546.7  321.87  4574.5  316.92  4636.8  313.82  4676.9  308.59
  4807.1  304.51  4917.3  299.07  4944.7     298  4994.4  297.51  4997.2  297.01
  5000.4  297.51  5027.5  298.75  5143.1  297.87  5238.7   299.5    5348  300.56
  5558.4  305.12  5628.5  308.61  5738.2  311.45  5785.7  314.57  5790.7  316.98
  5808.8  317.92  5838.8  322.37  5931.6  331.96  5990.2  340.53  6065.6  349.42
#Mann= 9 ,-1 , 0
  4157.4      .1       0  4349.6     .16       0  4392.6     .08       0
  4944.7     .05       0  4994.4     .04       0  5000.4     .05       0
  5143.1     .16       0  5238.7     .05       0  5738.2     .16       0
Bank Sta=4917.3,5027.5
XS Rating Curve= 0 ,0
Exp/Cntr=0.3,0.1

Type RM Length L Ch R = 1 ,28965   ,544,544,544
BEGIN DESCRIPTION:
RUNNING CREEK 32.0
END DESCRIPTION:
XS GIS Cut Line= 3
      3589054.02     10364736.29      3588502.25     10364609.47
      3586949.01     10364545.81
#Sta/Elev= 30
  4080.7  347.74  4144.2  343.92  4185.3     340  4302.8  330.45  4308.4  329.39
  4339.2  327.21  4345.6  326.27  4570.1  307.32    4687  299.74    4714  298.14
  4773.9  297.26  5314.6  296.39  5317.3  295.89  5320.6  296.39  5478.9  296.49
  5657.8  296.55  5677.9  296.92  5697.9  299.22  5753.3  302.52  5777.9  303.83
    5798  306.56    5818  308.27    5866   313.7  5958.1  326.22  5988.1  331.53
  6028.2   336.3  6058.2  340.72  6148.3  356.97  6188.3   361.9  6201.4  362.27
#Mann= 7 ,-1 , 0
  4080.7     .16       0  4773.9     .05       0  5314.6    .033       0
  5320.6     .05       0  5478.9     .16       0  5753.3     .05       0
    5866     .16       0
Bank Sta=4687,5697.9
XS Rating Curve= 0 ,0
Exp/Cntr=0.3,0.1

Type RM Length L Ch R = 1 ,28421   ,699,699,699
BEGIN DESCRIPTION:
RUNNING CREEK 31.0
END DESCRIPTION:
XS GIS Cut Line= 3
      3589068.48     10364493.02      3588468.49     10364093.03
       3586972.4     10363919.58
#Sta/Elev= 30
  3921.9  334.62  4121.9  325.54  4201.9  320.35  4222.9   319.9  4237.9  318.14
  4374.2  309.17  4526.4  300.42  4554.5  299.68  4593.6  297.47  5179.2  296.63
  5204.7  296.61  5441.7  296.33  5444.5  295.83  5447.7  296.33  5448.9  296.33
  5599.4  296.93    5636  299.27  5698.5   304.9  5741.1   308.3  5824.8  320.02
  5830.6   320.1  5877.6  326.97  5907.8  332.53  5913.5  334.34    5938  336.32
  5997.2  345.54  6002.2  344.91  6078.9  354.27  6119.2  360.75  6149.1  363.49
#Mann= 10 ,-1 , 0
  3921.9     .16       0  4593.6     .07       0  5179.2     .05       0
  5204.7      .1       0  5441.7     .07       0  5447.7      .1       0
  5448.9     .16       0  5599.4      .1       0  5698.5     .05       0
  5830.6     .16       0
Bank Sta=4554.5,5636
XS Rating Curve= 0 ,0
Exp/Cntr=0.3,0.1

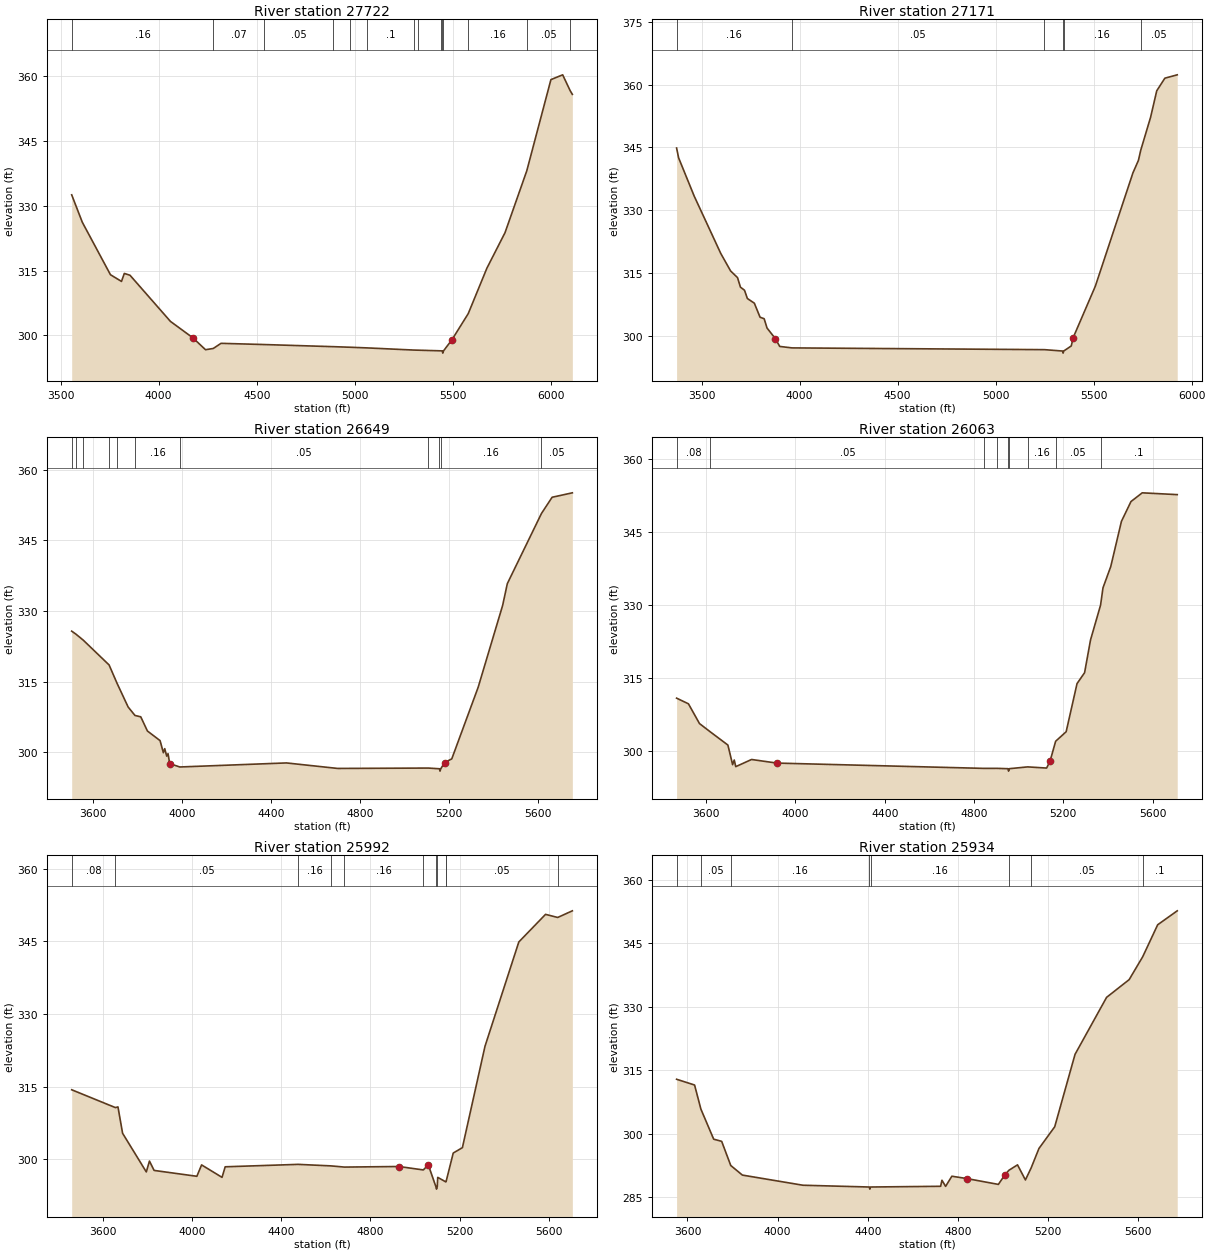
Type RM Length L Ch R = 1 ,27722   ,551,551,551
BEGIN DESCRIPTION:
RUNNING CREEK 29.0
END DESCRIPTION:
XS GIS Cut Line= 3
      3589389.98     10364189.52      3588430.75     10363461.25
      3587202.63     10362906.17
#Sta/Elev= 30
  3556.6  332.54  3610.7  326.19  3754.2  314.03  3810.4  312.48  3824.9  314.33
    3854   313.9    4060  303.21  4174.3  299.41  4238.8  296.65  4278.3  296.94
  4317.8  298.13  4536.7  297.85  4887.6  297.36  4976.9  297.22  5063.3  297.07
  5300.3  296.57  5324.3  296.54  5439.2  296.39  5445.7  296.36  5448.4  295.86
  5451.7  296.36  5494.7  298.94  5578.1  305.02  5673.2  315.55  5765.6  323.78
  5876.6  338.13  5999.5  359.24  6059.4  360.35  6097.7  356.67  6108.7  355.83
#Mann= 14 ,-1 , 0
  3556.6     .16       0  4278.3     .07       0  4536.7     .05       0
  4887.6     .07       0  4976.9     .05       0  5063.3      .1       0
  5300.3     .05       0  5324.3     .16       0  5439.2      .1       0
  5445.7    .033       0  5451.7      .1       0  5578.1     .16       0
  5876.6     .05       0  6097.7      .1       0
Bank Sta=4174.3,5494.7
XS Rating Curve= 0 ,0
Exp/Cntr=0.3,0.1

Type RM Length L Ch R = 1 ,27171   ,522,522,522
BEGIN DESCRIPTION:
RUNNING CREEK 28.0
END DESCRIPTION:
XS GIS Cut Line= 3
      3589597.44     10363711.27      3588458.53     10362870.98
      3587361.33     10362565.43
#Sta/Elev= 30
  3372.2  344.86  3382.5  342.52  3461.9  333.38  3597.6  319.66  3647.8  315.48
  3683.2  313.88  3697.9  311.61  3718.7  310.87  3733.4  308.89  3768.8  307.78
  3798.1  304.42    3819  304.06  3833.6  301.84  3875.9  299.32  3898.4  297.44
  3961.1  297.09  5249.2  296.67  5341.4  296.34  5344.1  295.84  5347.4  296.34
  5385.9  297.56  5395.6  299.54  5508.6  311.83  5700.4  338.91  5728.5  341.91
  5740.2  344.31  5790.8  352.25  5821.9  358.53  5863.4  361.55  5926.5  362.35
#Mann= 6 ,-1 , 0
  3372.2     .16       0  3961.1     .05       0  5249.2     .16       0
  5341.4    .033       0  5347.4     .16       0  5740.2     .05       0
Bank Sta=3875.9,5395.6
XS Rating Curve= 0 ,0
Exp/Cntr=0.3,0.1

Type RM Length L Ch R = 1 ,26649   ,586,586,586
BEGIN DESCRIPTION:
RUNNING CREEK 27.0
END DESCRIPTION:
XS GIS Cut Line= 3
      3589576.56     10363009.85      3588578.24     10362330.09
      3587541.88     10362197.37
#Sta/Elev= 30
  3503.2   325.7  3522.1  325.07    3555   323.8  3671.5  318.52  3707.2  314.64
  3757.1   309.6  3787.9   307.8    3814  307.51  3843.9   304.5  3900.8  302.46
  3915.7  299.89  3921.8  300.75  3930.7  299.17  3936.7  299.69  3944.1  297.57
  3989.7  296.86  4469.4  297.72  4699.8  296.55  5107.5  296.63  5157.8  296.48
  5160.5  295.98  5163.8  296.48  5180.9  297.79  5213.3  298.58  5332.1  313.79
  5442.3  331.19  5463.2  335.78  5616.8  350.68  5664.8  354.13  5755.8  355.07
#Mann= 11 ,-1 , 0
  3503.2      .1       0  3522.1     .05       0    3555      .1       0
  3671.5     .16       0  3707.2     .05       0  3787.9     .16       0
  3989.7     .05       0  5107.5     .16       0  5157.8    .033       0
  5163.8     .16       0  5616.8     .05       0
Bank Sta=3944.1,5180.9
XS Rating Curve= 0 ,0
Exp/Cntr=0.3,0.1

Type RM Length L Ch R = 1 ,26063   ,71,71,71
BEGIN DESCRIPTION:
Mapping XS f12f309f
END DESCRIPTION:
XS GIS Cut Line= 4
      3589355.61      10362703.1      3588674.22     10361978.31
      3588383.42     10361696.19       3587546.4     10361795.94
#Sta/Elev= 30
  3467.3  310.86  3520.4   309.7  3569.8  305.65  3617.8  303.96  3697.2  301.23
  3718.3  297.21  3725.6  298.16  3732.4   296.8  3803.2  298.27  3916.5  297.53
  4846.7  296.44  4901.7  296.45  4951.9  296.38  4954.6  295.88  4957.9  296.38
  5040.1  296.75    5125  296.51  5140.5  297.93  5165.4  302.01  5212.6  303.97
  5261.3  313.85  5295.1  316.08  5321.8  322.82  5366.7  329.95  5377.6  333.51
  5412.4  337.88  5460.2  347.15    5503  351.22  5553.4  353.01  5710.2  352.64
#Mann= 9 ,-1 , 0
  3467.3     .08       0  3617.8     .05       0  4846.7     .16       0
  4901.7     .05       0  4951.9    .033       0  4957.9     .05       0
  5040.1     .16       0  5165.4     .05       0  5366.7      .1       0
Bank Sta=3916.5,5140.5
XS Rating Curve= 0 ,0
Exp/Cntr=0.3,0.1

Type RM Length L Ch R = 1 ,25992   ,58,58,58
BEGIN DESCRIPTION:
Mapping XS af237081
END DESCRIPTION:
XS GIS Cut Line= 6
      3589386.43     10362609.78      3589015.37      10362182.3
      3588600.87     10361780.82      3588383.86     10361648.45
      3587913.94      10361710.3      3587541.81     10361717.89
#Sta/Elev= 30
  3458.9  314.35  3655.2  310.67  3666.6  310.81  3687.4  305.37  3793.8  297.39
    3808  299.63  3828.9   297.7  4020.8  296.49    4042  298.84  4133.8  296.27
    4148  298.45  4475.7  298.95    4622  298.64  4683.4  298.39  4928.3  298.51
  5037.5   297.8  5059.6  298.87  5093.9  294.34  5096.7  293.84  5099.9  294.34
  5102.1  296.27  5138.5  295.33  5139.6  295.39  5171.7  301.29  5212.8   302.4
  5314.3  323.33  5466.1  344.86  5586.1  350.56  5640.7  349.92  5706.4  351.29
#Mann= 11 ,-1 , 0
  3458.9     .08       0  3655.2     .05       0  4475.7     .16       0
    4622     .05       0  4683.4     .16       0  5037.5      .1       0
  5093.9     .07       0  5099.9      .1       0  5138.5     .16       0
  5139.6     .05       0  5640.7      .1       0
Bank Sta=4928.3,5059.6
XS Rating Curve= 0 ,0
Exp/Cntr=0.3,0.1

Type RM Length L Ch R = 1 ,25934   ,148,148,148
BEGIN DESCRIPTION:
Mapping XS 98e9512a
END DESCRIPTION:
XS GIS Cut Line= 4
      3589338.27     10362438.36      3588544.01     10361652.79
      3588405.12       10361579.      3587458.91     10361609.38
#Sta/Elev= 30
  3551.7  312.87  3631.5  311.51  3659.5  305.82  3716.3   298.7  3751.7  298.19
    3792  292.48  3843.6  290.21  4112.3  287.81  4406.3  287.39  4409.1  286.89
  4412.3  287.39  4723.2  287.56  4728.9  288.99  4745.2  287.54  4772.9  289.94
  4839.1  289.39  4979.2  288.01  5009.2  290.33  5025.9  291.34  5064.2  292.63
  5099.3  289.06  5124.9  291.93  5159.3   296.5  5229.3  301.64  5319.4  318.76
  5459.4  332.24  5559.5  336.43  5619.7  341.85    5686   349.4  5772.8   352.7
#Mann= 8 ,-1 , 0
  3551.7     .08       0  3659.5     .05       0    3792     .16       0
  4406.3     .07       0  4412.3     .16       0  5025.9      .1       0
  5124.9     .05       0  5619.7      .1       0
Bank Sta=4839.1,5009.2
XS Rating Curve= 0 ,0
Exp/Cntr=0.3,0.1

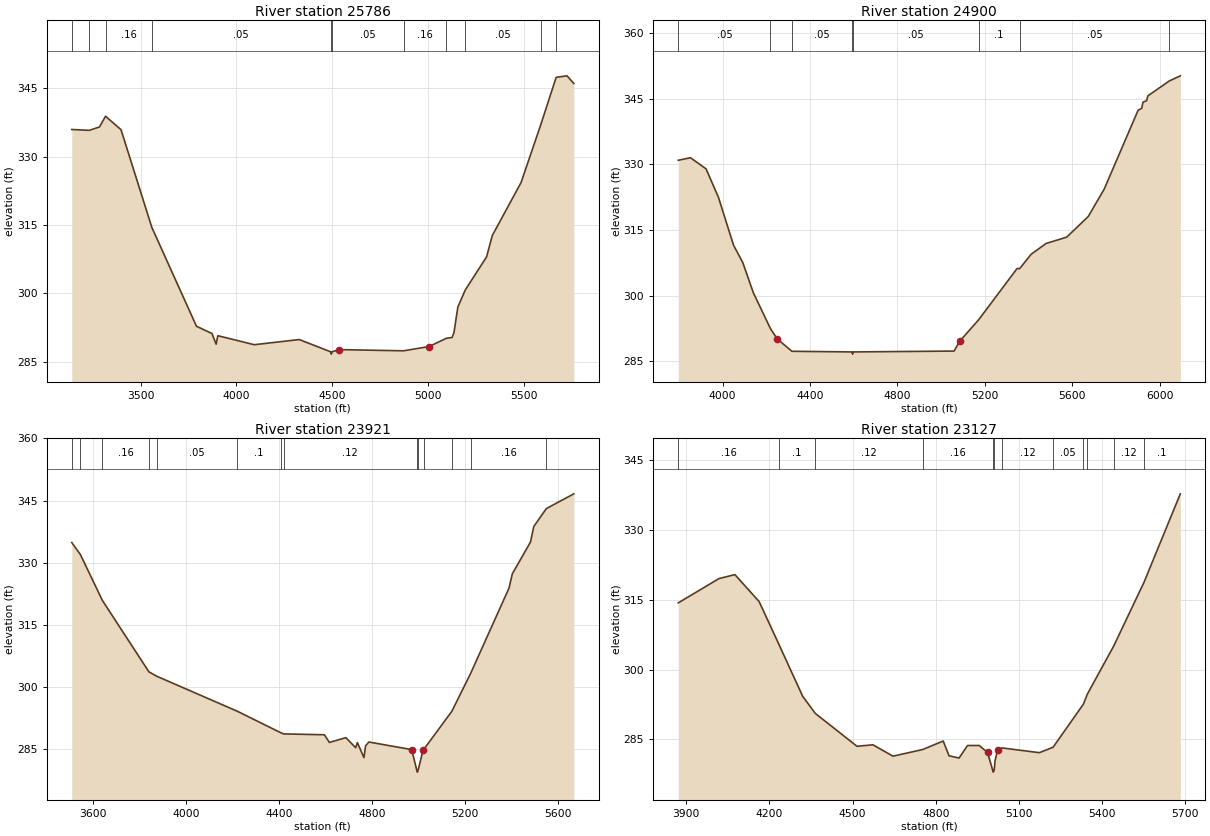
Type RM Length L Ch R = 1 ,25786   ,886,886,886
BEGIN DESCRIPTION:
RUNNING CREEK 26.0
END DESCRIPTION:
XS GIS Cut Line= 3
      3589896.02     10360766.81      3588743.25     10361419.59
      3587446.55     10361466.13
#Sta/Elev= 30
  3139.7  335.98    3231  335.79  3284.6  336.54    3316  338.89    3397  335.94
  3557.8  314.48  3791.1  292.75    3872  291.16  3893.6  288.82  3902.7  290.68
  4092.7   288.7  4327.9  289.83  4492.6  287.13  4495.4  286.63  4498.6  287.13
  4535.7  287.62    4873  287.36    5006   288.3  5095.9  290.11    5126  290.28
    5136  291.38  5156.1  296.95  5194.9  300.72  5306.2  307.99  5336.2   312.7
  5486.3  324.32  5590.9  337.23  5669.7  347.44  5726.4  347.77    5762  346.09
#Mann= 11 ,-1 , 0
  3139.7     .16       0    3231      .1       0    3316     .16       0
  3557.8     .05       0  4492.6     .07       0  4498.6     .05       0
    4873     .16       0  5095.9      .1       0  5194.9     .05       0
  5590.9      .1       0  5669.7     .05       0
Bank Sta=4535.7,5006
XS Rating Curve= 0 ,0
Exp/Cntr=0.3,0.1

Type RM Length L Ch R = 1 ,24900   ,979,979,979
BEGIN DESCRIPTION:
RUNNING CREEK 25.0
END DESCRIPTION:
XS GIS Cut Line= 3
      3589243.23     10360190.42      3587689.33     10360691.64
      3587097.42     10360995.97
#Sta/Elev= 30
  3796.6  330.92  3852.5  331.51  3923.9  328.97  3980.7  322.45  4050.1  311.48
    4092  307.56  4140.9   300.6  4218.6  292.47  4249.6  290.12    4317  287.28
  4591.9  287.13  4594.6  286.63  4597.9  287.13  5059.3  287.33  5086.1  289.64
  5171.4  294.45  5347.8   306.2  5359.1  306.15  5411.9  309.44  5480.4  311.91
  5574.8  313.36  5673.6  318.08  5746.6  324.34  5901.8  342.36  5918.4  342.82
    5924  344.21  5940.6  344.51  5946.2  345.63  6043.9  349.03  6094.9  350.22
#Mann= 8 ,-1 , 0
  3796.6     .05       0  4218.6     .16       0    4317     .05       0
  4591.9     .03       0  4597.9     .05       0  5171.4      .1       0
  5359.1     .05       0  6043.9      .1       0
Bank Sta=4249.6,5086.1
XS Rating Curve= 0 ,0
Exp/Cntr=0.3,0.1

Type RM Length L Ch R = 1 ,23921   ,794,794,794
BEGIN DESCRIPTION:
RUNNING CREEK 24.0
END DESCRIPTION:
XS GIS Cut Line= 3
      3589041.84     10358586.27      3587992.11     10359641.64
      3587486.69     10360078.97
#Sta/Elev= 30
  3510.1  334.88  3547.3  331.97  3641.4  320.92  3841.6  303.65    3875   302.6
  4221.3  294.14  4408.1  288.95    4420  288.67  4595.6  288.46  4616.8  286.61
  4687.5  287.76    4730  285.33    4737  286.58  4765.3  282.94  4772.4   285.8
  4786.5  286.71  4970.4  284.88  4992.1  279.94  4994.9  279.44  4998.1  279.94
    5020  284.89  5024.9  285.12    5143  294.14  5223.8   303.3  5388.6  323.89
  5402.8  327.33  5480.7  334.99  5494.9  338.74  5548.7  343.07    5667  346.64
#Mann= 14 ,-1 , 0
  3510.1     .16       0  3547.3      .1       0  3641.4     .16       0
  3841.6      .1       0    3875     .05       0  4221.3      .1       0
  4408.1     .05       0    4420     .12       0  4992.1     .07       0
  4998.1     .12       0  5024.9     .05       0    5143     .12       0
  5223.8     .16       0  5548.7     .05       0
Bank Sta=4970.4,5020
XS Rating Curve= 0 ,0
Exp/Cntr=0.3,0.1

Type RM Length L Ch R = 1 ,23127   ,979,979,979
BEGIN DESCRIPTION:
RUNNING CREEK 22.0
END DESCRIPTION:
XS GIS Cut Line= 3
      3588298.81     10358155.69      3587555.75     10359294.59
      3587342.13      10359691.6
#Sta/Elev= 30
    3871  314.28    4018  319.49  4075.3  320.34  4162.8  314.56  4234.1  305.39
  4319.9  294.25  4365.6  290.57  4515.8  283.54  4573.1  283.86  4645.5  281.42
  4752.3  282.84  4826.6  284.67  4847.6   281.5  4883.9  281.02  4914.1   283.7
  4956.3  283.72  4986.5  282.23  5004.6   278.5  5007.4     278  5010.6   278.5
  5013.6  280.46  5022.7  282.64  5038.6  283.19  5173.5  282.17  5222.8  283.33
  5332.3  292.58  5346.1  294.68  5441.5  305.03  5550.7  318.68  5681.7  337.66
#Mann= 12 ,-1 , 0
    3871     .16       0  4234.1      .1       0  4365.6     .12       0
  4752.3     .16       0  5004.6     .07       0  5010.6     .16       0
  5038.6     .12       0  5222.8     .05       0  5332.3     .12       0
  5346.1     .05       0  5441.5     .12       0  5550.7      .1       0
Bank Sta=4986.5,5022.7
XS Rating Curve= 0 ,0
Exp/Cntr=0.3,0.1