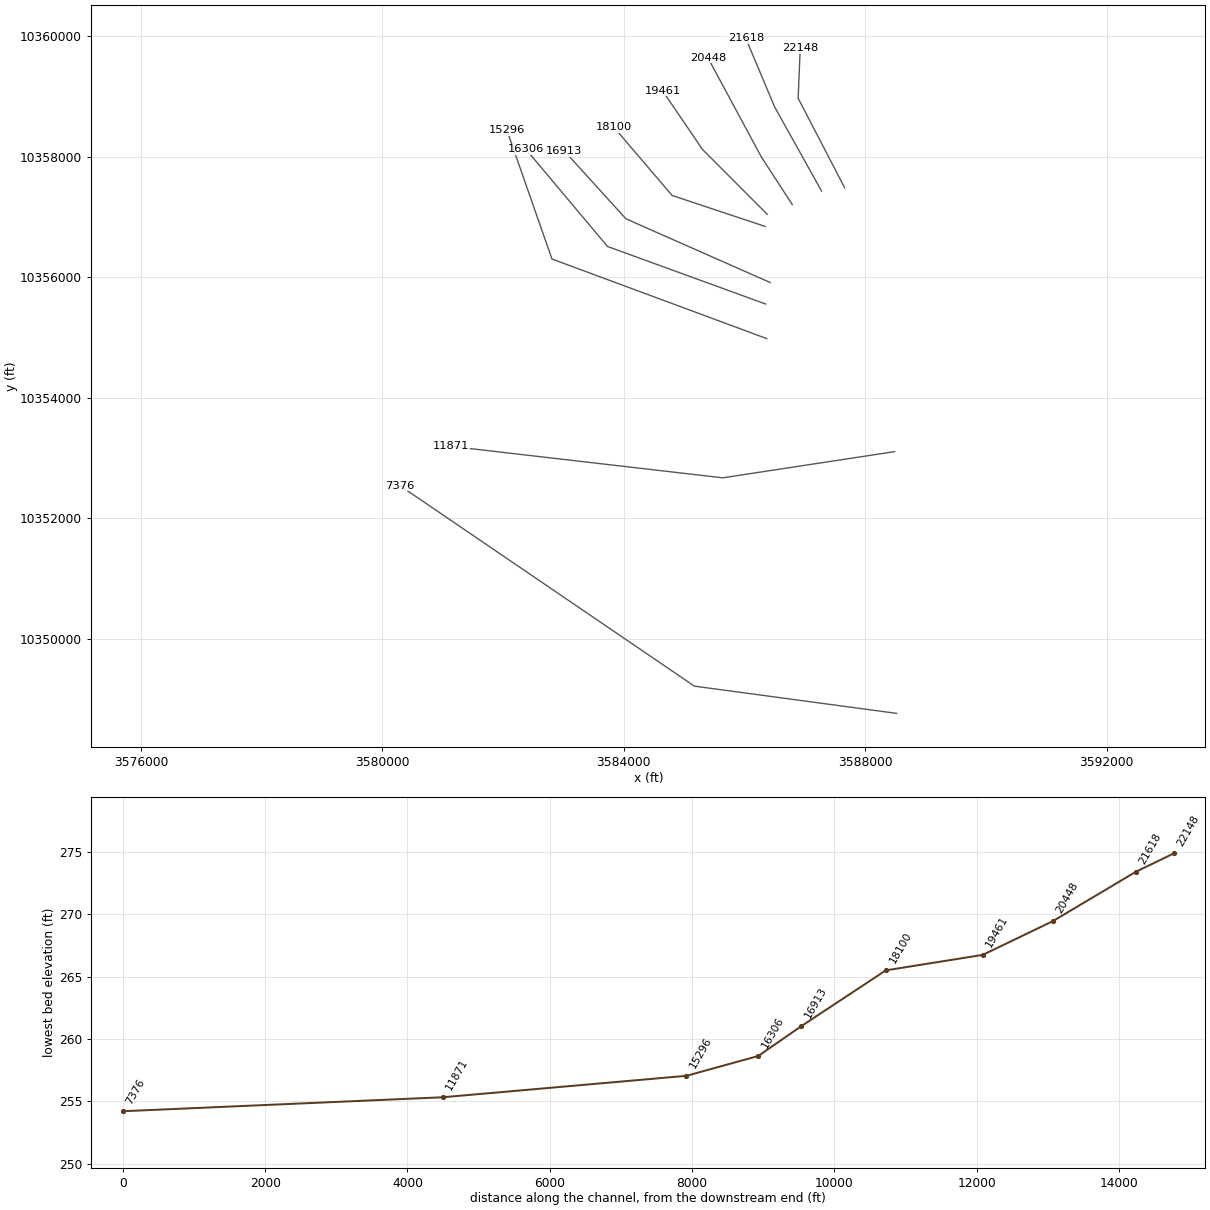
HEC-RAS study RUNNING CREEK.prj: RUNNING CREEK Base Level Engineering

--- RUNNING CREEK.g01 (geometry) --- (continued)

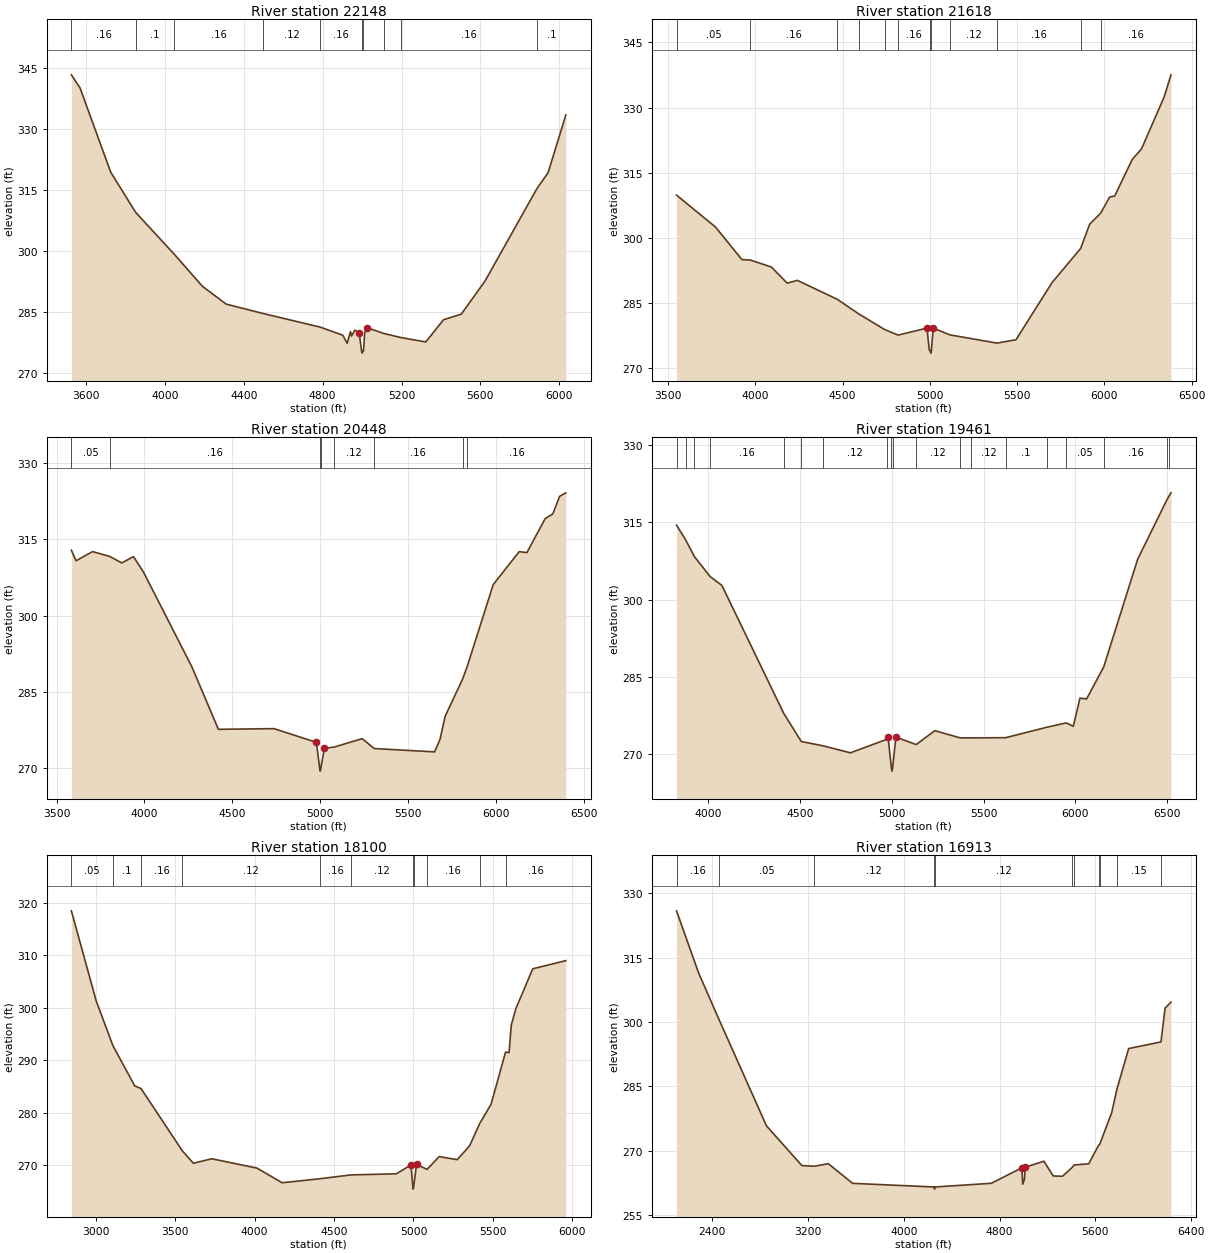
Type RM Length L Ch R = 1 ,22148   ,530,530,530
BEGIN DESCRIPTION:
RUNNING CREEK 21.0
END DESCRIPTION:
XS GIS Cut Line= 3
      3587659.91      10357482.1      3586889.08      10358968.2
      3586923.81     10359801.56
#Sta/Elev= 30
  3525.3  343.42  3569.5  340.16  3724.4  319.48    3851  309.57  4046.3  299.28
  4189.4  291.37  4310.5  286.95  4497.8  284.64  4787.1  281.29  4902.2  279.28
  4924.3   277.3  4940.8  280.18  4946.5  279.09  4962.9  280.55  4985.1  279.93
  4997.5  275.38  5000.3  274.88  5003.5  275.38  5007.2  275.46  5012.8  279.74
  5023.1  281.17  5109.6  279.73    5198   278.7    5323  277.63    5413   283.1
  5503.1  284.48  5623.2   292.6  5887.1  315.42  5943.5  319.32  6033.5  333.54
#Mann= 10 ,-1 , 0
  3525.3     .16       0    3851      .1       0  4046.3     .16       0
  4497.8     .12       0  4787.1     .16       0  4997.5     .07       0
  5003.5     .16       0  5109.6     .12       0    5198     .16       0
  5887.1      .1       0
Bank Sta=4985.1,5023.1
XS Rating Curve= 0 ,0
Exp/Cntr=0.3,0.1

Type RM Length L Ch R = 1 ,21618   ,1170,1170,1170
BEGIN DESCRIPTION:
RUNNING CREEK 20.0
END DESCRIPTION:
XS GIS Cut Line= 3
      3587277.95     10357426.57      3586500.19     10358822.36
      3586021.04     10359961.22
#Sta/Elev= 30
  3548.1  309.82  3770.8   302.5  3922.8  294.97  3970.8  294.87  4091.9  293.25
  4182.3  289.54  4240.8  290.18  4468.9  285.83    4592  282.47  4740.8  278.85
    4818  277.58  4983.5  279.19  4996.3  274.11  5002.3  273.92    5005  273.42
  5008.3  273.92  5019.2  279.19  5114.3  277.63  5384.4  275.73  5493.5  276.51
  5699.7  289.66  5864.1  297.55  5915.5  303.13  5978.8  305.67    6030  309.37
  6059.2  309.64  6159.6  318.05  6212.5  320.47    6342   332.4  6381.5  337.54
#Mann= 12 ,-1 , 0
  3548.1     .05       0  3970.8     .16       0  4468.9     .12       0
    4592     .16       0  4740.8     .12       0    4818     .16       0
  5002.3     .07       0  5008.3     .16       0  5114.3     .12       0
  5384.4     .16       0  5864.1     .05       0  5978.8     .16       0
Bank Sta=4983.5,5019.2
XS Rating Curve= 0 ,0
Exp/Cntr=0.3,0.1

Type RM Length L Ch R = 1 ,20448   ,987,987,987
BEGIN DESCRIPTION:
RUNNING CREEK 18.0
END DESCRIPTION:
XS GIS Cut Line= 3
      3586791.85     10357204.32      3586277.97     10357995.98
      3585392.09     10359641.67
#Sta/Elev= 30
  3584.7  312.86  3611.5   310.8  3705.1   312.6    3803  311.65  3871.3  310.37
  3937.8  311.61  3995.1  308.56    4270  289.96    4421  277.67  4737.5   277.8
  4978.5  275.11  4997.6  269.95  5000.3  269.45  5003.6  269.95  5023.3  273.91
  5080.5  274.19  5239.1  275.83  5307.2  273.89    5651  273.23    5682  275.72
  5711.1  280.24  5809.9  287.52  5835.4  289.89  5984.5  306.13  6132.2  312.59
    6176   312.4  6279.8  319.08  6323.6  320.02  6361.8  323.45  6397.5  324.15
#Mann= 8 ,-1 , 0
  3584.7     .05       0    3803     .16       0  4997.6     .07       0
  5003.6     .16       0  5080.5     .12       0  5307.2     .16       0
  5809.9     .05       0  5835.4     .16       0
Bank Sta=4978.5,5023.3
XS Rating Curve= 0 ,0
Exp/Cntr=0.3,0.1

Type RM Length L Ch R = 1 ,19461   ,1361,1361,1361
BEGIN DESCRIPTION:
RUNNING CREEK 17.0
END DESCRIPTION:
XS GIS Cut Line= 3
       3586375.2     10357044.58      3585303.55     10358118.93
      3584642.08     10359091.68
#Sta/Elev= 30
  3826.6  314.43  3876.3  311.57  3923.8  308.34  4009.7  304.46  4074.2  302.72
  4410.1  277.98  4506.3  272.48  4623.3  271.66  4774.2  270.29    4973  272.92
  4979.3  273.32  4997.5  267.24  5000.3  266.74  5003.5  267.24  5021.7  273.34
  5132.2  271.89  5233.9  274.58  5372.7  273.18  5432.6  273.19  5619.6  273.22
  5844.2  275.25  5949.7  276.09  5988.3  275.44  6024.5  280.89  6060.8  280.74
  6153.8  286.92  6339.3  307.85  6500.7  319.51  6509.1  320.03  6520.4  320.69
#Mann= 19 ,-1 , 0
  3826.6      .1       0  3876.3     .16       0  3923.8     .05       0
  4009.7     .16       0  4410.1     .12       0  4506.3     .16       0
  4623.3     .12       0    4973     .16       0  4997.5     .07       0
  5003.5     .16       0  5132.2     .12       0  5372.7      .1       0
  5432.6     .12       0  5619.6      .1       0  5844.2     .16       0
  5949.7     .05       0  6153.8     .16       0  6500.7     .05       0
  6509.1     .16       0
Bank Sta=4979.3,5021.7
XS Rating Curve= 0 ,0
Exp/Cntr=0.3,0.1

Type RM Length L Ch R = 1 ,18100   ,1187,1187,1187
BEGIN DESCRIPTION:
RUNNING CREEK 16.0
END DESCRIPTION:
XS GIS Cut Line= 3
      3586340.21     10356842.27      3584800.58     10357355.48
      3583834.51     10358487.87
#Sta/Elev= 30
  2847.5  318.46  3003.6  301.33  3108.4  292.83  3246.1  285.14  3285.5  284.65
  3545.3  272.81    3615  270.42  3730.9  271.28  4015.5   269.5  4173.7  266.71
  4413.2  267.48  4606.5  268.21  4892.2  268.41  4984.4  270.11  4995.7     266
  4998.4   265.5  5001.7     266  5019.5  270.23  5085.2  269.25    5162  271.69
  5275.4  271.11  5353.3  273.73  5416.4  277.96  5488.4  281.65  5579.6  291.57
  5601.5  291.48  5615.7  296.74  5644.3  299.83  5750.8  307.43  5958.9  308.98
#Mann= 11 ,-1 , 0
  2847.5     .05       0  3108.4      .1       0  3285.5     .16       0
  3545.3     .12       0  4413.2     .16       0  4606.5     .12       0
  4995.7     .07       0  5001.7     .12       0  5085.2     .16       0
  5416.4     .05       0  5579.6     .16       0
Bank Sta=4984.4,5019.5
XS Rating Curve= 0 ,0
Exp/Cntr=0.3,0.1

Type RM Length L Ch R = 1 ,16913   ,607,607,607
BEGIN DESCRIPTION:
RUNNING CREEK 15.0
END DESCRIPTION:
XS GIS Cut Line= 3
      3586423.84     10355912.63      3584034.92      10356968.2
      3583014.05     10358093.23
#Sta/Elev= 30
  2100.8  325.95  2283.5  311.59  2457.9  300.46  2852.3  275.79  3148.3  266.52
  3252.3  266.37    3369  266.97  3571.8  262.38  4253.4  261.53  4256.2  261.03
  4259.4  261.53  4730.8  262.39  4986.3     266    4993  262.18  5007.2  263.25
  5014.3  266.14  5170.1  267.54  5247.8   264.1  5325.5  264.03  5407.9  266.14
  5420.8  266.65  5545.1  266.95  5626.6  271.24    5636  271.45  5736.4  278.86
  5780.3  284.38  5878.3  293.82  6148.1  295.37  6182.4  303.25  6231.7  304.64
#Mann= 11 ,-1 , 0
  2100.8     .16       0  2457.9     .05       0  3252.3     .12       0
  4253.4     .07       0  4259.4     .12       0  5407.9     .16       0
  5420.8     .12       0  5626.6      .1       0    5636     .05       0
  5780.3     .15       0  6148.1      .1       0
Bank Sta=4986.3,5014.3
XS Rating Curve= 0 ,0
Exp/Cntr=0.3,0.1

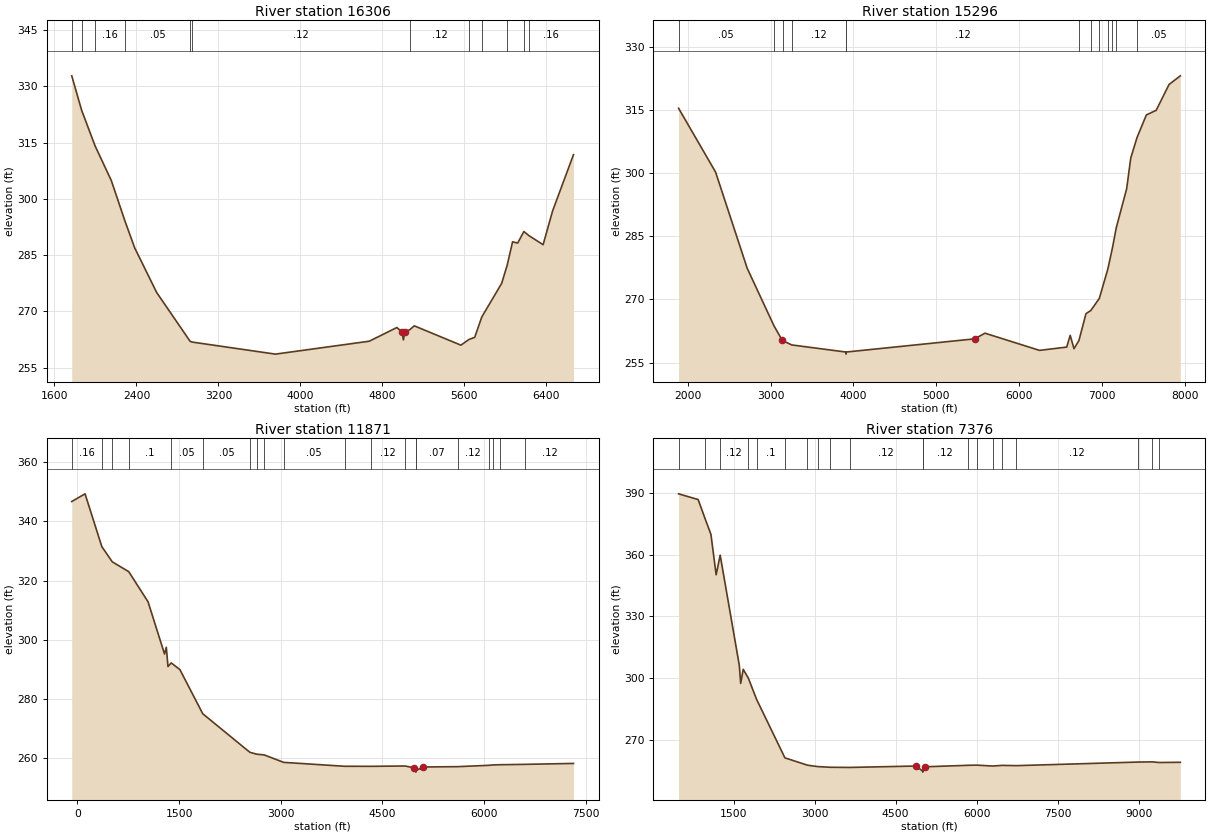
Type RM Length L Ch R = 1 ,16306   ,1010,1010,1010
BEGIN DESCRIPTION:
RUNNING CREEK 14.0
END DESCRIPTION:
XS GIS Cut Line= 3
      3586350.84     10355555.02      3583729.36     10356509.86
      3582376.12     10358123.34
#Sta/Elev= 30
  1768.7  332.83  1865.5  323.62  1996.2  314.16  2154.6  304.92    2288   294.1
  2383.2  286.94  2597.5  275.05  2923.7  262.05  2942.6  261.85    3756  258.63
  4671.5  262.07  4940.8  265.72  4991.5  264.53  5004.7  262.42  5018.9  264.47
  5069.6   265.2  5111.3  266.17    5566  261.02  5645.3  262.55  5700.6   263.1
  5769.4  268.52  5963.4  277.49  6017.5  282.34    6070  288.58  6119.5  288.24
  6180.5  291.32    6229  290.24    6368  287.81  6460.3  296.78  6664.5  311.82
#Mann= 12 ,-1 , 0
  1768.7      .1       0  1865.5     .05       0  1996.2     .16       0
    2288     .05       0  2923.7     .16       0  2942.6     .12       0
  5069.6     .12       0  5645.3     .16       0  5769.4     .05       0
  6017.5     .16       0  6180.5     .05       0    6229     .16       0
Bank Sta=4991.5,5018.9
XS Rating Curve= 0 ,0
Exp/Cntr=0.3,0.1

Type RM Length L Ch R = 1 ,15296   ,3425,3425,3425
BEGIN DESCRIPTION:
RUNNING CREEK 13.0
END DESCRIPTION:
XS GIS Cut Line= 3
      3586368.24     10354982.09      3582809.22     10356301.53
      3582062.75     10358436.78
#Sta/Elev= 30
  1889.3  315.37  2336.2  300.22  2717.1  277.44  3041.5  263.74  3138.9  260.38
  3148.4  260.22  3255.3  259.22  3908.2  257.54  3910.9  257.04  3914.2  257.54
  5466.5  260.67    5588  262.01  6246.6  257.93  6575.2  258.71  6617.4  261.51
  6663.1  258.33  6722.9  260.27  6807.7  266.63  6866.3  267.39  6968.9  270.26
  7071.5   277.2  7127.4  282.24  7174.1  287.07  7299.1  296.27  7348.3  303.54
  7423.4  308.38  7536.8  313.78  7655.5  314.88  7810.9  321.01    7947  323.06
#Mann= 13 ,-1 , 0
  1889.3     .05       0  3041.5     .12       0  3148.4     .07       0
  3255.3     .12       0  3908.2     .07       0  3914.2     .12       0
  6722.9     .16       0  6866.3     .12       0  6968.9     .05       0
  7071.5     .16       0  7127.4     .08       0  7174.1     .16       0
  7423.4     .05       0
Bank Sta=3138.9,5466.5
XS Rating Curve= 0 ,0
Exp/Cntr=0.3,0.1

Type RM Length L Ch R = 1 ,11871   ,4495,4495,4495
BEGIN DESCRIPTION:
RUNNING CREEK 2.0
END DESCRIPTION:
XS GIS Cut Line= 3
      3588486.28     10353107.08      3585639.08     10352673.06
      3581142.53     10353193.89
#Sta/Elev= 30
   -84.3  346.73   112.1  349.33   359.7   331.5   513.7  326.36     757  323.04
  1042.2  312.85  1285.5  295.21  1311.5  297.49  1336.1     291  1384.5  292.21
  1512.2  289.95  1849.7  275.04  2545.1  262.02  2644.4  261.39  2757.4  261.13
  3043.2  258.62  3942.3   257.3  4338.7  257.28  4838.4  257.39  4967.2  256.77
    4993  255.82  4995.8  255.32    4999  255.82  5098.1  257.06  5614.8  257.17
    6072  257.62  6140.3  257.76  6240.2  257.82  6610.3  257.95  7322.4  258.26
#Mann= 20 ,-1 , 0
   -84.3     .16       0   359.7     .05       0   513.7     .16       0
     757      .1       0  1384.5     .05       0  1849.7     .05       0
  2545.1      .1       0  2644.4     .16       0  2757.4      .1       0
  3043.2     .05       0  3942.3     .07       0  4338.7     .12       0
  4838.4     .07       0    4993     .07       0    4999     .07       0
  5614.8     .12       0    6072     .07       0  6140.3     .12       0
  6240.2     .07       0  6610.3     .12       0
Bank Sta=4967.2,5098.1
XS Rating Curve= 0 ,0
Exp/Cntr=0.3,0.1

Type RM Length L Ch R = 1 ,7376    ,0,0,0
BEGIN DESCRIPTION:
RUNNING CREEK 1.0
END DESCRIPTION:
XS GIS Cut Line= 3
      3588520.98     10348766.81      3585170.33      10349218.2
      3580292.07     10352541.66
#Sta/Elev= 30
   483.2   389.5   845.3  386.72   977.8  377.13  1081.8  369.79  1178.3  350.15
  1252.9   359.7  1606.3  306.19  1632.4  297.32  1679.1  304.17  1772.9  299.97
  1926.9  289.56  2450.7  261.14  2868.4  257.57  3055.9   256.9    3287  256.56
  3649.9  256.48  4879.1  257.17  4998.7   254.7  5001.5   254.2  5004.7   254.7
  5046.5   256.8  5832.6  257.51  5995.9  257.61  6294.4  257.16  6471.1  257.48
  6732.9  257.35  8979.5  259.09  9247.1  259.19  9374.3  258.88  9766.9  258.98
#Mann= 20 ,-1 , 0
   483.2     .05       0   977.8     .16       0  1252.9     .12       0
  1772.9     .12       0  1926.9      .1       0  2450.7     .16       0
  2868.4     .12       0  3055.9     .12       0    3287     .07       0
  3649.9     .12       0  4998.7     .07       0  5004.7     .12       0
  5832.6     .07       0  5995.9     .12       0  6294.4     .07       0
  6471.1     .07       0  6732.9     .12       0  8979.5     .07       0
  9247.1      .1       0  9374.3     .12       0
Bank Sta=4879.1,5046.5
XS Rating Curve= 0 ,0
Exp/Cntr=0.3,0.1

Chan Stop Cuts=-1
Use User Specified Reach Order=0
Composite Channel Slope=5