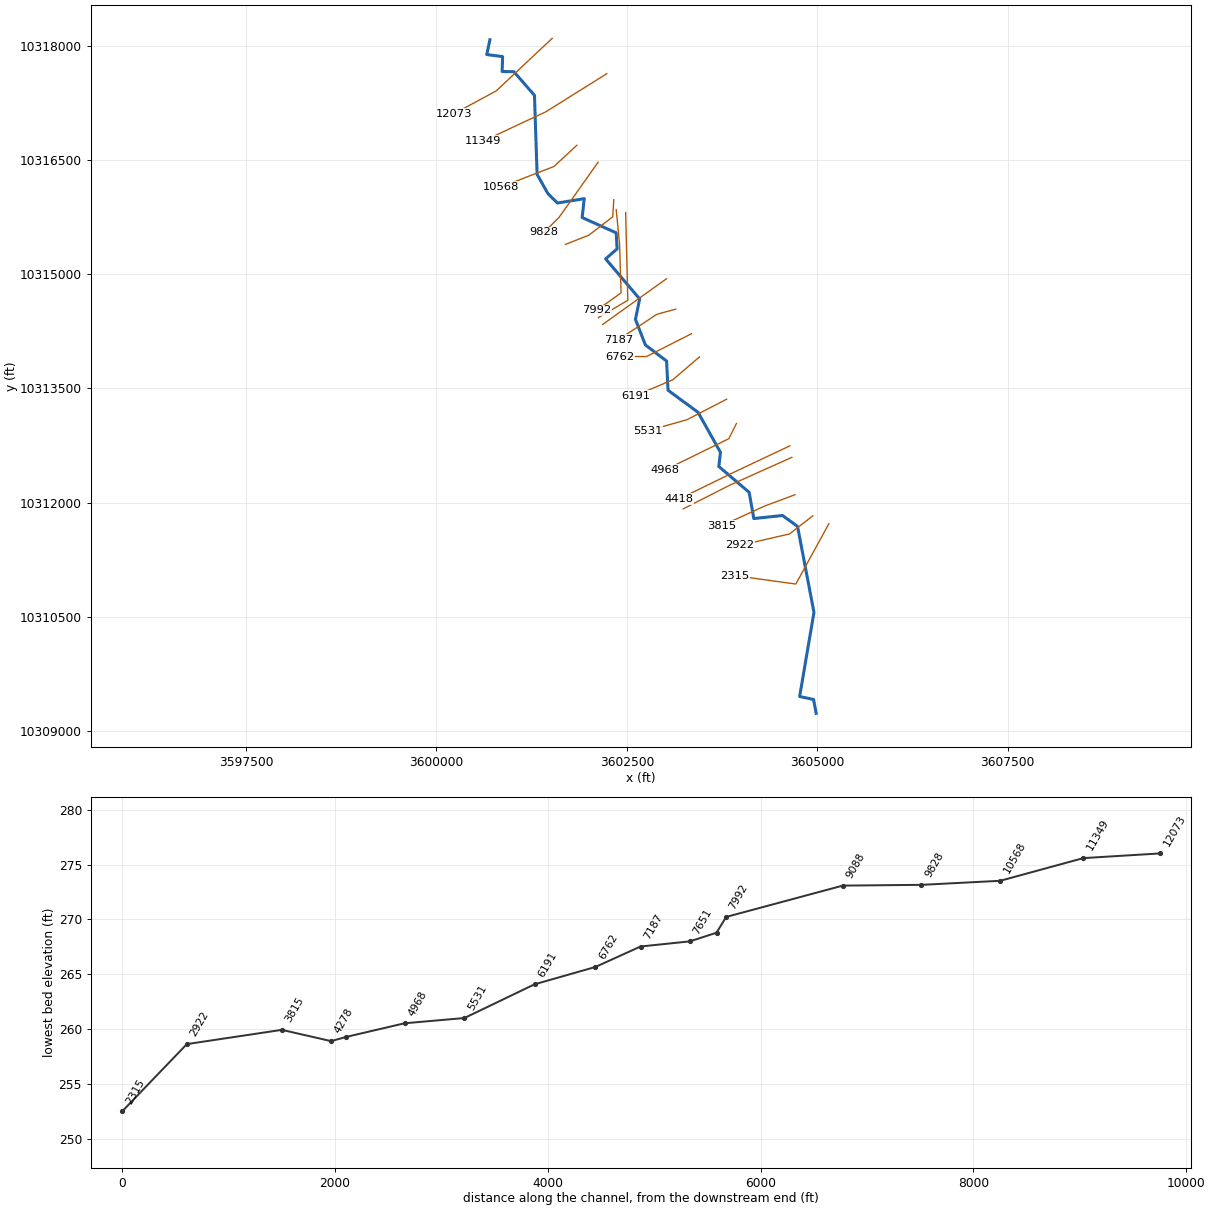
--- SAND BRANCH.prj (project) ---

Proj Title=SAND BRANCH Base Level Engineering
Current Plan=p01
Default Exp/Contr=0.3,0.1
English Units
Geom File=g01
Flow File=f01
Plan File=p01
Y Axis Title=Elevation
X Axis Title(PF)=Main Channel Distance
X Axis Title(XS)=Station
BEGIN DESCRIPTION:
SAND BRANCH
END DESCRIPTION:
DSS Export Rating Curves= 0
DSS Export Rating Curve Sorted= 0
DSS Export Volume Flow Curves= 0
DXF OffsetX= 0
DXF OffsetY= 0
DXF ScaleX= 1
DXF ScaleY= 10

--- SAND BRANCH.p01 (plan) ---

Plan Title=Multiple Run
Short Identifier=Multiple
Geom File=g01
Flow File=f01
Subcritical Flow
K Sum by GR= 0
Std Step Tol= 0.01
Critical Tol= 0.01
Num of Std Step Trials= 20
Max Error Tol= 0.3
Flow Tol Ratio= 0.001
Split Flow NTrial= 30
Split Flow Tol= 0.02
Split Flow Ratio= 0.02
Log Output Level= 0
Friction Slope Method= 1
Unsteady Friction Slope Method= 2
Unsteady Bridges Friction Slope Method= 1
Parabolic Critical Depth
Global Vel Dist=  1 , 1 , 1
Global Log Level= 0
CheckData=True
Encroach Param= -1, 0, 0, 0
BEGIN DESCRIPTION:
Multiple Run
END DESCRIPTION:

--- SAND BRANCH.f01 (steady flow) ---

Flow Title=Multiple
Program Version=4.10
Number of Profiles= 7
Profile Names=10-year,25-year,50-year,1pct_min,100-year,1pct_plu,500-year
River Rch & RM=SAND BRANCH,Reach-1         ,12073
     951    1297    1581    1409    1905    2576    2774
River Rch & RM=SAND BRANCH,Reach-1         ,4278
    1041    1427    1746    1561    2111    2855    3094
Boundary for River Rch & Prof#=SAND BRANCH,Reach-1         , 1
Up Type= 0
Dn Type= 3
Dn Slope=0.00325
Boundary for River Rch & Prof#=SAND BRANCH,Reach-1         , 2
Up Type= 0
Dn Type= 3
Dn Slope=0.00325
Boundary for River Rch & Prof#=SAND BRANCH,Reach-1         , 3
Up Type= 0
Dn Type= 3
Dn Slope=0.00325
Boundary for River Rch & Prof#=SAND BRANCH,Reach-1         , 4
Up Type= 0
Dn Type= 3
Dn Slope=0.00325
Boundary for River Rch & Prof#=SAND BRANCH,Reach-1         , 5
Up Type= 0
Dn Type= 3
Dn Slope=0.00325
Boundary for River Rch & Prof#=SAND BRANCH,Reach-1         , 6
Up Type= 0
Dn Type= 3
Dn Slope=0.00325
Boundary for River Rch & Prof#=SAND BRANCH,Reach-1         , 7
Up Type= 0
Dn Type= 3
Dn Slope=0.00325
DSS Import GetInterval= 0
DSS Import GetPeak= 0
DSS Import FillOption= 0

--- SAND BRANCH.g01 (geometry) ---

Geom Title=Existing Conditions
Program Version=4.10

River Reach=SAND BRANCH     ,Reach-1
Reach XY= 30
      3600702.11     10318081.64      3600660.92     10317887.73
      3600869.26     10317860.38      3600862.75     10317663.77
      3601016.39     10317662.47      3601287.22     10317351.27
      3601321.73     10316311.59      3601463.13     10316061.23
      3601589.25     10315936.22      3601940.64     10315993.86
      3601913.56     10315745.25      3602360.08     10315544.56
       3602372.7      10315333.5      3602221.66     10315202.59
      3602668.67     10314675.67      3602613.11     10314406.92
      3602743.67     10314070.81      3603022.14      10313859.7
      3603041.28     10313475.71      3603435.38     10313185.78
      3603729.65     10312659.74      3603707.95     10312473.97
      3604106.61     10312134.11      3604167.46     10311789.73
      3604544.46     10311829.91      3604741.95      10311686.6
      3604957.48     10310556.48      3604769.24     10309451.18
      3604952.06     10309411.95      3604986.26     10309229.52

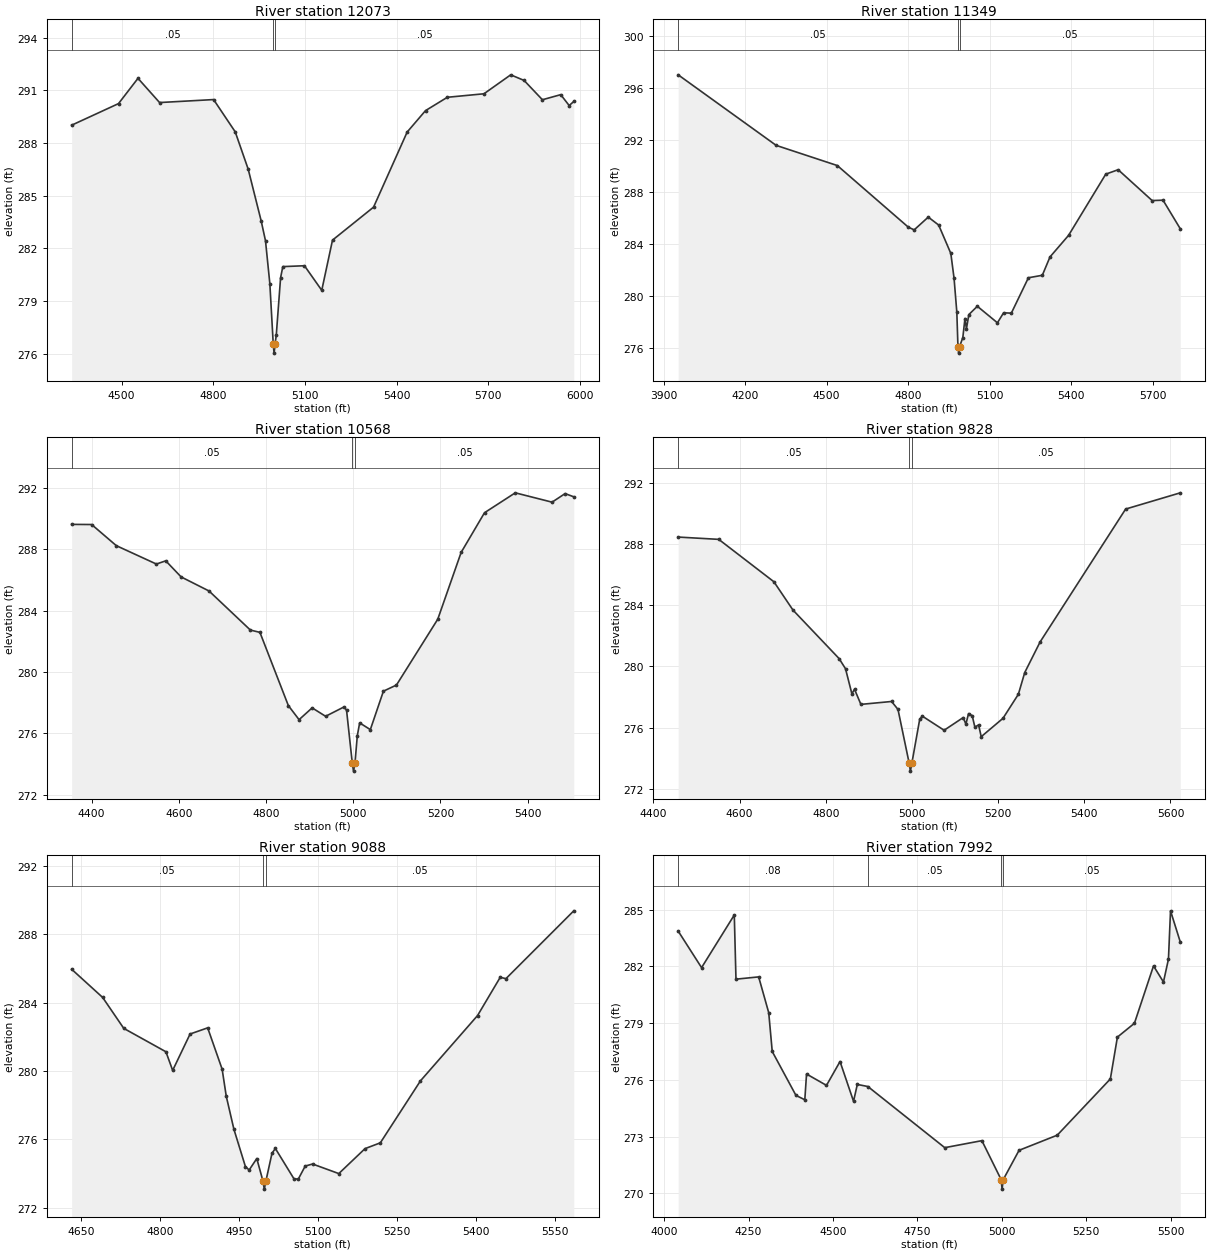
Type RM Length L Ch R = 1 ,12073   ,724,724,724
BEGIN DESCRIPTION:
SAND BRANCH 22.0
END DESCRIPTION:
XS GIS Cut Line= 3
      3601520.33     10318100.38       3600784.2     10317408.86
      3600226.78     10317107.86
#Sta/Elev= 30
  4336.7  289.02  4490.1  290.25  4553.8  291.69  4624.5  290.31  4801.3  290.48
  4872.1  288.64  4914.6  286.51  4957.1  283.56  4971.2  282.43  4985.4  279.99
  4996.6  276.53  4999.3  276.03  5002.6  276.53  5006.6  277.09  5020.6  280.33
  5027.9  280.96  5098.7  281.01  5155.3  279.61  5190.5  282.47  5324.9  284.35
  5434.9  288.63  5494.9  289.85  5566.3  290.61  5686.2  290.81  5773.8  291.89
  5817.6  291.57  5877.5  290.47  5937.5  290.76  5965.1  290.14  5980.2  290.37
#Mann= 3 ,-1 , 0
  4336.7     .05       0  4996.6     .03       0  5002.6     .05       0
Bank Sta=4996.6,5002.6
XS Rating Curve= 0 ,0
Exp/Cntr=0.3,0.1

Type RM Length L Ch R = 1 ,11349   ,781,781,781
BEGIN DESCRIPTION:
SAND BRANCH 21.0
END DESCRIPTION:
XS GIS Cut Line= 3
      3602237.08     10317635.47      3601437.11     10317135.49
      3600616.99     10316750.83
#Sta/Elev= 30
  3953.2  296.98  4314.1  291.56  4539.3  290.01  4801.1  285.27  4822.4  285.07
  4874.2  286.05  4912.5  285.44  4957.3  283.26  4969.2  281.35  4979.4  278.74
  4983.5   276.1  4986.2   275.6  4989.5   276.1  5001.5   276.8  5009.3  278.26
  5014.8  277.47  5023.6  278.56  5054.9   279.2  5128.9  277.93  5151.7   278.7
  5180.1  278.67    5243  281.39  5294.2  281.58  5322.5  282.99    5391  284.65
  5527.9  289.35  5573.5  289.69  5698.7  287.32  5738.8  287.35  5802.4  285.15
#Mann= 3 ,-1 , 0
  3953.2     .05       0  4983.5     .03       0  4989.5     .05       0
Bank Sta=4983.5,4989.5
XS Rating Curve= 0 ,0
Exp/Cntr=0.3,0.1

Type RM Length L Ch R = 1 ,10568   ,740,740,740
BEGIN DESCRIPTION:
SAND BRANCH 19.0
END DESCRIPTION:
XS GIS Cut Line= 3
      3601843.79     10316694.99      3601542.66     10316416.16
      3600851.15     10316148.48
#Sta/Elev= 30
  4354.1  289.64    4400  289.63  4456.6  288.25  4548.5  287.05    4570  287.26
  4605.2  286.21  4669.3  285.29  4764.1  282.74    4786  282.59  4851.2  277.81
  4875.8  276.89  4905.8  277.66  4936.7  277.11  4979.5  277.73  4984.8  277.49
    4998  274.03  5000.7  273.53    5004  274.03  5009.4  275.84  5014.8  276.68
  5039.3  276.24  5069.3  278.75  5099.2  279.15    5194  283.45  5247.6  287.81
  5301.2   290.4  5371.8   291.7  5456.2  291.09  5486.1  291.65    5506  291.44
#Mann= 3 ,-1 , 0
  4354.1     .05       0    4998     .03       0    5004     .05       0
Bank Sta=4998,5004
XS Rating Curve= 0 ,0
Exp/Cntr=0.3,0.1

Type RM Length L Ch R = 1 ,9828    ,740,740,740
BEGIN DESCRIPTION:
SAND BRANCH 18.0
END DESCRIPTION:
XS GIS Cut Line= 3
      3602122.65     10316471.92      3601612.93     10315751.36
      3601412.91     10315551.33
#Sta/Elev= 30
  4457.3  288.45  4551.5   288.3  4679.5  285.53  4723.8  283.68  4830.9  280.51
  4845.7  279.85  4860.5  278.21  4866.6  278.51  4881.4  277.52  4952.7  277.71
  4967.5  277.19  4993.6  273.66  4996.3  273.16  4999.6  273.66    5018  276.56
  5024.1  276.75  5074.6  275.83  5118.9  276.66  5125.1  276.23  5131.3  276.92
  5139.8  276.78    5146  276.03  5154.6  276.18  5160.7  275.41  5211.2  276.61
  5246.9  278.18  5261.7   279.6  5297.4   281.6  5495.9  290.28  5622.8  291.34
#Mann= 3 ,-1 , 0
  4457.3     .05       0  4993.6     .03       0  4999.6     .05       0
Bank Sta=4993.6,4999.6
XS Rating Curve= 0 ,0
Exp/Cntr=0.3,0.1

Type RM Length L Ch R = 1 ,9088    ,1096,1096,1096
BEGIN DESCRIPTION:
SAND BRANCH 16.0
END DESCRIPTION:
XS GIS Cut Line= 4
      3602329.04      10315980.4      3602314.83     10315755.14
      3601999.97      10315512.7      3601692.11     10315391.64
#Sta/Elev= 30
  4632.4  285.96  4691.3  284.31  4731.4   282.5  4811.5  281.13  4824.3  280.04
  4857.4  282.17  4890.8  282.53  4918.3  280.11  4926.1  278.53  4940.6   276.6
  4962.5  274.41  4969.6  274.21  4984.1  274.88  4995.6  273.59  4998.4  273.09
  5001.6  273.59    5013  275.19  5019.4  275.47  5054.8  273.69    5063  273.68
  5076.1  274.44  5090.1  274.56  5139.9     274  5189.7  275.46  5218.8   275.8
  5295.1  279.43  5403.5  283.25  5446.6  285.49  5457.4  285.41  5586.3  289.38
#Mann= 3 ,-1 , 0
  4632.4     .05       0  4995.6     .03       0  5001.6     .05       0
Bank Sta=4995.6,5001.6
XS Rating Curve= 0 ,0
Exp/Cntr=0.3,0.1

Type RM Length L Ch R = 1 ,7992    ,91,91,91
BEGIN DESCRIPTION:
SAND BRANCH 15.0
END DESCRIPTION:
XS GIS Cut Line= 4
      3602360.73     10315848.92        3602405.     10315393.18
      3602424.53     10314755.16      3602106.28     10314527.84
#Sta/Elev= 30
  4041.6  283.86  4110.9  281.93  4207.8  284.71  4212.8  281.32    4280  281.44
  4309.8  279.55  4320.2   277.5  4390.5  275.18  4416.7  274.95  4421.8  276.31
  4480.9  275.71    4521  276.97    4561  274.87  4572.2  275.76  4603.4  275.65
  4831.2  272.42  4941.2  272.79  4998.3  270.73    5001  270.23  5004.3  270.73
  5051.3  272.28  5164.4  273.08  5321.7  276.05  5342.6  278.26    5393  278.99
  5449.5  282.02    5479  281.17  5493.8  282.38  5499.9  284.93  5528.9  283.28
#Mann= 4 ,-1 , 0
  4041.6     .08       0  4603.4     .05       0  4998.3     .04       0
  5004.3     .05       0
Bank Sta=4998.3,5004.3
XS Rating Curve= 0 ,0
Exp/Cntr=0.3,0.1

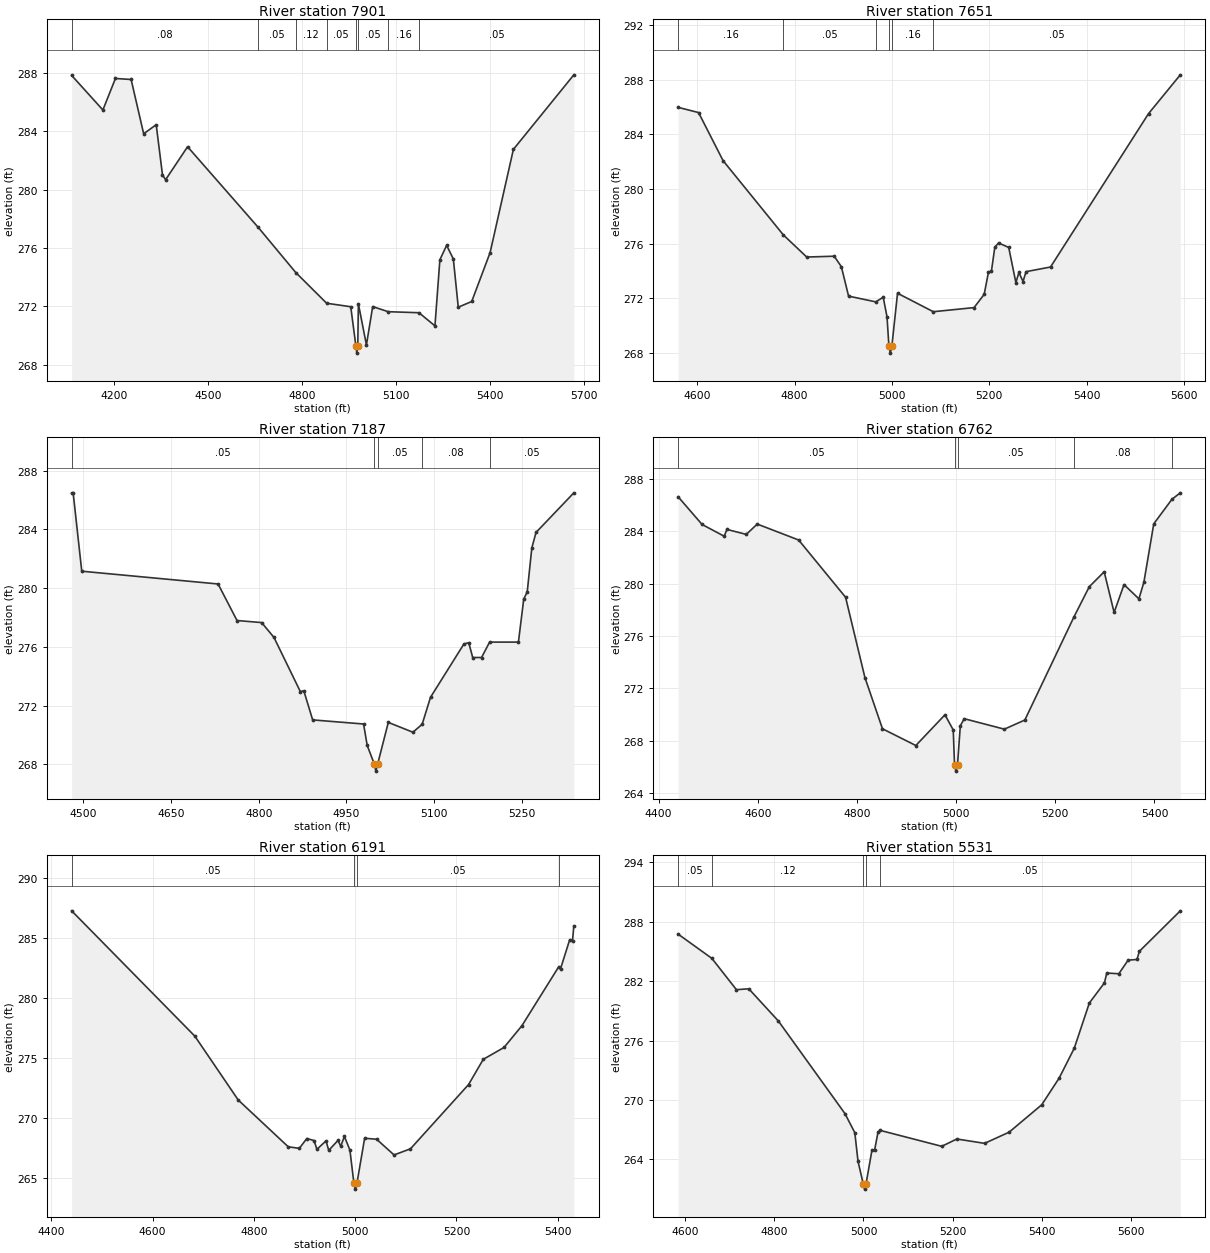
Type RM Length L Ch R = 1 ,7901    ,250,250,250
BEGIN DESCRIPTION:
Mapping XS 7370bd83
END DESCRIPTION:
XS GIS Cut Line= 3
      3602484.42     10315811.16      3602513.07      10314657.5
      3602127.65     10314430.94
#Sta/Elev= 30
  4065.3  287.83  4164.9  285.46  4204.9  287.62  4254.9  287.55  4294.9  283.83
  4334.9  284.45  4354.9  281.01  4364.9  280.68  4434.9  282.94  4659.8  277.42
  4780.1  274.31  4878.3  272.21  4955.1  271.97  4971.5  269.29  4974.3  268.79
  4977.5  269.29  4979.5  272.17  5005.1  269.35  5025.1  271.98  5074.6  271.63
  5172.7  271.56  5223.6  270.66  5239.3  275.19  5260.8  276.18  5282.2  275.25
  5297.9  271.94  5340.8  272.33  5399.4  275.68  5473.7  282.76  5666.4  287.87
#Mann= 8 ,-1 , 0
  4065.3     .08       0  4659.8     .05       0  4780.1     .12       0
  4878.3     .05       0  4971.5     .04       0  4977.5     .05       0
  5074.6     .16       0  5172.7     .05       0
Bank Sta=4971.5,4977.5
XS Rating Curve= 0 ,0
Exp/Cntr=0.3,0.1

Type RM Length L Ch R = 1 ,7651    ,464,464,464
BEGIN DESCRIPTION:
SAND BRANCH 13.0
END DESCRIPTION:
XS GIS Cut Line= 2
      3603020.91     10314941.37      3602182.37     10314339.81
#Sta/Elev= 30
  4560.6  285.98  4602.6   285.6    4653  282.08  4776.8  276.65  4824.9  275.03
  4881.4  275.09  4896.1  274.32  4910.9  272.17  4966.8  271.75  4982.1  272.09
  4989.9  270.65  4993.8   268.5  4996.6     268  4999.8   268.5  5011.5  272.38
    5085  271.03  5168.7  271.33  5189.6   272.3  5198.2   273.9  5204.4  273.99
  5211.4  275.74  5219.1  276.06    5240  275.73  5254.7  273.16  5260.9   273.9
  5269.4  273.24  5275.6  273.96  5325.9   274.3  5527.3  285.52  5592.6  288.36
#Mann= 6 ,-1 , 0
  4560.6     .16       0  4776.8     .05       0  4966.8     .16       0
  4993.8     .07       0  4999.8     .16       0    5085     .05       0
Bank Sta=4993.8,4999.8
XS Rating Curve= 0 ,0
Exp/Cntr=0.3,0.1

Type RM Length L Ch R = 1 ,7187    ,425,425,425
BEGIN DESCRIPTION:
SAND BRANCH 12.0
END DESCRIPTION:
XS GIS Cut Line= 3
      3603142.14     10314541.65      3602894.64     10314474.15
      3602392.12     10314141.65
#Sta/Elev= 30
  4479.9  286.48  4482.5  286.48  4497.2  281.15  4730.4  280.28  4762.8  277.79
  4804.9  277.65    4826  276.64  4871.1  272.95  4877.1     273  4892.2  271.02
  4979.3  270.74  4985.5  269.28  4997.5  268.03  5000.3  267.53  5003.5  268.03
  5021.6  270.85  5063.7  270.18  5079.5  270.72  5093.8  272.56  5150.9  276.19
  5159.2  276.28    5166  275.27  5181.1  275.27  5194.9  276.32  5244.2  276.32
  5253.3  279.25  5259.3  279.75  5267.1  282.73  5274.3  283.79    5339  286.49
#Mann= 5 ,-1 , 0
  4479.9     .05       0  4997.5     .03       0  5003.5     .05       0
  5079.5     .08       0  5194.9     .05       0
Bank Sta=4997.5,5003.5
XS Rating Curve= 0 ,0
Exp/Cntr=0.3,0.1

Type RM Length L Ch R = 1 ,6762    ,571,571,571
BEGIN DESCRIPTION:
SAND BRANCH 11.0
END DESCRIPTION:
XS GIS Cut Line= 3
      3603349.57     10314218.84      3602758.64     10313918.95
      3602408.61     10313918.95
#Sta/Elev= 30
  4439.4  286.65  4487.7  284.53  4532.3  283.63  4537.9  284.15  4576.8  283.77
    4599  284.56  4682.5  283.34  4777.1  278.96  4816.1  272.82  4851.5   268.9
  4918.8  267.62  4977.5  269.97  4994.2  268.81  4996.8  266.16  4999.5  265.66
  5002.8  266.16  5008.5  269.13  5016.4  269.67  5097.3  268.87  5138.6  269.57
  5237.8  277.47  5268.6  279.77  5298.6  280.91  5318.6   277.8  5338.6  279.93
  5368.6  278.84  5378.6   280.1  5398.6  284.58  5435.3  286.46  5452.1  286.95
#Mann= 5 ,-1 , 0
  4439.4     .05       0  4996.8     .03       0  5002.8     .05       0
  5237.8     .08       0  5435.3     .05       0
Bank Sta=4996.8,5002.8
XS Rating Curve= 0 ,0
Exp/Cntr=0.3,0.1

Type RM Length L Ch R = 1 ,6191    ,660,660,660
BEGIN DESCRIPTION:
SAND BRANCH 10.0
END DESCRIPTION:
XS GIS Cut Line= 3
      3603453.64     10313913.56      3603103.64     10313613.57
      3602615.23     10313405.38
#Sta/Elev= 30
    4440  287.28  4683.4  276.83    4769  271.51  4867.8  267.61  4889.7  267.48
  4904.5   268.3  4918.8  268.13  4924.4   267.4  4942.4   268.1  4947.8  267.31
    4966  268.14  4971.5  267.66  4978.7  268.47  4989.6  267.34  4997.5  264.58
  5000.3  264.08  5003.5  264.58  5018.7  268.32  5042.3  268.24  5076.8  266.93
  5109.2  267.44    5224   272.8    5253   274.9    5294  275.89  5329.3   277.7
  5402.1  282.62  5405.7  282.46  5423.8  284.88  5429.3   284.8  5431.9  286.03
#Mann= 4 ,-1 , 0
    4440     .05       0  4997.5     .03       0  5003.5     .05       0
  5402.1     .08       0
Bank Sta=4997.5,5003.5
XS Rating Curve= 0 ,0
Exp/Cntr=0.3,0.1

Type RM Length L Ch R = 1 ,5531    ,563,563,563
BEGIN DESCRIPTION:
SAND BRANCH 9.0
END DESCRIPTION:
XS GIS Cut Line= 3
      3603810.96     10313357.98      3603290.15     10313088.89
      3602769.36     10312941.34
#Sta/Elev= 30
  4583.8  286.74  4659.6  284.29  4714.7  281.13  4742.5  281.22  4808.9  277.97
  4958.3  268.63  4980.5   266.7  4987.7  263.81  4999.6   261.5  5002.4     261
  5005.6   261.5  5019.1  264.96  5024.8   264.9  5032.7  266.77  5037.4  266.93
  5175.7  265.32  5209.6  266.06  5271.9  265.62    5327  266.75  5400.1  269.51
  5439.2   272.2  5473.2  275.22  5507.1  279.79    5541  281.82  5546.2  282.81
  5573.3  282.74  5594.1  284.11  5614.1  284.18  5619.3     285  5711.3  289.09
#Mann= 5 ,-1 , 0
  4583.8     .05       0  4659.6     .12       0  4999.6     .07       0
  5005.6     .12       0  5037.4     .05       0
Bank Sta=4999.6,5005.6
XS Rating Curve= 0 ,0
Exp/Cntr=0.3,0.1

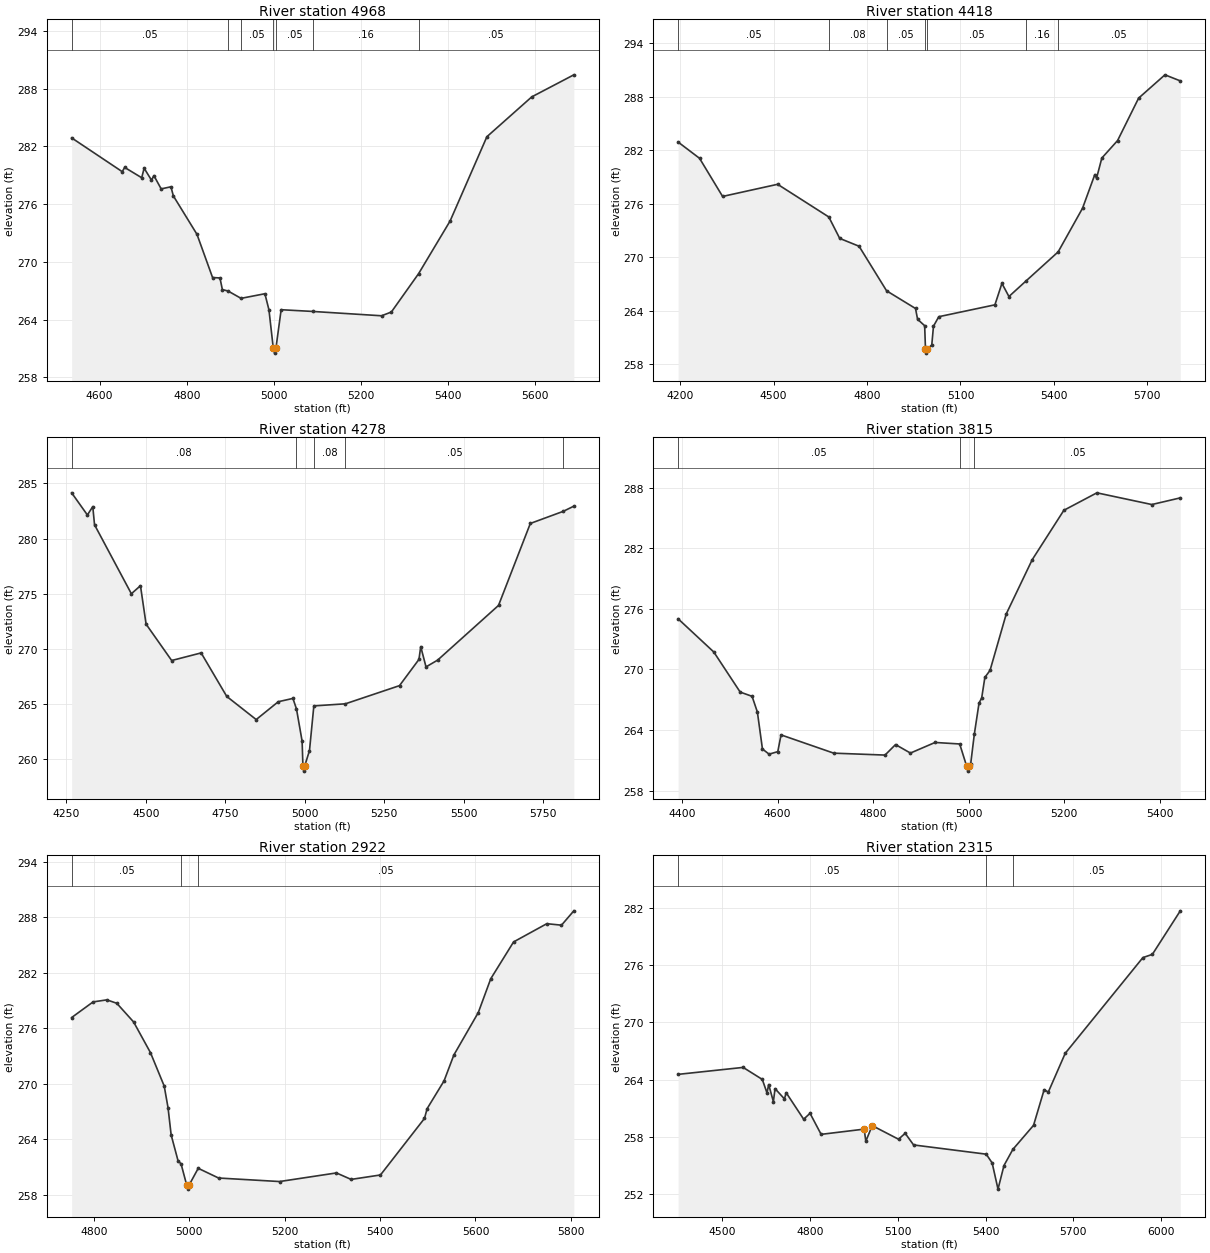
Type RM Length L Ch R = 1 ,4968    ,550,550,550
BEGIN DESCRIPTION:
SAND BRANCH 7.0
END DESCRIPTION:
XS GIS Cut Line= 3
      3603939.66     10313039.19      3603839.67     10312839.21
      3603005.41     10312430.01
#Sta/Elev= 30
  4535.8  282.88  4651.9  279.37  4657.5  279.81  4696.6  278.74  4702.2  279.73
    4719  278.49  4724.6  278.96  4741.3  277.58  4763.7   277.8  4769.3  276.85
  4823.5  272.86  4859.3  268.37  4876.2  268.33  4881.8  267.12  4894.9  266.97
  4924.7  266.21  4979.4  266.69  4988.7  265.02  4998.7  261.02  5001.5  260.52
  5004.7  261.02  5016.7  265.03  5089.3  264.85  5247.2   264.4  5269.7  264.79
  5332.3  268.78  5404.6  274.25    5489     283    5592  287.14  5688.6  289.43
#Mann= 7 ,-1 , 0
  4535.8     .05       0  4894.9     .16       0  4924.7     .05       0
  4998.7     .03       0  5004.7     .05       0  5089.3     .16       0
  5332.3     .05       0
Bank Sta=4998.7,5004.7
XS Rating Curve= 0 ,0
Exp/Cntr=0.3,0.1

Type RM Length L Ch R = 1 ,4418    ,140,140,140
BEGIN DESCRIPTION:
SAND BRANCH 6.0
END DESCRIPTION:
XS GIS Cut Line= 3
      3604641.25     10312745.13      3603892.11     10312391.64
      3603188.19     10312047.24
#Sta/Elev= 30
  4193.6  282.91  4262.4  281.09  4336.4  276.82    4513  278.18  4677.3  274.52
  4712.3  272.12  4774.5  271.24  4862.8  266.25  4955.6  264.27  4962.3  263.06
    4985  262.34  4987.6  259.77  4990.3  259.27  4993.6  259.77  5007.8  260.17
  5013.3  262.29  5030.4  263.35  5210.5  264.68    5233  267.08  5255.5  265.61
  5311.2  267.38  5413.5  270.61  5491.8   275.5  5531.2  279.27  5536.8  278.87
  5553.7  281.12  5604.3  283.08  5671.8  287.83  5756.3  290.44  5805.6  289.76
#Mann= 7 ,-1 , 0
  4193.6     .05       0  4677.3     .08       0  4862.8     .05       0
  4987.6     .04       0  4993.6     .05       0  5311.2     .16       0
  5413.5     .05       0
Bank Sta=4987.6,4993.6
XS Rating Curve= 0 ,0
Exp/Cntr=0.3,0.1

Type RM Length L Ch R = 1 ,4278    ,463,463,463
BEGIN DESCRIPTION:
SAND BRANCH 5.0
END DESCRIPTION:
XS GIS Cut Line= 3
       3604667.3     10312594.09      3603854.82     10312229.52
      3603240.23     10311917.02
#Sta/Elev= 30
  4266.5  284.15    4316  282.14    4333   282.9  4338.5  281.25  4454.4  274.99
    4483  275.72  4500.7  272.23  4581.2  268.93  4673.9  269.62  4754.5  265.67
  4847.1  263.57  4916.6  265.19  4962.7  265.49  4973.9  264.53  4991.6  261.61
  4994.1  259.39  4996.8  258.89  5000.1  259.39  5014.8  260.76  5028.5  264.81
  5127.7     265    5298  266.65  5359.2  269.03  5364.8  270.19  5381.4  268.35
  5418.1  268.97  5609.5  273.93  5709.6  281.37  5813.2  282.47  5846.5  282.94
#Mann= 5 ,-1 , 0
  4266.5     .08       0  4973.9     .05       0  5028.5     .08       0
  5127.7     .05       0  5813.2     .08       0
Bank Sta=4994.1,5000.1
XS Rating Curve= 0 ,0
Exp/Cntr=0.3,0.1

Type RM Length L Ch R = 1 ,3815    ,893,893,893
BEGIN DESCRIPTION:
SAND BRANCH 4.0
END DESCRIPTION:
XS GIS Cut Line= 3
      3604707.41     10312102.76      3604307.38     10311952.75
      3603740.24     10311693.06
#Sta/Elev= 30
    4392  275.01  4466.7  271.72  4521.9  267.75  4546.8  267.33  4557.9  265.77
  4568.5  262.11  4582.4   261.6  4600.6  261.85  4607.4  263.51  4717.7   261.7
    4825  261.51    4847  262.55  4878.2  261.71  4929.8  262.76  4981.3  262.61
  4995.8  260.42  4998.5  259.92  5001.8  260.42  5004.3  260.64    5012  263.61
  5021.8  266.67  5027.3  267.16    5034  269.21  5044.8   269.9  5078.8   275.5
    5133  280.86  5199.3  285.76  5268.4  287.49  5383.4  286.33    5443  286.99
#Mann= 3 ,-1 , 0
    4392     .05       0  4981.3     .03       0    5012     .05       0
Bank Sta=4995.8,5001.8
XS Rating Curve= 0 ,0
Exp/Cntr=0.3,0.1

Type RM Length L Ch R = 1 ,2922    ,607,607,607
BEGIN DESCRIPTION:
SAND BRANCH 3.0
END DESCRIPTION:
XS GIS Cut Line= 3
      3604941.62       10311825.      3604636.55     10311587.48
      3603986.86     10311437.55
#Sta/Elev= 30
    4753  277.16    4798  278.85  4826.9  279.07  4847.7   278.7    4883  276.68
  4918.3  273.37  4947.2  269.75  4955.2  267.41  4961.7  264.48  4976.2  261.68
  4982.5  261.35    4994  259.12  4996.8  258.62    5000  259.12  5018.5  260.87
  5061.2  259.82  5189.1  259.44  5308.4  260.37  5339.2  259.67  5400.8  260.15
  5493.1  266.26  5498.7  267.32  5534.2  270.32  5554.7  273.11    5606   277.7
  5632.1  281.35    5680  285.33  5749.7   287.3  5780.5  287.14  5806.4  288.69
#Mann= 3 ,-1 , 0
    4753     .05       0  4982.5     .03       0  5018.5     .05       0
Bank Sta=4994,5000
XS Rating Curve= 0 ,0
Exp/Cntr=0.3,0.1

Type RM Length L Ch R = 1 ,2315    ,0,0,0
BEGIN DESCRIPTION:
SAND BRANCH 1.0
END DESCRIPTION:
XS GIS Cut Line= 3
      3605153.44     10311721.98       3604719.4     10310929.17
      3603915.46     10311040.06
#Sta/Elev= 30
  4349.8  264.54  4571.9  265.27  4637.3  264.01  4653.4  262.59  4659.1  263.47
  4675.2  261.68  4680.9  263.04  4713.1  261.96  4718.8  262.62  4778.6  259.83
  4800.4  260.45  4838.3  258.24  4985.3  258.79    4991  257.52  5012.8  259.16
  5102.6  257.73  5125.4  258.35  5154.1  257.13  5402.3  256.16  5422.5  255.24
  5442.5  252.49  5462.9  254.97  5493.2  256.66  5563.9  259.19  5600.1  262.93
  5614.3  262.68  5672.1  266.75  5937.4   276.8  5969.8  277.14  6065.2  281.71
#Mann= 3 ,-1 , 0
  4349.8     .05       0  5402.3     .03       0  5493.2     .05       0
Bank Sta=4985.3,5012.8
XS Rating Curve= 0 ,0
Exp/Cntr=0.3,0.1

Chan Stop Cuts=-1
Use User Specified Reach Order=0
Composite Channel Slope=5