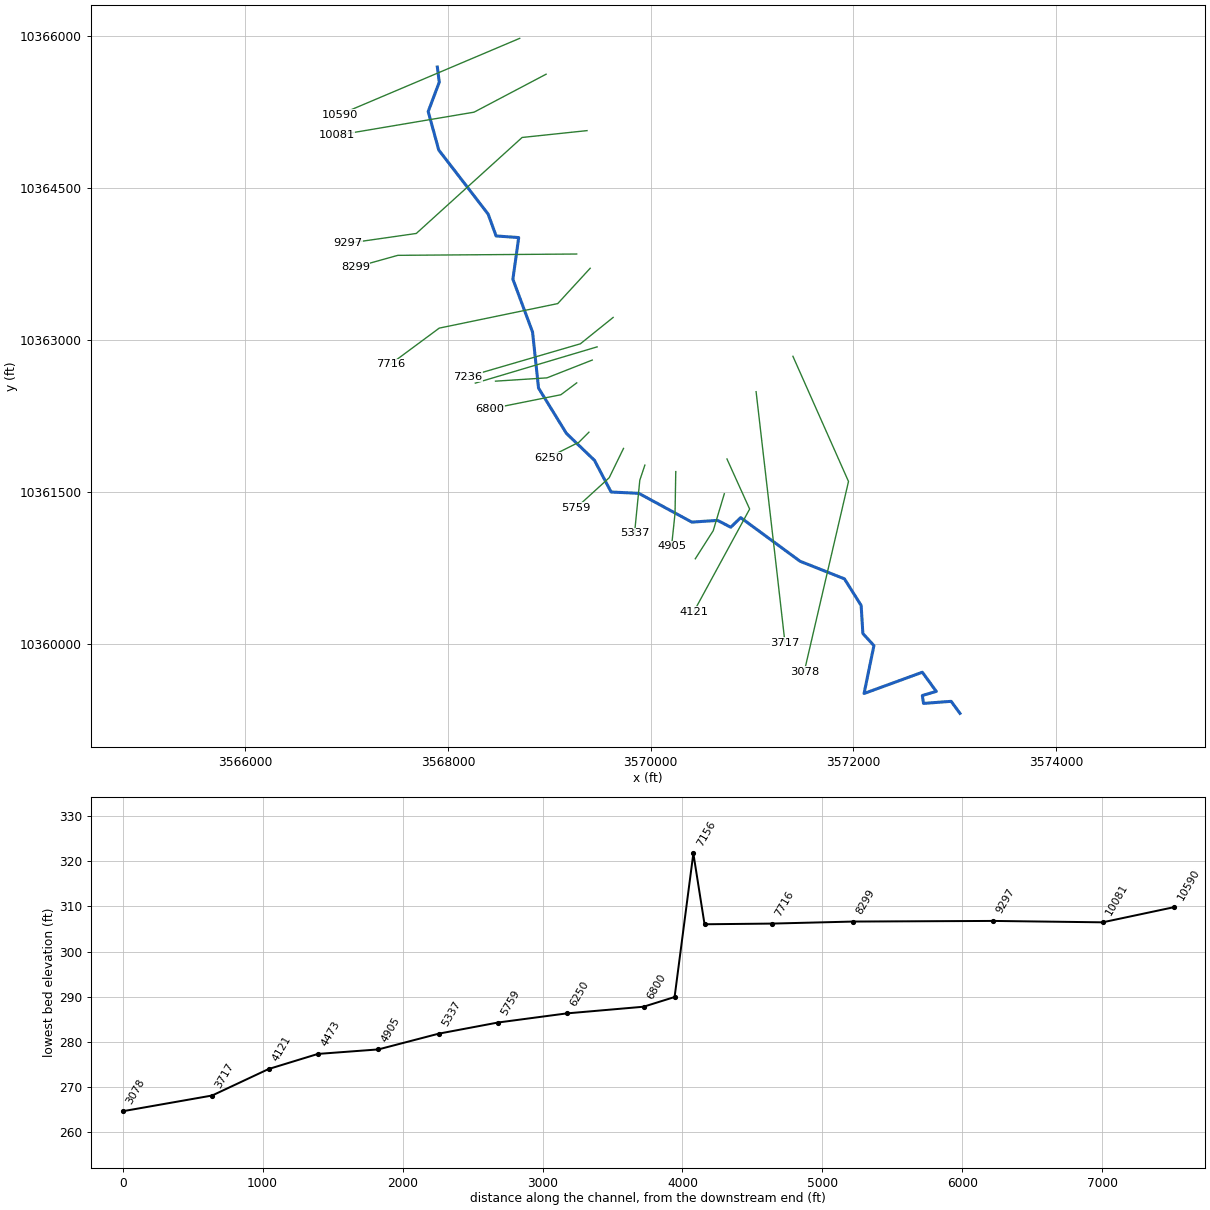
--- SANDYBRANCHSOUTH.prj (project) ---

Proj Title=SANDY BRANCH SOUTH Base Level Engineerin
Current Plan=p01
Default Exp/Contr=0.3,0.1
English Units
Geom File=g01
Flow File=f01
Plan File=p01
Y Axis Title=Elevation
X Axis Title(PF)=Main Channel Distance
X Axis Title(XS)=Station
BEGIN DESCRIPTION:
UNT0375 IN CEDR CR
END DESCRIPTION:
DSS Export Rating Curves= 0
DSS Export Rating Curve Sorted= 0
DSS Export Volume Flow Curves= 0
DXF Filename=UNT0375 IN CEDR CR.
DXF OffsetX= 0
DXF OffsetY= 0
DXF ScaleX= 1
DXF ScaleY= 10

--- SANDYBRANCHSOUTH.p01 (plan) ---

Plan Title=Multiple Run
Short Identifier=Multiple
Geom File=g01
Flow File=f01
Subcritical Flow
K Sum by GR= 0
Std Step Tol= 0.01
Critical Tol= 0.01
Num of Std Step Trials= 20
Max Error Tol= 0.3
Flow Tol Ratio= 0.001
Split Flow NTrial= 30
Split Flow Tol= 0.02
Split Flow Ratio= 0.02
Log Output Level= 0
Friction Slope Method= 1
Unsteady Friction Slope Method= 2
Unsteady Bridges Friction Slope Method= 1
Parabolic Critical Depth
Global Vel Dist=  1 , 1 , 1
Global Log Level= 0
CheckData=True
Encroach Param= -1, 0, 0, 0
BEGIN DESCRIPTION:
Multiple Run
END DESCRIPTION:

--- SANDYBRANCHSOUTH.f01 (steady flow) ---

Flow Title=Multiple
Program Version=4.10
Number of Profiles= 7
Profile Names=10-year,25-year,50-year,1pct_min,100-year,1pct_plu,500-year
River Rch & RM=UNT0375 IN CEDR,Reach-1         ,10590
     872    1185    1439    1275    1724    2332    2469
River Rch & RM=UNT0375 IN CEDR,Reach-1         ,7022
    1524    2146    2671    2422    3275    4429    4914
River Rch & RM=SANDY BRANCH SOU,Reach-1         ,10590
     872    1185    1439    1275    1724    2332    2469
River Rch & RM=SANDY BRANCH SOU,Reach-1         ,7022
    1524    2146    2671    2422    3275    4429    4914
Boundary for River Rch & Prof#=SANDY BRANCH SOU,Reach-1         , 1
Up Type= 0
Dn Type= 3
Dn Slope=0.005
Boundary for River Rch & Prof#=SANDY BRANCH SOU,Reach-1         , 2
Up Type= 0
Dn Type= 3
Dn Slope=0.005
Boundary for River Rch & Prof#=SANDY BRANCH SOU,Reach-1         , 3
Up Type= 0
Dn Type= 3
Dn Slope=0.005
Boundary for River Rch & Prof#=SANDY BRANCH SOU,Reach-1         , 4
Up Type= 0
Dn Type= 3
Dn Slope=0.005
Boundary for River Rch & Prof#=SANDY BRANCH SOU,Reach-1         , 5
Up Type= 0
Dn Type= 3
Dn Slope=0.005
Boundary for River Rch & Prof#=SANDY BRANCH SOU,Reach-1         , 6
Up Type= 0
Dn Type= 3
Dn Slope=0.005
Boundary for River Rch & Prof#=SANDY BRANCH SOU,Reach-1         , 7
Up Type= 0
Dn Type= 3
Dn Slope=0.005
DSS Import GetInterval= 0
DSS Import GetPeak= 0
DSS Import FillOption= 0

--- SANDYBRANCHSOUTH.g01 (geometry) ---

Geom Title=Existing Conditions
Program Version=4.10

River Reach=SANDY BRANCH SOU,Reach-1
Reach XY= 30
      3567896.08     10365698.06      3567915.17     10365548.75
       3567805.8     10365258.82      3567909.96     10364878.61
      3568397.49     10364245.44      3568475.94     10364029.65
      3568699.03     10364013.68      3568641.73     10363602.22
      3568835.75     10363080.72      3568894.77     10362527.34
      3569170.38      10362079.2      3569447.07     10361813.36
      3569610.92     10361500.86      3569884.81      10361487.6
      3570407.87     10361203.48       3570661.8     10361220.53
      3570791.86      10361152.9      3570890.07     10361247.89
      3571476.49     10360816.75      3571913.92     10360643.29
      3572078.87     10360380.46       3572095.9     10360103.22
      3572204.86      10359983.9      3572107.54     10359510.75
      3572682.77     10359720.83      3572820.23     10359531.63
      3572682.56     10359490.95      3572694.43     10359413.06
        3572967.      10359433.5      3573054.18     10359314.55

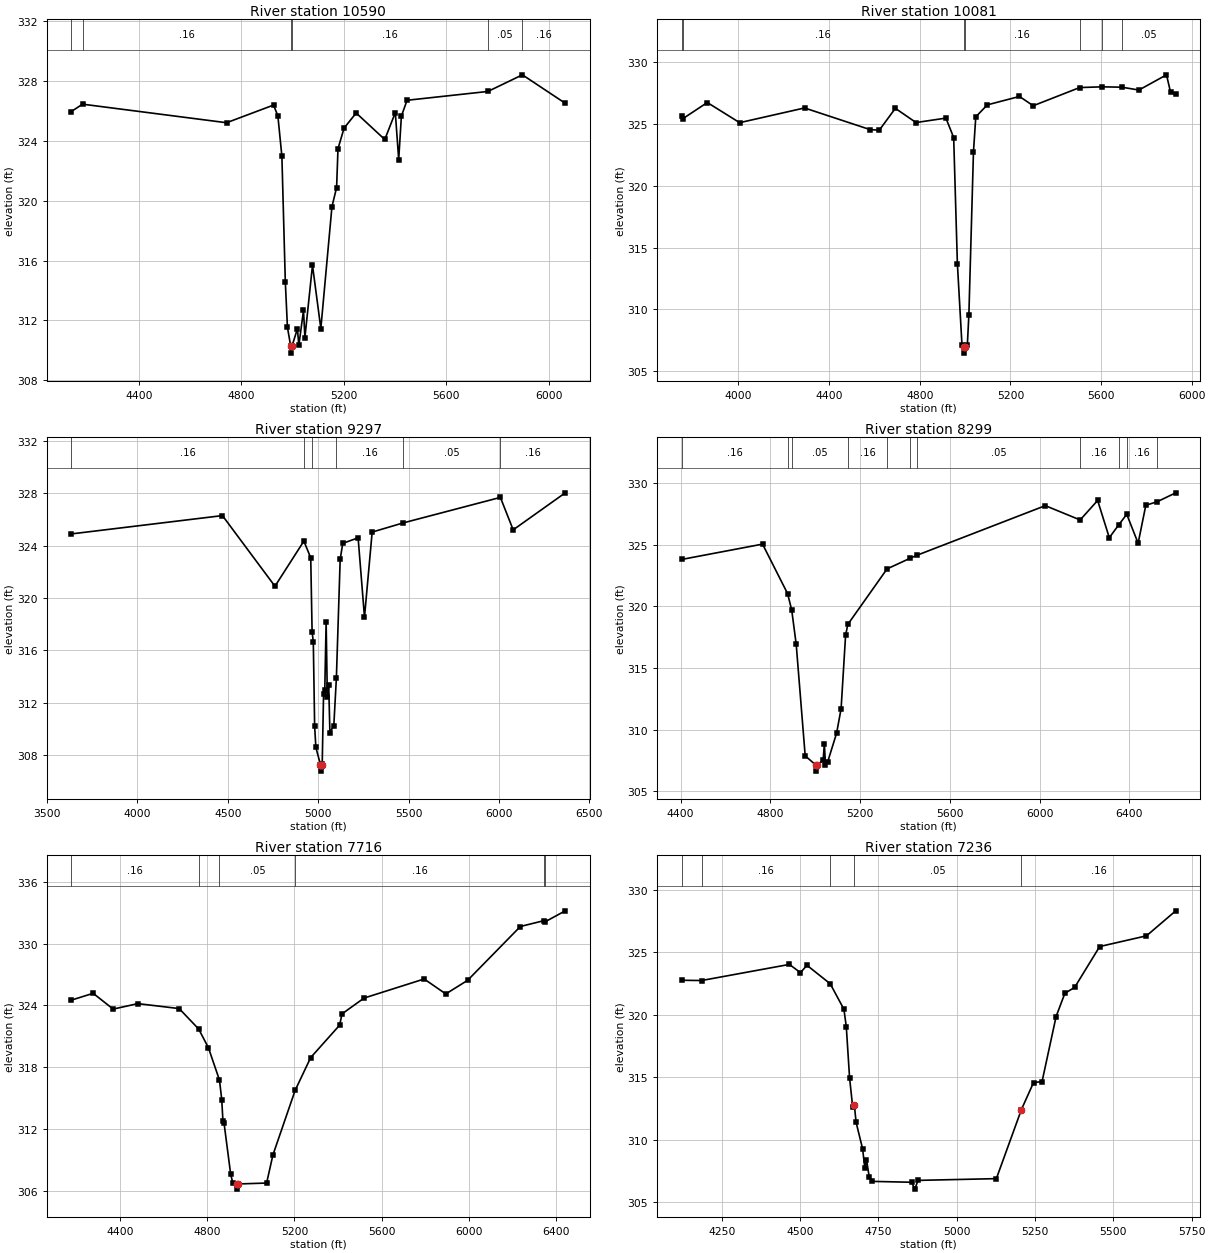
Type RM Length L Ch R = 1 ,10590   ,509,509,509
BEGIN DESCRIPTION:
Mapping XS 6de15b6a
END DESCRIPTION:
XS GIS Cut Line= 2
      3568709.16     10365981.53      3566933.14     10365228.93
#Sta/Elev= 30
  4136.3  325.96    4180  326.45  4742.5  325.21  4925.9  326.39  4942.8  325.67
  4958.5  322.97  4971.9  314.58  4980.2  311.54  4992.6  310.32  4995.3  309.82
  4998.6  310.32  5019.2  311.45  5024.7  310.34  5042.9  312.67  5048.4  310.86
    5078  315.69  5110.6  311.46    5154   319.6  5172.2  320.88  5177.6  323.47
  5201.3  324.85  5248.6  325.86  5360.4  324.09  5401.5  325.89  5414.7  322.75
  5425.2  325.65  5447.3  326.71  5763.1   327.3  5897.9  328.41  6065.2  326.51
#Mann= 6 ,-1 , 0
  4136.3     .05       0    4180     .16       0  4992.6     .07       0
  4998.6     .16       0  5763.1     .05       0  5897.9     .16       0
Bank Sta=4992.6,4998.6
XS Rating Curve= 0 ,0
Exp/Cntr=0.3,0.1

Type RM Length L Ch R = 1 ,10081   ,784,784,784
BEGIN DESCRIPTION:
Mapping XS 85bd55bd
END DESCRIPTION:
XS GIS Cut Line= 3
      3568969.63     10365627.39      3568258.66     10365252.37
      3566901.89      10365023.2
#Sta/Elev= 30
    3750  325.69  3753.3  325.42  3862.3  326.74  4005.2  325.11  4291.5   326.3
  4580.7  324.55  4621.3   324.5  4692.3  326.27  4783.6  325.12  4915.4  325.48
  4949.7  323.91  4966.1  313.69  4986.4  307.12  4993.6  306.97  4996.3  306.47
  4999.6  306.97  5010.1  307.15  5016.8  309.58  5037.1  322.77  5047.3  325.58
    5098  326.55    5240  327.23  5300.8  326.48  5505.7  327.95  5605.2  328.01
  5691.7  327.98  5767.3  327.75    5889  328.98  5906.7  327.59  5929.8  327.44
#Mann= 7 ,-1 , 0
    3750     .05       0  3753.3     .16       0  4993.6     .07       0
  4999.6     .16       0  5505.7     .05       0  5605.2     .16       0
  5691.7     .05       0
Bank Sta=4993.6,4999.6
XS Rating Curve= 0 ,0
Exp/Cntr=0.3,0.1

Type RM Length L Ch R = 1 ,9297    ,998,998,998
BEGIN DESCRIPTION:
Mapping XS 8f973b0a
END DESCRIPTION:
XS GIS Cut Line= 4
      3569373.29     10365070.08      3568732.62     10365002.37
      3567688.35     10364054.45      3567016.79     10363958.14
#Sta/Elev= 30
  3634.4  324.91  4470.4  326.31    4761  320.91    4921  324.36    4959  323.08
  4966.5  317.44  4973.2  316.66  4980.6  310.22  4987.4  308.59  5012.8  307.28
  5015.5  306.78  5018.8  307.28  5022.5  307.33    5030  312.68  5036.7  312.96
  5044.2  318.21  5050.9  312.42  5058.4  313.39  5065.1  309.72  5086.7  310.26
  5100.9   313.9  5121.9  322.96  5136.1  324.19  5221.2  324.61  5256.4  318.55
  5298.9  325.05  5467.7  325.74  6008.4   327.7  6079.2  325.22  6367.4  328.05
#Mann= 6 ,-1 , 0
  3634.4     .16       0    4921     .07       0  4966.5     .05       0
  5100.9     .16       0  5467.7     .05       0  6008.4     .16       0
Bank Sta=5012.8,5018.8
XS Rating Curve= 0 ,0
Exp/Cntr=0.3,0.1

Type RM Length L Ch R = 1 ,8299    ,583,583,583
BEGIN DESCRIPTION:
Mapping XS e08e983f
END DESCRIPTION:
XS GIS Cut Line= 3
      3569271.66     10363851.33      3567506.06     10363838.31
      3567086.97     10363721.17
#Sta/Elev= 30
  4405.6  323.81  4765.2  325.05  4876.7  321.04  4895.2   319.7  4915.2  316.92
  4955.2  307.88  5002.2  307.14  5004.9  306.64  5008.2  307.14  5035.2  307.52
  5040.6  308.87  5045.6  307.16  5055.2  307.38  5095.2  309.72  5115.2   311.7
  5135.2  317.65  5145.2  318.54    5320  323.04  5421.1  323.89  5452.3  324.14
  6025.2  328.17  6180.3  327.01  6258.4  328.59  6310.3  325.57  6351.4  326.59
  6388.1  327.47  6438.8  325.12    6473   328.2    6524  328.49  6606.4  329.21
#Mann= 11 ,-1 , 0
  4405.6     .16       0  4876.7     .07       0  4895.2     .05       0
  5145.2     .16       0    5320     .05       0  5421.1     .16       0
  5452.3     .05       0  6180.3     .16       0  6351.4     .05       0
  6388.1     .16       0    6524     .05       0
Bank Sta=5002.2,5008.2
XS Rating Curve= 0 ,0
Exp/Cntr=0.3,0.1

Type RM Length L Ch R = 1 ,7716    ,480,480,480
BEGIN DESCRIPTION:
Mapping XS 62621b92
END DESCRIPTION:
XS GIS Cut Line= 4
      3569404.49      10363710.7      3569084.18     10363361.75
      3567914.91     10363119.56       3567433.1     10362762.76
#Sta/Elev= 30
  4175.9  324.52    4276  325.18  4367.9  323.65  4481.3  324.18  4670.9   323.7
  4760.2  321.72  4804.9  319.91  4855.9  316.76  4866.2  314.88  4871.6  312.84
  4876.7  312.61    4907  307.68  4916.7   306.8  4934.6  306.69  4937.4  306.19
  4940.6  306.69  5072.3  306.78    5101  309.49  5203.2  315.77  5274.6  318.95
  5407.4  322.09  5418.5  323.19  5519.7  324.72  5795.5  326.57  5894.8  325.12
    5995  326.44  6237.1  331.66  6347.7  332.24  6349.3   332.1  6443.2  333.18
#Mann= 6 ,-1 , 0
  4175.9     .16       0  4760.2     .07       0  4855.9     .05       0
  5203.2     .16       0  6347.7     .05       0  6349.3     .16       0
Bank Sta=4934.6,4940.6
XS Rating Curve= 0 ,0
Exp/Cntr=0.3,0.1

Type RM Length L Ch R = 1 ,7236    ,80,80,80
BEGIN DESCRIPTION:
Mapping XS 0f891cdd
END DESCRIPTION:
XS GIS Cut Line= 3
      3569631.03       10363225.      3569307.71     10362964.61
      3568192.27     10362639.09
#Sta/Elev= 30
  4122.4  322.76  4185.2  322.74  4465.9  324.03  4501.1  323.37  4521.9  323.96
  4596.2  322.48  4639.9  320.44  4647.5  319.05    4658  314.94  4668.1  312.58
  4673.3  312.74  4678.8  311.39  4699.6  309.26  4706.8  307.71    4712   308.4
  4720.5  307.05  4730.9  306.66  4856.3  306.59  4866.1  306.04  4876.7  306.74
  5126.7  306.88  5206.7  312.41  5245.4  314.57  5272.6  314.65  5317.5  319.86
  5345.5  321.72  5376.7  322.19  5456.6  325.46  5606.1  326.32  5699.5  328.32
#Mann= 5 ,-1 , 0
  4122.4     .05       0  4185.2     .16       0  4596.2     .07       0
  4673.3     .05       0  5206.7     .16       0
Bank Sta=4673.3,5206.7
XS Rating Curve= 0 ,0
Exp/Cntr=0.3,0.1

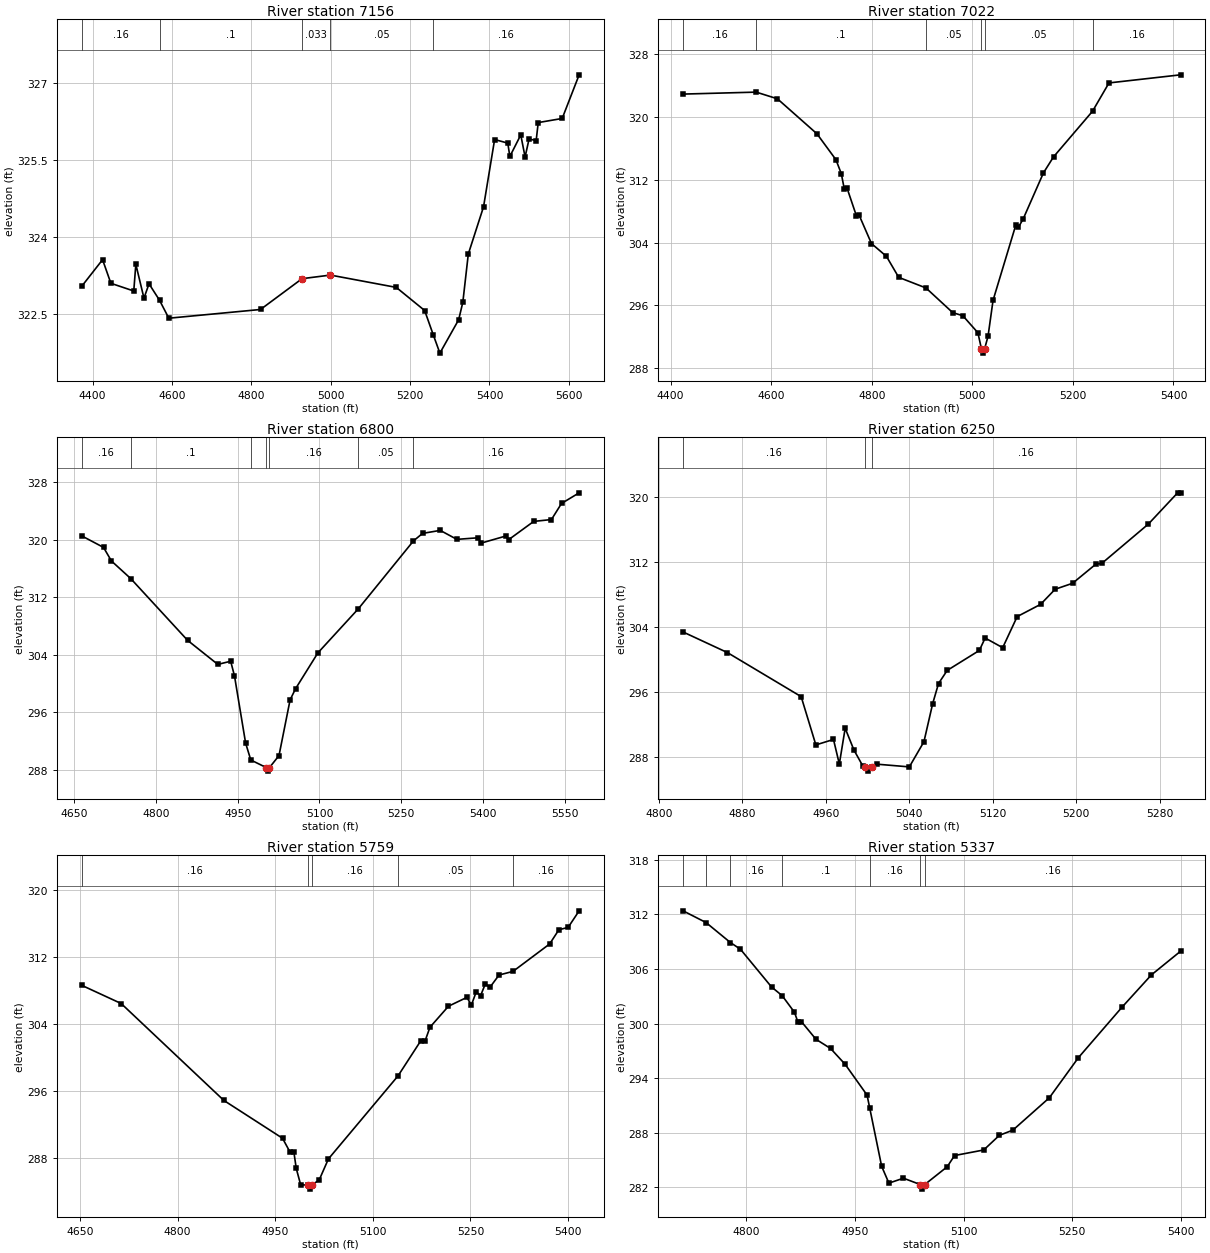
Type RM Length L Ch R = 1 ,7156    ,134,134,134
BEGIN DESCRIPTION:
Mapping XS 8eb2be72
END DESCRIPTION:
XS GIS Cut Line= 2
       3569472.6     10362934.22      3568271.16     10362576.39
#Sta/Elev= 30
  4372.4  323.03  4425.1  323.55    4446  323.09  4503.7  322.94  4508.9  323.46
  4529.4   322.8  4542.1  323.08  4568.6  322.76    4592  322.41  4823.1  322.58
  4927.8  323.18  4999.3  323.25  5165.2  323.01  5236.7  322.56  5258.7  322.08
  5275.1  321.73  5322.4  322.38  5332.9  322.72  5346.7  323.66  5385.1  324.58
    5413  325.89  5446.2  325.82  5451.4  325.56  5478.9  325.98  5489.8  325.55
  5499.8   325.9  5517.7  325.87  5522.9  326.22  5583.3   326.3    5626  327.15
#Mann= 5 ,-1 , 0
  4372.4     .16       0  4568.6      .1       0  4927.8    .033       0
  4999.3     .05       0  5258.7     .16       0
Bank Sta=4927.8,4999.3
XS Rating Curve= 0 ,0
Exp/Cntr=0.3,0.1

Type RM Length L Ch R = 1 ,7022    ,222,222,222
BEGIN DESCRIPTION:
Mapping XS 622e90ef
END DESCRIPTION:
XS GIS Cut Line= 3
      3569424.91     10362804.03      3568977.85     10362628.24
      3568470.07     10362595.69
#Sta/Elev= 30
  4424.9  322.88  4570.3  323.13  4612.5  322.28  4691.1  317.83  4728.8  314.54
  4739.5  312.77  4745.3  310.87  4750.7  310.97  4769.7  307.37  4775.1  307.46
  4799.5  303.87  4829.3  302.24  4853.7  299.57  4907.9  298.22  4961.1  295.08
  4981.2  294.69  5011.2  292.52  5018.3  290.43    5021  289.93  5024.3  290.43
  5031.3  292.07  5041.3  296.65  5086.5  306.22  5091.5  305.91  5101.4  307.03
  5141.5  312.86  5161.5  314.89  5239.1   320.7  5271.8   324.3  5414.1  325.33
#Mann= 6 ,-1 , 0
  4424.9     .16       0  4570.3      .1       0  4907.9     .05       0
  5018.3    .033       0  5024.3     .05       0  5239.1     .16       0
Bank Sta=5018.3,5024.3
XS Rating Curve= 0 ,0
Exp/Cntr=0.3,0.1

Type RM Length L Ch R = 1 ,6800    ,550,550,550
BEGIN DESCRIPTION:
Mapping XS 3e3910b0
END DESCRIPTION:
XS GIS Cut Line= 3
       3569271.7     10362578.77      3569115.43     10362461.57
      3568412.29     10362320.94
#Sta/Elev= 30
  4663.9  320.54    4704  318.93  4718.5  317.04  4753.9  314.59  4858.2  305.99
  4913.6  302.64  4937.2  303.08  4944.2  301.03  4964.6  291.68  4974.1  289.33
  5002.4  288.28  5005.1  287.78  5008.4  288.28  5025.8  289.94  5046.2  297.71
  5056.4  299.28  5097.2  304.25  5171.3  310.38  5272.5  319.84  5289.1  320.88
  5321.5   321.3  5352.1  320.05    5391  320.27  5396.1  319.52    5442  320.52
  5447.1  320.01    5493  322.55  5525.5  322.81    5544  325.05  5576.3  326.53
#Mann= 7 ,-1 , 0
  4663.9     .16       0  4753.9      .1       0  4974.1     .16       0
  5002.4     .07       0  5008.4     .16       0  5171.3     .05       0
  5272.5     .16       0
Bank Sta=5002.4,5008.4
XS Rating Curve= 0 ,0
Exp/Cntr=0.3,0.1

Type RM Length L Ch R = 1 ,6250    ,491,491,491
BEGIN DESCRIPTION:
UNT0375 IN CEDR CR 12.0
END DESCRIPTION:
XS GIS Cut Line= 3
      3569392.12     10362091.66      3569292.11     10361991.64
      3568992.07     10361841.62
#Sta/Elev= 30
  4823.1  303.39  4865.6  300.86  4936.3  295.45  4950.4  289.52  4967.3  290.19
  4972.9  287.17  4978.5  291.57  4986.9  288.89  4995.3  286.96  4997.9   286.8
  5000.6   286.3  5003.9   286.8  5009.3  287.15    5040  286.82    5054  289.91
  5062.4   294.6    5068  297.06  5076.3  298.67  5107.1  301.12  5112.7  302.65
  5129.5  301.46  5143.4  305.28  5165.8  306.78  5179.8  308.64  5196.5  309.37
  5218.9  311.73  5224.5  311.81  5269.2  316.65  5297.2  320.48    5300  320.48
#Mann= 3 ,-1 , 0
  4823.1     .16       0  4997.9     .07       0  5003.9     .16       0
Bank Sta=4997.9,5003.9
XS Rating Curve= 0 ,0
Exp/Cntr=0.3,0.1

Type RM Length L Ch R = 1 ,5759    ,422,422,422
BEGIN DESCRIPTION:
UNT0375 IN CEDR CR 11.0
END DESCRIPTION:
XS GIS Cut Line= 3
      3569733.56     10361931.52      3569592.11     10361641.64
      3569265.94     10361344.02
#Sta/Elev= 30
  4652.8  308.64  4713.5  306.46  4871.2  294.88  4961.3  290.36  4972.6  288.74
  4978.7  288.74  4982.4  286.75  4989.2  284.79  5000.4  284.78  5003.1  284.28
  5006.4  284.78  5017.6  285.37  5031.8  287.89  5138.7  297.81  5173.6     302
  5180.4  302.02  5187.8  303.63  5216.2  306.14  5244.6   307.2  5251.3  306.26
  5258.8  307.85  5265.5  307.39  5272.9  308.83  5279.7  308.38  5293.9  309.87
  5315.3   310.3  5371.6  313.58  5385.8  315.28    5400  315.56  5416.9  317.54
#Mann= 5 ,-1 , 0
  4652.8     .16       0  5000.4     .07       0  5006.4     .16       0
  5138.7     .05       0  5315.3     .16       0
Bank Sta=5000.4,5006.4
XS Rating Curve= 0 ,0
Exp/Cntr=0.3,0.1

Type RM Length L Ch R = 1 ,5337    ,432,432,432
BEGIN DESCRIPTION:
UNT0375 IN CEDR CR 10.0
END DESCRIPTION:
XS GIS Cut Line= 3
      3569944.19     10361766.65      3569894.19     10361616.64
      3569842.11     10361091.64
#Sta/Elev= 30
  4713.4  312.39  4745.1   311.1  4778.6  308.91  4792.5  308.17  4835.3  304.03
    4850  303.07  4866.9  301.25  4871.5  300.22  4876.5  300.22  4896.6  298.28
  4916.7  297.27  4936.8  295.53    4967  292.15  4970.7  290.72  4987.1  284.33
  4997.1  282.48  5017.2  283.02  5040.5  282.32  5043.2  281.82  5046.5  282.32
  5077.5  284.28  5087.6  285.51  5127.8  286.12  5149.4  287.73    5168   288.3
  5218.2  291.85  5258.4  296.27  5318.7  301.83  5358.9  305.35  5399.1  307.95
#Mann= 7 ,-1 , 0
  4713.4     .16       0  4745.1      .1       0  4778.6     .16       0
    4850      .1       0  4970.7     .16       0  5040.5     .07       0
  5046.5     .16       0
Bank Sta=5040.5,5046.5
XS Rating Curve= 0 ,0
Exp/Cntr=0.3,0.1

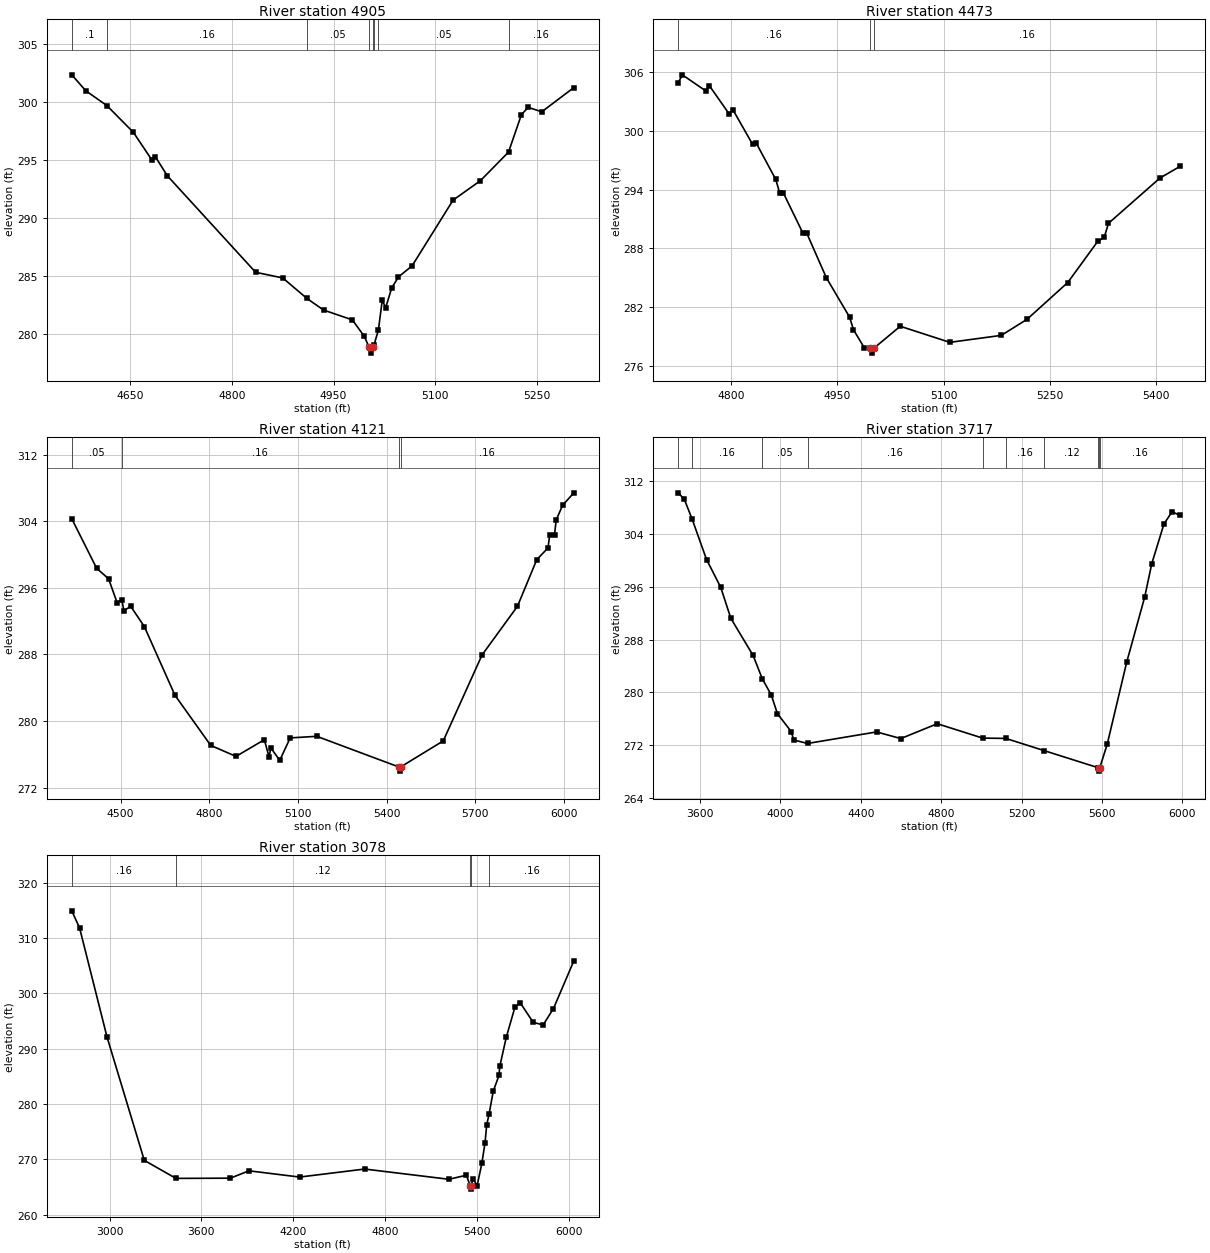
Type RM Length L Ch R = 1 ,4905    ,432,432,432
BEGIN DESCRIPTION:
UNT0375 IN CEDR CR 9.0
END DESCRIPTION:
XS GIS Cut Line= 3
      3570249.19     10361702.38      3570242.11     10361291.64
      3570207.73     10360964.75
#Sta/Elev= 30
  4564.4  302.36  4585.1  300.98    4616  299.71  4655.2  297.39  4682.7  294.98
  4687.7  295.27  4705.2  293.64  4835.2  285.31  4875.2  284.82  4910.8  283.05
  4935.2  282.05  4977.7   281.2  4995.3  279.77  5002.4  278.83  5005.1  278.33
  5008.4  278.83  5009.4     279    5016  280.32  5021.7  282.89  5026.8  282.26
  5035.5  283.94  5045.6  284.91  5065.7  285.87    5126  291.54  5166.3  293.22
  5207.7  295.69  5226.6  298.91  5236.6  299.55  5256.7  299.17  5303.9  301.26
#Mann= 8 ,-1 , 0
  4564.4      .1       0    4616     .16       0  4910.8     .05       0
  5002.4     .03       0  5008.4     .05       0  5009.4     .16       0
    5016     .05       0  5207.7     .16       0
Bank Sta=5002.4,5008.4
XS Rating Curve= 0 ,0
Exp/Cntr=0.3,0.1

Type RM Length L Ch R = 1 ,4473    ,352,352,352
BEGIN DESCRIPTION:
UNT0375 IN CEDR CR 8.0
END DESCRIPTION:
XS GIS Cut Line= 3
      3570728.36     10361483.62      3570618.98     10361119.03
      3570442.12     10360841.66
#Sta/Elev= 30
    4725   304.9  4730.8  305.71  4763.9  304.07  4769.1  304.59  4796.9  301.73
  4802.2  302.16    4830  298.63  4835.2  298.75  4862.8  295.05  4868.3  293.69
  4873.5  293.68  4901.3  289.55  4906.6  289.57  4934.4  285.01  4967.2     281
  4972.7  279.71  4988.1  277.86  4995.5  277.83  4998.3  277.33  5001.5  277.83
  5038.8  280.07  5108.8  278.43  5181.6  279.14    5218  280.78  5275.5  284.53
  5317.8  288.72  5327.1  289.14  5333.1  290.57  5405.9  295.19  5434.6  296.39
#Mann= 3 ,-1 , 0
    4725     .16       0  4995.5     .07       0  5001.5     .16       0
Bank Sta=4995.5,5001.5
XS Rating Curve= 0 ,0
Exp/Cntr=0.3,0.1

Type RM Length L Ch R = 1 ,4121    ,404,404,404
BEGIN DESCRIPTION:
UNT0375 IN CEDR CR 7.0
END DESCRIPTION:
XS GIS Cut Line= 3
      3570754.42     10361827.32      3570978.35     10361332.57
      3570426.68      10360317.7
#Sta/Elev= 30
  4334.7   304.3  4418.6  298.36  4459.3  297.08  4487.9  294.23  4503.6   294.6
    4511  293.26  4534.1  293.78  4580.3  291.34  4683.7   283.1  4804.7  277.08
  4890.2  275.76    4986  277.76  5002.2  275.67  5007.9  276.79  5038.2  275.28
  5073.4  277.98  5163.4  278.17    5441  274.49  5443.7  273.99    5447  274.49
  5591.2  277.62  5722.4  287.94  5842.1  293.78  5907.6  299.39  5945.6   300.8
  5951.3   302.4  5967.5  302.36  5973.2  304.16    5995  305.92  6032.9  307.41
#Mann= 4 ,-1 , 0
  4334.7     .05       0  4503.6     .16       0    5441     .07       0
    5447     .16       0
Bank Sta=5441,5447
XS Rating Curve= 0 ,0
Exp/Cntr=0.3,0.1

Type RM Length L Ch R = 1 ,3717    ,639,639,639
BEGIN DESCRIPTION:
UNT0375 IN CEDR CR 6.0
END DESCRIPTION:
XS GIS Cut Line= 3
      3571042.11     10362491.64      3571233.56     10360832.57
      3571327.21     10360010.57
#Sta/Elev= 30
  3491.9  310.16  3522.1  309.18  3560.5  306.23  3632.8  300.08  3703.3  295.88
  3753.6   291.2  3864.4  285.59  3909.7  282.09    3955   279.6  3985.2   276.8
  4054.7  274.06  4065.7  272.83  4135.4   272.3  4478.4  274.04  4599.2  273.04
  4780.4  275.28    5006  273.11  5121.5  273.06  5313.7   271.2  5582.3  268.62
  5582.6  268.62  5585.4  268.12  5588.6  268.62  5625.9  272.21  5722.4  284.55
  5811.9  294.39  5847.3  299.45  5907.7  305.44    5948   307.3  5989.3  306.74
#Mann= 10 ,-1 , 0
  3491.9      .1       0  3560.5     .16       0  3909.7     .05       0
  4135.4     .16       0    5006     .12       0  5121.5     .16       0
  5313.7     .12       0  5582.3     .16       0  5582.6     .07       0
  5588.6     .16       0
Bank Sta=5582.6,5588.6
XS Rating Curve= 0 ,0
Exp/Cntr=0.3,0.1

Type RM Length L Ch R = 1 ,3078    ,0,0,0
BEGIN DESCRIPTION:
UNT0375 IN CEDR CR 1.0
END DESCRIPTION:
XS GIS Cut Line= 3
      3571405.45     10362841.22      3571954.05     10361605.14
      3571517.22      10359726.1
#Sta/Elev= 30
  2753.4  314.93  2804.5  311.84  2983.7  292.14  3227.4  269.84  3434.3  266.58
  3789.8  266.62  3911.6  267.95  4242.8  266.82  4667.6  268.27  5218.1  266.42
  5332.5  267.15  5358.9  265.14  5361.6  264.64  5364.9  265.14  5375.1  266.56
  5402.9  265.28  5433.7  269.31  5454.3     273  5465.5  276.29  5480.4  278.14
  5508.1  282.33  5545.6  285.19  5550.7   286.8  5593.3  292.08  5649.3  297.47
  5683.7  298.35  5768.9  294.78  5834.1  294.31  5901.9  297.28  6034.9  305.89
#Mann= 5 ,-1 , 0
  2753.4     .16       0  3434.3     .12       0  5358.9     .07       0
  5364.9     .12       0  5480.4     .16       0
Bank Sta=5358.9,5364.9
XS Rating Curve= 0 ,0
Exp/Cntr=0.3,0.1

Chan Stop Cuts=-1
Use User Specified Reach Order=0
Composite Channel Slope=5