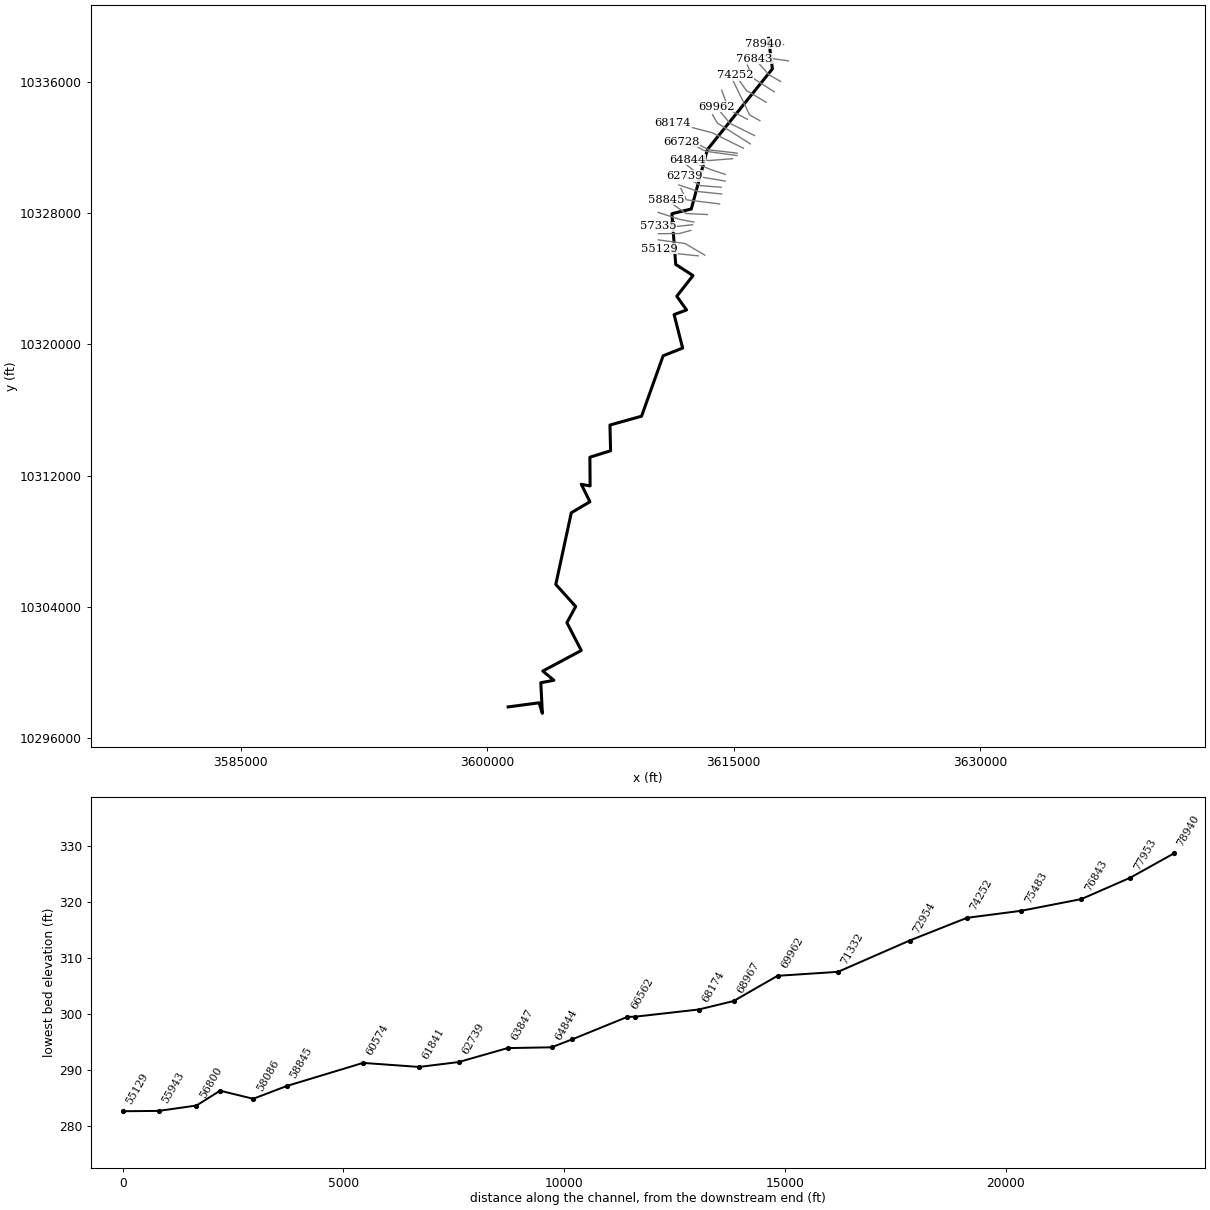
--- SHEPHERD CREEK.prj (project) ---

Proj Title=SHEPHERD CREEK Base Level Engineering
Current Plan=p01
Default Exp/Contr=0.3,0.1
English Units
Geom File=g01
Flow File=f01
Plan File=p01
Y Axis Title=Elevation
X Axis Title(PF)=Main Channel Distance
X Axis Title(XS)=Station
BEGIN DESCRIPTION:
SHEPHERD CREEK
END DESCRIPTION:
DSS Export Rating Curves= 0
DSS Export Rating Curve Sorted= 0
DSS Export Volume Flow Curves= 0
DXF OffsetX= 0
DXF OffsetY= 0
DXF ScaleX= 1
DXF ScaleY= 10

--- SHEPHERD CREEK.p01 (plan) ---

Plan Title=Multiple Run
Short Identifier=Multiple
Geom File=g01
Flow File=f01
Subcritical Flow
K Sum by GR= 0
Std Step Tol= 0.01
Critical Tol= 0.01
Num of Std Step Trials= 20
Max Error Tol= 0.3
Flow Tol Ratio= 0.001
Split Flow NTrial= 30
Split Flow Tol= 0.02
Split Flow Ratio= 0.02
Log Output Level= 0
Friction Slope Method= 1
Unsteady Friction Slope Method= 2
Unsteady Bridges Friction Slope Method= 1
Parabolic Critical Depth
Global Vel Dist=  1 , 1 , 1
Global Log Level= 0
CheckData=True
Encroach Param= -1, 0, 0, 0
BEGIN DESCRIPTION:
Multiple Run
END DESCRIPTION:

--- SHEPHERD CREEK.f01 (steady flow) ---

Flow Title=Multiple
Program Version=4.10
Number of Profiles= 7
Profile Names=10-year,25-year,50-year,1pct_min,100-year,1pct_plu,500-year
River Rch & RM=SHEPHERD CREEK,Reach-1         ,78940
     850    1154    1402    1246    1685    2279    2441
River Rch & RM=SHEPHERD CREEK,Reach-1         ,71332
    1027    1405    1717    1533    2073    2804    3032
River Rch & RM=SHEPHERD CREEK,Reach-1         ,68174
    1747    2445    3032    2743    3710    5017    5569
River Rch & RM=SHEPHERD CREEK,Reach-1         ,66562
    1747    2445    3032    2743    3710    5017    5569
River Rch & RM=SHEPHERD CREEK,Reach-1         ,58845
    1864    2611    3240    2932    3965    5363    5956
River Rch & RM=SHEPHERD CREEK,Reach-1         ,55943
    2208    3109    3871    3514    4753    6428    7183
River Rch & RM=SHEPHERD CREEK,Reach-1         ,55129
    2208    3109    3871    3514    4753    6428    7183
River Rch & RM=SHEPHERD CREEK,Reach-1         ,51205
    2293    3231    4025    3655    4943    6685    7475
River Rch & RM=SHEPHERD CREEK,Reach-1         ,47518
    2595    3669    4581    4168    5637    7624    8558
River Rch & RM=SHEPHERD CREEK,Reach-1         ,45710
    2595    3669    4581    4168    5637    7624    8558
River Rch & RM=SHEPHERD CREEK,Reach-1         ,42393
    2703    3823    4775    4344    5874    7944    8915
River Rch & RM=SHEPHERD CREEK,Reach-1         ,34397
    3019    4279    5353    4875    6594    8917   10030
River Rch & RM=SHEPHERD CREEK,Reach-1         ,33188
    3019    4279    5353    4875    6594    8917   10030
River Rch & RM=SHEPHERD CREEK,Reach-1         ,30379
    3481    4953    6212    5670    7668   10370   11715
River Rch & RM=SHEPHERD CREEK,Reach-1         ,25320
    3831    5459    6854    6262    8468   11452   12959
River Rch & RM=SHEPHERD CREEK,Reach-1         ,23436
    3831    5459    6854    6262    8468   11452   12959
River Rch & RM=SHEPHERD CREEK,Reach-1         ,19121
    3936    5594    7011    6392    8644   11690   13172
River Rch & RM=SHEPHERD CREEK,Reach-1         ,17100
    3936    5594    7011    6392    8644   11690   13172
Boundary for River Rch & Prof#=SHEPHERD CREEK,Reach-1         , 1
Up Type= 0
Dn Type= 3
Dn Slope=0.001
Boundary for River Rch & Prof#=SHEPHERD CREEK,Reach-1         , 2
Up Type= 0
Dn Type= 3
Dn Slope=0.001
Boundary for River Rch & Prof#=SHEPHERD CREEK,Reach-1         , 3
Up Type= 0
Dn Type= 3
Dn Slope=0.001
Boundary for River Rch & Prof#=SHEPHERD CREEK,Reach-1         , 4
Up Type= 0
Dn Type= 3
Dn Slope=0.001
Boundary for River Rch & Prof#=SHEPHERD CREEK,Reach-1         , 5
Up Type= 0
Dn Type= 3
Dn Slope=0.001
Boundary for River Rch & Prof#=SHEPHERD CREEK,Reach-1         , 6
Up Type= 0
Dn Type= 3
Dn Slope=0.001
Boundary for River Rch & Prof#=SHEPHERD CREEK,Reach-1         , 7
Up Type= 0
Dn Type= 3
Dn Slope=0.001
DSS Import GetInterval= 0
DSS Import GetPeak= 0
DSS Import FillOption= 0

--- SHEPHERD CREEK.g01 (geometry) ---

Geom Title=Existing Conditions
Program Version=4.10

River Reach=SHEPHERD CREEK  ,Reach-1
Reach XY= 30
      3617126.63     10338630.83      3617362.11     10336771.64
      3613406.28     10331857.57      3612426.55     10328238.74
      3611246.53     10327951.95      3611479.69     10324866.02
      3612531.94     10324186.33      3611543.99     10322926.32
       3612139.4     10322092.91      3611381.43     10321809.08
      3611901.34     10319770.97      3610714.24     10319300.95
       3609401.6     10315622.23       3607478.9     10315085.04
      3607516.67     10313519.04       3606258.3     10313124.66
      3606270.68     10311376.85      3605733.81     10311476.69
      3606259.05     10310412.94      3605125.49     10309742.09
      3604182.97     10305379.38      3605393.62     10304034.88
      3604859.94     10303049.29      3605733.65     10301355.76
      3603390.89     10300104.33      3604065.89     10299541.83
      3603270.75     10299394.61       3603365.6     10297527.07
      3603164.56     10298170.82      3601283.31     10297921.04

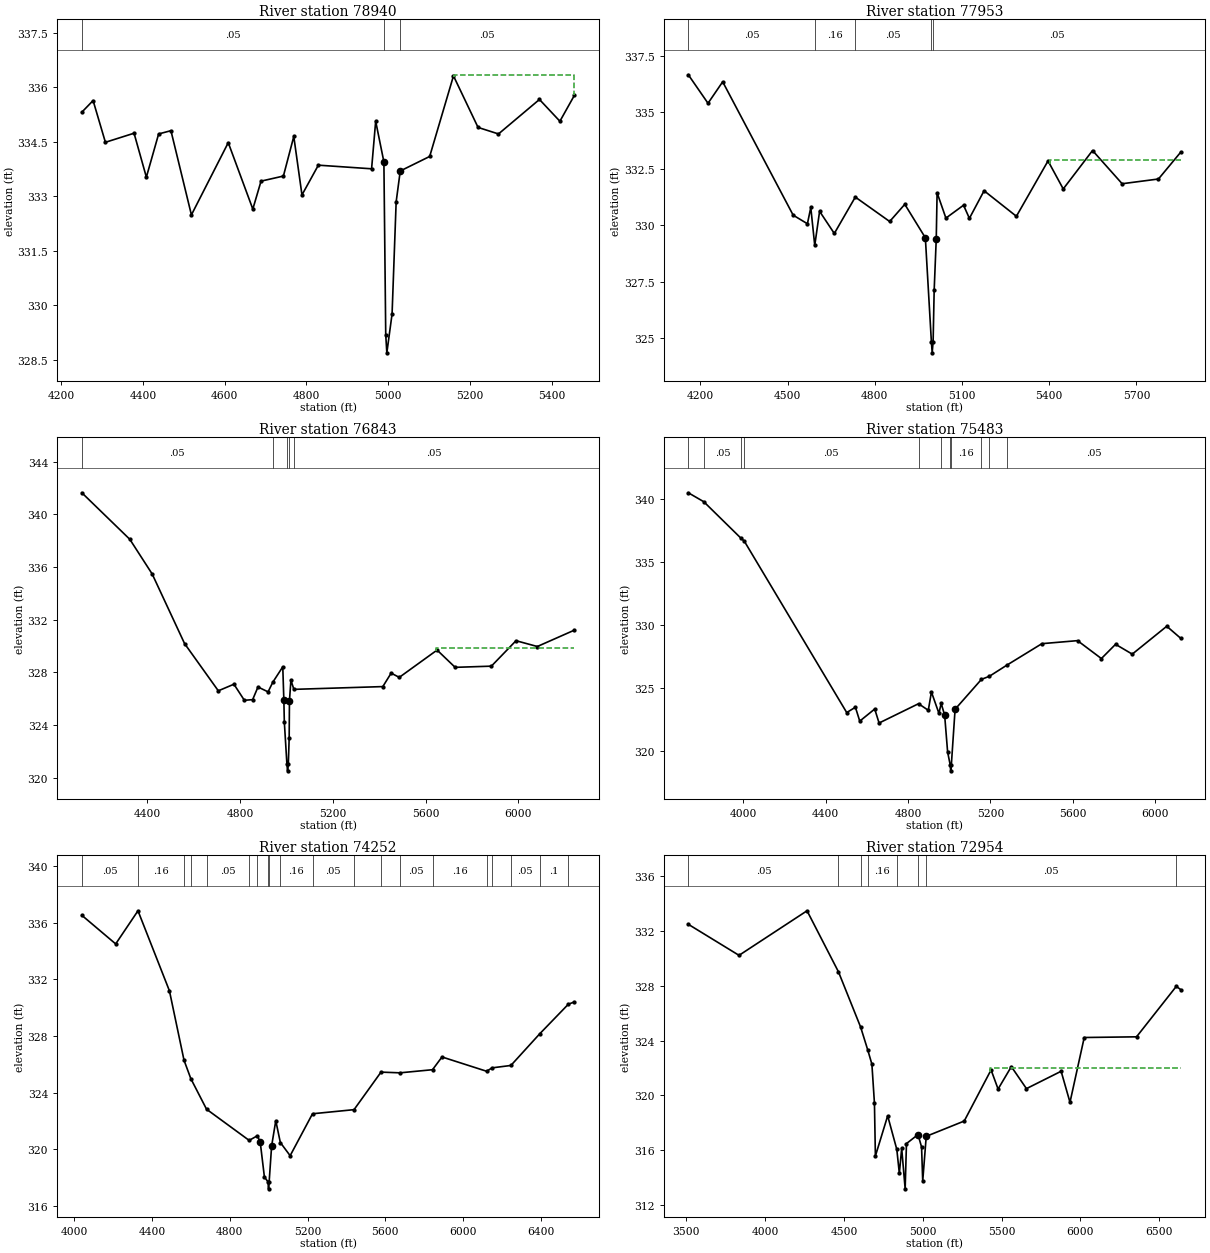
Type RM Length L Ch R = 1 ,78940   ,987,987,987
BEGIN DESCRIPTION:
SHEPHERD CREEK 86.0
END DESCRIPTION:
XS GIS Cut Line= 3
      3618039.61      10338247.8      3617292.11     10338291.64
      3616836.87     10338314.68
#Sta/Elev= 30
  4250.8  335.32  4278.3  335.64  4308.4  334.49  4378.5  334.74  4408.6  333.53
  4438.6  334.72  4468.7  334.81  4518.8  332.49  4608.9  334.48    4669  332.65
  4689.1  333.42  4743.8  333.56  4769.2  334.65  4789.2  333.04  4829.3  333.86
  4959.5  333.76  4969.5  335.07  4989.6  333.95  4994.1  329.19  4996.8  328.69
  5009.6  329.76  5019.6  332.85  5029.6   333.7  5101.6   334.1  5159.8  336.32
  5219.9   334.9  5269.9  334.72  5370.1  335.67  5420.1  335.07  5455.4  335.78
#Mann= 3 , 0 , 0
  4250.8     .05       0  4989.6     .07       0  5029.6     .05       0
#XS Ineff= 2 , 0
                          5161.7          336.35
Permanent Ineff=
       F       F
Bank Sta=4989.6,5029.6
XS Rating Curve= 0 ,0
Exp/Cntr=0.3,0.1

Type RM Length L Ch R = 1 ,77953   ,1110,1110,1110
BEGIN DESCRIPTION:
SHEPHERD CREEK 85.0
END DESCRIPTION:
XS GIS Cut Line= 3
      3618339.11     10337258.21      3617154.18     10337427.49
      3616729.71      10337685.5
#Sta/Elev= 30
  4158.7  336.66  4226.4   335.4  4276.9  336.35  4519.3  330.45  4568.3  330.07
  4579.9  330.79  4593.5  329.11  4610.2  330.62  4660.8  329.64    4733  331.25
  4851.2  330.17  4903.2  330.93  4973.9  329.45  4994.6  324.86  4997.4  324.36
  5000.6  324.86  5004.2  327.12 5011.36   329.4  5014.3  331.44  5044.6  330.32
  5105.2  330.89  5125.4  330.31  5175.9  331.53    5287   330.4  5395.8  332.85
  5448.1  331.61  5548.9  333.31  5650.7  331.84  5775.6  332.05  5852.4  333.24
#Mann= 5 ,-1 , 0
  4158.7     .05       0  4593.5     .16       0    4733     .05       0
  4994.6     .03       0  5000.6     .05       0
#XS Ineff= 2 , 0
                         5401.14          332.88
Permanent Ineff=
       F       F
Bank Sta=4973.9,5011.36
XS Rating Curve= 0 ,0
Exp/Cntr=0.3,0.1

Type RM Length L Ch R = 1 ,76843   ,1360,1360,1360
BEGIN DESCRIPTION:
SHEPHERD CREEK 84.0
END DESCRIPTION:
XS GIS Cut Line= 3
      3617861.36     10336006.76      3617161.38     10336406.75
      3616282.59     10337387.53
#Sta/Elev= 30
  4117.8  341.63  4324.6   338.1    4421  335.47  4560.7  330.19  4706.1  326.61
  4773.4  327.11  4818.4  325.89  4854.1  325.94  4877.1   326.9  4920.6  326.53
  4941.3  327.27    4984  328.43 4988.64  325.91  4990.7  324.24  5001.9  321.04
  5004.6  320.54  5007.9  321.04  5011.6  323.05 5012.78  325.85  5019.1  327.41
  5031.9  326.72  5415.3  326.93  5451.2  327.95  5486.3  327.63  5649.3   329.7
  5727.1  328.39  5883.3  328.48  5989.5  330.41  6081.4  329.97  6240.9  331.21
#Mann= 5 ,-1 , 0
  4117.8     .05       0  4941.3     .16       0  5001.9     .07       0
 5012.78     .16       0  5031.9     .05       0
#XS Ineff= 2 , 0
                         5644.89          329.82
Permanent Ineff=
       F       F
Bank Sta=4988.64,5012.78
XS Rating Curve= 0 ,0
Exp/Cntr=0.3,0.1

Type RM Length L Ch R = 1 ,75483   ,1231,1231,1231
BEGIN DESCRIPTION:
SHEPHERD CREEK 82.0
END DESCRIPTION:
XS GIS Cut Line= 3
      3617471.04     10335378.87      3616203.66     10336190.51
      3615840.06     10337000.88
#Sta/Elev= 30
  3731.9   340.5  3807.1  339.79  3988.9  336.88  4003.4  336.68  4501.6  323.08
  4543.9   323.5    4565   322.4  4637.7  323.36  4658.9  322.25  4850.5  323.78
  4898.1  323.26  4913.3  324.71  4949.7  323.02  4960.7   323.8  4977.5  322.88
    4992  319.95  5004.2  318.96  5006.9  318.46  5010.2  318.96  5028.3  323.34
  5156.3  325.71  5195.5  325.96  5279.2  326.83  5450.1  328.54  5623.3  328.78
  5739.2  327.36  5808.1  328.49  5889.2  327.71  6056.9  329.92  6125.1  328.96
#Mann= 11 ,-1 , 0
  3731.9     .12       0  3807.1     .05       0  3988.9     .12       0
  4003.4     .05       0  4850.5     .12       0  4960.7     .16       0
  5004.2     .07       0  5010.2     .16       0  5156.3     .05       0
  5195.5     .16       0  5279.2     .05       0
Bank Sta=4977.5,5028.3
XS Rating Curve= 0 ,0
Exp/Cntr=0.3,0.1

Type RM Length L Ch R = 1 ,74252   ,1298,1298,1298
BEGIN DESCRIPTION:
SHEPHERD CREEK 81.0
END DESCRIPTION:
XS GIS Cut Line= 3
      3616984.93     10334736.51      3615778.31       10335457.
      3615127.46     10336376.87
#Sta/Elev= 30
  4039.6  336.51  4213.6  334.49  4328.2  336.83  4489.9  331.18  4564.9  326.28
  4599.9  324.98  4680.8  322.82  4899.9  320.62  4942.3  320.95  4956.9  320.48
  4978.3  318.03  4996.7   317.7  4999.5   317.2  5002.7   317.7  5015.3  320.22
  5036.7  322.01  5060.2  320.47  5110.6  319.54  5225.6   322.5  5439.1  322.79
  5577.8  325.44  5675.3  325.39  5842.6  325.61  5891.4  326.51  6120.9   325.5
  6148.5  325.74  6245.6  325.91  6393.6  328.14  6541.5  330.24  6571.8  330.39
#Mann= 20 ,-1 , 0
  4039.6     .05       0  4328.2     .16       0  4564.9     .05       0
  4599.9     .16       0  4680.8     .05       0  4899.9     .16       0
  4942.3     .12       0  4996.7     .07       0  5002.7     .12       0
  5060.2     .16       0  5225.6     .05       0  5439.1     .16       0
  5577.8     .12       0  5675.3     .05       0  5842.6     .16       0
  6120.9     .05       0  6148.5     .16       0  6245.6     .05       0
  6393.6      .1       0  6541.5     .16       0
Bank Sta=4956.9,5015.3
XS Rating Curve= 0 ,0
Exp/Cntr=0.3,0.1

Type RM Length L Ch R = 1 ,72954   ,1622,1622,1622
BEGIN DESCRIPTION:
SHEPHERD CREEK 80.0
END DESCRIPTION:
XS GIS Cut Line= 3
      3616602.97     10333616.72      3615981.79     10333964.64
      3614927.61      10336134.1
#Sta/Elev= 30
    3513   332.5  3834.7  330.23  4266.1  333.49  4465.6  329.02  4606.1  324.98
  4651.2  323.31  4677.5  322.27  4693.7  319.41  4699.7  315.55  4777.6  318.49
  4835.6  316.03  4851.6  314.28  4866.5  316.11  4888.5  313.15  4896.8  316.46
    4970  317.12  4992.6  316.21  4999.9  313.72  5022.2  316.99  5263.3  318.11
  5433.5  321.85    5478  320.45  5562.1  322.09  5657.9  320.48  5877.9  321.75
  5934.1  319.48  6024.4  324.22  6356.3  324.27  6608.4  327.96    6637  327.72
#Mann= 8 ,-1 , 0
    3513     .05       0  4465.6     .16       0  4606.1     .05       0
  4651.2     .16       0  4835.6     .12       0    4970     .07       0
  5022.2     .05       0  6608.4     .16       0
#XS Ineff= 2 , 0
                         5426.99          321.98
Permanent Ineff=
       F       F
Bank Sta=4970,5022.2
XS Rating Curve= 0 ,0
Exp/Cntr=0.3,0.1

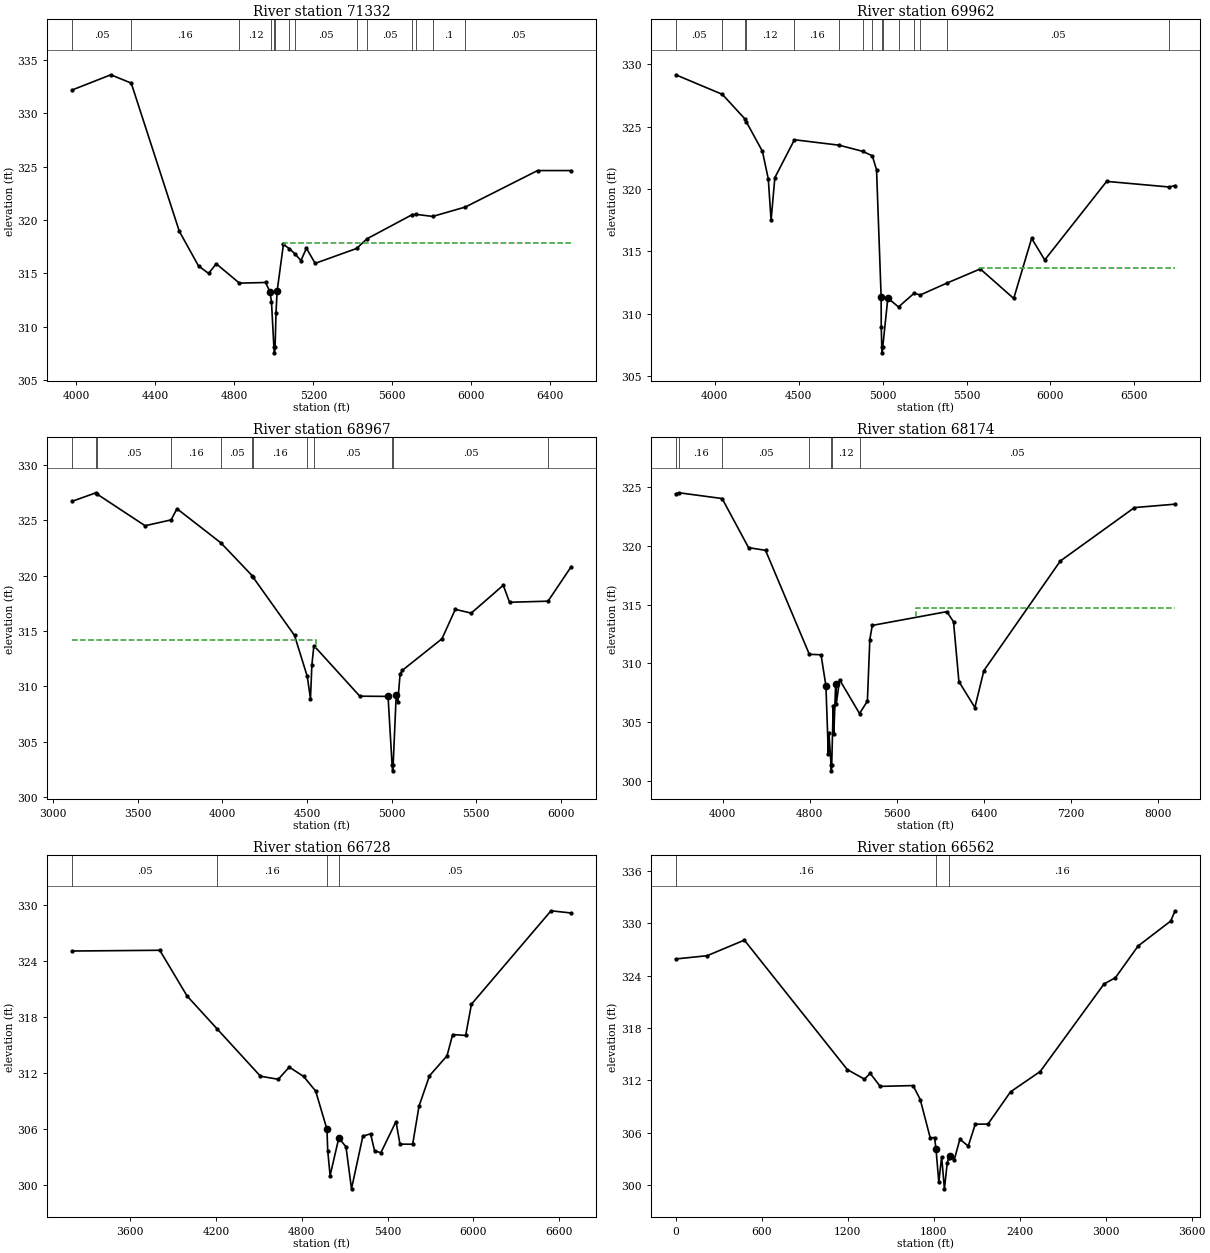
Type RM Length L Ch R = 1 ,71332   ,1370,1370,1370
BEGIN DESCRIPTION:
SHEPHERD CREEK 79.0
END DESCRIPTION:
XS GIS Cut Line= 3
      3615839.05     10333703.55      3614710.52     10334299.16
      3614276.82     10335473.69
#Sta/Elev= 30
  3977.9  332.15  4174.8  333.58  4278.1   332.8  4521.5  318.94    4619  315.69
    4670     315  4708.4   315.9    4826  314.09  4958.2  314.15  4980.8  313.26
  4988.2  312.32  5000.4  308.07  5003.2  307.57  5006.4  308.07    5011  311.27
  5016.6  313.32  5048.6  317.71  5078.9  317.31  5105.4  316.86  5137.4   316.2
  5165.1  317.36  5209.2  315.94  5418.9  317.33    5472  318.24    5701   320.5
  5721.2  320.52  5804.2  320.33  5969.9  321.21  6335.3  324.62    6506  324.62
#Mann= 14 ,-1 , 0
  3977.9     .05       0  4278.1     .16       0    4826     .12       0
  4988.2     .05       0  5000.4     .03       0  5006.4     .05       0
  5078.9     .12       0  5105.4     .05       0  5418.9     .16       0
    5472     .05       0    5701      .1       0  5721.2     .05       0
  5804.2      .1       0  5969.9     .05       0
#XS Ineff= 2 , 0
                         5049.15           317.8
Permanent Ineff=
       F       F
Bank Sta=4980.8,5016.6
XS Rating Curve= 0 ,0
Exp/Cntr=0.3,0.1

Type RM Length L Ch R = 1 ,69962   ,995,995,995
BEGIN DESCRIPTION:
SHEPHERD CREEK 77.0
END DESCRIPTION:
XS GIS Cut Line= 3
      3616274.83     10332713.95      3614780.13     10333453.61
      3613946.03     10334458.95
#Sta/Elev= 30
  3767.9  329.16  4045.7  327.59  4178.7  325.64  4188.7  325.38  4284.2  323.03
  4319.2  320.82    4336  317.48  4358.4  320.91  4475.1  323.95  4742.6  323.51
  4881.3  323.02  4939.1  322.66  4964.1  321.54 4991.48  311.35  4992.1  308.92
  4995.3  307.36    4998  306.86  5001.3  307.36  5031.4  311.25    5095  310.54
  5187.8  311.64  5224.5   311.5  5380.9  312.44  5581.9  313.59  5781.1  311.22
  5887.8  316.04  5965.8  314.31  6334.6  320.61  6707.6  320.16  6741.9  320.28
#Mann= 15 ,-1 , 0
  3767.9     .05       0  4045.7     .12       0  4178.7     .05       0
  4188.7     .12       0  4475.1     .16       0  4742.6     .12       0
  4881.3     .16       0  4939.1     .12       0  4995.3     .07       0
  5001.3     .12       0    5095     .16       0  5187.8     .12       0
  5224.5     .16       0  5380.9     .05       0  6707.6     .12       0
#XS Ineff= 2 , 0
                          5582.1           313.7
Permanent Ineff=
       F       F
Bank Sta=4991.48,5031.4
XS Rating Curve= 0 ,0
Exp/Cntr=0.3,0.1

Type RM Length L Ch R = 1 ,68967   ,793,793,793
BEGIN DESCRIPTION:
SHEPHERD CREEK 74.0
END DESCRIPTION:
XS GIS Cut Line= 3
       3616019.6     10332203.55      3614020.23     10333470.81
      3613720.21     10333970.85
#Sta/Elev= 30
  3111.2  326.72  3252.9   327.5  3256.7  327.41  3543.5  324.52  3697.2  325.05
  3731.6  326.06  3991.4  322.97  4176.9  319.99  4179.8   319.9  4426.4   314.6
  4501.7  310.89  4520.5  308.88    4529  311.96  4540.7  313.68    4812  309.11
  4978.9  309.09    5003  302.86  5005.8  302.36    5009  302.86  5027.2  309.24
  5036.6  308.61  5049.9  311.08  5063.7  311.45  5297.5   314.3  5376.3  316.96
  5470.4  316.62  5659.7  319.14  5696.7   317.6  5924.2   317.7  6061.5  320.83
#Mann= 12 ,-1 , 0
  3111.2     .05       0  3252.9     .16       0  3256.7     .05       0
  3697.2     .16       0  3991.4     .05       0  4176.9     .12       0
  4179.8     .16       0  4501.7     .12       0  4540.7     .05       0
    5003     .03       0    5009     .05       0  5924.2     .16       0
#XS Ineff= 2 , 0
         4555.11  314.19
Permanent Ineff=
       F       F
Bank Sta=4978.9,5027.2
XS Rating Curve= 0 ,0
Exp/Cntr=0.3,0.1

Type RM Length L Ch R = 1 ,68174   ,1446,1446,1446
BEGIN DESCRIPTION:
SHEPHERD CREEK 72.0
END DESCRIPTION:
XS GIS Cut Line= 3
      3615592.51     10331943.13       3613686.3     10332885.82
      3611300.88     10333505.61
#Sta/Elev= 30
  3566.5  324.43  3597.1  324.52  3993.3  324.03  4236.3  319.85  4392.5  319.62
  4795.1  310.77  4902.7  310.73  4947.6   308.1    4970  302.27  4975.6  304.04
  4995.1  301.35  4997.8  300.85  5001.1  301.35  5014.9  306.41  5020.5  303.98
  5037.3  308.23  5042.9  306.53    5073  308.61  5256.7  305.73    5329  306.78
  5351.4  312.03  5373.9  313.23  6059.2   314.4    6121  313.54  6170.5  308.45
  6317.3  306.24    6400  309.38  7102.6  318.71  7784.5  323.26  8157.7  323.55
#Mann= 7 ,-1 , 0
  3566.5     .05       0  3597.1     .16       0  3993.3     .05       0
  4795.1     .12       0  4995.1     .07       0  5001.1     .12       0
  5256.7     .05       0
#XS Ineff= 2 , 0
                         5771.59          314.68
Permanent Ineff=
       F       F
Bank Sta=4947.6,5037.3
XS Rating Curve= 0 ,0
Exp/Cntr=0.3,0.1

Type RM Length L Ch R = 1 ,66728   ,166,166,166
BEGIN DESCRIPTION:
SHEPHERD CREEK 71.1
END DESCRIPTION:
XS GIS Cut Line= 4
      3615222.71     10331641.04      3613509.22     10331838.95
      3612860.37     10332170.34      3611832.13     10332333.74
#Sta/Elev= 30
  3191.3  325.09    3806  325.17  3997.2  320.26  4208.6  316.71  4510.6  311.65
  4635.5  311.32  4711.9  312.63  4813.3  311.62  4897.1  310.05  4975.9  305.96
  4981.5  303.63  4998.1  300.98  5058.9  305.02  5109.2  304.07  5147.8  299.56
  5227.3  305.21  5281.4  305.47  5309.2  303.64  5353.6  303.44  5459.1  306.78
    5487  304.36  5575.9  304.35  5620.4  308.44  5693.6   311.7  5816.3  313.84
  5855.6  316.12  5946.8  316.03  5987.3  319.38  6544.2  329.41  6685.9  329.17
#Mann= 4 ,-1 , 0
  3191.3     .05       0  4208.6     .16       0  4975.9     .07       0
  5058.9     .05       0
Bank Sta=4975.9,5058.9
XS Rating Curve= 0 ,0
Exp/Cntr=0.3,0.1

Type RM Length L Ch R = 1 ,66562   ,1248,1248,1248
BEGIN DESCRIPTION:
SHEPHERD CREEK 71.0
END DESCRIPTION:
XS GIS Cut Line= 6
      3615204.55     10331492.59     3613385.768    10331744.249
     3613138.209    10331825.971     3612755.397    10332057.742
     3611813.903    10332185.3013611813.9027580710332185.3010328
#Sta/Elev= 30
       0325.9152219.5118326.2885478.9349328.07511197.337313.22321317.071312.1244
1356.982312.79411426.827311.29611656.316 311.3891706.205309.7884 1776.05305.3807
1805.984305.42191815.961304.16171835.917300.28111855.478303.22521875.039299.5405
  1894.6302.52351904.381303.05781914.161303.33181943.503302.86191982.625305.2261
2041.308304.44592090.211306.95792178.758306.9713 2336.29310.67242543.052312.9992
2988.781 323.0493068.022323.76273226.503 327.4043454.321330.27253484.036 331.443
#Mann= 3 ,-1 , 0
       0     .16       01815.961     .07       01904.381     .16       0
Bank Sta=1815.961,1914.161
XS Rating Curve= 0 ,0
Exp/Cntr=0.3,0.1

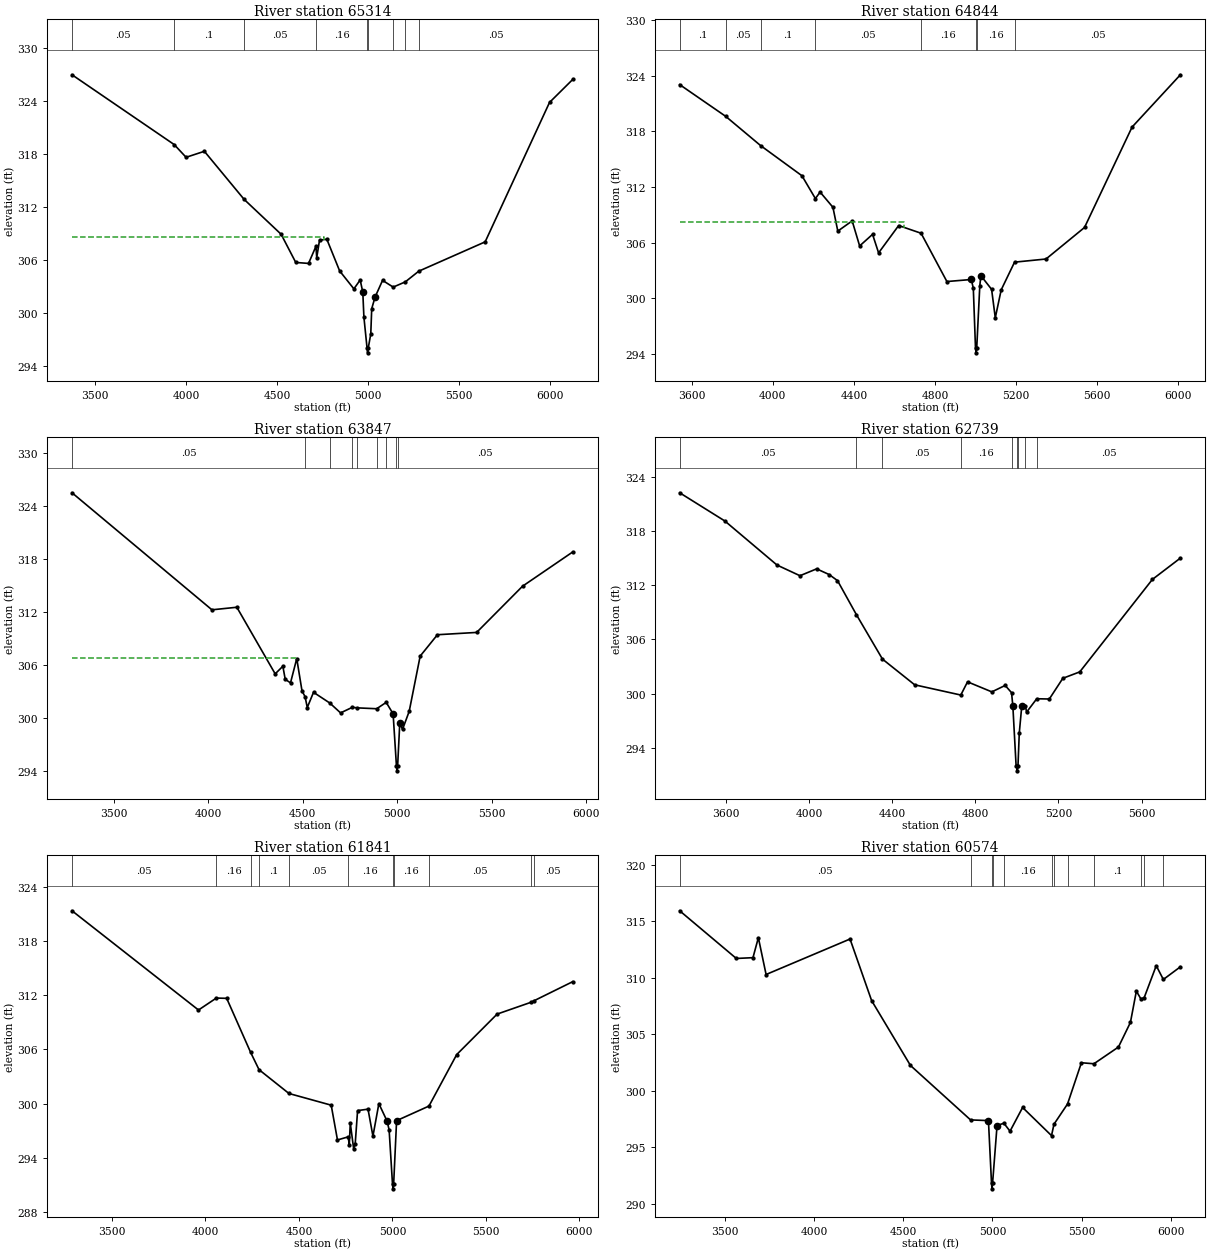
Type RM Length L Ch R = 1 ,65314   ,470,470,470
BEGIN DESCRIPTION:
SHEPHERD CREEK 70.0
END DESCRIPTION:
XS GIS Cut Line= 3
      3614936.28     10331302.49      3613481.69     10331187.48
      3612222.72     10331463.96
#Sta/Elev= 30
  3374.3  327.01  3935.2  319.11  4000.4  317.67  4100.7  318.35  4318.8  312.91
    4522  308.96  4602.3  305.77  4672.5  305.66  4713.2   307.6  4717.4  306.31
  4732.7  308.29  4772.8   308.4  4843.2  304.81  4921.4  302.78  4955.9  303.79
  4970.3   302.4  4976.3  299.59  4993.8  296.04  4996.6  295.54  4999.8  296.04
  5014.1  297.69  5019.2  300.54  5037.8  301.86  5078.7  303.74  5137.1  302.98
  5203.5  303.57  5277.3  304.78  5641.8   308.1  5995.1  323.88  6122.4  326.48
#Mann= 9 ,-1 , 0
  3374.3     .05       0  3935.2      .1       0  4318.8     .05       0
  4713.2     .16       0  4993.8     .07       0  4999.8     .16       0
  5137.1     .05       0  5203.5     .16       0  5277.3     .05       0
#XS Ineff= 2 , 0
         4757.95  308.62
Permanent Ineff=
       F       F
Bank Sta=4970.3,5037.8
XS Rating Curve= 0 ,0
Exp/Cntr=0.3,0.1

Type RM Length L Ch R = 1 ,64844   ,997,997,997
BEGIN DESCRIPTION:
SHEPHERD CREEK 68.0
END DESCRIPTION:
XS GIS Cut Line= 3
      3614492.08     10330346.86      3613592.11     10330646.85
      3612192.07     10331241.66
#Sta/Elev= 30
  3540.3  323.04  3767.1  319.62  3939.1  316.47  4143.4  313.21  4209.7  310.75
    4233  311.45  4296.2  309.81  4320.3  307.24  4391.1  308.34    4428  305.64
  4491.7  306.89  4521.5  304.89  4620.5  307.84    4731  307.01  4858.4   301.8
  4978.8  302.02  4988.7  301.08  4999.5  294.61  5002.2  294.11  5005.5  294.61
  5020.7  301.35  5026.1  302.43  5078.9  300.96  5097.1  297.89  5126.2   300.9
  5192.1  303.89  5347.3  304.23  5537.2  307.63  5771.8  318.46  6010.1   324.1
#Mann= 8 ,-1 , 0
  3540.3      .1       0  3767.1     .05       0  3939.1      .1       0
  4209.7     .05       0    4731     .16       0  4999.5     .07       0
  5005.5     .16       0  5192.1     .05       0
#XS Ineff= 2 , 0
         4648.86  308.27
Permanent Ineff=
       F       F
Bank Sta=4978.8,5026.1
XS Rating Curve= 0 ,0
Exp/Cntr=0.3,0.1

Type RM Length L Ch R = 1 ,63847   ,1108,1108,1108
BEGIN DESCRIPTION:
SHEPHERD CREEK 67.0
END DESCRIPTION:
XS GIS Cut Line= 3
      3614492.09     10329941.64      3613113.24     10330171.45
      3612124.63     10330937.26
#Sta/Elev= 30
  3279.4  325.45  4019.5   312.2  4151.2  312.49    4354  304.95  4394.6  305.81
  4407.2  304.33  4435.1  303.93  4468.1  306.68  4495.9  303.02  4512.1  302.37
  4523.8  301.14  4556.8  302.86  4642.7  301.65  4699.9  300.53    4762  301.16
  4788.6   301.1  4890.8     301  4941.3  301.72  4977.8  300.42  4995.6  294.47
  4998.4  293.97  5001.6  294.47  5013.1  299.42  5027.6  298.66  5062.9  300.71
  5120.9  306.96  5212.3  309.38  5419.6  309.64  5662.3  314.87  5927.8  318.75
#Mann= 9 ,-1 , 0
  3279.4     .05       0  4512.1     .12       0  4642.7     .05       0
    4762     .12       0  4788.6     .16       0  4890.8     .12       0
  4941.3     .16       0  4995.6     .03       0  5001.6     .05       0
#XS Ineff= 2 , 0
         4469.32  306.77
Permanent Ineff=
       F       F
Bank Sta=4977.8,5013.1
XS Rating Curve= 0 ,0
Exp/Cntr=0.3,0.1

Type RM Length L Ch R = 1 ,62739   ,898,898,898
BEGIN DESCRIPTION:
SHEPHERD CREEK 65.0
END DESCRIPTION:
XS GIS Cut Line= 3
      3614248.77     10329562.91      3612993.59     10329661.86
      3612006.35     10330249.56
#Sta/Elev= 30
  3378.3  322.22  3595.6   319.1  3846.4  314.23  3956.8  313.05    4037  313.81
  4097.2  313.18  4137.3  312.51  4228.6  308.73  4353.6  303.83  4508.5  300.99
  4730.3  299.86  4762.7  301.32  4879.5  300.21  4943.7  300.92  4974.4  300.12
  4980.7  298.61  4996.3  292.02  4999.2  291.98  5001.9  291.48  5005.2  291.98
  5011.5  295.65  5023.6  298.68  5041.3  298.68  5046.4  297.96  5095.5  299.45
    5156  299.42    5221  301.71  5302.5  302.42  5651.6  312.64  5786.3     315
#Mann= 9 ,-1 , 0
  3378.3     .05       0  4228.6     .16       0  4353.6     .05       0
  4730.3     .16       0  4974.4     .05       0  4999.2     .03       0
  5005.2     .05       0  5041.3     .12       0  5095.5     .05       0
Bank Sta=4980.7,5023.6
XS Rating Curve= 0 ,0
Exp/Cntr=0.3,0.1

Type RM Length L Ch R = 1 ,61841   ,1267,1267,1267
BEGIN DESCRIPTION:
SHEPHERD CREEK 64.0
END DESCRIPTION:
XS GIS Cut Line= 3
       3614274.8     10329151.45      3612889.42     10329297.28
      3611670.68     10329703.53
#Sta/Elev= 30
  3286.4  321.32  3962.8  310.36  4058.2  311.68  4113.6  311.65  4241.6  305.68
  4286.6  303.77  4446.7  301.14  4672.5  299.85    4706  296.01  4763.2  296.35
  4769.2  295.49  4774.5  297.87  4792.6  295.04  4800.9  295.58  4813.6  299.25
  4869.4  299.41  4895.7  296.43  4927.4  300.02  4971.8  298.07  4982.3  297.11
  5000.4  291.11  5003.1  290.61  5006.4  291.11  5022.2  298.14  5195.2  299.75
  5343.7  305.44  5559.8  309.91  5739.2   311.2  5754.9  311.36  5964.1  313.49
#Mann= 11 ,-1 , 0
  3286.4     .05       0  4058.2     .16       0  4241.6     .05       0
  4286.6      .1       0  4446.7     .05       0  4763.2     .16       0
  5000.4     .07       0  5006.4     .16       0  5195.2     .05       0
  5739.2      .1       0  5754.9     .05       0
Bank Sta=4971.8,5022.2
XS Rating Curve= 0 ,0
Exp/Cntr=0.3,0.1

Type RM Length L Ch R = 1 ,60574   ,1729,1729,1729
BEGIN DESCRIPTION:
SHEPHERD CREEK 63.0
END DESCRIPTION:
XS GIS Cut Line= 3
      3614149.87     10328547.28      3612134.22     10328797.28
      3611790.89     10329492.97
#Sta/Elev= 30
  3246.4  315.94  3563.9  311.72  3657.3  311.79  3687.5  313.56  3730.8   310.3
  4201.4  313.44  4322.4  307.99  4540.1  302.25  4877.1  297.43  4977.3  297.37
  4994.5  291.83  4997.2  291.33  5000.5  291.83  5025.6  296.93  5063.8  297.14
  5098.3  296.43  5168.8  298.53  5330.9  296.04  5344.7  297.05  5420.7  298.84
  5498.4  302.49  5568.6   302.4  5706.1  303.88  5773.3  306.06  5806.5  308.83
  5831.9  308.14  5850.4  308.25    5918  311.08  5957.8  309.86  6053.3  310.98
#Mann= 12 ,-1 , 0
  3246.4     .05       0  4877.1     .12       0  4994.5     .07       0
  5000.5     .12       0  5063.8     .16       0  5330.9     .12       0
  5344.7     .16       0  5420.7     .05       0  5568.6      .1       0
  5831.9     .05       0  5850.4      .1       0  5957.8     .05       0
Bank Sta=4977.3,5025.6
XS Rating Curve= 0 ,0
Exp/Cntr=0.3,0.1

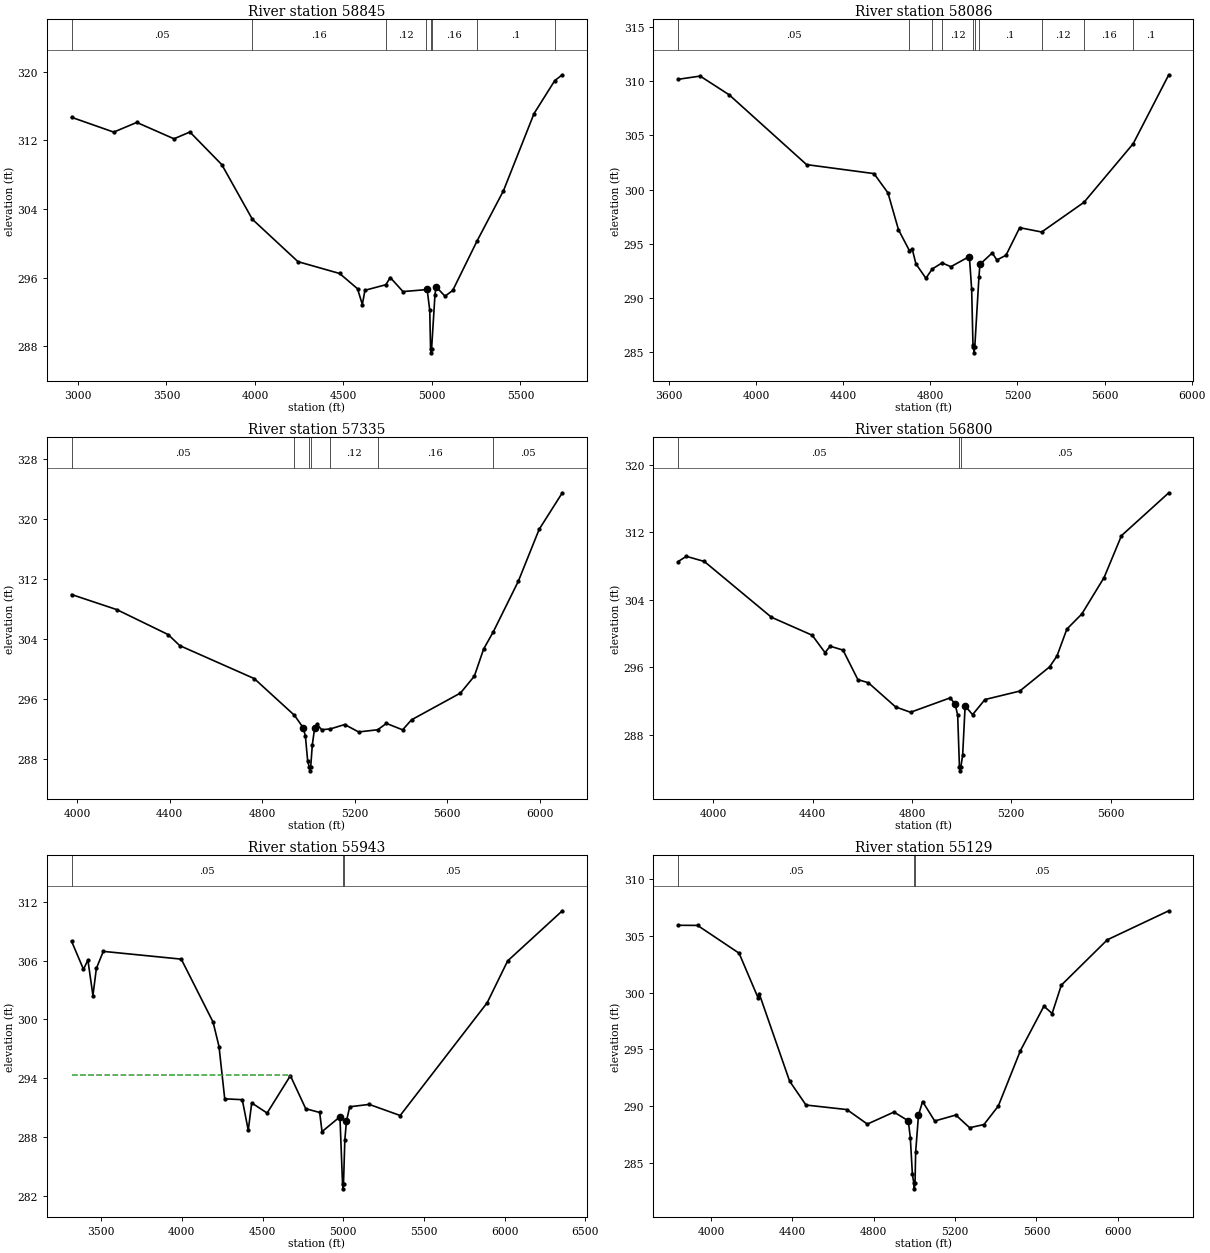
Type RM Length L Ch R = 1 ,58845   ,759,759,759
BEGIN DESCRIPTION:
SHEPHERD CREEK 62.0
END DESCRIPTION:
XS GIS Cut Line= 3
      3613410.28     10327901.45      3612108.17     10327963.95
      3610905.05      10328807.7
#Sta/Elev= 30
  2963.9   314.7  3202.3  312.97  3332.5   314.1  3542.7  312.19  3632.8  312.98
  3813.1  309.17  3985.9  302.79  4243.5  297.85  4478.8  296.47  4579.9  294.69
    4607  292.85  4621.8  294.51    4740  295.16  4764.7     296  4836.8  294.36
  4965.1  294.58    4973  294.65  4987.9  292.17  4992.5  287.71  4995.3  287.21
  4998.5  287.71  5017.5     294  5023.6  294.92  5074.1  293.82  5117.7  294.49
  5255.6  300.28  5404.5  306.13  5577.1  315.13  5694.2  318.98    5737  319.66
#Mann= 8 ,-1 , 0
  2963.9     .05       0  3985.9     .16       0    4740     .12       0
  4965.1     .16       0  4992.5     .07       0  4998.5     .16       0
  5255.6      .1       0  5694.2     .05       0
Bank Sta=4973,5023.6
XS Rating Curve= 0 ,0
Exp/Cntr=0.3,0.1

Type RM Length L Ch R = 1 ,58086   ,751,751,751
BEGIN DESCRIPTION:
SHEPHERD CREEK 60.0
END DESCRIPTION:
XS GIS Cut Line= 3
       3612582.1     10327443.12       3611736.9     10327605.18
      3610410.26     10328031.65
#Sta/Elev= 30
  3640.8  310.17  3742.6  310.47    3876  308.74  4231.4   302.3    4541  301.47
  4605.2  299.69  4653.5  296.29  4703.8  294.36  4716.5  294.52  4733.6  293.14
  4779.5  291.81  4808.1  292.66  4853.4  293.23  4894.1  292.88  4979.1  293.82
  4989.6  290.81  4995.6  285.65  4997.8  285.43  5000.6  284.93  5003.8  285.43
  5023.1  291.95  5027.7   293.1  5084.2  294.15  5105.2   293.5  5147.2  293.93
  5210.2  296.48  5311.1  296.08  5505.4  298.82  5731.4  304.23  5894.9  310.59
#Mann= 10 ,-1 , 0
  3640.8     .05       0  4703.8     .12       0  4808.1     .05       0
  4853.4     .12       0  4997.8     .07       0  5003.8     .12       0
  5023.1      .1       0  5311.1     .12       0  5505.4     .16       0
  5731.4      .1       0
Bank Sta=4979.1,5027.7
XS Rating Curve= 0 ,0
Exp/Cntr=0.3,0.1

Type RM Length L Ch R = 1 ,57335   ,535,535,535
BEGIN DESCRIPTION:
SHEPHERD CREEK 59.0
END DESCRIPTION:
XS GIS Cut Line= 3
      3612506.73     10327282.27      3611606.69     10327182.27
       3610392.1     10327191.64
#Sta/Elev= 30
  3976.5  309.94  4172.3  307.92  4394.2  304.58    4444  303.11    4766   298.7
  4939.6  293.79  4976.7  292.16  4986.7  291.05  4996.7  287.66  5003.7  286.87
  5006.4  286.37  5009.7  286.87  5016.7  289.86  5026.7  292.07  5036.7  292.63
  5056.7  291.87  5094.2  291.97  5156.7  292.56  5216.7  291.57    5299  291.86
  5336.7  292.71  5406.7  291.85  5445.3  293.19  5656.7  296.77  5716.7  299.03
  5756.7  302.65  5798.1  304.93  5906.7  311.72  5996.7  318.66  6096.7  323.54
#Mann= 7 ,-1 , 0
  3976.5     .05       0  4939.6     .16       0  5003.7     .07       0
  5009.7     .16       0  5094.2     .12       0    5299     .16       0
  5798.1     .05       0
Bank Sta=4976.7,5026.7
XS Rating Curve= 0 ,0
Exp/Cntr=0.3,0.1

Type RM Length L Ch R = 1 ,56800   ,857,857,857
BEGIN DESCRIPTION:
SHEPHERD CREEK 58.0
END DESCRIPTION:
XS GIS Cut Line= 3
      3612394.64      10326932.7      3611691.51      10326745.2
      3610441.56     10326734.78
#Sta/Elev= 30
  3857.1  308.52  3890.8  309.15  3963.3  308.54  4233.7  301.93  4397.9   299.8
  4449.6  297.74  4470.3   298.5  4522.1  298.04    4582  294.54  4624.2  294.17
  4734.2   291.3  4794.2  290.67  4954.2  292.38  4974.2  291.61  4984.2  290.31
  4991.2  284.23    4994  283.73  4997.2  284.23  5004.2  285.59  5014.2  291.42
  5044.2  290.39  5094.2  292.18  5234.2  293.18  5354.2  296.04  5384.2  297.33
  5424.2  300.53  5484.2  302.31  5574.2  306.64  5644.2   311.6  5834.8  316.68
#Mann= 3 ,-1 , 0
  3857.1     .05       0  4991.2     .03       0  4997.2     .05       0
Bank Sta=4974.2,5014.2
XS Rating Curve= 0 ,0
Exp/Cntr=0.3,0.1

Type RM Length L Ch R = 1 ,55943   ,814,814,814
BEGIN DESCRIPTION:
SHEPHERD CREEK 57.0
END DESCRIPTION:
XS GIS Cut Line= 3
      3613248.79     10325427.49      3612053.43     10326136.56
      3610416.31     10326359.67
#Sta/Elev= 30
  3316.2  307.97  3390.4   305.1  3417.7  306.05  3448.9  302.44  3470.3   305.2
  3513.2  306.93  3996.5  306.14  4193.4  299.74  4230.4  297.25  4265.8  291.93
  4374.6  291.84  4411.6  288.73  4433.1  291.51  4528.6  290.48  4672.8  294.28
  4767.9  290.92  4854.3  290.54  4868.9  288.59  4979.9   290.1    4996  283.27
  4998.7  282.77    5002  283.27  5010.2  287.74  5020.2  289.65  5040.4  291.12
  5161.5  291.36  5353.3  290.23  5892.4   301.7  6019.4  305.96  6358.3  311.06
#Mann= 3 ,-1 , 0
  3316.2     .05       0    4996     .03       0    5002     .05       0
#XS Ineff= 2 , 0
         4668.47  294.32
Permanent Ineff=
       F       F
Bank Sta=4979.9,5020.2
XS Rating Curve= 0 ,0
Exp/Cntr=0.3,0.1

Type RM Length L Ch R = 1 ,55129   ,484,484,484
BEGIN DESCRIPTION:
SHEPHERD CREEK 55.0
END DESCRIPTION:
XS GIS Cut Line= 3
       3612847.8     10325385.82      3611243.59     10325552.49
      3610495.32     10325833.09
#Sta/Elev= 30
  3838.1  305.95  3934.3  305.94  4138.4  303.49    4232  299.54  4237.1  299.93
  4386.7  292.21  4467.2   290.1  4668.2   289.7  4768.8  288.42  4899.5  289.48
  4969.9  288.71  4979.9  287.23    4990  284.02    4997  283.21  4999.8  282.71
    5003  283.21  5006.2  285.96  5020.1  289.21  5040.2  290.41  5099.8  288.69
  5203.5  289.22  5271.5   288.1  5341.8  288.38  5412.2  290.01  5520.8  294.89
  5636.5  298.82  5676.8  298.17    5722  300.67    5948  304.67  6250.1  307.23
#Mann= 3 ,-1 , 0
  3838.1     .05       0    4997     .03       0    5003     .05       0
Bank Sta=4969.9,5020.1
XS Rating Curve= 0 ,0
Exp/Cntr=0.3,0.1