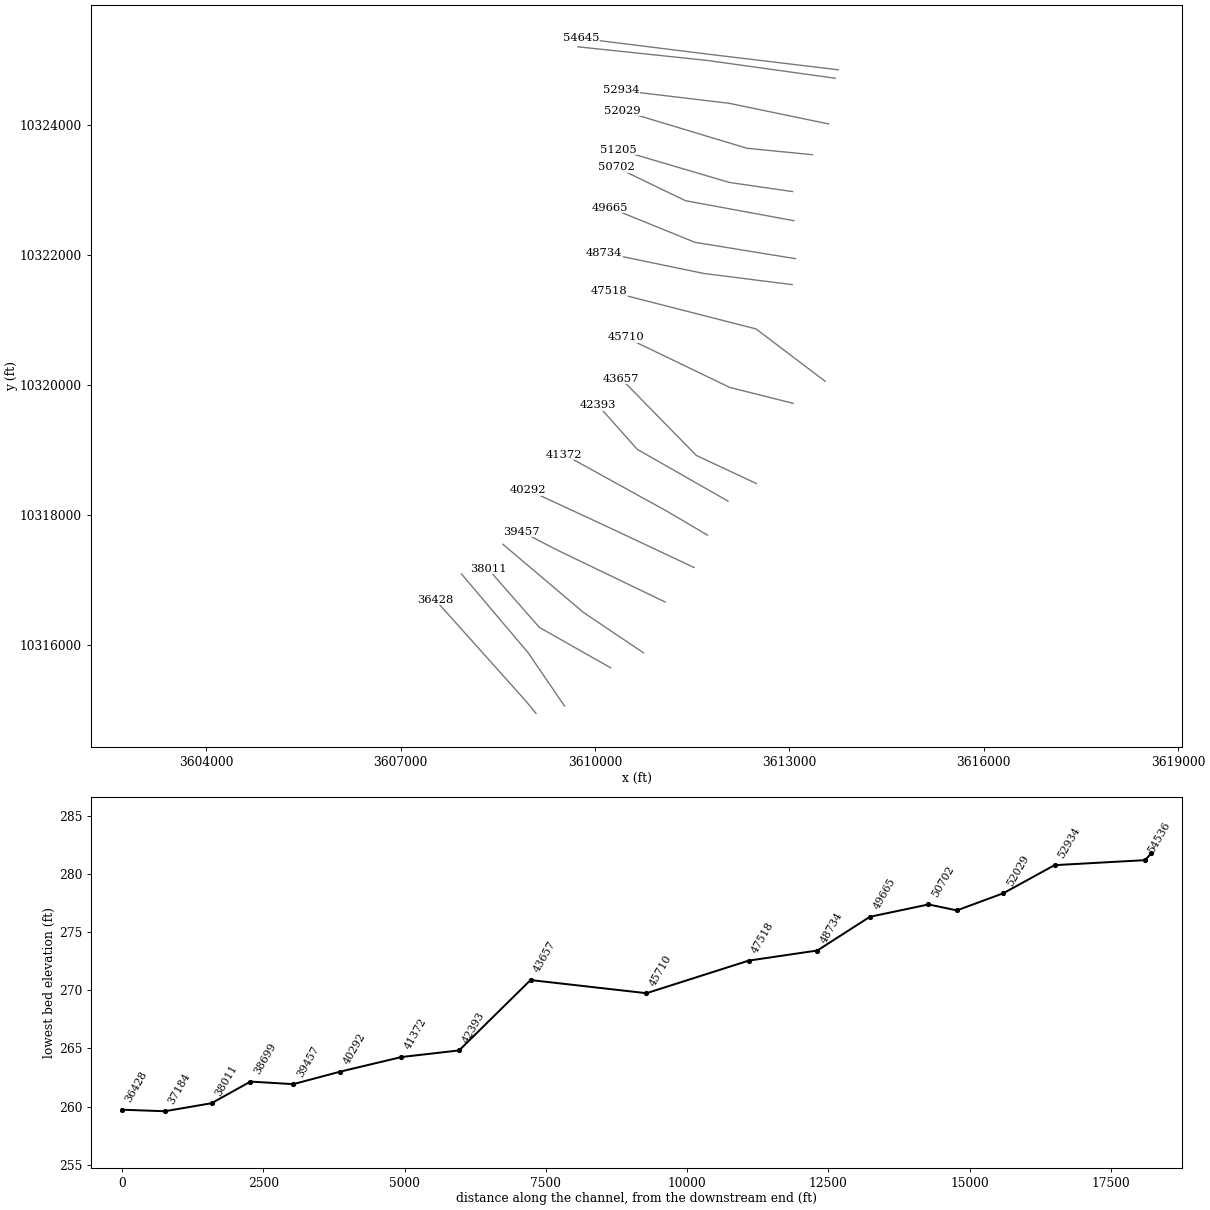
HEC-RAS study SHEPHERD CREEK.prj: SHEPHERD CREEK Base Level Engineering

--- SHEPHERD CREEK.g01 (geometry) --- (continued)

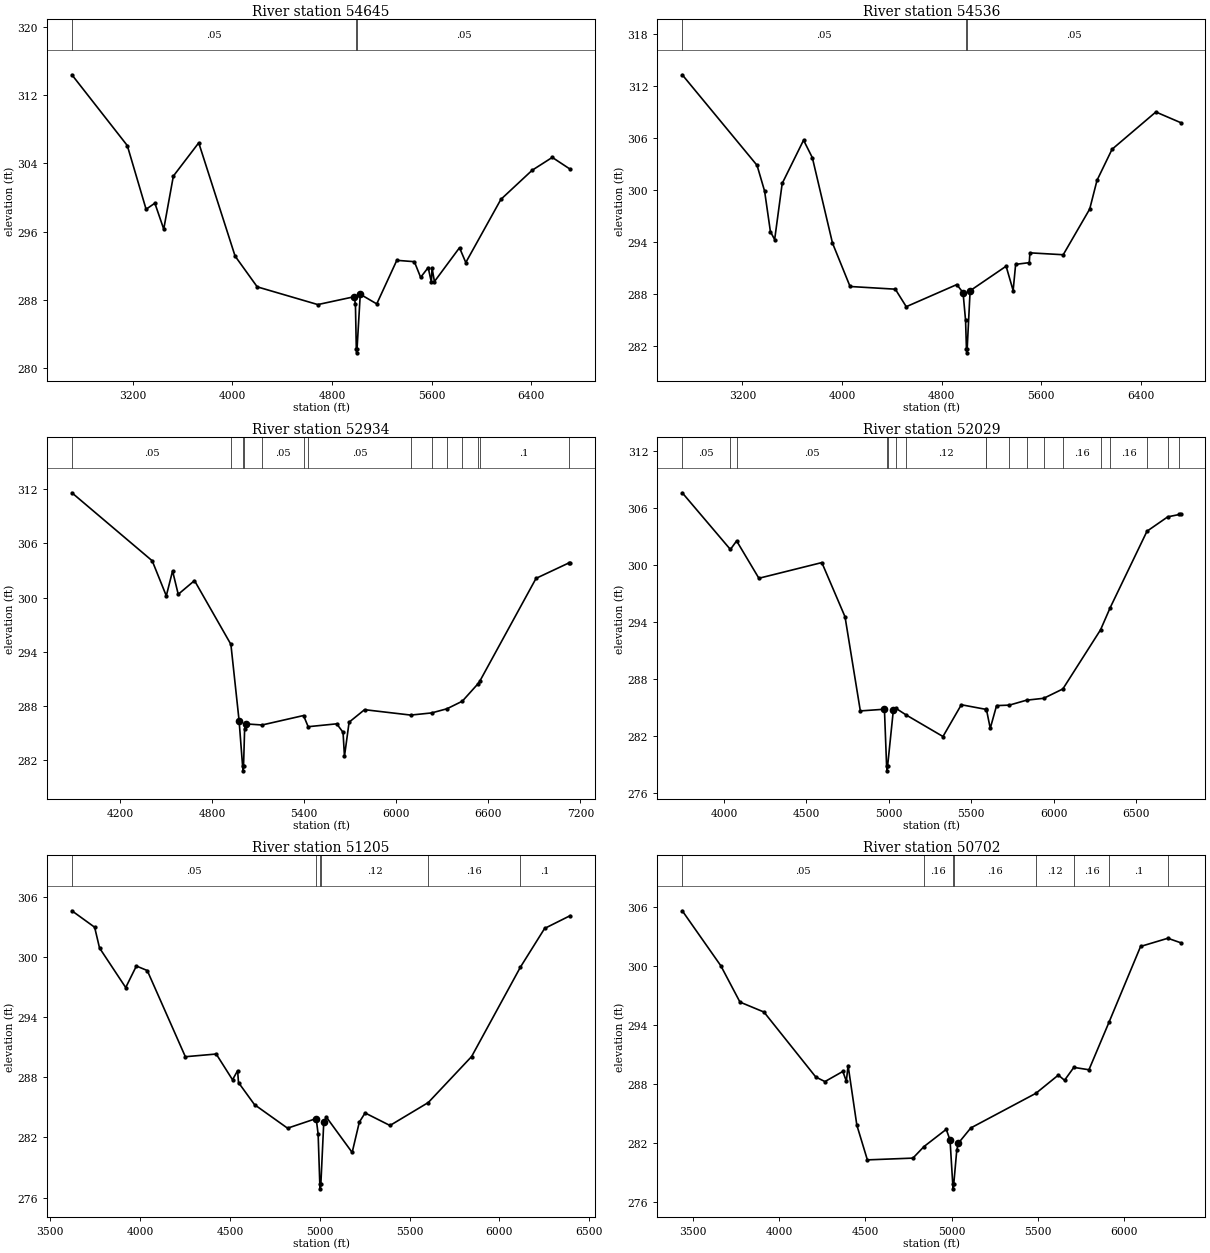
Type RM Length L Ch R = 1 ,54645   ,109,109,109
BEGIN DESCRIPTION:
SHEPHERD CREEK 54.1
END DESCRIPTION:
XS GIS Cut Line= 3
      3613754.03     10324849.36      3611754.01     10325088.95
      3609780.05     10325333.74
#Sta/Elev= 30
    2710  314.38  3155.1  306.08  3306.2  298.61  3376.7  299.32    3448  296.28
  3525.3   302.5  3729.2   306.4  4021.2  293.12    4199  289.51    4686  287.43
  4978.2  288.35  4988.2  287.47  4995.3  282.27  4998.1  281.77  5001.3  282.27
  5027.1  288.64  5159.5  287.51  5320.8  292.62  5461.8  292.46  5512.2  290.62
  5572.7  291.77  5598.6  290.05  5603.7  291.74  5623.1  290.13  5824.6   294.1
    5875  292.36  6157.1  299.77    6408  303.18  6569.9  304.69  6713.4  303.31
#Mann= 3 ,-1 , 0
    2710     .05       0  4995.3     .04       0  5001.3     .05       0
Bank Sta=4978.2,5027.1
XS Rating Curve= 0 ,0
Exp/Cntr=0.3,0.1

Type RM Length L Ch R = 1 ,54536   ,1602,1602,1602
BEGIN DESCRIPTION:
SHEPHERD CREEK 54.0
END DESCRIPTION:
XS GIS Cut Line= 3
      3613707.13     10324719.16       3611729.7     10324993.46
      3609735.18     10325203.32
#Sta/Elev= 30
  2716.2  313.25  3316.9  302.81  3377.5  299.84  3424.3  295.16  3458.3  294.25
  3518.8  300.72  3690.5  305.71  3761.1  303.69  3922.7  293.85    4064  288.84
  4427.5  288.53  4515.3  286.51  4921.3  289.06  4971.6  288.13  4991.7  284.93
  4998.7  281.69  5001.5  281.19  5004.7  281.69  5028.3  288.35  5317.4  291.18
  5373.8  288.37  5393.9  291.39  5503.5  291.59  5508.5  292.72    5776   292.5
  5988.8  297.77  6047.5  301.08  6168.2  304.66  6520.1  308.96  6718.1  307.74
#Mann= 3 ,-1 , 0
  2716.2     .05       0  4998.7     .03       0  5004.7     .05       0
Bank Sta=4971.6,5028.3
XS Rating Curve= 0 ,0
Exp/Cntr=0.3,0.1

Type RM Length L Ch R = 1 ,52934   ,905,905,905
BEGIN DESCRIPTION:
SHEPHERD CREEK 53.0
END DESCRIPTION:
XS GIS Cut Line= 3
      3613604.68     10324016.04      3612068.24     10324333.74
      3610401.59     10324531.65
#Sta/Elev= 30
  3886.2  311.63  4409.6  304.08  4501.5  300.19  4542.4  302.95  4579.3  300.36
  4685.3  301.88  4922.5   294.8    4976  286.32  4998.9  281.26  5001.6  280.76
  5004.9  281.26  5012.1  285.46  5021.1  285.97  5125.8  285.85    5396   286.9
  5426.1  285.66  5612.4  285.98  5653.5  285.03  5662.7  282.37  5692.9  286.16
  5793.6  287.55  6094.8  286.95  6230.8  287.19  6330.7  287.65  6430.7  288.49
  6530.6  290.38  6543.6  290.68  6911.4  302.13  7125.1  303.84  7133.5  303.83
#Mann= 14 ,-1 , 0
  3886.2     .05       0  4922.5     .12       0  4998.9     .07       0
  5004.9     .12       0  5125.8     .05       0    5396     .12       0
  5426.1     .05       0  6094.8     .16       0  6230.8     .05       0
  6330.7     .16       0  6430.7     .05       0  6530.6     .16       0
  6543.6      .1       0  7125.1     .05       0
Bank Sta=4976,5021.1
XS Rating Curve= 0 ,0
Exp/Cntr=0.3,0.1

Type RM Length L Ch R = 1 ,52029   ,824,824,824
BEGIN DESCRIPTION:
SHEPHERD CREEK 52.0
END DESCRIPTION:
XS GIS Cut Line= 3
      3613354.67     10323542.08      3612344.29     10323641.03
      3610422.37     10324219.17
#Sta/Elev= 30
  3747.5  307.59  4039.4  301.63  4077.2  302.53  4212.3   298.6  4594.1  300.25
  4734.8  294.55  4827.6  284.65  4973.8  284.83    4987  278.85  4989.7  278.35
    4993  278.85  5028.2  284.78    5041  284.95  5105.2  284.23  5328.9  281.96
  5440.2   285.3    5588  284.82  5592.8  284.78  5615.7  282.82    5654  285.21
  5731.5  285.26  5835.9  285.78  5940.3  285.98    6056  286.96  6284.7  293.18
  6343.5  295.52  6566.5  303.55  6692.3  305.06  6763.5  305.31  6769.7  305.39
#Mann= 18 ,-1 , 0
  3747.5     .05       0  4039.4     .16       0  4077.2     .05       0
    4987     .03       0    4993     .05       0    5041     .16       0
  5105.2     .12       0    5588     .16       0  5592.8     .12       0
  5731.5      .1       0  5835.9     .16       0  5940.3      .1       0
    6056     .16       0  6284.7      .1       0  6343.5     .16       0
  6566.5     .05       0  6692.3     .16       0  6763.5     .05       0
Bank Sta=4973.8,5028.2
XS Rating Curve= 0 ,0
Exp/Cntr=0.3,0.1

Type RM Length L Ch R = 1 ,51205   ,503,503,503
BEGIN DESCRIPTION:
SHEPHERD CREEK 50.0
END DESCRIPTION:
XS GIS Cut Line= 3
      3613047.44     10322974.36      3612073.45     10323114.99
       3610355.9     10323619.84
#Sta/Elev= 30
  3620.1  304.61  3746.7  302.97    3774   300.9  3919.8  296.95  3979.1   299.1
  4039.7  298.65  4251.9  290.05  4423.7  290.32  4514.6  287.75  4542.8  288.66
  4547.9  287.47  4636.9  285.27    4821  282.92  4976.8  283.86  4980.8  283.81
  4991.2  282.34  5000.5  277.37  5003.2  276.87  5006.5  277.37  5022.5  283.49
  5036.9  284.03  5180.7   280.5  5220.5  283.52  5252.7  284.44  5391.3  283.19
  5604.6  285.48  5845.9  290.07  6117.6  298.99  6252.4  302.85  6394.4  304.12
#Mann= 6 ,-1 , 0
  3620.1     .05       0  4976.8     .12       0  5000.5     .07       0
  5006.5     .12       0  5604.6     .16       0  6117.6      .1       0
Bank Sta=4980.8,5022.5
XS Rating Curve= 0 ,0
Exp/Cntr=0.3,0.1

Type RM Length L Ch R = 1 ,50702   ,1037,1037,1037
BEGIN DESCRIPTION:
SHEPHERD CREEK 49.0
END DESCRIPTION:
XS GIS Cut Line= 3
      3613068.24     10322526.45      3611396.37     10322833.74
      3610323.42     10323349.38
#Sta/Elev= 30
  3437.9  305.61  3661.5  300.03  3772.7  296.34  3911.8  295.33  4212.6  288.73
  4265.7  288.27  4369.4   289.3  4389.7  288.31  4399.9   289.9  4450.7  283.84
  4511.7  280.32  4776.1   280.5    4840  281.67  4969.3  283.42  4991.3  282.33
  5006.9  277.88  5009.7  277.38  5012.9  277.88  5030.3   281.3  5039.3  282.01
  5111.6  283.56  5489.4  287.08  5619.6  288.93  5655.4   288.4  5709.4  289.71
  5797.1  289.47  5914.3  294.33  6096.7  301.99  6254.8  302.82  6328.2  302.37
#Mann= 8 ,-1 , 0
  3437.9     .05       0    4840     .16       0  5006.9     .07       0
  5012.9     .16       0  5489.4     .12       0  5709.4     .16       0
  5914.3      .1       0  6254.8     .16       0
Bank Sta=4991.3,5039.3
XS Rating Curve= 0 ,0
Exp/Cntr=0.3,0.1

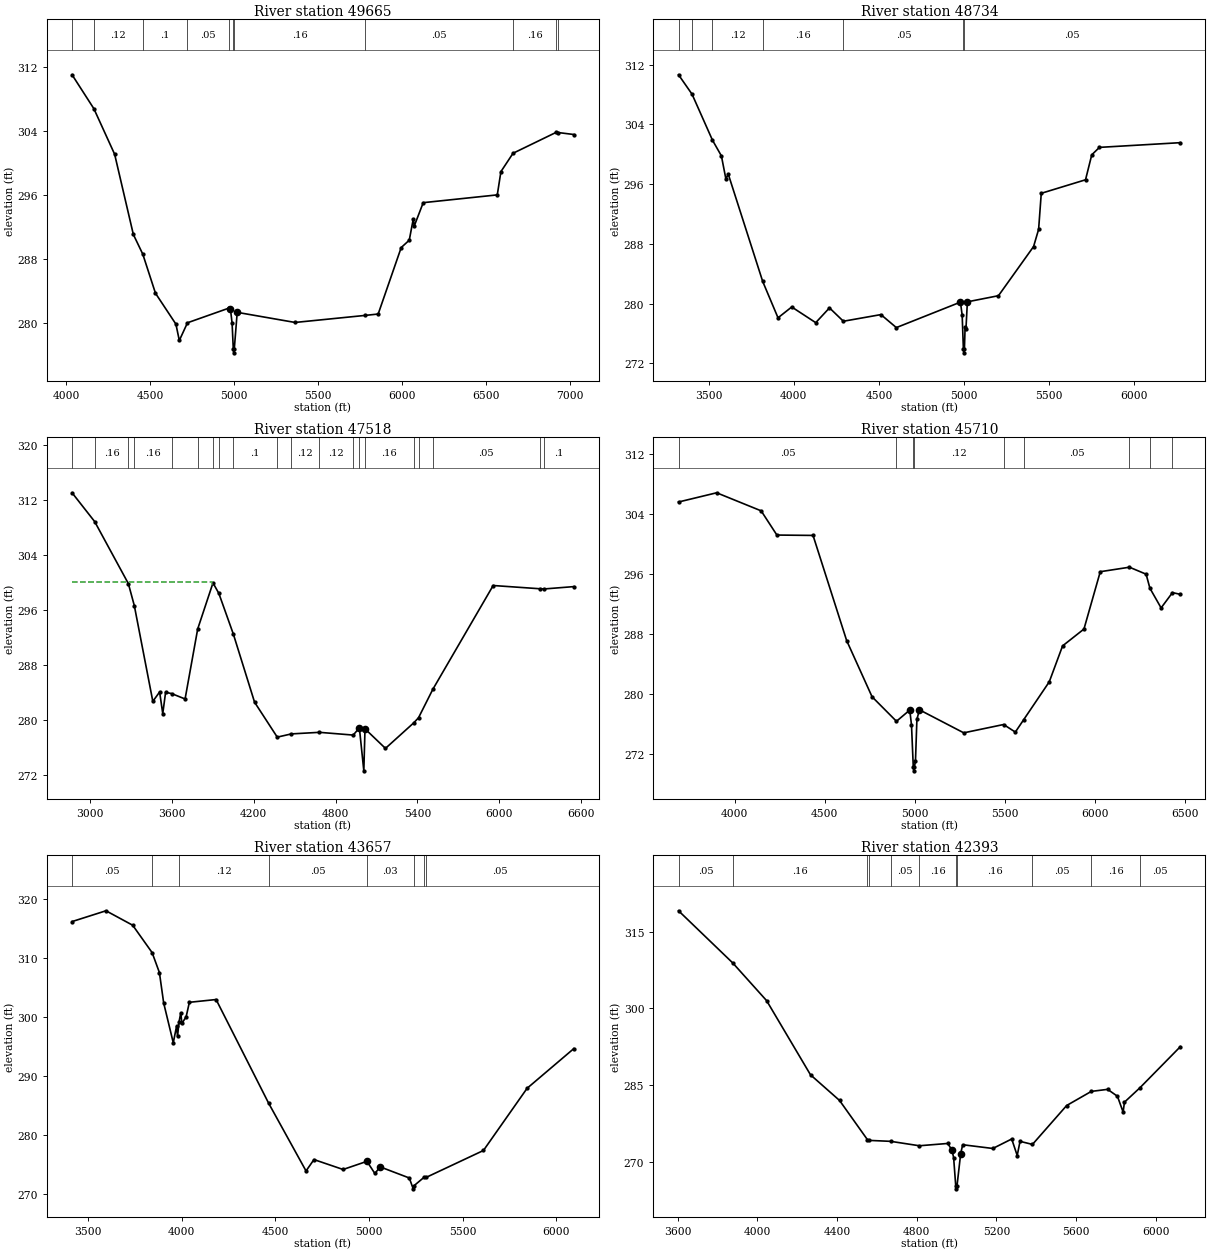
Type RM Length L Ch R = 1 ,49665   ,931,931,931
BEGIN DESCRIPTION:
SHEPHERD CREEK 48.0
END DESCRIPTION:
XS GIS Cut Line= 3
      3613092.09     10321941.64       3611542.2     10322193.11
       3610229.7     10322724.36
#Sta/Elev= 30
  4036.3     311  4166.1  306.77  4289.6  301.09    4401  291.08  4457.1  288.63
  4532.7  283.75  4654.3   279.9  4674.5  277.86  4723.1  280.07  4971.3  281.91
  4978.4  281.85  4988.6  280.02  4995.7  276.82  4998.5  276.32  5001.7  276.82
    5019  281.37  5363.4  280.11  5781.3  280.99  5857.9  281.16  5994.9  289.45
  6042.9  290.37    6067  293.04  6072.4  292.13    6126  295.05  6566.7  296.02
  6588.3  298.92  6660.4  301.21  6917.2  303.82  6927.5   303.8  7022.4  303.55
#Mann= 11 ,-1 , 0
  4036.3     .16       0  4166.1     .12       0  4457.1      .1       0
  4723.1     .05       0  4971.3     .16       0  4995.7     .07       0
  5001.7     .16       0  5781.3     .05       0  6660.4     .16       0
  6917.2     .05       0  6927.5     .16       0
Bank Sta=4978.4,5019
XS Rating Curve= 0 ,0
Exp/Cntr=0.3,0.1

Type RM Length L Ch R = 1 ,48734   ,1216,1216,1216
BEGIN DESCRIPTION:
SHEPHERD CREEK 47.0
END DESCRIPTION:
XS GIS Cut Line= 3
      3613042.07     10321541.65      3611677.62     10321713.95
      3610136.49     10322031.54
#Sta/Elev= 30
  3322.3  310.65  3401.7  308.05  3521.6   301.9  3574.2  299.79  3600.5  296.71
  3614.6  297.34  3816.9  282.98  3906.9  278.11  3987.5  279.56  4128.6  277.46
  4209.3  279.44    4291  277.65  4511.6  278.54  4602.3   276.8  4978.9  280.21
  4989.1  278.47  4996.3  273.92  4999.1  273.42  5002.3  273.92  5006.3  276.84
  5011.4  276.64  5019.7  280.25  5202.4  281.07  5408.7  287.65  5438.3  289.95
  5453.9  294.78    5714  296.59  5750.6  299.93  5795.7  300.93  6271.1  301.56
#Mann= 7 ,-1 , 0
  3322.3     .12       0  3401.7     .16       0  3521.6     .12       0
  3816.9     .16       0    4291     .05       0  4996.3     .03       0
  5002.3     .05       0
Bank Sta=4978.9,5019.7
XS Rating Curve= 0 ,0
Exp/Cntr=0.3,0.1

Type RM Length L Ch R = 1 ,47518   ,1808,1808,1808
BEGIN DESCRIPTION:
SHEPHERD CREEK 46.0
END DESCRIPTION:
XS GIS Cut Line= 3
      3613552.61     10320052.49      3612484.91     10320859.78
      3610219.26     10321437.91
#Sta/Elev= 30
  2869.2  313.06  3034.9  308.86  3281.6  299.83  3325.3  296.62  3460.9  282.67
  3510.8  284.04  3533.7  280.88  3554.5  283.99  3597.9  283.81  3697.3  283.02
  3789.7  293.22  3901.7  299.93  3944.5  298.41  4050.8  292.48  4206.4  282.55
  4372.7  277.46  4475.6  277.93  4681.6  278.16  4929.2  277.76  4974.4  278.81
    5007  272.55  5015.6  278.67  5165.5  275.82  5372.1  279.53  5407.7  280.28
  5512.7  284.43  5954.8  299.55  6294.8  299.08  6329.1  299.05    6546  299.39
#Mann= 20 ,-1 , 0
  2869.2     .05       0  3034.9     .16       0  3281.6     .12       0
  3325.3     .16       0  3597.9     .12       0  3789.7     .16       0
  3901.7      .1       0  3944.5     .16       0  4050.8      .1       0
  4372.7     .16       0  4475.6     .12       0  4681.6     .12       0
  4929.2     .16       0  4974.4     .07       0  5015.6     .16       0
  5372.1     .05       0  5407.7     .16       0  5512.7     .05       0
  6294.8     .16       0  6329.1      .1       0
#XS Ineff= 2 , 0
         3893.47  300.04
Permanent Ineff=
       F       F
Bank Sta=4974.4,5015.6
XS Rating Curve= 0 ,0
Exp/Cntr=0.3,0.1

Type RM Length L Ch R = 1 ,45710   ,2053,2053,2053
BEGIN DESCRIPTION:
SHEPHERD CREEK 45.0
END DESCRIPTION:
XS GIS Cut Line= 3
      3613057.86     10319713.94      3612078.24     10319959.56
      3610475.82     10320728.94
#Sta/Elev= 30
  3687.6  305.62  3899.4  306.85  4146.5  304.44    4234  301.21  4434.8  301.16
  4621.4  287.14  4762.7  279.63  4898.2  276.36  4972.1  277.86  4981.7  275.87
  4991.7  270.25  4994.5  269.75  4997.7  270.25  5003.9   271.1  5011.8  276.63
    5026  277.89    5272  274.82  5493.4  275.93  5558.5  274.92  5605.1  276.58
  5747.1  281.63    5821  286.42  5939.8  288.67  6030.4  296.32  6192.4  296.92
    6285  295.99  6306.2  294.11  6368.3  291.49  6431.5  293.53  6475.1   293.3
#Mann= 9 ,-1 , 0
  3687.6     .05       0  4898.2     .12       0  4991.7     .07       0
  4997.7     .12       0  5493.4     .16       0  5605.1     .05       0
  6192.4     .16       0  6306.2     .05       0  6431.5     .16       0
Bank Sta=4972.1,5026
XS Rating Curve= 0 ,0
Exp/Cntr=0.3,0.1

Type RM Length L Ch R = 1 ,43657   ,1264,1264,1264
BEGIN DESCRIPTION:
SHEPHERD CREEK 44.0
END DESCRIPTION:
XS GIS Cut Line= 3
      3612490.11     10318479.58      3611563.04     10318911.86
      3610401.54     10320094.19
#Sta/Elev= 30
  3414.4  316.17  3595.5     318  3738.2  315.55    3842  310.91  3880.9  307.53
  3903.8  302.36    3955  295.63  3972.4  298.41  3977.9  296.73  3985.5  299.14
  3995.2  300.71  4000.8  298.91  4023.6  300.02    4041  302.49  4183.7  302.96
  4464.2   285.4  4664.1  273.91  4706.5  275.84  4862.1  274.16  4989.4  275.54
  5031.8  273.48  5060.1   274.6  5215.7  272.72  5236.6  270.88  5239.8  271.38
  5294.4  272.83  5305.8  272.82  5611.7  277.38    5845  287.92  6094.7  294.65
#Mann= 8 ,-1 , 0
  3414.4     .05       0    3842     .16       0  3985.5     .12       0
  4464.2     .05       0  4989.4     .03       0  5239.8     .05       0
  5294.4     .12       0  5305.8     .05       0
Bank Sta=4989.4,5060.1
XS Rating Curve= 0 ,0
Exp/Cntr=0.3,0.1

Type RM Length L Ch R = 1 ,42393   ,1021,1021,1021
BEGIN DESCRIPTION:
SHEPHERD CREEK 43.0
END DESCRIPTION:
XS GIS Cut Line= 3
      3612052.58     10318208.76      3610651.58     10319005.61
      3610047.42     10319682.69
#Sta/Elev= 30
    3604  319.05  3876.1  308.88  4046.1  301.53  4266.6  287.06  4412.2  282.07
  4552.5  274.41  4559.1  274.28  4669.5  274.09  4812.9  273.23  4955.6  273.68
  4977.2  272.35  4985.1  270.91  4995.8  265.33  4998.6  264.83  5001.8  265.33
  5020.5  271.71  5030.6  273.43  5181.9   272.7  5276.7  274.55  5304.3  271.33
  5318.5  274.09  5380.8  273.49  5552.6  281.08  5676.3  283.83  5758.2  284.23
  5807.5  282.88    5836   279.8  5842.7  281.73  5919.7  284.51  6123.2  292.55
#Mann= 11 ,-1 , 0
    3604     .05       0  3876.1     .16       0  4552.5     .05       0
  4559.1     .16       0  4669.5     .05       0  4812.9     .16       0
  4995.8     .07       0  5001.8     .16       0  5380.8     .05       0
  5676.3     .16       0  5919.7     .05       0
Bank Sta=4977.2,5020.5
XS Rating Curve= 0 ,0
Exp/Cntr=0.3,0.1

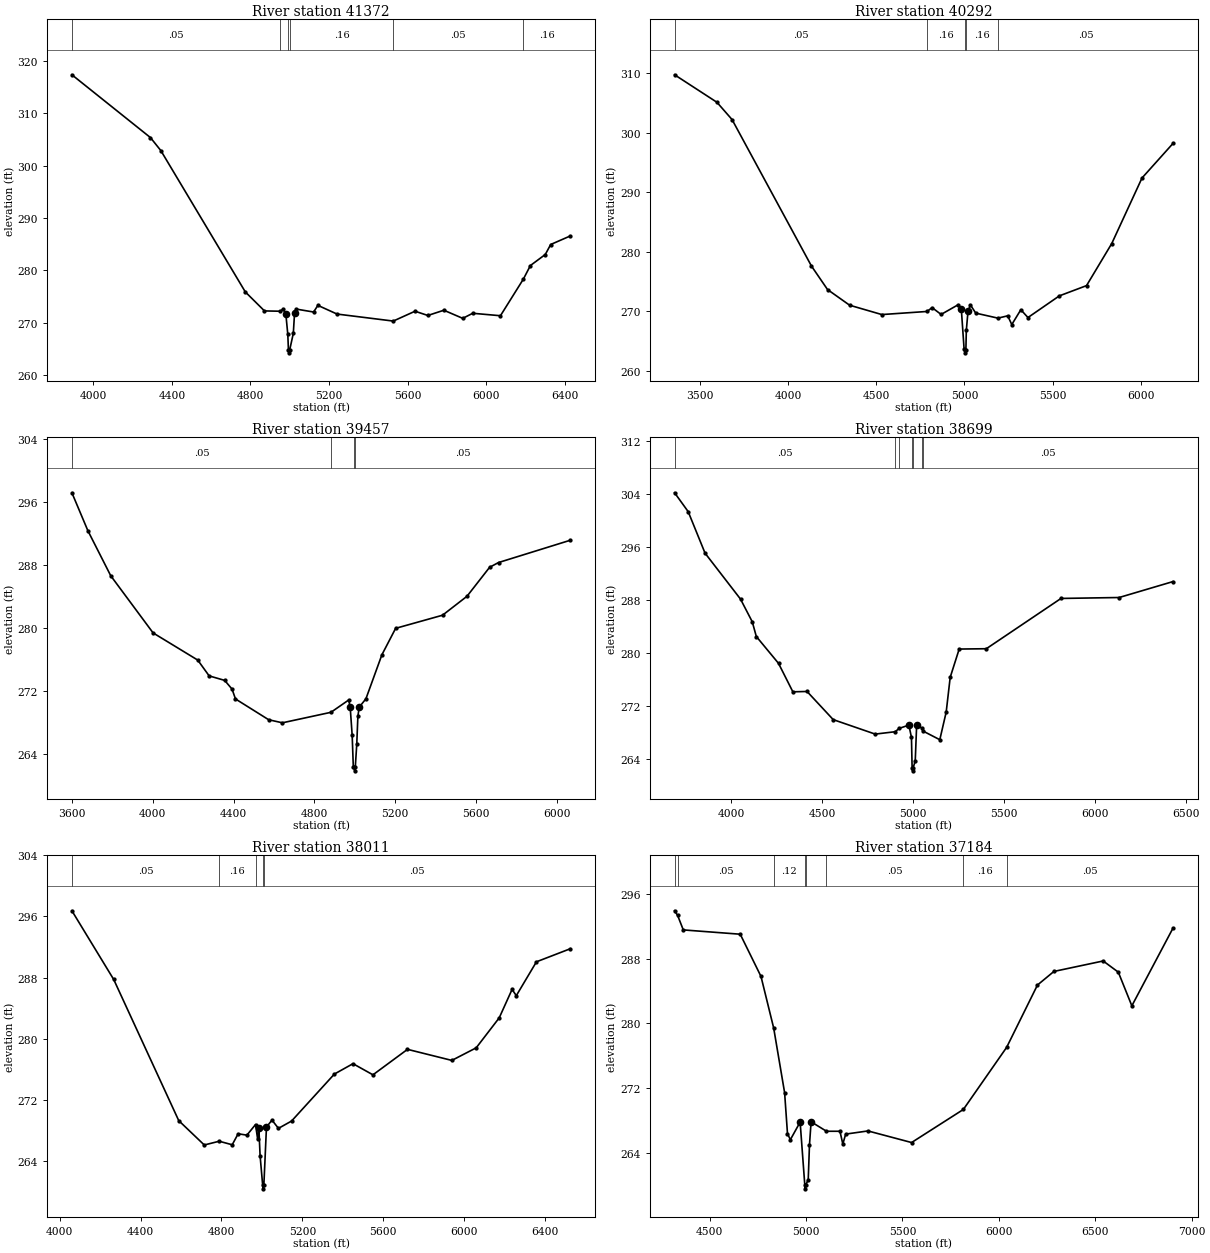
Type RM Length L Ch R = 1 ,41372   ,1080,1080,1080
BEGIN DESCRIPTION:
SHEPHERD CREEK 41.0
END DESCRIPTION:
XS GIS Cut Line= 3
      3611734.49     10317685.72      3611106.19     10318054.97
      3609522.77     10318926.31
#Sta/Elev= 30
  3891.3  317.39    4291  305.39  4343.8  302.91  4773.8   275.9  4871.3  272.27
    4952  272.21  4967.2  272.64  4980.2  271.62    4990  267.78  4993.3  264.76
    4996  264.26  4999.3  264.76  5018.1  267.99  5024.2  271.78  5034.2  272.61
  5121.3  272.06  5143.1  273.33  5240.6  271.67  5526.7  270.33  5637.4  272.21
  5702.7   271.4  5784.2   272.4  5880.3  270.85    5931  271.82  6072.1  271.35
  6188.8  278.35  6224.5  280.94  6300.3  283.05  6327.8  284.96  6427.4  286.59
#Mann= 6 ,-1 , 0
  3891.3     .05       0    4952     .16       0  4993.3     .07       0
  4999.3     .16       0  5526.7     .05       0  6188.8     .16       0
Bank Sta=4980.2,5024.2
XS Rating Curve= 0 ,0
Exp/Cntr=0.3,0.1

Type RM Length L Ch R = 1 ,40292   ,835,835,835
BEGIN DESCRIPTION:
SHEPHERD CREEK 40.0
END DESCRIPTION:
XS GIS Cut Line= 3
      3611528.31      10317186.6      3610154.06     10317831.19
      3608967.53     10318380.19
#Sta/Elev= 30
  3357.1  309.72  3597.1   305.1  3682.8   302.2    4133  277.59  4224.2  273.64
  4349.4  271.01  4531.9  269.44  4788.4  269.96  4816.8  270.61    4868  269.46
  4965.3   271.1  4982.5   270.4  4998.4  263.63  5002.5  263.51  5005.2  263.01
  5008.5  263.51    5011  266.79  5020.4  269.96  5033.9  271.07  5064.5  269.68
  5190.2  268.84  5245.7  269.23  5268.7  267.76    5320  270.25  5360.4  268.94
  5538.3  272.58  5692.4   274.3  5835.4  281.37  6006.9  292.38  6182.4  298.18
#Mann= 5 ,-1 , 0
  3357.1     .05       0  4788.4     .16       0  5002.5     .07       0
  5008.5     .16       0  5190.2     .05       0
Bank Sta=4982.5,5020.4
XS Rating Curve= 0 ,0
Exp/Cntr=0.3,0.1

Type RM Length L Ch R = 1 ,39457   ,758,758,758
BEGIN DESCRIPTION:
SHEPHERD CREEK 39.0
END DESCRIPTION:
XS GIS Cut Line= 3
      3611083.47      10316654.9       3609374.5     10317475.03
       3608869.9     10317739.98
#Sta/Elev= 30
  3600.4  297.13  3679.6  292.32  3792.7  286.62  4002.1  279.39    4223  275.95
  4279.4  273.95  4356.2  273.38  4392.6  272.28  4409.7  271.03  4573.8   268.4
  4641.8  268.01    4882  269.34  4969.9   270.9  4977.3  269.95    4987  266.41
  4992.6  262.46  4996.5  262.43  4999.2  261.93  5002.5  262.43  5009.7  265.31
  5015.2  268.82  5021.7  269.99    5055  271.05    5134  276.62    5202  279.97
    5434  281.63  5555.1  284.03    5667   287.7  5711.1   288.3  6065.9  291.12
#Mann= 4 ,-1 , 0
  3600.4     .05       0    4882     .16       0  4996.5     .07       0
  5002.5     .05       0
Bank Sta=4977.3,5021.7
XS Rating Curve= 0 ,0
Exp/Cntr=0.3,0.1

Type RM Length L Ch R = 1 ,38699   ,688,688,688
BEGIN DESCRIPTION:
SHEPHERD CREEK 37.0
END DESCRIPTION:
XS GIS Cut Line= 3
      3610747.06     10315873.67      3609824.75     10316492.16
      3608577.02     10317544.59
#Sta/Elev= 30
  3687.6  304.23  3762.3  301.38  3855.3  295.09  4050.4  288.14    4115  284.71
  4137.4  282.48  4259.5  278.42  4338.5  274.11  4416.6  274.16  4560.6   269.9
  4791.7  267.71  4901.8  268.07  4923.2  268.57  4976.9  269.07  4991.2  267.22
  4994.8  262.65  4997.5  262.15  5000.8  262.65    5012  263.62  5019.8  269.08
  5047.3  268.65    5055  268.17  5147.2  266.86  5182.4  271.05  5204.4   276.3
  5253.9  280.58  5403.3  280.63  5814.3  288.24  6134.1  288.38  6430.4  290.79
#Mann= 7 ,-1 , 0
  3687.6     .05       0  4901.8     .16       0  4923.2     .12       0
  4994.8     .07       0  5000.8     .12       0  5047.3     .16       0
    5055     .05       0
Bank Sta=4976.9,5019.8
XS Rating Curve= 0 ,0
Exp/Cntr=0.3,0.1

Type RM Length L Ch R = 1 ,38011   ,827,827,827
BEGIN DESCRIPTION:
SHEPHERD CREEK 36.0
END DESCRIPTION:
XS GIS Cut Line= 3
      3610242.08     10315641.65      3609141.16     10316264.29
      3608349.05     10317164.92
#Sta/Elev= 30
  4060.4  296.75  4267.2  287.74  4588.8  269.23    4715  266.04  4788.7  266.53
  4853.1  266.07  4882.4  267.51  4925.7  267.33  4968.3  268.72  4979.2  266.76
  4984.9  268.26  4990.9  264.65  5003.6  260.79  5006.3  260.29  5009.6  260.79
  5022.5   268.4  5049.9   269.3  5081.7  268.22  5146.6  269.18  5358.3  275.34
  5450.3   276.7    5549  275.24  5719.8  278.58    5939  277.13  6059.5  278.78
  6173.3  282.71  6236.9  286.44  6257.8  285.62  6357.4  290.06  6524.6  291.77
#Mann= 5 ,-1 , 0
  4060.4     .05       0  4788.7     .16       0  4968.3     .05       0
  5003.6     .03       0  5009.6     .05       0
Bank Sta=4984.9,5022.5
XS Rating Curve= 0 ,0
Exp/Cntr=0.3,0.1

Type RM Length L Ch R = 1 ,37184   ,756,756,756
BEGIN DESCRIPTION:
SHEPHERD CREEK 35.0
END DESCRIPTION:
XS GIS Cut Line= 3
      3609528.48     10315054.41      3608967.55     10315873.67
      3607937.87      10317087.6
#Sta/Elev= 30
  4318.3  293.89    4334  293.32  4363.4  291.53  4658.7     291  4766.3   285.8
  4832.2  279.43  4888.9  271.46  4903.8  266.41  4918.7  265.66  4969.4  267.83
  4993.5   260.1  4996.3   259.6  4999.5   260.1  5011.4  260.75  5017.9  265.04
  5026.3  267.87  5106.1   266.7  5175.9   266.7  5190.8  265.13  5205.7  266.35
  5321.2  266.74  5547.4  265.31    5816  269.39  6040.5  277.05  6200.2  284.73
  6285.6  286.41  6541.1   287.7  6619.6  286.32  6689.8  282.17    6903  291.74
#Mann= 8 ,-1 , 0
  4318.3     .08       0    4334     .05       0  4832.2     .12       0
  4993.5     .07       0  4999.5     .12       0  5106.1     .05       0
    5816     .16       0  6040.5     .05       0
Bank Sta=4969.4,5026.3
XS Rating Curve= 0 ,0
Exp/Cntr=0.3,0.1

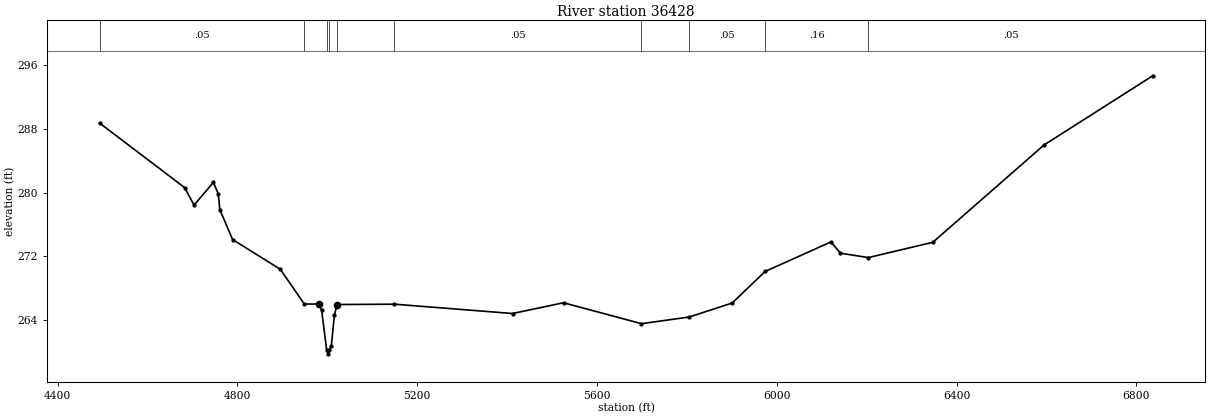
Type RM Length L Ch R = 1 ,36428   ,919,919,919
BEGIN DESCRIPTION:
SHEPHERD CREEK 34.0
END DESCRIPTION:
XS GIS Cut Line= 3
       3609088.2     10314940.96      3608921.54     10315142.33
        3607531.     10316691.63
#Sta/Elev= 30
  4493.2  288.74  4682.7  280.62  4703.5  278.42  4746.5  281.28  4757.5  279.82
  4760.8  277.87  4789.2   274.1  4895.4  270.36  4948.8  265.99  4980.6  265.99
  4987.3  265.23  4998.5  260.23  5001.3  259.73  5004.5  260.23    5009  260.72
  5015.7   264.6  5021.8  265.93  5149.3  265.97  5412.1   264.8  5525.5  266.15
  5698.9  263.52  5805.3  264.36  5900.8  266.12  5973.9  270.08  6120.6   273.8
  6141.5  272.38  6203.6  271.83  6347.1  273.75  6594.5  285.98  6836.4  294.68
#Mann= 10 ,-1 , 0
  4493.2     .05       0  4948.8     .16       0  4998.5     .07       0
  5004.5     .16       0  5021.8     .12       0  5149.3     .05       0
  5698.9     .16       0  5805.3     .05       0  5973.9     .16       0
  6203.6     .05       0
Bank Sta=4980.6,5021.8
XS Rating Curve= 0 ,0
Exp/Cntr=0.3,0.1