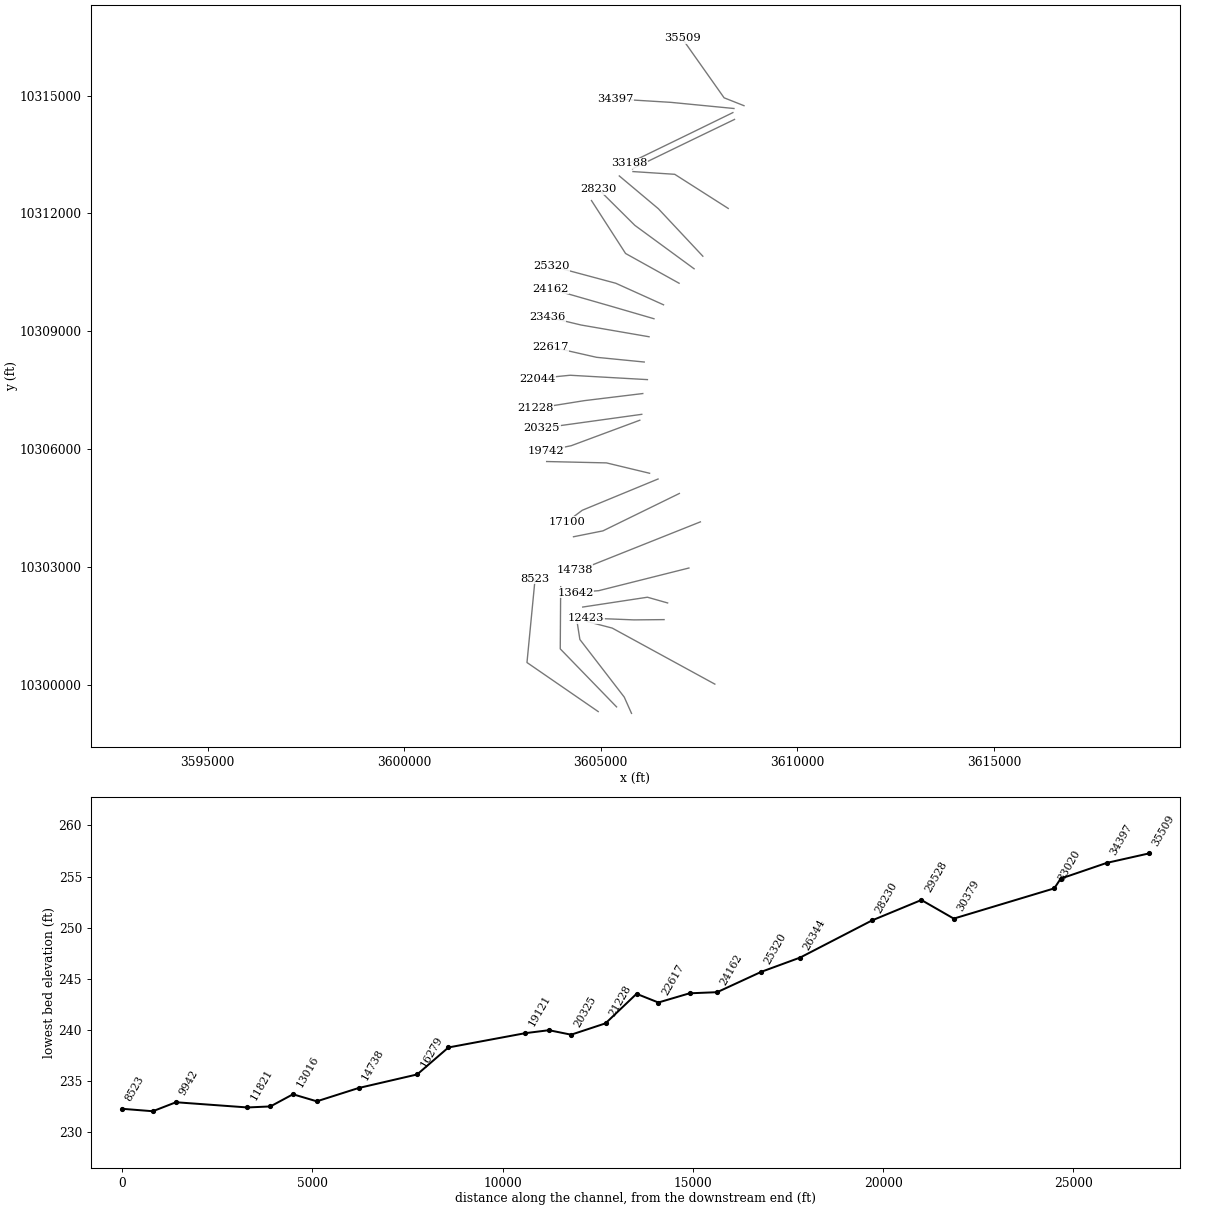
HEC-RAS study SHEPHERD CREEK.prj: SHEPHERD CREEK Base Level Engineering

--- SHEPHERD CREEK.g01 (geometry) --- (continued)

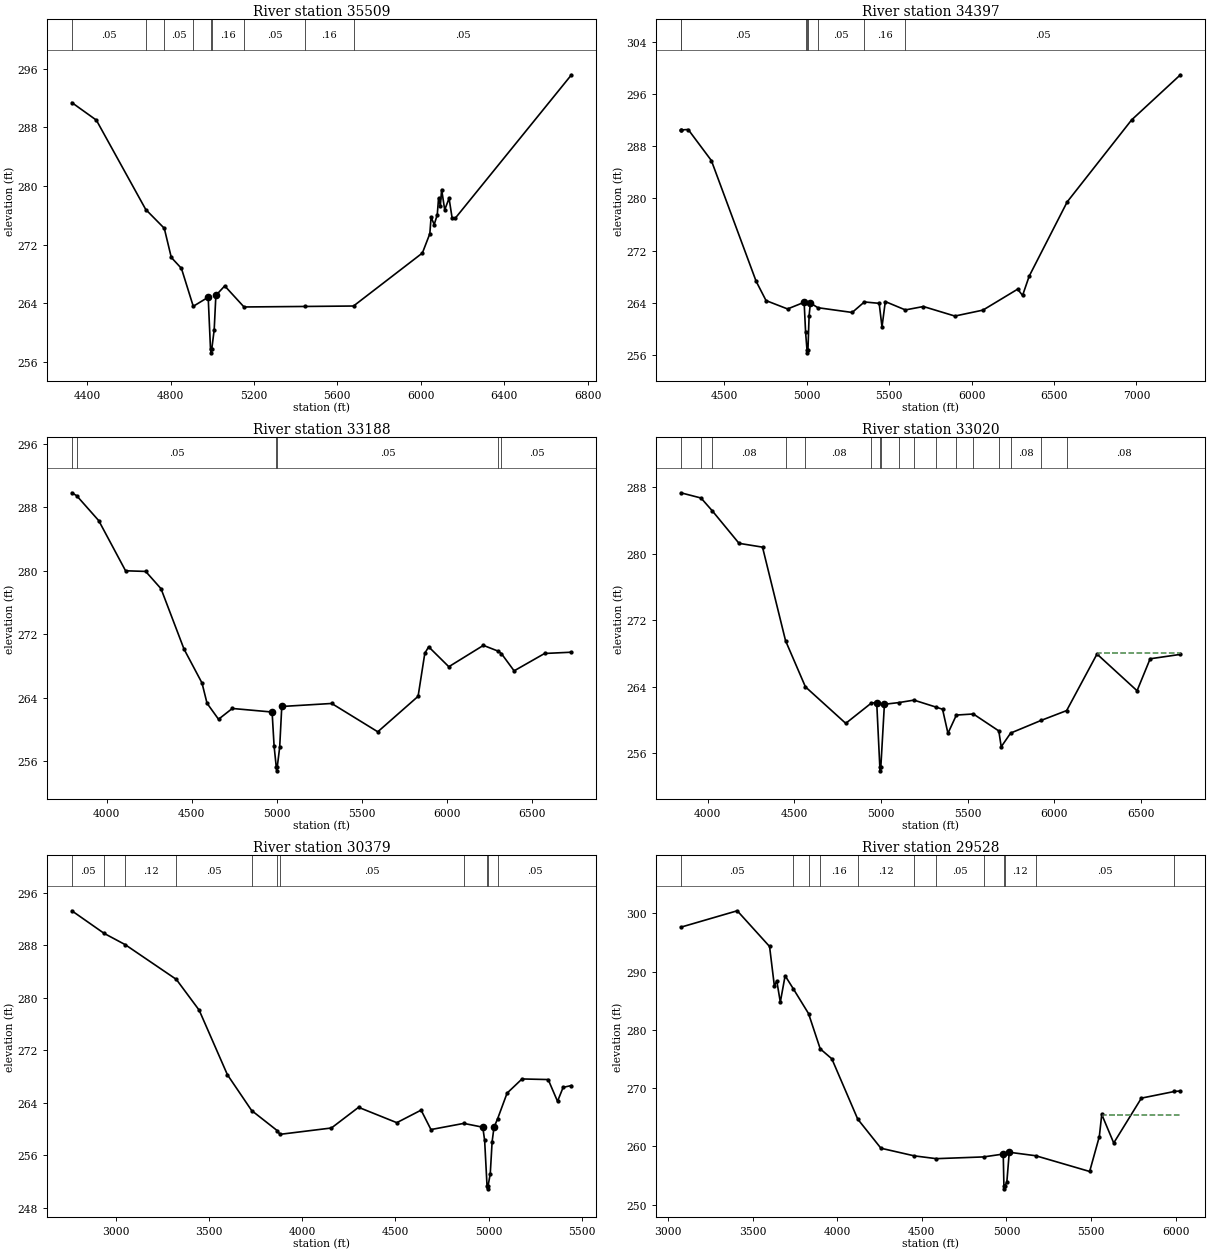
Type RM Length L Ch R = 1 ,35509   ,1112,1112,1112
BEGIN DESCRIPTION:
SHEPHERD CREEK 33.0
END DESCRIPTION:
XS GIS Cut Line= 3
      3608642.08     10314741.65      3608135.98     10314942.04
      3607067.36     10316454.85
#Sta/Elev= 30
  4326.6  291.36  4444.2  288.97  4681.1  276.79    4770  274.23  4803.6  270.26
  4852.2  268.77    4909   263.6  4980.6  264.84  4991.7  257.76  4994.4  257.26
  4997.7  257.76  5009.4  260.41  5017.4  265.08  5059.9  266.38  5152.4  263.51
  5444.1  263.58  5677.6  263.64  6007.9  270.86  6043.6  273.49  6049.7  275.76
  6064.5  274.74  6079.3  276.07  6085.4  278.31  6094.1   277.3  6100.2  279.51
    6115  276.75  6135.9  278.32  6150.7   275.6  6165.5   275.6  6723.1  295.15
#Mann= 9 ,-1 , 0
  4326.6     .05       0  4681.1     .16       0    4770     .05       0
    4909     .16       0  4991.7     .07       0  4997.7     .16       0
  5152.4     .05       0  5444.1     .16       0  5677.6     .05       0
Bank Sta=4980.6,5017.4
XS Rating Curve= 0 ,0
Exp/Cntr=0.3,0.1

Type RM Length L Ch R = 1 ,34397   ,1209,1209,1209
BEGIN DESCRIPTION:
SHEPHERD CREEK 32.0
END DESCRIPTION:
XS GIS Cut Line= 3
      3608386.86     10314670.11      3606781.74     10314826.55
      3605366.51     10314913.13
#Sta/Elev= 30
  4235.9   290.5  4236.1   290.5  4280.9  290.57  4421.5  285.81  4692.8  267.31
  4753.1  264.34  4883.7  263.06  4984.2  264.08    4993  259.46  5001.3  256.83
    5004  256.33  5007.3  256.83  5014.3  262.02  5022.1  263.97  5067.4  263.25
  5275.6  262.52  5349.4  264.13  5439.3  263.92  5456.4   260.3  5476.5  264.19
    5598  262.91  5707.6  263.43  5898.4  261.97  6068.7  262.88  6279.1  266.09
  6309.1  265.13  6349.2  268.09  6579.6  279.47  6970.4  292.04  7266.5  298.96
#Mann= 8 ,-1 , 0
  4235.9     .08       0  4236.1     .05       0    4993     .16       0
  5001.3     .07       0  5007.3     .16       0  5067.4     .05       0
  5349.4     .16       0    5598     .05       0
Bank Sta=4984.2,5022.1
XS Rating Curve= 0 ,0
Exp/Cntr=0.3,0.1

Type RM Length L Ch R = 1 ,33188   ,168,168,168
BEGIN DESCRIPTION:
SHEPHERD CREEK 31.0
END DESCRIPTION:
XS GIS Cut Line= 3
      3608359.09     10314565.97      3607277.54     10314037.61
      3605720.11      10313281.2
#Sta/Elev= 30
  3796.3  289.83  3824.8  289.46  3954.3  286.32  4111.9     280  4230.1  279.92
  4320.2  277.74  4455.3  270.13  4560.9  265.86  4590.4  263.31    4658  261.29
  4738.9  262.65  4972.7   262.2  4984.4  257.91    4997  255.29  4999.8  254.79
    5003  255.29  5017.2  257.75  5029.5   262.9  5322.8  263.28  5593.5  259.71
  5830.3  264.18  5869.8  269.61  5892.4  270.42  6010.8  267.91  6213.8   270.6
  6298.7  269.89  6319.5  269.57  6394.3  267.39  6573.5  269.58  6731.4  269.74
#Mann= 6 ,-1 , 0
  3796.3     .08       0  3824.8     .05       0    4997     .04       0
    5003     .05       0  6298.7     .08       0  6319.5     .05       0
Bank Sta=4972.7,5029.5
XS Rating Curve= 0 ,0
Exp/Cntr=0.3,0.1

Type RM Length L Ch R = 1 ,33020   ,2641,2641,2641
BEGIN DESCRIPTION:
SHEPHERD CREEK 30.0
END DESCRIPTION:
XS GIS Cut Line= 3
      3608400.67     10314392.31      3607359.49     10313890.04
      3605804.79     10313136.02
#Sta/Elev= 30
    3844  287.34  3960.7  286.71  4025.3  285.18  4180.2  281.25  4315.8  280.79
  4448.7  269.52  4563.4  263.96  4796.2  259.56  4944.8  262.02  4974.9  262.06
  4992.8  254.34  4995.5  253.84  4998.8  254.34  5019.3  261.86  5101.7  262.06
  5189.9  262.36  5317.1  261.52  5354.9  261.26  5386.1  258.36  5434.7  260.56
  5532.6  260.69  5679.6  258.65  5693.5  256.74    5748  258.39  5924.4  259.92
  6071.2   261.1  6246.3  267.91  6477.6  263.49  6553.1  267.34  6727.9  267.87
#Mann= 17 ,-1 , 0
    3844     .08       0  3960.7     .05       0  4025.3     .08       0
  4448.7     .05       0  4563.4     .08       0  4944.8     .05       0
  4992.8     .04       0  4998.8     .05       0  5101.7     .08       0
  5189.9     .05       0  5317.1     .08       0  5434.7     .05       0
  5532.6     .08       0  5679.6     .05       0    5748     .08       0
  5924.4     .05       0  6071.2     .08       0
#XS Ineff= 2 , 0
                         6254.26          268.07
Permanent Ineff=
       F       F
Bank Sta=4974.9,5019.3
XS Rating Curve= 0 ,0
Exp/Cntr=0.3,0.1

Type RM Length L Ch R = 1 ,30379   ,851,851,851
BEGIN DESCRIPTION:
SHEPHERD CREEK 29.0
END DESCRIPTION:
XS GIS Cut Line= 3
      3608240.98     10312128.45      3606879.88      10312996.5
      3605817.39     10313065.94
#Sta/Elev= 30
  2765.3  293.24  2938.8  289.79  3050.9  288.09  3325.5  282.79    3448   278.1
  3599.5  268.26  3729.4  262.81    3867  259.74  3880.8  259.18  4157.2  260.15
  4302.7   263.3  4507.7  260.96    4638  262.87  4690.8  259.91  4866.9  260.85
  4968.7  260.27  4978.7  258.26  4991.4  251.38  4994.2  250.88  4997.4  251.38
  5008.8  253.16  5018.8  258.06  5028.8  260.24  5047.8  261.52    5099  265.46
  5179.1  267.62  5319.4  267.53  5369.5  264.21  5399.6  266.34  5444.4  266.62
#Mann= 11 ,-1 , 0
  2765.3     .05       0  2938.8     .16       0  3050.9     .12       0
  3325.5     .05       0  3729.4     .16       0    3867     .12       0
  3880.8     .05       0  4866.9     .16       0  4991.4     .07       0
  4997.4     .16       0  5047.8     .05       0
Bank Sta=4968.7,5028.8
XS Rating Curve= 0 ,0
Exp/Cntr=0.3,0.1

Type RM Length L Ch R = 1 ,29528   ,1298,1298,1298
BEGIN DESCRIPTION:
SHEPHERD CREEK 25.0
END DESCRIPTION:
XS GIS Cut Line= 3
      3607595.19     10310913.13      3606463.21      10312121.5
      3605470.18     10312954.81
#Sta/Elev= 30
  3075.9  297.61  3409.5  300.43  3600.5   294.3  3628.9  287.51    3643  288.41
    3664  284.75  3692.4  289.28  3739.9  287.08  3830.7  282.79  3899.8  276.73
  3968.4  275.02  4121.4  264.67  4258.5  259.67  4455.6  258.36  4585.6  257.88
  4865.2  258.18  4981.1  258.67  4985.1   253.2  4987.9   252.7  4991.1   253.2
  5002.4  253.88  5016.7  258.98  5173.3  258.38  5491.6  255.68  5548.8  261.67
  5563.1  265.47  5633.9  260.57  5797.3  268.27    5992  269.41    6028   269.5
#Mann= 12 ,-1 , 0
  3075.9     .05       0  3739.9     .16       0  3830.7     .05       0
  3899.8     .16       0  4121.4     .12       0  4455.6     .16       0
  4585.6     .05       0  4865.2     .12       0  4985.1     .07       0
  4991.1     .12       0  5173.3     .05       0    5992     .08       0
#XS Ineff= 2 , 0
                         5569.32          265.39
Permanent Ineff=
       F       F
Bank Sta=4981.1,5016.7
XS Rating Curve= 0 ,0
Exp/Cntr=0.3,0.1

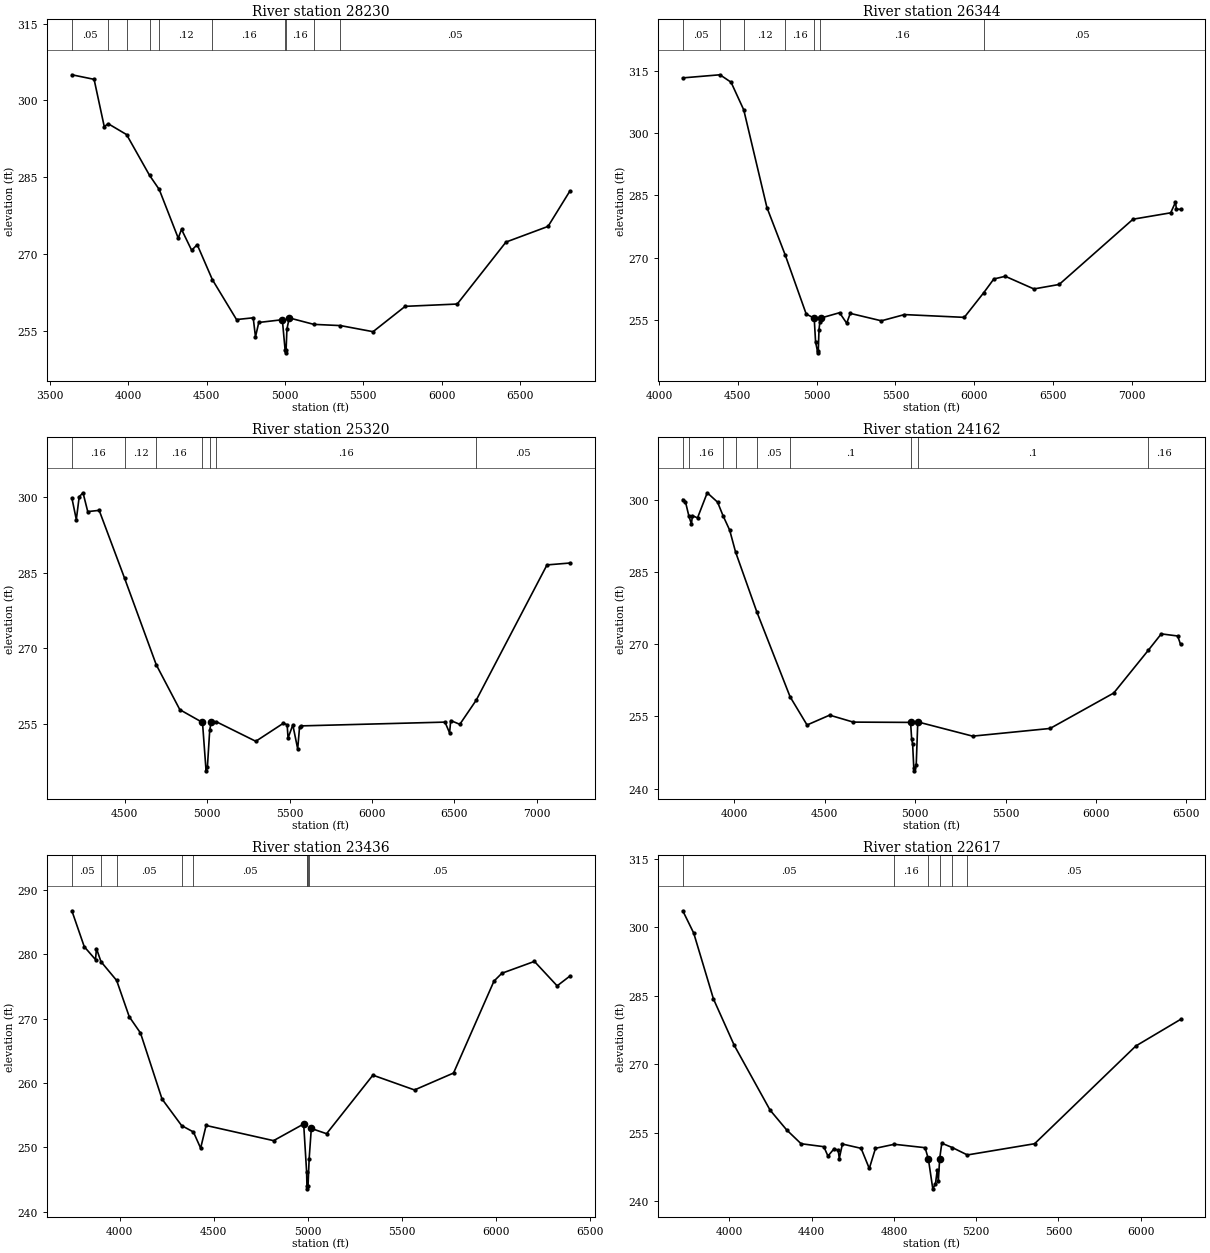
Type RM Length L Ch R = 1 ,28230   ,1886,1886,1886
BEGIN DESCRIPTION:
SHEPHERD CREEK 24.0
END DESCRIPTION:
XS GIS Cut Line= 3
       3607372.9     10310593.74      3605865.99     10311697.89
      3604936.24      10312620.7
#Sta/Elev= 30
  3639.4     305  3781.3  304.11  3846.1  294.89  3871.6  295.44  3988.7  293.32
  4135.2  285.37  4197.2   282.6  4318.6  273.09  4339.4  274.82  4404.2  270.73
  4439.8  271.82  4536.5  264.99  4690.6   257.2  4797.2  257.54  4811.8  253.82
  4832.7  256.63  4983.2  257.17  5001.1   251.2  5003.8   250.7  5007.1   251.2
  5012.5  255.32  5027.2  257.52  5184.1  256.26  5354.5  256.02  5562.4  254.83
  5767.5  259.78  6099.8  260.23    6411  272.33  6679.7  275.39  6817.5  282.21
#Mann= 10 ,-1 , 0
  3639.4     .05       0  3871.6     .16       0  3988.7     .12       0
  4135.2     .16       0  4197.2     .12       0  4536.5     .16       0
  5001.1     .07       0  5007.1     .16       0  5184.1     .12       0
  5354.5     .05       0
Bank Sta=4983.2,5027.2
XS Rating Curve= 0 ,0
Exp/Cntr=0.3,0.1

Type RM Length L Ch R = 1 ,26344   ,1024,1024,1024
BEGIN DESCRIPTION:
SHEPHERD CREEK 23.0
END DESCRIPTION:
XS GIS Cut Line= 3
      3606990.97     10310225.67      3605629.88     10310982.61
      3604762.84     10312328.26
#Sta/Elev= 30
  4150.4  313.34  4386.3  314.09  4456.7   312.3  4537.4  305.62  4684.3   282.1
  4800.5  270.64  4933.6  256.42  4984.4  255.42    4993  249.71    5007  247.07
  5010.3  247.57  5014.8  252.65  5020.5   254.6  5030.2   255.5  5145.2  256.74
  5190.4  254.21  5213.2  256.58  5410.5  254.79  5556.9  256.29  5936.6  255.62
  6060.7   261.6    6124  264.87  6196.7  265.52  6378.2  262.47  6538.6  263.55
  7007.3  279.28  7246.3  280.82  7276.6  283.38  7282.6  281.73  7308.6  281.64
#Mann= 7 ,-1 , 0
  4150.4     .05       0  4386.3     .16       0  4537.4     .12       0
  4800.5     .16       0  4984.4     .07       0  5020.5     .16       0
  6060.7     .05       0
Bank Sta=4984.4,5030.2
XS Rating Curve= 0 ,0
Exp/Cntr=0.3,0.1

Type RM Length L Ch R = 1 ,25320   ,1158,1158,1158
BEGIN DESCRIPTION:
SHEPHERD CREEK 22.0
END DESCRIPTION:
XS GIS Cut Line= 3
      3606595.13     10309677.07      3605379.88     10310225.67
      3603747.94     10310663.16
#Sta/Elev= 30
  4178.1  299.89  4205.1  295.59  4222.7  300.13  4245.9  300.91  4274.5  297.17
  4343.9  297.42  4498.5  283.91  4690.6  266.74  4833.8  257.82  4971.4  255.28
  4993.1  245.67  5001.1  246.37  5015.3  253.76  5024.2  255.33  5053.7  255.45
  5295.1  251.54  5462.4  255.12  5485.5  254.83    5491  252.18  5519.9  254.79
  5549.6  250.02  5560.9  254.39  5571.3   254.6  6444.1  255.35    6472  253.21
  6478.9  255.66  6534.1  254.91  6633.8  259.71  7063.6  286.58    7201  286.95
#Mann= 7 ,-1 , 0
  4178.1     .16       0  4498.5     .12       0  4690.6     .16       0
  4971.4     .07       0  5015.3     .12       0  5053.7     .16       0
  6633.8     .05       0
Bank Sta=4971.4,5024.2
XS Rating Curve= 0 ,0
Exp/Cntr=0.3,0.1

Type RM Length L Ch R = 1 ,24162   ,726,726,726
BEGIN DESCRIPTION:
SHEPHERD CREEK 21.0
END DESCRIPTION:
XS GIS Cut Line= 3
      3606352.09     10309322.89      3605254.88     10309642.33
      3603706.93     10310086.59
#Sta/Elev= 30
  3714.5  300.14    3729  299.72  3748.3   296.7  3762.5  295.02  3767.7  296.79
    3796  296.31  3849.9  301.54    3907  299.59  3937.2  296.77    3974  293.76
  4006.5  289.22  4123.5  276.82  4308.1  259.09  4401.9  253.22  4526.9  255.27
  4657.5  253.82  4974.6  253.76  4980.7  250.22  4985.9  249.28  4992.4  244.18
  4995.1  243.68  5005.8  244.94  5014.4  253.86  5317.9   250.9  5746.3   252.5
  6098.2  259.87  6288.6  268.73  6361.3  272.18  6451.9  271.74  6467.7     270
#Mann= 9 ,-1 , 0
  3714.5     .05       0  3748.3     .16       0  3937.2     .05       0
  4006.5     .16       0  4123.5     .05       0  4308.1      .1       0
  4974.6     .07       0  5014.4      .1       0  6288.6     .16       0
Bank Sta=4974.6,5014.4
XS Rating Curve= 0 ,0
Exp/Cntr=0.3,0.1

Type RM Length L Ch R = 1 ,23436   ,819,819,819
BEGIN DESCRIPTION:
SHEPHERD CREEK 20.0
END DESCRIPTION:
XS GIS Cut Line= 3
      3606227.06     10308864.56      3604497.93     10309163.17
       3603629.9     10309371.49
#Sta/Elev= 30
  3746.2  286.79  3812.1  281.21  3871.9   279.2    3877  280.91  3901.1  278.88
  3984.4  275.96  4051.4  270.32  4111.2  267.79  4225.8  257.53    4330   253.4
  4392.7  252.41  4431.1  249.89  4460.1  253.42    4819  251.06  4979.1  253.65
  4994.7  246.22  4996.4  244.07  4999.2  243.57  5002.4  244.07  5008.2  248.23
  5019.7  252.95  5100.9  252.14  5347.3  261.24  5568.6  258.94  5776.2  261.57
  5991.3  275.86  6033.3  277.08  6206.4  278.92  6327.2  275.12  6393.6  276.61
#Mann= 9 ,-1 , 0
  3746.2     .05       0  3901.1     .16       0  3984.4     .05       0
    4330     .16       0  4392.7     .05       0  4994.7     .16       0
  4996.4     .07       0  5002.4     .16       0  5008.2     .05       0
Bank Sta=4979.1,5019.7
XS Rating Curve= 0 ,0
Exp/Cntr=0.3,0.1

Type RM Length L Ch R = 1 ,22617   ,573,573,573
BEGIN DESCRIPTION:
SHEPHERD CREEK 18.0
END DESCRIPTION:
XS GIS Cut Line= 3
      3606104.57     10308221.86      3604892.11     10308341.64
      3603720.17     10308607.61
#Sta/Elev= 30
  3773.4  303.63  3826.6  298.74  3922.7  284.29  4023.8  274.12  4197.9  259.93
  4278.3   255.6  4348.6  252.56  4459.2  251.91  4479.3  249.85  4509.4  251.48
  4529.3   251.1  4534.3  249.32  4549.6  252.49  4640.4  251.55  4680.3  247.13
  4710.4  251.56  4801.9  252.44  4951.6  251.69  4967.7  249.18    4989  242.67
    5002  243.76  5010.8  246.86  5015.9  244.37  5022.5  249.31  5032.8  252.67
  5083.9  251.72  5157.1   250.1    5484  252.56  5976.2  273.99  6193.5  279.81
#Mann= 6 ,-1 , 0
  3773.4     .05       0  4801.9     .16       0  4967.7     .07       0
  5022.5     .05       0  5083.9     .16       0  5157.1     .05       0
Bank Sta=4967.7,5022.5
XS Rating Curve= 0 ,0
Exp/Cntr=0.3,0.1

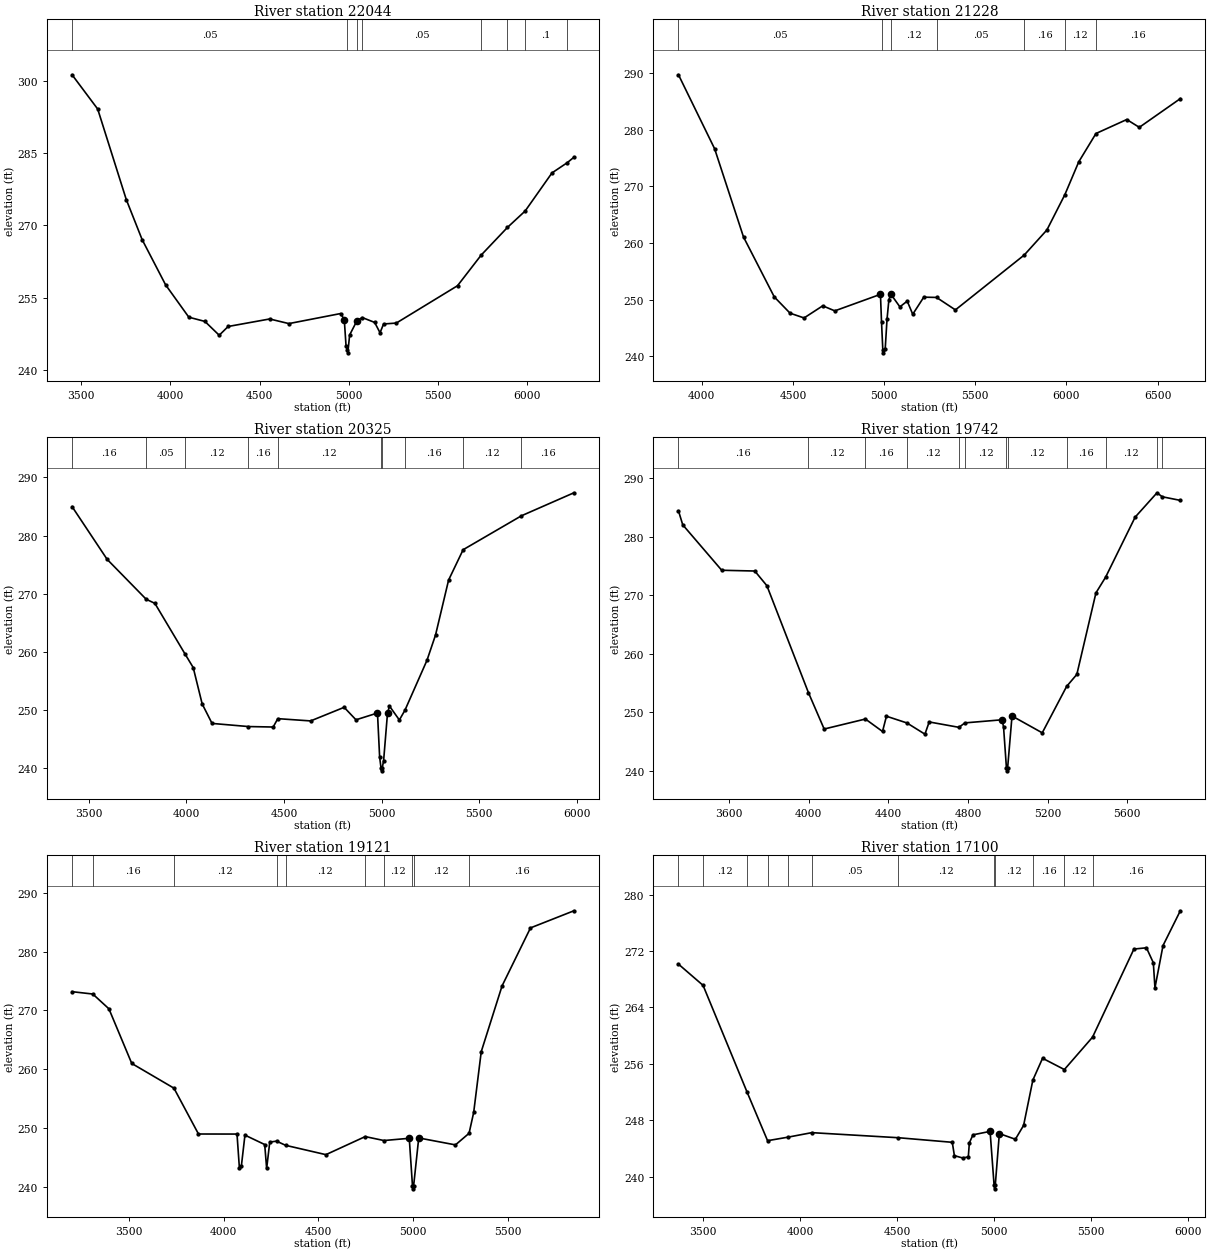
Type RM Length L Ch R = 1 ,22044   ,816,816,816
BEGIN DESCRIPTION:
SHEPHERD CREEK 17.0
END DESCRIPTION:
XS GIS Cut Line= 3
      3606185.47     10307774.27      3604220.15     10307885.39
      3603379.83     10307802.05
#Sta/Elev= 30
  3448.7  301.24  3592.3  294.13  3752.5  275.34  3841.3  267.03  3972.9  257.64
  4103.1  250.92  4193.3  250.04  4273.4  247.17  4323.5  248.99  4556.2  250.55
    4664  249.59  4954.5  251.68  4974.5  250.38  4984.5  244.85  4991.5  244.02
  4994.3  243.52  5004.5  247.23  5044.6  250.12  5074.9  250.85  5144.8  249.83
  5174.8  247.69  5194.8  249.51  5266.1   249.7  5609.1  257.45  5742.3  263.83
  5889.2  269.56    5988  272.95  6138.7  280.87  6223.8  282.98  6261.6  284.12
#Mann= 8 ,-1 , 0
  3448.7     .05       0  4991.5     .07       0  5044.6     .05       0
  5074.9     .05       0  5742.3     .12       0  5889.2     .16       0
    5988      .1       0  6223.8     .16       0
Bank Sta=4974.5,5044.6
XS Rating Curve= 0 ,0
Exp/Cntr=0.3,0.1

Type RM Length L Ch R = 1 ,21228   ,903,903,903
BEGIN DESCRIPTION:
SHEPHERD CREEK 16.0
END DESCRIPTION:
XS GIS Cut Line= 3
      3606067.38     10307420.11      3604581.26     10307239.55
      3603342.11     10307041.64
#Sta/Elev= 30
  3872.5  289.72  4070.7  276.66  4229.1  261.08  4397.7  250.51  4484.4  247.63
  4561.2  246.79  4663.5  248.93  4729.7  248.04    4980  250.96  4985.9   246.1
    4993  241.13  4995.7  240.63    5006  241.26  5016.1  246.57  5026.2  249.96
  5036.3  251.02  5086.6  248.75  5126.9  249.76  5157.1  247.44  5217.6  250.46
  5287.7  250.41    5391  248.21  5768.6   257.9  5892.7  262.32  5991.2  268.55
  6067.4  274.35  6161.8  279.35  6330.7  281.82  6399.5  280.44  6624.4  285.51
#Mann= 7 ,-1 , 0
  3872.5     .05       0  4985.9     .07       0  5036.3     .12       0
  5287.7     .05       0  5768.6     .16       0  5991.2     .12       0
  6161.8     .16       0
Bank Sta=4980,5036.3
XS Rating Curve= 0 ,0
Exp/Cntr=0.3,0.1

Type RM Length L Ch R = 1 ,20325   ,583,583,583
BEGIN DESCRIPTION:
SHEPHERD CREEK 14.0
END DESCRIPTION:
XS GIS Cut Line= 3
      3606042.06     10306891.64      3603894.88     10306594.42
      3603496.03     10306544.56
#Sta/Elev= 30
  3415.5  284.99  3594.9  275.92  3794.9  269.05  3839.5  268.34  3993.3  259.66
  4035.8  257.29  4081.7  251.03  4132.2  247.68  4318.7  247.14  4445.2  247.06
  4468.9   248.5    4637  248.11  4808.6  250.45  4869.2   248.3  4979.3  249.47
  4990.3  241.88  4997.4  240.02  5000.2  239.52  5003.4  240.02  5010.5   241.2
  5030.7  249.49  5040.8  250.66  5091.3  248.27  5119.9  249.95  5232.6  258.53
  5276.6   262.9  5343.4  272.35  5417.8  277.57  5716.4  283.41  5985.1  287.37
#Mann= 10 ,-1 , 0
  3415.5     .16       0  3794.9     .05       0  3993.3     .12       0
  4318.7     .16       0  4468.9     .12       0  4997.4     .07       0
  5003.4     .12       0  5119.9     .16       0  5417.8     .12       0
  5716.4     .16       0
Bank Sta=4979.3,5030.7
XS Rating Curve= 0 ,0
Exp/Cntr=0.3,0.1

Type RM Length L Ch R = 1 ,19742   ,621,621,621
BEGIN DESCRIPTION:
SHEPHERD CREEK 13.0
END DESCRIPTION:
XS GIS Cut Line= 3
      3605992.14     10306741.65      3604247.93     10306093.72
      3603602.13     10305961.78
#Sta/Elev= 30
  3346.8  284.42  3368.2  282.03  3563.9  274.26    3730  274.13  3790.7  271.62
  3999.1  253.35  4078.3  247.11  4285.3  248.82  4371.3  246.69    4391   249.3
  4493.8  248.15  4584.3  246.23  4605.6  248.32  4755.1   247.4  4784.9  248.16
  4971.5  248.69    4979  247.47  4993.5  240.46  4996.3  239.96  4999.5  240.46
  5021.5  249.34  5173.3  246.46  5295.8   254.4    5347  256.45  5442.9  270.39
  5491.8   273.1  5639.7  283.34  5749.6  287.51  5775.5  286.83  5866.6  286.21
#Mann= 12 ,-1 , 0
  3346.8     .16       0  3999.1     .12       0  4285.3     .16       0
  4493.8     .12       0  4755.1     .16       0  4784.9     .12       0
  4993.5     .07       0  4999.5     .12       0  5295.8     .16       0
  5491.8     .12       0  5749.6     .16       0  5775.5     .12       0
Bank Sta=4971.5,5021.5
XS Rating Curve= 0 ,0
Exp/Cntr=0.3,0.1

Type RM Length L Ch R = 1 ,19121   ,2021,2021,2021
BEGIN DESCRIPTION:
SHEPHERD CREEK 12.0
END DESCRIPTION:
XS GIS Cut Line= 3
      3606241.02     10305392.32      3605143.76     10305656.22
       3603622.9     10305690.94
#Sta/Elev= 30
  3200.2  273.18  3309.6  272.78  3394.7  270.27  3515.4  260.98  3738.1  256.78
  3867.6  248.99  4071.1  248.98  4083.6  243.24  4093.9  243.49    4113   248.8
  4217.3   247.2  4227.6  243.13    4244  247.61  4279.8  247.78  4327.3  247.07
  4540.5  245.48    4748  248.55  4846.9  247.88  4980.6  248.26  4997.6  240.17
  5000.3  239.67  5003.6  240.17  5030.6  248.32  5224.5  247.14  5296.4  249.11
  5320.7  252.65  5360.7  262.99  5470.7  274.17  5620.7  284.02    5850  286.93
#Mann= 10 ,-1 , 0
  3200.2      .1       0  3309.6     .16       0  3738.1     .12       0
  4279.8      .1       0  4327.3     .12       0    4748     .16       0
  4846.9     .12       0  4997.6     .07       0  5003.6     .12       0
  5296.4     .16       0
Bank Sta=4980.6,5030.6
XS Rating Curve= 0 ,0
Exp/Cntr=0.3,0.1

Type RM Length L Ch R = 1 ,17100   ,821,821,821
BEGIN DESCRIPTION:
SHEPHERD CREEK 11.0
END DESCRIPTION:
XS GIS Cut Line= 3
      3606456.24     10305246.49      3604528.22     10304451.36
      3604128.26     10304151.39
#Sta/Elev= 30
  3373.2  270.14  3499.9  267.13  3727.1  251.96  3832.2   245.1  3937.4   245.6
    4060  246.24  4506.2  245.52  4783.8  244.87  4794.7  242.98  4837.1  242.65
  4866.4   242.8  4871.8  244.79  4890.4  245.93  4978.6  246.42  4999.3  238.77
  5002.1  238.27  5005.3  238.77  5026.3  246.11  5108.9   245.3  5151.3  247.27
    5199   253.7    5249  256.79  5361.3  255.19  5506.4  259.78  5719.6  272.28
  5784.2  272.46  5819.6  270.34    5828  266.78  5869.6  272.78  5958.7  277.71
#Mann= 12 ,-1 , 0
  3373.2     .16       0  3499.9     .12       0  3727.1     .05       0
  3832.2     .12       0  3937.4     .16       0    4060     .05       0
  4506.2     .12       0  4999.3     .07       0  5005.3     .12       0
    5199     .16       0  5361.3     .12       0  5506.4     .16       0
Bank Sta=4978.6,5026.3
XS Rating Curve= 0 ,0
Exp/Cntr=0.3,0.1

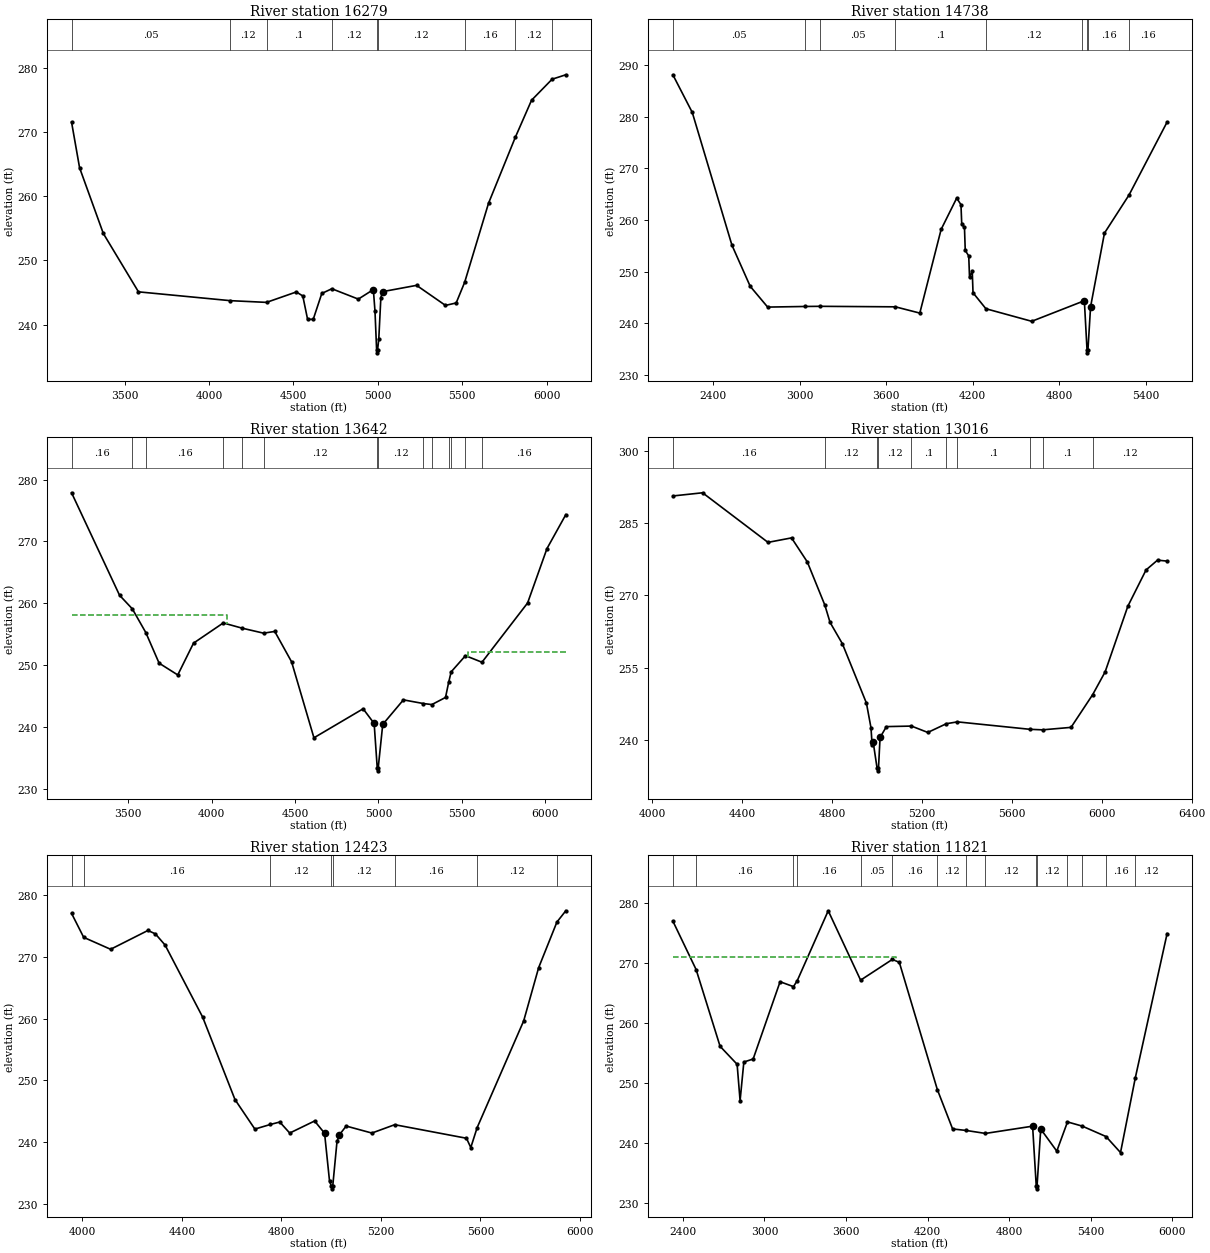
Type RM Length L Ch R = 1 ,16279   ,1541,1541,1541
BEGIN DESCRIPTION:
SHEPHERD CREEK 10.0
END DESCRIPTION:
XS GIS Cut Line= 3
      3606997.91     10304878.43      3605053.49     10303927.05
      3604305.29     10303777.42
#Sta/Elev= 30
  3185.9  271.51  3233.4  264.42    3374   254.2  3582.2  245.12    4125  243.75
  4340.7  243.48  4517.2   245.1  4555.6  244.48    4584  240.85  4617.4  240.84
  4668.2  244.87  4727.7   245.6  4884.5  243.99  4973.6  245.47  4983.3   242.1
  4992.9  236.13  4995.6  235.63  4998.9  236.13  5005.8  237.81  5018.1  244.23
  5028.3  245.15  5229.7  246.13  5400.8  243.01  5464.2  243.39  5514.4   246.6
  5655.7  258.89  5814.2  269.14  5910.7  274.93  6032.4   278.2  6113.6  278.89
#Mann= 9 ,-1 , 0
  3185.9     .05       0    4125     .12       0  4340.7      .1       0
  4727.7     .12       0  4992.9     .07       0  4998.9     .12       0
  5514.4     .16       0  5814.2     .12       0  6032.4     .16       0
Bank Sta=4973.6,5028.3
XS Rating Curve= 0 ,0
Exp/Cntr=0.3,0.1

Type RM Length L Ch R = 1 ,14738   ,1096,1096,1096
BEGIN DESCRIPTION:
SHEPHERD CREEK 9.0
END DESCRIPTION:
XS GIS Cut Line= 3
      3607532.67     10304156.23      3604732.38     10303040.25
      3604332.36     10302940.25
#Sta/Elev= 30
  2120.9  288.09  2255.4  280.81  2530.6  255.12  2657.2  247.17  2778.2  243.15
  3038.6  243.27  3141.7   243.3  3664.1   243.2  3833.1  241.99    3981  258.18
  4088.9  264.23  4118.5  262.96  4123.9  259.16  4142.8   258.6  4148.2  254.12
  4172.4  253.04  4177.8  248.93  4196.7  250.12  4202.1  245.92  4291.5  242.83
  4609.2   240.4  4960.1  244.23  4974.2  244.27  4992.7   234.8  4995.5   234.3
  4998.7   234.8  5017.2  243.22  5113.4  257.46  5283.9  264.84  5547.7  278.94
#Mann= 9 ,-1 , 0
  2120.9     .05       0  3038.6      .1       0  3141.7     .05       0
  3664.1      .1       0  4291.5     .12       0  4960.1     .16       0
  4992.7     .07       0  4998.7     .16       0  5283.9     .16       0
Bank Sta=4974.2,5017.2
XS Rating Curve= 0 ,0
Exp/Cntr=0.3,0.1

Type RM Length L Ch R = 1 ,13642   ,626,626,626
BEGIN DESCRIPTION:
SHEPHERD CREEK 8.0
END DESCRIPTION:
XS GIS Cut Line= 3
      3607240.95      10302982.6      3604947.76     10302406.57
       3604352.1     10302357.61
#Sta/Elev= 30
  3160.8  277.86  3448.3  261.33    3525  259.13  3605.7  255.31  3685.5  250.37
  3797.3  248.47  3891.7   253.6  4069.9  256.86    4184  256.01  4311.6  255.21
  4378.5  255.49  4479.4  250.59  4613.4  238.33  4908.2  243.01  4974.3  240.64
  4992.7   233.5  4995.4     233  4998.7   233.5  5025.8  240.49  5149.6  244.45
    5269  243.86    5320  243.69    5402  244.84  5420.8  247.27  5435.8  248.97
  5521.7  251.58  5620.5  250.52  5893.9  260.08  6010.1  268.86  6122.9  274.33
#Mann= 14 ,-1 , 0
  3160.8     .16       0    3525     .12       0  3605.7     .16       0
  4069.9     .12       0    4184     .16       0  4311.6     .12       0
  4992.7     .07       0  4998.7     .12       0    5269     .16       0
    5320     .12       0  5420.8     .16       0  5435.8      .1       0
  5521.7     .12       0  5620.5     .16       0
#XS Ineff= 2 , 0
         4091.76  258.16  5537.5          252.15
Permanent Ineff=
       F       F
Bank Sta=4974.3,5025.8
XS Rating Curve= 0 ,0
Exp/Cntr=0.3,0.1

Type RM Length L Ch R = 1 ,13016   ,593,593,593
BEGIN DESCRIPTION:
SHEPHERD CREEK 6.0
END DESCRIPTION:
XS GIS Cut Line= 3
       3606699.3     10302093.73      3606185.43     10302239.55
      3604539.57     10301989.55
#Sta/Elev= 30
  4091.5  290.61  4223.7  291.27  4514.8     281  4619.5  281.93  4689.7  276.95
  4767.7  268.01  4790.9  264.43  4845.7  260.01  4952.7  247.72  4972.9  242.63
    4978  239.14    4983  239.57  5000.3  234.19    5003  233.69  5006.3  234.19
  5013.4   240.6  5041.6  242.85    5153  242.96  5225.8  241.64  5308.3  243.45
  5357.6  243.83  5680.1  242.29  5736.1  242.18    5863  242.69  5959.3  249.47
  6014.7  254.18  6115.9  267.79  6196.8  275.29  6247.8  277.32  6290.4  277.12
#Mann= 10 ,-1 , 0
  4091.5     .16       0  4767.7     .12       0  5000.3     .07       0
  5006.3     .12       0    5153      .1       0  5308.3     .12       0
  5357.6      .1       0  5680.1     .16       0  5736.1      .1       0
  5959.3     .12       0
Bank Sta=4983,5013.4
XS Rating Curve= 0 ,0
Exp/Cntr=0.3,0.1

Type RM Length L Ch R = 1 ,12423   ,602,602,602
BEGIN DESCRIPTION:
SHEPHERD CREEK 5.0
END DESCRIPTION:
XS GIS Cut Line= 3
      3606609.08     10301670.11      3605842.68     10301663.11
      3604622.98     10301711.77
#Sta/Elev= 30
  3956.3  276.99    4005  273.12  4113.3  271.19  4263.3  274.23  4293.3  273.68
  4332.2  271.88  4483.3  260.24  4613.3  246.92  4693.3  242.15  4755.8   242.9
  4793.4  243.29  4833.4  241.51  4933.5  243.46  4973.5  241.48  4993.5  233.74
  5000.5     233  5003.3   232.5  5006.5     233  5023.5  240.15  5033.5  241.24
  5060.3  242.64  5163.7  241.51  5255.6  242.86    5544  240.67  5561.4  239.17
    5587  242.39  5774.1  259.63  5834.2  268.22  5907.7  275.59  5943.4  277.41
#Mann= 8 ,-1 , 0
  3956.3     .12       0    4005     .16       0  4755.8     .12       0
  5000.5     .07       0  5006.5     .12       0  5255.6     .16       0
    5587     .12       0  5907.7     .16       0
Bank Sta=4973.5,5033.5
XS Rating Curve= 0 ,0
Exp/Cntr=0.3,0.1

Type RM Length L Ch R = 1 ,11821   ,1879,1879,1879
BEGIN DESCRIPTION:
SHEPHERD CREEK 4.0
END DESCRIPTION:
XS GIS Cut Line= 3
      3607900.35      10300029.3       3605289.6     10301454.83
      3604650.67     10301621.51
#Sta/Elev= 30
  2326.3  277.05  2497.5  268.96  2673.6  256.17  2798.9  253.17  2820.7   247.1
  2848.4  253.55  2916.8  254.05  3114.9  266.94  3213.4  266.12  3241.6  267.14
  3468.9  278.77  3707.1   267.2  3940.8  270.66  3991.8  270.17  4271.5  248.95
  4383.7  242.39  4485.1  242.13  4625.3  241.64  4972.1  242.85  4998.8   232.9
  5001.5   232.4  5004.8   232.9  5031.8  242.37  5149.9  238.69  5228.7  243.56
  5337.1  242.86  5512.1  241.12  5618.7  238.45  5727.6  250.93  5961.2  274.96
#Mann= 15 ,-1 , 0
  2326.3     .12       0  2497.5     .16       0  3213.4     .05       0
  3241.6     .16       0  3707.1     .05       0  3940.8     .16       0
  4271.5     .12       0  4485.1     .16       0  4625.3     .12       0
  4998.8     .07       0  5004.8     .12       0  5228.7     .16       0
  5337.1     .12       0  5512.1     .16       0  5727.6     .12       0
#XS Ineff= 2 , 0
         3970.45  271.11
Permanent Ineff=
       F       F
Bank Sta=4972.1,5031.8
XS Rating Curve= 0 ,0
Exp/Cntr=0.3,0.1

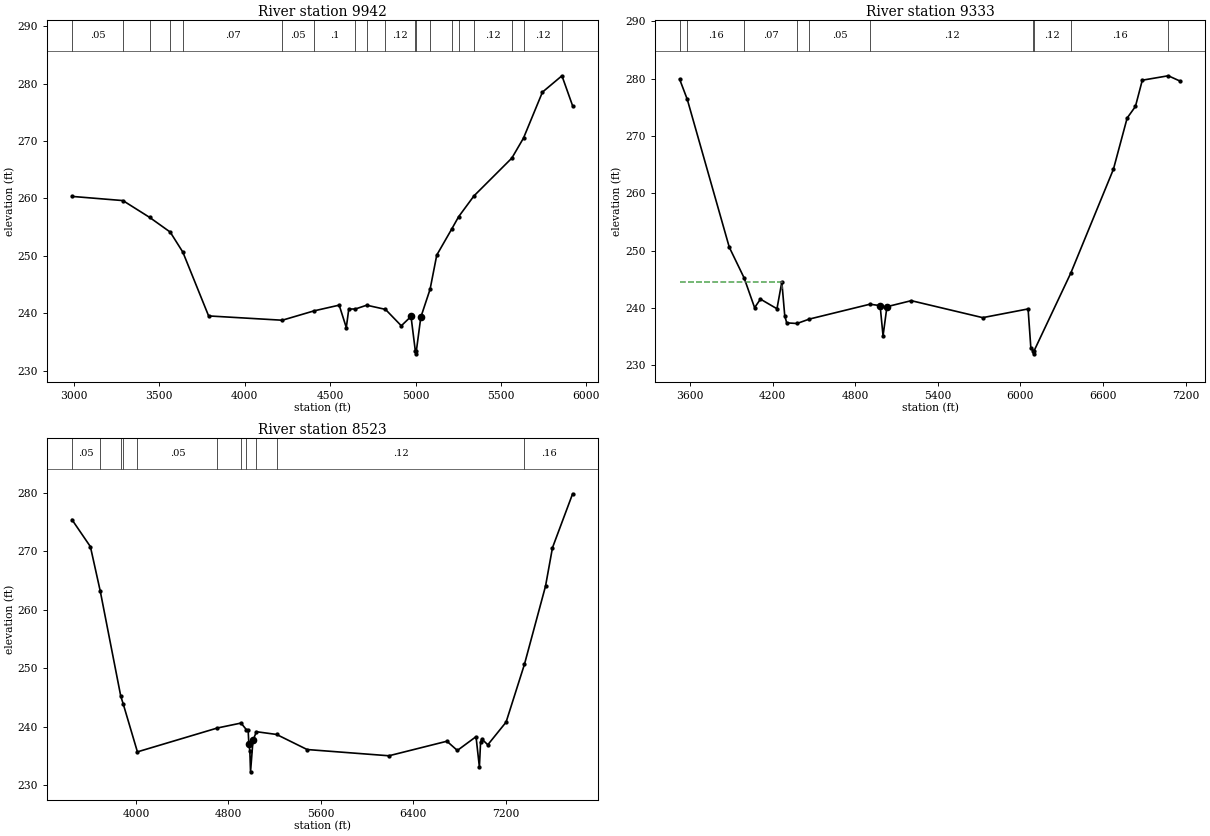
Type RM Length L Ch R = 1 ,9942    ,609,609,609
BEGIN DESCRIPTION:
SHEPHERD CREEK 3.0
END DESCRIPTION:
XS GIS Cut Line= 4
      3605780.99      10299285.2      3605596.02     10299699.62
      3604467.55     10301164.47      3604369.89     10301782.96
#Sta/Elev= 30
  2989.9  260.36  3288.4  259.63  3444.6   256.7    3565  254.14    3639  250.64
  3789.7  239.52  4220.4  238.77  4407.4  240.41  4553.5   241.4  4595.1  237.49
  4609.6  240.72  4648.1  240.73  4714.6  241.39  4824.2  240.66  4916.8   237.8
  4973.7  239.43  4998.9  233.41  5001.7  232.91  5004.9  233.41  5030.9  239.29
  5085.1  244.16  5124.3  250.13  5210.8  254.62  5252.2  256.82  5341.7  260.44
  5563.5  267.04  5631.7  270.53  5742.5  278.54  5856.5  281.39    5919  276.15
#Mann= 19 ,-1 , 0
  2989.9     .05       0  3288.4     .16       0  3444.6     .07       0
    3565     .16       0    3639     .07       0  4220.4     .05       0
  4407.4      .1       0  4648.1     .16       0  4714.6     .05       0
  4824.2     .12       0  4998.9     .07       0  5004.9     .12       0
  5085.1     .16       0  5210.8     .12       0  5252.2     .16       0
  5341.7     .12       0  5563.5     .16       0  5631.7     .12       0
  5856.5     .16       0
Bank Sta=4973.7,5030.9
XS Rating Curve= 0 ,0
Exp/Cntr=0.3,0.1

Type RM Length L Ch R = 1 ,9333    ,810,810,810
BEGIN DESCRIPTION:
SHEPHERD CREEK 2.0
END DESCRIPTION:
XS GIS Cut Line= 3
       3605400.7     10299450.07      3603968.42     10300925.75
      3603979.26     10302508.35
#Sta/Elev= 30
  3523.5   279.9  3579.1  276.38  3884.3  250.61  3992.3  245.25  4068.2  240.08
  4110.7  241.57  4230.8  239.89  4266.1  244.58  4287.4  238.65  4301.6  237.43
  4376.6  237.32  4465.8  238.09  4906.1  240.68  4980.4  240.44  5001.7  235.16
    5030  240.25  5206.7   241.3  5725.9  238.34  6055.9  239.86  6075.9  233.05
  6092.9  232.53  6095.6  232.03  6098.9  232.53    6366   246.1  6675.9  264.21
  6775.9  273.15  6835.9  275.16  6885.9  279.74  7074.5  280.51  7162.6  279.56
#Mann= 10 ,-1 , 0
  3523.5     .05       0  3579.1     .16       0  3992.3     .07       0
  4376.6      .1       0  4465.8     .05       0  4906.1     .12       0
  6092.9     .07       0  6098.9     .12       0    6366     .16       0
  7074.5      .1       0
#XS Ineff= 2 , 0
         4270.45  244.57
Permanent Ineff=
       F       F
Bank Sta=4980.4,5030
XS Rating Curve= 0 ,0
Exp/Cntr=0.3,0.1

Type RM Length L Ch R = 1 ,8523    ,0,0,0
BEGIN DESCRIPTION:
SHEPHERD CREEK 1.0
END DESCRIPTION:
XS GIS Cut Line= 3
       3604934.1     10299330.72      3603122.06     10300578.53
      3603328.22     10302705.25
#Sta/Elev= 30
    3444  275.46  3604.3  270.82  3689.6  263.21  3867.3  245.22  3888.3  243.91
  4011.5  235.69    4705  239.78    4909  240.62  4955.6  239.48  4970.5  239.38
  4976.6  237.12  4985.4  235.79  4991.2  232.27  5012.7  237.68  5042.2  239.14
  5216.7  238.67  5481.1  236.09  6189.8  235.02  6692.1  237.51  6782.5  235.93
  6944.2  238.29  6973.4  233.09  6983.5   237.3  6993.5   237.9  7046.2   236.9
  7204.5  240.78  7363.3  250.66  7546.1  264.06  7606.4  270.64  7780.8  279.87
#Mann= 11 ,-1 , 0
    3444     .05       0  3689.6      .1       0  3867.3     .07       0
  3888.3     .16       0  4011.5     .05       0    4705     .12       0
    4909     .16       0  4955.6     .07       0  5042.2     .16       0
  5216.7     .12       0  7363.3     .16       0
Bank Sta=4976.6,5012.7
XS Rating Curve= 0 ,0
Exp/Cntr=0.3,0.1

Chan Stop Cuts=-1
Use User Specified Reach Order=0
Composite Channel Slope=5