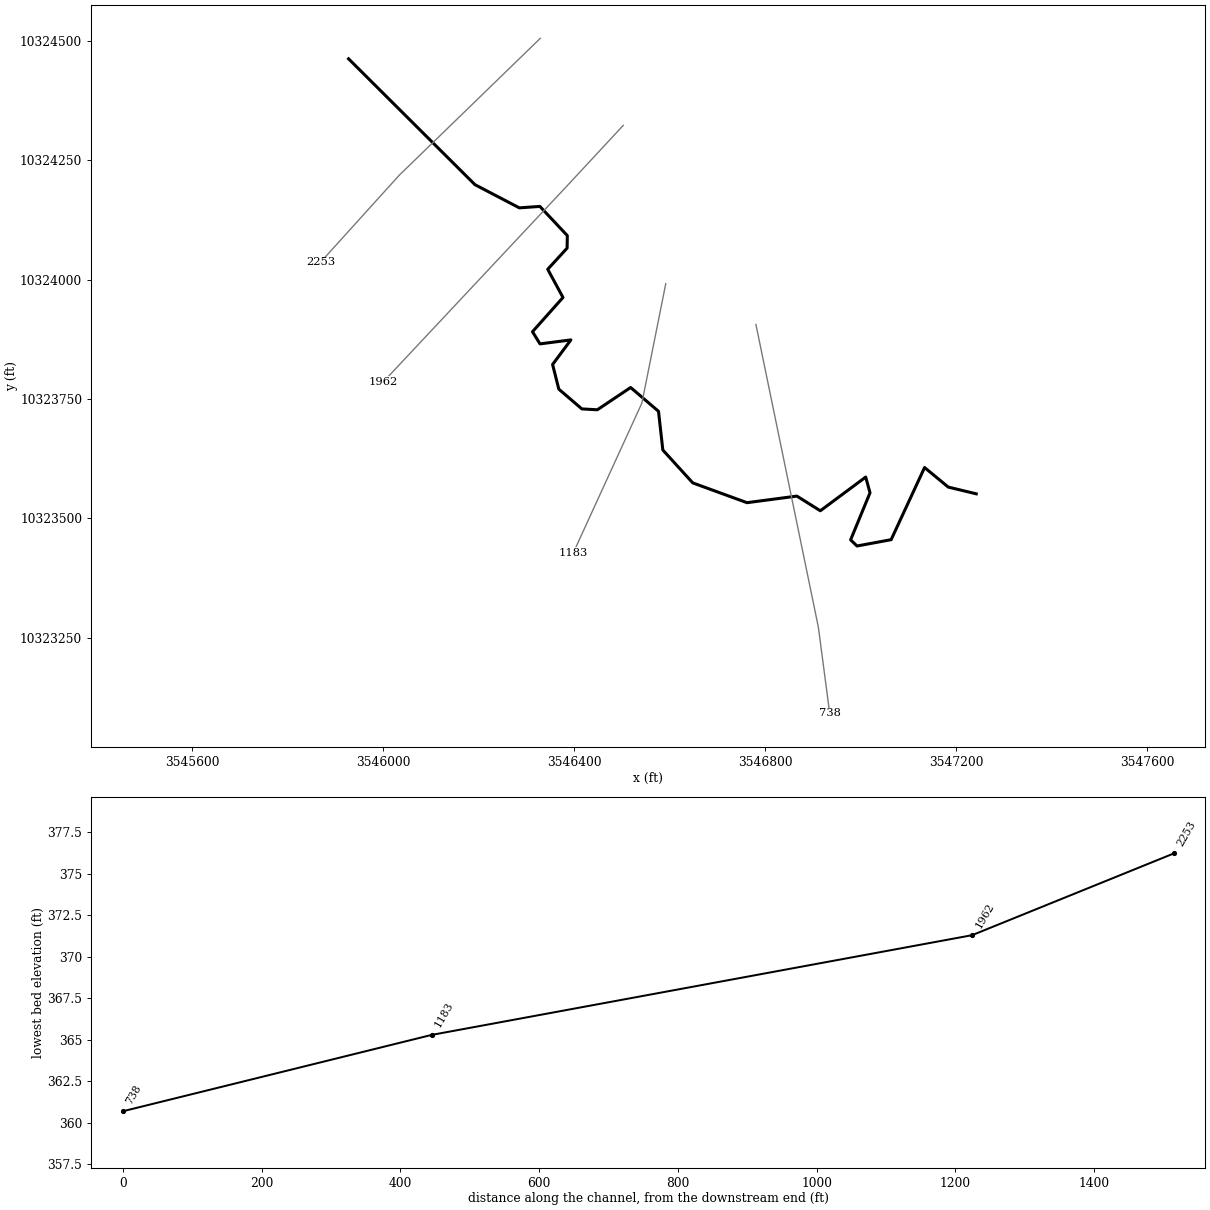
--- SMITH BRANCH TRIBUTARY 1 1.prj (project) ---

Proj Title=SMITH BRANCH TRIBUTARY 1 1 Base Level Engineering
Current Plan=p01
Default Exp/Contr=0.3,0.1
English Units
Geom File=g01
Flow File=f01
Plan File=p01
Y Axis Title=Elevation
X Axis Title(PF)=Main Channel Distance
X Axis Title(XS)=Station
BEGIN DESCRIPTION:
SMITH BRANCH TRIBUTARY 1 1
END DESCRIPTION:
DSS Export Rating Curves= 0
DSS Export Rating Curve Sorted= 0
DSS Export Volume Flow Curves= 0
DXF OffsetX= 0
DXF OffsetY= 0
DXF ScaleX= 1
DXF ScaleY= 10

--- SMITH BRANCH TRIBUTARY 1 1.p01 (plan) ---

Plan Title=Multiple Run
Short Identifier=Multiple
Geom File=g01
Flow File=f01
Subcritical Flow
K Sum by GR= 0
Std Step Tol= 0.01
Critical Tol= 0.01
Num of Std Step Trials= 20
Max Error Tol= 0.3
Flow Tol Ratio= 0.001
Split Flow NTrial= 30
Split Flow Tol= 0.02
Split Flow Ratio= 0.02
Log Output Level= 0
Friction Slope Method= 1
Unsteady Friction Slope Method= 2
Unsteady Bridges Friction Slope Method= 1
Parabolic Critical Depth
Global Vel Dist=  1 , 1 , 1
Global Log Level= 0
CheckData=True
Encroach Param= -1, 0, 0, 0
BEGIN DESCRIPTION:
Multiple Run
END DESCRIPTION:

--- SMITH BRANCH TRIBUTARY 1 1.f01 (steady flow) ---

Flow Title=Multiple
Number of Profiles=7
Profile Names=10-year,25-year,50-year,1pct_min,100-year,1pct_plu,500-year
River Rch & RM= SMITH BRANCH TRI,Reach-1,2253
     218     278     324     279     377     510     508
Boundary for River Rch & Prof#=SMITH BRANCH TRI,Reach-1,1
Up Type=0
Dn Type=3
Dn Slope=0.005
Boundary for River Rch & Prof#=SMITH BRANCH TRI,Reach-1,2
Up Type=0
Dn Type=3
Dn Slope=0.005
Boundary for River Rch & Prof#=SMITH BRANCH TRI,Reach-1,3
Up Type=0
Dn Type=3
Dn Slope=0.005
Boundary for River Rch & Prof#=SMITH BRANCH TRI,Reach-1,4
Up Type=0
Dn Type=3
Dn Slope=0.005
Boundary for River Rch & Prof#=SMITH BRANCH TRI,Reach-1,5
Up Type=0
Dn Type=3
Dn Slope=0.005
Boundary for River Rch & Prof#=SMITH BRANCH TRI,Reach-1,6
Up Type=0
Dn Type=3
Dn Slope=0.005
Boundary for River Rch & Prof#=SMITH BRANCH TRI,Reach-1,7
Up Type=0
Dn Type=3
Dn Slope=0.005

--- SMITH BRANCH TRIBUTARY 1 1.g01 (geometry) ---

Geom Title=Existing Conditions
Program Version=4.10

River Reach=SMITH BRANCH TRI,Reach-1
Reach XY= 30
      3545928.07     10324462.33      3546192.64     10324198.86
      3546285.56     10324150.33      3546328.54     10324153.36
      3546385.96     10324092.29      3546385.56     10324066.04
      3546344.96     10324021.74      3546376.94     10323962.71
      3546313.06     10323890.99      3546328.83     10323865.55
      3546393.48      10323873.9      3546355.16     10323822.42
      3546368.19     10323770.78      3546416.43     10323729.43
      3546448.79     10323727.59      3546518.55     10323774.24
      3546576.89     10323724.39      3546585.94     10323643.39
      3546648.59     10323574.54      3546762.13      10323533.1
      3546866.55      10323546.9      3546915.65     10323516.17
      3547010.66     10323586.74      3547019.69     10323553.81
      3546979.07     10323455.26       3546992.5     10323442.42
      3547063.93     10323455.68       3547133.9      10323606.7
      3547183.45     10323565.76      3547242.11     10323551.64

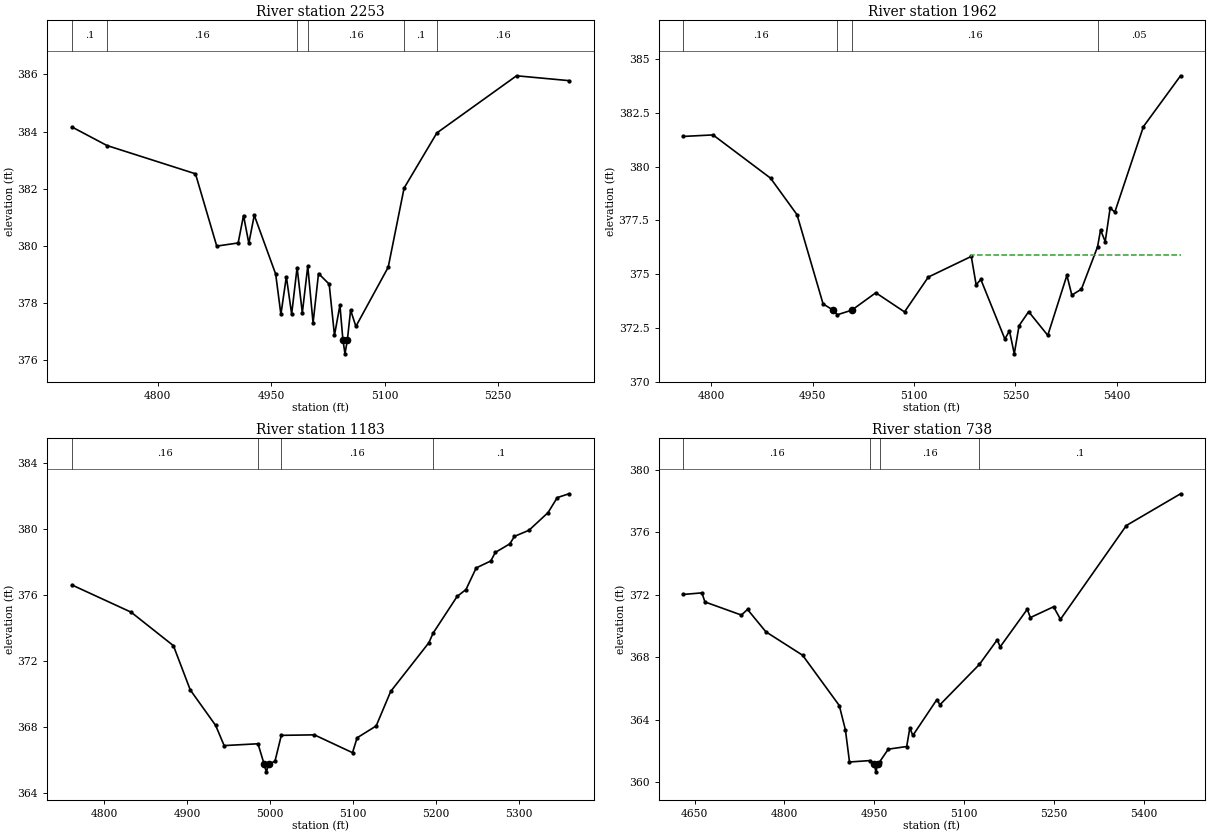
Type RM Length L Ch R = 1 ,2253    ,291,291,291
BEGIN DESCRIPTION:
SMITH BRANCH TRIBUTARY 1.1 4.0
END DESCRIPTION:
XS GIS Cut Line= 3
      3546329.41     10324505.22      3546034.27     10324218.77
      3545869.42     10324036.57
#Sta/Elev= 30
  4686.6  384.16    4733  383.51    4850  382.52  4878.1  379.99  4906.4   380.1
  4913.5  381.06  4920.5  380.09  4927.7  381.07    4956  379.01  4962.9   377.6
  4970.1  378.92  4977.1  377.61  4984.3  379.24  4991.2  377.65  4998.4  379.29
  5005.4   377.3  5012.6  379.03  5026.7  378.66  5033.7  376.87  5040.9  377.92
  5044.8  376.72  5047.6  376.22  5050.8  376.72    5055  377.75    5062  377.18
  5104.7  379.25  5125.7  382.02    5169  383.95  5274.3  385.95  5343.6  385.78
#Mann= 6 ,-1 , 0
  4686.6      .1       0    4733     .16       0  4984.3    .033       0
  4998.4     .16       0  5125.7      .1       0    5169     .16       0
Bank Sta=5044.8,5050.8
XS Rating Curve= 0 ,0
Exp/Cntr=0.3,0.1

Type RM Length L Ch R = 1 ,1962    ,779,779,779
BEGIN DESCRIPTION:
SMITH BRANCH TRIBUTARY 1.1 3.0
END DESCRIPTION:
XS GIS Cut Line= 3
      3546503.05     10324322.96      3546390.17     10324201.41
      3546000.45      10323785.7
#Sta/Elev= 30
  4758.6   381.4  4802.4  381.47  4887.5  379.46  4926.7  377.76  4965.3  373.61
  4979.3  373.34  4986.6  373.11  5007.7  373.32  5043.3  374.13  5085.8  373.24
    5121  374.86  5184.6  375.82  5191.8   374.5  5198.7  374.75  5234.3  371.98
  5241.1  372.36  5248.2  371.29  5255.3   372.6  5269.5  373.25  5297.8  372.15
  5326.1  374.94  5333.4  374.02  5347.6   374.3  5371.5  376.27  5375.9  377.05
  5382.8  376.51  5390.1  378.07    5397  377.88  5439.4  381.86  5494.3  384.22
#Mann= 4 ,-1 , 0
  4758.6     .16       0  4986.6     .07       0  5007.7     .16       0
  5371.5     .05       0
#XS Ineff= 2 , 0
                          5184.3          375.87
Permanent Ineff=
       F       F
Bank Sta=4979.3,5007.7
XS Rating Curve= 0 ,0
Exp/Cntr=0.3,0.1

Type RM Length L Ch R = 1 ,1183    ,445,445,445
BEGIN DESCRIPTION:
SMITH BRANCH TRIBUTARY 1.1 2.0
END DESCRIPTION:
XS GIS Cut Line= 3
       3546592.1     10323991.62      3546542.11     10323741.64
      3546398.84     10323428.81
#Sta/Elev= 30
  4761.2   376.6  4832.6  374.95  4883.6  372.92  4903.9  370.24  4934.5  368.09
  4944.7  366.87  4985.5  366.98  4992.7  365.78  4995.5  365.28  4998.7  365.78
  5005.9  365.91  5013.6  367.49  5053.4  367.52  5099.4  366.44  5104.9  367.34
  5127.9  368.06  5145.4  370.15  5191.4   373.1  5196.5  373.68  5225.4   375.9
  5236.1  376.32  5248.4  377.63    5266  378.05  5271.5  378.57    5289  379.09
  5294.5  379.54    5312  379.91    5335  380.98  5346.1  381.89  5360.2  382.12
#Mann= 4 ,-1 , 0
  4761.2     .16       0  4985.5    .035       0  5013.6     .16       0
  5196.5      .1       0
Bank Sta=4992.7,4998.7
XS Rating Curve= 0 ,0
Exp/Cntr=0.3,0.1

Type RM Length L Ch R = 1 ,738     ,0,0,0
BEGIN DESCRIPTION:
SMITH BRANCH TRIBUTARY 1.1 1.0
END DESCRIPTION:
XS GIS Cut Line= 3
      3546780.79     10323906.31      3546911.55     10323272.55
      3546935.31     10323092.02
#Sta/Elev= 30
  4631.5  372.03  4662.3  372.13  4667.4  371.55  4728.2  370.71  4738.4  371.07
    4769  369.64  4830.3  368.14  4891.5  364.92  4901.7  363.36  4908.5  361.31
  4942.6   361.4  4949.8  361.18  4952.5  360.68  4955.8  361.18  4958.8  361.32
  4973.2  362.13  5003.9   362.3  5009.1  363.48  5014.2  363.01  5054.2   365.3
  5059.3  364.97  5125.1  367.55  5154.8  369.12  5159.9  368.68    5205  371.08
  5210.2  370.55  5248.9  371.24  5260.4  370.44  5370.3  376.44  5460.7  378.47
#Mann= 4 ,-1 , 0
  4631.5     .16       0  4942.6    .035       0  4958.8     .16       0
  5125.1      .1       0
Bank Sta=4949.8,4955.8
XS Rating Curve= 0 ,0
Exp/Cntr=0.3,0.1

Chan Stop Cuts=-1
Use User Specified Reach Order=0
Composite Channel Slope=5