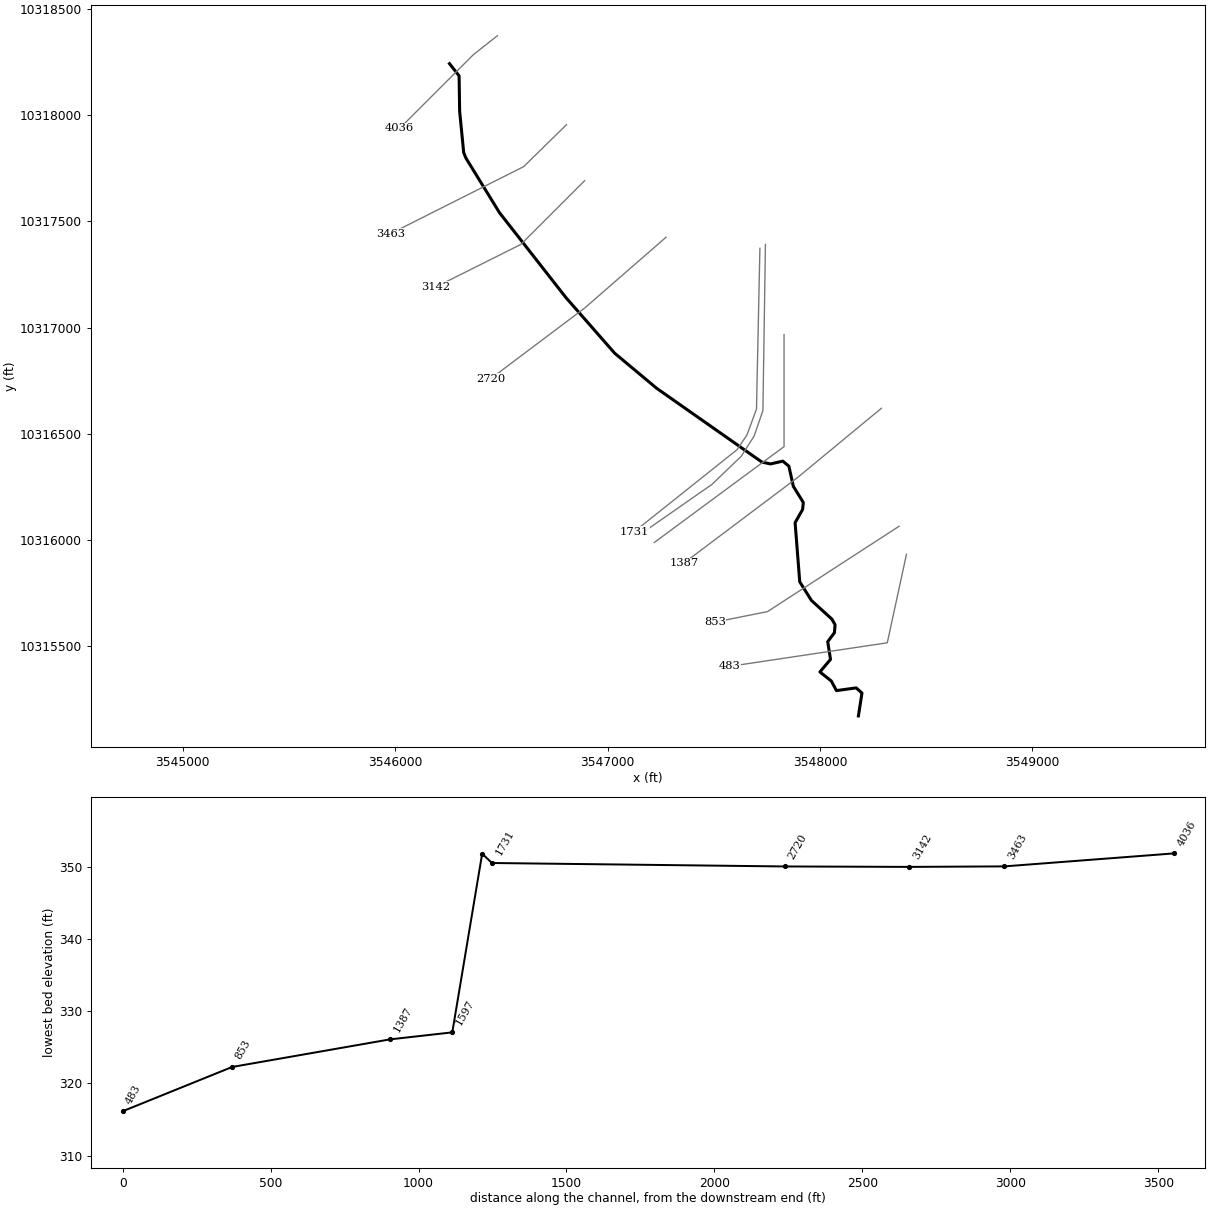
--- SMITH BRANCH TRIBUTARY 1.prj (project) ---

Proj Title=SMITH BRANCH TRIBUTARY 1 Base Level Engineering
Current Plan=p01
Default Exp/Contr=0.3,0.1
English Units
Geom File=g01
Flow File=f01
Plan File=p01
Y Axis Title=Elevation
X Axis Title(PF)=Main Channel Distance
X Axis Title(XS)=Station
BEGIN DESCRIPTION:
SMITH BRANCH TRIBUTARY 1
END DESCRIPTION:
DSS Export Rating Curves= 0
DSS Export Rating Curve Sorted= 0
DSS Export Volume Flow Curves= 0
DXF OffsetX= 0
DXF OffsetY= 0
DXF ScaleX= 1
DXF ScaleY= 10

--- SMITH BRANCH TRIBUTARY 1.p01 (plan) ---

Plan Title=Multiple Run
Short Identifier=Multiple
Geom File=g01
Flow File=f01
Subcritical Flow
K Sum by GR= 0
Std Step Tol= 0.01
Critical Tol= 0.01
Num of Std Step Trials= 20
Max Error Tol= 0.3
Flow Tol Ratio= 0.001
Split Flow NTrial= 30
Split Flow Tol= 0.02
Split Flow Ratio= 0.02
Log Output Level= 0
Friction Slope Method= 1
Unsteady Friction Slope Method= 2
Unsteady Bridges Friction Slope Method= 1
Parabolic Critical Depth
Global Vel Dist=  1 , 1 , 1
Global Log Level= 0
CheckData=True
Encroach Param= -1, 0, 0, 0
BEGIN DESCRIPTION:
Multiple Run
END DESCRIPTION:

--- SMITH BRANCH TRIBUTARY 1.f01 (steady flow) ---

Flow Title=Multiple
Number of Profiles=7
Profile Names=10-year,25-year,50-year,1pct_min,100-year,1pct_plu,500-year
River Rch & RM= SMITH BRANCH TRI,Reach-1,4036
     267     345     405     351     474     641     648
Boundary for River Rch & Prof#=SMITH BRANCH TRI,Reach-1,1
Up Type=0
Dn Type=3
Dn Slope=0.005
Boundary for River Rch & Prof#=SMITH BRANCH TRI,Reach-1,2
Up Type=0
Dn Type=3
Dn Slope=0.005
Boundary for River Rch & Prof#=SMITH BRANCH TRI,Reach-1,3
Up Type=0
Dn Type=3
Dn Slope=0.005
Boundary for River Rch & Prof#=SMITH BRANCH TRI,Reach-1,4
Up Type=0
Dn Type=3
Dn Slope=0.005
Boundary for River Rch & Prof#=SMITH BRANCH TRI,Reach-1,5
Up Type=0
Dn Type=3
Dn Slope=0.005
Boundary for River Rch & Prof#=SMITH BRANCH TRI,Reach-1,6
Up Type=0
Dn Type=3
Dn Slope=0.005
Boundary for River Rch & Prof#=SMITH BRANCH TRI,Reach-1,7
Up Type=0
Dn Type=3
Dn Slope=0.005

--- SMITH BRANCH TRIBUTARY 1.g01 (geometry) ---

Geom Title=Existing Conditions
Program Version=4.10

River Reach=SMITH BRANCH TRI,Reach-1
Reach XY= 30
      3546255.86     10318242.58      3546301.03      10318185.3
      3546303.63     10318018.64      3546322.73     10317823.33
      3546333.14     10317798.15      3546491.13     10317540.99
      3546803.63     10317141.68      3547033.66      10316879.1
      3547231.15     10316714.17      3547726.81     10316366.58
      3547766.95      10316357.9      3547825.55     10316370.92
      3547854.03     10316347.06      3547874.66      10316252.8
      3547921.91     10316176.27      3547918.53     10316143.38
      3547883.18     10316081.17      3547905.01     10315802.87
      3547959.98     10315715.05      3548055.68     10315627.85
      3548071.47     10315601.06      3548068.48     10315563.52
      3548036.73     10315520.64      3548049.95     10315437.52
      3548000.05     10315378.37      3548053.57     10315335.77
      3548077.86     10315290.53      3548170.93     10315303.29
      3548198.01     10315278.98      3548181.29     10315171.14

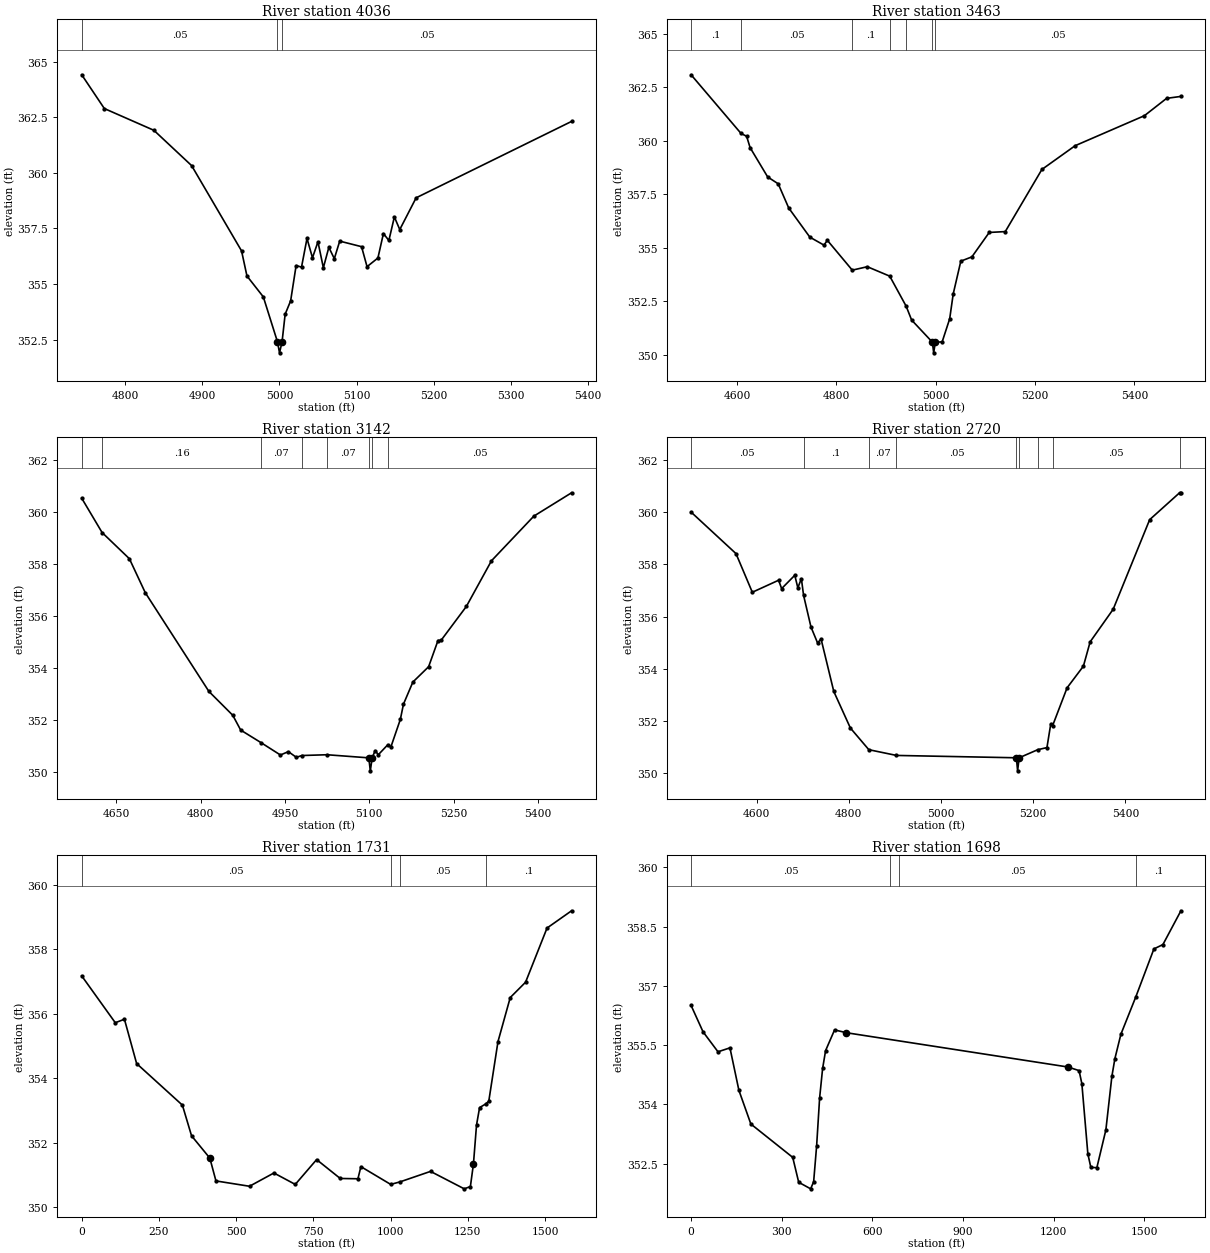
Type RM Length L Ch R = 1 ,4036    ,573,573,573
BEGIN DESCRIPTION:
SMITH BRANCH TRIBUTARY 1 7.02
END DESCRIPTION:
XS GIS Cut Line= 3
      3546481.19     10318373.98      3546368.36     10318285.01
      3546021.16     10317937.82
#Sta/Elev= 30
  4743.8  364.42  4773.1   362.9  4837.3  361.92  4886.2  360.33  4950.9  356.49
  4957.9  355.36  4979.1  354.42  4997.4   352.4  5000.1   351.9  5003.4   352.4
  5007.4  353.64  5014.5  354.24  5021.6  355.83  5028.6  355.76  5035.7  357.05
  5042.8  356.18  5049.9   356.9  5056.9  355.73    5064  356.65  5071.1  356.14
  5078.1  356.93  5106.4  356.68  5113.5  355.78  5127.6  356.17  5134.7  357.27
  5141.8  356.96  5148.9  358.02  5155.9  357.45  5177.1  358.88  5378.5  362.32
#Mann= 3 ,-1 , 0
  4743.8     .05       0  4997.4     .04       0  5003.4     .05       0
Bank Sta=4997.4,5003.4
XS Rating Curve= 0 ,0
Exp/Cntr=0.3,0.1

Type RM Length L Ch R = 1 ,3463    ,321,321,321
BEGIN DESCRIPTION:
SMITH BRANCH TRIBUTARY 1 7.01
END DESCRIPTION:
XS GIS Cut Line= 3
      3546806.69     10317955.12       3546604.9     10317757.67
      3545976.29      10317441.2
#Sta/Elev= 30
  4507.7  363.08  4608.3  360.34  4619.5  360.21  4626.5  359.68  4661.9  358.31
  4683.1  357.99  4704.3  356.86  4746.8   355.5  4775.1  355.13  4782.1  355.35
  4832.2  353.96  4862.5  354.12  4907.6  353.68  4940.6  352.28  4951.7  351.63
  4993.4   350.6  4996.1   350.1  4999.4   350.6  5013.1  350.61  5028.3  351.69
  5035.4  352.85  5050.7  354.38    5073  354.58  5107.9  355.72  5140.2  355.76
  5213.9  358.66  5280.9  359.77  5420.3  361.17    5465  361.98  5493.8  362.07
#Mann= 7 ,-1 , 0
  4507.7      .1       0  4608.3     .05       0  4832.2      .1       0
  4907.6     .07       0  4940.6     .05       0  4993.4     .03       0
  4999.4     .05       0
Bank Sta=4993.4,4999.4
XS Rating Curve= 0 ,0
Exp/Cntr=0.3,0.1

Type RM Length L Ch R = 1 ,3142    ,422,422,422
BEGIN DESCRIPTION:
SMITH BRANCH TRIBUTARY 1 7.0
END DESCRIPTION:
XS GIS Cut Line= 3
      3546892.07     10317691.61      3546592.11     10317391.64
      3546192.13     10317191.66
#Sta/Elev= 30
  4588.4  360.53  4624.6  359.21  4673.2   358.2  4701.5  356.89  4814.6  353.09
  4857.1  352.17  4871.2   351.6  4907.1  351.12  4941.9  350.64    4956  350.77
  4970.2  350.55    4980  350.62  5024.8  350.65  5099.1  350.53  5101.8  350.03
  5105.1  350.53  5110.4  350.81    5116  350.65  5133.1  351.04  5138.4  350.95
  5155.2  352.01  5160.8   352.6  5177.5  353.45  5205.5  354.04  5222.2  355.05
  5227.8  355.06  5272.6  356.36  5317.3  358.12  5392.7  359.84  5459.8  360.74
#Mann= 8 ,-1 , 0
  4588.4      .1       0  4624.6     .16       0  4907.1     .07       0
    4980     .05       0  5024.8     .07       0  5099.1    .033       0
  5105.1     .07       0  5133.1     .05       0
Bank Sta=5099.1,5105.1
XS Rating Curve= 0 ,0
Exp/Cntr=0.3,0.1

Type RM Length L Ch R = 1 ,2720    ,989,989,989
BEGIN DESCRIPTION:
SMITH BRANCH TRIBUTARY 1 6.0
END DESCRIPTION:
XS GIS Cut Line= 3
      3547275.57     10317425.34      3546892.11     10317091.64
      3546449.22     10316758.71
#Sta/Elev= 30
    4458     360  4555.4  358.41  4590.8  356.93  4647.8  357.39  4654.4  357.07
  4682.9  357.58  4689.5   357.1  4697.2  357.45    4702  356.81    4718   355.6
  4732.3  354.99  4739.9  355.14  4767.5  353.13  4803.5  351.73  4843.5   350.9
  4903.5  350.68  5163.5  350.59  5166.2  350.09  5169.5  350.59  5209.9   350.9
  5229.8  350.98  5238.1  351.89  5242.1  351.82  5273.5  353.27  5308.9   354.1
  5323.5  355.03  5373.5  356.28  5452.6  359.71  5517.5  360.74  5520.4  360.74
#Mann= 9 ,-1 , 0
    4458     .05       0    4702      .1       0  4843.5     .07       0
  4903.5     .05       0  5163.5    .033       0  5169.5     .05       0
  5209.9     .07       0  5242.1     .05       0  5517.5      .1       0
Bank Sta=5163.5,5169.5
XS Rating Curve= 0 ,0
Exp/Cntr=0.3,0.1

Type RM Length L Ch R = 1 ,1731    ,33,33,33
BEGIN DESCRIPTION:
SMITH BRANCH TRIBUTARY 1 5.1
END DESCRIPTION:
XS GIS Cut Line= 5
     3547717.464    10317372.769      3547701.36     10316615.99
      3547656.56     10316494.11      3547609.17     10316424.32
       3547126.6     10316039.49
#Sta/Elev= 30
       0357.1689108.6411 355.718138.2706355.8259177.7764354.4521325.9234353.1642
355.5528352.2144414.8116351.5217434.5646350.8154543.2057350.6502622.2175351.0616
691.3527350.7076 760.488351.4764836.9148350.8916894.2349350.8823903.7882351.2587
1000.262 350.7081030.037350.78481129.286351.1111 1238.46350.5703 1258.31350.6415
1268.235351.3452 1278.16352.54711288.084353.08791307.934353.20161317.859353.2858
1347.634355.13291387.333356.49861436.958356.97351506.432358.65211585.832 359.187
#Mann= 4 ,-1 , 0
       0     .05       01000.262    .033       01030.037     .05       0
1307.934      .1       0
Bank Sta=414.8116,1268.235
XS Rating Curve= 0 ,0
Exp/Cntr=0.3,0.1

Type RM Length L Ch R = 1 ,1698    ,101,101,101
BEGIN DESCRIPTION:
SMITH BRANCH TRIBUTARY 1 5.0
END DESCRIPTION:
XS GIS Cut Line= 6
     3547743.505    10317390.998      3547731.57     10316608.75
      3547690.34      10316489.4      3547629.57     10316393.91
      3547491.77     10316261.53      3547156.22     10316027.73
#Sta/Elev= 30
       0356.504839.55985355.837689.00966355.3318128.5695355.4315158.2394354.3547
197.7993353.5027336.2587352.6585356.0386352.0283395.5985 351.862405.4885352.0419
415.3784352.9535425.2684354.1651435.1584354.9097445.0483355.3627474.7182355.8861
 514.062355.81411246.774 354.9471283.641354.85561292.858354.52491312.722352.7455
1322.654352.40281342.519352.39891372.316353.3539 1392.18354.70961402.112355.1577
1421.977355.77571471.638356.72731531.232357.93641561.028358.04661620.622358.9021
#Mann= 4 ,-1 , 0
       0     .05       0659.1713    .033       0688.1931     .05       0
1471.638      .1       0
Bank Sta=514.062,1246.774
XS Rating Curve= 0 ,0
Exp/Cntr=0.3,0.1

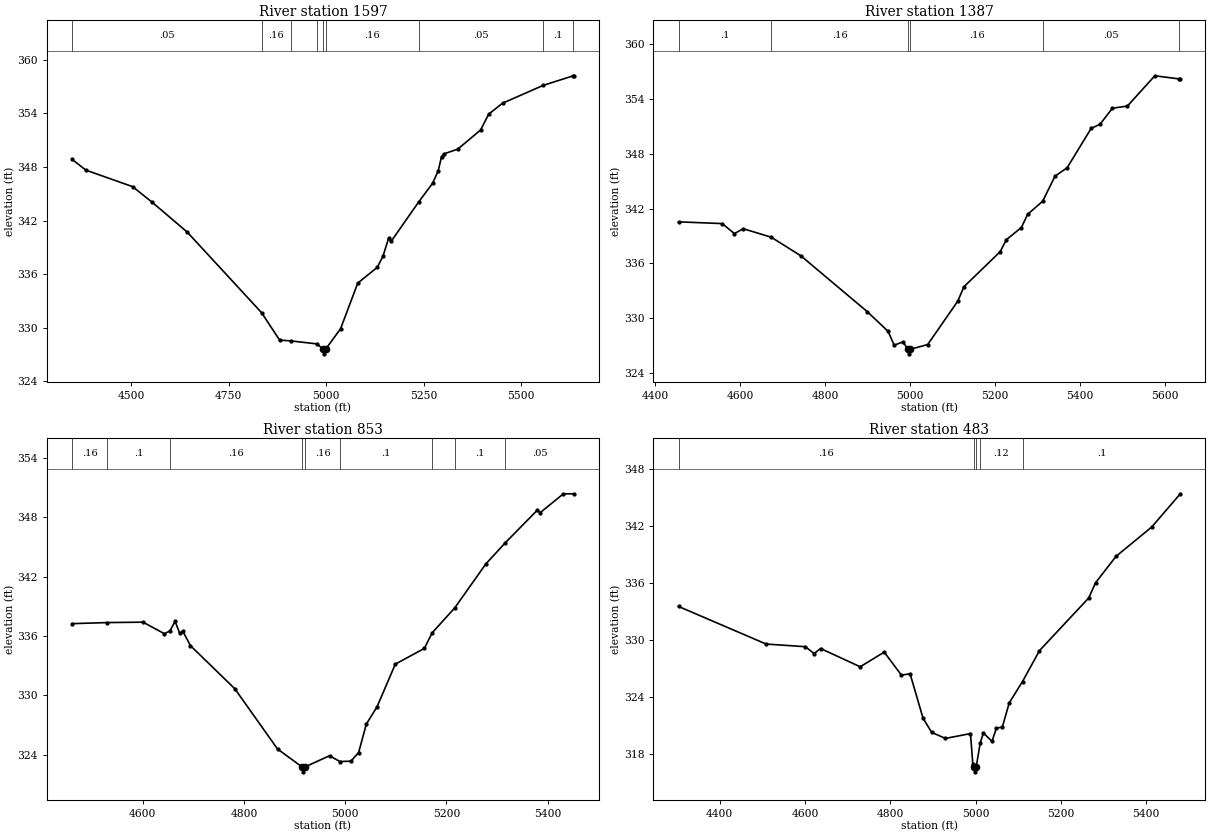
Type RM Length L Ch R = 1 ,1597    ,210,210,210
BEGIN DESCRIPTION:
SMITH BRANCH TRIBUTARY 1 4.0
END DESCRIPTION:
XS GIS Cut Line= 3
      3547831.15     10316967.06      3547831.15     10316439.25
        3547220.     10315987.84
#Sta/Elev= 30
  4348.2  348.85  4383.6  347.64  4503.6  345.79  4553.6  344.05  4643.6  340.71
  4834.6  331.68  4880.7  328.62  4908.9  328.53    4977  328.19  4992.6  327.58
  4995.3  327.08  4998.6  327.58  5037.3   329.9  5081.2  334.99  5131.3  336.76
  5145.9  337.99  5160.5  340.03  5166.8  339.66  5237.3  344.06  5273.2  346.16
  5287.8  347.56  5296.2  349.16  5302.5  349.46  5337.9  349.99  5396.5  352.13
  5417.3  353.91  5452.8  355.13  5556.8  357.12  5634.3   358.2  5635.8   358.2
#Mann= 9 ,-1 , 0
  4348.2     .05       0  4834.6     .16       0  4908.9     .05       0
    4977     .16       0  4992.6     .07       0  4998.6     .16       0
  5237.3     .05       0  5556.8      .1       0  5634.3     .05       0
Bank Sta=4992.6,4998.6
XS Rating Curve= 0 ,0
Exp/Cntr=0.3,0.1

Type RM Length L Ch R = 1 ,1387    ,534,534,534
BEGIN DESCRIPTION:
SMITH BRANCH TRIBUTARY 1 3.0
END DESCRIPTION:
XS GIS Cut Line= 3
       3548289.5     10316619.83      3547892.11     10316291.64
      3547358.95     10315890.66
#Sta/Elev= 30
  4454.7  340.55  4557.7  340.36  4586.4  339.26  4607.2   339.8  4673.1  338.87
  4742.8  336.84  4899.1  330.74  4948.6  328.57  4962.9  327.05  4983.6  327.42
  4995.2  326.61    4998  326.11  5001.2  326.61  5041.9  327.13  5112.7  331.87
  5127.3  333.45  5212.7  337.29  5227.3   338.6  5262.7  339.93  5277.3  341.37
  5312.7   342.8  5341.8  345.54  5370.5  346.47  5427.2  350.78    5448  351.23
  5477.2  352.98  5512.6  353.22  5577.1  356.53  5634.1  356.19  5637.2  356.19
#Mann= 6 ,-1 , 0
  4454.7      .1       0  4673.1     .16       0  4995.2     .07       0
  5001.2     .16       0  5312.7     .05       0  5634.1      .1       0
Bank Sta=4995.2,5001.2
XS Rating Curve= 0 ,0
Exp/Cntr=0.3,0.1

Type RM Length L Ch R = 1 ,853     ,370,370,370
BEGIN DESCRIPTION:
SMITH BRANCH TRIBUTARY 1 2.0
END DESCRIPTION:
XS GIS Cut Line= 3
      3548372.83     10316064.27      3547753.22     10315662.48
      3547505.12     10315612.86
#Sta/Elev= 30
  4460.3  337.25  4530.3  337.36  4600.6   337.4  4642.8  336.23  4653.6  336.52
  4663.9  337.48  4673.1  336.26  4679.1  336.48  4694.2  335.03  4781.9  330.67
  4866.4  324.58  4914.7  322.78  4917.5  322.28  4920.7  322.78  4969.1  323.91
  4989.4  323.32  5011.4  323.36  5026.5  324.23  5041.7   327.1  5062.8  328.84
    5099  333.16  5156.4  334.75  5171.9  336.33  5216.4  338.84    5278  343.29
  5316.3  345.42  5379.9  348.73    5385  348.45  5430.9  350.36  5451.8  350.37
#Mann= 9 ,-1 , 0
  4460.3     .16       0  4530.3      .1       0  4653.6     .16       0
  4914.7     .07       0  4920.7     .16       0  4989.4      .1       0
  5171.9     .05       0  5216.4      .1       0  5316.3     .05       0
Bank Sta=4914.7,4920.7
XS Rating Curve= 0 ,0
Exp/Cntr=0.3,0.1

Type RM Length L Ch R = 1 ,483     ,0,0,0
BEGIN DESCRIPTION:
SMITH BRANCH TRIBUTARY 1 1.0
END DESCRIPTION:
XS GIS Cut Line= 3
      3548407.53     10315932.28      3548317.26     10315515.64
       3547575.6     10315404.74
#Sta/Elev= 30
  4303.6  333.52  4508.9  329.57    4601  329.29  4621.4  328.57  4636.5   329.1
  4729.4  327.18  4785.7  328.72  4826.1   326.3  4846.3  326.45  4876.7  321.78
  4896.9  320.29  4929.1  319.65  4987.9  320.16  4993.3  317.01  4995.3  316.64
  4998.1  316.14  5001.3  316.64  5010.7  319.17  5018.2  320.22  5038.4  319.34
  5048.6  320.73  5062.5  320.84  5078.9   323.4  5109.9  325.63  5149.7  328.88
    5265  334.41  5281.1  336.01  5329.2  338.79  5412.6  341.86  5479.8  345.36
#Mann= 5 ,-1 , 0
  4303.6     .16       0  4995.3     .07       0  5001.3     .16       0
  5010.7     .12       0  5109.9      .1       0
Bank Sta=4995.3,5001.3
XS Rating Curve= 0 ,0
Exp/Cntr=0.3,0.1

Chan Stop Cuts=-1
Use User Specified Reach Order=0
Composite Channel Slope=5