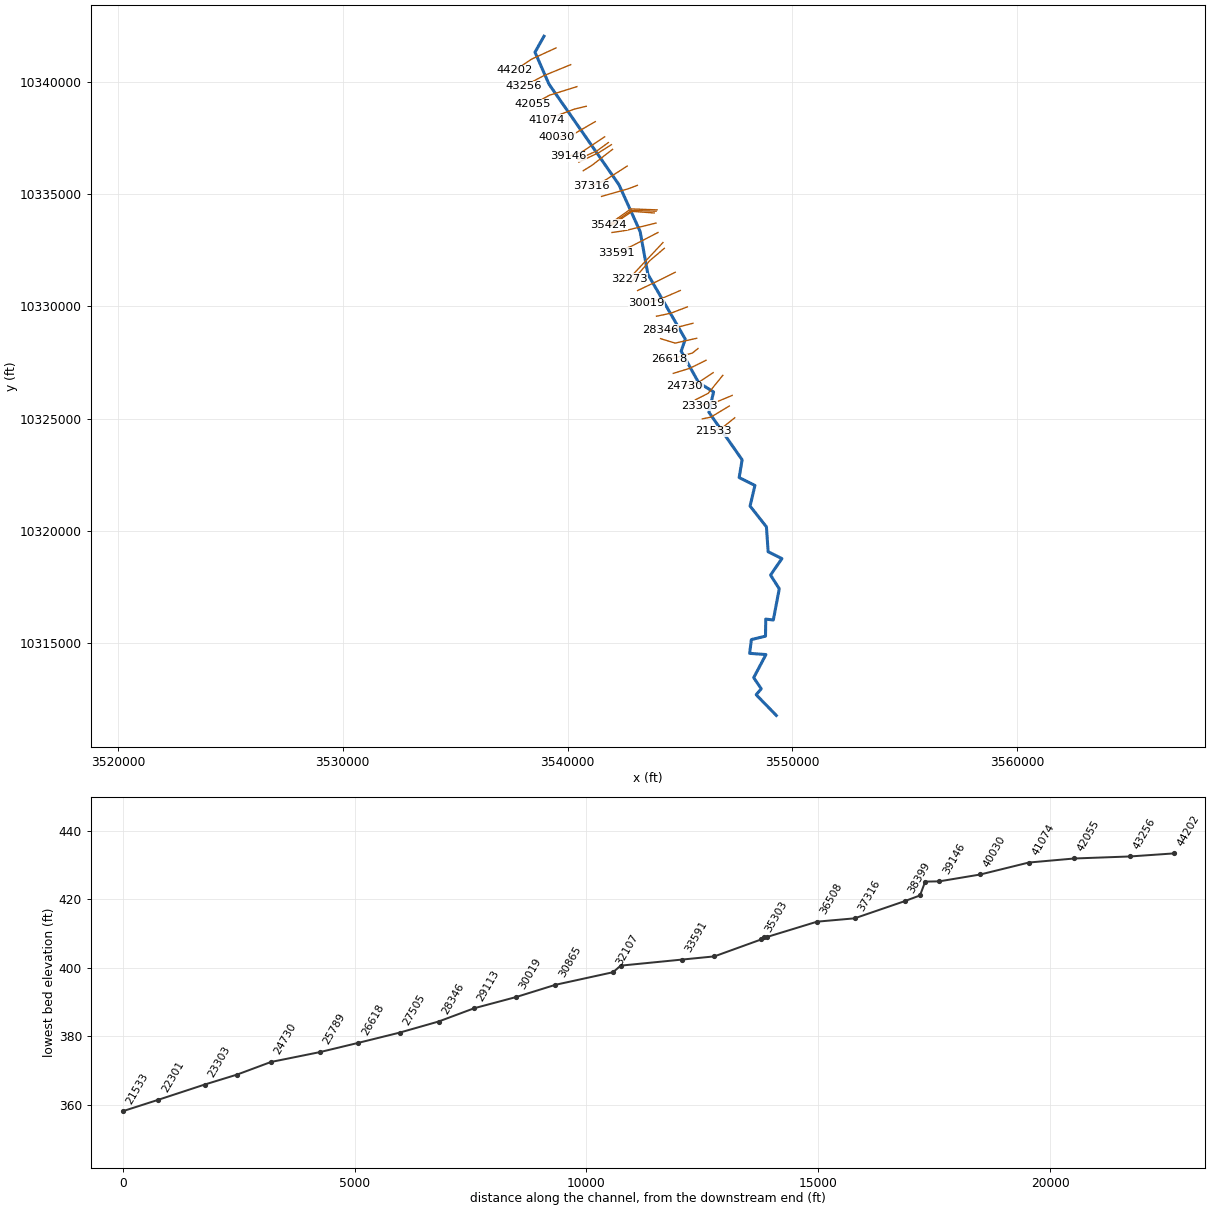
--- SMITH BRANCH.prj (project) ---

Proj Title=SMITH BRANCH Base Level Engineering
Current Plan=p01
Default Exp/Contr=0.3,0.1
English Units
Geom File=g01
Flow File=f01
Plan File=p01
BEGIN DESCRIPTION:
SMITH BRANCH
END DESCRIPTION:

--- SMITH BRANCH.p01 (plan) ---

Plan Title=Multiple Run
Short Identifier=Multiple
Geom File=g01
Flow File=f01
Subcritical Flow
K Sum by GR= 0
Std Step Tol= 0.01
Critical Tol= 0.01
Num of Std Step Trials= 20
Max Error Tol= 0.3
Flow Tol Ratio= 0.001
Split Flow NTrial= 30
Split Flow Tol= 0.02
Split Flow Ratio= 0.02
Log Output Level= 0
Friction Slope Method= 1
Unsteady Friction Slope Method= 2
Unsteady Bridges Friction Slope Method= 1
Parabolic Critical Depth
Global Vel Dist=  1 , 1 , 1
Global Log Level= 0
CheckData=True
Encroach Param= -1, 0, 0, 0
BEGIN DESCRIPTION:
Multiple Run
END DESCRIPTION:

--- SMITH BRANCH.f01 (steady flow) ---

Flow Title=Multiple
Number of Profiles=7
Profile Names=10-year,25-year,50-year,1pct_min,100-year,1pct_plu,500-year
River Rch & RM= SMITH BRANCH,Reach-1,44202
     561     751     905     798    1079    1459    1538
River Rch & RM= SMITH BRANCH,Reach-1,42055
     852    1164    1420    1266    1712    2316    2499
River Rch & RM= SMITH BRANCH,Reach-1,30865
    1108    1535    1889    1699    2298    3108    3411
River Rch & RM= SMITH BRANCH,Reach-1,19969
    1425    1994    2473    2237    3026    4092    4549
River Rch & RM= SMITH BRANCH,Reach-1,5919
    1556    2185    2715    2462    3330    4504    5027
Boundary for River Rch & Prof#=SMITH BRANCH,Reach-1,1
Up Type=0
Dn Type=3
Dn Slope=0.005
Boundary for River Rch & Prof#=SMITH BRANCH,Reach-1,2
Up Type=0
Dn Type=3
Dn Slope=0.005
Boundary for River Rch & Prof#=SMITH BRANCH,Reach-1,3
Up Type=0
Dn Type=3
Dn Slope=0.005
Boundary for River Rch & Prof#=SMITH BRANCH,Reach-1,4
Up Type=0
Dn Type=3
Dn Slope=0.005
Boundary for River Rch & Prof#=SMITH BRANCH,Reach-1,5
Up Type=0
Dn Type=3
Dn Slope=0.005
Boundary for River Rch & Prof#=SMITH BRANCH,Reach-1,6
Up Type=0
Dn Type=3
Dn Slope=0.005
Boundary for River Rch & Prof#=SMITH BRANCH,Reach-1,7
Up Type=0
Dn Type=3
Dn Slope=0.005

--- SMITH BRANCH.g01 (geometry) ---

Geom Title=Existing Conditions

River Reach=SMITH BRANCH,Reach-1
Reach XY= 30
      3538951.57     10342016.86      3538552.51     10341306.59
      3539175.31     10339884.17      3542286.63     10335414.14
      3543231.02     10333326.19      3543575.75     10331423.62
      3545239.05     10328540.20      3545055.82     10328003.00
      3545834.53     10326602.91      3546498.88     10326190.44
      3546289.78     10325288.29      3547768.88     10323170.35
      3547637.05     10322379.22      3548338.77     10322030.49
      3548123.01     10321111.49      3548850.58     10320185.71
      3548926.41     10319078.57      3549538.42     10318774.66
      3549033.31     10318041.15      3549421.34     10317431.39
      3549157.39     10316043.21      3548820.07     10316080.93
      3548808.86     10315322.98      3548181.29     10315171.14
      3548103.02     10314558.18      3548828.02     10314504.49
      3548283.50     10313475.49      3548620.20     10312981.64
      3548394.05     10312717.71      3549291.47     10311794.56

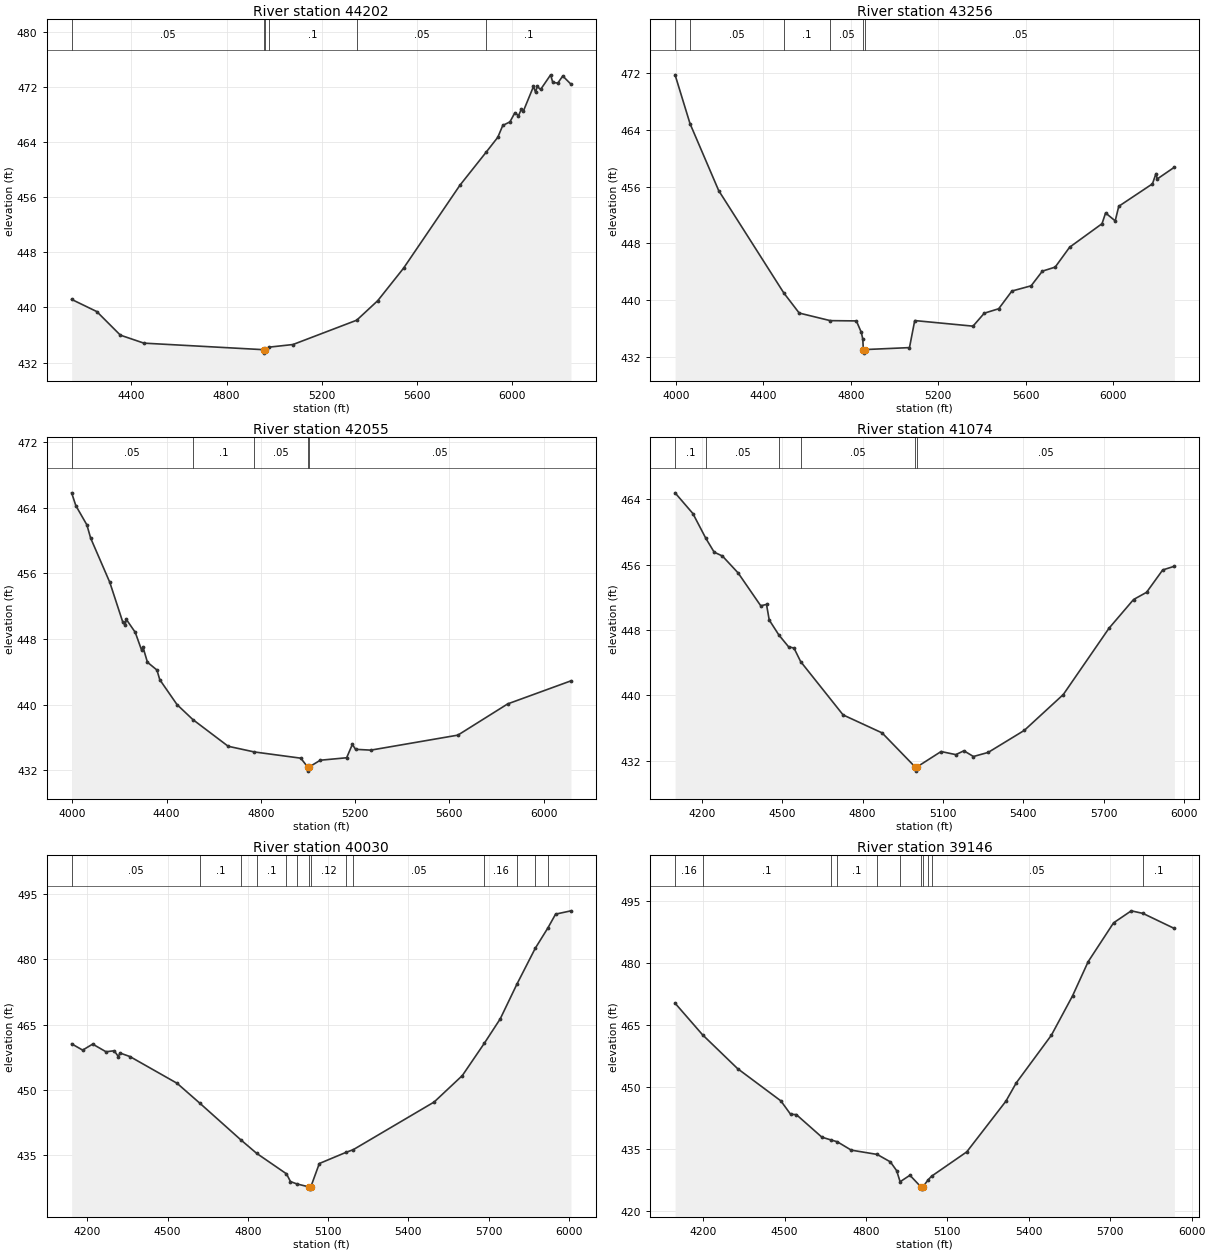
Type RM Length L Ch R = 1,44202,946,946,946
BEGIN DESCRIPTION:
SMITH BRANCH 71.0
END DESCRIPTION:
XS GIS Cut Line= 3
      3539488.38     10341497.59      3538398.65     10340997.43
      3537648.67     10340497.44
#Sta/Elev= 30
  4148.2  441.17  4254.1  439.40  4353.2  435.98  4452.2  434.82  4955.3  433.87
  4958.1  433.37  4961.3  433.87  4976.8  434.23  5079.4  434.62  5347.4  438.15
  5436.0  440.99  5544.2  445.69  5781.5  457.74  5891.6  462.53  5940.8  464.70
  5961.8  466.42  5991.9  466.94  6012.9  468.27  6027.9  467.83  6040.1  468.80
  6048.9  468.54  6091.0  472.08  6100.0  471.21  6106.0  472.08  6121.1  471.65
  6163.1  473.77  6172.1  472.67  6193.2  472.57  6214.2  473.60  6248.6  472.41
#Mann=6,-1,0
  4148.2    0.05       0  4955.3    0.07       0  4961.3    0.05       0
  4976.8     0.1       0  5347.4    0.05       0  5891.6     0.1       0
Bank Sta=4955.3,4961.3
Exp/Cntr=0.3,0.1

Type RM Length L Ch R = 1,43256,1201,1201,1201
BEGIN DESCRIPTION:
SMITH BRANCH 70.0
END DESCRIPTION:
XS GIS Cut Line= 3
      3540139.88     10340753.07      3538927.85     10340255.36
      3538069.16     10339799.15
#Sta/Elev= 30
  3996.8  471.79  4065.2  464.89  4196.2  455.44  4493.9  440.98  4564.3  438.14
  4706.1  437.07  4825.6  437.03  4848.4  435.40  4855.0  434.45  4857.4  432.98
  4860.1  432.48  4863.4  432.98  5068.4  433.26  5092.4  437.08  5358.8  436.29
  5410.3  438.12  5476.3  438.75  5536.6  441.25  5624.5  441.99  5675.9  444.06
  5734.4  444.63  5800.5  447.44  5948.5  450.76  5964.9  452.28  6008.8  451.16
  6025.1  453.22  6179.0  456.39  6195.3  457.84  6201.0  457.08  6279.4  458.74
#Mann=6,-1,0
  3996.8     0.1       0  4065.2    0.05       0  4493.9     0.1       0
  4706.1    0.05       0  4857.4   0.033       0  4863.4    0.05       0
Bank Sta=4857.4,4863.4
Exp/Cntr=0.3,0.1

Type RM Length L Ch R = 1,42055,981,981,981
BEGIN DESCRIPTION:
SMITH BRANCH 69.0
END DESCRIPTION:
XS GIS Cut Line= 3
      3540419.09     10339775.87      3539197.65     10339393.50
      3538464.68     10338984.81
#Sta/Elev= 30
  3996.9  465.83  4014.7  464.27  4061.6  461.92  4077.6  460.31  4158.9  454.91
  4213.8  450.08  4223.8  449.68  4229.1  450.39  4266.8  448.82  4294.0  446.63
  4299.2  447.06  4318.6  445.17  4358.9  444.22  4371.0  443.04  4444.3  440.00
  4511.3  438.18  4661.4  434.92  4772.0  434.23  4969.3  433.47  4998.7  432.39
  5001.5  431.89  5004.7  432.39  5052.1  433.22  5164.0  433.52  5188.3  435.15
  5201.7  434.55  5266.6  434.45  5636.1  436.28  5847.6  440.09  6116.0  442.90
#Mann=5,-1,0
  3996.9    0.05       0  4511.3     0.1       0  4772.0    0.05       0
  4998.7    0.03       0  5004.7    0.05       0
Bank Sta=4998.7,5004.7
Exp/Cntr=0.3,0.1

Type RM Length L Ch R = 1,41074,1044,1044,1044
BEGIN DESCRIPTION:
SMITH BRANCH 68.0
END DESCRIPTION:
XS GIS Cut Line= 3
      3540834.25     10338901.43      3540302.73     10338775.40
      3539069.57     10338310.06
#Sta/Elev= 30
  4100.1  464.78  4166.7  462.24  4215.3  459.19  4246.0  457.52  4277.0  457.04
  4335.6  454.97  4420.0  450.95  4441.5  451.12  4451.7  449.21  4487.8  447.37
  4523.7  445.94  4544.2  445.77  4569.0  444.12  4727.5  437.59  4873.1  435.39
  4996.7  431.21  4999.5  430.71  5002.7  431.21  5093.3  433.11  5148.4  432.73
  5178.5  433.20  5214.1  432.50  5269.1  433.00  5404.1  435.70  5549.7  440.09
  5720.2  448.20  5812.0  451.72  5860.5  452.60  5920.8  455.34  5964.4  455.79
#Mann=6,-1,0
  4100.1     0.1       0  4215.3    0.05       0  4487.8     0.1       0
  4569.0    0.05       0  4996.7    0.03       0  5002.7    0.05       0
Bank Sta=4996.7,5002.7
Exp/Cntr=0.3,0.1

Type RM Length L Ch R = 1,40030,884,884,884
BEGIN DESCRIPTION:
SMITH BRANCH 67.0
END DESCRIPTION:
XS GIS Cut Line= 3
      3541233.38     10338216.99      3540186.40     10337612.07
      3539535.97     10337519.15
#Sta/Elev= 30
  4141.3  460.60  4182.6  459.16  4219.9  460.54  4269.8  458.78  4300.3  459.01
  4316.0  457.67  4321.8  458.50  4359.2  457.68  4535.4  451.54  4621.1  446.93
  4772.7  438.60  4832.8  435.45  4944.3  430.74  4959.3  428.96  4983.4  428.42
  5029.1  427.73  5031.8  427.23  5035.1  427.73  5067.0  433.11  5167.4  435.69
  5194.1  436.30  5496.2  447.24  5601.6  453.32  5683.7  460.73  5743.1  466.33
  5805.7  474.33  5874.2  482.56  5921.0  487.19  5950.1  490.39  6007.5  491.15
#Mann=14,-1,0
  4141.3    0.05       0  4621.1     0.1       0  4772.7    0.12       0
  4832.8     0.1       0  4944.3    0.05       0  4983.4    0.12       0
  5029.1    0.07       0  5035.1    0.12       0  5167.4     0.1       0
  5194.1    0.05       0  5683.7    0.16       0  5805.7    0.05       0
  5874.2    0.16       0  5921.0    0.05       0
Bank Sta=5029.1,5035.1
Exp/Cntr=0.3,0.1

Type RM Length L Ch R = 1,39146,307,307,307
BEGIN DESCRIPTION:
SMITH BRANCH 66.0
END DESCRIPTION:
XS GIS Cut Line= 3
      3541652.18     10337542.26      3540605.20     10336844.27
      3540046.98     10336681.46
#Sta/Elev= 30
  4096.6  470.28  4197.8  462.63  4327.1  454.42  4486.3  446.62  4522.4  443.35
  4543.4  443.29  4637.5  437.82  4671.8  437.13  4694.5  436.70  4745.7  434.68
  4841.2  433.64  4889.9  431.83  4913.0  429.71  4925.8  427.02  4962.0  428.59
  5003.1  425.73  5005.9  425.23  5009.1  425.73  5029.4  427.51  5041.5  428.35
  5171.4  434.26  5315.6  446.54  5353.8  450.98  5483.1  462.52  5561.0  472.04
  5618.6  480.33  5712.3  489.75  5777.5  492.66  5820.7  492.03  5936.4  488.38
#Mann=11,-1,0
  4096.6    0.16       0  4197.8     0.1       0  4671.8    0.05       0
  4694.5     0.1       0  4841.2    0.16       0  4925.8    0.12       0
  5003.1    0.07       0  5009.1    0.12       0  5029.4    0.16       0
  5041.5    0.05       0  5820.7     0.1       0
Bank Sta=5003.1,5009.1
Exp/Cntr=0.3,0.1

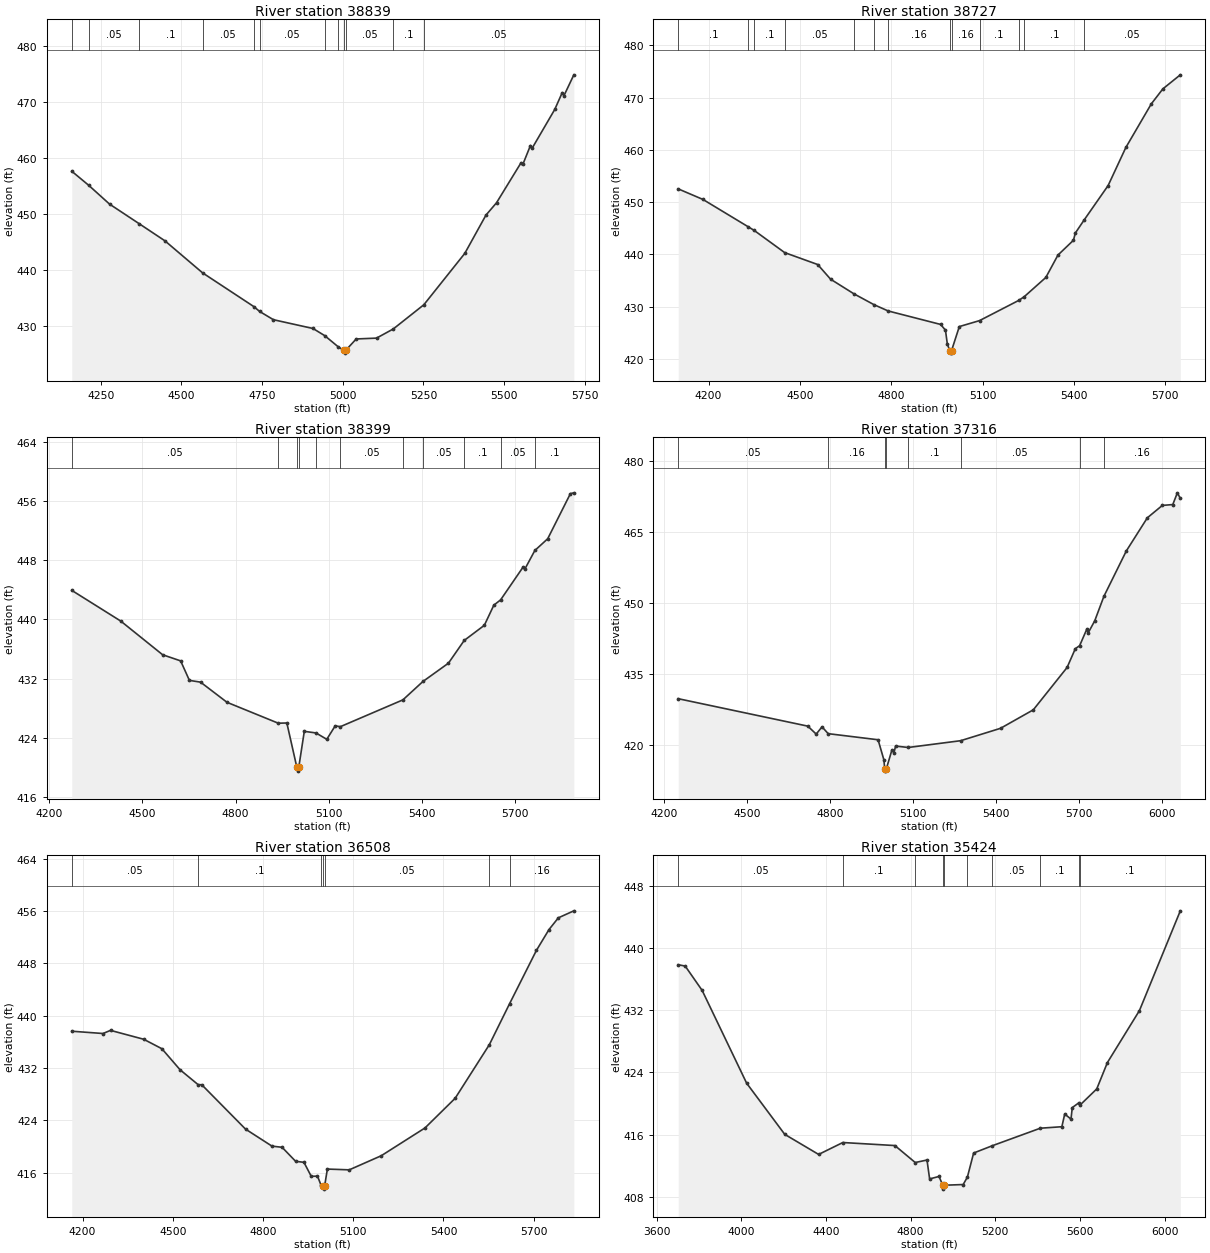
Type RM Length L Ch R = 1,38839,112,112,112
BEGIN DESCRIPTION:
Mapping XS 0c2ede12
END DESCRIPTION:
XS GIS Cut Line= 3
      3541819.04     10337287.42      3541310.34     10336917.61
      3540463.14     10336542.62
#Sta/Elev= 30
  4160.6  457.63  4212.6  455.14  4277.6  451.76  4369.1  448.27  4449.2  445.20
  4565.8  439.48  4725.2  433.43  4742.4  432.59  4785.3  431.11  4907.9  429.54
  4944.3  428.26  4984.9  426.32  5003.3  425.64  5006.1  425.14  5009.3  425.64
  5041.8  427.67  5104.7  427.82  5156.7  429.46  5251.3  433.78  5378.1  442.95
  5443.7  449.79  5476.5  452.00  5552.7  459.17  5558.2  458.88  5581.5  462.22
  5586.9  461.75  5656.8  468.66  5680.1  471.68  5685.6  471.15  5716.0  474.85
#Mann=12,-1,0
  4160.6     0.1       0  4212.6    0.05       0  4369.1     0.1       0
  4565.8    0.05       0  4725.2     0.1       0  4742.4    0.05       0
  4944.3    0.16       0  4984.9    0.05       0  5003.3    0.04       0
  5009.3    0.05       0  5156.7     0.1       0  5251.3    0.05       0
Bank Sta=5003.3,5009.3
Exp/Cntr=0.3,0.1

Type RM Length L Ch R = 1,38727,328,328,328
BEGIN DESCRIPTION:
Mapping XS 9f3c47e3
END DESCRIPTION:
XS GIS Cut Line= 3
      3541952.67     10337191.89      3541386.73     10336836.01
      3540500.43     10336416.28
#Sta/Elev= 30
  4100.4  452.54  4181.6  450.52  4330.5  445.28  4350.0  444.59  4450.0  440.35
  4558.5  438.07  4600.9  435.26  4677.7  432.46  4743.7  430.38  4790.3  429.18
  4962.2  426.61  4978.2  425.51  4984.3  422.86  4992.3  421.62  4995.1  421.12
  4998.3  421.62  5023.7  426.20  5090.1  427.34  5219.4  431.22  5237.4  431.94
  5307.8  435.59  5347.7  439.88  5398.7  442.72  5404.7  444.09  5434.0  446.62
  5512.5  453.18  5570.7  460.46  5654.5  468.82  5692.4  471.68  5749.6  474.36
#Mann=13,-1,0
  4100.4     0.1       0  4330.5    0.05       0  4350.0     0.1       0
  4450.0    0.05       0  4677.7    0.16       0  4743.7    0.05       0
  4790.3    0.16       0  4992.3    0.07       0  4998.3    0.16       0
  5090.1     0.1       0  5219.4    0.05       0  5237.4     0.1       0
  5434.0    0.05       0
Bank Sta=4992.3,4998.3
Exp/Cntr=0.3,0.1

Type RM Length L Ch R = 1,38399,1083,1083,1083
BEGIN DESCRIPTION:
SMITH BRANCH 65.0
END DESCRIPTION:
XS GIS Cut Line= 3
      3542001.20     10336983.88      3541097.11     10336281.17
      3540697.08     10336031.15
#Sta/Elev= 30
  4272.5  443.94  4430.3  439.78  4565.1  435.22  4623.1  434.39  4651.3  431.75
  4687.3  431.51  4772.4  428.78  4937.5  425.95  4965.1  425.98  4997.4  419.96
  5000.2  419.46  5003.4  419.96  5021.3  424.85  5058.9  424.63  5093.7  423.77
  5120.8  425.59  5137.4  425.48  5338.8  429.11  5403.3  431.60  5485.5  434.08
  5536.3  437.16  5601.1  439.21  5631.7  441.94  5653.4  442.65  5726.1  447.11
  5732.0  446.86  5763.7  449.34  5805.1  450.93  5878.2  457.04  5889.3  457.15
#Mann=11,-1,0
  4272.5    0.05       0  4937.5    0.16       0  4997.4    0.07       0
  5003.4    0.16       0  5058.9     0.1       0  5137.4    0.05       0
  5338.8     0.1       0  5403.3    0.05       0  5536.3     0.1       0
  5653.4    0.05       0  5763.7     0.1       0
Bank Sta=4997.4,5003.4
Exp/Cntr=0.3,0.1

Type RM Length L Ch R = 1,37316,808,808,808
BEGIN DESCRIPTION:
SMITH BRANCH 64.0
END DESCRIPTION:
XS GIS Cut Line= 3
      3542652.67     10336239.35      3541675.46     10335611.14
      3541072.24     10335355.93
#Sta/Elev= 30
  4251.1  429.75  4719.9  423.95  4750.3  422.27  4771.4  423.80  4793.7  422.36
  4974.2  421.07  4995.3  416.81  4998.2  414.94  5001.0  414.44  5004.2  414.94
  5024.5  418.96  5031.6  418.31  5037.6  419.74  5083.3  419.44  5272.8  420.87
  5417.3  423.49  5535.9  427.40  5658.1  436.35  5687.9  440.32  5703.5  440.96
  5729.1  444.40  5734.6  443.68  5758.2  446.22  5791.4  451.40  5872.5  460.99
  5948.5  467.99  6002.8  470.61  6040.6  470.79  6057.1  473.27  6067.8  472.10
#Mann=8,-1,0
  4251.1    0.05       0  4793.7    0.16       0  4998.2    0.07       0
  5004.2    0.16       0  5083.3     0.1       0  5272.8    0.05       0
  5703.5     0.1       0  5791.4    0.16       0
Bank Sta=4998.2,5004.2
Exp/Cntr=0.3,0.1

Type RM Length L Ch R = 1,36508,1084,1084,1084
BEGIN DESCRIPTION:
SMITH BRANCH 63.0
END DESCRIPTION:
XS GIS Cut Line= 3
      3543106.96     10335382.16      3542706.97     10335232.17
      3541512.63     10334889.89
#Sta/Elev= 30
  4164.0  437.63  4267.9  437.28  4292.8  437.76  4403.2  436.40  4463.7  434.95
  4524.2  431.73  4584.3  429.45  4596.3  429.44  4741.9  422.65  4829.7  420.05
  4863.4  419.87  4908.3  417.73  4936.1  417.57  4960.3  415.43  4981.1  415.46
  4992.8  414.09  4998.9  413.97  5001.7  413.47  5004.9  413.97  5014.0  416.54
  5086.7  416.42  5193.2  418.58  5338.6  422.83  5438.9  427.37  5552.6  435.57
  5619.8  441.83  5709.3  450.01  5750.9  453.18  5782.1  454.98  5833.6  456.05
#Mann=7,-1,0
  4164.0    0.05       0  4584.3     0.1       0  4992.8    0.05       0
  4998.9    0.03       0  5004.9    0.05       0  5552.6     0.1       0
  5619.8    0.16       0
Bank Sta=4998.9,5004.9
Exp/Cntr=0.3,0.1

Type RM Length L Ch R = 1,35424,71,71,71
BEGIN DESCRIPTION:
Mapping XS d9686384
END DESCRIPTION:
XS GIS Cut Line= 3
      3543985.01     10334292.26      3542815.77     10334333.93
      3541835.99     10333637.43
#Sta/Elev= 30
  3702.5  437.83  3735.4  437.66  3815.5  434.53  4025.6  422.61  4205.7  416.03
  4365.8  413.45  4480.2  414.98  4726.1  414.59  4822.2  412.41  4877.8  412.73
  4890.2  410.30  4934.5  410.62  4952.4  409.49  4955.2  408.99  4958.4  409.49
  5048.7  409.58  5068.6  410.53  5098.1  413.63  5186.5  414.57  5413.2  416.82
  5515.0  417.01  5528.5  418.64  5558.1  417.99  5564.2  419.47  5596.4  420.11
  5600.7  419.79  5679.8  421.87  5730.2  425.26  5881.5  431.94  6074.6  444.76
#Mann=10,-1,0
  3702.5    0.05       0  4480.2     0.1       0  4822.2    0.05       0
  4952.4    0.03       0  4958.4    0.05       0  5068.6     0.1       0
  5186.5    0.05       0  5413.2     0.1       0  5596.4    0.05       0
  5600.7     0.1       0
Bank Sta=4952.4,4958.4
Exp/Cntr=0.3,0.1

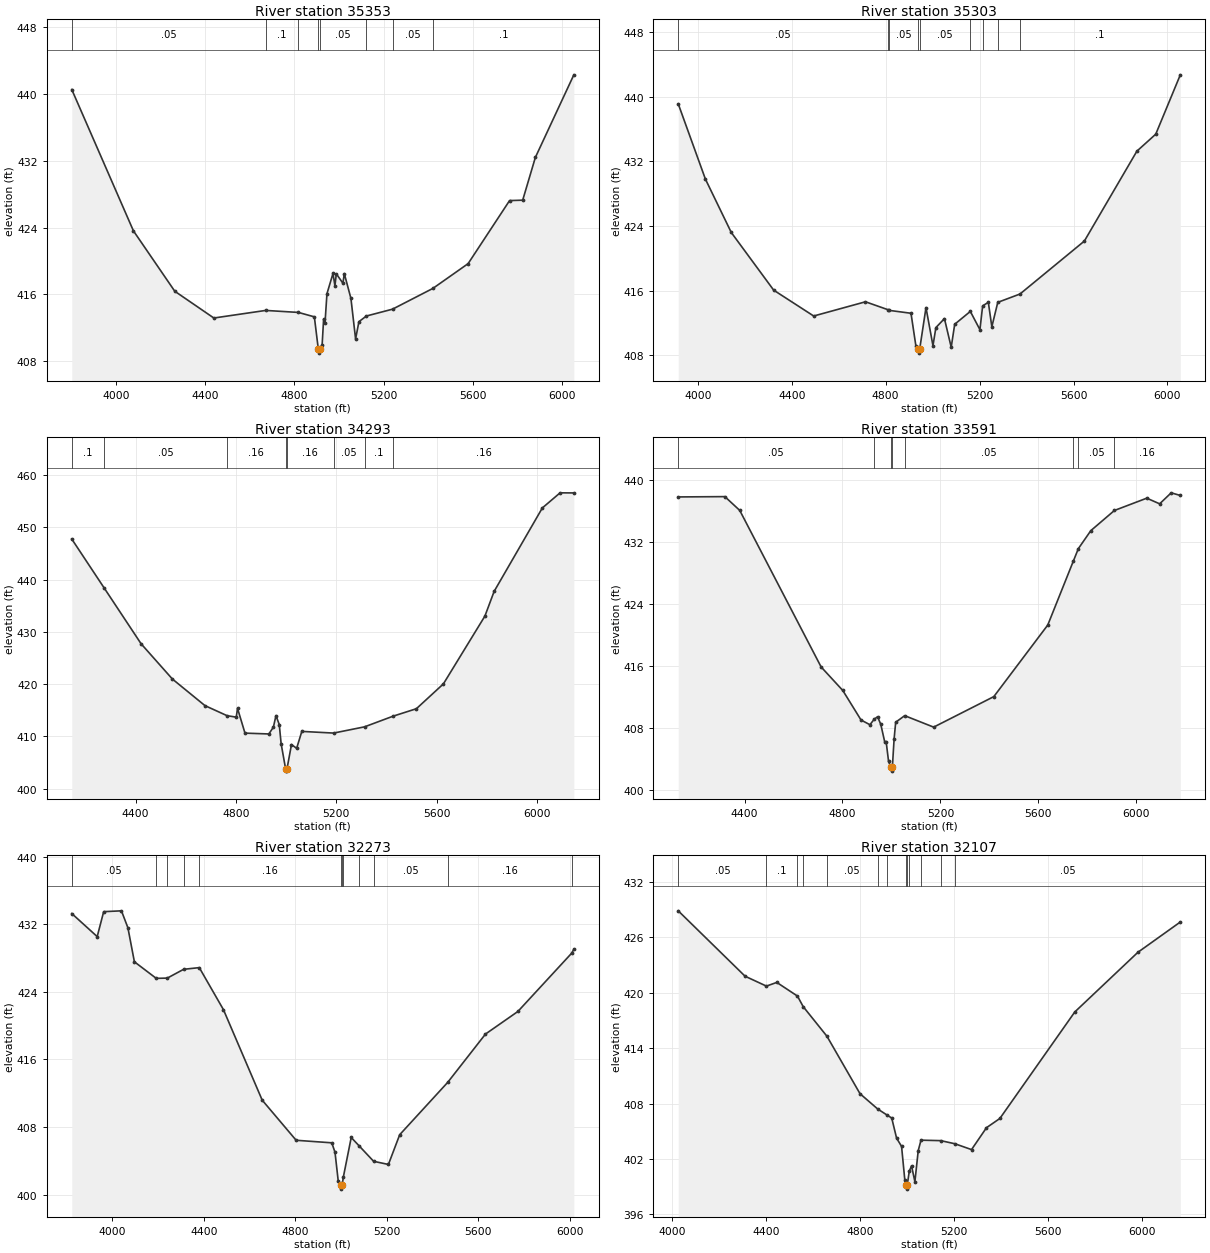
Type RM Length L Ch R = 1,35353,50,50,50
BEGIN DESCRIPTION:
Mapping XS d493fc30
END DESCRIPTION:
XS GIS Cut Line= 3
      3543938.21     10334232.37      3542844.41     10334266.22
      3541895.50     10333608.48
#Sta/Elev= 30
  3802.8  440.56  4079.0  423.61  4264.2  416.37  4439.2  413.16  4671.5  414.07
  4818.0  413.83  4889.4  413.30  4907.0  409.45  4909.7  408.95  4913.0  409.45
  4924.3  409.97  4930.9  413.03  4937.0  412.51  4945.8  416.07  4972.9  418.51
  4981.6  417.01  4987.7  418.46  5017.4  417.33  5023.5  418.49  5053.2  415.51
  5074.1  410.65  5089.0  412.72  5122.5  413.40  5239.5  414.22  5420.3  416.71
  5578.1  419.68  5763.8  427.24  5822.6  427.29  5879.4  432.42  6051.7  442.32
#Mann=8,-1,0
  3802.8    0.05       0  4671.5     0.1       0  4818.0    0.05       0
  4907.0    0.03       0  4913.0    0.05       0  5122.5     0.1       0
  5239.5    0.05       0  5420.3     0.1       0
Bank Sta=4907,4913
Exp/Cntr=0.3,0.1

Type RM Length L Ch R = 1,35303,1010,1010,1010
BEGIN DESCRIPTION:
SMITH BRANCH 62.0
END DESCRIPTION:
XS GIS Cut Line= 3
      3543857.43     10334153.37      3542871.32     10334224.55
      3541926.11     10333570.71
#Sta/Elev= 30
  3916.8  439.12  4032.4  429.82  4142.7  423.21  4323.2  416.08  4493.6  412.88
  4714.2  414.64  4811.0  413.65  4814.5  413.58  4908.0  413.22  4928.8  409.18
  4939.0  408.79  4941.8  408.29  4945.0  408.79  4971.8  413.92  5001.5  409.21
  5014.0  411.45  5050.4  412.56  5079.2  409.02  5094.1  411.86  5160.6  413.45
  5201.5  411.19  5213.1  414.14  5237.3  414.57  5252.2  411.55  5277.5  414.57
  5372.0  415.60  5646.2  422.15  5869.9  433.27  5950.2  435.37  6054.8  442.71
#Mann=9,-1,0
  3916.8    0.05       0  4811.0     0.1       0  4814.5    0.05       0
  4939.0    0.03       0  4945.0    0.05       0  5160.6     0.1       0
  5213.1    0.16       0  5277.5    0.05       0  5372.0     0.1       0
Bank Sta=4939,4945
Exp/Cntr=0.3,0.1

Type RM Length L Ch R = 1,34293,702,702,702
BEGIN DESCRIPTION:
SMITH BRANCH 61.0
END DESCRIPTION:
XS GIS Cut Line= 3
      3543932.35     10333703.29      3542606.13     10333377.55
      3541977.93     10333284.48
#Sta/Elev= 30
  4146.0  447.75  4275.5  438.36  4422.3  427.71  4546.9  420.97  4676.8  415.88
  4765.2  413.95  4801.4  413.68  4806.6  415.35  4836.2  410.62  4931.3  410.46
  4949.4  411.75  4959.7  413.97  4972.8  412.27  4980.3  408.58  4997.9  403.85
  5000.7  403.35  5003.9  403.85  5021.5  408.44  5042.1  407.71  5062.7  410.95
  5189.3  410.63  5312.5  411.82  5426.9  413.87  5519.3  415.29  5626.9  420.04
  5792.3  433.01  5829.1  437.74  6021.2  453.70  6091.9  456.59  6146.7  456.57
#Mann=8,-1,0
  4146.0     0.1       0  4275.5    0.05       0  4765.2    0.16       0
  4997.9    0.07       0  5003.9    0.16       0  5189.3    0.05       0
  5312.5     0.1       0  5426.9    0.16       0
Bank Sta=4997.9,5003.9
Exp/Cntr=0.3,0.1

Type RM Length L Ch R = 1,33591,1318,1318,1318
BEGIN DESCRIPTION:
SMITH BRANCH 60.0
END DESCRIPTION:
XS GIS Cut Line= 3
      3544025.38     10333284.48      3542880.24     10332693.11
      3542180.24     10332393.11
#Sta/Elev= 30
  4129.2  437.81  4319.6  437.85  4380.4  436.07  4712.7  415.86  4801.3  412.82
  4875.7  409.01  4912.1  408.40  4928.9  409.09  4943.2  409.43  4956.4  408.45
  4972.9  406.12  4978.5  406.16  4988.2  403.66  4997.7  402.91  5000.4  402.41
  5003.7  402.91  5010.7  406.53  5017.2  408.72  5054.0  409.57  5172.3  408.09
  5418.0  412.03  5638.3  421.27  5742.3  429.49  5763.3  431.14  5814.2  433.46
  5910.4  436.06  6042.6  437.65  6095.2  436.92  6142.4  438.34  6179.6  438.00
#Mann=8,-1,0
  4129.2    0.05       0  4928.9    0.16       0  4997.7    0.07       0
  5003.7    0.16       0  5054.0    0.05       0  5742.3     0.1       0
  5763.3    0.05       0  5910.4    0.16       0
Bank Sta=4997.7,5003.7
Exp/Cntr=0.3,0.1

Type RM Length L Ch R = 1,32273,166,166,166
BEGIN DESCRIPTION:
SMITH BRANCH 59.0
END DESCRIPTION:
XS GIS Cut Line= 2
      3544244.94     10332835.83      3542742.18     10331235.50
#Sta/Elev= 30
  3823.2  433.26  3934.4  430.53  3962.7  433.48  4040.4  433.58  4068.7  431.57
  4097.0  427.55  4192.5  425.59  4240.9  425.62  4312.3  426.66  4380.8  426.86
  4486.3  421.89  4655.8  411.18  4804.3  406.43  4960.1  406.13  4974.2  405.01
  4988.4  401.58  4999.6  401.15  5002.3  400.65  5005.6  401.15  5010.9  402.11
  5045.1  406.76  5080.3  405.75  5143.1  403.94  5207.7  403.57  5257.1  407.09
  5467.2  413.29  5632.2  419.00  5773.8  421.67  6008.7  428.56  6018.5  429.03
#Mann=12,-1,0
  3823.2    0.05       0  4192.5     0.1       0  4240.9    0.16       0
  4312.3     0.1       0  4380.8    0.16       0  4999.6    0.07       0
  5005.6    0.16       0  5010.9    0.05       0  5080.3    0.16       0
  5143.1    0.05       0  5467.2    0.16       0  6008.7    0.05       0
Bank Sta=4999.6,5005.6
Exp/Cntr=0.3,0.1

Type RM Length L Ch R = 1,32107,1242,1242,1242
BEGIN DESCRIPTION:
SMITH BRANCH 58.0
END DESCRIPTION:
XS GIS Cut Line= 3
      3544305.75     10332579.80      3543656.84     10332026.38
      3542817.08     10331052.09
#Sta/Elev= 30
  4025.6  428.86  4310.4  421.78  4401.3  420.71  4445.5  421.11  4533.6  419.63
  4557.9  418.49  4659.2  415.28  4800.1  409.06  4875.2  407.41  4915.2  406.75
  4935.1  406.43  4956.0  404.24  4977.1  403.36  4991.1  399.68  4995.7  399.23
  4998.5  398.73  5001.7  399.23  5009.9  400.67  5019.6  401.25  5033.9  399.53
  5048.1  402.90  5059.9  404.03  5144.1  403.98  5204.6  403.64  5275.2  403.01
  5338.9  405.38  5395.9  406.38  5715.1  417.91  5984.0  424.37  6164.7  427.65
#Mann=13,-1,0
  4025.6    0.05       0  4401.3     0.1       0  4533.6    0.05       0
  4557.9     0.1       0  4659.2    0.05       0  4875.2    0.16       0
  4915.2    0.05       0  4995.7    0.04       0  5001.7    0.05       0
  5009.9    0.16       0  5059.9    0.05       0  5144.1    0.16       0
  5204.6    0.05       0
Bank Sta=4995.7,5001.7
Exp/Cntr=0.3,0.1

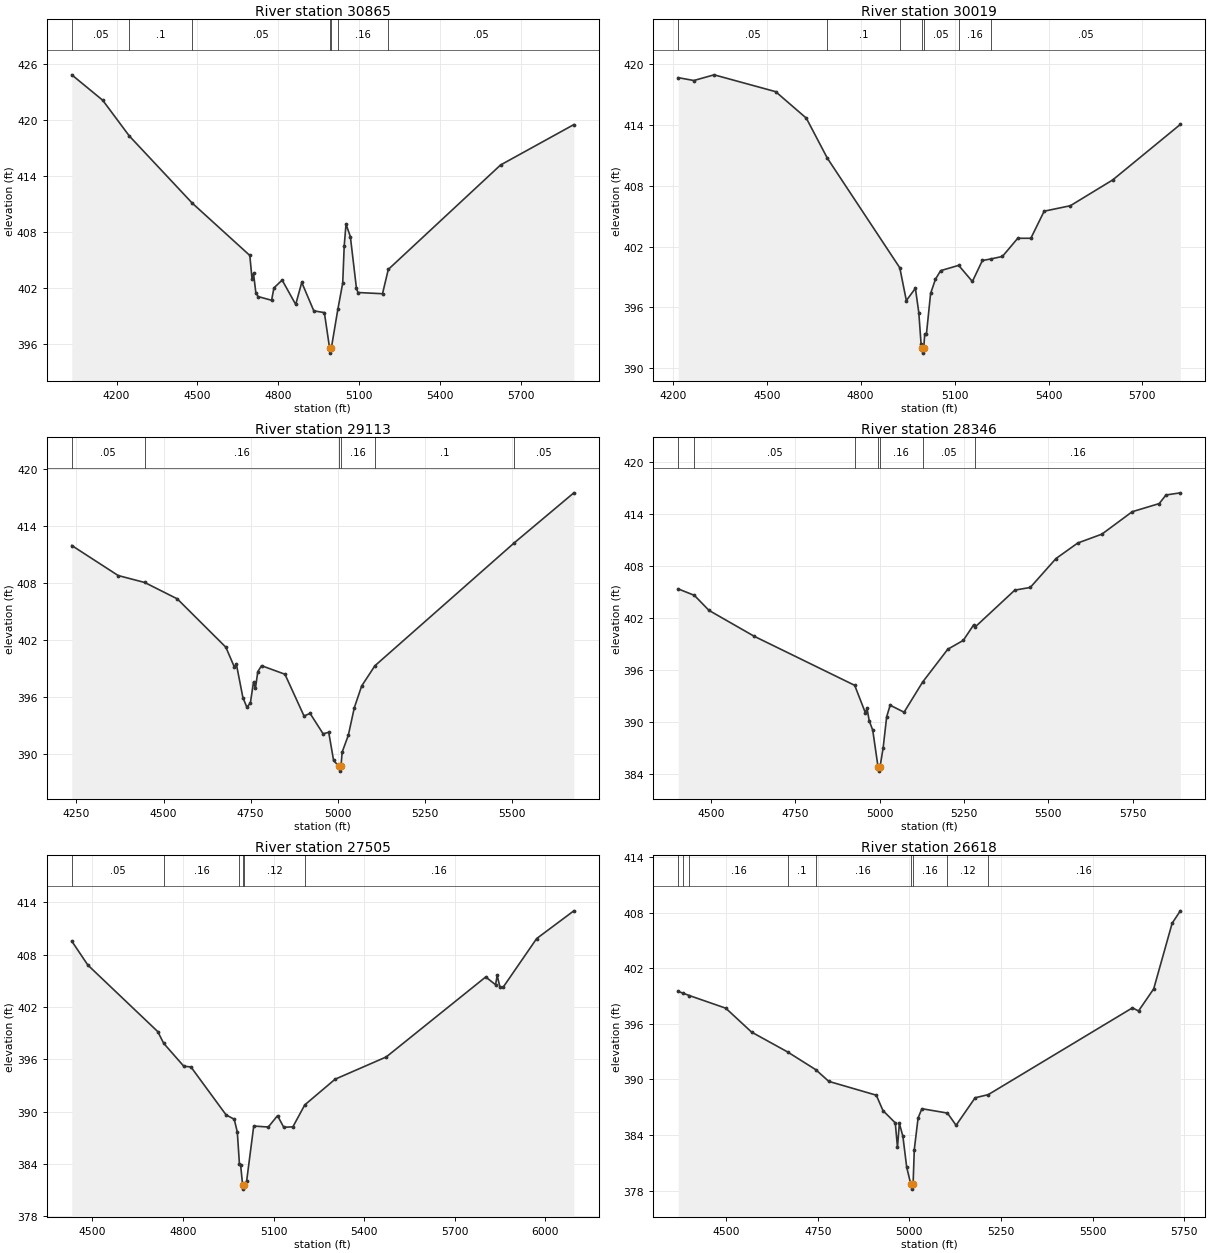
Type RM Length L Ch R = 1,30865,846,846,846
BEGIN DESCRIPTION:
SMITH BRANCH 57.0
END DESCRIPTION:
XS GIS Cut Line= 3
      3544793.23     10331516.24      3543942.11     10331091.64
      3543117.98     10330701.89
#Sta/Elev= 30
  4033.8  424.81  4148.7  422.09  4247.1  418.28  4480.6  411.10  4694.4  405.50
  4702.5  403.03  4708.1  403.58  4716.7  401.53  4724.8  401.11  4775.2  400.71
  4783.8  402.03  4814.3  402.87  4864.7  400.26  4887.1  402.62  4931.8  399.58
  4971.0  399.39  4990.6  395.56  4993.3  395.06  4996.6  395.56  5021.0  399.74
  5039.1  402.56  5044.6  406.52  5051.3  408.84  5067.4  407.52  5090.1  401.97
  5095.7  401.54  5186.7  401.41  5208.2  404.01  5624.6  415.17  5896.6  419.49
#Mann=7,-1,0
  4033.8    0.05       0  4247.1     0.1       0  4480.6    0.05       0
  4990.6    0.03       0  4996.6    0.05       0  5021.0    0.16       0
  5208.2    0.05       0
Bank Sta=4990.6,4996.6
Exp/Cntr=0.3,0.1

Type RM Length L Ch R = 1,30019,906,906,906
BEGIN DESCRIPTION:
SMITH BRANCH 55.0
END DESCRIPTION:
XS GIS Cut Line= 3
      3545017.95     10330703.83      3544292.11     10330391.64
      3543517.99     10330141.35
#Sta/Elev= 30
  4217.3  418.65  4267.2  418.37  4331.9  418.93  4528.5  417.27  4626.4  414.66
  4693.5  410.72  4925.0  399.91  4945.9  396.68  4974.8  397.89  4985.7  395.50
  4992.9  392.44  4995.4  392.00  4998.1  391.50  5001.4  392.00  5004.7  393.39
  5010.1  393.39  5023.4  397.38  5039.0  398.79  5055.5  399.63  5113.1  400.15
  5156.8  398.56  5188.8  400.63  5215.6  400.78  5252.8  401.03  5301.7  402.82
  5343.6  402.82  5386.1  405.49  5469.9  406.03  5605.0  408.57  5821.0  414.04
#Mann=7,-1,0
  4217.3    0.05       0  4693.5     0.1       0  4925.0    0.05       0
  4995.4   0.035       0  5001.4    0.05       0  5113.1    0.16       0
  5215.6    0.05       0
Bank Sta=4995.4,5001.4
Exp/Cntr=0.3,0.1

Type RM Length L Ch R = 1,29113,767,767,767
BEGIN DESCRIPTION:
SMITH BRANCH 53.0
END DESCRIPTION:
XS GIS Cut Line= 3
      3545330.47     10329974.68      3544592.11     10329691.64
      3543956.31     10329558.18
#Sta/Elev= 30
  4236.8  411.96  4370.0  408.80  4446.1  408.07  4539.4  406.35  4678.9  401.26
  4703.6  399.15  4708.9  399.51  4727.7  395.97  4739.0  394.96  4749.1  395.38
  4758.3  397.62  4763.7  396.94  4770.5  398.69  4781.2  399.32  4848.4  398.42
  4903.1  394.03  4920.5  394.30  4957.8  392.16  4974.0  392.31  4987.9  389.36
  5003.1  388.73  5005.9  388.23  5009.1  388.73  5012.5  390.23  5030.1  391.99
  5047.4  394.90  5068.4  397.18  5106.4  399.31  5506.9  412.26  5677.2  417.50
#Mann=6,-1,0
  4236.8    0.05       0  4446.1    0.16       0  5003.1    0.07       0
  5009.1    0.16       0  5106.4     0.1       0  5506.9    0.05       0
Bank Sta=5003.1,5009.1
Exp/Cntr=0.3,0.1

Type RM Length L Ch R = 1,28346,841,841,841
BEGIN DESCRIPTION:
SMITH BRANCH 51.0
END DESCRIPTION:
XS GIS Cut Line= 3
      3545580.46     10329245.51      3544429.61     10328949.98
      3544129.60     10328949.98
#Sta/Elev= 30
  4402.8  405.39  4450.5  404.65  4494.0  402.91  4628.2  399.92  4925.9  394.26
  4957.3  391.11  4962.4  391.59  4968.9  390.17  4979.3  389.09  4995.0  384.86
  4997.8  384.36  5001.0  384.86  5010.2  387.06  5020.6  390.63  5030.9  391.97
  5072.2  391.16  5127.2  394.64  5201.8  398.43  5247.7  399.45  5278.1  401.22
  5283.5  401.02  5400.4  405.25  5446.3  405.56  5522.6  408.90  5587.1  410.69
  5658.5  411.71  5748.5  414.30  5828.5  415.24  5848.5  416.23  5891.0  416.48
#Mann=7,-1,0
  4402.8     0.1       0  4450.5    0.05       0  4925.9    0.16       0
  4995.0    0.07       0  5001.0    0.16       0  5127.2    0.05       0
  5283.5    0.16       0
Bank Sta=4995,5001
Exp/Cntr=0.3,0.1

Type RM Length L Ch R = 1,27505,887,887,887
BEGIN DESCRIPTION:
SMITH BRANCH 50.0
END DESCRIPTION:
XS GIS Cut Line= 3
      3545747.09     10328578.83      3544787.94     10328362.48
      3544137.96     10328562.47
#Sta/Elev= 30
  4431.6  409.55  4484.9  406.80  4716.4  399.18  4736.2  397.83  4802.9  395.20
  4826.3  395.13  4942.8  389.63  4969.8  389.13  4980.0  387.67  4987.1  383.97
  4991.1  383.85  4997.5  381.62  5000.3  381.12  5003.5  381.62  5010.8  382.01
  5034.4  388.35  5082.7  388.24  5113.3  389.54  5133.8  388.21  5164.1  388.26
  5203.6  390.78  5304.0  393.72  5473.3  396.27  5802.9  405.44  5835.6  404.55
  5840.9  405.61  5849.9  404.31  5860.4  404.25  5971.7  409.84  6094.9  413.02
#Mann=6,-1,0
  4431.6    0.05       0  4736.2    0.16       0  4987.1    0.12       0
  4997.5    0.07       0  5003.5    0.12       0  5203.6    0.16       0
Bank Sta=4997.5,5003.5
Exp/Cntr=0.3,0.1

Type RM Length L Ch R = 1,26618,829,829,829
BEGIN DESCRIPTION:
SMITH BRANCH 48.0
END DESCRIPTION:
XS GIS Cut Line= 3
      3545804.60     10328120.80      3545554.61     10327920.81
      3544542.13     10327641.65
#Sta/Elev= 30
  4369.1  399.49  4381.5  399.31  4399.8  399.04  4498.9  397.68  4569.3  395.10
  4667.5  392.96  4744.2  391.05  4780.1  389.78  4909.7  388.29  4927.9  386.63
  4961.5  385.30  4967.5  382.67  4972.7  385.24  4982.3  383.85  4992.7  380.51
  5004.1  378.65  5006.8  378.15  5010.1  378.65  5013.4  382.42  5023.8  385.84
  5034.2  386.83  5103.9  386.36  5127.5  385.04  5179.4  388.01  5215.3  388.35
  5608.9  397.72  5625.4  397.38  5666.9  399.77  5717.2  406.85  5739.5  408.19
#Mann=9,-1,0
  4369.1    0.16       0  4381.5     0.1       0  4399.8    0.16       0
  4667.5     0.1       0  4744.2    0.16       0  5004.1    0.07       0
  5010.1    0.16       0  5103.9    0.12       0  5215.3    0.16       0
Bank Sta=5004.1,5010.1
Exp/Cntr=0.3,0.1

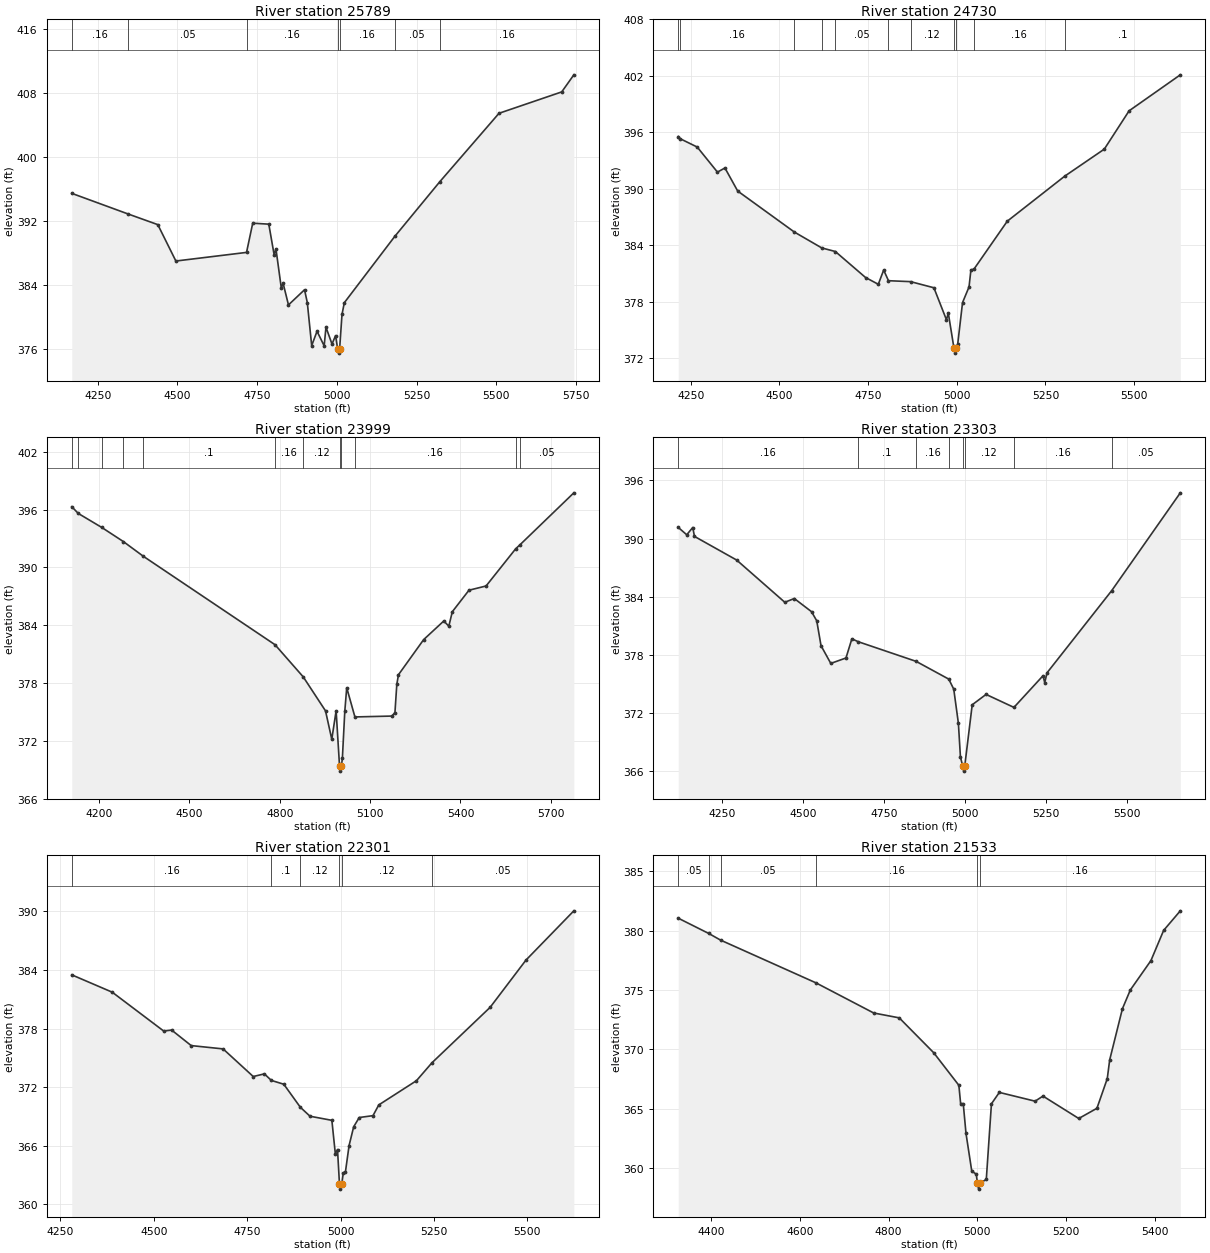
Type RM Length L Ch R = 1,25789,1059,1059,1059
BEGIN DESCRIPTION:
SMITH BRANCH 46.0
END DESCRIPTION:
XS GIS Cut Line= 3
      3546163.82     10327599.69      3545442.11     10327241.64
      3544706.78     10327016.74
#Sta/Elev= 30
  4168.5  395.47  4345.5  392.88  4438.3  391.55  4495.0  386.99  4716.6  388.07
  4736.0  391.73  4786.4  391.61  4803.3  387.74  4808.8  388.52  4825.7  383.59
  4831.2  384.22  4848.1  381.49  4898.5  383.39  4907.2  381.78  4920.9  376.39
  4937.7  378.19  4960.1  376.36  4965.7  378.70  4984.6  376.59  4995.8  377.64
  5002.5  375.95  5005.3  375.45  5008.5  375.95  5016.0  380.30  5023.3  381.77
  5181.4  390.07  5322.4  396.91  5508.4  405.50  5705.1  408.18  5743.1  410.32
#Mann=7,-1,0
  4168.5    0.16       0  4345.5    0.05       0  4716.6    0.16       0
  5002.5    0.07       0  5008.5    0.16       0  5181.4    0.05       0
  5322.4    0.16       0
Bank Sta=5002.5,5008.5
Exp/Cntr=0.3,0.1

Type RM Length L Ch R = 1,24730,731,731,731
BEGIN DESCRIPTION:
SMITH BRANCH 44.0
END DESCRIPTION:
XS GIS Cut Line= 3
      3546478.87     10327048.21      3545878.91     10326648.24
      3545218.27     10326432.30
#Sta/Elev= 30
  4214.4  395.56  4219.7  395.33  4268.0  394.44  4325.0  391.78  4346.1  392.22
  4382.1  389.77  4541.8  385.42  4619.2  383.73  4657.5  383.35  4742.7  380.59
  4778.7  379.87  4793.8  381.38  4807.4  380.25  4869.8  380.15  4935.5  379.50
  4970.9  376.10  4976.1  376.82  4992.2  373.06  4995.0  372.56  4998.2  373.06
  5002.7  373.53  5016.3  377.93  5034.6  379.59  5039.9  381.39  5048.5  381.48
  5142.5  386.57  5304.5  391.35  5416.1  394.22  5486.1  398.29  5630.5  402.11
#Mann=11,-1,0
  4214.4    0.05       0  4219.7    0.16       0  4541.8    0.05       0
  4619.2    0.16       0  4657.5    0.05       0  4807.4    0.16       0
  4869.8    0.12       0  4992.2    0.07       0  4998.2    0.12       0
  5048.5    0.16       0  5304.5     0.1       0
Bank Sta=4992.2,4998.2
Exp/Cntr=0.3,0.1

Type RM Length L Ch R = 1,23999,696,696,696
BEGIN DESCRIPTION:
SMITH BRANCH 42.0
END DESCRIPTION:
XS GIS Cut Line= 3
      3546909.81     10326928.79      3546259.81     10326128.80
      3545692.08     10325841.63
#Sta/Elev= 30
  4109.5  396.30  4131.2  395.60  4209.1  394.15  4280.6  392.69  4347.1  391.16
  4784.3  381.99  4878.1  378.65  4952.0  375.13  4972.8  372.18  4987.2  375.14
  4998.6  369.38  5001.3  368.88  5004.6  369.38  5008.0  370.22  5016.0  375.08
  5022.4  377.53  5049.6  374.50  5172.1  374.59  5182.5  374.95  5188.7  377.88
  5194.3  378.88  5277.9  382.52  5344.7  384.45  5361.4  383.91  5373.0  385.41
  5428.3  387.64  5485.1  388.08  5583.2  391.93  5597.6  392.35  5776.5  397.74
#Mann=12,-1,0
  4109.5     0.1       0  4131.2    0.05       0  4209.1     0.1       0
  4280.6    0.05       0  4347.1     0.1       0  4784.3    0.16       0
  4878.1    0.12       0  4998.6    0.07       0  5004.6    0.12       0
  5049.6    0.16       0  5583.2     0.1       0  5597.6    0.05       0
Bank Sta=4998.6,5004.6
Exp/Cntr=0.3,0.1

Type RM Length L Ch R = 1,23303,1002,1002,1002
BEGIN DESCRIPTION:
SMITH BRANCH 40.0
END DESCRIPTION:
XS GIS Cut Line= 3
      3547326.17     10326034.71      3546726.13     10325784.70
      3545851.96     10325581.61
#Sta/Elev= 30
  4115.7  391.15  4141.9  390.39  4160.4  391.14  4165.8  390.22  4295.8  387.78
  4444.2  383.42  4473.4  383.81  4526.5  382.45  4542.6  381.51  4555.8  378.94
  4585.9  377.11  4632.7  377.67  4650.9  379.65  4670.4  379.35  4849.0  377.32
  4949.5  375.49  4964.9  374.45  4979.2  370.93  4985.5  367.45  4992.7  366.49
  4995.5  365.99  4998.7  366.49  5021.8  372.84  5064.5  373.91  5150.4  372.57
  5240.1  375.84  5245.3  375.12  5252.4  376.14  5451.9  384.63  5663.2  394.72
#Mann=8,-1,0
  4115.7    0.16       0  4670.4     0.1       0  4849.0    0.16       0
  4949.5    0.12       0  4992.7    0.07       0  4998.7    0.12       0
  5150.4    0.16       0  5451.9    0.05       0
Bank Sta=4992.7,4998.7
Exp/Cntr=0.3,0.1

Type RM Length L Ch R = 1,22301,768,768,768
BEGIN DESCRIPTION:
SMITH BRANCH 39.0
END DESCRIPTION:
XS GIS Cut Line= 3
      3547197.46     10325564.25      3546381.49     10325069.46
      3545999.57     10324991.34
#Sta/Elev= 30
  4280.4  383.50  4388.8  381.72  4526.5  377.74  4547.8  377.84  4600.1  376.25
  4685.5  375.91  4766.2  373.08  4796.0  373.35  4814.7  372.68  4848.0  372.29
  4892.3  369.93  4918.2  369.01  4976.7  368.59  4985.9  365.19  4991.8  365.60
  4997.1  362.04  4999.8  361.54  5003.1  362.04  5007.3  363.20  5013.1  363.33
  5022.8  366.01  5035.1  367.93  5050.0  368.88  5086.8  369.07  5102.3  370.17
  5203.1  372.65  5244.7  374.49  5400.4  380.17  5496.3  385.01  5624.5  390.06
#Mann=6,-1,0
  4280.4    0.16       0  4814.7     0.1       0  4892.3    0.12       0
  4997.1    0.07       0  5003.1    0.12       0  5244.7    0.05       0
Bank Sta=4997.1,5003.1
Exp/Cntr=0.3,0.1

Type RM Length L Ch R = 1,21533,548,548,548
BEGIN DESCRIPTION:
SMITH BRANCH 37.0
END DESCRIPTION:
XS GIS Cut Line= 3
      3547442.09     10325041.63      3546942.11     10324641.64
      3546492.13     10324441.66
#Sta/Elev= 30
  4325.4  381.06  4394.2  379.77  4420.9  379.21  4636.3  375.60  4766.4  373.06
  4824.0  372.65  4901.7  369.71  4958.5  366.96  4962.5  365.41  4968.4  365.41
  4974.6  362.90  4987.6  359.72  4997.8  359.46  5000.3  358.70  5003.1  358.20
  5006.3  358.70  5020.4  359.02  5032.0  365.40  5049.8  366.36  5130.5  365.62
  5148.3  366.05  5229.0  364.16  5270.0  365.02  5293.3  367.52  5298.8  369.11
  5327.5  373.42  5345.3  375.00  5391.8  377.48  5420.5  380.03  5458.1  381.68
#Mann=6,-1,0
  4325.4    0.05       0  4394.2    0.16       0  4420.9    0.05       0
  4636.3    0.16       0  5000.3    0.07       0  5006.3    0.16       0
Bank Sta=5000.3,5006.3
Exp/Cntr=0.3,0.1