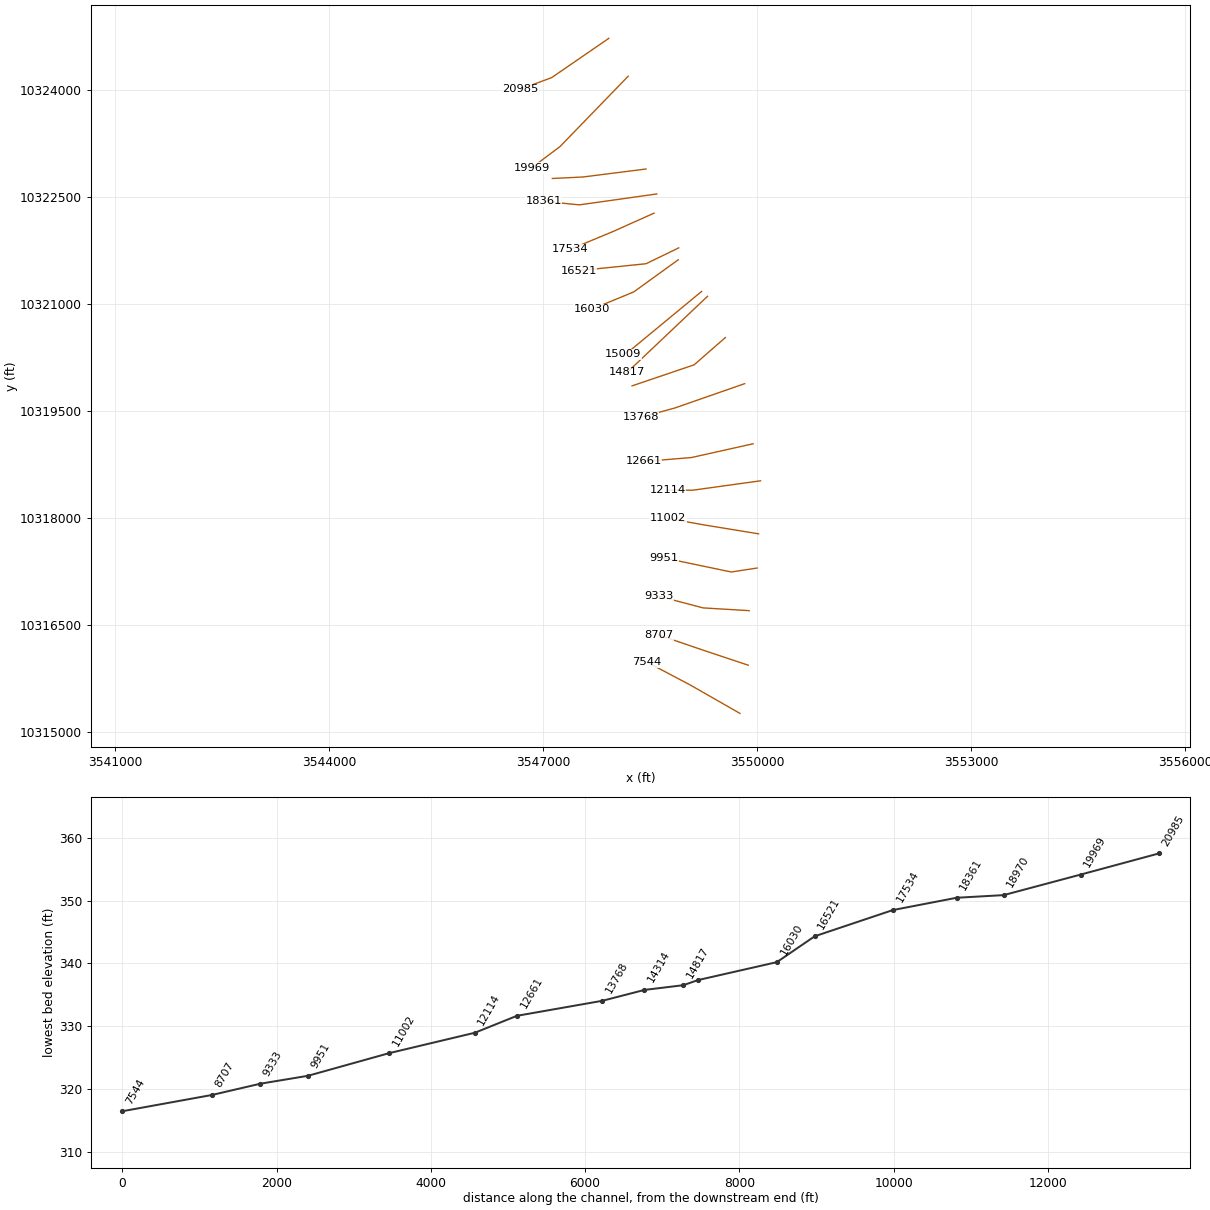
HEC-RAS study SMITH BRANCH.prj: SMITH BRANCH Base Level Engineering

--- SMITH BRANCH.g01 (geometry) --- (continued)

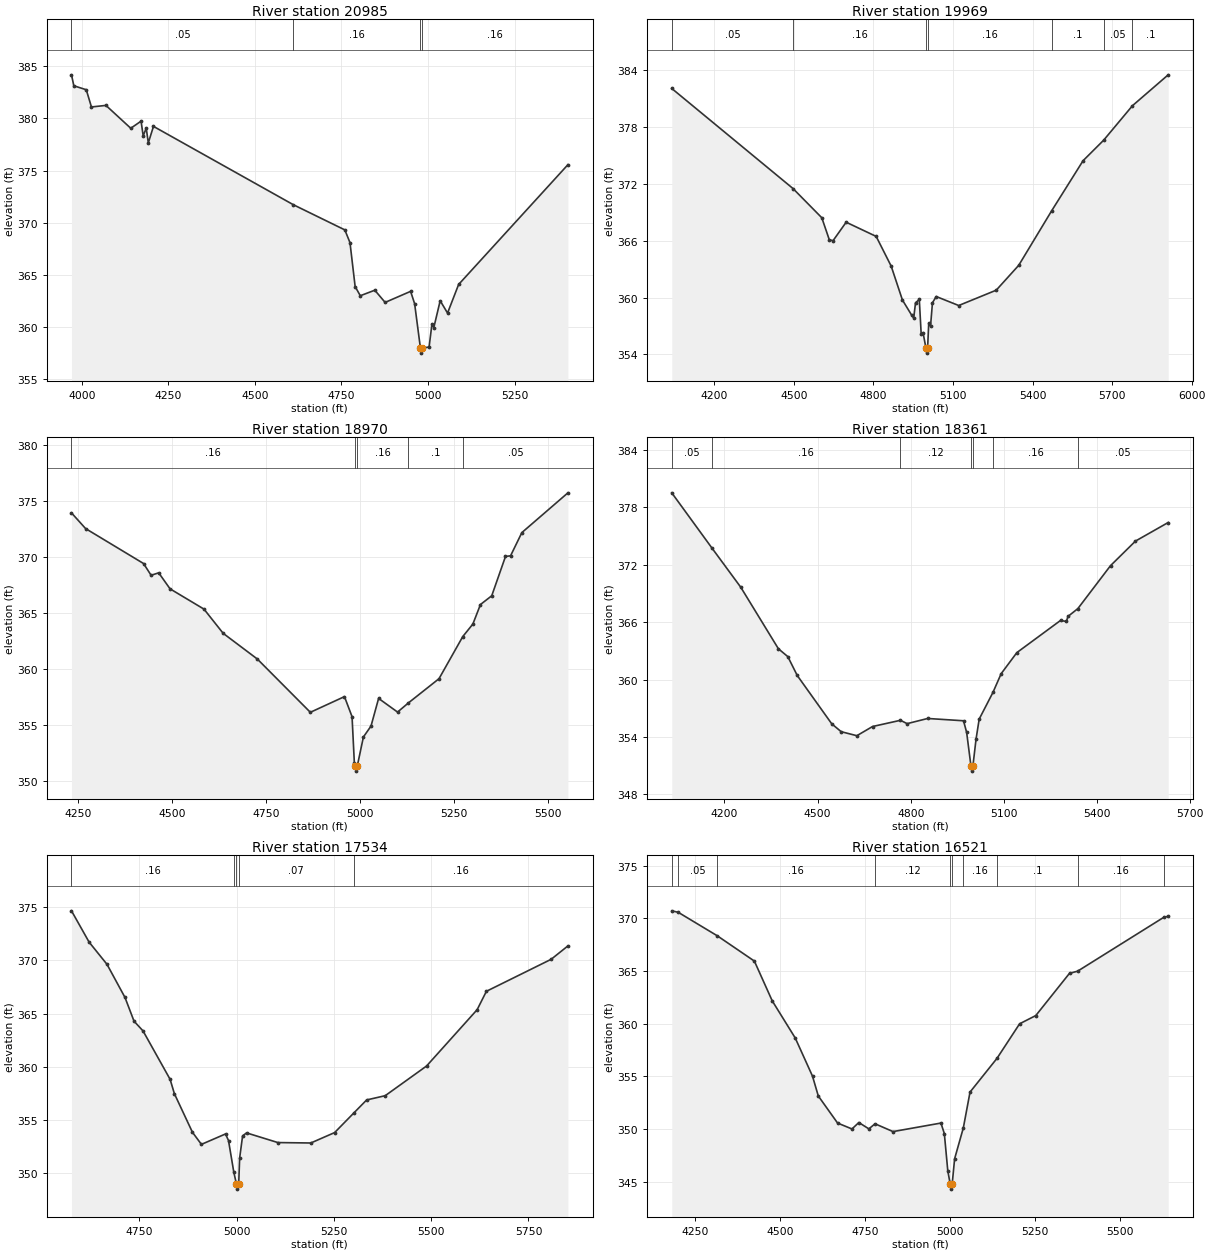
Type RM Length L Ch R = 1,20985,1016,1016,1016
BEGIN DESCRIPTION:
SMITH BRANCH 36.0
END DESCRIPTION:
XS GIS Cut Line= 3
      3547920.25     10324722.21      3547120.23     10324172.20
      3546686.22     10324010.77
#Sta/Elev= 30
  3970.3  384.17  3977.1  383.12  4013.0  382.74  4027.9  381.09  4069.8  381.24
  4141.5  379.05  4171.3  379.73  4177.4  378.32  4186.2  379.06  4192.2  377.65
  4207.1  379.23  4611.2  371.72  4759.8  369.31  4774.7  368.09  4789.6  363.88
  4804.5  363.00  4846.4  363.53  4876.2  362.36  4949.8  363.42  4961.4  362.24
  4978.1  358.00  4980.9  357.50  4984.1  358.00  5003.2  358.08  5011.5  360.31
  5016.8  359.94  5035.2  362.52  5056.5  361.34  5088.5  364.08  5404.2  375.56
#Mann=4,-1,0
  3970.3    0.05       0  4611.2    0.16       0  4978.1    0.07       0
  4984.1    0.16       0
Bank Sta=4978.1,4984.1
Exp/Cntr=0.3,0.1

Type RM Length L Ch R = 1,19969,999,999,999
BEGIN DESCRIPTION:
SMITH BRANCH 34.0
END DESCRIPTION:
XS GIS Cut Line= 3
      3548192.11     10324191.64      3547235.86     10323205.18
      3546837.43     10322906.37
#Sta/Elev= 30
  4039.6  382.09  4496.7  371.52  4605.4  368.43  4633.7  366.10  4647.8  366.01
  4697.2  367.96  4810.4  366.46  4867.0  363.32  4909.4  359.74  4944.9  358.11
  4951.9  357.85  4958.8  359.45  4973.0  359.80  4980.2  356.10  4987.1  356.30
  4998.3  354.63  5001.0  354.13  5004.3  354.63  5008.5  357.26  5015.4  356.99
  5022.6  359.45  5036.8  360.11  5121.6  359.16  5263.1  360.78  5348.0  363.41
  5472.6  369.19  5590.6  374.46  5668.0  376.62  5776.8  380.27  5911.5  383.53
#Mann=7,-1,0
  4039.6    0.05       0  4496.7    0.16       0  4998.3    0.07       0
  5004.3    0.16       0  5472.6     0.1       0  5668.0    0.05       0
  5776.8     0.1       0
Bank Sta=4998.3,5004.3
Exp/Cntr=0.3,0.1

Type RM Length L Ch R = 1,18970,609,609,609
BEGIN DESCRIPTION:
SMITH BRANCH 32.0
END DESCRIPTION:
XS GIS Cut Line= 3
      3548442.14     10322891.65      3547560.31     10322779.53
      3547129.74     10322758.70
#Sta/Elev= 30
  4232.3  373.91  4269.8  372.51  4423.9  369.39  4444.0  368.34  4464.2  368.56
  4494.4  367.13  4584.6  365.32  4635.6  363.16  4726.3  360.87  4867.4  356.11
  4958.1  357.51  4978.3  355.72  4984.4  351.61  4986.5  351.36  4989.2  350.86
  4992.5  351.36  5008.5  353.91  5028.7  354.88  5048.9  357.35  5099.3  356.13
  5128.2  356.95  5209.5  359.11  5272.7  362.87  5299.6  363.99  5319.7  365.73
  5349.7  366.51  5386.3  370.02  5399.8  370.08  5429.8  372.15  5552.3  375.70
#Mann=5,-1,0
  4232.3    0.16       0  4986.5    0.07       0  4992.5    0.16       0
  5128.2     0.1       0  5272.7    0.05       0
Bank Sta=4986.5,4992.5
Exp/Cntr=0.3,0.1

Type RM Length L Ch R = 1,18361,827,827,827
BEGIN DESCRIPTION:
SMITH BRANCH 31.0
END DESCRIPTION:
XS GIS Cut Line= 3
      3548592.07     10322541.64      3547507.38     10322388.86
      3547007.37     10322438.87
#Sta/Elev= 30
  4030.6  379.51  4160.9  373.70  4252.7  369.65  4373.9  363.22  4404.2  362.40
  4434.5  360.43  4545.6  355.38  4575.9  354.56  4626.4  354.14  4676.9  355.10
  4766.8  355.75  4788.2  355.40  4854.4  355.94  4969.7  355.70  4979.8  354.48
  4993.8  350.94  4996.5  350.44  4999.8  350.94  5010.1  353.80  5020.2  355.88
  5064.4  358.66  5090.9  360.62  5141.4  362.82  5282.0  366.18  5300.9  366.07
  5305.9  366.60  5337.6  367.41  5442.8  371.90  5523.2  374.47  5628.5  376.41
#Mann=7,-1,0
  4030.6    0.05       0  4160.9    0.16       0  4766.8    0.12       0
  4993.8    0.07       0  4999.8    0.12       0  5064.4    0.16       0
  5337.6    0.05       0
Bank Sta=4993.8,4999.8
Exp/Cntr=0.3,0.1

Type RM Length L Ch R = 1,17534,1013,1013,1013
BEGIN DESCRIPTION:
SMITH BRANCH 29.0
END DESCRIPTION:
XS GIS Cut Line= 3
      3548553.32     10322272.57      3547982.38     10322016.64
      3547382.36     10321766.63
#Sta/Elev= 30
  4575.7  374.66  4620.9  371.72  4666.9  369.63  4713.2  366.51  4736.4  364.28
  4759.6  363.36  4829.1  358.81  4840.1  357.46  4886.5  353.83  4909.6  352.69
  4971.5  353.67  4979.2  353.05  4992.7  350.10  4999.4  348.98  5002.1  348.48
  5005.4  348.98  5007.8  351.40  5015.4  353.49  5025.6  353.77  5106.1  352.86
  5190.7  352.82  5251.9  353.80  5301.4  355.65  5334.2  356.87  5381.9  357.27
  5488.1  360.06  5618.1  365.36  5641.9  367.09  5808.3  370.10  5851.4  371.36
#Mann=5,-1,0
  4575.7    0.16       0  4992.7    0.07       0  4999.4    0.07       0
  5005.4    0.07       0  5301.4    0.16       0
Bank Sta=4999.4,5005.4
Exp/Cntr=0.3,0.1

Type RM Length L Ch R = 1,16521,491,491,491
BEGIN DESCRIPTION:
SMITH BRANCH 28.0
END DESCRIPTION:
XS GIS Cut Line= 3
      3548900.55     10321786.46      3548442.26     10321564.25
      3547497.77     10321467.03
#Sta/Elev= 30
  4182.1  370.72  4201.1  370.58  4315.9  368.35  4424.9  365.95  4477.3  362.18
  4545.0  358.65  4595.7  355.03  4612.7  353.15  4669.4  350.58  4711.7  350.02
  4731.8  350.63  4761.3  350.03  4779.5  350.51  4832.3  349.77  4973.1  350.58
  4983.1  349.58  4993.2  346.06  5000.2  344.81  5003.0  344.31  5006.2  344.81
  5013.3  347.19  5038.9  350.12  5058.6  353.52  5137.8  356.72  5204.3  360.00
  5251.8  360.78  5350.9  364.79  5374.6  364.99  5627.7  370.10  5640.9  370.20
#Mann=10,-1,0
  4182.1     0.1       0  4201.1    0.05       0  4315.9    0.16       0
  4779.5    0.12       0  5000.2    0.07       0  5006.2    0.12       0
  5038.9    0.16       0  5137.8     0.1       0  5374.6    0.16       0
  5627.7     0.1       0
Bank Sta=5000.2,5006.2
Exp/Cntr=0.3,0.1

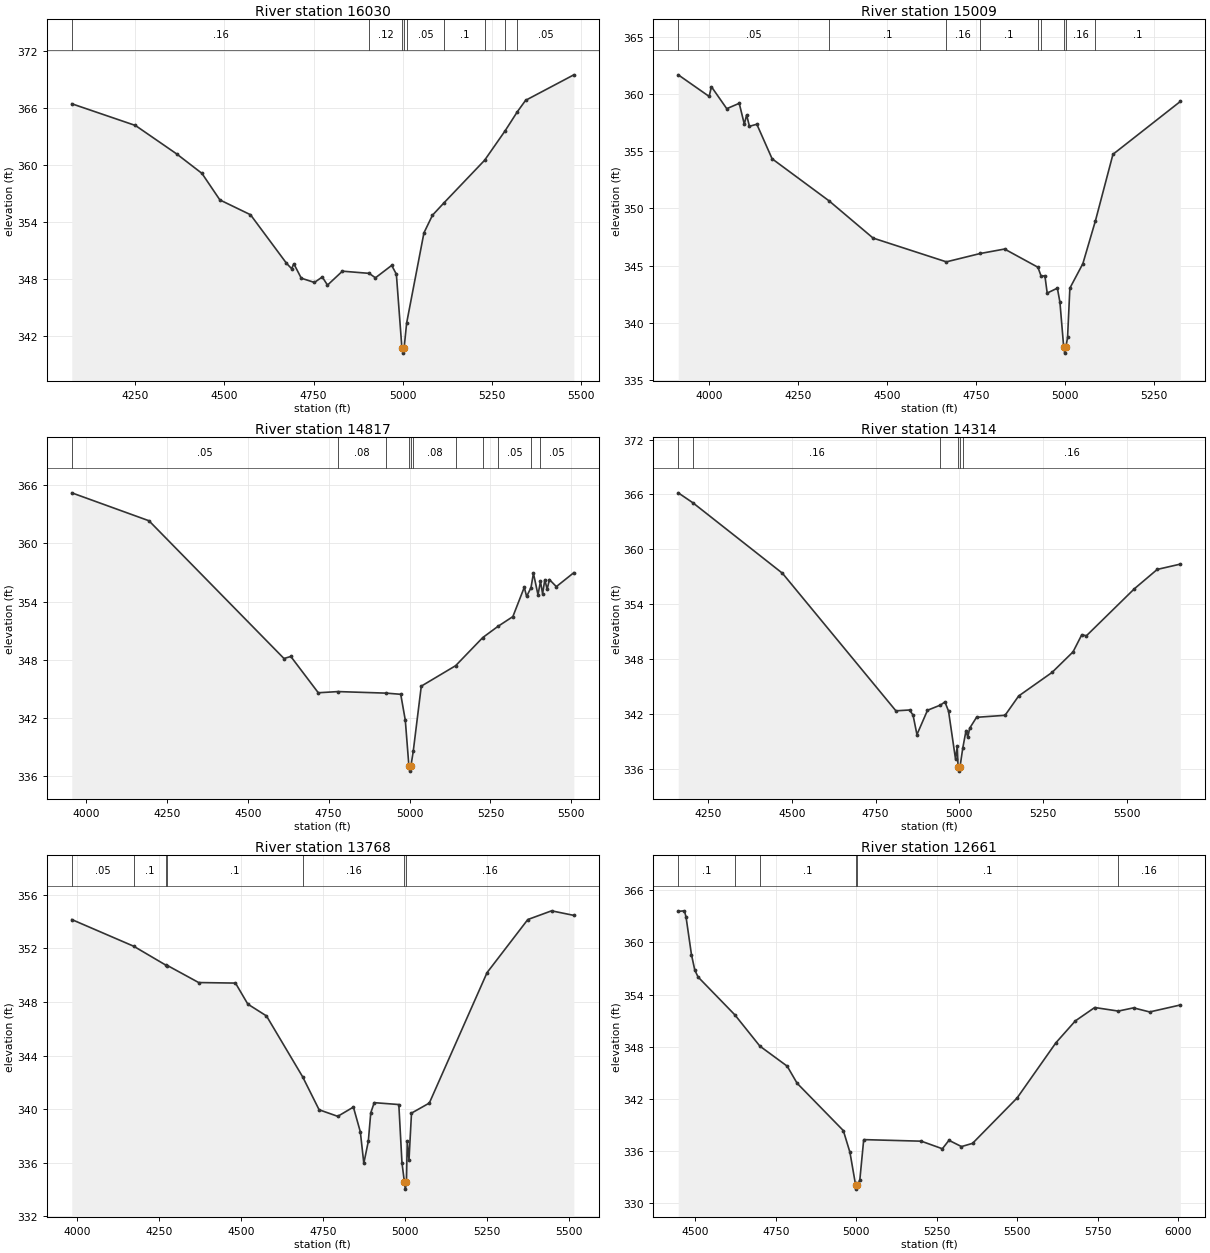
Type RM Length L Ch R = 1,16030,1021,1021,1021
BEGIN DESCRIPTION:
SMITH BRANCH 27.0
END DESCRIPTION:
XS GIS Cut Line= 3
      3548893.67     10321619.83      3548268.65     10321168.42
      3547679.89     10320925.99
#Sta/Elev= 30
  4072.2  366.48  4250.7  364.19  4366.0  361.20  4437.2  359.14  4487.5  356.34
  4573.3  354.78  4673.9  349.68  4688.6  349.09  4694.8  349.61  4715.7  348.09
  4752.6  347.64  4774.5  348.22  4789.2  347.36  4831.0  348.83  4906.0  348.60
  4923.6  348.13  4969.2  349.44  4982.3  348.51  4997.9  340.69  5000.6  340.19
  5003.9  340.69  5011.1  343.36  5059.6  352.87  5083.5  354.73  5116.2  356.05
  5229.6  360.52  5287.6  363.65  5321.5  365.64  5344.6  366.84  5479.9  369.53
#Mann=9,-1,0
  4072.2    0.16       0  4906.0    0.12       0  4997.9    0.07       0
  5003.9    0.12       0  5011.1    0.05       0  5116.2     0.1       0
  5229.6    0.05       0  5287.6     0.1       0  5321.5    0.05       0
Bank Sta=4997.9,5003.9
Exp/Cntr=0.3,0.1

Type RM Length L Ch R = 1,15009,192,192,192
BEGIN DESCRIPTION:
SMITH BRANCH 25.0
END DESCRIPTION:
XS GIS Cut Line= 3
      3549220.06     10321175.39      3548217.11     10320347.20
      3548117.11     10320297.20
#Sta/Elev= 30
  3912.1  361.67  3999.1  359.78  4005.5  360.63  4048.6  358.71  4083.7  359.18
  4098.0  357.36  4104.5  358.16  4112.4  357.17  4133.2  357.35  4176.2  354.33
  4336.5  350.65  4460.2  347.40  4666.4  345.32  4761.9  346.05  4830.2  346.44
  4923.9  344.85  4933.3  344.05  4943.6  344.11  4950.1  342.59  4978.7  343.02
  4985.9  341.80  4996.6  337.84  4999.3  337.34  5002.6  337.84  5007.4  338.72
  5013.9  343.02  5050.4  345.16  5085.9  348.92  5135.1  354.72  5324.6  359.34
#Mann=9,-1,0
  3912.1    0.05       0  4336.5     0.1       0  4666.4    0.16       0
  4761.9     0.1       0  4923.9    0.05       0  4933.3    0.16       0
  4996.6    0.07       0  5002.6    0.16       0  5085.9     0.1       0
Bank Sta=4996.6,5002.6
Exp/Cntr=0.3,0.1

Type RM Length L Ch R = 1,14817,503,503,503
BEGIN DESCRIPTION:
Mapping XS fe797ba2
END DESCRIPTION:
XS GIS Cut Line= 2
      3549303.46     10321107.72      3548176.51     10320040.63
#Sta/Elev= 30
  3956.0  365.21  4194.6  362.33  4612.0  348.13  4633.1  348.34  4718.0  344.60
  4779.3  344.72  4928.4  344.56  4972.9  344.44  4987.0  341.77  4998.2  337.02
  5000.9  336.52  5004.2  337.02  5011.5  338.55  5036.4  345.28  5142.6  347.39
  5226.5  350.29  5273.7  351.45  5319.5  352.45  5354.8  355.47  5362.0  354.53
  5375.5  355.43  5383.1  356.92  5397.2  354.69  5404.8  356.08  5411.4  354.80
  5418.3  356.26  5425.5  355.26  5432.4  356.27  5453.9  355.54  5508.0  356.98
#Mann=11,-1,0
  3956.0    0.05       0  4779.3    0.08       0  4928.4    0.05       0
  4998.2    0.04       0  5004.2    0.05       0  5011.5    0.08       0
  5142.6    0.05       0  5226.5    0.08       0  5273.7    0.05       0
  5375.5    0.08       0  5404.8    0.05       0
Bank Sta=4998.2,5004.2
Exp/Cntr=0.3,0.1

Type RM Length L Ch R = 1,14314,546,546,546
BEGIN DESCRIPTION:
SMITH BRANCH 23.0
END DESCRIPTION:
XS GIS Cut Line= 3
      3549553.40     10320529.56      3549115.87     10320147.59
      3548246.67     10319852.89
#Sta/Elev= 30
  4160.8  366.18  4205.0  365.08  4471.9  357.39  4810.5  342.36  4851.2  342.45
  4861.7  341.89  4873.3  339.76  4904.8  342.42  4943.6  342.99  4956.8  343.33
  4967.6  342.33  4988.4  337.10  4993.7  338.50  4996.0  336.27  4998.7  335.77
  5002.0  336.27  5010.0  338.27  5019.8  340.20  5025.1  339.47  5030.7  340.46
  5051.2  341.65  5136.3  341.87  5176.9  343.98  5276.4  346.55  5339.2  348.80
  5365.4  350.68  5379.1  350.56  5522.4  355.70  5590.5  357.81  5659.4  358.39
#Mann=6,-1,0
  4160.8     0.1       0  4205.0    0.16       0  4943.6    0.12       0
  4996.0    0.07       0  5002.0    0.12       0  5010.0    0.16       0
Bank Sta=4996,5002
Exp/Cntr=0.3,0.1

Type RM Length L Ch R = 1,13768,1107,1107,1107
BEGIN DESCRIPTION:
SMITH BRANCH 22.0
END DESCRIPTION:
XS GIS Cut Line= 3
      3549824.21     10319883.70      3548842.11     10319541.64
      3548366.51     10319411.65
#Sta/Elev= 30
  3982.7  354.15  4171.7  352.16  4269.2  350.76  4274.9  350.72  4370.2  349.45
  4482.6  349.41  4520.3  347.84  4577.2  346.96  4687.6  342.42  4737.9  339.96
  4794.8  339.47  4842.6  340.16  4863.8  338.31  4874.4  335.97  4888.1  337.60
  4895.6  339.73  4906.2  340.49  4981.3  340.35  4990.9  336.01  4998.5  334.54
  5001.2  334.04  5004.5  334.54  5007.1  337.61  5012.4  336.23  5020.0  339.71
  5074.4  340.46  5250.7  350.19  5375.1  354.15  5447.7  354.80  5515.7  354.46
#Mann=7,-1,0
  3982.7    0.05       0  4171.7     0.1       0  4269.2    0.05       0
  4274.9     0.1       0  4687.6    0.16       0  4998.5    0.07       0
  5004.5    0.16       0
Bank Sta=4998.5,5004.5
Exp/Cntr=0.3,0.1

Type RM Length L Ch R = 1,12661,547,547,547
BEGIN DESCRIPTION:
SMITH BRANCH 20.0
END DESCRIPTION:
XS GIS Cut Line= 3
      3549942.14     10319041.65      3549081.15     10318848.98
      3548407.35     10318793.03
#Sta/Elev= 30
  4447.4  363.57  4466.6  363.63  4471.7  362.90  4488.4  358.61  4498.7  356.83
  4508.9  356.03  4623.3  351.67  4700.9  348.08  4785.6  345.78  4816.3  343.82
  4959.8  338.38  4980.3  335.89  4997.8  332.15  5000.5  331.65  5003.8  332.15
  5011.0  332.69  5023.1  337.34  5201.8  337.16  5267.2  336.29  5287.7  337.26
  5326.6  336.54  5360.9  336.91  5499.3  342.13  5619.7  348.47  5679.9  350.98
  5740.1  352.52  5813.3  352.11  5860.5  352.48  5910.7  352.01  6005.8  352.81
#Mann=6,-1,0
  4447.4     0.1       0  4623.3    0.05       0  4700.9     0.1       0
  4997.8    0.07       0  5003.8     0.1       0  5813.3    0.16       0
Bank Sta=4997.8,5003.8
Exp/Cntr=0.3,0.1

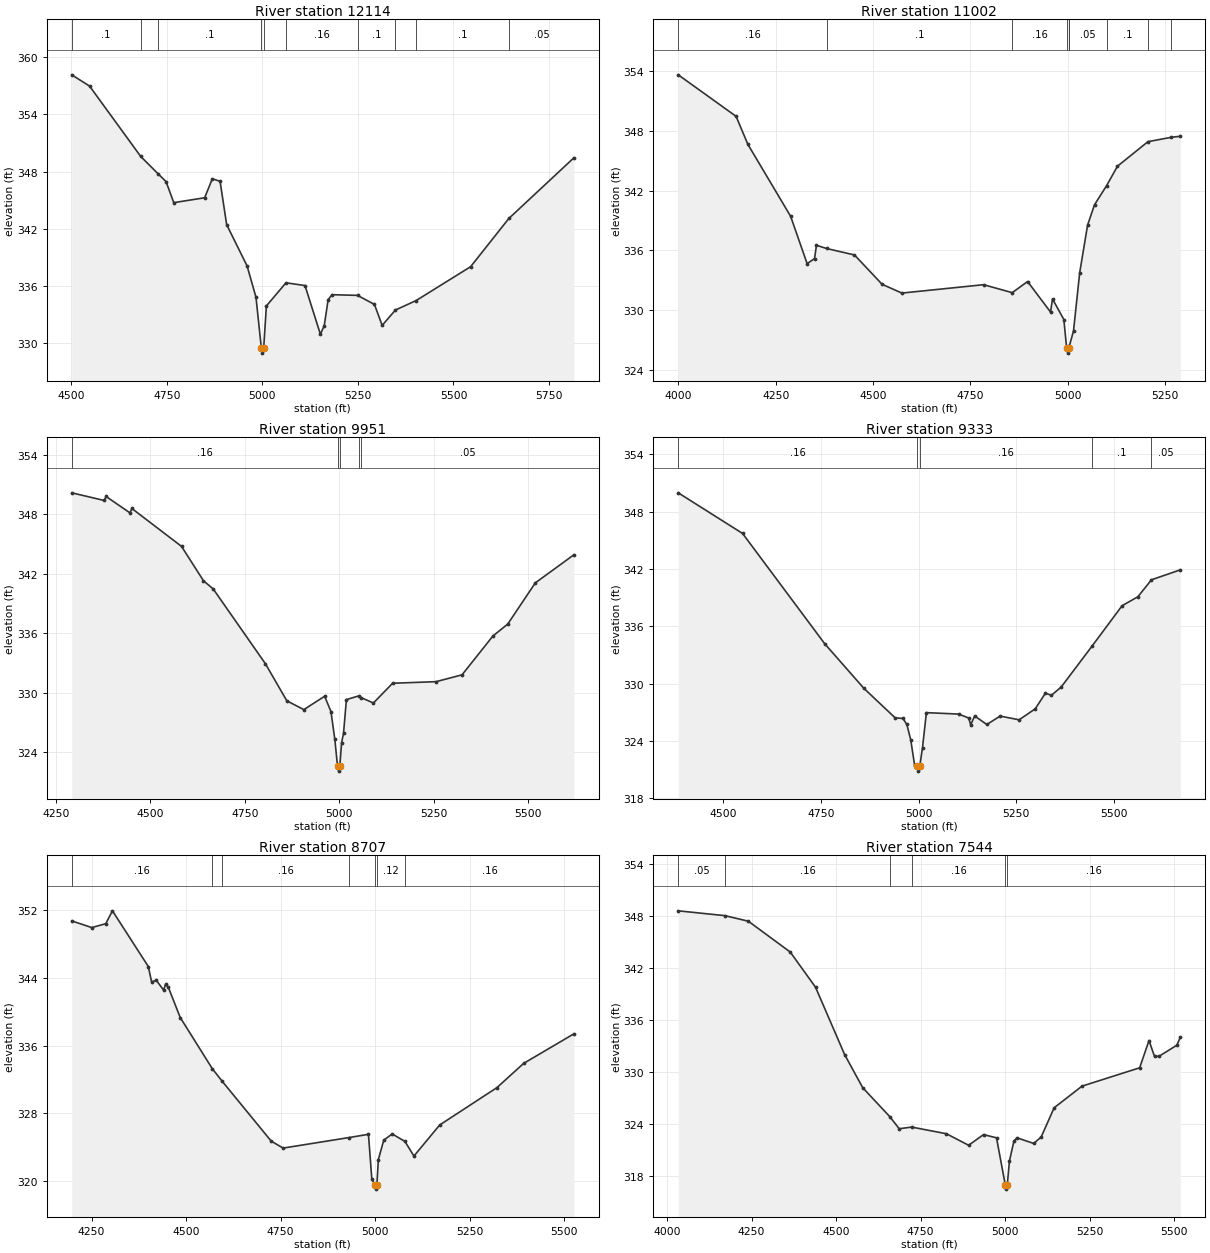
Type RM Length L Ch R = 1,12114,1112,1112,1112
BEGIN DESCRIPTION:
SMITH BRANCH 18.0
END DESCRIPTION:
XS GIS Cut Line= 3
      3550046.38     10318522.58      3549095.03     10318390.64
      3548742.09     10318391.64
#Sta/Elev= 30
  4501.5  358.15  4548.0  356.97  4681.8  349.59  4726.9  347.78  4748.1  346.95
  4768.3  344.74  4849.1  345.25  4869.3  347.25  4889.5  346.97  4906.7  342.43
  4960.1  338.10  4983.4  334.81  4997.5  329.45  5000.3  328.95  5003.5  329.45
  5010.6  333.90  5061.9  336.33  5111.6  336.04  5151.9  330.93  5162.0  331.84
  5172.1  334.55  5182.2  335.08  5249.0  335.01  5293.3  334.06  5313.5  331.86
  5348.1  333.47  5402.5  334.47  5544.9  338.02  5644.9  343.08  5814.9  349.44
#Mann=10,-1,0
  4501.5     0.1       0  4681.8    0.05       0  4726.9     0.1       0
  4997.5    0.07       0  5003.5     0.1       0  5061.9    0.16       0
  5249.0     0.1       0  5348.1    0.05       0  5402.5     0.1       0
  5644.9    0.05       0
Bank Sta=4997.5,5003.5
Exp/Cntr=0.3,0.1

Type RM Length L Ch R = 1,11002,1051,1051,1051
BEGIN DESCRIPTION:
SMITH BRANCH 16.0
END DESCRIPTION:
XS GIS Cut Line= 3
      3550018.64     10317779.53      3549254.76     10317904.53
      3548747.78     10317994.81
#Sta/Elev= 30
  3999.9  353.60  4148.4  349.44  4178.8  346.62  4288.4  339.42  4330.8  334.67
  4349.8  335.18  4354.8  336.51  4380.6  336.19  4452.4  335.54  4523.3  332.60
  4574.0  331.72  4783.9  332.56  4857.4  331.76  4896.8  332.88  4955.7  329.82
  4960.8  331.13  4989.9  329.07  4997.1  326.20  4999.9  325.70  5003.1  326.20
  5003.8  326.37  5014.7  327.93  5030.6  333.77  5050.9  338.54  5068.6  340.57
  5099.8  342.50  5127.6  344.44  5205.9  346.90  5266.2  347.34  5288.9  347.44
#Mann=9,-1,0
  3999.9    0.16       0  4380.6     0.1       0  4857.4    0.16       0
  4997.1    0.07       0  5003.1    0.16       0  5003.8    0.05       0
  5099.8     0.1       0  5205.9    0.05       0  5266.2     0.1       0
Bank Sta=4997.1,5003.1
Exp/Cntr=0.3,0.1

Type RM Length L Ch R = 1,9951,618,618,618
BEGIN DESCRIPTION:
SMITH BRANCH 15.0
END DESCRIPTION:
XS GIS Cut Line= 3
      3549997.80     10317300.36      3549636.70     10317244.81
      3548692.13     10317441.64
#Sta/Elev= 30
  4291.6  350.16  4377.5  349.39  4382.6  349.79  4445.8  348.14  4450.9  348.58
  4582.4  344.76  4640.6  341.29  4666.3  340.47  4804.6  332.93  4861.4  329.19
  4906.4  328.30  4961.5  329.65  4978.3  328.11  4988.5  325.32  4995.7  322.60
  4998.5  322.10  5001.7  322.60  5006.5  324.97  5011.6  325.91  5019.2  329.31
  5051.4  329.68  5058.4  329.51  5090.7  328.97  5141.7  330.96  5256.7  331.12
  5325.6  331.81  5407.3  335.72  5446.7  336.93  5519.7  341.08  5621.8  343.91
#Mann=5,-1,0
  4291.6    0.16       0  4995.7    0.07       0  5001.7    0.16       0
  5051.4     0.1       0  5058.4    0.05       0
Bank Sta=4995.7,5001.7
Exp/Cntr=0.3,0.1

Type RM Length L Ch R = 1,9333,626,626,626
BEGIN DESCRIPTION:
SMITH BRANCH 13.0
END DESCRIPTION:
XS GIS Cut Line= 3
      3549886.66     10316703.15      3549242.11     10316741.64
      3548622.77     10316904.54
#Sta/Elev= 30
  4384.2  349.96  4549.0  345.71  4759.4  334.17  4859.6  329.51  4939.7  326.42
  4959.8  326.35  4969.8  325.72  4979.8  324.11  4989.8  321.43  4996.8  321.34
  4999.6  320.84  5002.8  321.34  5009.9  323.30  5019.9  326.96  5102.3  326.81
  5128.2  326.40  5133.3  325.69  5143.6  326.61  5174.7  325.72  5208.8  326.60
  5257.4  326.21  5298.7  327.36  5324.7  328.99  5340.1  328.78  5365.0  329.63
  5444.0  333.91  5521.2  338.15  5561.5  339.08  5596.4  340.86  5670.3  341.90
#Mann=5,-1,0
  4384.2    0.16       0  4996.8    0.07       0  5002.8    0.16       0
  5444.0     0.1       0  5596.4    0.05       0
Bank Sta=4996.8,5002.8
Exp/Cntr=0.3,0.1

Type RM Length L Ch R = 1,8707,1163,1163,1163
BEGIN DESCRIPTION:
SMITH BRANCH 12.0
END DESCRIPTION:
XS GIS Cut Line= 3
      3549874.06     10315938.86      3549274.05     10316138.86
      3548616.46     10316362.66
#Sta/Elev= 30
  4197.8  350.75  4250.7  349.96  4287.6  350.42  4305.3  351.94  4400.1  345.36
  4408.8  343.54  4421.2  343.73  4440.4  342.58  4445.7  343.26  4452.8  342.93
  4484.5  339.33  4569.3  333.28  4594.3  331.86  4725.0  324.72  4756.6  323.90
  4931.4  325.15  4982.0  325.53  4990.8  320.30  4998.3  319.55  5001.1  319.05
  5004.3  319.55  5008.1  322.53  5022.5  324.84  5044.8  325.57  5078.4  324.69
  5102.2  322.96  5170.3  326.63  5321.7  331.05  5392.2  333.91  5524.9  337.40
#Mann=7,-1,0
  4197.8    0.16       0  4569.3     0.1       0  4594.3    0.16       0
  4931.4    0.12       0  4998.3    0.07       0  5004.3    0.12       0
  5078.4    0.16       0
Bank Sta=4998.3,5004.3
Exp/Cntr=0.3,0.1

Type RM Length L Ch R = 1,7544,1625,1625,1625
BEGIN DESCRIPTION:
SMITH BRANCH 11.0
END DESCRIPTION:
XS GIS Cut Line= 3
      3549757.42     10315263.84      3549057.38     10315663.86
      3548456.66     10315980.65
#Sta/Elev= 30
  4033.2  348.62  4171.7  348.06  4240.6  347.42  4364.5  343.86  4439.3  339.80
  4525.7  331.99  4579.0  328.18  4659.0  324.84  4686.9  323.44  4724.0  323.63
  4826.6  322.86  4892.3  321.53  4936.4  322.76  4974.8  322.39  5000.7  316.96
  5003.5  316.46  5006.7  316.96  5013.1  319.72  5026.3  322.00  5035.2  322.39
  5084.9  321.74  5106.9  322.48  5145.3  325.86  5227.7  328.36  5398.3  330.48
  5426.0  333.63  5442.3  331.79  5455.9  331.82  5508.4  333.09  5518.6  334.01
#Mann=6,-1,0
  4033.2    0.05       0  4171.7    0.16       0  4659.0     0.1       0
  4724.0    0.16       0  5000.7    0.07       0  5006.7    0.16       0
Bank Sta=5000.7,5006.7
Exp/Cntr=0.3,0.1