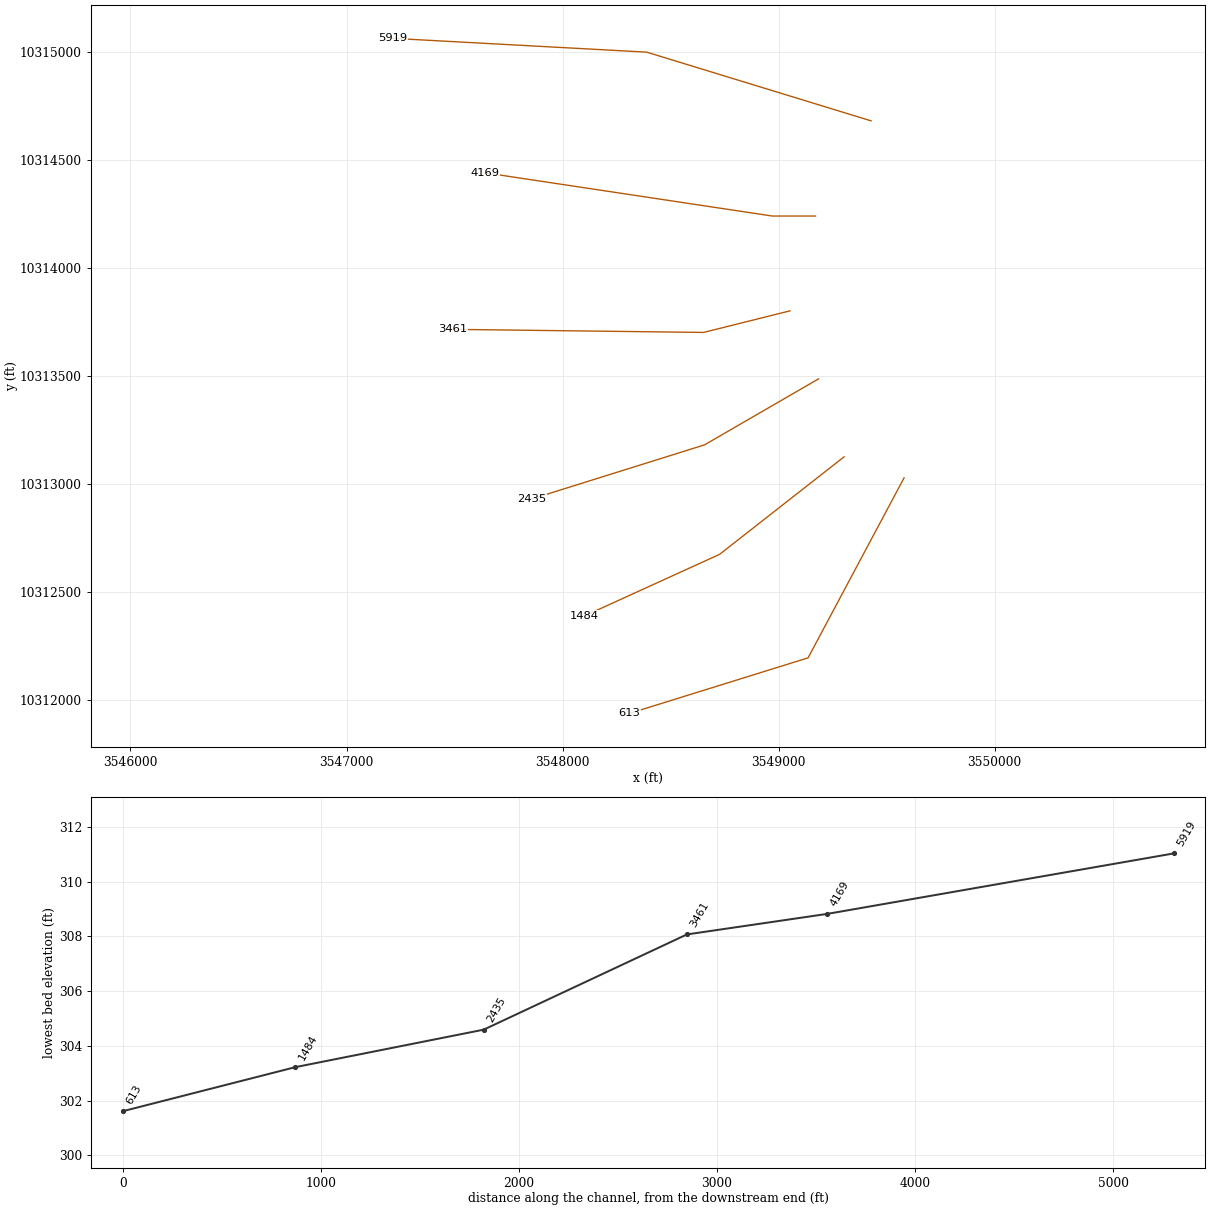
HEC-RAS study SMITH BRANCH.prj: SMITH BRANCH Base Level Engineering

--- SMITH BRANCH.g01 (geometry) --- (continued)

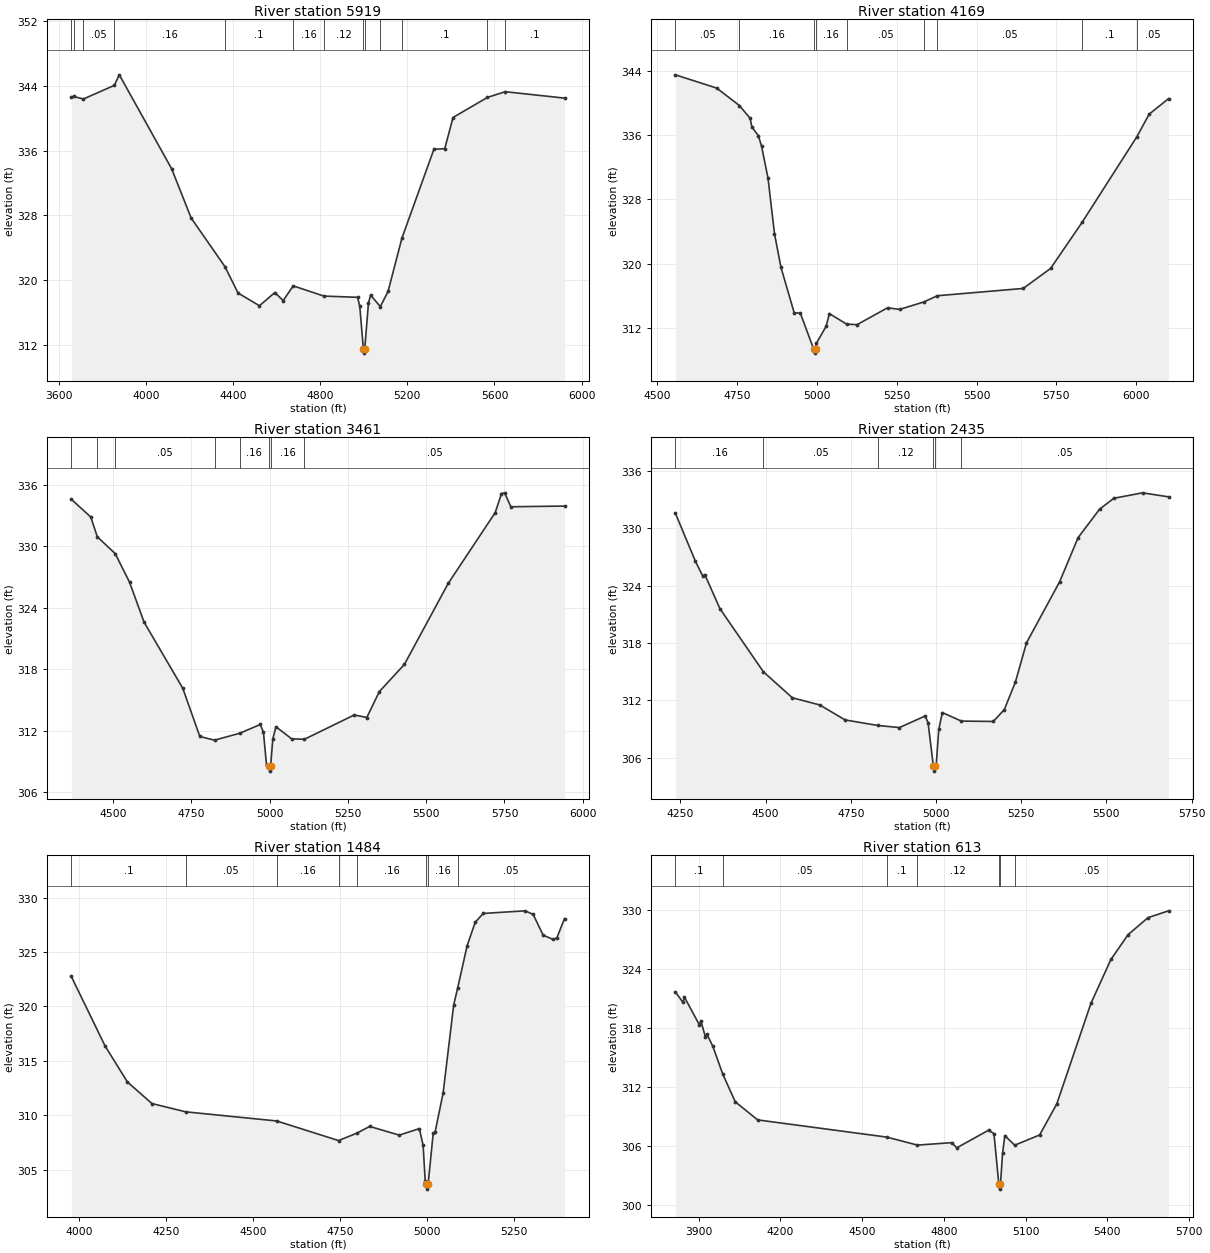
Type RM Length L Ch R = 1,5919,1750,1750,1750
BEGIN DESCRIPTION:
SMITH BRANCH 9.0
END DESCRIPTION:
XS GIS Cut Line= 3
      3549428.32     10314682.32      3548389.48     10315000.36
      3547213.05     10315064.26
#Sta/Elev= 30
  3657.0  342.61  3667.4  342.66  3712.2  342.35  3854.5  344.03  3877.3  345.33
  4117.1  333.78  4207.3  327.68  4362.1  321.70  4422.5  318.44  4520.8  316.87
  4591.6  318.50  4629.6  317.50  4675.8  319.32  4816.7  318.06  4971.1  317.91
  4981.2  316.85  4998.2  311.53  5000.9  311.03  5004.2  311.53  5021.2  317.17
  5031.2  318.18  5075.8  316.76  5111.4  318.64  5174.9  325.19  5321.7  336.15
  5371.7  336.23  5409.6  340.07  5567.8  342.55  5649.5  343.25  5921.6  342.46
#Mann=13,-1,0
  3657.0    0.05       0  3667.4    0.16       0  3712.2    0.05       0
  3854.5    0.16       0  4362.1     0.1       0  4675.8    0.16       0
  4816.7    0.12       0  4998.2    0.07       0  5004.2    0.12       0
  5075.8    0.12       0  5174.9     0.1       0  5567.8    0.05       0
  5649.5     0.1       0
Bank Sta=4998.2,5004.2
Exp/Cntr=0.3,0.1

Type RM Length L Ch R = 1,4169,708,708,708
BEGIN DESCRIPTION:
SMITH BRANCH 7.0
END DESCRIPTION:
XS GIS Cut Line= 3
      3549171.31     10314241.64      3548971.27     10314241.64
      3547642.07     10314441.65
#Sta/Elev= 30
  4556.9  343.54  4686.1  341.89  4757.5  339.71  4791.0  338.11  4796.5  337.04
  4816.8  335.95  4826.9  334.63  4847.1  330.62  4867.3  323.73  4887.6  319.51
  4929.0  313.85  4948.2  313.81  4990.0  309.32  4992.7  308.82  4996.0  309.32
  4998.8  310.06  5029.1  312.18  5039.2  313.75  5093.1  312.44  5125.9  312.37
  5221.3  314.48  5258.8  314.27  5336.0  315.22  5377.1  315.98  5646.0  316.89
  5731.7  319.38  5830.2  325.12  6001.9  335.82  6040.4  338.63  6101.1  340.57
#Mann=9,-1,0
  4556.9    0.05       0  4757.5    0.16       0  4990.0    0.07       0
  4996.0    0.16       0  5093.1    0.05       0  5336.0    0.16       0
  5377.1    0.05       0  5830.2     0.1       0  6001.9    0.05       0
Bank Sta=4990,4996
Exp/Cntr=0.3,0.1

Type RM Length L Ch R = 1,3461,1026,1026,1026
BEGIN DESCRIPTION:
SMITH BRANCH 6.0
END DESCRIPTION:
XS GIS Cut Line= 3
      3549053.22     10313802.76      3548653.22     10313702.75
      3547490.82     10313717.03
#Sta/Elev= 30
  4367.0  334.59  4429.1  332.86  4450.0  330.93  4507.1  329.29  4552.8  326.51
  4599.2  322.61  4722.9  316.15  4777.3  311.45  4824.4  311.09  4905.4  311.77
  4970.4  312.62  4980.4  311.87  4990.4  308.63  4997.4  308.57  5000.2  308.07
  5003.4  308.57  5010.4  311.22  5020.4  312.40  5070.5  311.22  5111.4  311.18
  5270.5  313.55  5310.5  313.30  5350.5  315.83  5430.5  318.48  5570.5  326.39
  5720.5  333.29  5740.5  335.14  5750.5  335.22  5770.5  333.86  5941.8  333.93
#Mann=8,-1,0
  4367.0    0.05       0  4450.0    0.16       0  4507.1    0.05       0
  4824.4    0.12       0  4905.4    0.16       0  4997.4    0.07       0
  5003.4    0.16       0  5111.4    0.05       0
Bank Sta=4997.4,5003.4
Exp/Cntr=0.3,0.1

Type RM Length L Ch R = 1,2435,951,951,951
BEGIN DESCRIPTION:
SMITH BRANCH 5.0
END DESCRIPTION:
XS GIS Cut Line= 3
      3549185.34     10313487.88      3548657.53     10313182.31
      3547858.93     10312932.31
#Sta/Elev= 30
  4235.5  331.60  4294.5  326.55  4316.1  325.00  4321.9  325.17  4366.3  321.60
  4494.0  314.98  4578.7  312.27  4659.1  311.52  4733.6  309.95  4829.6  309.37
  4892.8  309.15  4968.2  310.36  4976.8  309.66  4992.4  305.09  4995.1  304.59
  4998.4  305.09  5000.6  305.18  5008.2  308.96  5018.7  310.72  5074.4  309.83
  5168.1  309.79  5200.6  311.04  5233.0  313.92  5265.5  318.02  5362.9  324.43
  5416.9  329.04  5479.8  332.01  5521.7  333.16  5605.8  333.73  5682.2  333.31
#Mann=6,-1,0
  4235.5    0.16       0  4494.0    0.05       0  4829.6    0.12       0
  4992.4    0.07       0  4998.4    0.12       0  5074.4    0.05       0
Bank Sta=4992.4,4998.4
Exp/Cntr=0.3,0.1

Type RM Length L Ch R = 1,1484,871,871,871
BEGIN DESCRIPTION:
SMITH BRANCH 3.0
END DESCRIPTION:
XS GIS Cut Line= 3
      3549303.37     10313126.76      3548726.98     10312675.36
      3548101.99     10312390.65
#Sta/Elev= 30
  3976.5  322.75  4073.7  316.36  4137.9  313.06  4208.4  311.08  4305.4  310.32
  4567.4  309.48  4745.2  307.68  4798.1  308.36  4834.8  308.98  4919.9  308.18
  4977.7  308.78  4988.7  307.23  4994.6  303.95  4997.1  303.72  4999.8  303.22
  5003.1  303.72  5017.6  308.35  5023.1  308.47  5046.2  312.06  5076.6  320.15
  5087.7  321.65  5115.3  325.59  5138.4  327.72  5161.4  328.54  5282.2  328.78
  5305.2  328.45  5333.8  326.55  5362.3  326.15  5373.3  326.29  5395.4  328.07
#Mann=8,-1,0
  3976.5     0.1       0  4305.4    0.05       0  4567.4    0.16       0
  4745.2    0.12       0  4798.1    0.16       0  4997.1    0.07       0
  5003.1    0.16       0  5087.7    0.05       0
Bank Sta=4997.1,5003.1
Exp/Cntr=0.3,0.1

Type RM Length L Ch R = 1,613,0,0,0
BEGIN DESCRIPTION:
SMITH BRANCH 1.0
END DESCRIPTION:
XS GIS Cut Line= 3
      3549581.13     10313029.50      3549136.70     10312196.20
      3548310.34     10311939.26
#Sta/Elev= 30
  3814.5  321.64  3842.4  320.57  3848.0  321.10  3902.6  318.29  3908.2  318.69
  3924.5  317.09  3930.2  317.35  3952.1  316.11  3988.3  313.30  4034.3  310.48
  4116.5  308.64  4591.0  306.89  4702.8  306.08  4828.3  306.33  4847.5  305.81
  4963.7  307.59  4983.6  307.25  5001.6  302.11  5004.3  301.61  5007.6  302.11
  5015.1  305.23  5023.6  307.04  5059.8  306.07  5151.2  307.11  5214.0  310.25
  5339.7  320.49  5413.0  324.94  5475.8  327.45  5549.1  329.18  5624.3  329.87
#Mann=7,-1,0
  3814.5     0.1       0  3988.3    0.05       0  4591.0     0.1       0
  4702.8    0.12       0  5001.6    0.07       0  5007.6    0.12       0
  5059.8    0.05       0
Bank Sta=5001.6,5007.6
Exp/Cntr=0.3,0.1

Chan Stop Cuts=-1