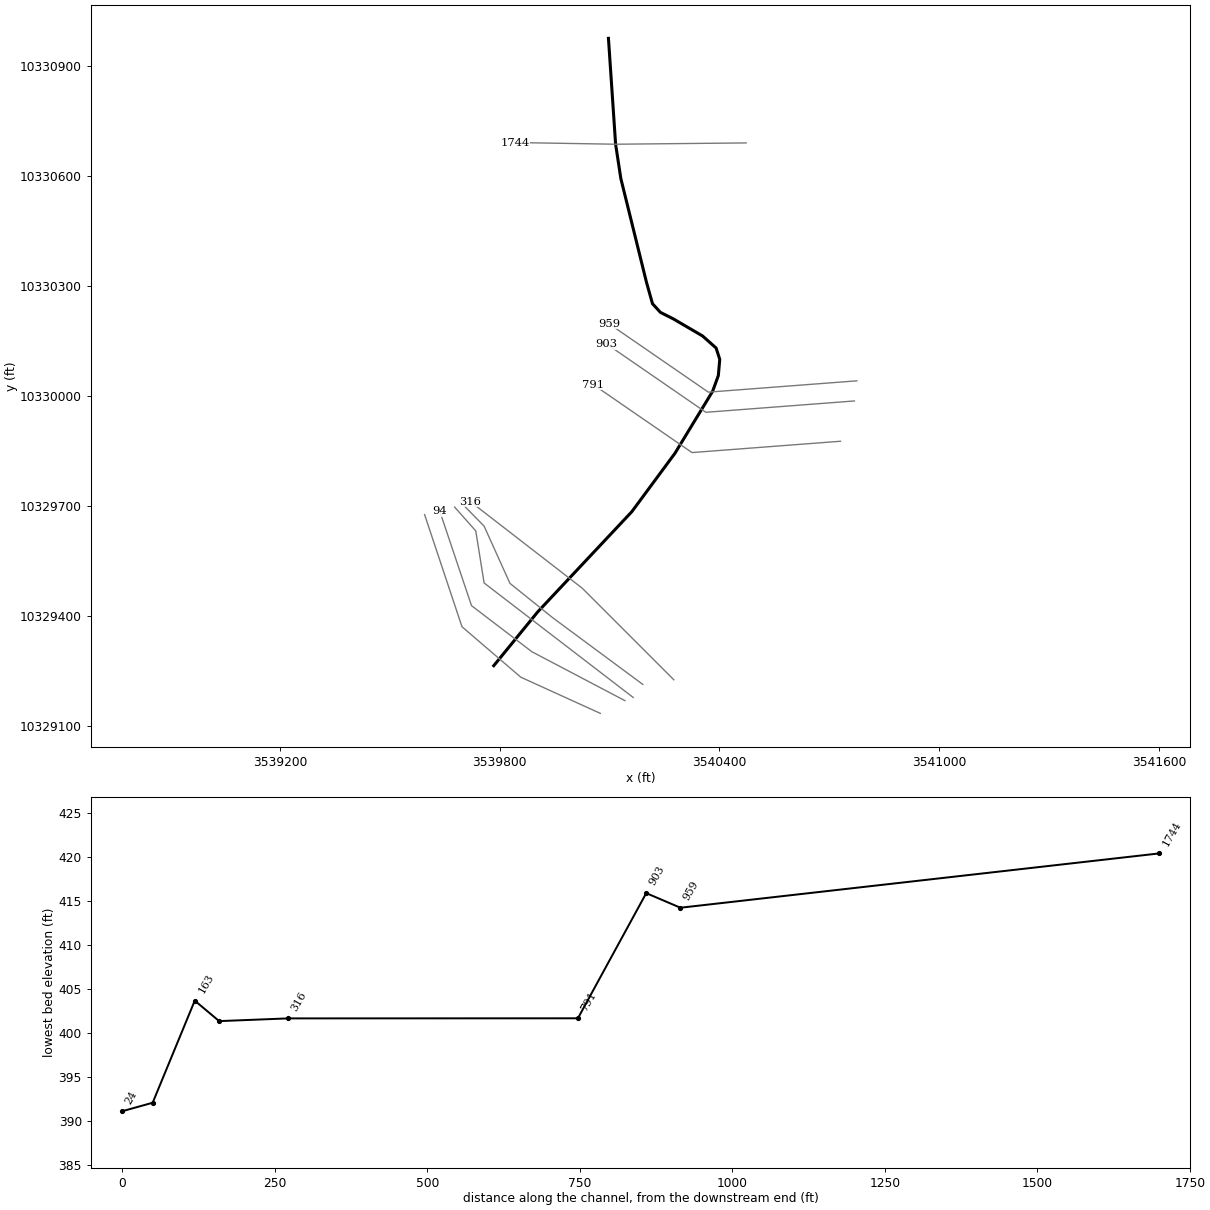
--- SMITH CREEK TRIBUTARY 2.prj (project) ---

Proj Title=SMITH CREEK TRIBUTARY 2 Base Level Engineering
Current Plan=p01
Default Exp/Contr=0.3,0.1
English Units
Geom File=g01
Flow File=f01
Plan File=p01
Y Axis Title=Elevation
X Axis Title(PF)=Main Channel Distance
X Axis Title(XS)=Station
BEGIN DESCRIPTION:
SMITH CREEK TRIBUTARY 2
END DESCRIPTION:
DSS Export Rating Curves= 0
DSS Export Rating Curve Sorted= 0
DSS Export Volume Flow Curves= 0
DXF OffsetX= 0
DXF OffsetY= 0
DXF ScaleX= 1
DXF ScaleY= 10

--- SMITH CREEK TRIBUTARY 2.p01 (plan) ---

Plan Title=Multiple Run
Short Identifier=Multiple
Geom File=g01
Flow File=f01
Subcritical Flow
K Sum by GR= 0
Std Step Tol= 0.01
Critical Tol= 0.01
Num of Std Step Trials= 20
Max Error Tol= 0.3
Flow Tol Ratio= 0.001
Split Flow NTrial= 30
Split Flow Tol= 0.02
Split Flow Ratio= 0.02
Log Output Level= 0
Friction Slope Method= 1
Unsteady Friction Slope Method= 2
Unsteady Bridges Friction Slope Method= 1
Parabolic Critical Depth
Global Vel Dist=  1 , 1 , 1
Global Log Level= 0
CheckData=True
Encroach Param= -1, 0, 0, 0
BEGIN DESCRIPTION:
Multiple Run
END DESCRIPTION:

--- SMITH CREEK TRIBUTARY 2.f01 (steady flow) ---

Flow Title=Multiple
Number of Profiles=7
Profile Names=10-year,25-year,50-year,1pct_min,100-year,1pct_plu,500-year
River Rch & RM= SMITH CREEK TRIB,Reach-1,1744
     143     178     204     173     234     317     308
Boundary for River Rch & Prof#=SMITH CREEK TRIB,Reach-1,1
Up Type=0
Dn Type=3
Dn Slope=0.005
Boundary for River Rch & Prof#=SMITH CREEK TRIB,Reach-1,2
Up Type=0
Dn Type=3
Dn Slope=0.005
Boundary for River Rch & Prof#=SMITH CREEK TRIB,Reach-1,3
Up Type=0
Dn Type=3
Dn Slope=0.005
Boundary for River Rch & Prof#=SMITH CREEK TRIB,Reach-1,4
Up Type=0
Dn Type=3
Dn Slope=0.005
Boundary for River Rch & Prof#=SMITH CREEK TRIB,Reach-1,5
Up Type=0
Dn Type=3
Dn Slope=0.005
Boundary for River Rch & Prof#=SMITH CREEK TRIB,Reach-1,6
Up Type=0
Dn Type=3
Dn Slope=0.005
Boundary for River Rch & Prof#=SMITH CREEK TRIB,Reach-1,7
Up Type=0
Dn Type=3
Dn Slope=0.005

--- SMITH CREEK TRIBUTARY 2.g01 (geometry) ---

Geom Title=Existing Conditions
Program Version=4.10

River Reach=SMITH CREEK TRIB,Reach-1
Reach XY= 16
      3540096.93     10330976.06      3540116.46       10330687.
      3540130.78     10330593.25      3540200.66     10330310.44
      3540217.15     10330251.67      3540238.85     10330227.97
      3540274.45     10330210.01      3540353.87     10330163.56
      3540390.76     10330130.75      3540400.75     10330099.76
      3540396.84     10330055.48      3540381.22     10330012.52
      3540278.35     10329843.25      3540160.73     10329683.96
       3539903.9     10329410.48      3539783.84     10329263.55

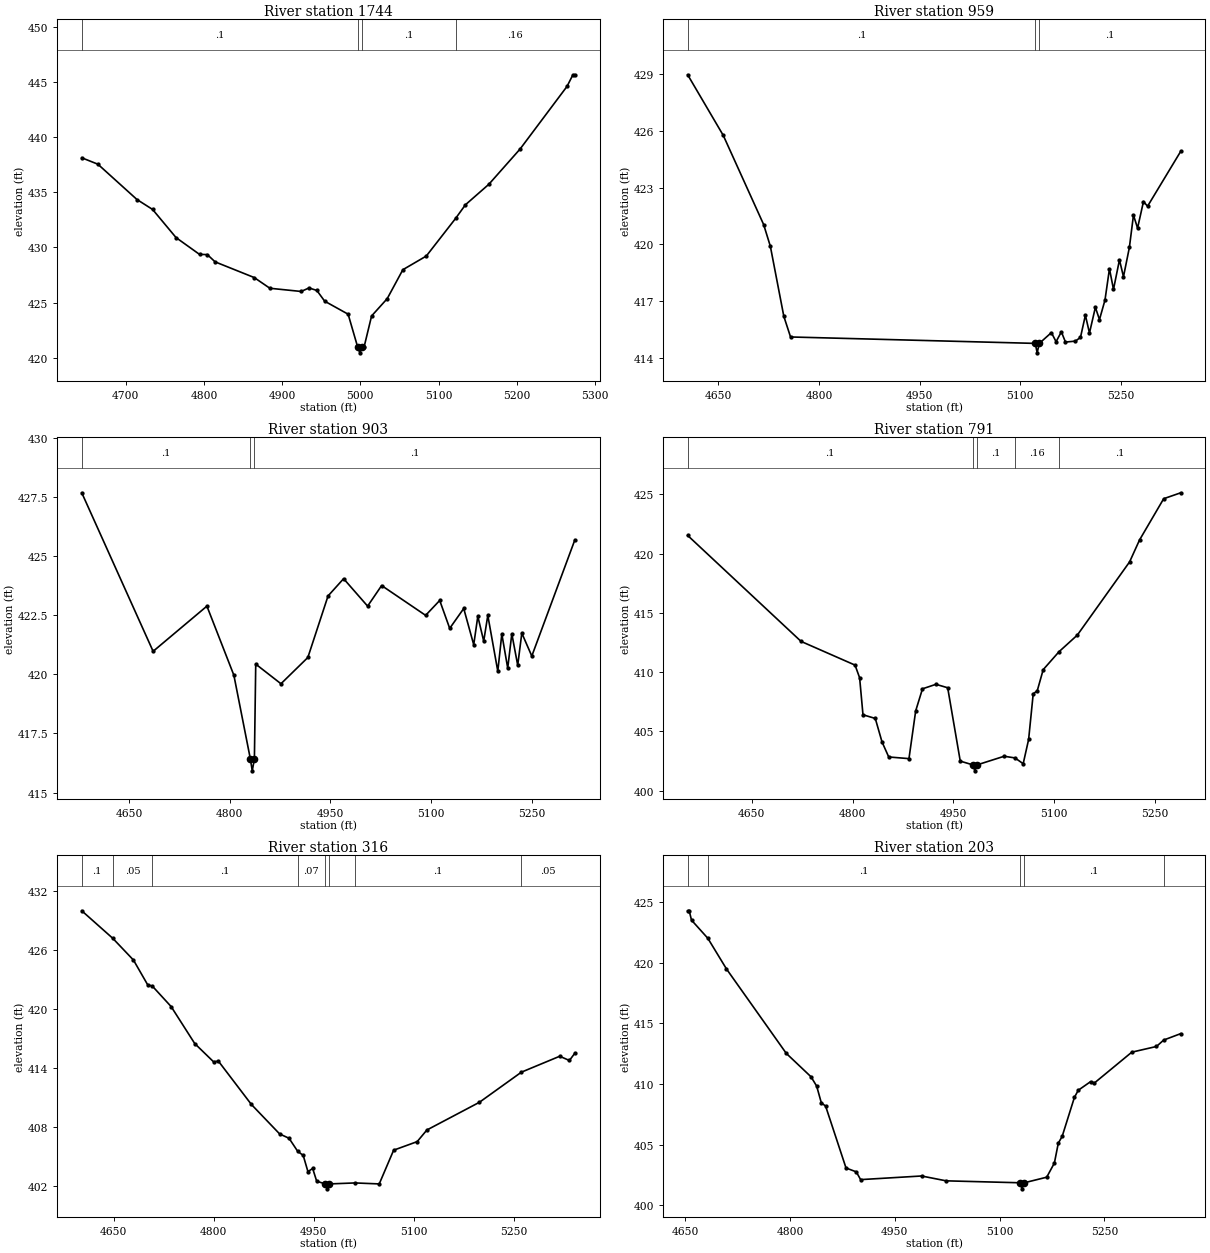
Type RM Length L Ch R = 1 ,1744    ,785,785,785
BEGIN DESCRIPTION:
SMITH CREEK TRIBUTARY 2 4.0
END DESCRIPTION:
XS GIS Cut Line= 3
      3540472.74     10330690.55      3540116.46       10330687.
       3539842.1     10330691.64
#Sta/Elev= 30
  4643.7  438.11  4664.3  437.53  4714.3  434.33  4734.3  433.43  4764.3  430.88
  4794.3  429.36  4804.3  429.34  4814.3  428.68  4864.3  427.26  4884.3  426.29
  4924.3     426  4934.4  426.32  4944.4  426.09  4954.4  425.12  4984.4  423.94
  4996.7  420.94  4999.4  420.44  5002.7  420.94  5004.7  420.94  5014.4  423.78
  5034.4  425.35  5054.4  427.97  5084.4  429.21  5121.9  432.62  5134.4  433.85
  5164.4  435.71  5204.4  438.91  5264.4  444.58  5271.9  445.63  5274.4  445.63
#Mann= 4 ,-1 , 0
  4643.7      .1       0  4996.7     .07       0  5002.7      .1       0
  5121.9     .16       0
Bank Sta=4996.7,5002.7
XS Rating Curve= 0 ,0
Exp/Cntr=0.3,0.1

Type RM Length L Ch R = 1 ,959     ,56,56,56
BEGIN DESCRIPTION:
SMITH CREEK TRIBUTARY 2 2.2
END DESCRIPTION:
XS GIS Cut Line= 3
      3540775.08     10330041.16      3540369.62     10330010.24
      3540099.02     10330196.59
#Sta/Elev= 30
  4604.1  428.98  4657.2  425.77  4717.4  421.05  4727.4   419.9  4747.5  416.19
  4757.5   415.1  5122.4  414.76  5125.2  414.26  5128.4  414.76  5146.4  415.33
  5153.4  414.85  5161.3  415.37  5167.4  414.83  5182.2  414.88  5189.8  415.08
  5197.1  416.25  5203.2  415.31    5212  416.67  5218.1  416.02  5226.3  417.05
    5233  418.71    5239  417.62  5247.9  419.18  5253.9  418.29  5262.7  419.84
  5268.8  421.55  5274.9  420.86  5283.7  422.27  5289.8  422.02  5339.3  424.93
#Mann= 3 ,-1 , 0
  4604.1      .1       0  5122.4     .07       0  5128.4      .1       0
Bank Sta=5122.4,5128.4
XS Rating Curve= 0 ,0
Exp/Cntr=0.3,0.1

Type RM Length L Ch R = 1 ,903     ,112,112,112
BEGIN DESCRIPTION:
SMITH CREEK TRIBUTARY 2 2.1
END DESCRIPTION:
XS GIS Cut Line= 3
       3540768.2     10329986.19      3540362.75     10329955.26
      3540092.14     10330141.62
#Sta/Elev= 30
  4579.4  427.67  4685.8  420.97    4766  422.88  4806.2  419.96  4830.8  416.42
  4833.6  415.92  4836.8  416.42  4838.8  420.43  4876.4   419.6  4916.5  420.71
  4946.6  423.31  4969.8  424.04  5005.6  422.88  5026.5  423.75  5092.1  422.49
  5113.1  423.12    5128  421.94  5148.9  422.78  5163.8  421.25  5169.9  422.45
  5178.7   421.4  5184.8  422.49  5199.7  420.13  5205.7   421.7  5214.5  420.26
  5220.6  421.71  5229.4  420.38  5235.5  421.74  5250.4  420.77  5314.6  425.68
#Mann= 3 ,-1 , 0
  4579.4      .1       0  4830.8     .07       0  4836.8      .1       0
Bank Sta=4830.8,4836.8
XS Rating Curve= 0 ,0
Exp/Cntr=0.3,0.1

Type RM Length L Ch R = 1 ,791     ,475,475,475
BEGIN DESCRIPTION:
SMITH CREEK TRIBUTARY 2 2.0
END DESCRIPTION:
XS GIS Cut Line= 3
      3540730.36     10329876.24      3540324.96     10329845.32
      3540055.71     10330030.73
#Sta/Elev= 30
  4554.6  421.54  4723.3   412.6  4803.6   410.6  4810.4  409.53  4815.4  406.41
  4833.7   406.1  4843.7  404.12  4853.7  402.85  4883.8  402.71  4893.8  406.74
  4903.9   408.6  4923.9  408.98  4941.4  408.69  4960.1   402.5    4979  402.18
  4981.8  401.68    4985  402.18  5025.4  402.91  5041.5  402.77  5053.7  402.28
  5061.8  404.33  5068.6  408.17  5074.7  408.45  5083.5  410.22    5107  411.73
  5134.2  413.13    5212  419.31  5226.8  421.16  5262.7  424.64  5288.1  425.14
#Mann= 5 ,-1 , 0
  4554.6      .1       0    4979     .07       0    4985      .1       0
  5041.5     .16       0    5107      .1       0
Bank Sta=4979,4985
XS Rating Curve= 0 ,0
Exp/Cntr=0.3,0.1

Type RM Length L Ch R = 1 ,316     ,113,113,113
BEGIN DESCRIPTION:
SMITH CREEK TRIBUTARY 2 1.0
END DESCRIPTION:
XS GIS Cut Line= 3
      3540275.25     10329225.21      3540025.28     10329475.18
      3539720.21     10329711.33
#Sta/Elev= 30
  4602.1  429.94  4648.6  427.14  4679.6  424.93  4700.8  422.43  4708.1  422.27
  4736.1   420.2  4771.5  416.44  4799.8  414.58  4806.9  414.66  4856.4  410.25
  4898.8  407.25  4912.9  406.81  4925.8  405.49  4934.1  405.07  4941.2  403.42
  4948.3  403.74  4954.3  402.45  4967.1  402.17  4969.9  401.67  4973.1  402.17
  5011.9  402.27  5048.1  402.17  5069.7   405.6    5105  406.47  5119.5  407.65
  5198.3  410.47  5261.2  413.53  5318.7  415.15  5333.2  414.72  5341.4  415.46
#Mann= 8 ,-1 , 0
  4602.1      .1       0  4648.6     .05       0  4708.1      .1       0
  4925.8     .07       0  4967.1     .07       0  4973.1     .07       0
  5011.9      .1       0  5261.2     .05       0
Bank Sta=4967.1,4973.1
XS Rating Curve= 0 ,0
Exp/Cntr=0.3,0.1

Type RM Length L Ch R = 1 ,203     ,40,40,40
BEGIN DESCRIPTION:
SMITH CREEK TRIBUTARY 2 1.03
END DESCRIPTION:
XS GIS Cut Line= 5
      3540190.54     10329212.63       3539944.2     10329394.94
       3539828.1     10329488.25      3539757.57      10329644.5
      3539702.21     10329700.94
#Sta/Elev= 30
  4653.4  424.29  4655.6  424.29  4658.9  423.52  4682.3  422.02    4709  419.49
  4794.6  412.53    4830   410.6  4838.1  409.83  4844.7  408.46  4850.9  408.18
  4880.1  403.08  4894.8  402.76    4901  402.12  4988.2  402.42  5023.4  402.02
  5129.3  401.86    5132  401.36  5135.3  401.86  5167.4  402.32  5178.4  403.49
    5184  405.13  5189.5  405.68  5207.1  408.91  5212.6  409.49  5230.2   410.2
  5235.7  410.09  5289.2  412.63  5324.5   413.1  5334.9  413.63  5359.3  414.16
#Mann= 5 ,-1 , 0
  4653.4     .05       0  4682.3      .1       0  5129.3     .07       0
  5135.3      .1       0  5334.9     .05       0
Bank Sta=5129.3,5135.3
XS Rating Curve= 0 ,0
Exp/Cntr=0.3,0.1

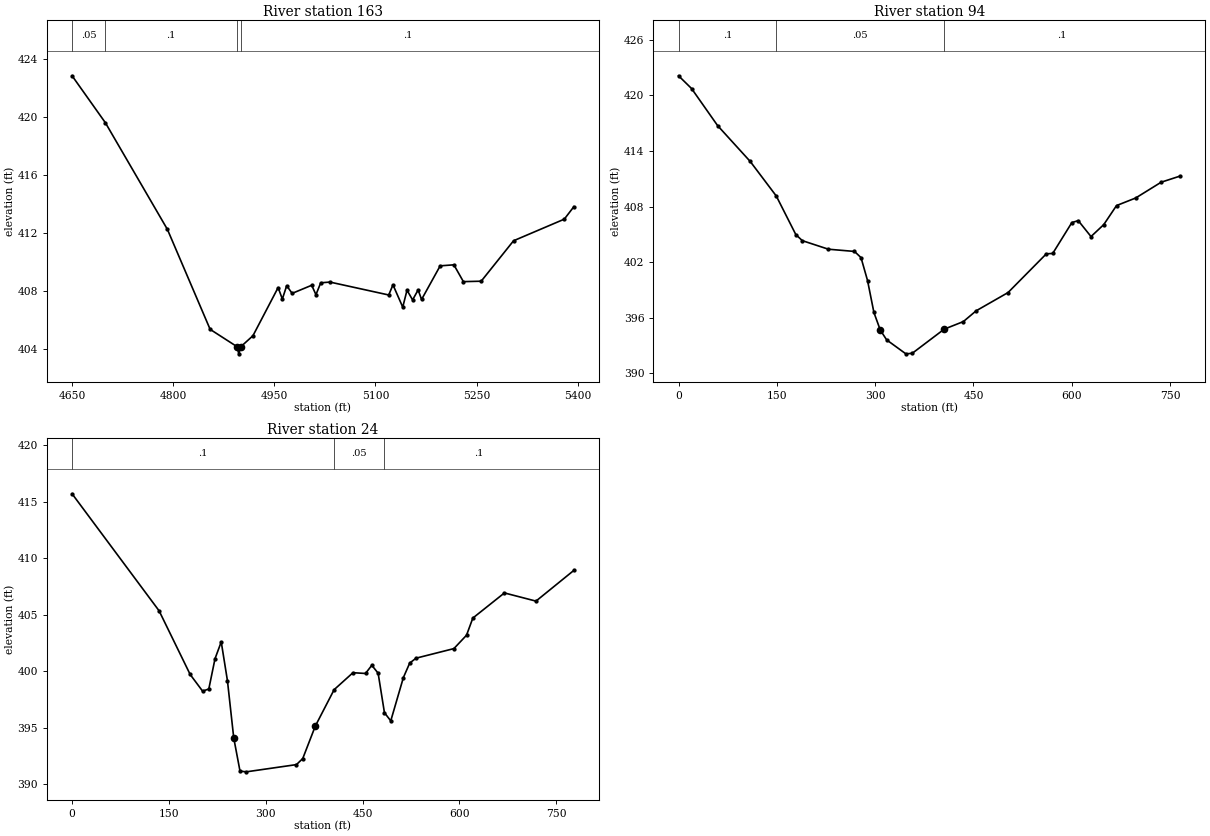
Type RM Length L Ch R = 1 ,163     ,69,69,69
BEGIN DESCRIPTION:
SMITH CREEK TRIBUTARY 2 1.02
END DESCRIPTION:
XS GIS Cut Line= 4
      3540164.49     10329176.82      3539757.57     10329489.34
      3539734.78     10329631.48      3539677.07     10329696.53
#Sta/Elev= 30
  4650.2  422.87  4699.6  419.63  4791.6  412.27  4854.9  405.38  4894.6  404.19
  4897.4  403.69  4900.6  404.19  4918.4  404.94  4955.7  408.26    4962  407.47
  4968.4  408.39  4976.5  407.86  5005.5  408.42  5011.8  407.77  5018.9  408.59
  5032.6  408.64  5119.7  407.75    5126  408.45  5140.5  406.91  5146.8  408.08
  5155.1  407.41  5163.3   408.1  5168.4  407.44    5196  409.76  5216.3  409.83
  5230.4  408.67  5256.8   408.7  5304.8  411.49    5380  412.98  5394.2  413.84
#Mann= 4 ,-1 , 0
  4650.2     .05       0  4699.6      .1       0  4894.6     .07       0
  4900.6      .1       0
Bank Sta=4894.6,4900.6
XS Rating Curve= 0 ,0
Exp/Cntr=0.3,0.1

Type RM Length L Ch R = 1 ,94      ,50,50,50
XS GIS Cut Line= 4
     3540141.995     10329168.13     3539888.089    10329301.594
     3539723.158    10329427.462     3539636.352    10329685.708
#Sta/Elev= 30
       0422.131519.88796420.752559.66389 416.741109.3838412.8701149.1597409.1342
178.9917404.9617188.9356 404.307228.7116403.3835268.4875403.1434278.4315402.4763
288.3755400.0006298.1225396.5431307.8696394.6381317.6166393.5786346.8578392.0739
356.6048392.1314405.3401394.7413434.5813395.5598454.0754396.7237502.7989398.6992
561.2103402.8854570.9456 402.926600.1512 406.263609.8865406.4751 629.357404.7513
648.8275406.0431668.2979408.1009697.5037408.9194736.4446410.6277765.6503 411.298
#Mann= 3 ,-1 , 0
       0      .1       0149.1597     .05       0405.3401      .1       0
Bank Sta=307.8696,405.3401
XS Rating Curve= 0 ,0
Exp/Cntr=0.3,0.1

Type RM Length L Ch R = 1 ,24      ,0,0,0
XS GIS Cut Line= 4
     3540074.721    10329133.408     3539857.707    10329232.149
     3539697.116    10329369.953      3539595.12    10329675.943
#Sta/Elev= 30
       0415.7212 134.819 405.363182.9686399.7263202.2284398.2513211.8584398.4408
221.4883401.1239231.1182402.6093240.7481399.1691250.4704394.1141260.1927391.1708
 269.915 391.107347.6935391.7475357.4158392.2857376.8604395.1567406.0273398.3808
435.1942 399.882454.6389399.8152464.4212400.5396474.2035399.8375483.9858396.3417
493.7682395.6196513.3328399.4548523.1152400.7325532.8975401.1679591.5915402.0161
611.1561403.2006620.9385404.7186669.8501406.9437718.7618406.2196777.4557408.9399
#Mann= 3 ,-1 , 0
       0      .1       0406.0273     .05       0483.9858      .1       0
Bank Sta=250.4704,376.8604
XS Rating Curve= 0 ,0
Exp/Cntr=0.3,0.1

Chan Stop Cuts=-1
Use User Specified Reach Order=0
Composite Channel Slope=5