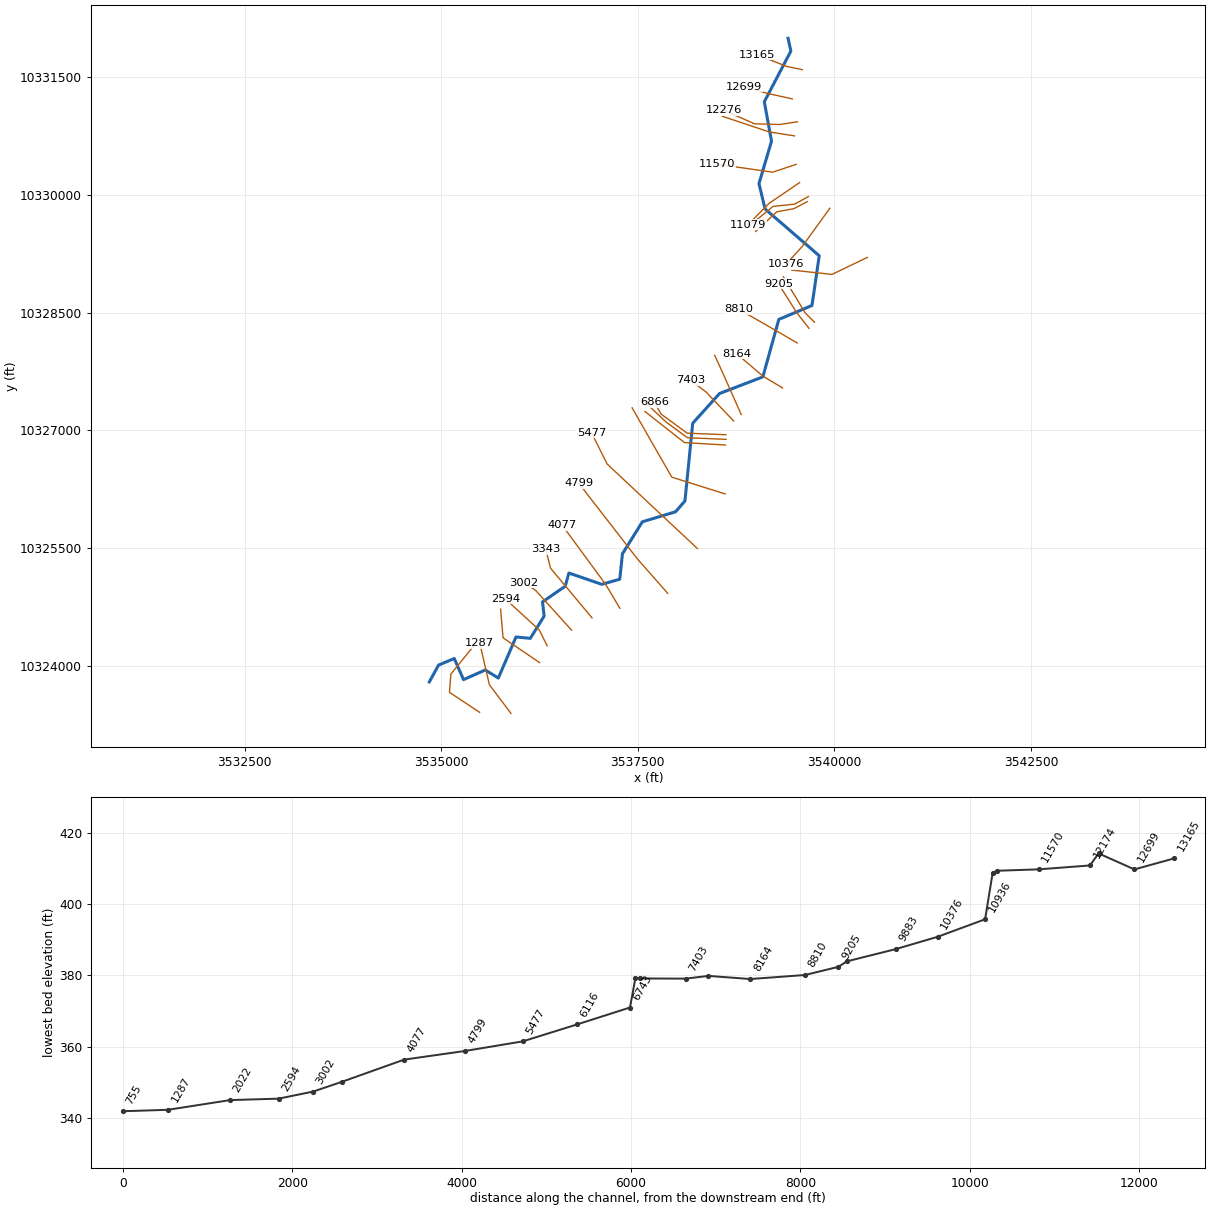
--- SMITH CREEK.prj (project) ---

Proj Title=SMITH CREEK Base Level Engineering
Current Plan=p01
Default Exp/Contr=0.3,0.1
English Units
Geom File=g01
Flow File=f01
Plan File=p01
Y Axis Title=Elevation
X Axis Title(PF)=Main Channel Distance
X Axis Title(XS)=Station
BEGIN DESCRIPTION:
SMITH CREEK
END DESCRIPTION:
DSS Export Rating Curves= 0
DSS Export Rating Curve Sorted= 0
DSS Export Volume Flow Curves= 0
DXF OffsetX= 0
DXF OffsetY= 0
DXF ScaleX= 1
DXF ScaleY= 10

--- SMITH CREEK.p01 (plan) ---

Plan Title=Multiple Run
Short Identifier=Multiple
Geom File=g01
Flow File=f01
Subcritical Flow
K Sum by GR= 0
Std Step Tol= 0.01
Critical Tol= 0.01
Num of Std Step Trials= 20
Max Error Tol= 0.3
Flow Tol Ratio= 0.001
Split Flow NTrial= 30
Split Flow Tol= 0.02
Split Flow Ratio= 0.02
Log Output Level= 0
Friction Slope Method= 1
Unsteady Friction Slope Method= 2
Unsteady Bridges Friction Slope Method= 1
Parabolic Critical Depth
Global Vel Dist=  1 , 1 , 1
Global Log Level= 0
CheckData=True
Encroach Param= -1, 0, 0, 0
BEGIN DESCRIPTION:
Multiple Run
END DESCRIPTION:

--- SMITH CREEK.f01 (steady flow) ---

Flow Title=Multiple
Number of Profiles=7
Profile Names=10-year,25-year,50-year,1pct_min,100-year,1pct_plu,500-year
River Rch & RM= SMITH CREEK,Reach-1,13165
     288     376     446     389     526     712     732
River Rch & RM= SMITH CREEK,Reach-1,9883
     454     609     735     652     881    1192    1268
River Rch & RM= SMITH CREEK,Reach-1,4799
     692     951    1166    1048    1417    1916    2096
Boundary for River Rch & Prof#=SMITH CREEK,Reach-1,1
Up Type=0
Dn Type=3
Dn Slope=0.005
Boundary for River Rch & Prof#=SMITH CREEK,Reach-1,2
Up Type=0
Dn Type=3
Dn Slope=0.005
Boundary for River Rch & Prof#=SMITH CREEK,Reach-1,3
Up Type=0
Dn Type=3
Dn Slope=0.005
Boundary for River Rch & Prof#=SMITH CREEK,Reach-1,4
Up Type=0
Dn Type=3
Dn Slope=0.005
Boundary for River Rch & Prof#=SMITH CREEK,Reach-1,5
Up Type=0
Dn Type=3
Dn Slope=0.005
Boundary for River Rch & Prof#=SMITH CREEK,Reach-1,6
Up Type=0
Dn Type=3
Dn Slope=0.005
Boundary for River Rch & Prof#=SMITH CREEK,Reach-1,7
Up Type=0
Dn Type=3
Dn Slope=0.005

--- SMITH CREEK.g01 (geometry) ---

Geom Title=Existing Conditions
Program Version=4.10

River Reach=SMITH CREEK     ,Reach-1
Reach XY= 30
      3539412.36     10331990.42      3539447.83     10331828.54
      3539110.16     10331183.14      3539201.81     10330681.62
      3539042.09     10330141.23      3539120.58     10329818.07
      3539808.66     10329223.62      3539716.23     10328590.67
      3539294.52      10328413.4      3539091.95     10327682.06
      3538540.74     10327470.26      3538199.59     10327091.78
       3538100.8     10326102.35      3537980.66     10325964.74
      3537559.54     10325837.88      3537306.15     10325430.35
      3537272.09      10325107.3       3537042.4      10325042.2
      3536625.11     10325185.82      3536578.11     10325017.47
      3536289.52      10324818.3      3536310.23     10324637.44
       3536134.6      10324354.4      3535952.54     10324371.97
      3535727.58     10323848.93      3535562.13     10323951.94
       3535285.4     10323829.38      3535167.34     10324097.81
      3534967.65     10324014.29      3534849.98     10323799.52

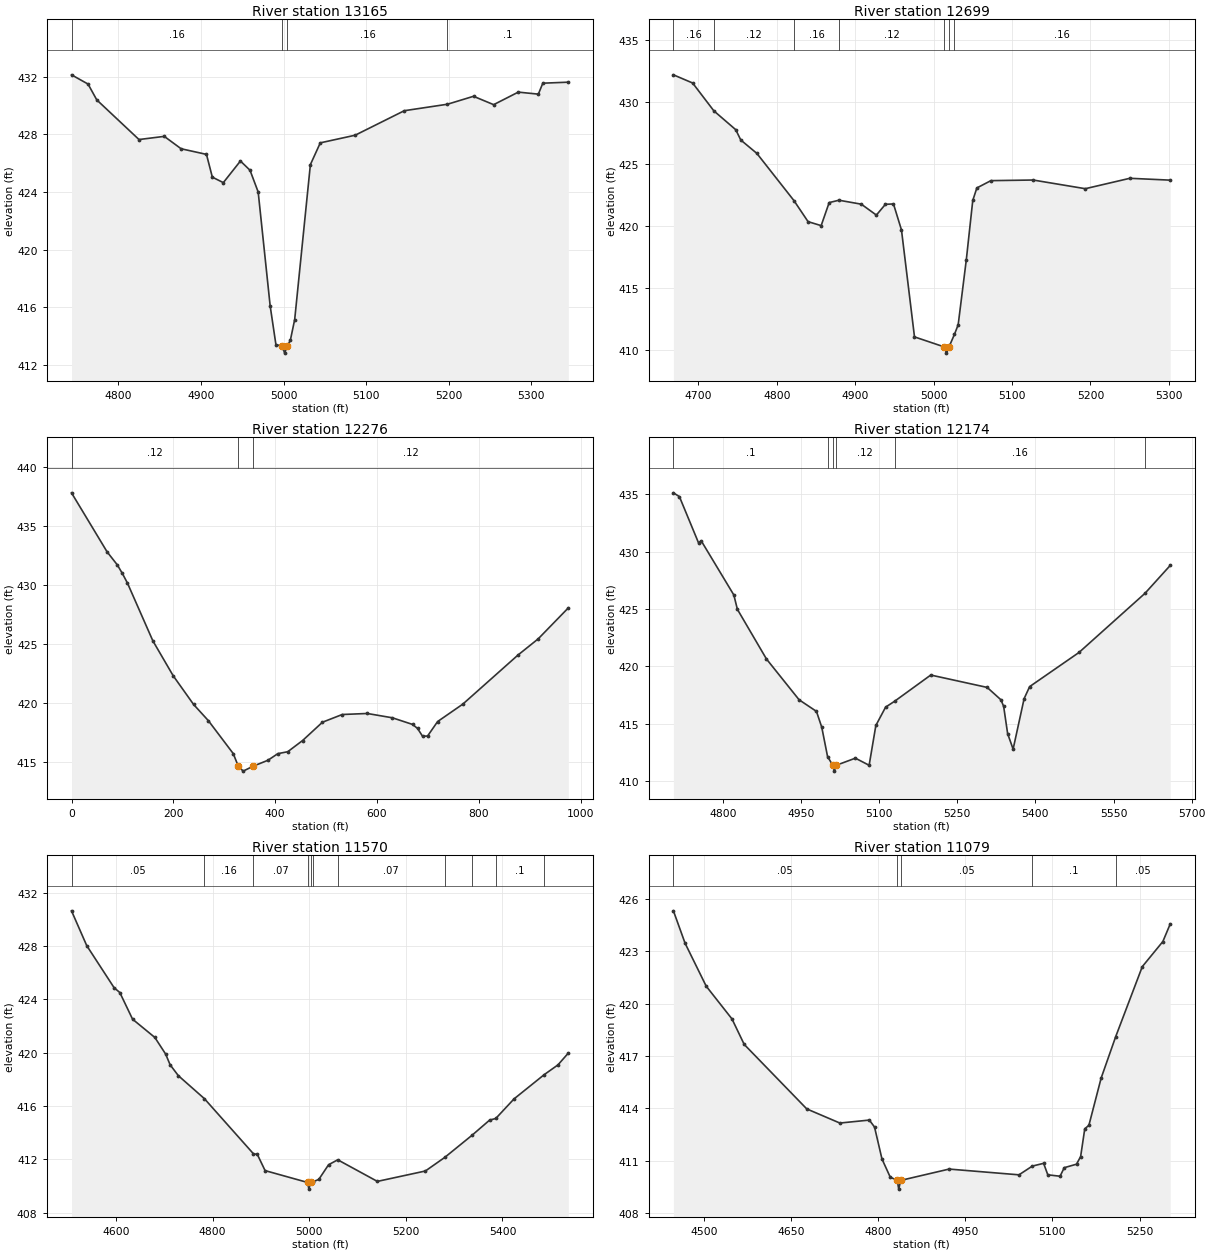
Type RM Length L Ch R = 1 ,13165   ,466,466,466
BEGIN DESCRIPTION:
SMITH CREEK 27.0
END DESCRIPTION:
XS GIS Cut Line= 3
      3539592.07     10331591.65      3539397.26     10331631.99
      3539022.79     10331779.72
#Sta/Elev= 30
  4743.2  432.13  4763.2  431.49  4773.8  430.39  4824.9  427.64  4855.5  427.86
  4875.9     427  4906.6  426.61  4913.7  425.03    4927  424.65  4947.7  426.15
  4959.3  425.51  4969.2     424  4983.7   416.1  4990.7   413.4  4998.4  413.32
  5001.2  412.82  5004.4  413.32  5008.1   413.7  5013.4  415.15  5032.4   425.9
  5044.4  427.41  5086.6  427.94  5146.1  429.64  5198.4  430.09  5229.9  430.64
  5254.3  430.06  5284.1  430.93  5308.4  430.79  5313.8  431.55  5344.7  431.62
#Mann= 4 ,-1 , 0
  4743.2     .16       0  4998.4     .07       0  5004.4     .16       0
  5198.4      .1       0
Bank Sta=4998.4,5004.4
XS Rating Curve= 0 ,0
Exp/Cntr=0.3,0.1

Type RM Length L Ch R = 1 ,12699   ,423,423,423
BEGIN DESCRIPTION:
SMITH CREEK 26.0
END DESCRIPTION:
XS GIS Cut Line= 3
      3539465.98     10331219.68      3539142.11     10331291.64
      3538852.77      10331377.2
#Sta/Elev= 30
  4668.2  432.21  4692.7  431.55  4719.8   429.3  4747.7  427.78  4754.1  426.95
  4774.6  425.87  4821.9  422.06  4839.9  420.36  4856.6  420.04  4866.8   421.9
  4879.3  422.09  4907.8  421.77    4927  420.89  4938.5  421.76  4948.8  421.79
    4959  419.69  4975.6  411.06  5013.6  410.25  5016.4  409.75  5019.6  410.25
  5026.6  411.27  5031.3  412.04  5041.7   417.3  5049.9  422.07  5055.1  423.08
    5073  423.67  5126.9  423.72  5193.4  423.02  5250.2  423.86  5301.7  423.71
#Mann= 7 ,-1 , 0
  4668.2     .16       0  4719.8     .12       0  4821.9     .16       0
  4879.3     .12       0  5013.6     .07       0  5019.6     .12       0
  5026.6     .16       0
Bank Sta=5013.6,5019.6
XS Rating Curve= 0 ,0
Exp/Cntr=0.3,0.1

Type RM Length L Ch R = 1 ,12276   ,102,102,102
XS GIS Cut Line= 4
     3539531.232    10330928.433     3539305.538    10330893.711
     3538987.613    10330902.391     3538595.902    10331073.832
#Sta/Elev= 30
       0 437.77669.92673432.783389.90579 431.68699.89533430.9591109.8849430.1442
159.8325425.2559199.7907422.3036239.7488419.8827268.9583418.5024317.6408415.7276
327.3773414.6816337.1138414.2413356.5868414.6533385.7963415.1588405.2693415.7186
424.7423415.8819453.9518416.8299492.8978418.3769531.8438419.0298580.9404419.1159
 630.313418.7515669.8112418.1918679.6857417.8529689.5602417.1913699.4348417.2101
719.1838418.4351768.5565419.9051877.1763424.0639916.6744425.4256975.9216428.0479
#Mann= 3 , 0 , 0
       0     .12       0327.3773     .07       0356.5868     .12       0
Bank Sta=327.3773,356.5868
XS Rating Curve= 0 ,0
Exp/Cntr=0.3,0.1

Type RM Length L Ch R = 1 ,12174   ,604,604,604
BEGIN DESCRIPTION:
SMITH CREEK 25.0
END DESCRIPTION:
XS GIS Cut Line= 3
      3539493.44     10330748.97      3539174.93     10330798.87
      3538576.02     10330998.51
#Sta/Elev= 30
  4705.2  435.13  4716.7   434.8  4753.4  430.77  4758.5  430.95  4821.2  426.22
    4828  424.97  4883.8  420.64  4946.5  417.08  4979.8  416.07    4990  414.68
  5001.1  412.13  5011.2  411.36    5014  410.86  5017.2  411.36  5054.5  411.99
  5080.9  411.37  5093.8  414.84  5112.5  416.44  5129.7  416.95  5199.2  419.24
  5307.5  418.16  5333.9  417.08  5339.1  416.51  5346.8  414.12  5357.3  412.78
  5378.4  417.18    5389  418.23  5483.8  421.21  5610.3  426.36  5658.9   428.8
#Mann= 6 ,-1 , 0
  4705.2      .1       0  5001.1     .12       0  5011.2     .07       0
  5017.2     .12       0  5129.7     .16       0  5610.3      .1       0
Bank Sta=5011.2,5017.2
XS Rating Curve= 0 ,0
Exp/Cntr=0.3,0.1

Type RM Length L Ch R = 1 ,11570   ,491,491,491
BEGIN DESCRIPTION:
SMITH CREEK 24.0
END DESCRIPTION:
XS GIS Cut Line= 3
      3539515.77     10330387.02       3539215.8     10330287.03
      3538510.81     10330388.19
#Sta/Elev= 30
  4507.9  430.65  4539.4  428.04  4596.1  424.88  4607.9  424.52  4634.3  422.52
  4680.4  421.15  4702.8   419.9    4712   419.1  4729.1  418.28  4782.9  416.56
  4884.3  412.43  4892.6  412.37  4908.6  411.16  4996.6  410.27  4999.3  409.77
  5002.6  410.27  5007.1  410.31  5019.8   410.5    5040   411.6    5059  411.97
    5141  410.35  5240.4  411.13  5280.5  412.15  5336.9  413.81  5373.4  414.95
  5386.1  415.07  5423.9  416.54  5486.4  418.36  5514.8  419.09  5536.3  419.98
#Mann= 11 ,-1 , 0
  4507.9     .05       0  4782.9     .16       0  4884.3     .07       0
  4996.6     .07       0  5002.6     .07       0  5007.1     .16       0
    5059     .07       0  5280.5      .1       0  5336.9     .16       0
  5386.1      .1       0  5486.4     .16       0
Bank Sta=4996.6,5002.6
XS Rating Curve= 0 ,0
Exp/Cntr=0.3,0.1

Type RM Length L Ch R = 1 ,11079   ,54,54,54
BEGIN DESCRIPTION:
SMITH CREEK 23.1
END DESCRIPTION:
XS GIS Cut Line= 3
      3539558.72     10330154.53      3539170.49     10329889.98
      3538899.83     10329615.89
#Sta/Elev= 30
  4447.8  425.33  4467.9  423.47  4504.2  421.01  4548.6  419.13  4569.6  417.67
  4677.3  413.97  4734.2  413.16    4785  413.33  4793.9  412.93  4806.7   411.1
  4820.9  410.06  4832.9  409.87  4835.6  409.37  4838.9  409.87  4922.3  410.52
  5042.5  410.19  5065.4  410.69  5084.9  410.85  5092.1  410.19  5113.2  410.11
  5120.4   410.6  5141.5   410.8  5148.6  411.24  5155.7  412.83  5162.8  413.03
  5183.9  415.74    5209  418.12  5254.7  422.13  5290.1  423.57  5302.8  424.58
#Mann= 5 ,-1 , 0
  4447.8     .05       0  4832.9    .033       0  4838.9     .05       0
  5065.4      .1       0    5209     .05       0
Bank Sta=4832.9,4838.9
XS Rating Curve= 0 ,0
Exp/Cntr=0.3,0.1

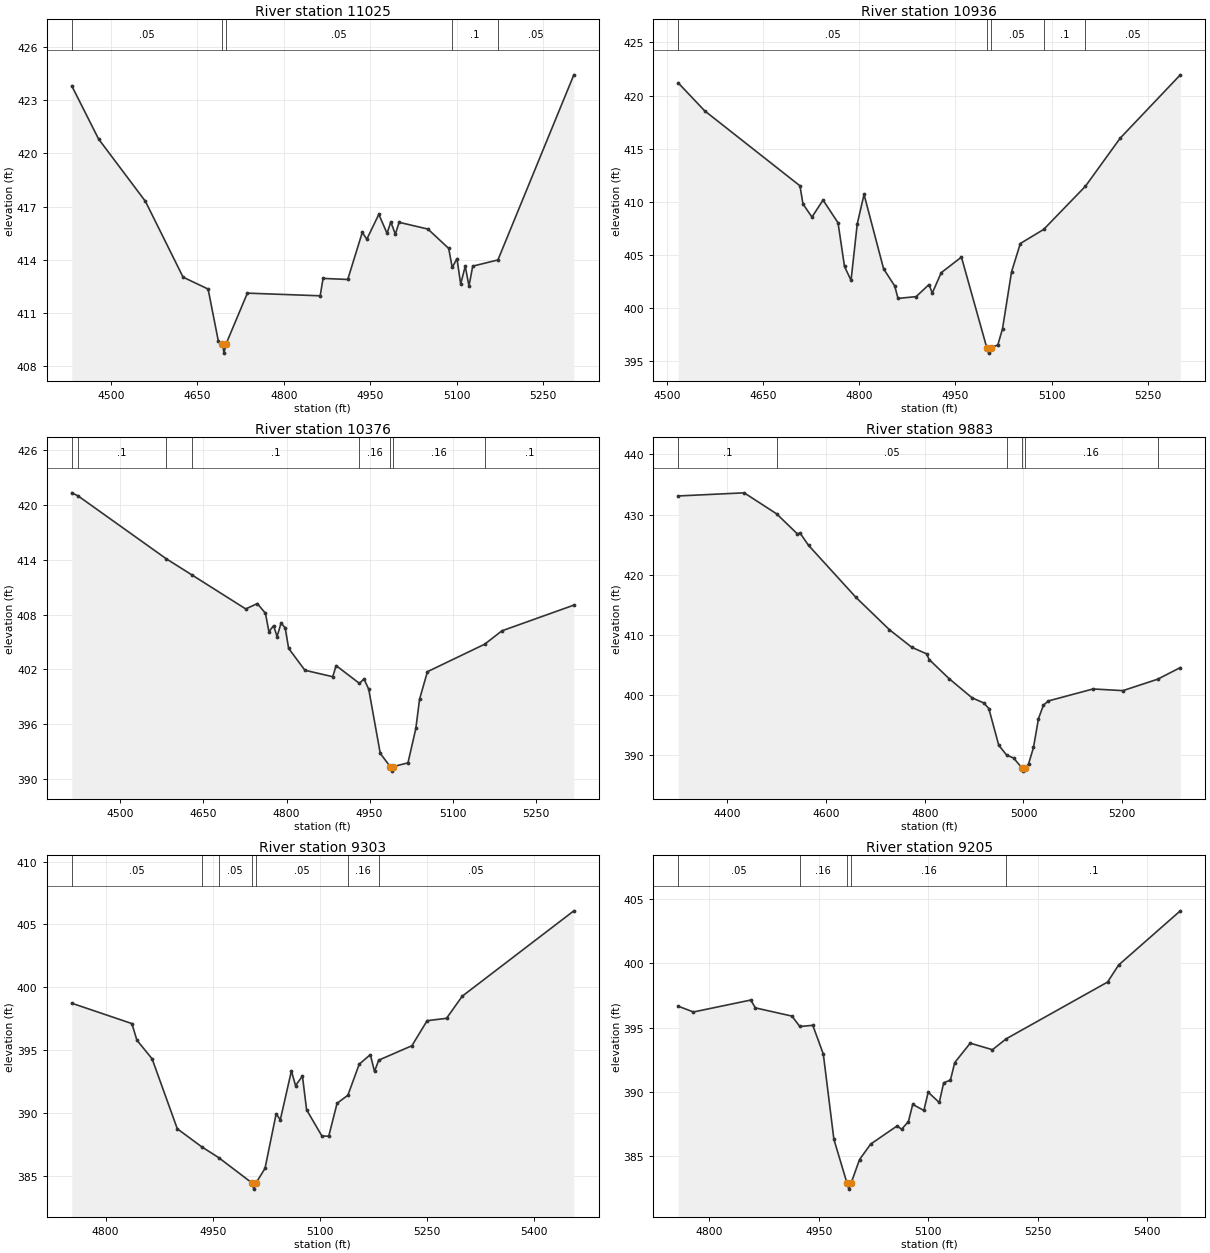
Type RM Length L Ch R = 1 ,11025   ,89,89,89
BEGIN DESCRIPTION:
SMITH CREEK 23.0
END DESCRIPTION:
XS GIS Cut Line= 4
      3539671.13     10329977.15      3539494.72     10329879.92
      3539222.03     10329852.19      3538916.64     10329601.08
#Sta/Elev= 30
    4432  423.81  4478.4  420.82  4559.8   417.3  4625.1  413.03  4668.5  412.36
  4686.3  409.42  4693.4  409.25  4696.1  408.75  4699.4  409.25  4736.6  412.13
  4862.9  411.98  4867.9  412.96  4910.7   412.9  4935.9  415.55  4943.8  415.17
  4964.6  416.57  4978.9   415.5  4985.4  416.14  4993.3  415.45  4999.8  416.12
  5049.8  415.74  5085.8  414.65  5091.9  413.58  5100.2  414.07  5106.6  412.64
  5114.5  413.65    5121  412.53  5127.5  413.65  5171.2     414  5302.9  424.43
#Mann= 5 ,-1 , 0
    4432     .05       0  4693.4     .03       0  4699.4     .05       0
  5091.9      .1       0  5171.2     .05       0
Bank Sta=4693.4,4699.4
XS Rating Curve= 0 ,0
Exp/Cntr=0.3,0.1

Type RM Length L Ch R = 1 ,10936   ,560,560,560
BEGIN DESCRIPTION:
SMITH CREEK 22.0
END DESCRIPTION:
XS GIS Cut Line= 4
      3539658.63     10329912.57       3539484.3     10329822.28
      3539270.13     10329783.47      3538998.66     10329532.62
#Sta/Elev= 30
  4517.3  421.19  4558.4  418.57  4707.3   411.5    4712  409.79    4726  408.56
  4743.3  410.16  4766.7  408.02  4776.8  403.91    4787   402.6  4796.7  407.92
  4807.3  410.69  4837.8  403.69  4855.2  402.07  4860.3   400.9  4888.6  401.07
  4908.7  402.21  4913.8   401.4  4927.7  403.32  4959.3  404.79  4998.9  396.25
  5001.6  395.75  5004.9  396.25  5016.1  396.52  5023.4  398.04  5037.5   403.4
  5051.2  406.07  5087.7   407.4  5152.8  411.46  5207.1  415.99  5300.9  421.95
#Mann= 5 ,-1 , 0
  4517.3     .05       0  4998.9     .03       0  5004.9     .05       0
  5087.7      .1       0  5152.8     .05       0
Bank Sta=4998.9,5004.9
XS Rating Curve= 0 ,0
Exp/Cntr=0.3,0.1

Type RM Length L Ch R = 1 ,10376   ,493,493,493
BEGIN DESCRIPTION:
SMITH CREEK 21.0
END DESCRIPTION:
XS GIS Cut Line= 3
      3539943.56     10329828.13      3539592.11     10329341.64
      3539387.02     10329113.54
#Sta/Elev= 30
  4412.1  421.35  4423.1  421.03  4582.8  414.12  4629.9  412.32  4726.4  408.62
  4747.3  409.21    4762  408.14  4768.2  406.12  4776.7  406.79  4782.9  405.59
  4790.2  407.08  4797.6  406.54  4803.8   404.3  4833.2   401.9  4883.5  401.19
  4889.6  402.41  4931.7  400.46  4939.9  400.95  4948.5  399.82  4969.3  392.79
  4987.2  391.34    4990  390.84  4993.2  391.34  5019.4  391.75  5033.6  395.52
  5040.3  398.72  5054.5  401.74  5158.1  404.76    5189  406.22    5319  409.04
#Mann= 8 ,-1 , 0
  4412.1     .16       0  4423.1      .1       0  4582.8     .05       0
  4629.9      .1       0  4931.7     .16       0  4987.2     .07       0
  4993.2     .16       0  5158.1      .1       0
Bank Sta=4987.2,4993.2
XS Rating Curve= 0 ,0
Exp/Cntr=0.3,0.1

Type RM Length L Ch R = 1 ,9883    ,580,580,580
BEGIN DESCRIPTION:
SMITH CREEK 20.0
END DESCRIPTION:
XS GIS Cut Line= 3
      3540421.16      10329202.8      3539971.06     10328986.34
      3539456.42     10329041.23
#Sta/Elev= 30
  4300.7   433.1  4434.3  433.62    4500  430.13  4541.9  426.81  4547.5  426.93
  4564.6   424.9  4660.6  416.26  4728.5  410.88  4773.8  407.96  4803.6  406.88
  4809.1  405.92  4849.4  402.75    4896  399.56  4919.8  398.71  4929.8  397.79
  4949.9   391.7  4966.1  390.04  4980.1  389.56  4997.2  387.89    5000  387.39
  5003.2  387.89  5010.3  388.58  5020.3  391.32  5030.4  396.11  5040.5  398.36
  5050.5  399.05    5141  401.04  5201.4  400.76  5271.5  402.65  5317.7  404.59
#Mann= 6 ,-1 , 0
  4300.7      .1       0    4500     .05       0  4966.1     .16       0
  4997.2     .07       0  5003.2     .16       0  5271.5      .1       0
Bank Sta=4997.2,5003.2
XS Rating Curve= 0 ,0
Exp/Cntr=0.3,0.1

Type RM Length L Ch R = 1 ,9303    ,98,98,98
BEGIN DESCRIPTION:
SMITH CREEK 19.0
END DESCRIPTION:
XS GIS Cut Line= 3
      3539747.71      10328378.2       3539630.9       10328495.
      3539352.58     10328955.43
#Sta/Elev= 30
  4752.5  398.73  4836.7  397.11  4843.7  395.79    4865  394.31  4900.3  388.74
  4934.9  387.29  4958.2  386.45  5004.7  384.44  5007.5  383.94  5010.7  384.44
  5023.2   385.6  5038.7  389.92  5044.6  389.46  5060.1  393.34  5065.9  392.18
  5075.6  392.93  5081.4  390.25  5102.8  388.17  5112.4  388.15  5124.1  390.77
  5139.2  391.41  5155.1  393.88  5170.7  394.64  5176.5   393.3  5182.4   394.2
  5228.9  395.35  5250.2  397.34  5277.4  397.53  5299.4  399.29  5455.7  406.08
#Mann= 7 ,-1 , 0
  4752.5     .05       0  4934.9     .16       0  4958.2     .05       0
  5004.7     .04       0  5010.7     .05       0  5139.2     .16       0
  5182.4     .05       0
Bank Sta=5004.7,5010.7
XS Rating Curve= 0 ,0
Exp/Cntr=0.3,0.1

Type RM Length L Ch R = 1 ,9205    ,395,395,395
BEGIN DESCRIPTION:
SMITH CREEK 18.0
END DESCRIPTION:
XS GIS Cut Line= 3
      3539679.01     10328299.14      3539527.82     10328491.56
      3539290.73     10328866.11
#Sta/Elev= 30
  4757.2  396.66    4778  396.21  4856.6  397.14  4862.9  396.53    4913  395.89
  4923.8  395.08  4941.6  395.17    4956  392.93  4970.5  386.29  4988.3  382.91
    4991  382.41  4994.3  382.91  5005.6  384.71  5020.9  385.92  5057.3  387.34
  5063.2  387.07  5072.6  387.67  5078.5  389.01  5093.8  388.54  5099.7  389.96
  5114.9  389.16  5120.9  390.69  5130.2  390.91  5136.1  392.27  5157.3  393.78
  5187.8  393.27  5206.6  394.12  5345.5  398.54  5360.7  399.87  5445.2  404.09
#Mann= 5 ,-1 , 0
  4757.2     .05       0  4923.8     .16       0  4988.3     .07       0
  4994.3     .16       0  5206.6      .1       0
Bank Sta=4988.3,4994.3
XS Rating Curve= 0 ,0
Exp/Cntr=0.3,0.1

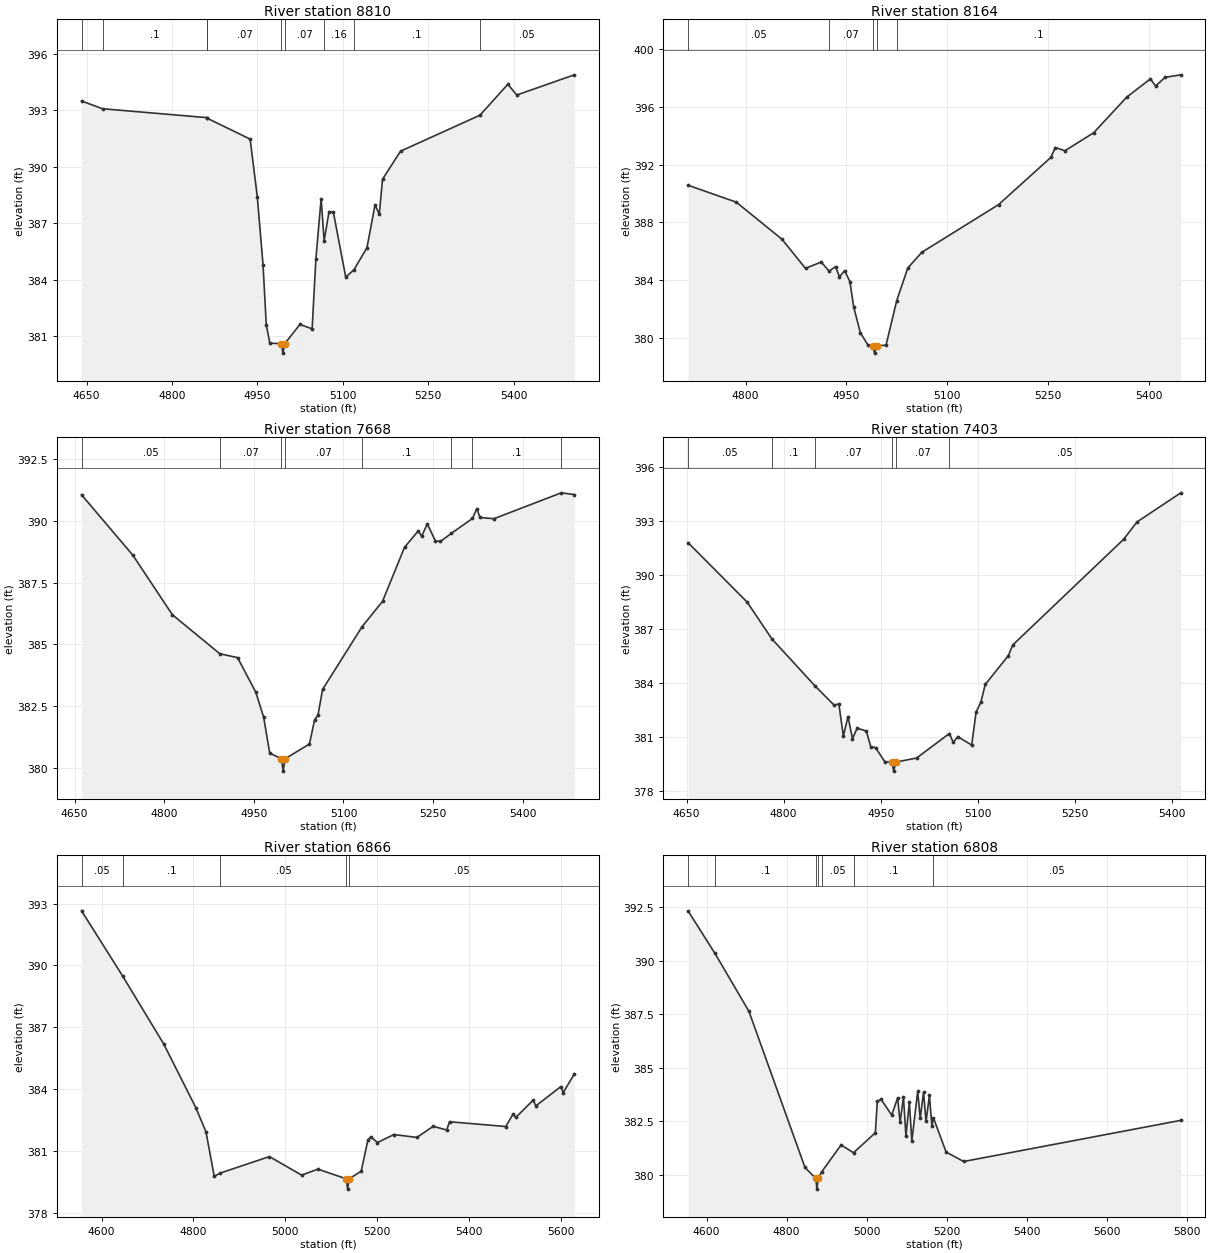
Type RM Length L Ch R = 1 ,8810    ,646,646,646
BEGIN DESCRIPTION:
SMITH CREEK 17.0
END DESCRIPTION:
XS GIS Cut Line= 3
      3539527.81     10328113.62      3539304.49     10328244.18
      3538778.82     10328546.53
#Sta/Elev= 30
  4641.2  393.48  4678.3  393.07  4861.3   392.6  4862.3  392.56  4937.2  391.46
  4949.7  388.41  4959.8   384.8  4965.5  381.61  4971.8  380.64  4991.9  380.61
  4994.7  380.11  4997.9  380.61  5024.5  381.63    5046   381.4  5052.6   385.1
  5061.8   388.3  5067.1  386.07  5075.7  387.62  5083.4  387.57    5105  384.14
  5119.4  384.53  5142.3   385.7  5156.4  387.97  5163.9  387.48  5169.6  389.33
  5201.2  390.82  5340.7  392.73  5389.6  394.37  5405.3   393.8  5506.3  394.87
#Mann= 9 ,-1 , 0
  4641.2     .05       0  4678.3      .1       0  4861.3     .16       0
  4862.3     .07       0  4991.9     .07       0  4997.9     .07       0
  5067.1     .16       0  5119.4      .1       0  5340.7     .05       0
Bank Sta=4991.9,4997.9
XS Rating Curve= 0 ,0
Exp/Cntr=0.3,0.1

Type RM Length L Ch R = 1 ,8164    ,496,496,496
BEGIN DESCRIPTION:
SMITH CREEK 16.0
END DESCRIPTION:
XS GIS Cut Line= 3
      3539342.11     10327541.64      3539092.11     10327691.64
      3538755.89     10327978.64
#Sta/Elev= 30
  4714.2  390.57  4786.1   389.4  4854.1  386.84  4889.1  384.83  4912.5  385.27
  4924.1  384.64  4933.8  384.95  4939.7  384.25  4947.4  384.67  4955.2  383.92
    4961  382.13  4970.8  380.38  4982.4  379.52  4989.1  379.48  4991.9  378.98
  4995.1  379.48    5009  379.53  5024.9   382.6  5041.4  384.86  5062.3  385.94
  5176.5  389.23  5254.4  392.49    5261  393.17  5275.3  392.95  5318.1  394.19
  5367.5  396.66  5402.6  397.91  5410.3  397.42  5424.6  398.02  5447.8  398.19
#Mann= 5 ,-1 , 0
  4714.2     .05       0  4924.1     .07       0  4989.1     .07       0
  4995.1     .07       0  5024.9      .1       0
Bank Sta=4989.1,4995.1
XS Rating Curve= 0 ,0
Exp/Cntr=0.3,0.1

Type RM Length L Ch R = 1 ,7668    ,265,265,265
BEGIN DESCRIPTION:
SMITH CREEK 15.0
END DESCRIPTION:
XS GIS Cut Line= 3
      3538816.59      10327203.1      3538613.87     10327660.07
      3538479.86     10327955.59
#Sta/Elev= 30
  4661.8  391.06  4747.7  388.61  4813.7   386.2    4893  384.62  4922.8  384.46
  4953.3  383.06  4966.5  382.04  4976.6  380.59  4996.3  380.36  4999.1  379.86
  5002.3  380.36  5043.1  380.96  5051.8  381.95  5057.3  382.12    5065  383.17
  5131.3  385.72  5165.3  386.74  5202.1  388.93  5225.2   389.6  5230.7  389.38
  5240.3  389.88  5253.8  389.19  5262.3  389.17  5280.6   389.5  5315.8   390.1
    5323   390.5  5328.5  390.14  5351.6  390.09  5464.3  391.14  5486.2  391.07
#Mann= 8 ,-1 , 0
  4661.8     .05       0    4893     .07       0  4996.3     .07       0
  5002.3     .07       0  5131.3      .1       0  5280.6     .05       0
  5315.8      .1       0  5464.3     .05       0
Bank Sta=4996.3,5002.3
XS Rating Curve= 0 ,0
Exp/Cntr=0.3,0.1

Type RM Length L Ch R = 1 ,7403    ,537,537,537
BEGIN DESCRIPTION:
SMITH CREEK 14.0
END DESCRIPTION:
XS GIS Cut Line= 3
      3538720.37     10327120.65      3538368.05     10327490.93
      3538168.05     10327640.93
#Sta/Elev= 30
  4652.3   391.8  4743.7  388.49  4781.7  386.45    4849  383.81    4878  382.76
  4885.3  382.83  4892.2  381.04  4899.4  382.12  4906.3   380.9  4913.6  381.48
  4927.7  381.32  4934.6  380.45  4941.9   380.4  4956.1  379.62  4967.2  379.59
    4970  379.09  4973.2  379.59  5005.4  379.82  5055.9  381.18    5062  380.69
  5068.9  381.01  5090.4  380.54  5097.3  382.38  5104.5  382.91  5111.4  383.91
    5147  385.51  5153.9  386.11    5325  391.98  5345.8  392.95  5413.4  394.57
#Mann= 6 ,-1 , 0
  4652.3     .05       0  4781.7      .1       0    4849     .07       0
  4967.2     .07       0  4973.2     .07       0  5055.9     .05       0
Bank Sta=4967.2,4973.2
XS Rating Curve= 0 ,0
Exp/Cntr=0.3,0.1

Type RM Length L Ch R = 1 ,6866    ,58,58,58
BEGIN DESCRIPTION:
SMITH CREEK 13.1
END DESCRIPTION:
XS GIS Cut Line= 4
      3538620.77      10326945.4      3538129.41     10326966.02
      3537795.85     10327209.66      3537714.95     10327356.83
#Sta/Elev= 30
  4556.5  392.65  4645.8  389.49  4735.3  386.19  4805.4  383.09  4827.5  381.91
  4845.4  379.76  4858.6  379.92  4965.5  380.72  5035.6  379.82  5071.1  380.11
    5133  379.64  5135.7  379.14    5139  379.64  5165.3  380.01    5180  381.53
  5186.2  381.68  5200.8   381.4  5236.4  381.79  5286.6  381.65  5322.1  382.19
  5351.4  382.01  5357.6  382.41  5480.1  382.18  5496.2  382.79  5501.9  382.62
  5539.8  383.46  5545.5  383.18  5599.5  384.11  5605.2  383.83  5629.3  384.73
#Mann= 5 ,-1 , 0
  4556.5     .05       0  4645.8      .1       0  4858.6     .05       0
    5133    .033       0    5139     .05       0
Bank Sta=5133,5139
XS Rating Curve= 0 ,0
Exp/Cntr=0.3,0.1

Type RM Length L Ch R = 1 ,6808    ,65,65,65
BEGIN DESCRIPTION:
SMITH CREEK 13.0
END DESCRIPTION:
XS GIS Cut Line= 4
      3538624.15     10326886.99      3538132.84     10326907.61
      3537866.18      10327103.3      3537568.08     10327383.17
#Sta/Elev= 30
  4553.7  392.32  4621.1  390.33  4705.9  387.63    4846  380.34    4873  379.83
  4875.8  379.33    4879  379.83  4887.8  380.14  4936.1  381.39  4967.3  381.03
  5021.8  381.96  5026.8  383.43  5036.2  383.52  5062.8  382.78  5077.5  383.59
  5083.7  382.46  5092.1  383.63  5098.3   381.8  5106.8  383.39    5113  381.58
  5127.7   383.9  5133.9  382.64  5142.3  383.85  5148.5  382.49    5157  383.71
  5163.2  382.26  5166.7  382.67  5198.7  381.06  5242.6  380.62  5785.1  382.54
#Mann= 7 ,-1 , 0
  4553.7     .05       0  4621.1      .1       0    4873     .07       0
    4879      .1       0  4887.8     .05       0  4967.3      .1       0
  5166.7     .05       0
Bank Sta=4873,4879
XS Rating Curve= 0 ,0
Exp/Cntr=0.3,0.1

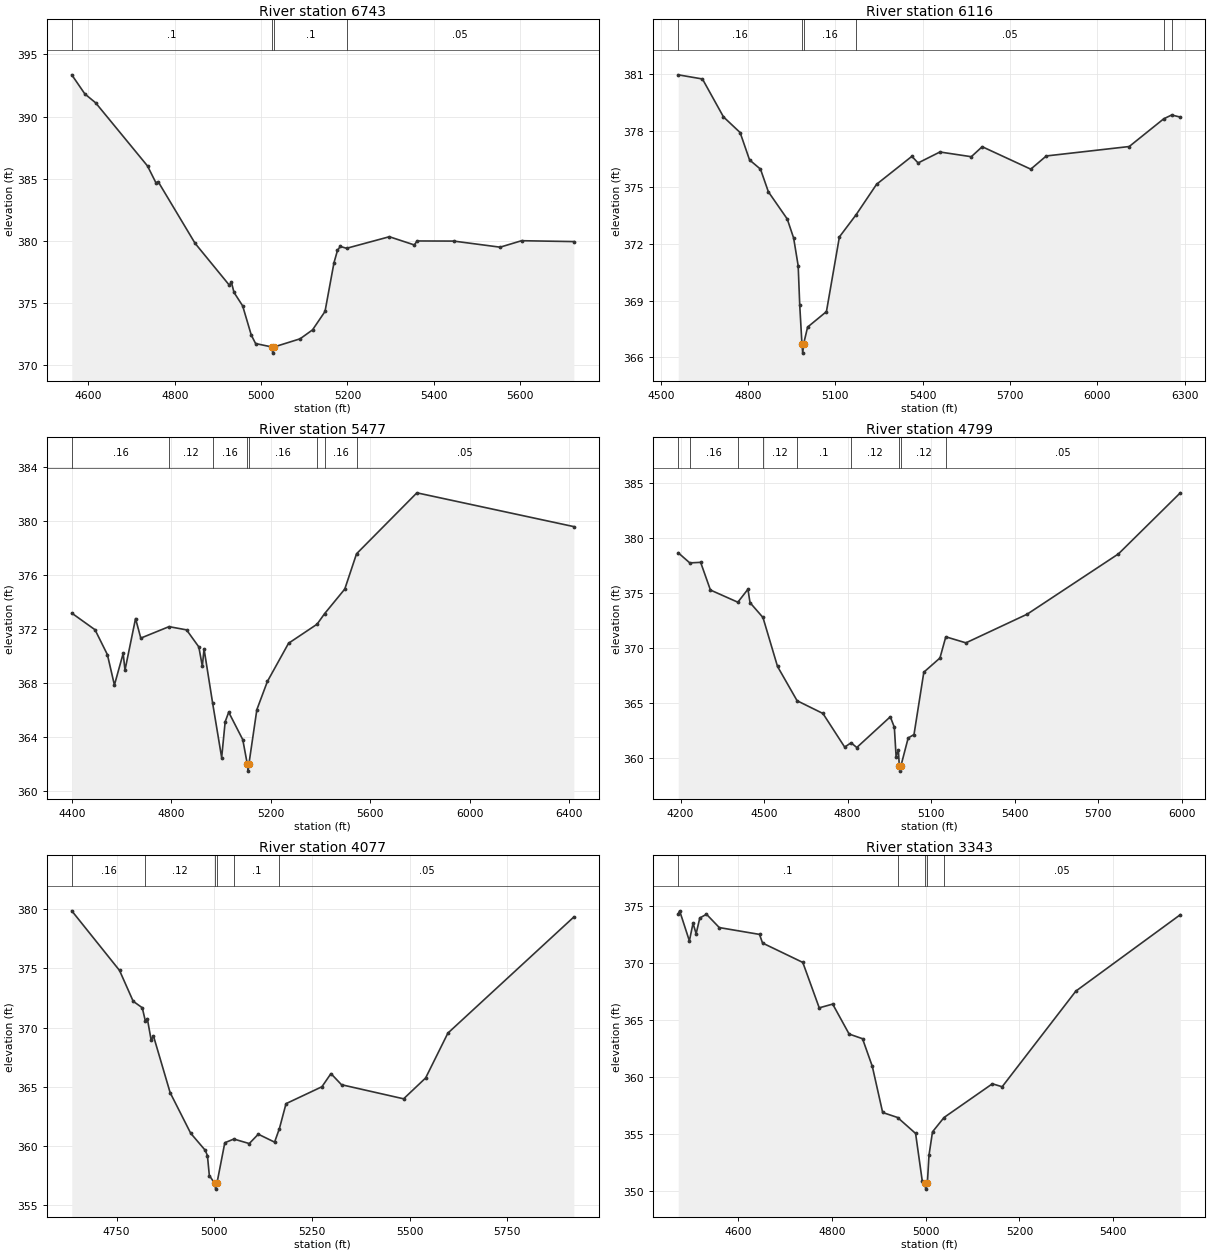
Type RM Length L Ch R = 1 ,6743    ,627,627,627
BEGIN DESCRIPTION:
SMITH CREEK 12.0
END DESCRIPTION:
XS GIS Cut Line= 3
       3538617.3     10326814.84      3538095.05     10326845.76
      3537592.12     10327241.63
#Sta/Elev= 30
  4561.3  393.36  4591.7  391.82  4616.6  391.11  4736.8  386.03  4756.4  384.67
  4761.4  384.77    4847  379.81  4926.2  376.45  4931.2  376.67  4937.2  375.86
  4957.2  374.78  4977.2  372.43  4987.2  371.75  5024.3  371.48  5027.1  370.98
  5030.3  371.48  5090.2  372.13  5119.1  372.85    5148  374.33  5168.8  378.25
  5176.9  379.24  5183.3  379.56    5198  379.41  5297.1  380.34  5354.9  379.68
  5361.3     380  5446.2  379.99  5553.7   379.5  5603.4  380.02  5724.5  379.95
#Mann= 4 ,-1 , 0
  4561.3      .1       0  5024.3     .07       0  5030.3      .1       0
    5198     .05       0
Bank Sta=5024.3,5030.3
XS Rating Curve= 0 ,0
Exp/Cntr=0.3,0.1

Type RM Length L Ch R = 1 ,6116    ,639,639,639
BEGIN DESCRIPTION:
SMITH CREEK 11.0
END DESCRIPTION:
XS GIS Cut Line= 3
      3538610.43     10326192.94      3537933.56     10326405.96
      3537429.16      10327287.8
#Sta/Elev= 30
  4560.1  380.97  4643.3  380.75  4715.6  378.74  4772.8  377.91  4805.2  376.46
  4842.8  375.97  4869.9  374.77  4934.7  373.33  4956.7  372.32  4972.3  370.85
  4977.7  368.75  4985.2  366.72  4987.9  366.22  4991.2  366.72  5004.7   367.6
  5069.4  368.42    5114  372.38  5171.6  373.56  5241.8  375.17    5363  376.65
  5384.5   376.3  5459.4  376.88  5567.3  376.63  5604.8  377.16  5771.7  375.97
    5825  376.67    6110  377.17  6228.7  378.64  6255.8  378.84  6285.6  378.73
#Mann= 6 ,-1 , 0
  4560.1     .16       0  4985.2     .07       0  4991.2     .16       0
  5171.6     .05       0  6228.7      .1       0  6255.8     .05       0
Bank Sta=4985.2,4991.2
XS Rating Curve= 0 ,0
Exp/Cntr=0.3,0.1

Type RM Length L Ch R = 1 ,5477    ,678,678,678
BEGIN DESCRIPTION:
SMITH CREEK 10.0
END DESCRIPTION:
XS GIS Cut Line= 3
      3538259.86     10325496.98      3537112.24      10326572.2
      3536912.26     10326972.17
#Sta/Elev= 30
  4399.8  373.17  4493.3  371.94  4543.1   370.1  4571.4  367.85  4606.6  370.19
  4613.9  368.95  4656.4  372.77  4677.4  371.32  4791.1  372.17  4861.6  371.93
  4910.9  370.67  4925.1  369.24  4931.9  370.53  4966.5  366.51  5002.8  362.48
  5016.9  365.13  5031.1  365.84  5087.7  363.81  5106.2  361.98    5109  361.48
  5112.2  361.98  5144.4  366.03  5186.9  368.12  5271.9  370.94  5386.6  372.35
  5416.9  373.13  5498.1  374.95  5545.4  377.56  5788.2  382.07  6419.6  379.57
#Mann= 8 ,-1 , 0
  4399.8     .16       0  4791.1     .12       0  4966.5     .16       0
  5106.2     .07       0  5112.2     .16       0  5386.6     .05       0
  5416.9     .16       0  5545.4     .05       0
Bank Sta=5106.2,5112.2
XS Rating Curve= 0 ,0
Exp/Cntr=0.3,0.1

Type RM Length L Ch R = 1 ,4799    ,722,722,722
BEGIN DESCRIPTION:
SMITH CREEK 9.0
END DESCRIPTION:
XS GIS Cut Line= 3
       3537881.4     10324927.53      3537499.45     10325361.56
      3536749.45     10326330.31
#Sta/Elev= 30
  4191.8  378.68  4233.3  377.76  4272.3  377.81  4307.4  375.29  4405.9  374.18
  4442.1  375.36  4449.7  374.14  4496.1  372.79  4548.4  368.33  4618.7  365.21
  4711.5  364.05  4789.6  360.99  4812.7  361.38  4833.1  360.95  4953.5  363.75
    4968  362.79  4974.3  360.13  4982.4  360.73  4985.8   359.3  4988.5   358.8
  4991.8   359.3  5017.7  361.82  5038.6  362.13  5073.9  367.81  5131.8   369.1
  5152.8  371.03  5225.1  370.48  5445.1  373.09  5772.9  378.58  5995.1  384.14
#Mann= 9 ,-1 , 0
  4191.8      .1       0  4233.3     .16       0  4405.9      .1       0
  4496.1     .12       0  4618.7      .1       0  4812.7     .12       0
  4985.8     .07       0  4991.8     .12       0  5152.8     .05       0
Bank Sta=4985.8,4991.8
XS Rating Curve= 0 ,0
Exp/Cntr=0.3,0.1

Type RM Length L Ch R = 1 ,4077    ,734,734,734
BEGIN DESCRIPTION:
SMITH CREEK 8.0
END DESCRIPTION:
XS GIS Cut Line= 3
      3537273.74     10324736.58      3537092.11     10325041.64
       3536542.1     10325791.64
#Sta/Elev= 30
  4635.5  379.87  4757.8  374.83  4792.7  372.23    4816  371.68  4823.7  370.58
  4828.9  370.76  4838.7  368.95  4844.5  369.31  4887.3  364.51  4939.9  361.08
  4976.9  359.65  4982.7   359.2  4987.6  357.51  5001.1  356.86  5003.8  356.36
  5007.1  356.86  5027.2  360.28  5050.4  360.59  5089.8  360.21  5112.9     361
  5154.6  360.33    5167  361.48  5183.9  363.58  5275.8  365.01  5298.9  366.12
  5325.9  365.18  5484.9  363.99  5541.2  365.75  5598.2  369.54  5920.6  379.35
#Mann= 6 ,-1 , 0
  4635.5     .16       0  4823.7     .12       0  5001.1     .07       0
  5007.1     .12       0  5050.4      .1       0    5167     .05       0
Bank Sta=5001.1,5007.1
XS Rating Curve= 0 ,0
Exp/Cntr=0.3,0.1

Type RM Length L Ch R = 1 ,3343    ,341,341,341
BEGIN DESCRIPTION:
SMITH CREEK 7.0
END DESCRIPTION:
XS GIS Cut Line= 3
       3536919.6     10324615.01      3536391.81     10325246.98
      3536330.59     10325487.74
#Sta/Elev= 30
  4471.6  374.32  4474.6  374.58  4495.4  371.94  4503.2  373.49  4509.8  372.57
  4517.6  373.95  4531.9  374.28  4559.2  373.11  4645.1  372.51  4651.6  371.75
  4737.5  370.05  4772.6  366.06  4801.3  366.39  4836.4  363.76    4865  363.35
  4885.9  360.92    4908  356.87  4939.9  356.43  4978.3  355.03  4992.6  350.83
  4997.4  350.64  5000.1  350.14  5003.4  350.64  5006.9  353.12  5014.4  355.17
    5039  356.43  5142.2  359.39  5163.1  359.13  5320.4  367.53  5543.4  374.24
#Mann= 5 ,-1 , 0
  4471.6      .1       0  4939.9     .12       0  4997.4     .07       0
  5003.4     .12       0    5039     .05       0
Bank Sta=4997.4,5003.4
XS Rating Curve= 0 ,0
Exp/Cntr=0.3,0.1

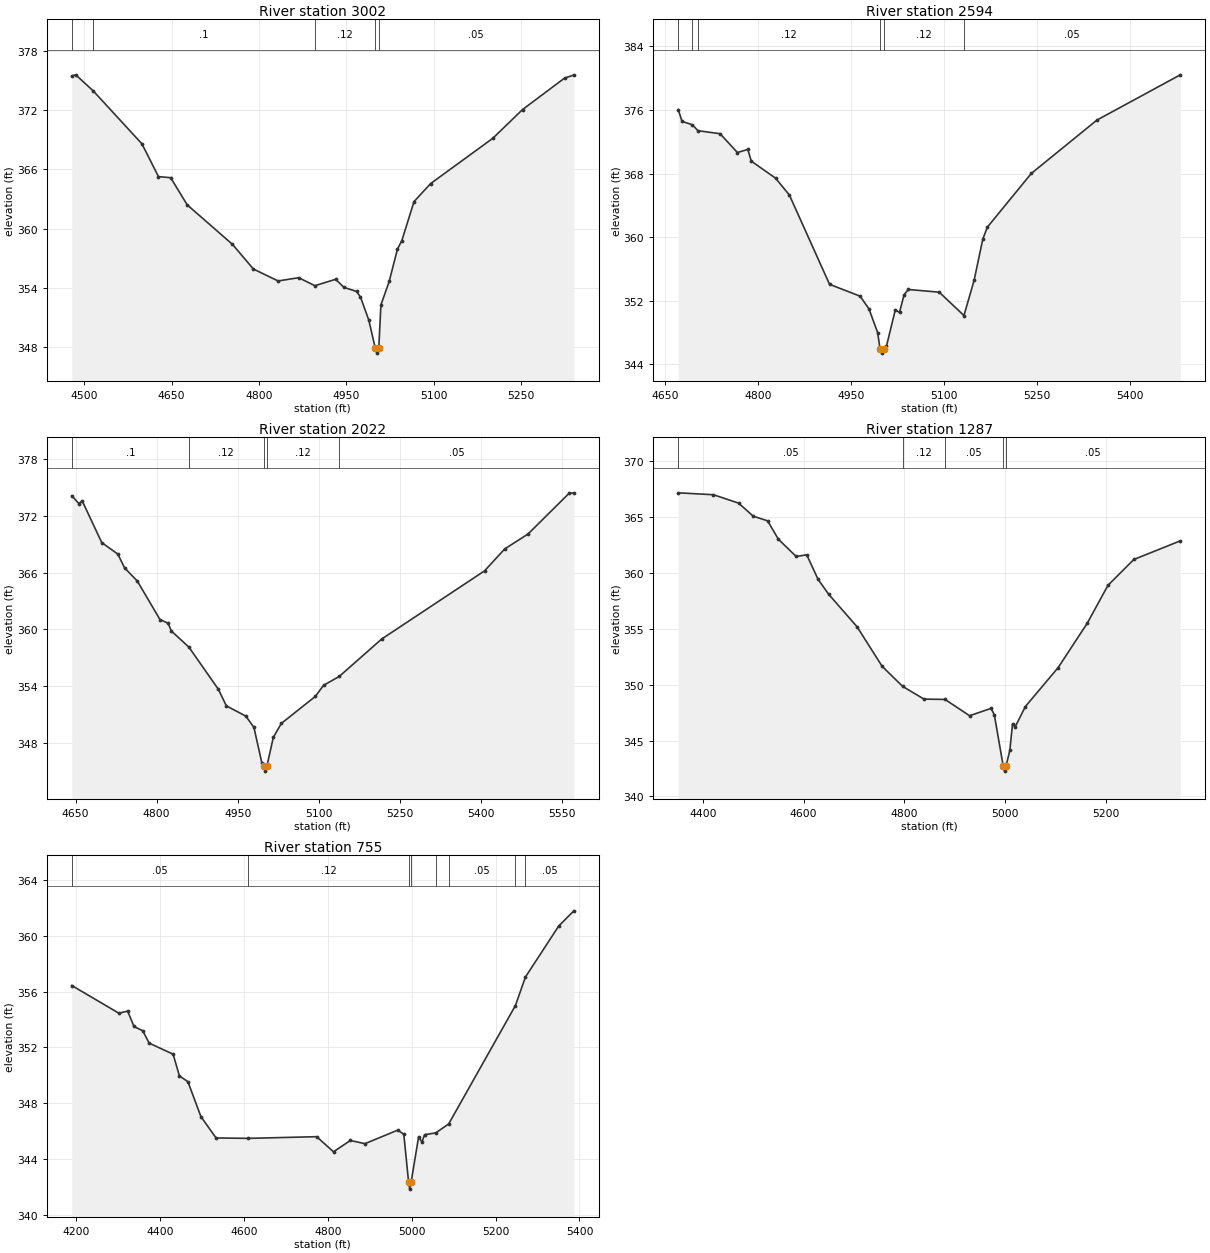
Type RM Length L Ch R = 1 ,3002    ,408,408,408
BEGIN DESCRIPTION:
SMITH CREEK 6.0
END DESCRIPTION:
XS GIS Cut Line= 3
      3536659.14     10324458.82      3536202.52     10324964.56
      3536052.48     10325064.58
#Sta/Elev= 30
  4478.8  375.47  4485.6  375.58  4515.4  373.97  4599.2  368.59  4627.6  365.27
  4648.5  365.16  4676.9  362.41  4754.6  358.41  4790.5  355.91  4832.9   354.7
  4868.2  355.03  4896.1  354.22  4931.7  354.87  4945.9  354.05  4967.6  353.64
  4974.3  353.07  4988.5  350.75  4999.7  347.89  5002.5  347.39  5005.7  347.89
  5009.4  352.27  5023.6  354.66  5037.8  357.93  5045.3  358.79  5066.2  362.74
  5094.6  364.56  5201.4  369.15  5252.4  372.06  5324.6  375.25  5340.5  375.56
#Mann= 5 ,-1 , 0
  4478.8     .16       0  4515.4      .1       0  4896.1     .12       0
  4999.7     .07       0  5005.7     .05       0
Bank Sta=4999.7,5005.7
XS Rating Curve= 0 ,0
Exp/Cntr=0.3,0.1

Type RM Length L Ch R = 1 ,2594    ,572,572,572
BEGIN DESCRIPTION:
SMITH CREEK 5.0
END DESCRIPTION:
XS GIS Cut Line= 3
      3536349.05     10324259.69      3536249.05      10324459.7
      3535817.02     10324856.62
#Sta/Elev= 30
  4671.4  376.04  4677.5  374.57  4694.3  374.13  4703.2  373.39    4739  373.01
  4766.9  370.64  4783.7  371.03  4789.3  369.56  4828.4  367.42  4850.8  365.29
  4915.6  354.06    4965  352.56  4979.2  350.97  4993.3  347.96  4997.1   345.9
  4999.9   345.4  5003.1   345.9  5007.5  346.29  5021.7  350.84  5028.5  350.53
  5035.9  352.74  5042.7  353.41  5092.6  353.07  5132.5  350.13  5148.9  354.55
  5162.9  359.73  5170.3  361.25  5241.2  368.01  5347.2  374.73  5481.7  380.42
#Mann= 6 ,-1 , 0
  4671.4     .16       0  4694.3      .1       0  4703.2     .12       0
  4997.1     .07       0  5003.1     .12       0  5132.5     .05       0
Bank Sta=4997.1,5003.1
XS Rating Curve= 0 ,0
Exp/Cntr=0.3,0.1

Type RM Length L Ch R = 1 ,2022    ,735,735,735
BEGIN DESCRIPTION:
SMITH CREEK 4.0
END DESCRIPTION:
XS GIS Cut Line= 3
      3536252.94     10324045.58      3535787.64     10324361.56
      3535756.39     10324726.17
#Sta/Elev= 30
    4643  374.12  4656.1   373.3  4662.4  373.57  4698.4  369.17  4728.2  367.95
  4740.7  366.49  4764.2   365.1  4806.1  361.03  4821.1  360.64  4827.1  359.82
  4859.5  358.12  4913.9  353.67  4928.9   351.9  4964.8  350.82  4979.8  349.63
  4994.6  345.84  4997.7   345.5  5000.5     345  5003.7   345.5  5015.7  348.57
  5030.6  350.05  5093.6  352.91  5108.5  354.07  5137.5  355.01  5216.1  358.97
  5406.3  366.18  5443.6   368.5  5486.6  370.07  5562.4  374.37  5571.4  374.43
#Mann= 5 ,-1 , 0
    4643      .1       0  4859.5     .12       0  4997.7     .07       0
  5003.7     .12       0  5137.5     .05       0
Bank Sta=4997.7,5003.7
XS Rating Curve= 0 ,0
Exp/Cntr=0.3,0.1

Type RM Length L Ch R = 1 ,1287    ,532,532,532
BEGIN DESCRIPTION:
SMITH CREEK 2.0
END DESCRIPTION:
XS GIS Cut Line= 3
      3535888.35     10323399.73      3535614.03     10323764.34
       3535492.1     10324291.65
#Sta/Elev= 30
  4351.1  367.19    4421  367.02    4471  366.27  4500.1   365.1  4528.7  364.68
  4550.1  363.03  4585.5  361.49  4606.4  361.64  4628.8  359.45  4650.1   358.1
  4706.3   355.2  4756.3  351.65  4796.9  349.86  4839.3  348.72  4881.2  348.69
  4929.9  347.23  4972.6  347.89  4979.1  347.31  4996.6  342.77  4999.4  342.27
  5002.6  342.77  5009.9  344.13  5015.3   346.5  5020.5  346.23  5040.7  348.05
  5105.9  351.54  5163.8  355.52  5204.9  358.91  5256.2  361.22  5348.6  362.89
#Mann= 5 ,-1 , 0
  4351.1     .05       0  4796.9     .12       0  4881.2     .05       0
  4996.6     .03       0  5002.6     .05       0
Bank Sta=4996.6,5002.6
XS Rating Curve= 0 ,0
Exp/Cntr=0.3,0.1

Type RM Length L Ch R = 1 ,755     ,0,0,0
BEGIN DESCRIPTION:
SMITH CREEK 1.0
END DESCRIPTION:
XS GIS Cut Line= 4
      3535489.06     10323413.62      3535106.59     10323667.34
      3535124.45     10323899.76      3535442.08     10324291.61
#Sta/Elev= 30
  4190.1  356.43  4302.3  354.45  4323.3   354.6  4338.4   353.5  4359.4  353.19
  4374.5  352.31  4431.6  351.52  4446.6  349.97  4466.9  349.55  4497.8  347.06
  4533.9  345.53    4611   345.5  4773.7  345.62  4813.9  344.54    4854  345.35
  4888.7  345.12    4967  346.09  4981.4  345.79  4992.8  342.37  4995.5  341.87
  4998.8  342.37  5016.6   345.6  5024.5  345.24    5031  345.76  5057.4  345.89
  5088.3  346.53  5247.4     355  5271.3  357.04  5350.7  360.69  5386.6  361.77
#Mann= 8 ,-1 , 0
  4190.1     .05       0    4611     .12       0  4992.8     .07       0
  4998.8     .12       0  5057.4     .16       0  5088.3     .05       0
  5247.4     .16       0  5271.3     .05       0
Bank Sta=4992.8,4998.8
XS Rating Curve= 0 ,0
Exp/Cntr=0.3,0.1

Chan Stop Cuts=-1
Use User Specified Reach Order=0
Composite Channel Slope=5