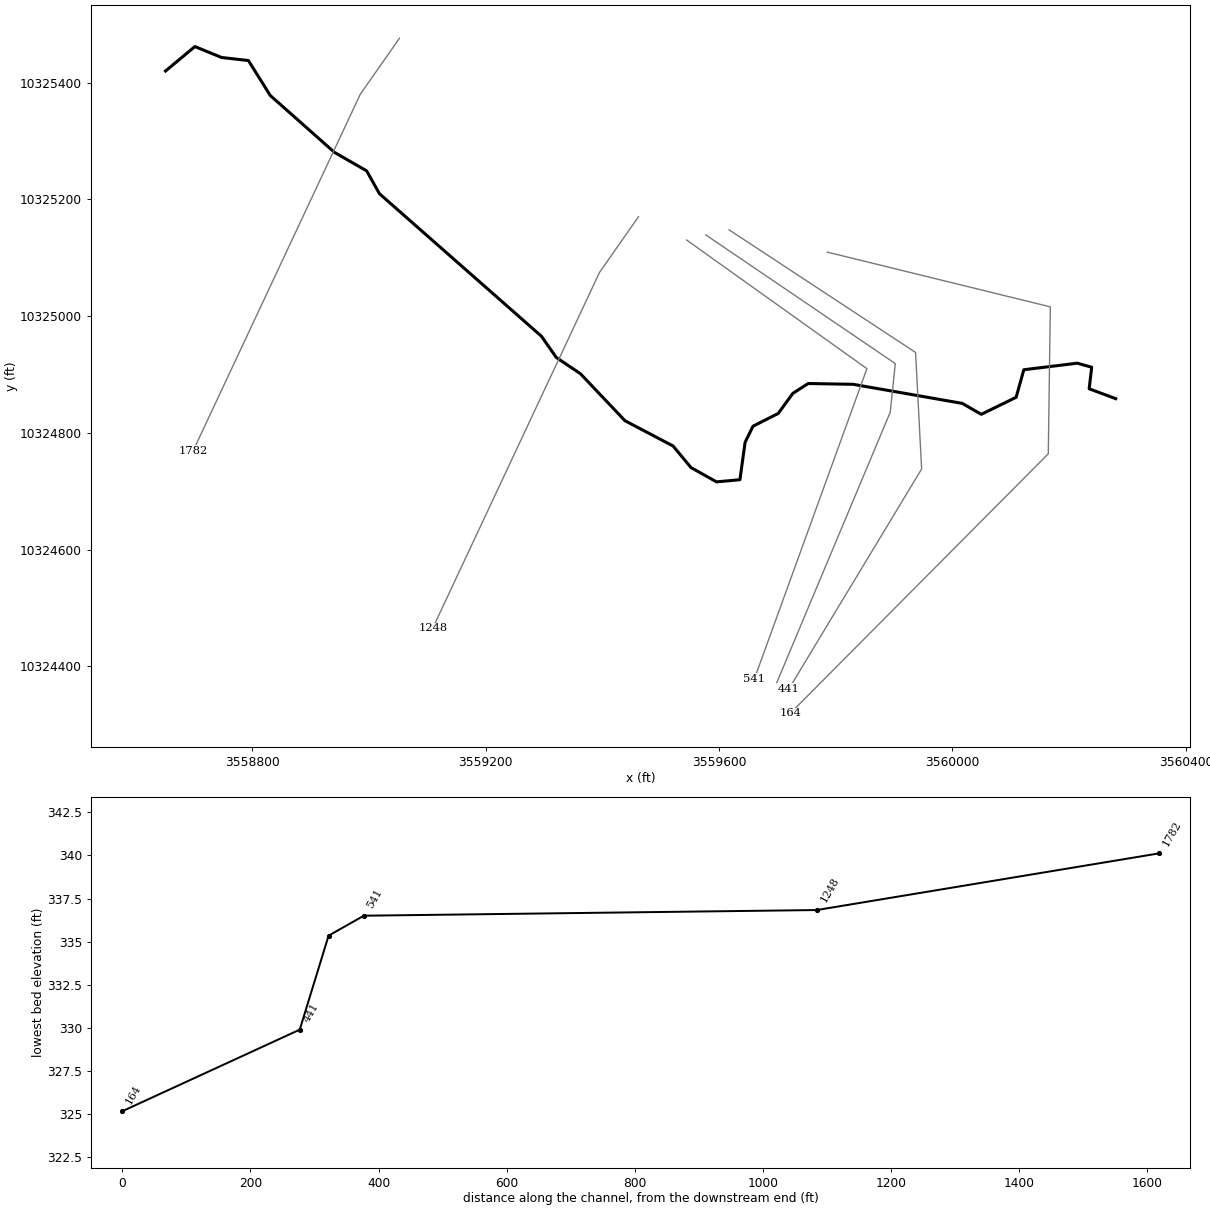
--- SNAKE BRANCH TRIBUTARY 1.prj (project) ---

Proj Title=SNAKE BRANCH TRIBUTARY 1 Base Level Engineering
Current Plan=p01
Default Exp/Contr=0.3,0.1
English Units
Geom File=g01
Flow File=f01
Plan File=p01
Y Axis Title=Elevation
X Axis Title(PF)=Main Channel Distance
X Axis Title(XS)=Station
BEGIN DESCRIPTION:
SNAKE BRANCH TRIBUTARY 1
END DESCRIPTION:
DSS Export Rating Curves= 0
DSS Export Rating Curve Sorted= 0
DSS Export Volume Flow Curves= 0
DXF OffsetX= 0
DXF OffsetY= 0
DXF ScaleX= 1
DXF ScaleY= 10

--- SNAKE BRANCH TRIBUTARY 1.p01 (plan) ---

Plan Title=Multiple Run
Short Identifier=Multiple
Geom File=g01
Flow File=f01
Subcritical Flow
K Sum by GR= 0
Std Step Tol= 0.01
Critical Tol= 0.01
Num of Std Step Trials= 20
Max Error Tol= 0.3
Flow Tol Ratio= 0.001
Split Flow NTrial= 30
Split Flow Tol= 0.02
Split Flow Ratio= 0.02
Log Output Level= 0
Friction Slope Method= 1
Unsteady Friction Slope Method= 2
Unsteady Bridges Friction Slope Method= 1
Parabolic Critical Depth
Global Vel Dist=  1 , 1 , 1
Global Log Level= 0
CheckData=True
Encroach Param= -1, 0, 0, 0
BEGIN DESCRIPTION:
Multiple Run
END DESCRIPTION:

--- SNAKE BRANCH TRIBUTARY 1.f01 (steady flow) ---

Flow Title=Multiple
Number of Profiles=7
Profile Names=10-year,25-year,50-year,1pct_min,100-year,1pct_plu,500-year
River Rch & RM= SNAKE BRANCH TRI,Reach-1,1782
      77      90      99      80     109     147     131
Boundary for River Rch & Prof#=SNAKE BRANCH TRI,Reach-1,1
Up Type=0
Dn Type=3
Dn Slope=0.005
Boundary for River Rch & Prof#=SNAKE BRANCH TRI,Reach-1,2
Up Type=0
Dn Type=3
Dn Slope=0.005
Boundary for River Rch & Prof#=SNAKE BRANCH TRI,Reach-1,3
Up Type=0
Dn Type=3
Dn Slope=0.005
Boundary for River Rch & Prof#=SNAKE BRANCH TRI,Reach-1,4
Up Type=0
Dn Type=3
Dn Slope=0.005
Boundary for River Rch & Prof#=SNAKE BRANCH TRI,Reach-1,5
Up Type=0
Dn Type=3
Dn Slope=0.005
Boundary for River Rch & Prof#=SNAKE BRANCH TRI,Reach-1,6
Up Type=0
Dn Type=3
Dn Slope=0.005
Boundary for River Rch & Prof#=SNAKE BRANCH TRI,Reach-1,7
Up Type=0
Dn Type=3
Dn Slope=0.005

--- SNAKE BRANCH TRIBUTARY 1.g01 (geometry) ---

Geom Title=Existing Conditions

River Reach=SNAKE BRANCH TRI,Reach-1
Reach XY= 30
      3558651.60     10325419.94      3558701.97     10325461.90
      3558747.81     10325443.15      3558793.64     10325437.95
      3558831.14     10325378.05      3558941.04     10325280.65
      3558996.25     10325248.88      3559018.12     10325209.82
      3559295.72     10324965.55      3559321.25     10324929.09
      3559362.39     10324901.49      3559438.95     10324820.76
      3559521.25     10324777.53      3559551.97     10324740.55
      3559595.72     10324716.07      3559635.83     10324719.72
      3559644.68     10324783.78      3559658.22     10324811.38
      3559701.45     10324833.26      3559726.45     10324867.63
      3559752.84     10324884.56      3559829.93     10324883.17
      3560016.73     10324850.53      3560049.37     10324831.78
      3560109.09     10324860.95      3560122.29     10324908.17
      3560213.81     10324919.37      3560238.55     10324912.42
      3560234.21     10324875.53      3560279.69     10324858.64

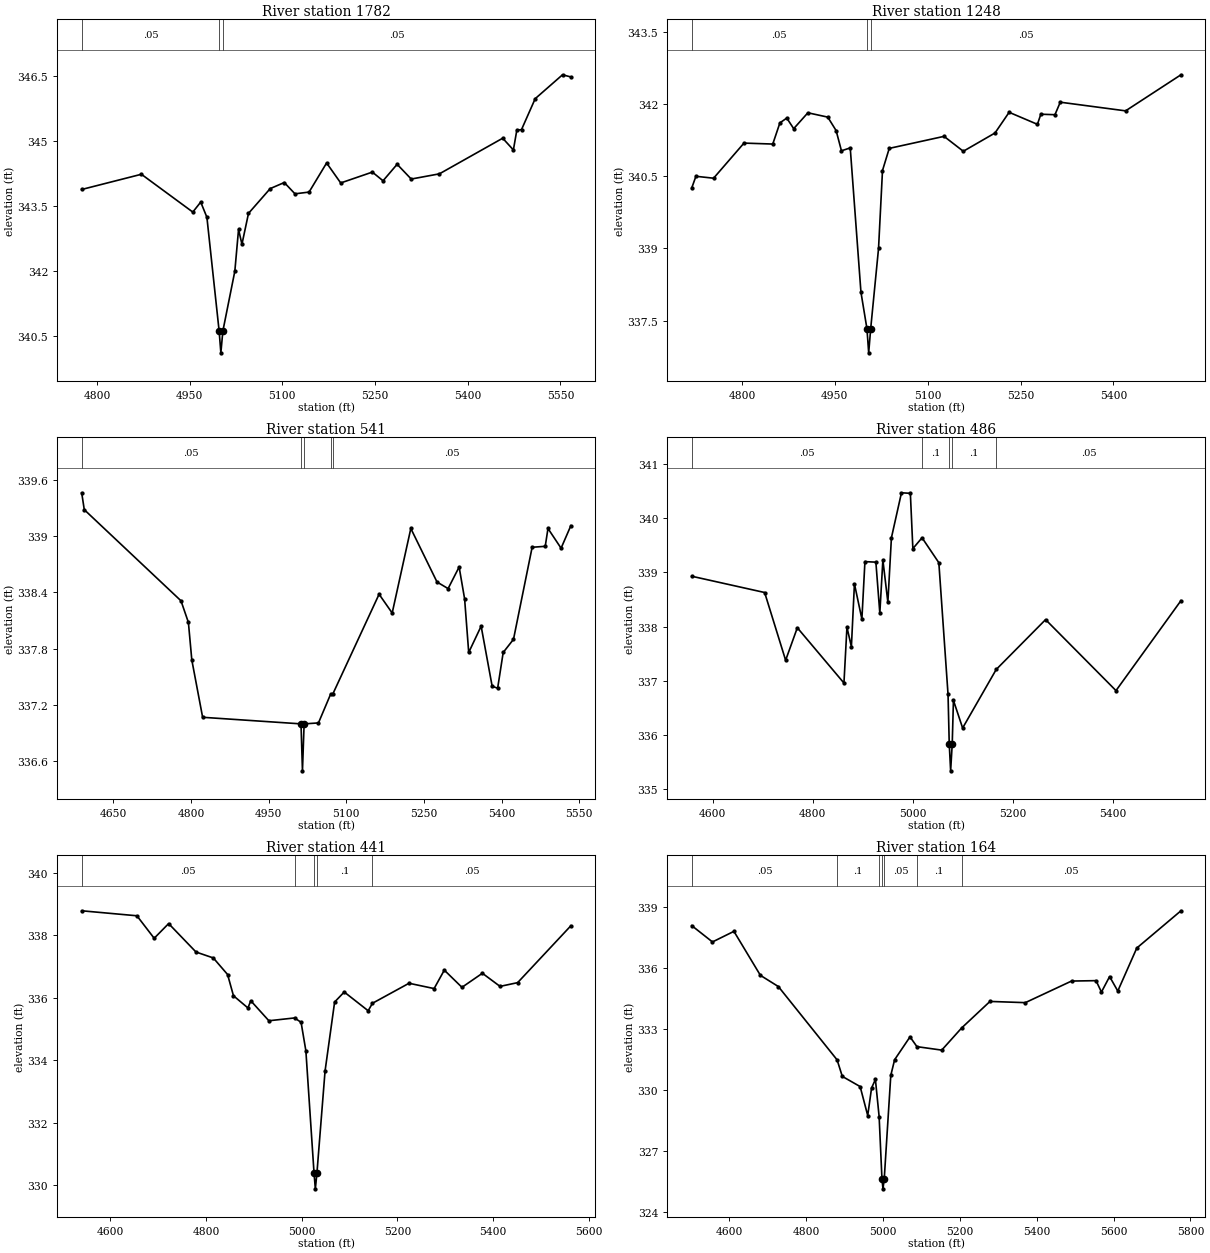
Type RM Length L Ch R = 1,1782,534,534,534
BEGIN DESCRIPTION:
SNAKE BRANCH TRIBUTARY 1 1.2
END DESCRIPTION:
XS GIS Cut Line= 3
      3559052.41     10325475.99      3558985.48     10325380.39
      3558699.04     10324769.40
#Sta/Elev= 30
  4775.4  343.88  4872.0  344.23  4955.2  343.36  4968.0  343.59  4978.0  343.24
  4997.8  340.62  5000.6  340.12  5003.8  340.62  5023.2  342.00  5029.2  342.96
  5034.7  342.62  5045.3  343.33  5080.4  343.90  5103.2  344.04  5120.5  343.78
  5143.3  343.82  5171.7  344.49  5194.5  344.03  5245.7  344.28  5263.0  344.08
  5285.8  344.46  5308.6  344.12  5354.2  344.24  5456.6  345.06  5473.9  344.79
  5479.4  345.24  5487.1  345.26  5509.2  345.97  5553.4  346.52  5566.9  346.47
#Mann=3,-1,0
  4775.4    0.05       0  4997.8    0.03       0  5003.8    0.05       0
Bank Sta=4997.8,5003.8
Exp/Cntr=0.3,0.1

Type RM Length L Ch R = 1,1248,707,707,707
BEGIN DESCRIPTION:
SNAKE BRANCH TRIBUTARY 1 1.1
END DESCRIPTION:
XS GIS Cut Line= 3
      3559462.14     10325170.44      3559395.20     10325074.84
      3559109.41     10324465.22
#Sta/Elev= 30
  4719.1  340.26  4725.8  340.50  4754.3  340.46  4803.4  341.19  4849.9  341.17
  4861.4  341.61  4872.5  341.71  4883.7  341.49  4906.6  341.82  4938.7  341.73
  4952.2  341.45  4960.8  341.03  4975.0  341.09  4992.3  338.09  5002.0  337.33
  5004.8  336.83  5008.0  337.33  5020.7  339.00  5027.1  340.62  5038.0  341.08
  5126.5  341.33  5157.6  341.02  5208.8  341.40  5231.6  341.83  5277.3  341.58
  5282.8  341.79  5305.6  341.78  5314.2  342.04  5419.7  341.86  5509.1  342.61
#Mann=3,-1,0
  4719.1    0.05       0  5002.0    0.03       0  5008.0    0.05       0
Bank Sta=5002,5008
Exp/Cntr=0.3,0.1

Type RM Length L Ch R = 1,541,55,55,55
BEGIN DESCRIPTION:
Mapping XS 8fc7271d
END DESCRIPTION:
XS GIS Cut Line= 3
      3559544.37     10325130.51      3559853.42     10324910.01
      3559660.70     10324378.73
#Sta/Elev= 30
  4589.0  339.46  4594.0  339.28  4780.8  338.31  4795.1  338.08  4801.7  337.68
  4822.6  337.07  5012.6  337.00  5015.4  336.50  5018.6  337.00  5046.3  337.01
  5070.1  337.32  5074.2  337.32  5163.4  338.38  5188.7  338.18  5224.7  339.08
  5275.3  338.51  5296.7  338.44  5318.0  338.67  5328.6  338.33  5336.5  337.76
  5360.5  338.04  5381.8  337.40  5392.4  337.38  5403.1  337.76  5423.0  337.90
  5459.0  338.88  5484.3  338.89  5489.6  339.08  5514.9  338.87  5533.8  339.11
#Mann=5,-1,0
  4589.0    0.05       0  5012.6    0.03       0  5018.6    0.05       0
  5070.1     0.1       0  5074.2    0.05       0
Bank Sta=5012.6,5018.6
Exp/Cntr=0.3,0.1

Type RM Length L Ch R = 1,486,45,45,45
BEGIN DESCRIPTION:
Mapping XS 8498e5ef
END DESCRIPTION:
XS GIS Cut Line= 4
      3559577.38     10325139.17      3559902.03     10324918.69
      3559893.35     10324835.35      3559698.91     10324371.82
#Sta/Elev= 30
  4558.0  338.93  4703.8  338.63  4745.8  337.38  4769.2  337.98  4862.5  336.96
  4868.5  337.99  4877.4  337.63  4883.5  338.79  4898.4  338.14  4904.5  339.20
  4926.4  339.19  4934.3  338.25  4940.4  339.23  4950.4  338.45  4957.5  339.64
  4977.6  340.47  4995.4  340.46  5000.4  339.44  5018.8  339.64  5052.4  339.18
  5070.8  336.75  5073.2  335.84  5076.0  335.34  5079.2  335.84  5081.6  336.64
  5100.0  336.13  5167.2  337.21  5266.0  338.13  5406.9  336.82  5536.9  338.48
#Mann=5,-1,0
  4558.0    0.05       0  5018.8     0.1       0  5073.2    0.03       0
  5079.2     0.1       0  5167.2    0.05       0
Bank Sta=5073.2,5079.2
Exp/Cntr=0.3,0.1

Type RM Length L Ch R = 1,441,277,277,277
BEGIN DESCRIPTION:
Mapping XS 1602147a
END DESCRIPTION:
XS GIS Cut Line= 4
      3559617.34     10325147.83      3559936.75     10324937.79
      3559947.17     10324738.13      3559719.72     10324361.37
#Sta/Elev= 30
  4540.2  338.78  4655.6  338.62  4691.7  337.90  4721.9  338.37  4779.1  337.46
  4815.3  337.27  4845.1  336.74  4857.4  336.06  4887.6  335.67  4893.6  335.90
  4931.4  335.26  4985.1  335.35  4998.7  335.21  5008.7  334.30  5025.8  330.38
  5028.5  329.88  5031.8  330.38  5048.8  333.65  5068.8  335.86  5088.9  336.18
  5138.9  335.58  5147.9  335.82  5224.3  336.46  5276.7  336.29  5298.0  336.88
  5334.9  336.33  5377.6  336.78  5414.5  336.36  5451.3  336.48  5562.5  338.30
#Mann=5,-1,0
  4540.2    0.05       0  4985.1     0.1       0  5025.8    0.07       0
  5031.8     0.1       0  5147.9    0.05       0
Bank Sta=5025.8,5031.8
Exp/Cntr=0.3,0.1

Type RM Length L Ch R = 1,164,0,0,0
BEGIN DESCRIPTION:
SNAKE BRANCH TRIBUTARY 1 1.0
END DESCRIPTION:
XS GIS Cut Line= 4
      3559785.68     10325109.67      3560167.66     10325015.91
      3560164.18     10324764.17      3559721.96     10324319.37
#Sta/Elev= 30
  4503.1  338.06  4556.9  337.26  4612.7  337.78  4681.6  335.62  4728.3  335.07
  4881.1  331.47  4894.6  330.66  4941.0  330.16  4960.7  328.74  4970.7  330.09
  4980.7  330.51  4990.4  328.68  4997.7  325.64  5000.4  325.14  5003.7  325.64
  5020.7  330.71  5030.7  331.48  5070.7  332.60  5088.7  332.12  5153.2  331.95
  5205.1  333.04  5278.7  334.34  5370.6  334.28  5490.8  335.34  5554.5  335.36
  5568.6  334.80  5589.8  335.56  5611.1  334.85  5660.5  336.96  5775.4  338.79
#Mann=7,-1,0
  4503.1    0.05       0  4881.1     0.1       0  4990.4    0.05       0
  4997.7    0.03       0  5003.7    0.05       0  5088.7     0.1       0
  5205.1    0.05       0
Bank Sta=4997.7,5003.7
Exp/Cntr=0.3,0.1

Chan Stop Cuts=-1