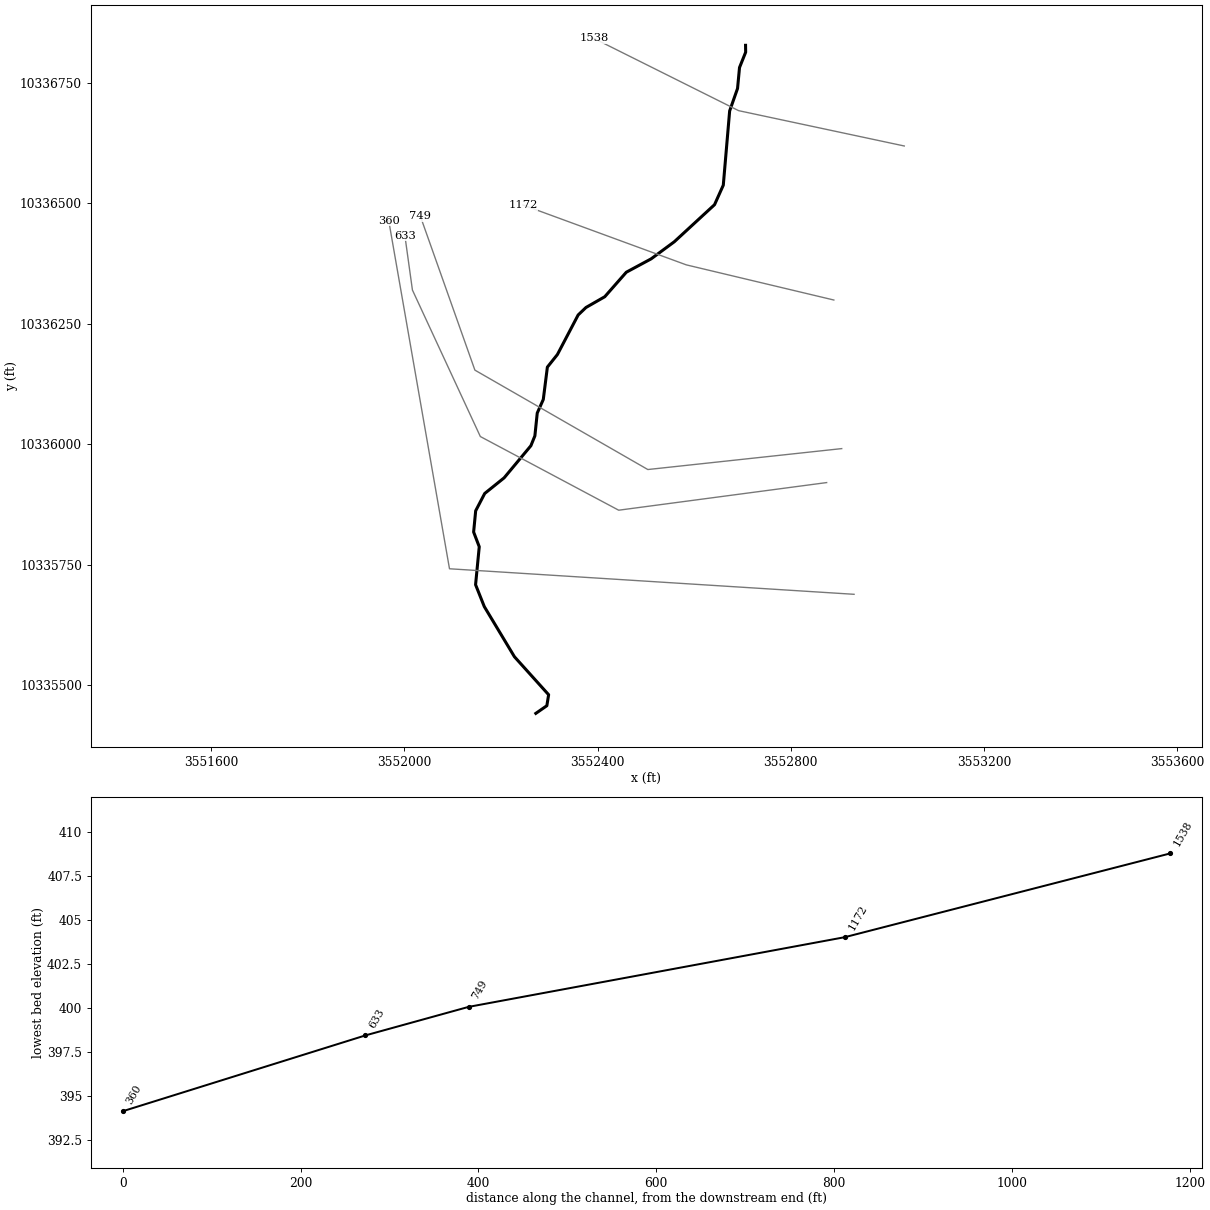
--- SNAKE BRANCH TRIBUTARY 2.prj (project) ---

Proj Title=SNAKE BRANCH TRIBUTARY 2 Base Level Engineering
Current Plan=p01
Default Exp/Contr=0.3,0.1
English Units
Geom File=g01
Flow File=f01
Plan File=p01
Y Axis Title=Elevation
X Axis Title(PF)=Main Channel Distance
X Axis Title(XS)=Station
BEGIN DESCRIPTION:
SNAKE BRANCH TRIBUTARY 2
END DESCRIPTION:
DSS Export Rating Curves= 0
DSS Export Rating Curve Sorted= 0
DSS Export Volume Flow Curves= 0
DXF OffsetX= 0
DXF OffsetY= 0
DXF ScaleX= 1
DXF ScaleY= 10

--- SNAKE BRANCH TRIBUTARY 2.p01 (plan) ---

Plan Title=Multiple Run
Short Identifier=Multiple
Geom File=g01
Flow File=f01
Subcritical Flow
K Sum by GR= 0
Std Step Tol= 0.01
Critical Tol= 0.01
Num of Std Step Trials= 20
Max Error Tol= 0.3
Flow Tol Ratio= 0.001
Split Flow NTrial= 30
Split Flow Tol= 0.02
Split Flow Ratio= 0.02
Log Output Level= 0
Friction Slope Method= 1
Unsteady Friction Slope Method= 2
Unsteady Bridges Friction Slope Method= 1
Parabolic Critical Depth
Global Vel Dist=  1 , 1 , 1
Global Log Level= 0
CheckData=True
Encroach Param= -1, 0, 0, 0
BEGIN DESCRIPTION:
Multiple Run
END DESCRIPTION:

--- SNAKE BRANCH TRIBUTARY 2.f01 (steady flow) ---

Flow Title=Multiple
Number of Profiles=7
Profile Names=10-year,25-year,50-year,1pct_min,100-year,1pct_plu,500-year
River Rch & RM= SNAKE BRANCH TRI,Reach-1,1538
     233     297     347     298     402     544     542
Boundary for River Rch & Prof#=SNAKE BRANCH TRI,Reach-1,1
Up Type=0
Dn Type=3
Dn Slope=0.005
Boundary for River Rch & Prof#=SNAKE BRANCH TRI,Reach-1,2
Up Type=0
Dn Type=3
Dn Slope=0.005
Boundary for River Rch & Prof#=SNAKE BRANCH TRI,Reach-1,3
Up Type=0
Dn Type=3
Dn Slope=0.005
Boundary for River Rch & Prof#=SNAKE BRANCH TRI,Reach-1,4
Up Type=0
Dn Type=3
Dn Slope=0.005
Boundary for River Rch & Prof#=SNAKE BRANCH TRI,Reach-1,5
Up Type=0
Dn Type=3
Dn Slope=0.005
Boundary for River Rch & Prof#=SNAKE BRANCH TRI,Reach-1,6
Up Type=0
Dn Type=3
Dn Slope=0.005
Boundary for River Rch & Prof#=SNAKE BRANCH TRI,Reach-1,7
Up Type=0
Dn Type=3
Dn Slope=0.005

--- SNAKE BRANCH TRIBUTARY 2.g01 (geometry) ---

Geom Title=Existing Conditions
Program Version=4.10

River Reach=SNAKE BRANCH TRI,Reach-1
Reach XY= 30
      3552706.39     10336827.19       3552706.6     10336812.92
      3552693.88     10336781.07      3552689.79     10336737.65
      3552673.45     10336691.09      3552660.28     10336537.06
      3552642.15     10336496.63      3552558.77      10336419.7
      3552510.96     10336384.35      3552459.45     10336356.57
      3552414.85     10336305.75        3552376.     10336283.45
      3552359.77     10336267.93       3552316.8     10336185.86
      3552296.04     10336159.79      3552287.57     10336092.64
      3552275.06     10336064.48      3552270.17     10336017.16
      3552261.92     10335996.75      3552206.47     10335930.11
       3552166.3     10335897.73      3552147.59      10335861.8
      3552143.34     10335817.74      3552154.98     10335787.23
      3552147.37     10335708.51      3552165.42     10335663.11
      3552227.84     10335559.09      3552298.65     10335480.31
      3552294.93     10335457.51      3552272.11     10335441.64

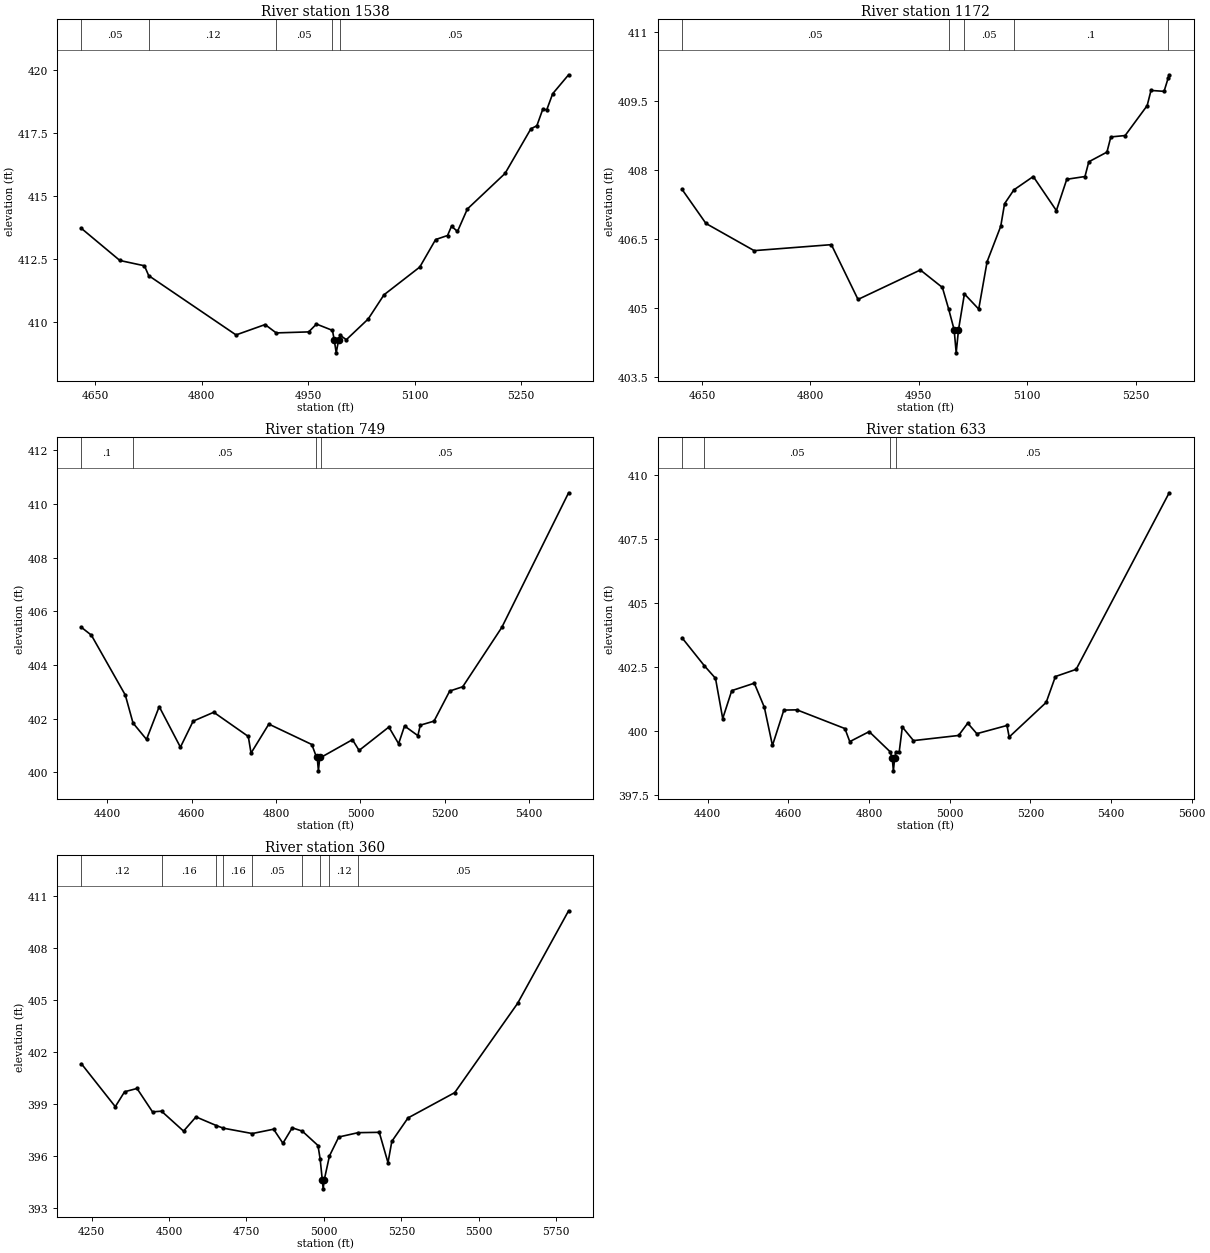
Type RM Length L Ch R = 1 ,1538    ,366,366,366
BEGIN DESCRIPTION:
SNAKE BRANCH TRIBUTARY 2 3.0
END DESCRIPTION:
XS GIS Cut Line= 3
      3553035.04     10336618.37      3552692.11     10336691.64
      3552392.09     10336841.65
#Sta/Elev= 30
  4630.6  413.71  4684.7  412.44  4719.3  412.23  4725.3  411.84  4848.3  409.49
  4889.2   409.9  4904.9  409.57  4950.6  409.61  4961.6  409.92  4984.1  409.67
  4986.7  409.28  4989.4  408.78  4992.7  409.28  4995.3  409.47  5003.6   409.3
  5034.4  410.12  5056.7  411.08  5107.1  412.18  5129.4  413.27  5146.2  413.43
  5151.8   413.8  5160.2  413.59  5174.1  414.48  5227.2  415.89  5263.6  417.66
    5272  417.78  5280.4  418.44  5285.9  418.41  5294.3  419.05  5316.7   419.8
#Mann= 5 ,-1 , 0
  4630.6     .05       0  4725.3     .12       0  4904.9     .05       0
  4984.1     .03       0  4995.3     .05       0
Bank Sta=4986.7,4992.7
XS Rating Curve= 0 ,0
Exp/Cntr=0.3,0.1

Type RM Length L Ch R = 1 ,1172    ,423,423,423
BEGIN DESCRIPTION:
SNAKE BRANCH TRIBUTARY 2 2.0
END DESCRIPTION:
XS GIS Cut Line= 3
      3552889.21     10336298.93      3552583.68     10336371.84
      3552245.48     10336496.07
#Sta/Elev= 30
  4622.2  407.57  4655.3  406.83    4722  406.24  4828.9  406.37  4865.8  405.18
  4952.1  405.82  4982.6  405.44  4991.3  404.97  4998.9  404.52  5001.7  404.02
  5004.9  404.52  5013.1   405.3  5032.9  404.97  5044.5     406  5063.4  406.77
  5068.7  407.26  5081.6  407.56  5108.4  407.85  5140.4  407.11  5154.8  407.79
    5180  407.85  5185.3  408.17  5210.4  408.38  5215.8  408.71  5235.6  408.74
  5266.1  409.39  5271.4  409.72  5289.5   409.7  5295.2  409.99  5296.6  410.06
#Mann= 5 ,-1 , 0
  4622.2     .05       0  4991.3     .03       0  5013.1     .05       0
  5081.6      .1       0  5295.2     .16       0
Bank Sta=4998.9,5004.9
XS Rating Curve= 0 ,0
Exp/Cntr=0.3,0.1

Type RM Length L Ch R = 1 ,749     ,116,116,116
BEGIN DESCRIPTION:
Mapping XS e3fc568e
END DESCRIPTION:
XS GIS Cut Line= 4
      3552905.48     10335990.76      3552504.03     10335947.36
      3552145.95     10336153.53      3552033.09     10336472.58
#Sta/Elev= 30
  4338.4   405.4  4361.9  405.11  4442.4  402.88  4460.7  401.84  4492.7  401.23
  4522.8  402.45  4573.1  400.94  4603.3  401.91  4652.2  402.24  4734.1  401.34
  4740.6  400.72  4782.8   401.8  4884.8  401.04  4894.4  400.63  4897.6  400.56
  4900.4  400.06  4903.6  400.56  4906.4  400.56  4981.1  401.22  4996.9  400.82
  5067.5  401.69  5090.6  401.07  5104.7  401.73  5136.3  401.37    5142  401.76
  5174.6  401.91  5211.8  403.03  5242.7  403.19  5335.4   405.4  5493.8  410.41
#Mann= 4 ,-1 , 0
  4338.4      .1       0  4460.7     .05       0  4894.4     .03       0
  4906.4     .05       0
Bank Sta=4897.6,4903.6
XS Rating Curve= 0 ,0
Exp/Cntr=0.3,0.1

Type RM Length L Ch R = 1 ,633     ,273,273,273
BEGIN DESCRIPTION:
Mapping XS a40d302d
END DESCRIPTION:
XS GIS Cut Line= 5
      3552874.28      10335920.3       3552443.7     10335863.01
      3552157.24     10336015.79      3552016.62     10336319.61
        3552001.     10336432.42
#Sta/Elev= 30
  4336.6  403.63  4391.9  402.54  4419.5  402.05  4437.4  400.48  4459.8  401.57
  4515.7  401.86  4540.6  400.92  4560.7  399.43  4588.9  400.81  4621.3  400.82
  4740.3  400.09  4752.4  399.58  4800.5  399.97  4852.1  399.19  4857.7  398.94
  4860.5  398.44  4863.7  398.94  4866.4  399.17  4874.8  399.16  4882.7  400.15
  4910.3  399.62  5022.1  399.82  5044.8   400.3  5067.4  399.89  5142.1  400.21
  5147.6  399.76  5239.3  401.11  5262.2  402.12  5313.6   402.4  5544.3  409.29
#Mann= 4 ,-1 , 0
  4336.6      .1       0  4391.9     .05       0  4852.1     .03       0
  4866.4     .05       0
Bank Sta=4857.7,4863.7
XS Rating Curve= 0 ,0
Exp/Cntr=0.3,0.1

Type RM Length L Ch R = 1 ,360     ,0,0,0
BEGIN DESCRIPTION:
SNAKE BRANCH TRIBUTARY 2 1.0
END DESCRIPTION:
XS GIS Cut Line= 3
      3552931.06     10335688.59      3552093.37     10335741.55
       3551967.5      10336463.8
#Sta/Elev= 30
  4217.4  401.34  4326.6  398.87  4356.6  399.73  4396.7  399.92  4446.8  398.57
  4475.8  398.61    4547  397.46  4587.1  398.28  4652.9  397.78  4675.2  397.63
  4768.8  397.32  4837.6  397.57  4867.7  396.76  4897.7  397.65  4930.2  397.46
  4980.9  396.63  4987.9  395.85  4994.9  394.63  4997.7  394.13  5000.9  394.63
    5018  396.03    5048  397.12  5110.4  397.37  5178.7  397.39  5206.9  395.64
  5219.3  396.87  5271.5  398.22  5422.3  399.68  5625.3  404.83  5789.9  410.17
#Mann= 9 ,-1 , 0
  4217.4     .12       0  4475.8     .16       0  4652.9     .05       0
  4675.2     .16       0  4768.8     .05       0  4930.2     .12       0
  4987.9     .03       0    5018     .12       0  5110.4     .05       0
Bank Sta=4994.9,5000.9
XS Rating Curve= 0 ,0
Exp/Cntr=0.3,0.1

Chan Stop Cuts=-1
Use User Specified Reach Order=0
Composite Channel Slope=5