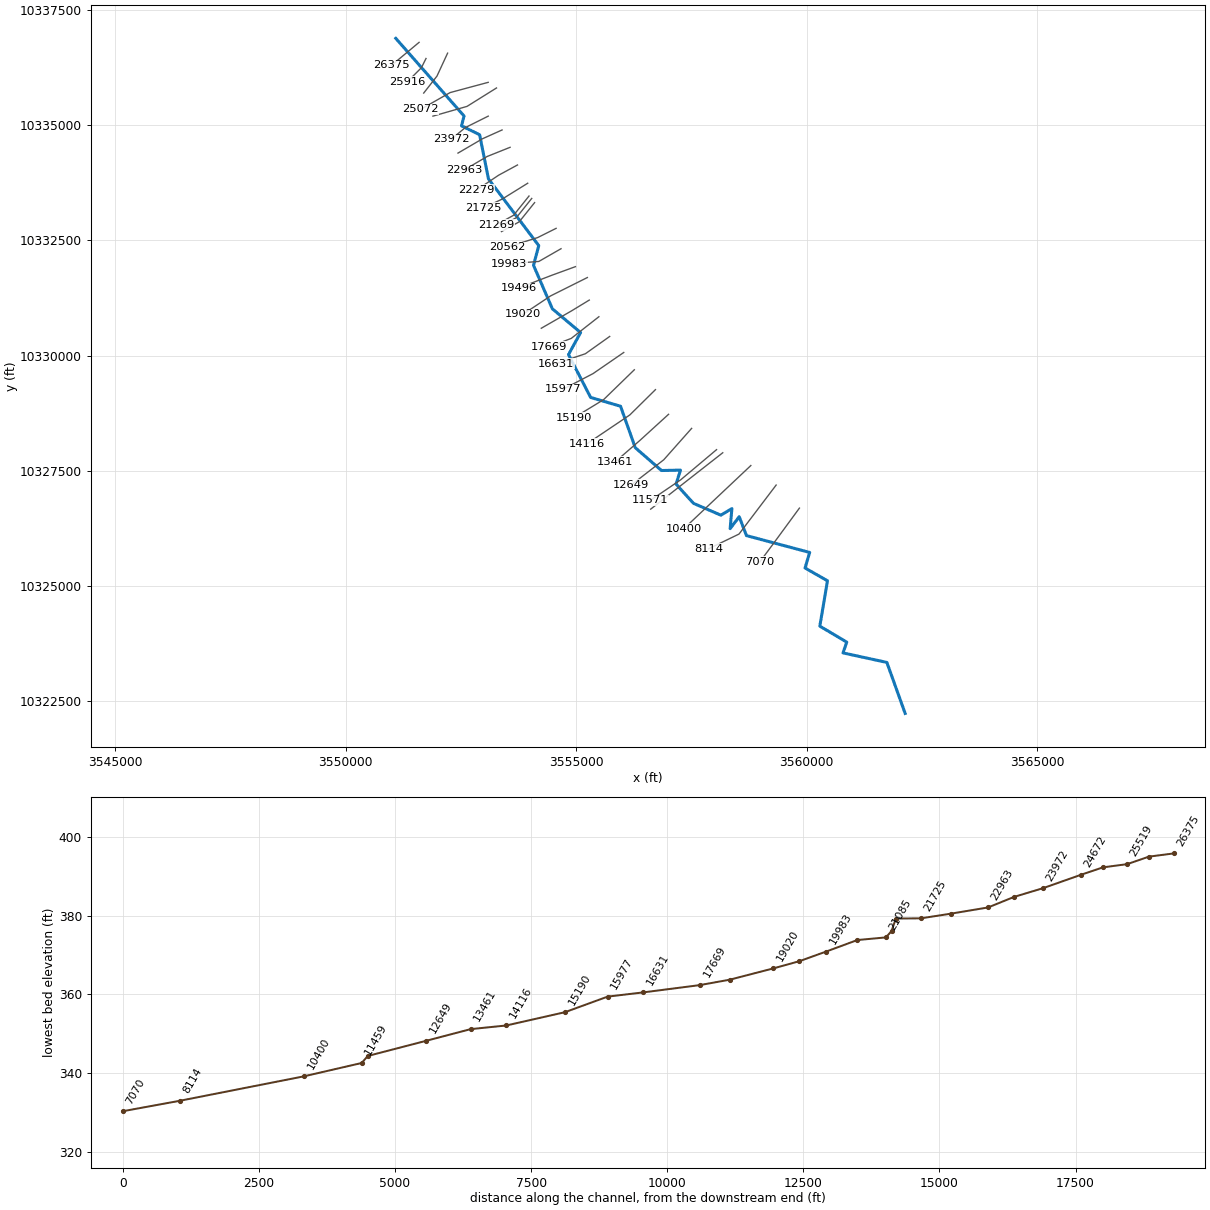
--- SNAKE BRANCH.prj (project) ---

Proj Title=SNAKE BRANCH Base Level Engineering
Current Plan=p01
Default Exp/Contr=0.3,0.1
English Units
Geom File=g01
Flow File=f01
Plan File=p01
Y Axis Title=Elevation
X Axis Title(PF)=Main Channel Distance
X Axis Title(XS)=Station
BEGIN DESCRIPTION:
SNAKE BRANCH
END DESCRIPTION:
DSS Export Rating Curves= 0
DSS Export Rating Curve Sorted= 0
DSS Export Volume Flow Curves= 0
DXF OffsetX= 0
DXF OffsetY= 0
DXF ScaleX= 1
DXF ScaleY= 10

--- SNAKE BRANCH.p01 (plan) ---

Plan Title=Multiple Run
Short Identifier=Multiple
Geom File=g01
Flow File=f01
Subcritical Flow
K Sum by GR= 0
Std Step Tol= 0.01
Critical Tol= 0.01
Num of Std Step Trials= 20
Max Error Tol= 0.3
Flow Tol Ratio= 0.001
Split Flow NTrial= 30
Split Flow Tol= 0.02
Split Flow Ratio= 0.02
Log Output Level= 0
Friction Slope Method= 1
Unsteady Friction Slope Method= 2
Unsteady Bridges Friction Slope Method= 1
Parabolic Critical Depth
Global Vel Dist=  1 , 1 , 1
Global Log Level= 0
CheckData=True
Encroach Param= -1, 0, 0, 0
BEGIN DESCRIPTION:
Multiple Run
END DESCRIPTION:

--- SNAKE BRANCH.f01 (steady flow) ---

Flow Title=Multiple
Number of Profiles=7
Profile Names=10-year,25-year,50-year,1pct_min,100-year,1pct_plu,500-year
River Rch & RM= SNAKE BRANCH,Reach-1,26375
     392     520     622     548     741    1002    1051
River Rch & RM= SNAKE BRANCH,Reach-1,25072
     796    1090    1333    1193    1613    2181    2368
River Rch & RM= SNAKE BRANCH,Reach-1,11571
     978    1352    1663    1496    2024    2737    3005
River Rch & RM= SNAKE BRANCH,Reach-1,3879
    1064    1476    1820    1640    2218    3000    3306
Boundary for River Rch & Prof#=SNAKE BRANCH,Reach-1,1
Up Type=0
Dn Type=3
Dn Slope=0.005
Boundary for River Rch & Prof#=SNAKE BRANCH,Reach-1,2
Up Type=0
Dn Type=3
Dn Slope=0.005
Boundary for River Rch & Prof#=SNAKE BRANCH,Reach-1,3
Up Type=0
Dn Type=3
Dn Slope=0.005
Boundary for River Rch & Prof#=SNAKE BRANCH,Reach-1,4
Up Type=0
Dn Type=3
Dn Slope=0.005
Boundary for River Rch & Prof#=SNAKE BRANCH,Reach-1,5
Up Type=0
Dn Type=3
Dn Slope=0.005
Boundary for River Rch & Prof#=SNAKE BRANCH,Reach-1,6
Up Type=0
Dn Type=3
Dn Slope=0.005
Boundary for River Rch & Prof#=SNAKE BRANCH,Reach-1,7
Up Type=0
Dn Type=3
Dn Slope=0.005

--- SNAKE BRANCH.g01 (geometry) ---

Geom Title=Existing Conditions

River Reach=SNAKE BRANCH,Reach-1
Reach XY= 30
      3551085.97     10336878.55      3552567.06     10335194.28
      3552512.54     10334981.55      3552904.38     10334787.94
      3553097.05     10333829.12      3554187.79     10332383.79
      3554073.74     10331956.66      3554483.35     10331012.38
      3555095.69     10330498.47      3554832.93     10330021.69
      3555312.69     10329091.47      3555961.79     10328900.40
      3556280.79     10328001.78      3556849.57     10327506.70
      3557262.56     10327514.66      3557165.15     10327213.26
      3557544.14     10326794.58      3558137.88     10326538.30
      3558376.99     10326680.61      3558339.48     10326246.79
      3558536.02     10326504.61      3558693.33     10326095.12
      3560064.49     10325730.08      3559964.44     10325392.47
      3560450.86     10325115.50      3560284.30     10324132.06
      3560869.46     10323784.72      3560787.14     10323551.63
      3561738.62     10323345.07      3562135.34     10322240.19

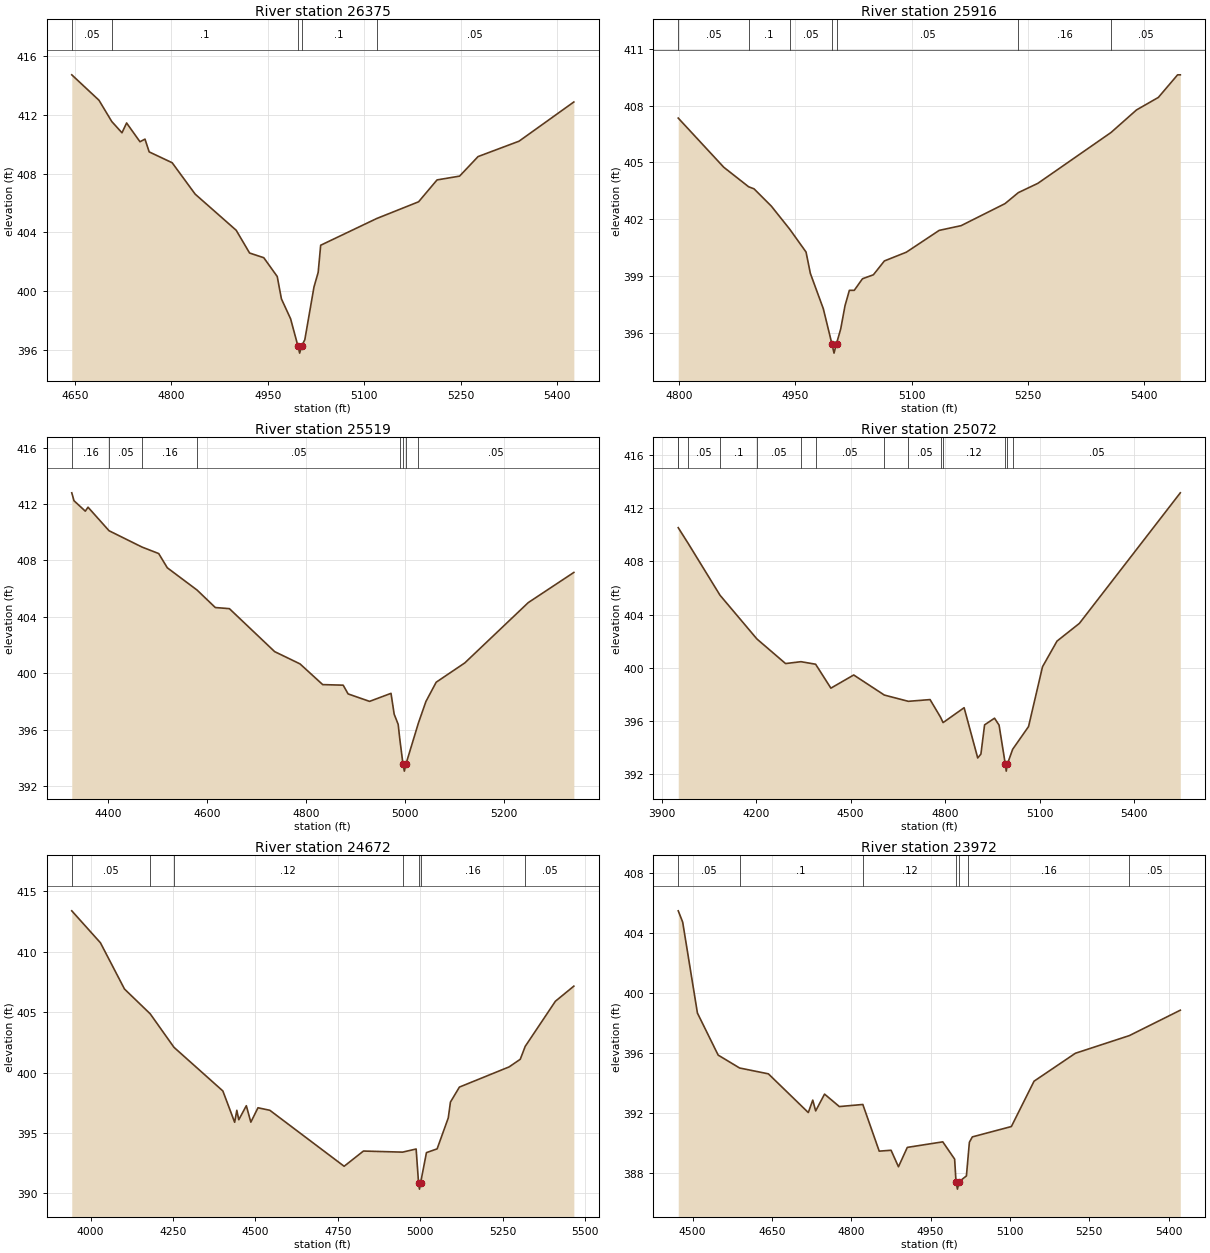
Type RM Length L Ch R = 1,26375,459,459,459
BEGIN DESCRIPTION:
SNAKE BRANCH 48.0
END DESCRIPTION:
XS GIS Cut Line= 3
      3551592.10     10336791.64      3551292.11     10336541.64
      3550992.12     10336291.65
#Sta/Elev= 30
  4645.1  414.73  4687.4  413.00  4707.3  411.55  4723.2  410.78  4730.4  411.45
  4751.2  410.17  4759.0  410.35  4765.5  409.48  4801.3  408.74  4837.1  406.60
  4900.9  404.14  4921.7  402.59  4943.8  402.27  4964.7  400.99  4971.2  399.47
  4985.5  398.11  4996.8  396.27  4999.6  395.77  5002.8  396.27  5007.6  396.68
  5021.9  400.28  5028.4  401.27  5032.3  403.12  5119.4  404.94  5184.6  406.08
  5213.3  407.57  5248.4  407.83  5277.1  409.16  5340.9  410.21  5426.1  412.88
#Mann=5,-1,0
  4645.1    0.05       0  4707.3     0.1       0  4996.8    0.07       0
  5002.8     0.1       0  5119.4    0.05       0
Bank Sta=4996.8,5002.8
Exp/Cntr=0.3,0.1

Type RM Length L Ch R = 1,25916,397,397,397
BEGIN DESCRIPTION:
SNAKE BRANCH 47.0
END DESCRIPTION:
XS GIS Cut Line= 3
      3551742.09     10336441.60      3551642.11     10336241.64
      3551342.13     10335941.66
#Sta/Elev= 30
  4799.0  407.34  4857.7  404.75  4889.8  403.72  4896.8  403.61  4919.1  402.70
  4942.9  401.48  4963.9  400.28  4969.5  399.15  4986.2  397.29  4997.2  395.45
  5000.0  394.95  5003.2  395.45  5008.6  396.22  5014.2  397.45  5019.8  398.26
  5026.1  398.26  5036.7  398.87  5050.8  399.08  5065.0  399.81  5093.3  400.27
  5135.7  401.42  5164.0  401.67  5220.6  402.83  5237.8  403.41  5263.0  403.90
  5357.4  406.58  5390.3  407.77  5418.5  408.43  5443.3  409.62  5446.8  409.62
#Mann=7,-1,0
  4799.0    0.05       0  4889.8     0.1       0  4942.9    0.05       0
  4997.2    0.03       0  5003.2    0.05       0  5237.8    0.16       0
  5357.4    0.05       0
Bank Sta=4997.2,5003.2
Exp/Cntr=0.3,0.1

Type RM Length L Ch R = 1,25519,447,447,447
BEGIN DESCRIPTION:
SNAKE BRANCH 46.0
END DESCRIPTION:
XS GIS Cut Line= 3
      3552210.48     10336557.53      3551979.51     10336059.34
      3551692.12     10335691.66
#Sta/Elev= 30
  4326.3  412.80  4330.8  412.24  4353.7  411.50  4359.2  411.78  4401.7  410.11
  4468.5  408.95  4502.2  408.49  4519.6  407.48  4579.8  405.90  4616.7  404.66
  4645.2  404.58  4736.8  401.53  4788.1  400.66  4834.0  399.19  4875.4  399.15
  4885.4  398.53  4928.8  398.00  4972.2  398.57  4978.6  397.09  4986.7  396.37
  4990.0  395.32  4996.4  393.55  4999.2  393.05  5002.4  393.55  5027.6  396.46
  5042.8  397.99  5063.6  399.36  5121.5  400.73  5249.9  405.01  5342.1  407.15
#Mann=8,-1,0
  4326.3    0.16       0  4401.7    0.05       0  4468.5    0.16       0
  4579.8    0.05       0  4990.0    0.16       0  4996.4    0.07       0
  5002.4    0.16       0  5027.6    0.05       0
Bank Sta=4996.4,5002.4
Exp/Cntr=0.3,0.1

Type RM Length L Ch R = 1,25072,400,400,400
BEGIN DESCRIPTION:
Mapping XS a47a8af3
END DESCRIPTION:
XS GIS Cut Line= 3
      3553090.40     10335924.06      3552265.06     10335702.20
      3551621.67     10335336.29
#Sta/Elev= 30
  3952.4  410.54  3952.6  410.53  3983.9  409.36  4085.1  405.46  4202.3  402.17
  4293.3  400.32  4342.3  400.46  4388.8  400.27  4437.3  398.47  4509.8  399.46
  4607.1  397.95  4683.3  397.48  4752.3  397.61  4785.7  396.28  4793.7  395.88
  4860.5  397.00  4903.7  393.22  4913.8  393.51  4925.5  395.71  4957.1  396.21
  4971.5  395.69  4991.5  392.73  4994.3  392.23  4997.5  392.73  5014.6  393.87
  5065.1  395.58  5109.5  400.08  5155.6  402.01  5226.6  403.34  5547.2  413.16
#Mann=14,-1,0
  3952.4    0.05       0  3952.6     0.1       0  3983.9    0.05       0
  4085.1     0.1       0  4202.3    0.05       0  4342.3    0.16       0
  4388.8    0.05       0  4607.1    0.16       0  4683.3    0.05       0
  4785.7    0.16       0  4793.7    0.12       0  4991.5    0.07       0
  4997.5    0.12       0  5014.6    0.05       0
Bank Sta=4991.5,4997.5
Exp/Cntr=0.3,0.1

Type RM Length L Ch R = 1,24672,700,700,700
BEGIN DESCRIPTION:
SNAKE BRANCH 45.0
END DESCRIPTION:
XS GIS Cut Line= 3
      3553271.22     10335802.42      3552632.29     10335403.09
      3551892.06     10335191.63
#Sta/Elev= 30
  3943.0  413.38  4029.9  410.74  4103.0  406.91  4181.0  404.86  4253.1  402.09
  4401.4  398.48  4437.2  395.89  4443.8  396.88  4449.7  396.10  4472.6  397.26
  4486.3  395.90  4508.0  397.09  4544.0  396.88  4769.4  392.25  4827.9  393.51
  4946.9  393.42  4987.8  393.68  4995.2  390.86  4998.0  390.36  5001.2  390.86
  5019.1  393.38  5051.5  393.69  5085.3  396.25  5091.9  397.56  5119.1  398.80
  5269.9  400.47  5303.7  401.10  5318.8  402.17  5410.3  405.90  5466.3  407.15
#Mann=7,-1,0
  3943.0    0.05       0  4181.0     0.1       0  4253.1    0.12       0
  4946.9    0.16       0  4995.2    0.07       0  5001.2    0.16       0
  5318.8    0.05       0
Bank Sta=4995.2,5001.2
Exp/Cntr=0.3,0.1

Type RM Length L Ch R = 1,23972,533,533,533
BEGIN DESCRIPTION:
SNAKE BRANCH 44.0
END DESCRIPTION:
XS GIS Cut Line= 3
      3553092.10     10335191.64      3552592.11     10334941.64
      3552292.13     10334691.66
#Sta/Elev= 30
  4472.8  405.49  4481.2  404.74  4509.1  398.68  4548.3  395.88  4588.8  395.02
  4643.3  394.63  4718.8  392.05  4727.2  392.88  4732.7  392.16  4749.5  393.28
  4777.5  392.45  4821.9  392.59  4852.9  389.48  4875.3  389.54  4889.3  388.44
  4906.0  389.73  4973.1  390.10  4995.5  388.95  4998.1  387.45  5000.8  386.95
  5004.1  387.45  5017.8  387.83  5020.9  389.07  5023.4  390.07  5029.0  390.43
  5102.8  391.12  5145.7  394.14  5223.8  396.00  5326.1  397.18  5422.3  398.87
#Mann=7,-1,0
  4472.8    0.05       0  4588.8     0.1       0  4821.9    0.12       0
  4998.1    0.07       0  5004.1    0.12       0  5020.9    0.16       0
  5326.1    0.05       0
Bank Sta=4998.1,5004.1
Exp/Cntr=0.3,0.1

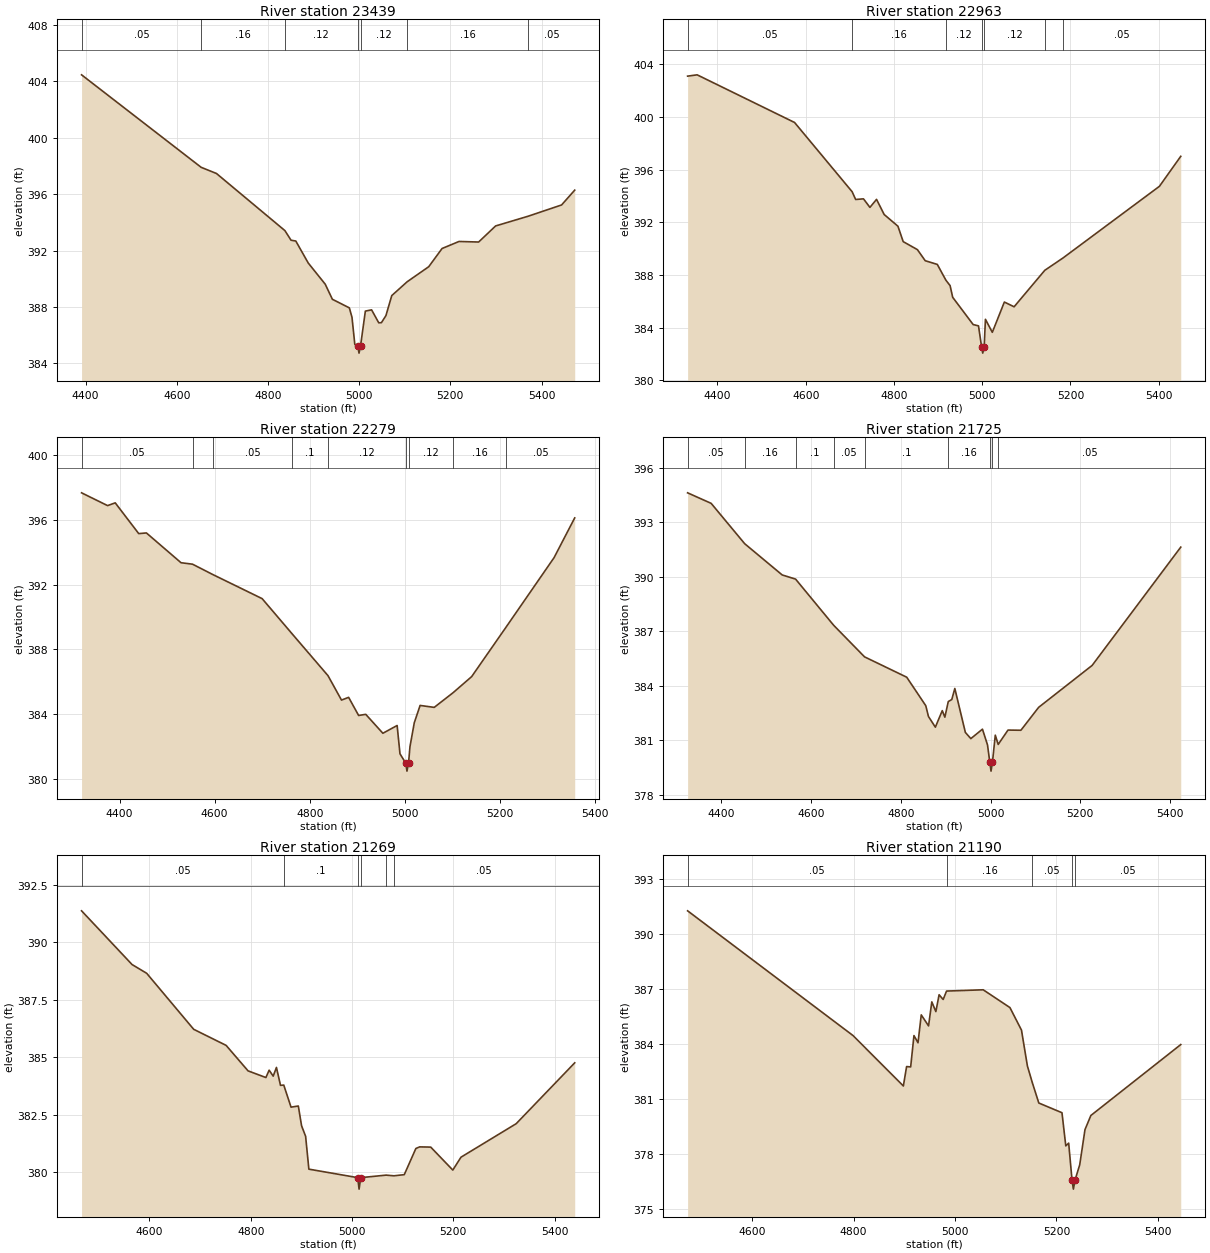
Type RM Length L Ch R = 1,23439,476,476,476
BEGIN DESCRIPTION:
SNAKE BRANCH 43.0
END DESCRIPTION:
XS GIS Cut Line= 3
      3553392.08     10334891.63      3552969.10     10334701.70
      3552435.76     10334390.01
#Sta/Elev= 30
  4391.3  404.47  4653.5  397.91  4687.2  397.47  4837.2  393.42  4850.6  392.74
  4861.1  392.68  4888.4  391.12  4925.6  389.62  4941.3  388.55  4978.5  387.94
  4984.3  387.27  4990.5  385.35  4997.0  385.23  4999.7  384.73  5003.0  385.23
  5013.6  387.71  5027.3  387.80  5043.0  386.88  5048.8  386.89  5058.7  387.39
  5071.5  388.81  5105.2  389.79  5152.6  390.86  5181.8  392.15  5219.0  392.65
  5262.0  392.61  5299.2  393.75  5370.5  394.44  5443.9  395.24  5472.7  396.29
#Mann=7,-1,0
  4391.3    0.05       0  4653.5    0.16       0  4837.2    0.12       0
  4997.0    0.07       0  5003.0    0.12       0  5105.2    0.16       0
  5370.5    0.05       0
Bank Sta=4997,5003
Exp/Cntr=0.3,0.1

Type RM Length L Ch R = 1,22963,684,684,684
BEGIN DESCRIPTION:
SNAKE BRANCH 42.0
END DESCRIPTION:
XS GIS Cut Line= 3
      3553565.74     10334515.26      3553065.72     10334315.25
      3552566.67     10334021.35
#Sta/Elev= 30
  4332.3  403.10  4353.9  403.20  4574.7  399.58  4705.2  394.32  4713.2  393.73
  4730.9  393.78  4745.5  393.13  4760.5  393.74  4777.8  392.59  4809.0  391.70
  4820.9  390.53  4853.2  389.92  4870.8  389.08  4898.2  388.80  4917.7  387.60
  4927.2  387.19  4933.1  386.30  4979.5  384.23  4991.6  384.13  4998.5  382.56
  5001.2  382.06  5004.5  382.56  5007.3  384.63  5022.9  383.64  5050.2  385.94
  5072.3  385.58  5141.8  388.35  5183.2  389.29  5401.6  394.73  5450.0  397.01
#Mann=7,-1,0
  4332.3    0.05       0  4705.2    0.16       0  4917.7    0.12       0
  4998.5    0.07       0  5004.5    0.12       0  5141.8    0.16       0
  5183.2    0.05       0
Bank Sta=4998.5,5004.5
Exp/Cntr=0.3,0.1

Type RM Length L Ch R = 1,22279,554,554,554
BEGIN DESCRIPTION:
SNAKE BRANCH 40.0
END DESCRIPTION:
XS GIS Cut Line= 3
      3553726.00     10334132.24      3553316.32     10333910.03
      3552842.15     10333591.67
#Sta/Elev= 30
  4320.1  397.68  4374.8  396.89  4390.9  397.06  4440.3  395.16  4456.5  395.20
  4529.3  393.36  4553.5  393.27  4596.1  392.63  4699.9  391.14  4763.4  388.95
  4838.4  386.38  4866.8  384.87  4881.8  385.04  4902.8  383.92  4917.8  383.99
  4953.8  382.82  4983.8  383.30  4989.8  381.55  5001.8  380.98  5004.5  380.48
  5007.8  380.98  5010.8  381.99  5019.8  383.46  5032.1  384.54  5061.8  384.42
  5101.2  385.32  5140.5  386.32  5212.7  389.37  5313.8  393.67  5357.3  396.13
#Mann=9,-1,0
  4320.1    0.05       0  4553.5     0.1       0  4596.1    0.05       0
  4763.4     0.1       0  4838.4    0.12       0  5001.8    0.07       0
  5007.8    0.12       0  5101.2    0.16       0  5212.7    0.05       0
Bank Sta=5001.8,5007.8
Exp/Cntr=0.3,0.1

Type RM Length L Ch R = 1,21725,456,456,456
BEGIN DESCRIPTION:
SNAKE BRANCH 39.0
END DESCRIPTION:
XS GIS Cut Line= 3
      3553948.29     10333736.44      3553392.11     10333391.64
      3552989.90     10333201.69
#Sta/Elev= 30
  4324.6  394.61  4377.1  394.03  4451.8  391.81  4535.4  390.09  4565.3  389.86
  4650.1  387.32  4719.0  385.58  4813.0  384.46  4855.5  382.89  4861.4  382.30
  4876.8  381.71  4892.2  382.62  4898.0  382.26  4905.6  383.12  4913.4  383.23
  4920.2  383.84  4943.7  381.42  4955.9  381.08  4981.8  381.60  4993.1  380.73
  4998.1  379.79  5000.9  379.29  5004.1  379.79  5010.4  381.27  5016.9  380.76
  5038.7  381.55  5067.5  381.54  5107.0  382.80  5226.3  385.11  5423.8  391.62
#Mann=9,-1,0
  4324.6    0.05       0  4451.8    0.16       0  4565.3     0.1       0
  4650.1    0.05       0  4719.0     0.1       0  4905.6    0.16       0
  4998.1    0.07       0  5004.1    0.16       0  5016.9    0.05       0
Bank Sta=4998.1,5004.1
Exp/Cntr=0.3,0.1

Type RM Length L Ch R = 1,21269,79,79,79
BEGIN DESCRIPTION:
SNAKE BRANCH 38.1
END DESCRIPTION:
XS GIS Cut Line= 3
      3553976.05     10333458.65      3553642.11     10333041.64
      3553257.32     10332830.19
#Sta/Elev= 30
  4466.2  391.37  4565.9  389.03  4594.7  388.65  4687.5  386.21  4751.5  385.51
  4794.8  384.40  4830.0  384.11  4836.4  384.43  4844.4  384.17  4850.8  384.55
  4858.8  383.77  4865.3  383.78  4879.6  382.82  4894.0  382.87  4900.4  382.01
  4908.4  381.55  4914.8  380.12  5011.2  379.75  5013.9  379.25  5017.2  379.75
  5067.4  379.86  5082.6  379.83  5103.1  379.88  5126.0  381.02  5133.5  381.09
  5155.3  381.08  5198.9  380.08  5215.0  380.64  5324.0  382.10  5439.5  384.75
#Mann=6,-1,0
  4466.2    0.05       0  4865.3     0.1       0  5011.2    0.07       0
  5017.2     0.1       0  5067.4    0.16       0  5082.6    0.05       0
Bank Sta=5011.2,5017.2
Exp/Cntr=0.3,0.1

Type RM Length L Ch R = 1,21190,105,105,105
BEGIN DESCRIPTION:
SNAKE BRANCH 38.0
END DESCRIPTION:
XS GIS Cut Line= 3
      3554035.05     10333406.53      3553701.13     10332989.56
      3553316.75     10332778.33
#Sta/Elev= 30
  4472.5  391.26  4798.9  384.45  4898.1  381.70  4904.5  382.76  4912.5  382.74
  4919.0  384.45  4927.0  384.06  4933.4  385.58  4947.8  384.98  4954.2  386.29
  4962.2  385.76  4968.6  386.68  4976.6  386.42  4983.3  386.88  5055.6  386.95
  5108.3  385.98  5131.1  384.75  5142.8  382.79  5152.4  381.89  5165.3  380.77
  5211.0  380.24  5218.5  378.43  5224.2  378.58  5230.8  376.57  5233.5  376.07
  5236.8  376.57  5246.0  377.40  5256.4  379.32  5268.0  380.09  5445.3  383.96
#Mann=5,-1,0
  4472.5    0.05       0  4983.3    0.16       0  5152.4    0.05       0
  5230.8    0.07       0  5236.8    0.05       0
Bank Sta=5230.8,5236.8
Exp/Cntr=0.3,0.1

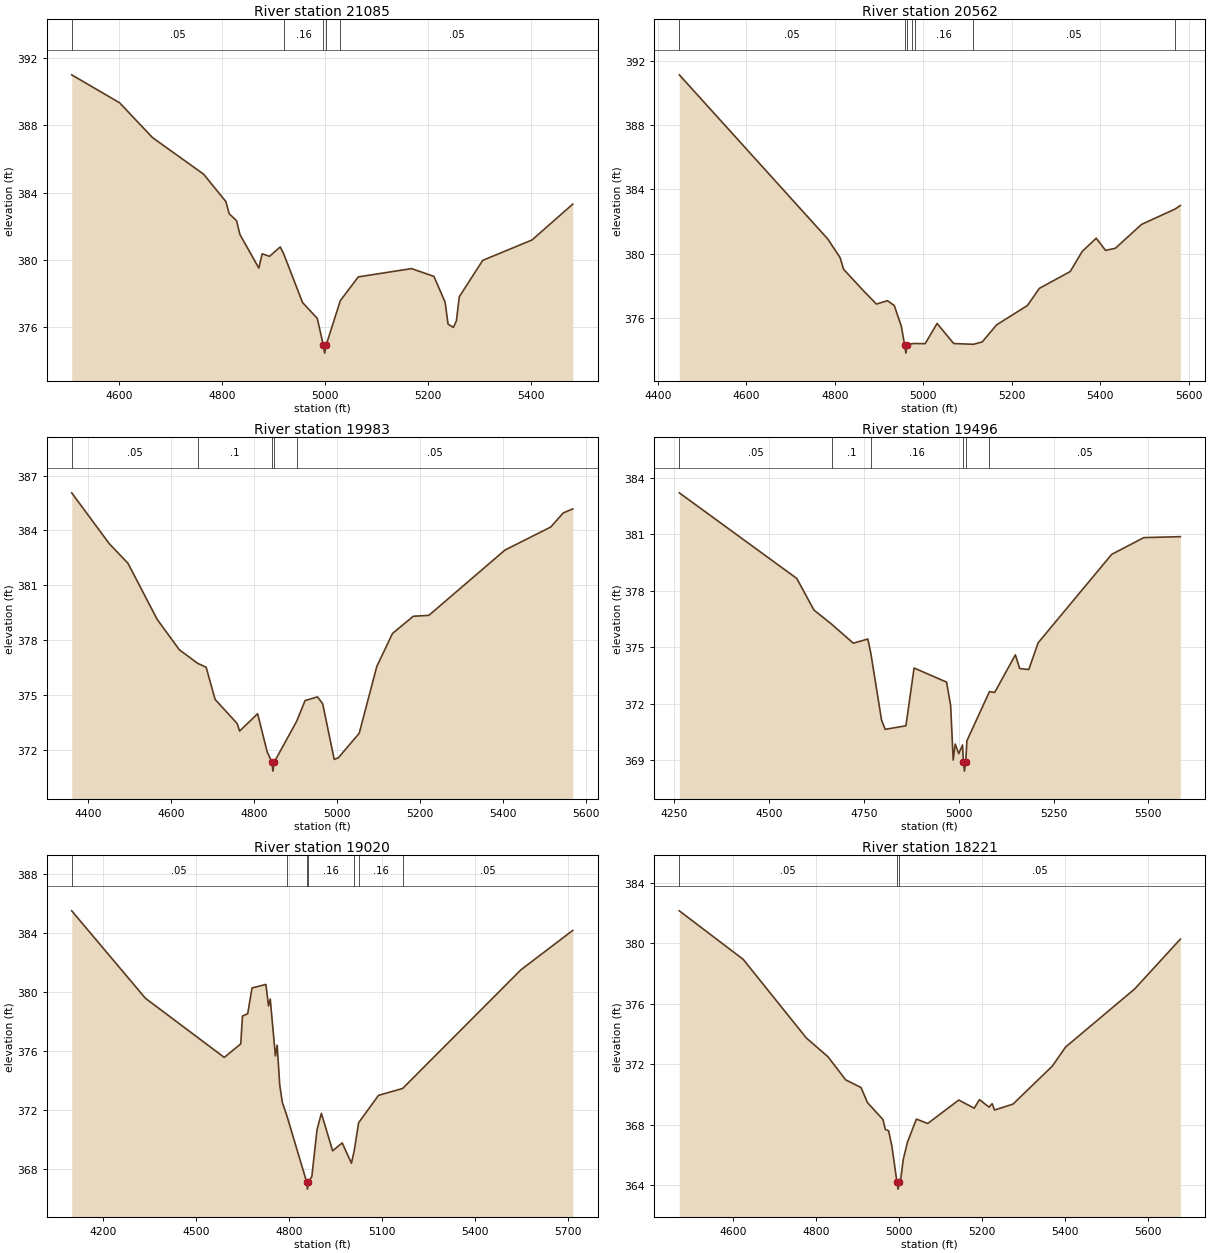
Type RM Length L Ch R = 1,21085,523,523,523
BEGIN DESCRIPTION:
SNAKE BRANCH 37.0
END DESCRIPTION:
XS GIS Cut Line= 3
      3554097.57     10333316.29      3553763.63     10332899.28
      3553378.84     10332687.83
#Sta/Elev= 30
  4507.2  390.99  4600.2  389.33  4664.2  387.26  4763.4  385.09  4806.7  383.46
  4813.1  382.74  4827.5  382.32  4833.9  381.51  4870.7  379.51  4877.1  380.36
  4891.5  380.21  4912.3  380.77  4919.1  380.35  4955.5  377.47  4984.3  376.52
  4995.7  374.96  4998.5  374.46  5001.7  374.96  5029.0  377.58  5064.0  378.99
  5167.2  379.48  5210.8  379.02  5232.6  377.48  5238.3  376.18  5248.6  375.99
  5254.4  376.37  5260.1  377.81  5305.6  379.97  5401.3  381.18  5480.5  383.31
#Mann=5,-1,0
  4507.2    0.05       0  4919.1    0.16       0  4995.7    0.07       0
  5001.7    0.16       0  5029.0    0.05       0
Bank Sta=4995.7,5001.7
Exp/Cntr=0.3,0.1

Type RM Length L Ch R = 1,20562,579,579,579
BEGIN DESCRIPTION:
SNAKE BRANCH 36.0
END DESCRIPTION:
XS GIS Cut Line= 3
      3554564.29     10332758.29      3554164.33     10332558.31
      3553510.79     10332351.02
#Sta/Elev= 30
  4448.7  391.15  4784.4  380.91  4812.3  379.74  4820.1  379.02  4864.8  377.69
  4894.3  376.85  4919.2  377.06  4934.7  376.76  4950.7  375.46  4958.2  374.29
  4960.9  373.79  4964.2  374.29  4975.0  374.38  4981.6  374.39  5004.5  374.38
  5031.5  375.64  5069.0  374.39  5113.7  374.34  5133.6  374.49  5165.9  375.55
  5235.7  376.76  5262.7  377.83  5332.5  378.88  5359.5  380.13  5391.3  380.96
  5412.3  380.20  5434.5  380.33  5493.8  381.82  5569.7  382.78  5581.5  383.00
#Mann=7,-1,0
  4448.7    0.05       0  4958.2    0.07       0  4964.2    0.05       0
  4975.0     0.1       0  4981.6    0.16       0  5113.7    0.05       0
  5569.7    0.16       0
Bank Sta=4958.2,4964.2
Exp/Cntr=0.3,0.1

Type RM Length L Ch R = 1,19983,487,487,487
BEGIN DESCRIPTION:
SNAKE BRANCH 35.0
END DESCRIPTION:
XS GIS Cut Line= 3
      3554670.50     10332316.30      3554189.33     10332040.25
      3553539.28     10331990.25
#Sta/Elev= 30
  4360.7  386.06  4451.1  383.28  4496.1  382.21  4566.5  379.14  4619.8  377.48
  4663.7  376.74  4684.5  376.52  4706.1  374.76  4759.3  373.44  4765.0  373.03
  4808.5  373.98  4831.5  371.89  4842.6  371.34  4845.3  370.84  4848.6  371.34
  4902.5  373.57  4922.7  374.70  4952.8  374.90  4965.2  374.52  4992.9  371.48
  5002.9  371.57  5053.1  372.91  5095.5  376.57  5133.3  378.37  5183.4  379.31
  5220.9  379.36  5404.1  382.93  5514.4  384.19  5544.5  384.96  5567.4  385.18
#Mann=5,-1,0
  4360.7    0.05       0  4663.7     0.1       0  4842.6    0.03       0
  4848.6     0.1       0  4902.5    0.05       0
Bank Sta=4842.6,4848.6
Exp/Cntr=0.3,0.1

Type RM Length L Ch R = 1,19496,476,476,476
BEGIN DESCRIPTION:
SNAKE BRANCH 34.0
END DESCRIPTION:
XS GIS Cut Line= 3
      3554982.95     10331927.38      3554469.10     10331739.90
      3553746.96     10331462.15
#Sta/Elev= 30
  4263.6  383.21  4573.2  378.66  4618.5  376.98  4665.0  376.23  4722.2  375.22
  4760.6  375.44  4768.7  374.65  4796.7  371.13  4806.3  370.64  4860.9  370.83
  4882.4  373.90  4968.1  373.15  4978.8  371.91  4985.5  369.01  4990.8  369.86
  5000.2  369.35  5010.1  369.81  5012.5  368.92  5015.2  368.42  5018.5  368.92
  5021.6  370.03  5081.2  372.65  5094.8  372.60  5149.4  374.60  5160.9  373.87
  5184.8  373.82  5209.4  375.24  5403.3  379.94  5488.0  380.83  5584.3  380.88
#Mann=6,-1,0
  4263.6    0.05       0  4665.0     0.1       0  4768.7    0.16       0
  5012.5    0.07       0  5018.5    0.16       0  5081.2    0.05       0
Bank Sta=5012.5,5018.5
Exp/Cntr=0.3,0.1

Type RM Length L Ch R = 1,19020,799,799,799
BEGIN DESCRIPTION:
SNAKE BRANCH 33.0
END DESCRIPTION:
XS GIS Cut Line= 3
      3555242.11     10331691.64      3554442.11     10331291.64
      3553842.14     10330891.66
#Sta/Elev= 30
  4099.1  385.51  4336.7  379.57  4591.0  375.55  4644.1  376.47  4649.7  378.36
  4666.5  378.52  4680.5  380.27  4725.2  380.51  4733.6  379.05  4739.2  379.52
  4755.9  375.65  4761.5  376.38  4769.9  373.65  4778.3  372.48  4792.5  371.61
  4856.4  367.10  4859.1  366.60  4862.4  367.10  4873.3  367.45  4890.1  370.65
  4904.1  371.75  4940.4  369.20  4971.2  369.74  5001.0  368.36  5010.1  369.23
  5024.1  371.11  5088.2  372.97  5166.0  373.44  5547.9  381.51  5714.6  384.18
#Mann=7,-1,0
  4099.1    0.05       0  4792.5    0.16       0  4856.4    0.07       0
  4862.4    0.16       0  5010.1     0.1       0  5024.1    0.16       0
  5166.0    0.05       0
Bank Sta=4856.4,4862.4
Exp/Cntr=0.3,0.1

Type RM Length L Ch R = 1,18221,552,552,552
BEGIN DESCRIPTION:
SNAKE BRANCH 31.0
END DESCRIPTION:
XS GIS Cut Line= 3
      3555283.80     10331202.77      3554899.65     10330969.06
      3554242.12     10330591.65
#Sta/Elev= 30
  4471.0  382.14  4625.1  378.93  4777.3  373.73  4829.5  372.49  4872.2  370.96
  4909.0  370.46  4924.6  369.46  4961.9  368.34  4967.7  367.68  4975.5  367.60
  4983.5  366.57  4995.5  364.24  4998.3  363.74  5001.5  364.24  5005.1  364.47
  5010.8  365.70  5020.9  366.84  5042.5  368.37  5069.8  368.08  5144.6  369.63
  5182.0  369.09  5194.5  369.66  5217.6  369.16  5225.1  369.39  5230.9  368.97
  5275.3  369.36  5370.4  371.88  5402.0  373.13  5568.8  376.98  5678.8  380.27
#Mann=3,-1,0
  4471.0    0.05       0  4995.5   0.035       0  5001.5    0.05       0
Bank Sta=4995.5,5001.5
Exp/Cntr=0.3,0.1

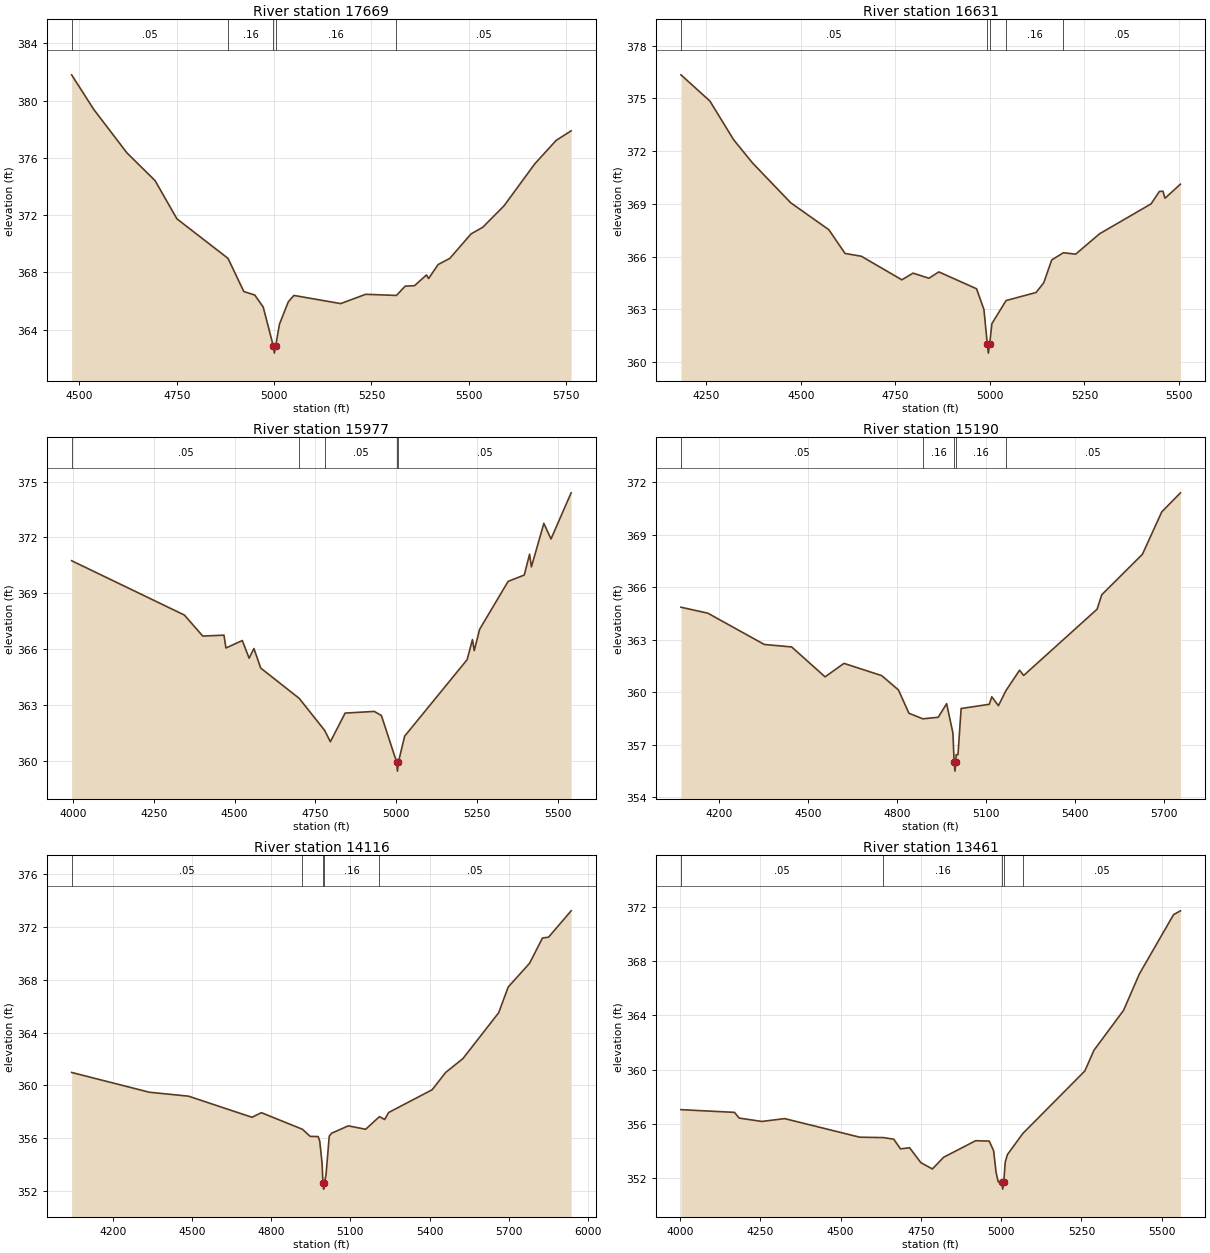
Type RM Length L Ch R = 1,17669,1038,1038,1038
BEGIN DESCRIPTION:
SNAKE BRANCH 30.0
END DESCRIPTION:
XS GIS Cut Line= 3
      3555492.09     10330841.63      3554892.71     10330371.84
      3554406.85     10330184.44
#Sta/Elev= 30
  4480.3  381.80  4537.2  379.38  4622.2  376.35  4694.5  374.41  4750.6  371.74
  4881.7  368.98  4922.4  366.66  4950.4  366.42  4972.1  365.58  4998.0  362.86
  5000.7  362.36  5004.0  362.86  5013.9  364.39  5036.3  365.93  5050.7  366.39
  5171.0  365.82  5235.2  366.47  5314.2  366.39  5336.6  367.04  5360.4  367.07
  5391.2  367.82  5396.6  367.57  5421.2  368.55  5451.2  368.98  5505.7  370.69
  5535.7  371.15  5590.3  372.65  5669.5  375.59  5724.1  377.22  5762.6  377.89
#Mann=5,-1,0
  4480.3    0.05       0  4881.7    0.16       0  4998.0    0.07       0
  5004.0    0.16       0  5314.2    0.05       0
Bank Sta=4998,5004
Exp/Cntr=0.3,0.1

Type RM Length L Ch R = 1,16631,654,654,654
BEGIN DESCRIPTION:
SNAKE BRANCH 29.0
END DESCRIPTION:
XS GIS Cut Line= 3
      3555726.03     10330413.50      3555198.26     10330038.51
      3554559.38     10329823.23
#Sta/Elev= 30
  4182.4  376.34  4259.0  374.85  4322.1  372.64  4372.1  371.32  4473.0  369.06
  4573.8  367.53  4616.6  366.18  4659.9  366.02  4766.9  364.68  4796.5  365.06
  4838.6  364.77  4864.8  365.13  4964.6  364.17  4984.1  362.99  4993.1  361.01
  4995.8  360.51  4999.1  361.01  5005.2  362.19  5042.6  363.50  5122.0  363.96
  5142.3  364.51  5163.4  365.81  5194.3  366.22  5226.8  366.14  5290.1  367.30
  5426.3  369.00  5448.4  369.71  5457.8  369.72  5463.1  369.32  5504.0  370.12
#Mann=5,-1,0
  4182.4    0.05       0  4993.1    0.03       0  4999.1    0.05       0
  5042.6    0.16       0  5194.3    0.05       0
Bank Sta=4993.1,4999.1
Exp/Cntr=0.3,0.1

Type RM Length L Ch R = 1,15977,787,787,787
BEGIN DESCRIPTION:
SNAKE BRANCH 28.0
END DESCRIPTION:
XS GIS Cut Line= 3
      3556031.56     10330066.26      3555364.93     10329607.95
      3554712.17     10329267.68
#Sta/Elev= 30
  3995.9  370.75  4344.7  367.83  4401.5  366.70  4467.1  366.75  4473.2  366.06
  4523.9  366.46  4544.9  365.51  4559.8  366.03  4580.8  364.98  4699.9  363.35
  4778.5  361.63  4796.2  361.02  4841.9  362.56  4932.0  362.65  4954.1  362.43
  5000.9  359.94  5003.7  359.44  5006.9  359.94  5026.0  361.32  5219.2  365.43
  5235.7  366.51  5241.3  365.92  5257.8  367.06  5346.1  369.64  5396.0  369.98
  5412.4  371.10  5418.1  370.42  5456.6  372.76  5478.7  371.92  5541.0  374.40
#Mann=5,-1,0
  3995.9    0.05       0  4699.9    0.16       0  4778.5    0.05       0
  5000.9    0.03       0  5006.9    0.05       0
Bank Sta=5000.9,5006.9
Exp/Cntr=0.3,0.1

Type RM Length L Ch R = 1,15190,1074,1074,1074
BEGIN DESCRIPTION:
SNAKE BRANCH 26.0
END DESCRIPTION:
XS GIS Cut Line= 3
      3556260.75     10329691.27      3555592.11     10329041.64
      3554948.23     10328649.60
#Sta/Elev= 30
  4070.2  364.85  4160.9  364.51  4351.8  362.72  4443.9  362.58  4556.8  360.87
  4620.6  361.64  4747.9  360.94  4804.5  360.12  4839.8  358.79  4886.8  358.47
  4938.8  358.56  4967.1  359.34  4988.4  357.65  4992.4  355.98  4995.1  355.48
  4998.4  355.98  4999.0  356.42  5005.4  356.42  5016.0  359.06  5111.0  359.30
  5119.5  359.73  5141.9  359.22  5166.8  360.07  5213.2  361.25  5227.2  360.95
  5475.1  364.74  5490.6  365.56  5628.1  367.88  5693.2  370.30  5756.3  371.39
#Mann=5,-1,0
  4070.2    0.05       0  4886.8    0.16       0  4992.4    0.07       0
  4998.4    0.16       0  5166.8    0.05       0
Bank Sta=4992.4,4998.4
Exp/Cntr=0.3,0.1

Type RM Length L Ch R = 1,14116,655,655,655
BEGIN DESCRIPTION:
SNAKE BRANCH 25.0
END DESCRIPTION:
XS GIS Cut Line= 3
      3556719.13     10329260.76      3556163.54     10328712.12
      3555242.10     10328091.64
#Sta/Elev= 30
  4044.4  360.97  4338.6  359.47  4487.2  359.17  4727.6  357.57  4762.9  357.92
  4918.5  356.66  4948.0  356.12  4978.0  356.11  4984.0  355.76  4992.9  354.08
  4996.0  352.62  4998.7  352.12  5002.0  352.62  5007.8  353.21  5020.0  356.14
  5028.9  356.36  5092.2  356.92  5157.9  356.66  5210.2  357.62  5229.9  357.40
  5244.8  357.93  5409.8  359.66  5460.8  360.97  5526.2  362.02  5661.7  365.50
  5697.7  367.45  5778.6  369.25  5827.6  371.17  5850.6  371.23  5936.1  373.23
#Mann=5,-1,0
  4044.4    0.05       0  4918.5    0.16       0  4996.0    0.07       0
  5002.0    0.16       0  5210.2    0.05       0
Bank Sta=4996,5002
Exp/Cntr=0.3,0.1

Type RM Length L Ch R = 1,13461,812,812,812
BEGIN DESCRIPTION:
SNAKE BRANCH 23.0
END DESCRIPTION:
XS GIS Cut Line= 3
      3557003.80     10328725.99      3556378.82     10328156.56
      3555842.08     10327691.62
#Sta/Elev= 30
  4002.7  357.05  4169.6  356.85  4183.8  356.43  4254.7  356.18  4325.6  356.39
  4559.4  355.02  4632.9  354.99  4665.5  354.87  4686.4  354.16  4714.8  354.24
  4750.0  353.14  4785.8  352.68  4820.9  353.54  4920.5  354.76  4962.9  354.73
  4976.5  354.02  4984.1  352.44  4990.8  351.73  5002.0  351.69  5004.8  351.19
  5008.0  351.69  5012.6  353.17  5019.3  353.73  5067.3  355.29  5260.5  359.90
  5289.0  361.43  5381.1  364.37  5430.5  367.06  5536.9  371.43  5558.3  371.71
#Mann=5,-1,0
  4002.7    0.05       0  4632.9    0.16       0  5002.0    0.07       0
  5008.0    0.16       0  5067.3    0.05       0
Bank Sta=5002,5008
Exp/Cntr=0.3,0.1

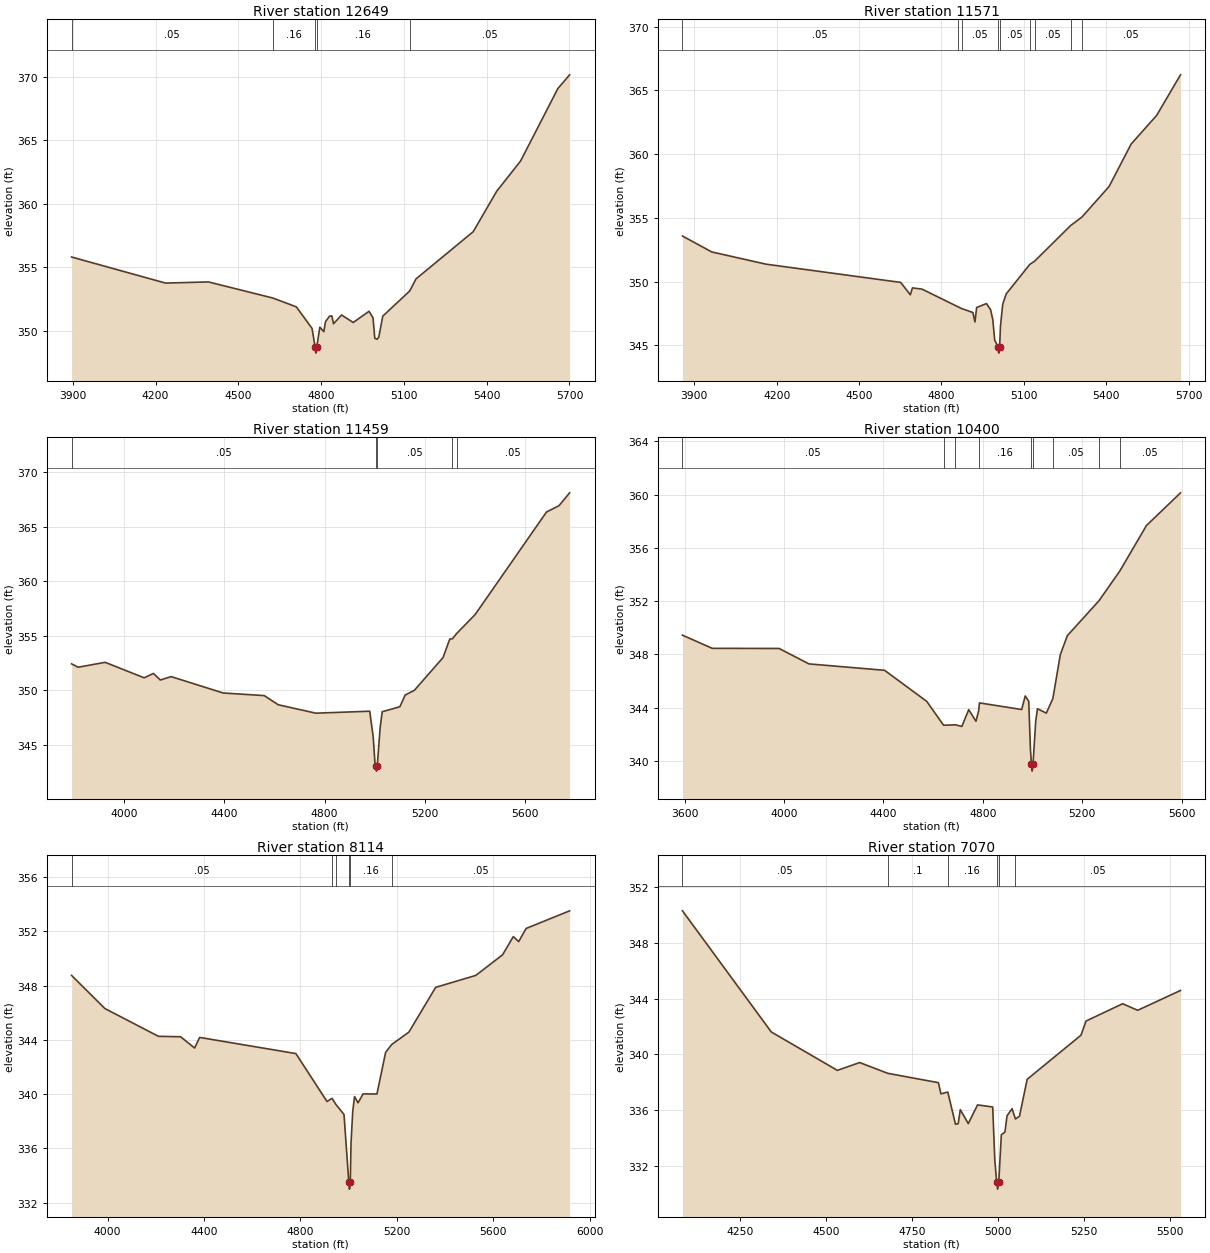
Type RM Length L Ch R = 1,12649,1078,1078,1078
BEGIN DESCRIPTION:
SNAKE BRANCH 21.0
END DESCRIPTION:
XS GIS Cut Line= 3
      3557503.83     10328420.46      3556899.65     10327739.90
      3556192.07     10327191.61
#Sta/Elev= 30
  3895.4  355.81  4235.9  353.76  4391.4  353.85  4625.4  352.58  4710.0  351.89
  4766.9  350.20  4778.1  348.75  4780.9  348.25  4784.1  348.75  4795.3  350.29
  4809.7  349.94  4816.0  350.73  4830.5  351.16  4838.7  351.18  4845.0  350.56
  4874.0  351.25  4916.2  350.66  4973.6  351.54  4988.1  351.02  4994.4  349.42
  5002.6  349.34  5008.9  349.51  5023.4  351.16  5121.1  353.14  5143.9  354.09
  5351.1  357.80  5436.2  360.98  5523.1  363.37  5658.0  369.06  5700.6  370.14
#Mann=5,-1,0
  3895.4    0.05       0  4625.4    0.16       0  4778.1    0.07       0
  4784.1    0.16       0  5121.1    0.05       0
Bank Sta=4778.1,4784.1
Exp/Cntr=0.3,0.1

Type RM Length L Ch R = 1,11571,112,112,112
BEGIN DESCRIPTION:
Mapping XS 242b7f13
END DESCRIPTION:
XS GIS Cut Line= 3
      3558044.37     10327959.06      3557267.48     10327305.87
      3556606.36     10326857.17
#Sta/Elev= 30
  3856.8  353.57  3963.5  352.32  4161.3  351.36  4651.6  349.93  4686.7  348.96
  4694.5  349.50  4729.7  349.40  4859.9  348.02  4873.2  347.88  4914.5  347.57
  4922.2  346.83  4928.3  347.96  4964.2  348.27  4979.1  347.79  4987.1  347.00
  4994.1  345.40  5006.0  344.88  5008.8  344.38  5012.0  344.88  5015.1  346.51
  5023.3  348.22  5036.1  349.03  5122.1  351.35  5139.1  351.59  5270.5  354.39
  5312.3  355.07  5410.4  357.45  5491.1  360.79  5584.0  363.04  5670.8  366.22
#Mann=9,-1,0
  3856.8    0.05       0  4859.9    0.16       0  4873.2    0.05       0
  5006.0    0.04       0  5012.0    0.05       0  5122.1    0.16       0
  5139.1    0.05       0  5270.5    0.16       0  5312.3    0.05       0
Bank Sta=5006,5012
Exp/Cntr=0.3,0.1

Type RM Length L Ch R = 1,11459,1059,1059,1059
BEGIN DESCRIPTION:
SNAKE BRANCH 19.0
END DESCRIPTION:
XS GIS Cut Line= 2
      3558178.97     10327891.83      3556615.65     10326668.93
#Sta/Elev= 30
  3791.3  352.43  3817.5  352.12  3925.1  352.57  4080.7  351.15  4117.4  351.55
  4144.9  350.95  4188.2  351.26  4395.3  349.76  4559.0  349.52  4615.1  348.68
  4764.9  347.91  4979.5  348.09  4993.4  345.72  5000.3  343.36  5003.6  343.10
  5006.4  342.60  5009.6  343.10  5021.1  346.59  5029.2  348.04  5099.8  348.50
  5120.6  349.57  5157.6  350.01  5271.5  353.00  5298.7  354.71  5308.8  354.72
  5326.0  355.21  5399.7  356.95  5683.9  366.34  5733.6  366.92  5776.1  368.10
#Mann=5,-1,0
  3791.3    0.05       0  5003.6    0.04       0  5009.6    0.05       0
  5308.8    0.16       0  5326.0    0.05       0
Bank Sta=5003.6,5009.6
Exp/Cntr=0.3,0.1

Type RM Length L Ch R = 1,10400,2286,2286,2286
BEGIN DESCRIPTION:
SNAKE BRANCH 17.0
END DESCRIPTION:
XS GIS Cut Line= 3
      3558788.53     10327614.89      3557948.26     10326823.23
      3557330.23     10326239.91
#Sta/Elev= 30
  3591.2  349.44  3711.1  348.45  3980.1  348.44  4100.3  347.28  4404.5  346.80
  4574.5  344.46  4642.0  342.67  4689.8  342.70  4715.6  342.58  4743.2  343.84
  4772.3  342.97  4783.3  343.76  4786.4  344.35  4956.4  343.85  4970.5  344.87
  4984.7  344.47  4991.6  340.84  4995.8  339.72  4998.6  339.22  5001.8  339.72
  5013.0  343.02  5019.9  343.91  5055.5  343.58  5081.9  344.68  5111.7  347.97
  5140.0  349.40  5267.5  352.03  5351.5  354.27  5458.4  357.68  5595.5  360.14
#Mann=9,-1,0
  3591.2    0.05       0  4642.0    0.12       0  4689.8    0.05       0
  4783.3    0.16       0  4995.8    0.07       0  5001.8    0.16       0
  5081.9    0.05       0  5267.5     0.1       0  5351.5    0.05       0
Bank Sta=4995.8,5001.8
Exp/Cntr=0.3,0.1

Type RM Length L Ch R = 1,8114,1044,1044,1044
BEGIN DESCRIPTION:
SNAKE BRANCH 15.0
END DESCRIPTION:
XS GIS Cut Line= 3
      3559337.16     10327191.29      3558531.60     10326128.78
      3557871.83     10325809.32
#Sta/Elev= 30
  3850.6  348.75  3988.8  346.31  4211.3  344.26  4302.9  344.23  4361.1  343.40
  4381.9  344.18  4781.3  342.99  4910.3  339.46  4931.3  339.69  4947.8  339.23
  4981.0  338.50  5000.9  333.50  5003.6  333.00  5006.9  333.50  5010.1  336.42
  5017.2  338.74  5024.7  339.82  5039.2  339.36  5060.1  340.02  5117.6  340.01
  5153.6  343.08  5178.9  343.66  5250.1  344.57  5361.2  347.87  5527.7  348.75
  5638.9  350.27  5683.4  351.61  5705.6  351.24  5736.5  352.21  5917.0  353.51
#Mann=6,-1,0
  3850.6    0.05       0  4931.3    0.12       0  4947.8    0.16       0
  5000.9    0.07       0  5006.9    0.16       0  5178.9    0.05       0
Bank Sta=5000.9,5006.9
Exp/Cntr=0.3,0.1

Type RM Length L Ch R = 1,7070,877,877,877
BEGIN DESCRIPTION:
SNAKE BRANCH 12.0
END DESCRIPTION:
XS GIS Cut Line= 3
      3559842.11     10326691.65      3559292.11     10325941.64
      3558983.73     10325525.63
#Sta/Elev= 30
  4083.4  350.28  4341.6  341.61  4533.8  338.86  4598.6  339.42  4680.1  338.65
  4827.4  337.98  4834.8  337.18  4854.8  337.31  4877.0  335.01  4884.9  335.04
  4891.1  336.05  4914.3  335.05  4941.3  336.39  4985.3  336.24  4991.5  332.41
  4996.9  330.86  4999.7  330.36  5002.9  330.86  5010.4  334.25  5020.8  334.44
  5027.0  335.61  5041.6  336.12  5051.4  335.38  5063.2  335.58  5085.5  338.22
  5242.0  341.38  5256.6  342.39  5363.0  343.63  5406.8  343.16  5531.3  344.58
#Mann=6,-1,0
  4083.4    0.05       0  4680.1     0.1       0  4854.8    0.16       0
  4996.9    0.07       0  5002.9    0.16       0  5051.4    0.05       0
Bank Sta=4996.9,5002.9
Exp/Cntr=0.3,0.1