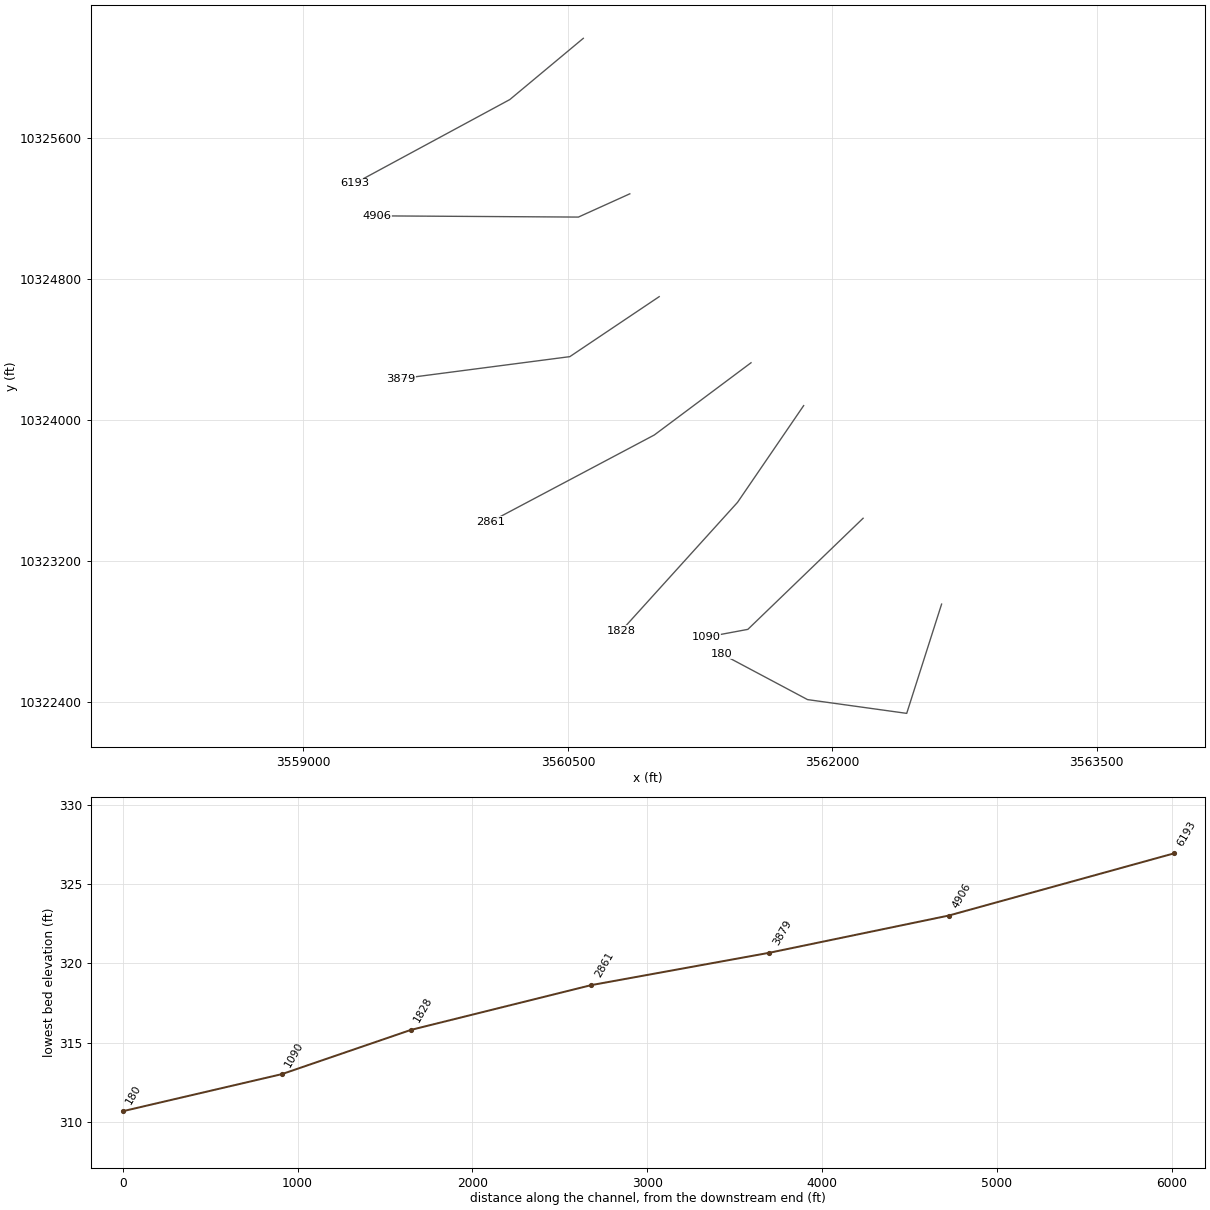
HEC-RAS study SNAKE BRANCH.prj: SNAKE BRANCH Base Level Engineering

--- SNAKE BRANCH.g01 (geometry) --- (continued)

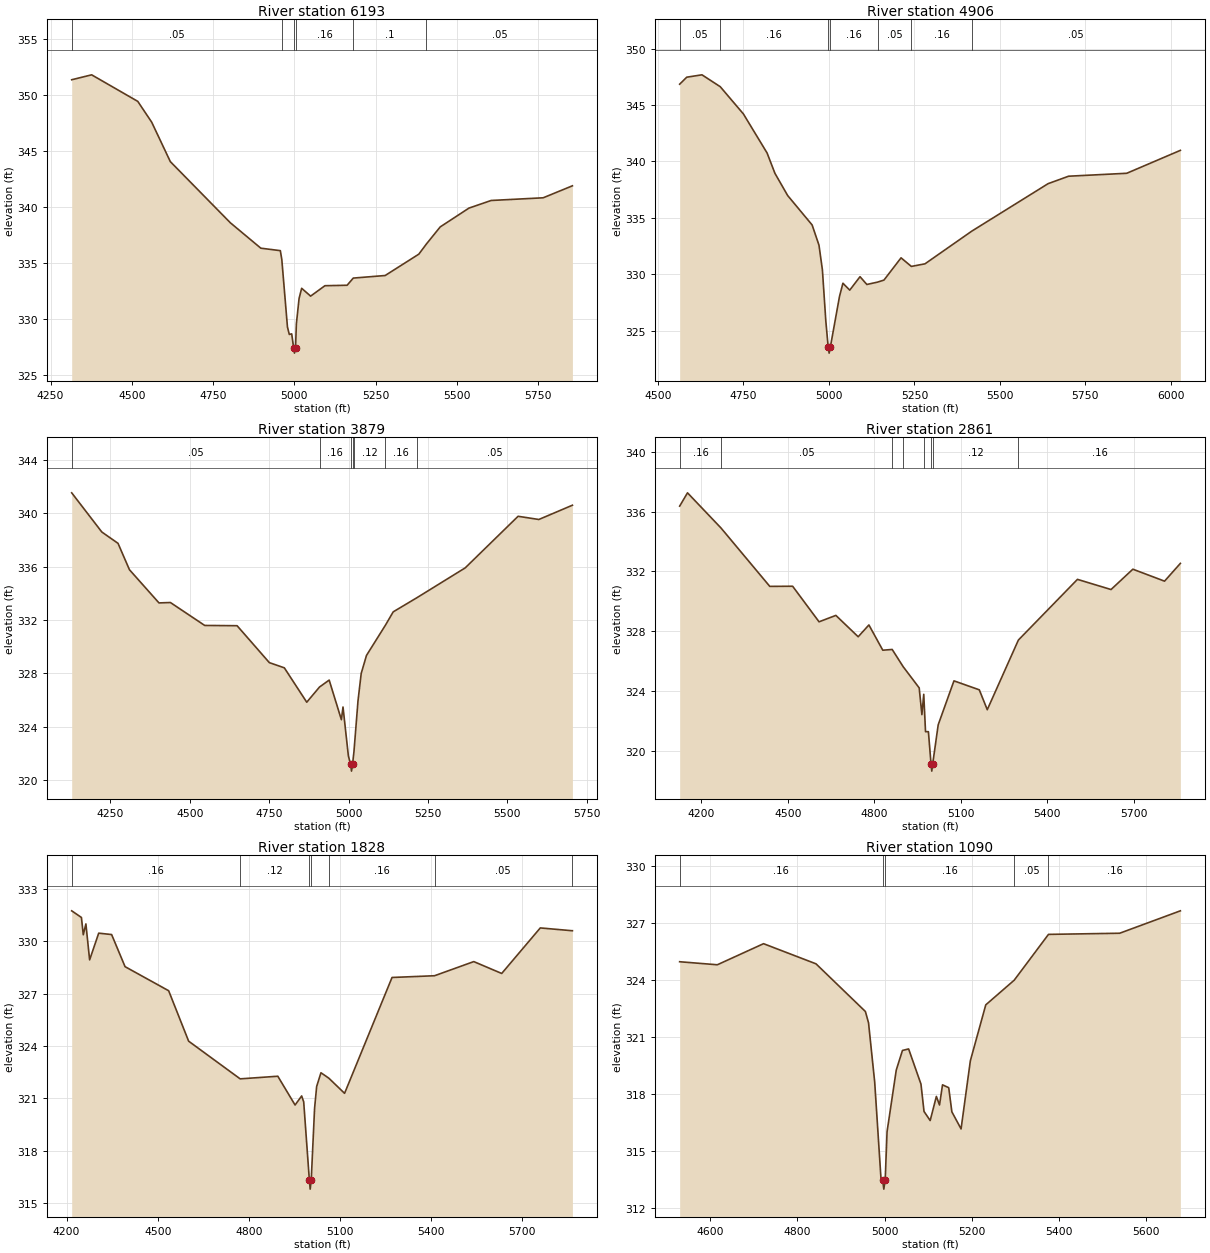
Type RM Length L Ch R = 1,6193,1287,1287,1287
BEGIN DESCRIPTION:
SNAKE BRANCH 10.0
END DESCRIPTION:
XS GIS Cut Line= 3
      3560587.16     10326163.52      3560170.48     10325816.28
      3559292.12     10325341.65
#Sta/Elev= 30
  4315.1  351.35  4376.5  351.79  4518.4  349.42  4561.3  347.56  4618.6  344.04
  4803.3  338.58  4897.1  336.31  4957.1  336.09  4961.6  335.32  4979.0  329.28
  4984.7  328.61  4992.1  328.66  4997.9  327.44  5000.6  326.94  5003.9  327.44
  5006.5  329.57  5014.8  331.82  5022.7  332.73  5050.3  332.03  5094.4  332.96
  5162.6  333.00  5181.5  333.64  5279.7  333.87  5383.4  335.78  5406.2  336.67
  5449.1  338.21  5537.6  339.89  5605.8  340.57  5766.0  340.81  5855.9  341.88
#Mann=6,-1,0
  4315.1    0.05       0  4961.6    0.16       0  4997.9    0.07       0
  5003.9    0.16       0  5181.5     0.1       0  5406.2    0.05       0
Bank Sta=4997.9,5003.9
Exp/Cntr=0.3,0.1

Type RM Length L Ch R = 1,4906,1027,1027,1027
BEGIN DESCRIPTION:
SNAKE BRANCH 9.0
END DESCRIPTION:
XS GIS Cut Line= 3
      3560851.01     10325281.55      3560559.37     10325149.62
      3559415.28     10325156.55
#Sta/Elev= 30
  4563.5  346.84  4584.2  347.46  4628.8  347.67  4682.1  346.62  4749.8  344.21
  4819.1  340.75  4842.2  338.94  4879.3  336.98  4950.9  334.37  4970.9  332.58
  4980.9  330.40  4990.9  325.86  4997.9  323.52  5000.6  323.02  5003.9  323.52
  5030.9  328.04  5040.9  329.21  5060.9  328.60  5090.9  329.79  5110.9  329.10
  5142.2  329.31  5160.9  329.49  5210.9  331.46  5241.0  330.70  5280.9  330.93
  5418.0  333.83  5640.9  338.03  5700.9  338.69  5870.9  338.95  6027.7  340.98
#Mann=7,-1,0
  4563.5    0.05       0  4682.1    0.16       0  4997.9    0.07       0
  5003.9    0.16       0  5142.2    0.05       0  5241.0    0.16       0
  5418.0    0.05       0
Bank Sta=4997.9,5003.9
Exp/Cntr=0.3,0.1

Type RM Length L Ch R = 1,3879,1018,1018,1018
BEGIN DESCRIPTION:
SNAKE BRANCH 7.0
END DESCRIPTION:
XS GIS Cut Line= 3
      3561017.73     10324698.25      3560510.76     10324357.95
      3559552.47     10324232.96
#Sta/Elev= 30
  4128.1  341.55  4223.0  338.61  4274.0  337.76  4310.0  335.78  4403.0  333.29
  4439.0  333.32  4547.0  331.60  4649.0  331.58  4750.6  328.81  4797.8  328.42
  4868.4  325.84  4908.6  326.98  4939.0  327.50  4977.5  324.53  4982.6  325.48
  4999.5  321.81  5006.6  321.17  5009.4  320.67  5012.6  321.17  5017.1  322.14
  5029.8  325.94  5039.9  328.00  5056.5  329.35  5116.2  331.62  5140.7  332.62
  5215.3  333.68  5367.5  335.92  5534.0  339.79  5599.4  339.55  5705.1  340.62
#Mann=7,-1,0
  4128.1    0.05       0  4908.6    0.16       0  5006.6    0.07       0
  5012.6    0.16       0  5017.1    0.12       0  5116.2    0.16       0
  5215.3    0.05       0
Bank Sta=5006.6,5012.6
Exp/Cntr=0.3,0.1

Type RM Length L Ch R = 1,2861,1033,1033,1033
BEGIN DESCRIPTION:
SNAKE BRANCH 5.0
END DESCRIPTION:
XS GIS Cut Line= 3
      3561538.55     10324323.23      3560989.93     10323913.51
      3560059.41     10323420.47
#Sta/Elev= 30
  4124.8  336.36  4152.0  337.25  4268.6  334.89  4437.6  330.99  4516.9  331.00
  4608.6  328.62  4666.9  329.05  4744.4  327.62  4781.6  328.41  4829.8  326.72
  4862.4  326.77  4900.4  325.62  4956.1  324.20  4965.5  322.41  4971.9  323.77
  4978.1  321.27  4988.1  321.27  4997.1  319.13  4999.8  318.63  5003.1  319.13
  5022.1  321.73  5076.8  324.67  5164.7  324.07  5192.4  322.74  5300.4  327.40
  5505.4  331.46  5621.9  330.78  5697.7  332.14  5807.7  331.34  5862.6  332.53
#Mann=8,-1,0
  4124.8    0.16       0  4268.6    0.05       0  4862.4     0.1       0
  4900.4    0.05       0  4971.9    0.12       0  4997.1    0.07       0
  5003.1    0.12       0  5300.4    0.16       0
Bank Sta=4997.1,5003.1
Exp/Cntr=0.3,0.1

Type RM Length L Ch R = 1,1828,738,738,738
BEGIN DESCRIPTION:
SNAKE BRANCH 4.0
END DESCRIPTION:
XS GIS Cut Line= 3
      3561837.14     10324080.16      3561462.15     10323531.56
      3560802.45     10322802.42
#Sta/Elev= 30
  4216.9  331.75  4248.9  331.37  4255.0  330.38  4263.6  331.00  4275.9  328.94
  4305.8  330.47  4348.3  330.39  4392.5  328.55  4536.0  327.17  4601.7  324.28
  4771.3  322.12  4895.2  322.27  4952.0  320.62  4973.7  321.14  4980.4  320.80
  4999.1  316.30  5001.8  315.80  5005.1  316.30  5016.2  320.43  5023.0  321.68
  5037.2  322.47  5063.0  322.16  5114.9  321.29  5271.1  327.93  5411.0  328.03
  5540.1  328.84  5632.0  328.16  5759.0  330.77  5863.4  330.61  5864.7  330.61
#Mann=7,-1,0
  4216.9    0.16       0  4771.3    0.12       0  4999.1    0.07       0
  5005.1    0.12       0  5063.0    0.16       0  5411.0    0.05       0
  5863.4    0.16       0
Bank Sta=4999.1,5005.1
Exp/Cntr=0.3,0.1

Type RM Length L Ch R = 1,1090,910,910,910
BEGIN DESCRIPTION:
Mapping XS 6b17d239
END DESCRIPTION:
XS GIS Cut Line= 3
      3562174.32     10323441.21      3561520.66     10322810.99
      3561285.42     10322767.05
#Sta/Elev= 30
  4530.5  324.98  4616.8  324.82  4722.7  325.93  4842.9  324.87  4956.1  322.36
  4963.3  321.76  4977.4  318.64  4991.6  313.63  4995.5  313.51  4998.3  313.01
  5001.5  313.51  5005.7  316.03  5026.8  319.28  5041.0  320.31  5055.1  320.39
  5083.4  318.54  5090.4  317.10  5104.5  316.62  5118.7  317.89  5125.9  317.44
  5132.8  318.50  5147.0  318.35  5154.2  317.08  5175.3  316.18  5196.6  319.77
  5231.9  322.71  5297.1  324.01  5375.6  326.42  5538.7  326.48  5677.8  327.66
#Mann=5,-1,0
  4530.5    0.16       0  4995.5    0.07       0  5001.5    0.16       0
  5297.1    0.05       0  5375.6    0.16       0
Bank Sta=4995.5,5001.5
Exp/Cntr=0.3,0.1

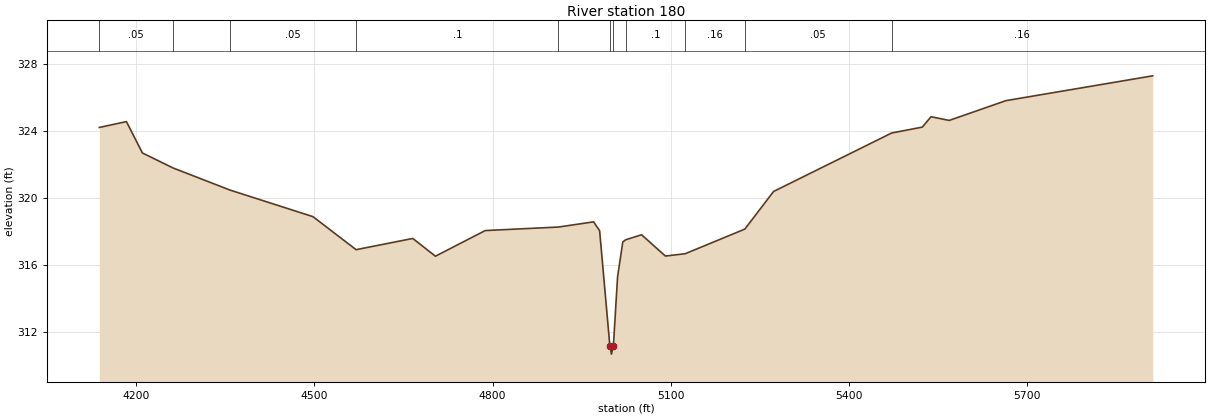
Type RM Length L Ch R = 1,180,0,0,0
BEGIN DESCRIPTION:
SNAKE BRANCH 1.0
END DESCRIPTION:
XS GIS Cut Line= 4
      3562619.62     10322954.24      3562421.70     10322334.43
      3561859.20     10322412.55      3561369.60     10322672.98
#Sta/Elev= 30
  4138.2  324.19  4183.8  324.54  4210.7  322.67  4261.9  321.78  4357.8  320.46
  4497.8  318.87  4570.4  316.90  4665.8  317.57  4703.9  316.51  4787.7  318.04
  4910.9  318.25  4970.2  318.56  4980.3  318.03  4997.5  311.17  5000.2  310.67
  5003.5  311.17  5010.5  315.28  5019.3  317.36  5024.2  317.49  5050.9  317.79
  5091.0  316.52  5124.5  316.66  5224.8  318.13  5273.0  320.37  5471.9  323.86
  5523.4  324.21  5538.1  324.83  5568.7  324.61  5664.3  325.79  5911.3  327.27
#Mann=11,-1,0
  4138.2    0.05       0  4261.9     0.1       0  4357.8    0.05       0
  4570.4     0.1       0  4910.9    0.12       0  4997.5    0.07       0
  5003.5    0.12       0  5024.2     0.1       0  5124.5    0.16       0
  5224.8    0.05       0  5471.9    0.16       0
Bank Sta=4997.5,5003.5
Exp/Cntr=0.3,0.1

Chan Stop Cuts=-1