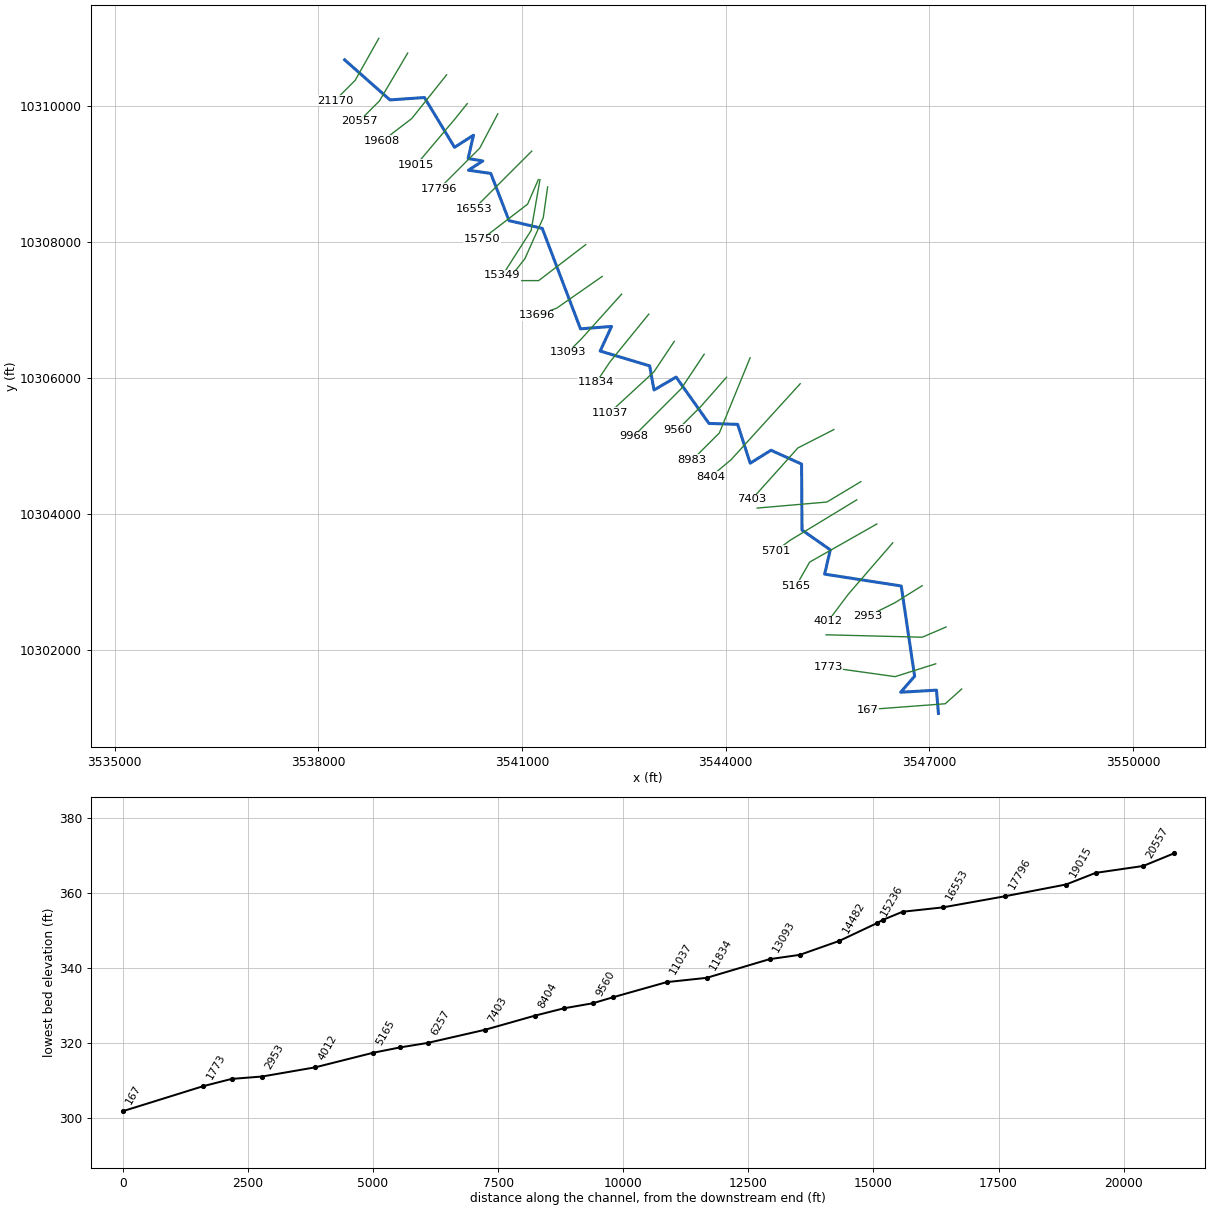
--- SPARKS BRANCH.prj (project) ---

Proj Title=SPARKS BRANCH Base Level Engineering
Current Plan=p01
Default Exp/Contr=0.3,0.1
English Units
Geom File=g01
Flow File=f01
Plan File=p01
Y Axis Title=Elevation
X Axis Title(PF)=Main Channel Distance
X Axis Title(XS)=Station
BEGIN DESCRIPTION:
SPARKS BRANCH
END DESCRIPTION:
DSS Export Rating Curves= 0
DSS Export Rating Curve Sorted= 0
DSS Export Volume Flow Curves= 0
DXF OffsetX= 0
DXF OffsetY= 0
DXF ScaleX= 1
DXF ScaleY= 10

--- SPARKS BRANCH.p01 (plan) ---

Plan Title=Multiple Run
Short Identifier=Multiple
Geom File=g01
Flow File=f01
Subcritical Flow
K Sum by GR= 0
Std Step Tol= 0.01
Critical Tol= 0.01
Num of Std Step Trials= 20
Max Error Tol= 0.3
Flow Tol Ratio= 0.001
Split Flow NTrial= 30
Split Flow Tol= 0.02
Split Flow Ratio= 0.02
Log Output Level= 0
Friction Slope Method= 1
Unsteady Friction Slope Method= 2
Unsteady Bridges Friction Slope Method= 1
Parabolic Critical Depth
Global Vel Dist=  1 , 1 , 1
Global Log Level= 0
CheckData=True
Encroach Param= -1, 0, 0, 0
BEGIN DESCRIPTION:
Multiple Run
END DESCRIPTION:

--- SPARKS BRANCH.f01 (steady flow) ---

Flow Title=Multiple
Number of Profiles=7
Profile Names=10-year,25-year,50-year,1pct_min,100-year,1pct_plu,500-year
River Rch & RM= SPARKS BRANCH,Reach-1,21170
     484     647     778     686     928    1255    1323
River Rch & RM= SPARKS BRANCH,Reach-1,11834
     743    1012    1232    1098    1484    2008    2162
Boundary for River Rch & Prof#=SPARKS BRANCH,Reach-1,1
Up Type=0
Dn Type=3
Dn Slope=0.005
Boundary for River Rch & Prof#=SPARKS BRANCH,Reach-1,2
Up Type=0
Dn Type=3
Dn Slope=0.005
Boundary for River Rch & Prof#=SPARKS BRANCH,Reach-1,3
Up Type=0
Dn Type=3
Dn Slope=0.005
Boundary for River Rch & Prof#=SPARKS BRANCH,Reach-1,4
Up Type=0
Dn Type=3
Dn Slope=0.005
Boundary for River Rch & Prof#=SPARKS BRANCH,Reach-1,5
Up Type=0
Dn Type=3
Dn Slope=0.005
Boundary for River Rch & Prof#=SPARKS BRANCH,Reach-1,6
Up Type=0
Dn Type=3
Dn Slope=0.005
Boundary for River Rch & Prof#=SPARKS BRANCH,Reach-1,7
Up Type=0
Dn Type=3
Dn Slope=0.005

--- SPARKS BRANCH.g01 (geometry) ---

Geom Title=Existing Conditions
Program Version=4.10

River Reach=SPARKS BRANCH   ,Reach-1
Reach XY= 30
      3538386.54     10310686.96      3539053.75     10310096.76
      3539562.18     10310131.76      3540005.26     10309398.65
      3540283.72     10309576.57      3540205.11     10309232.66
      3540421.64     10309198.15      3540210.18      10309061.7
      3540539.34     10309013.26      3540807.92     10308318.81
      3541296.81     10308204.92      3541860.25     10306725.46
      3542318.18     10306760.48      3542150.09     10306398.36
      3542879.14     10306179.73      3542943.18     10305824.31
       3543268.4     10306014.46      3543752.33     10305331.91
      3544174.74     10305318.15      3544359.84     10304746.35
      3544666.29      10304936.8      3545116.26     10304733.14
      3545122.79     10303761.64      3545538.84     10303470.41
      3545456.08      10303112.4      3546584.11     10302938.03
      3546781.34     10301608.67      3546575.61     10301372.91
      3547103.15     10301403.84      3547132.11     10301061.64

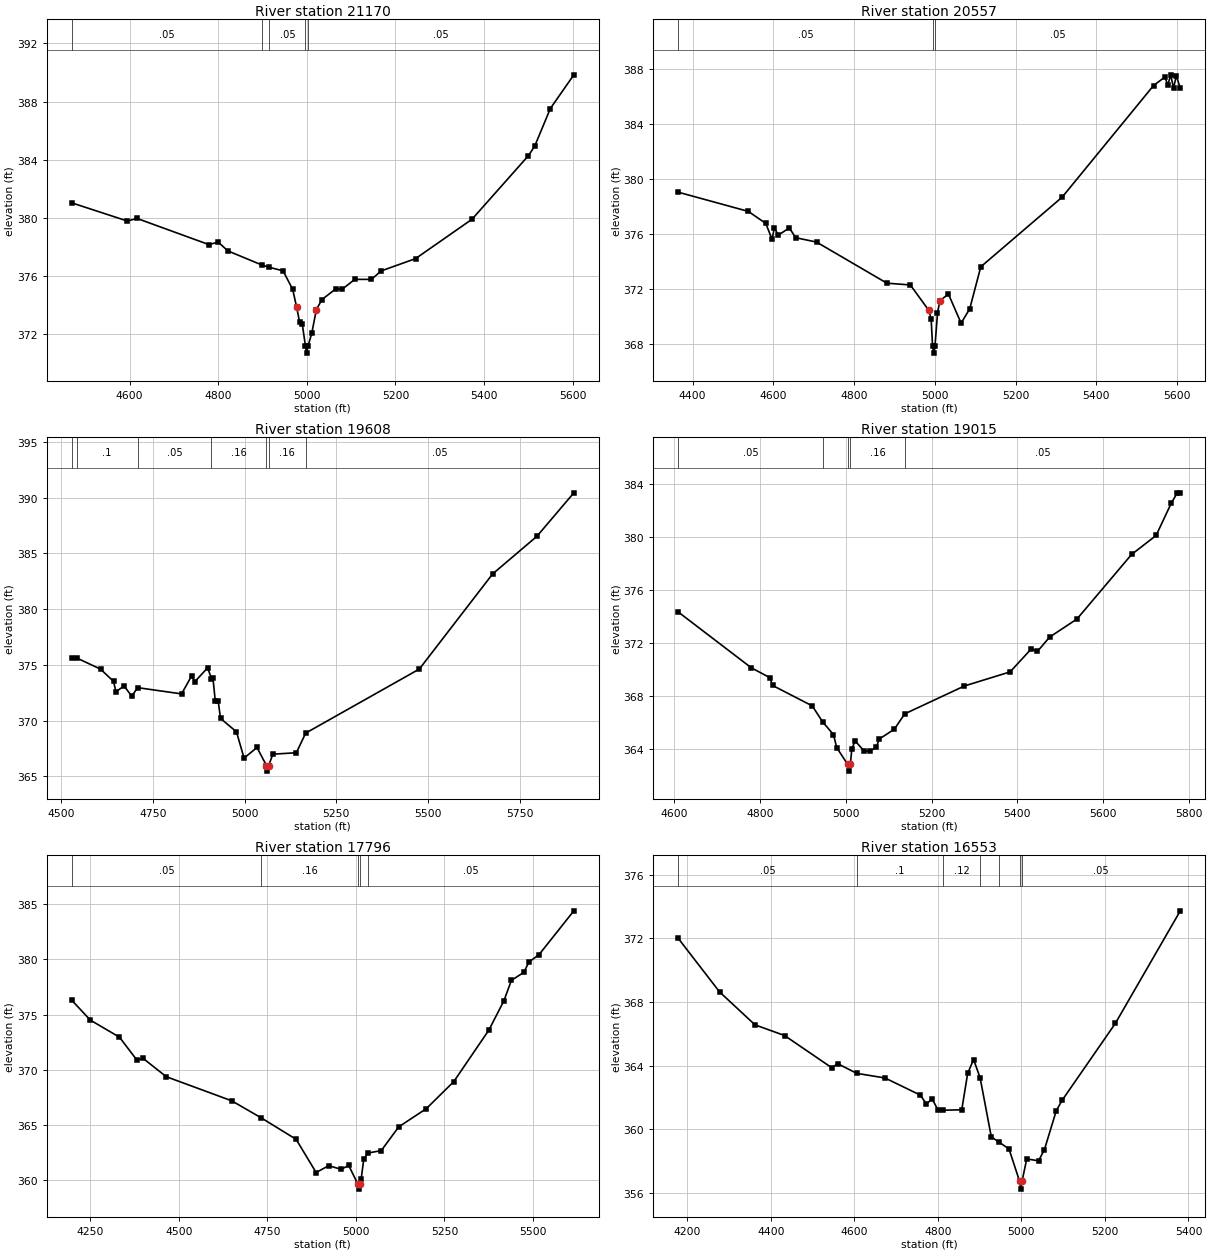
Type RM Length L Ch R = 1 ,21170   ,613,613,613
BEGIN DESCRIPTION:
SPARKS BRANCH 40.0
END DESCRIPTION:
XS GIS Cut Line= 3
      3538889.85     10311003.64      3538542.11     10310385.39
      3538242.74     10310086.03
#Sta/Elev= 30
  4469.7  381.02  4595.1  379.77  4616.7  379.95  4778.7  378.15  4800.3  378.31
    4822  377.71  4898.7  376.74  4915.5  376.58  4946.3  376.34    4968  375.07
  4976.8  373.87  4983.9  372.78  4989.6   372.7  4996.8  371.17  4999.5  370.67
  5002.8  371.17  5011.3  372.06  5021.5  373.67  5034.2  374.36  5064.9  375.09
  5080.1  375.08  5108.2  375.75  5145.8  375.75  5167.5  376.33  5245.3  377.18
  5372.6  379.89  5499.9  384.27    5514  384.92  5549.4  387.52  5602.4  389.84
#Mann= 5 ,-1 , 0
  4469.7     .05       0  4898.7     .16       0  4915.5     .05       0
  4996.8     .03       0  5002.8     .05       0
Bank Sta=4976.8,5021.5
XS Rating Curve= 0 ,0
Exp/Cntr=0.3,0.1

Type RM Length L Ch R = 1 ,20557   ,949,949,949
BEGIN DESCRIPTION:
SPARKS BRANCH 39.0
END DESCRIPTION:
XS GIS Cut Line= 3
      3539315.22     10310786.67       3538898.7     10310081.23
       3538598.7     10309781.22
#Sta/Elev= 30
  4364.5  379.02  4538.3  377.62  4581.2  376.75  4596.8   375.6  4602.6  376.41
  4612.4   375.9  4639.7  376.42  4655.3  375.71  4707.1  375.39  4881.3   372.4
  4939.4  372.27  4985.1  370.42  4990.9  369.79  4994.4  367.81  4997.2  367.31
  5000.4  367.81  5006.6   370.2  5012.4  371.13  5033.8   371.6  5065.1  369.49
  5086.5  370.54  5113.8  373.59  5315.4  378.66  5541.7  386.78  5569.9   387.4
    5577  386.81  5584.1  387.56  5591.2   386.6  5598.2  387.49    5608  386.57
#Mann= 3 ,-1 , 0
  4364.5     .05       0  4994.4     .03       0  5000.4     .05       0
Bank Sta=4985.1,5012.4
XS Rating Curve= 0 ,0
Exp/Cntr=0.3,0.1

Type RM Length L Ch R = 1 ,19608   ,593,593,593
BEGIN DESCRIPTION:
SPARKS BRANCH 37.0
END DESCRIPTION:
XS GIS Cut Line= 3
      3539888.12     10310465.47      3539375.97     10309823.11
      3538942.13     10309491.66
#Sta/Elev= 30
  4529.5  375.64  4542.4  375.63    4608  374.62  4643.3  373.52  4649.7   372.6
  4672.1  373.11  4692.9  372.19  4708.7  372.96  4828.6   372.4  4856.2  374.03
  4864.3  373.48  4899.5  374.74    4910  373.78  4913.9  373.86  4920.3  371.79
  4928.3  371.75  4934.7   370.2    4978     369  4998.8  366.64    5034  367.59
  5059.8  365.97  5062.6  365.47  5065.8  365.97  5077.2  366.99  5141.3  367.12
  5166.5  368.88  5476.2  374.63  5675.7  383.16  5796.4  386.54    5897  390.44
#Mann= 7 ,-1 , 0
  4529.5     .05       0  4542.4      .1       0  4708.7     .05       0
    4910     .16       0  5059.8     .07       0  5065.8     .16       0
  5166.5     .05       0
Bank Sta=5059.8,5065.8
XS Rating Curve= 0 ,0
Exp/Cntr=0.3,0.1

Type RM Length L Ch R = 1 ,19015   ,1219,1219,1219
BEGIN DESCRIPTION:
SPARKS BRANCH 35.0
END DESCRIPTION:
XS GIS Cut Line= 3
      3540192.13     10310041.67      3540009.66     10309814.43
      3539442.13     10309141.67
#Sta/Elev= 30
  4608.9  374.34  4779.4  370.14  4822.5   369.4    4829  368.81  4921.7  367.27
  4945.8  366.07  4971.1  365.11  4978.9  364.12  5004.5  362.86  5007.2  362.36
  5010.5  362.86    5014  364.04  5021.7  364.64  5042.6  363.87  5056.9  363.88
  5071.2  364.16  5077.7  364.77  5113.3  365.52  5137.3  366.67  5276.7  368.77
  5383.3  369.83  5432.7  371.56    5447  371.37  5475.6  372.45  5539.3  373.81
  5666.8  378.67    5724   380.1  5759.1  382.51  5773.4  383.31  5780.5   383.3
#Mann= 5 ,-1 , 0
  4608.9     .05       0  4945.8     .16       0  5004.5     .07       0
  5010.5     .16       0  5137.3     .05       0
Bank Sta=5004.5,5010.5
XS Rating Curve= 0 ,0
Exp/Cntr=0.3,0.1

Type RM Length L Ch R = 1 ,17796   ,1243,1243,1243
BEGIN DESCRIPTION:
SPARKS BRANCH 33.0
END DESCRIPTION:
XS GIS Cut Line= 3
      3540642.09     10309891.61      3540376.83     10309387.13
      3539776.97     10308787.27
#Sta/Elev= 30
  4197.2  376.29  4249.4   374.5    4332  372.95  4381.7  370.86  4398.1  371.05
  4464.2  369.38  4649.1   367.2  4732.5  365.66    4831  363.72  4887.5  360.72
  4922.9  361.34  4958.2  361.01  4979.5  361.36  5004.7  359.72  5007.5  359.22
  5010.7  359.72  5014.8  360.15  5021.9   361.9  5033.6  362.48  5071.4   362.7
  5120.9  364.85  5198.7  366.49  5276.4  368.94  5375.4  373.59  5417.9  376.24
  5439.1  378.09  5474.4  378.81  5488.6  379.75  5516.9   380.4  5615.5  384.37
#Mann= 5 ,-1 , 0
  4197.2     .05       0  4732.5     .16       0  5004.7     .07       0
  5010.7     .16       0  5033.6     .05       0
Bank Sta=5004.7,5010.7
XS Rating Curve= 0 ,0
Exp/Cntr=0.3,0.1

Type RM Length L Ch R = 1 ,16553   ,803,803,803
BEGIN DESCRIPTION:
SPARKS BRANCH 31.0
END DESCRIPTION:
XS GIS Cut Line= 3
       3541142.1     10309341.63      3540542.11     10308741.64
      3540292.08     10308491.62
#Sta/Elev= 30
  4178.4  372.01  4277.4  368.64  4362.2  366.57  4432.9   365.9  4546.1  363.87
  4560.2  364.13  4605.7  363.52  4673.4  363.23  4758.2  362.15  4772.4   361.6
  4786.5  361.91  4800.6   361.2  4811.6   361.2  4857.2  361.23  4871.4  363.52
  4885.5  364.39  4901.2  363.24  4927.9  359.53    4946   359.2  4970.3  358.77
  4995.6  356.74  4998.4  356.24  5001.6  356.74  5012.8  358.14  5041.1  358.02
  5055.2  358.73  5083.5  361.17  5097.6  361.83  5224.9  366.66  5380.5  373.74
#Mann= 7 ,-1 , 0
  4178.4     .05       0  4605.7      .1       0  4811.6     .12       0
  4901.2      .1       0    4946     .05       0  4995.6     .03       0
  5001.6     .05       0
Bank Sta=4995.6,5001.6
XS Rating Curve= 0 ,0
Exp/Cntr=0.3,0.1

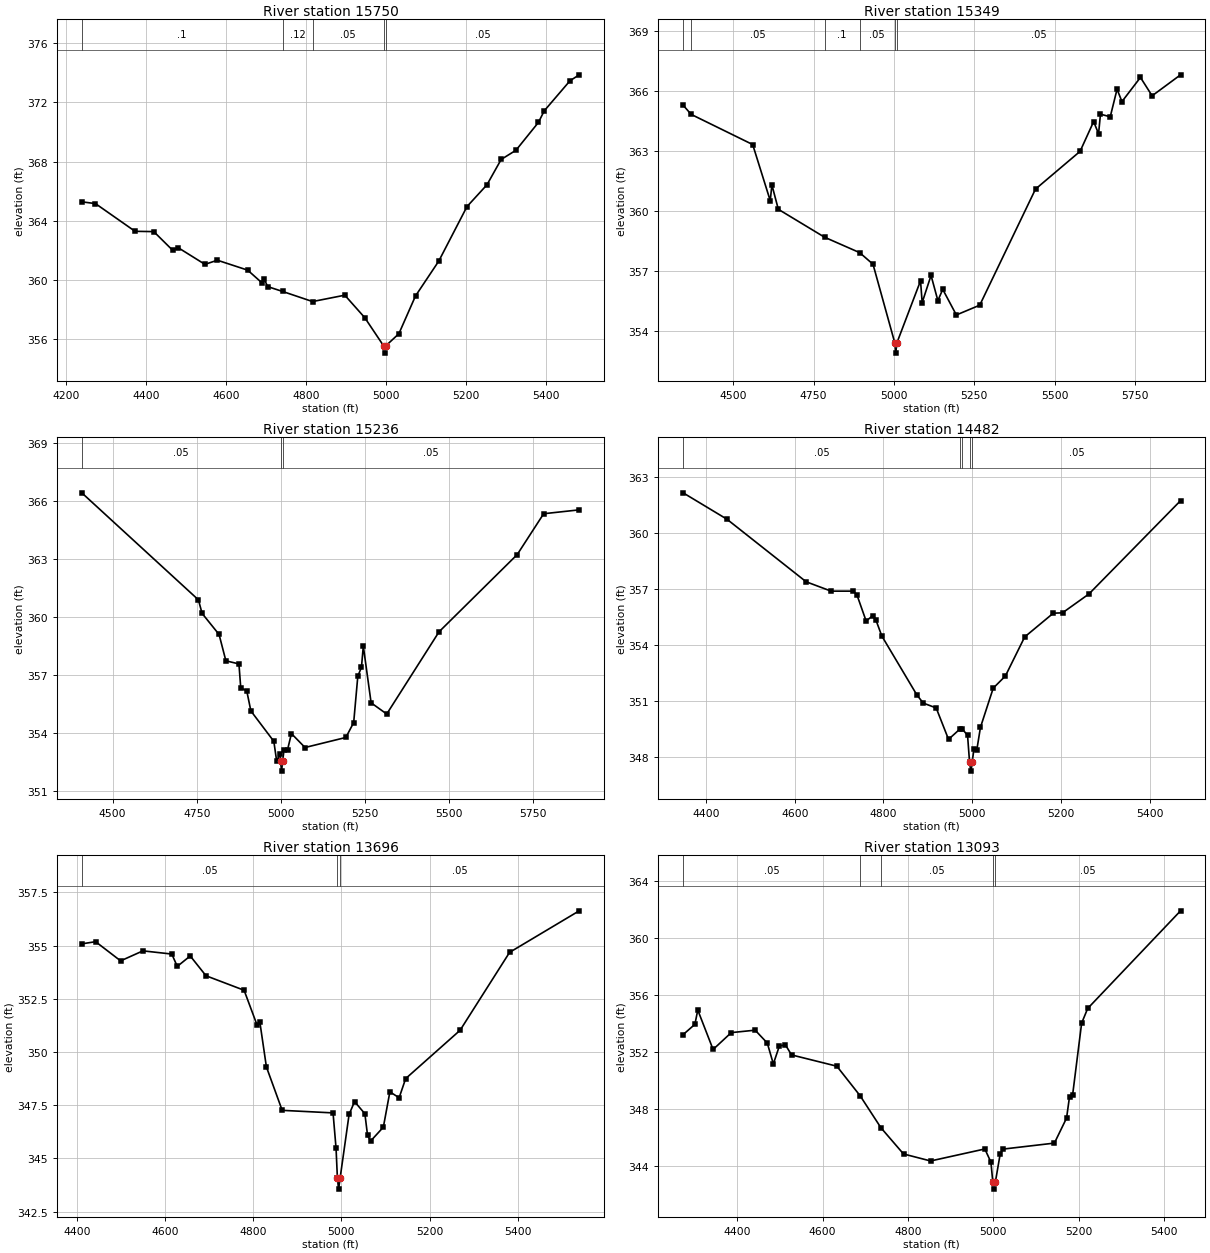
Type RM Length L Ch R = 1 ,15750   ,401,401,401
BEGIN DESCRIPTION:
SPARKS BRANCH 30.0
END DESCRIPTION:
XS GIS Cut Line= 3
      3541238.97     10308922.17      3541080.99     10308561.07
      3540407.39     10308043.71
#Sta/Elev= 30
    4240  365.29  4274.2  365.17  4373.2   363.3    4420  363.28  4466.8  362.03
  4480.7   362.2  4547.9  361.07  4578.9  361.35  4654.7  360.68  4690.1  359.83
  4696.4  360.06  4704.6  359.57  4742.2  359.24  4816.9  358.56  4897.5  358.99
  4947.5  357.47  4994.3  355.58  4997.1  355.08  5000.3  355.58  5032.7  356.39
  5074.3  358.94  5132.4  361.29    5203  364.97  5252.9  366.44  5288.4  368.15
  5325.4  368.77  5381.6  370.65  5396.1  371.43  5460.5  373.46  5483.5  373.86
#Mann= 5 ,-1 , 0
    4240      .1       0  4742.2     .12       0  4816.9     .05       0
  4994.3     .03       0  5000.3     .05       0
Bank Sta=4994.3,5000.3
XS Rating Curve= 0 ,0
Exp/Cntr=0.3,0.1

Type RM Length L Ch R = 1 ,15349   ,113,113,113
BEGIN DESCRIPTION:
Mapping XS f36bdecd
END DESCRIPTION:
XS GIS Cut Line= 3
      3541263.49     10308923.32      3541133.29     10308173.31
      3540709.68     10307511.86
#Sta/Elev= 30
  4344.5  365.28  4369.5  364.82  4560.8  363.31  4615.4   360.5  4620.5  361.29
  4640.5  360.07  4784.5  358.67  4893.4   357.9  4934.9  357.32  5002.9  353.37
  5005.7  352.87  5008.9  353.37  5082.7  356.49  5087.8   355.4  5115.4  356.76
  5136.6   355.5  5151.8  356.06  5194.1  354.78  5266.8  355.27  5440.2  361.08
  5578.8  362.97    5621  364.46  5636.3  363.85  5642.2  364.83  5672.6   364.7
  5693.8  366.08    5709  365.46  5766.5  366.67  5802.8  365.75  5891.2   366.8
#Mann= 6 ,-1 , 0
  4344.5      .1       0  4369.5     .05       0  4784.5      .1       0
  4893.4     .05       0  5002.9     .04       0  5008.9     .05       0
Bank Sta=5002.9,5008.9
XS Rating Curve= 0 ,0
Exp/Cntr=0.3,0.1

Type RM Length L Ch R = 1 ,15236   ,754,754,754
BEGIN DESCRIPTION:
SPARKS BRANCH 29.0
END DESCRIPTION:
XS GIS Cut Line= 4
      3541376.34     10308815.64       3541312.1     10308362.55
      3541041.27     10307758.38      3540819.03      10307477.1
#Sta/Elev= 30
  4408.3   366.4  4754.9  360.87  4765.8  360.17  4816.3  359.08  4836.5  357.72
  4875.3  357.56  4880.7  356.32  4898.5  356.17  4910.8  355.13    4979  353.56
  4987.5  352.53  4996.7  352.93  4999.1  352.52  5001.9  352.02  5005.1  352.52
  5009.4  353.13  5019.8  353.13  5031.3  353.96  5071.7  353.24  5193.1  353.76
  5216.3  354.53  5228.6  356.93  5239.4  357.38  5244.9  358.48  5268.1  355.55
  5314.5  354.97    5470  359.22  5702.3  363.21  5780.9  365.32  5886.5  365.52
#Mann= 3 ,-1 , 0
  4408.3     .05       0  4999.1     .04       0  5005.1     .05       0
Bank Sta=4999.1,5005.1
XS Rating Curve= 0 ,0
Exp/Cntr=0.3,0.1

Type RM Length L Ch R = 1 ,14482   ,786,786,786
BEGIN DESCRIPTION:
SPARKS BRANCH 27.0
END DESCRIPTION:
XS GIS Cut Line= 3
      3541936.77      10307965.5      3541244.54     10307435.39
      3540995.83     10307435.39
#Sta/Elev= 30
  4348.6  362.16  4447.2  360.75  4625.8   357.4    4682   356.9  4732.3   356.9
    4740  356.71  4760.9   355.3  4775.4  355.58  4782.7  355.37  4796.2   354.5
  4875.1  351.35  4889.6  350.91  4918.7  350.65  4946.5  348.97  4973.1  349.54
  4977.4  349.53  4989.4  349.18  4993.8  347.77  4996.6  347.27  4999.8  347.77
  5003.9  348.46  5010.2   348.4  5018.4  349.61  5047.2  351.71  5074.6  352.36
  5118.1  354.45  5182.5  355.72  5203.3  355.74  5262.9  356.75  5469.2  361.74
#Mann= 5 ,-1 , 0
  4348.6     .05       0  4973.1     .12       0  4977.4     .05       0
  4993.8     .03       0  4999.8     .05       0
Bank Sta=4993.8,4999.8
XS Rating Curve= 0 ,0
Exp/Cntr=0.3,0.1

Type RM Length L Ch R = 1 ,13696   ,603,603,603
BEGIN DESCRIPTION:
SPARKS BRANCH 25.0
END DESCRIPTION:
XS GIS Cut Line= 3
       3542179.8     10307496.73      3541507.73     10307028.45
      3541216.64     10306923.95
#Sta/Elev= 30
  4411.1  355.08  4442.5  355.18  4499.2  354.28  4549.8  354.75  4615.3   354.6
  4627.7  354.02  4657.1  354.51  4692.9  353.58  4779.3   352.9    4809  351.25
  4815.1   351.4  4829.9   349.3  4865.7  347.26  4981.1  347.14  4987.9  345.48
    4991  344.06  4993.7  343.56    4997  344.06  5017.5  347.07  5029.9  347.67
  5053.3   347.1  5059.4  346.08  5066.4  345.82  5095.2  346.47    5110  348.13
    5131  347.85  5145.8  348.75  5269.3  351.02  5381.6  354.68  5539.5  356.63
#Mann= 3 ,-1 , 0
  4411.1     .05       0    4991     .03       0    4997     .05       0
Bank Sta=4991,4997
XS Rating Curve= 0 ,0
Exp/Cntr=0.3,0.1

Type RM Length L Ch R = 1 ,13093   ,1259,1259,1259
BEGIN DESCRIPTION:
SPARKS BRANCH 24.0
END DESCRIPTION:
XS GIS Cut Line= 3
      3542466.27     10307236.33      3541875.09      10306578.8
      3541676.12     10306379.83
#Sta/Elev= 30
  4273.2  353.22  4300.8  353.94  4307.5  354.94  4343.4  352.18    4386  353.36
    4442  353.53  4470.4  352.63  4484.6  351.17  4498.8  352.43    4513   352.5
  4527.2   351.8  4633.4  351.01    4688  348.94  4736.8   346.7  4789.6  344.87
  4853.1  344.38  4980.2  345.22  4994.4   344.3  4998.9  342.91  5001.6  342.41
  5004.9  342.91  5016.1  344.86  5022.8  345.21  5143.2  345.63  5171.7  347.38
  5178.7  348.89  5185.8  348.98    5207  354.02  5221.2  355.05  5438.8  361.88
#Mann= 5 ,-1 , 0
  4273.2     .05       0    4688      .1       0  4736.8     .05       0
  4998.9    .035       0  5004.9     .05       0
Bank Sta=4998.9,5004.9
XS Rating Curve= 0 ,0
Exp/Cntr=0.3,0.1

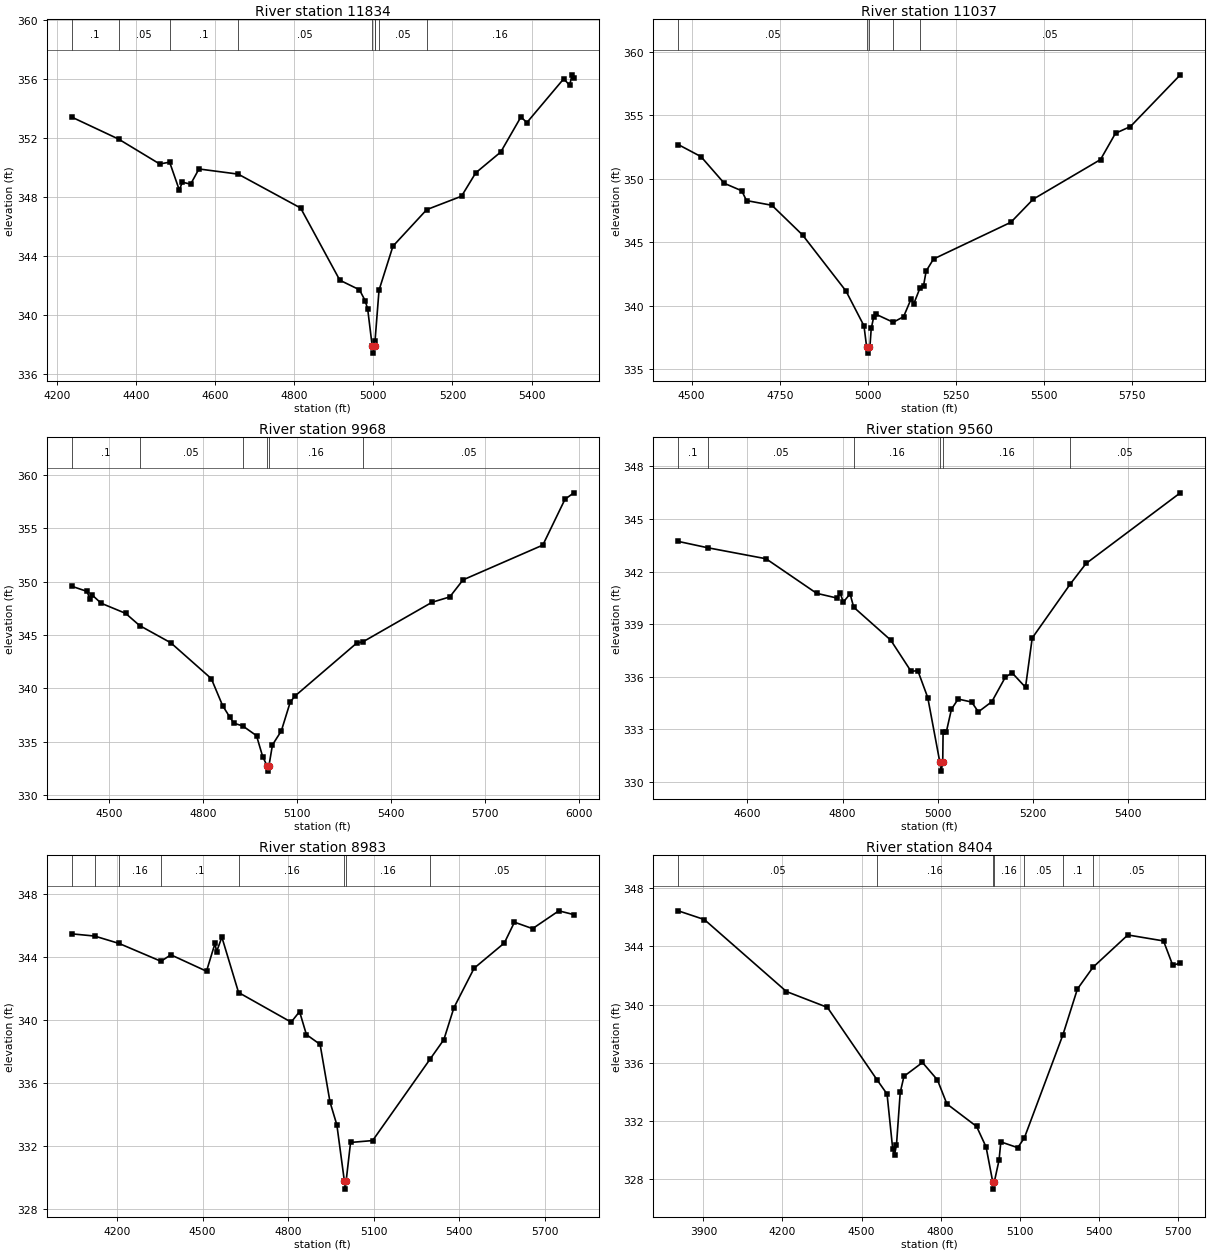
Type RM Length L Ch R = 1 ,11834   ,797,797,797
BEGIN DESCRIPTION:
SPARKS BRANCH 22.0
END DESCRIPTION:
XS GIS Cut Line= 3
      3542865.54     10306941.15      3542292.11     10306235.39
       3542092.5     10305935.98
#Sta/Elev= 30
  4237.6  353.43  4355.8  351.94  4459.8  350.25    4485  350.37  4509.3  348.49
  4517.3  349.01  4538.1  348.88  4559.1  349.91  4658.3  349.56  4816.1  347.26
  4915.2  342.36  4964.8  341.71  4979.1  340.98  4985.6  340.41    4997  337.91
  4999.7  337.41    5003  337.91  5004.1   338.2  5014.3  341.68  5049.5  344.67
  5134.9  347.15  5222.8  348.06  5258.9  349.65    5322  351.06    5373  353.44
  5388.1  353.06  5481.2  356.03  5496.2  355.59  5502.2   356.3  5506.8  356.09
#Mann= 9 ,-1 , 0
  4237.6      .1       0  4355.8     .05       0    4485      .1       0
  4658.3     .05       0    4997    .035       0    5003     .05       0
  5004.1     .16       0  5014.3     .05       0  5134.9     .16       0
Bank Sta=4997,5003
XS Rating Curve= 0 ,0
Exp/Cntr=0.3,0.1

Type RM Length L Ch R = 1 ,11037   ,1069,1069,1069
BEGIN DESCRIPTION:
SPARKS BRANCH 20.0
END DESCRIPTION:
XS GIS Cut Line= 3
      3543242.09     10306541.63      3542942.11     10306091.64
      3542292.11     10305491.64
#Sta/Elev= 30
  4461.9  352.69  4526.5  351.74  4592.6  349.64  4642.2  349.05  4655.7  348.28
  4727.8  347.91  4814.9  345.57  4938.1  341.16  4989.2  338.42  4996.7  336.77
  4999.5  336.27  5002.7  336.77  5006.1  336.77  5009.8  338.21  5016.6  339.08
    5024  339.32  5072.2   338.7  5101.7  339.14  5123.2  340.55    5130  340.11
  5148.1  341.39  5158.4  341.58  5165.7  342.73  5186.7  343.68  5406.2  346.57
  5469.7  348.39  5660.8  351.51  5703.3  353.58  5745.8  354.11  5887.3  358.18
#Mann= 5 ,-1 , 0
  4461.9     .05       0  4996.7    .035       0  5002.7     .05       0
  5072.2     .16       0  5148.1     .05       0
Bank Sta=4996.7,5002.7
XS Rating Curve= 0 ,0
Exp/Cntr=0.3,0.1

Type RM Length L Ch R = 1 ,9968    ,408,408,408
BEGIN DESCRIPTION:
SPARKS BRANCH 18.0
END DESCRIPTION:
XS GIS Cut Line= 3
      3543681.52     10306350.88      3543342.11     10305841.64
      3542642.13     10305141.67
#Sta/Elev= 30
  4380.8  349.57  4429.4  349.09  4438.4  348.39  4444.4  348.79  4474.5  347.98
  4552.6  347.03  4597.1  345.89  4696.8  344.27    4826  340.91  4862.1  338.38
  4884.6  337.32  4898.1  336.73  4926.1  336.48  4970.3  335.56  4989.8  333.61
  5003.9  332.74  5006.7  332.24  5009.9  332.74  5021.1   334.7  5049.4  336.01
  5077.6  338.69  5091.8  339.25  5289.8  344.24  5310.3  344.37  5530.2  348.07
  5586.8  348.57  5629.2  350.17  5883.7  353.43  5954.5  357.73  5982.7  358.33
#Mann= 6 ,-1 , 0
  4380.8      .1       0  4597.1     .05       0  4926.1     .16       0
  5003.9     .07       0  5009.9     .16       0  5310.3     .05       0
Bank Sta=5003.9,5009.9
XS Rating Curve= 0 ,0
Exp/Cntr=0.3,0.1

Type RM Length L Ch R = 1 ,9560    ,577,577,577
BEGIN DESCRIPTION:
SPARKS BRANCH 17.0
END DESCRIPTION:
XS GIS Cut Line= 3
      3544011.37     10306012.33      3543642.11     10305591.64
      3543292.13     10305241.67
#Sta/Elev= 30
  4454.7  343.72  4516.3  343.36  4639.2  342.73  4745.4  340.76  4788.1  340.49
  4794.8  340.77  4801.6  340.26  4815.7  340.73  4823.2  339.97  4901.1  338.09
  4943.8  336.31    4958  336.35  4978.9  334.81  5004.3  331.12  5007.1  330.62
  5010.3  331.12  5011.1  332.87    5018  332.87  5028.6  334.15  5042.7  334.73
    5071  334.56  5085.2     334  5113.5  334.58  5141.7  335.97  5155.9  336.23
  5184.2   335.4  5198.3  338.21    5278  341.28  5311.4  342.46  5509.4  346.49
#Mann= 6 ,-1 , 0
  4454.7      .1       0  4516.3     .05       0  4823.2     .16       0
  5004.3     .07       0  5010.3     .16       0    5278     .05       0
Bank Sta=5004.3,5010.3
XS Rating Curve= 0 ,0
Exp/Cntr=0.3,0.1

Type RM Length L Ch R = 1 ,8983    ,579,579,579
BEGIN DESCRIPTION:
SPARKS BRANCH 16.0
END DESCRIPTION:
XS GIS Cut Line= 3
      3544358.61     10306298.79       3543905.3     10305191.99
      3543506.24     10304792.93
#Sta/Elev= 30
    4041  345.46  4121.1  345.32    4207  344.85  4353.8  343.72  4388.5  344.13
  4513.4  343.09  4543.3  344.86  4548.7  344.32  4567.3  345.25  4625.8  341.74
  4810.3  339.86  4839.7  340.53  4863.7  339.07  4911.7  338.45  4946.5  334.79
  4970.5  333.34  4996.9  329.77  4999.7  329.27  5002.9  329.77  5018.5  332.23
  5095.9  332.35  5298.7  337.55  5345.6  338.75    5381  340.78  5451.7  343.28
  5557.7  344.88  5593.1   346.2  5656.7  345.79  5748.7  346.92  5801.4  346.68
#Mann= 8 ,-1 , 0
    4041     .16       0  4121.1      .1       0    4207     .16       0
  4353.8      .1       0  4625.8     .16       0  4996.9     .07       0
  5002.9     .16       0  5298.7     .05       0
Bank Sta=4996.9,5002.9
XS Rating Curve= 0 ,0
Exp/Cntr=0.3,0.1

Type RM Length L Ch R = 1 ,8404    ,1001,1001,1001
BEGIN DESCRIPTION:
SPARKS BRANCH 15.0
END DESCRIPTION:
XS GIS Cut Line= 3
      3545096.45     10305916.85      3544077.17      10304796.5
      3543777.29      10304546.6
#Sta/Elev= 30
  3804.6  346.45  3903.6  345.85  4215.1   340.9  4370.5  339.81  4558.8  334.83
  4596.9  333.85  4618.5  330.05  4625.2  329.66  4632.7  330.36  4646.9  333.96
  4661.1  335.07  4731.3  336.02  4788.1  334.82  4823.9  333.17  4936.7  331.62
  4972.6  330.21  4997.9  327.81  5000.7  327.31  5003.9  327.81  5021.9  329.31
  5028.6  330.56  5092.8  330.16    5118  330.84  5264.3  337.93  5319.1  341.07
  5378.4  342.57  5510.5  344.79  5645.9  344.38    5681   342.7  5709.6  342.86
#Mann= 7 ,-1 , 0
  3804.6     .05       0  4558.8     .16       0  4997.9     .07       0
  5003.9     .16       0    5118     .05       0  5264.3      .1       0
  5378.4     .05       0
Bank Sta=4997.9,5003.9
XS Rating Curve= 0 ,0
Exp/Cntr=0.3,0.1

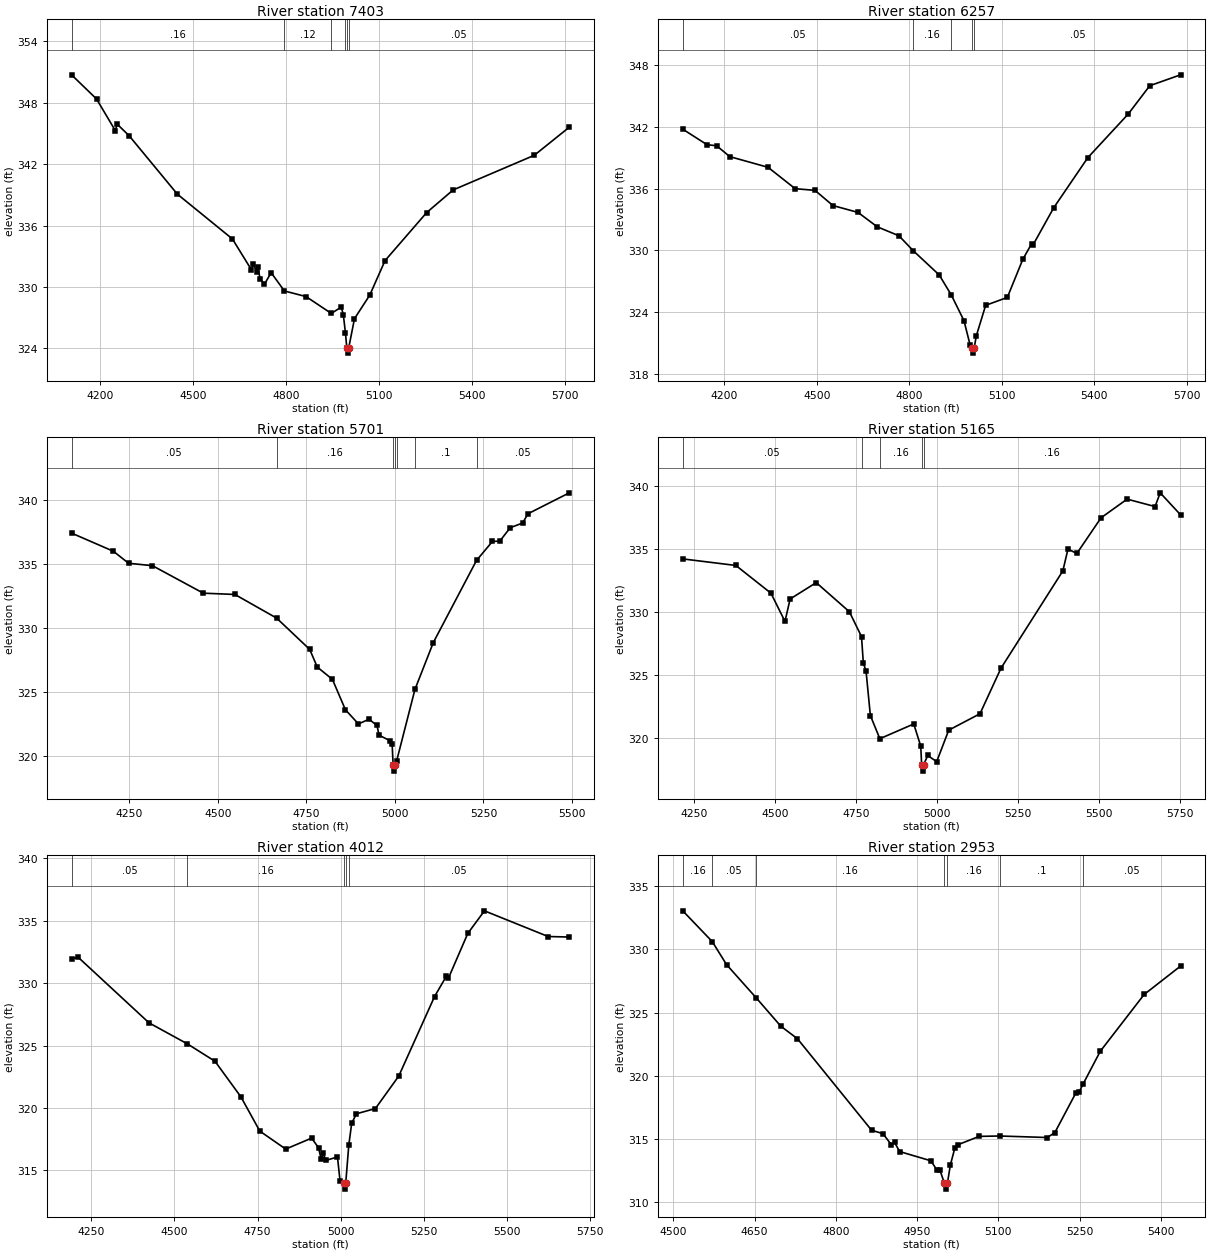
Type RM Length L Ch R = 1 ,7403    ,1146,1146,1146
BEGIN DESCRIPTION:
SPARKS BRANCH 13.0
END DESCRIPTION:
XS GIS Cut Line= 3
       3545592.1     10305241.64      3545061.74     10304970.68
      3544386.43     10304217.45
#Sta/Elev= 30
  4107.7  350.74  4188.3  348.38  4249.3  345.27  4254.9  345.92  4293.7  344.78
  4449.3  339.07    4627  334.69  4688.1  331.69  4693.7  332.22    4706  331.45
  4709.4  331.96  4716.2  330.81  4730.4  330.25  4752.1  331.39    4795   329.6
  4864.9  329.05  4946.5   327.4  4978.6  328.03  4985.3  327.25    4992  325.51
  4996.5  324.02  4999.2  323.52  5002.5  324.02  5021.2  326.89  5070.5  329.19
  5119.9  332.57  5254.4  337.27  5339.7  339.48  5601.8  342.87  5714.9  345.62
#Mann= 6 ,-1 , 0
  4107.7     .16       0    4795     .12       0  4946.5     .16       0
    4992     .05       0  4996.5    .035       0  5002.5     .05       0
Bank Sta=4996.5,5002.5
XS Rating Curve= 0 ,0
Exp/Cntr=0.3,0.1

Type RM Length L Ch R = 1 ,6257    ,556,556,556
BEGIN DESCRIPTION:
SPARKS BRANCH 11.0
END DESCRIPTION:
XS GIS Cut Line= 3
      3545989.32     10304474.27      3545489.33     10304174.28
      3544462.76     10304085.27
#Sta/Elev= 30
  4065.7   341.8  4144.4  340.29  4175.5  340.19  4218.2  339.13  4342.3  338.09
  4430.1  336.01  4494.2  335.85  4552.5  334.37  4633.9   333.7  4696.2   332.3
  4766.4  331.43  4812.6  329.98  4896.9  327.62    4936  325.68  4977.2  323.17
  4997.3  320.79  5004.3  320.51  5007.1  320.01  5010.3  320.51  5017.4  321.71
  5047.5  324.66  5117.8  325.43  5167.9  329.13  5196.6  330.66  5201.7  330.57
  5268.3  334.16  5378.7  339.03  5509.2  343.26  5579.5  346.03  5679.2  347.09
#Mann= 5 ,-1 , 0
  4065.7     .05       0  4812.6     .16       0    4936     .05       0
  5004.3     .03       0  5010.3     .05       0
Bank Sta=5004.3,5010.3
XS Rating Curve= 0 ,0
Exp/Cntr=0.3,0.1

Type RM Length L Ch R = 1 ,5701    ,536,536,536
BEGIN DESCRIPTION:
SPARKS BRANCH 10.0
END DESCRIPTION:
XS GIS Cut Line= 3
      3545929.76     10304206.78      3544942.45     10303607.27
      3544742.43     10303457.25
#Sta/Elev= 30
  4087.3  337.42  4205.3     336  4248.3  335.06  4315.7  334.87  4459.2  332.72
  4548.3  332.62  4666.2  330.77  4759.6  328.32  4780.9  326.94  4823.6  325.98
  4860.4   323.6  4897.2  322.49  4926.9  322.86  4949.5  322.37  4955.4  321.61
  4985.4  321.19  4992.2  320.94    4995   319.3  4997.8   318.8    5001   319.3
  5004.7  319.57  5056.6  325.19  5108.5  328.86  5230.4  335.28  5275.4  336.77
  5296.2  336.79  5325.4  337.84  5360.8  338.21  5375.4  338.93  5492.4  340.57
#Mann= 7 ,-1 , 0
  4087.3     .05       0  4666.2     .16       0    4995     .07       0
    5001     .16       0  5004.7     .05       0  5056.6      .1       0
  5230.4     .05       0
Bank Sta=4995,5001
XS Rating Curve= 0 ,0
Exp/Cntr=0.3,0.1

Type RM Length L Ch R = 1 ,5165    ,1153,1153,1153
BEGIN DESCRIPTION:
SPARKS BRANCH 9.0
END DESCRIPTION:
XS GIS Cut Line= 3
       3546224.9     10303850.87      3545235.86     10303289.91
      3545036.48     10302941.01
#Sta/Elev= 30
  4213.8   334.2    4378  333.68  4486.5  331.48  4529.8  329.24  4545.7  331.02
  4626.5  332.32  4728.9  330.01  4766.4  328.04  4772.1  325.92  4780.3  325.34
  4793.8  321.78  4823.1  319.94  4927.9  321.11  4949.6  319.35  4952.3  317.87
  4955.1  317.37  4958.3  317.87  4971.2  318.61  4998.8  318.12  5036.1  320.62
  5132.7  321.92  5197.6  325.53  5388.9  333.25  5404.7  334.98  5432.1  334.63
    5507  337.46  5587.6  338.94    5674  338.35  5689.8  339.44  5752.7   337.7
#Mann= 5 ,-1 , 0
  4213.8     .05       0  4766.4      .1       0  4823.1     .16       0
  4952.3     .07       0  4958.3     .16       0
Bank Sta=4952.3,4958.3
XS Rating Curve= 0 ,0
Exp/Cntr=0.3,0.1

Type RM Length L Ch R = 1 ,4012    ,1059,1059,1059
BEGIN DESCRIPTION:
SPARKS BRANCH 7.0
END DESCRIPTION:
XS GIS Cut Line= 3
      3546459.32     10303573.13      3545805.65     10302818.03
      3545506.39     10302419.02
#Sta/Elev= 30
  4190.5  331.97  4210.7  332.07  4423.5  326.82  4539.2  325.13    4622  323.74
  4699.9  320.89  4756.9  318.14  4834.8   316.7  4912.7  317.58  4933.5  316.81
  4941.2  315.91  4947.8  316.35  4955.4  315.79  4990.5  316.07  4998.2  314.15
  5009.4  313.99  5012.2  313.49  5015.4  313.99  5024.5  317.01  5033.3  318.77
  5047.5  319.53  5104.6  319.95  5174.8  322.55  5282.6  328.93  5318.1  330.56
  5324.3   330.4  5382.6  333.99  5432.6   335.8  5624.3  333.74    5688   333.7
#Mann= 5 ,-1 , 0
  4190.5     .05       0  4539.2     .16       0  5009.4     .07       0
  5015.4     .16       0  5024.5     .05       0
Bank Sta=5009.4,5015.4
XS Rating Curve= 0 ,0
Exp/Cntr=0.3,0.1

Type RM Length L Ch R = 1 ,2953    ,609,609,609
BEGIN DESCRIPTION:
SPARKS BRANCH 5.0
END DESCRIPTION:
XS GIS Cut Line= 3
      3546892.09     10302941.63      3546492.11     10302691.64
       3546092.1     10302491.64
#Sta/Elev= 30
  4517.4  333.04    4572   330.6  4598.2  328.79    4653  326.16  4698.4  323.92
  4729.1  322.93  4865.9   315.7  4887.1  315.42  4902.4  314.55  4908.3  314.74
  4917.7  314.01  4975.5  313.28  4986.1  312.58  4991.9  312.58  5000.1  311.54
  5002.8  311.04  5006.1  311.54  5011.4  312.95  5019.8  314.31  5025.4  314.55
  5064.6  315.21  5102.5  315.24  5190.3  315.12  5204.3  315.51  5243.4  318.67
    5249  318.71  5256.3  319.34  5288.2  321.94  5369.2  326.43  5436.3  328.67
#Mann= 7 ,-1 , 0
  4517.4     .16       0    4572     .05       0    4653     .16       0
  5000.1     .07       0  5006.1     .16       0  5102.5      .1       0
  5256.3     .05       0
Bank Sta=5000.1,5006.1
XS Rating Curve= 0 ,0
Exp/Cntr=0.3,0.1

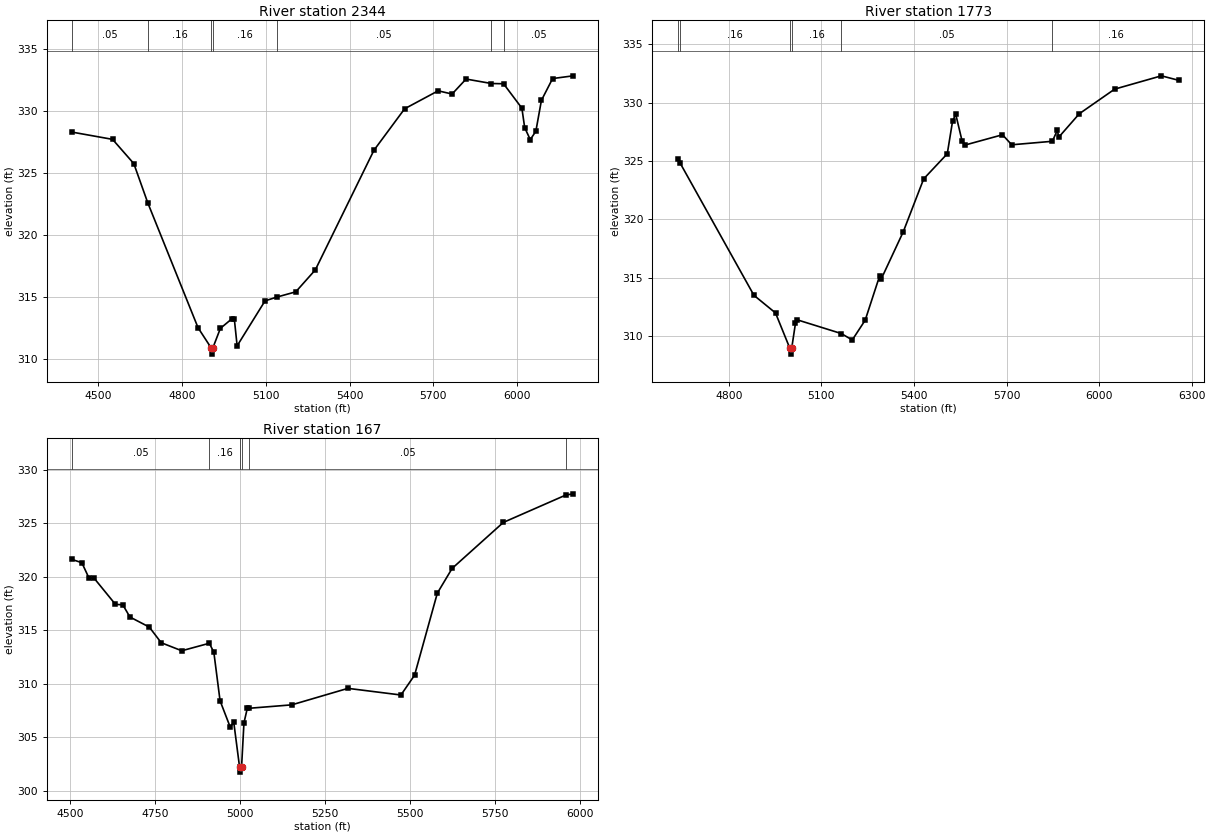
Type RM Length L Ch R = 1 ,2344    ,571,571,571
BEGIN DESCRIPTION:
SPARKS BRANCH 4.0
END DESCRIPTION:
XS GIS Cut Line= 3
      3547243.85     10302333.31      3546893.84     10302183.31
      3545478.39     10302218.95
#Sta/Elev= 30
  4404.6  328.33  4550.9  327.74  4627.1  325.78  4676.8  322.63  4857.2  312.53
  4904.2   310.9  4906.9   310.4  4910.2   310.9  4937.2  312.48  4977.2  313.23
  4987.2  313.23  4997.2  311.07  5097.2   314.7  5138.5     315  5207.3  315.43
  5277.3   317.2  5487.4  326.86  5597.4  330.21  5717.4  331.66  5767.4   331.4
  5817.5  332.61  5908.3  332.25  5951.8  332.23  6017.5  330.26  6027.5  328.69
  6047.5  327.72  6067.5  328.39  6087.5  330.89  6127.6  332.65  6201.3  332.87
#Mann= 7 ,-1 , 0
  4404.6     .05       0  4676.8     .16       0  4904.2     .07       0
  4910.2     .16       0  5138.5     .05       0  5908.3      .1       0
  5951.8     .05       0
Bank Sta=4904.2,4910.2
XS Rating Curve= 0 ,0
Exp/Cntr=0.3,0.1

Type RM Length L Ch R = 1 ,1773    ,1606,1606,1606
BEGIN DESCRIPTION:
SPARKS BRANCH 2.0
END DESCRIPTION:
XS GIS Cut Line= 3
      3547092.11     10301791.64      3546494.03     10301602.63
      3545505.76     10301741.33
#Sta/Elev= 30
  4633.7  325.17  4641.8  324.84  4881.4  313.49  4951.3  311.98  4997.8  308.95
  5000.5  308.45  5003.8  308.95  5015.9  311.08  5021.7  311.39    5165  310.21
    5200  309.66    5242  311.36    5289  315.17    5294  314.89  5365.3  318.93
  5431.6  323.47    5508  325.62  5525.4  328.45  5535.5     329  5555.7  326.75
  5565.8  326.37    5687  327.25  5716.9  326.39  5848.5  326.69  5864.6  327.62
  5869.6  327.05  5935.9  329.05  6050.5  331.16    6202   332.3  6258.9  331.91
#Mann= 6 ,-1 , 0
  4633.7     .05       0  4641.8     .16       0  4997.8     .07       0
  5003.8     .16       0    5165     .05       0  5848.5     .16       0
Bank Sta=4997.8,5003.8
XS Rating Curve= 0 ,0
Exp/Cntr=0.3,0.1

Type RM Length L Ch R = 1 ,167     ,0,0,0
BEGIN DESCRIPTION:
SPARKS BRANCH 1.0
END DESCRIPTION:
XS GIS Cut Line= 3
      3547474.92     10301420.33      3547231.88     10301203.32
      3546087.38     10301116.62
#Sta/Elev= 30
  4505.2  321.62  4534.9  321.31  4555.8  319.88    4570   319.9  4633.6  317.42
  4655.3  317.38  4676.2  316.24  4733.1   315.3  4768.2  313.84  4828.5  313.09
  4909.6  313.79  4922.8  312.95  4941.1  308.42  4971.2  305.94  4981.2  306.45
  4998.3  302.26    5001  301.76  5004.3  302.26  5011.3  306.36  5021.3  307.74
  5026.3  307.72  5151.7  308.04  5316.9  309.58  5472.6  308.96  5512.7  310.81
  5579.6  318.47  5623.1  320.78  5773.5  325.07  5957.4  327.63  5978.8  327.74
#Mann= 6 ,-1 , 0
  4505.2     .05       0  4909.6     .16       0  4998.3     .07       0
  5004.3     .16       0  5026.3     .05       0  5957.4      .1       0
Bank Sta=4998.3,5004.3
XS Rating Curve= 0 ,0
Exp/Cntr=0.3,0.1

Chan Stop Cuts=-1
Use User Specified Reach Order=0
Composite Channel Slope=5