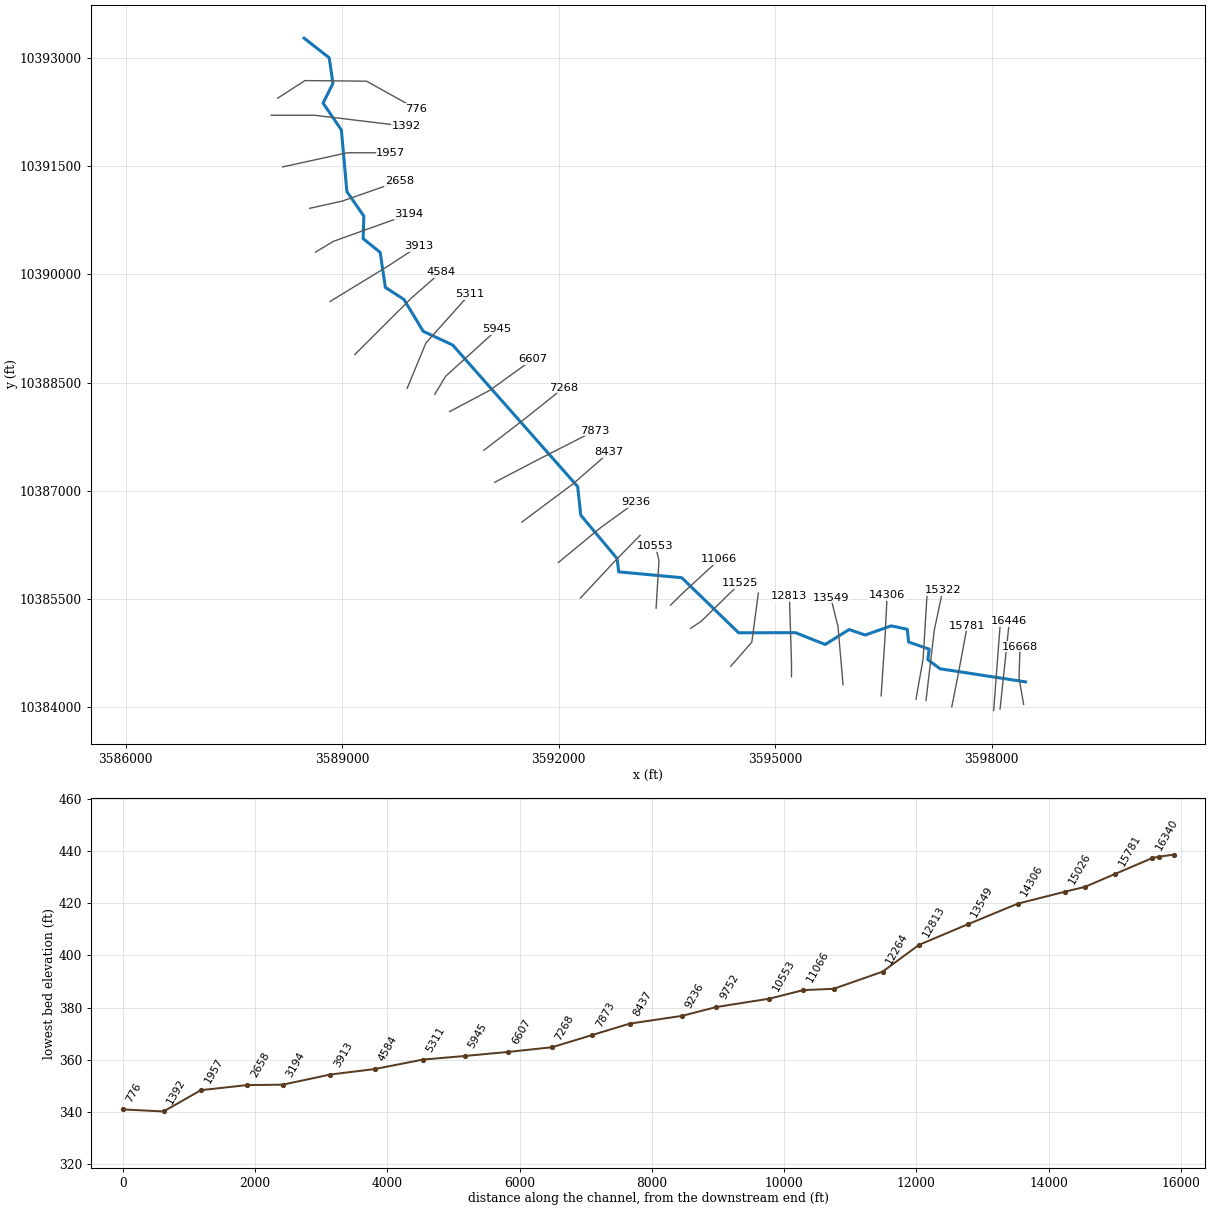
--- SYCAMORE BRANCH.prj (project) ---

Proj Title=SYCAMORE BRANCH Base Level Engineering
Current Plan=p01
Default Exp/Contr=0.3,0.1
English Units
Geom File=g01
Flow File=f01
Plan File=p01
BEGIN DESCRIPTION:
SYCAMORE BRANCH
END DESCRIPTION:

--- SYCAMORE BRANCH.p01 (plan) ---

Plan Title=Multiple Run
Short Identifier=Multiple
Geom File=g01
Flow File=f01
Subcritical Flow
K Sum by GR= 0
Std Step Tol= 0.01
Critical Tol= 0.01
Num of Std Step Trials= 20
Max Error Tol= 0.3
Flow Tol Ratio= 0.001
Split Flow NTrial= 30
Split Flow Tol= 0.02
Split Flow Ratio= 0.02
Log Output Level= 0
Friction Slope Method= 1
Unsteady Friction Slope Method= 2
Unsteady Bridges Friction Slope Method= 1
Parabolic Critical Depth
Global Vel Dist=  1 , 1 , 1
Global Log Level= 0
CheckData=True
Encroach Param= -1, 0, 0, 0
BEGIN DESCRIPTION:
Multiple Run
END DESCRIPTION:

--- SYCAMORE BRANCH.f01 (steady flow) ---

Flow Title=Multiple
Number of Profiles=7
Profile Names=10-year,25-year,50-year,1pct_min,100-year,1pct_plu,500-year
River Rch & RM= SYCAMORE BRANCH,Reach-1,16668
    1991    2880    3654    3381    4573    6184    7142
River Rch & RM= SYCAMORE BRANCH,Reach-1,11525
    2670    3917    5015    4678    6327    8557   10047
River Rch & RM= SYCAMORE BRANCH,Reach-1,9752
    3361    4979    6415    6018    8138   11006   13069
River Rch & RM= SYCAMORE BRANCH,Reach-1,7268
    3746    5561    7176    6736    9110   12321   14654
River Rch & RM= SYCAMORE BRANCH,Reach-1,3913
    3908    5796    7473    7008    9478   12818   15214
Boundary for River Rch & Prof#=SYCAMORE BRANCH,Reach-1,1
Up Type=0
Dn Type=3
Dn Slope=0.005
Boundary for River Rch & Prof#=SYCAMORE BRANCH,Reach-1,2
Up Type=0
Dn Type=3
Dn Slope=0.005
Boundary for River Rch & Prof#=SYCAMORE BRANCH,Reach-1,3
Up Type=0
Dn Type=3
Dn Slope=0.005
Boundary for River Rch & Prof#=SYCAMORE BRANCH,Reach-1,4
Up Type=0
Dn Type=3
Dn Slope=0.005
Boundary for River Rch & Prof#=SYCAMORE BRANCH,Reach-1,5
Up Type=0
Dn Type=3
Dn Slope=0.005
Boundary for River Rch & Prof#=SYCAMORE BRANCH,Reach-1,6
Up Type=0
Dn Type=3
Dn Slope=0.005
Boundary for River Rch & Prof#=SYCAMORE BRANCH,Reach-1,7
Up Type=0
Dn Type=3
Dn Slope=0.005

--- SYCAMORE BRANCH.g01 (geometry) ---

Geom Title=Existing Conditions

River Reach=SYCAMORE BRANCH,Reach-1
Reach XY= 30
      3598467.94     10384353.54      3597283.75     10384534.86
      3597114.13     10384662.28      3597133.48     10384807.06
      3596849.18     10384905.10      3596828.79     10385082.88
      3596606.45     10385129.58      3596246.84     10385002.60
      3596023.50     10385078.50      3595691.77     10384871.55
      3595281.74     10385034.74      3594492.13     10385033.73
      3593704.69     10385796.69      3592830.71     10385877.90
      3592809.48     10386060.44      3592305.68     10386663.12
      3592262.77     10387059.02      3590530.91     10389020.53
      3590121.98     10389210.71      3589855.38     10389652.32
      3589597.62     10389819.53      3589525.83     10390304.44
      3589289.66     10390494.59      3589300.16     10390805.58
      3589064.30     10391147.30      3588988.22     10392000.25
      3588734.70     10392372.63      3588871.47     10392645.60
      3588819.58     10393000.63      3588472.11     10393271.64

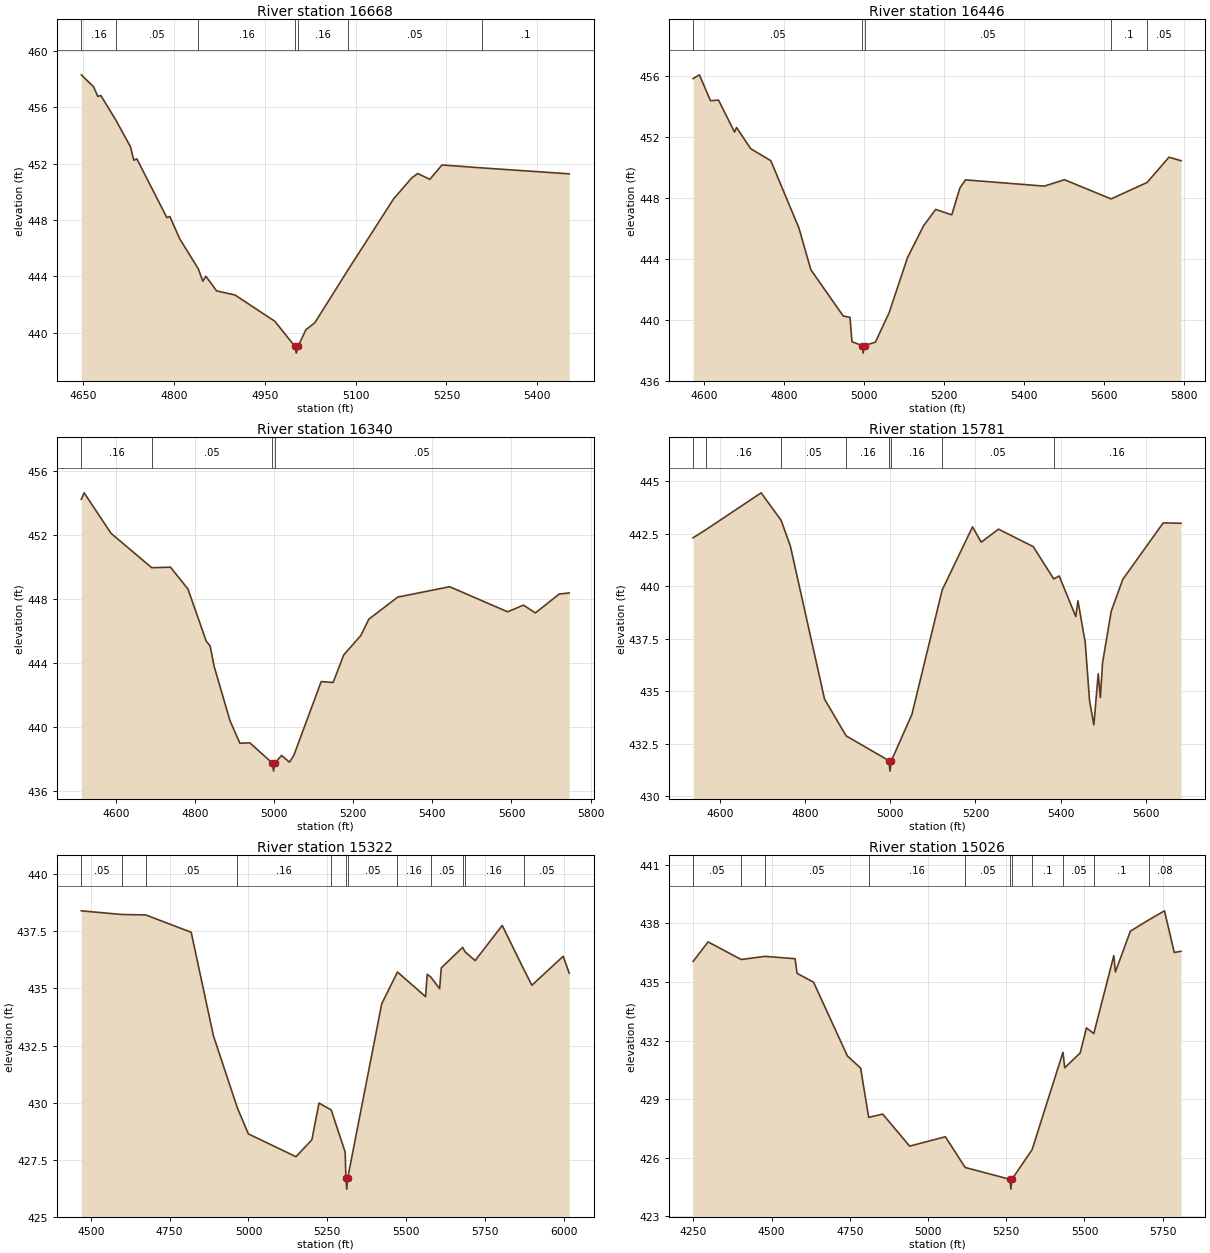
Type RM Length L Ch R = 1,16668,222,222,222
BEGIN DESCRIPTION:
SYCAMORE BRANCH 35.0
END DESCRIPTION:
XS GIS Cut Line= 3
      3598442.11     10384041.61      3598378.21     10384407.32
      3598392.11     10384841.65
#Sta/Elev= 30
  4647.0  458.31  4667.3  457.46  4674.2  456.78  4679.3  456.84  4704.3  455.08
  4728.2  453.20  4733.7  452.25  4738.8  452.34  4788.2  448.18  4793.3  448.25
  4809.5  446.67  4840.2  444.54  4847.7  443.66  4852.8  444.01  4870.4  442.97
  4900.8  442.68  4966.7  440.81  4999.3  439.05  5002.1  438.55  5005.3  439.05
  5017.9  440.21  5032.6  440.70  5086.9  444.42  5162.6  449.49  5192.7  450.99
  5202.7  451.30  5222.7  450.89  5242.7  451.91  5309.2  451.70  5452.8  451.28
#Mann=7,-1,0
  4647.0    0.16       0  4704.3    0.05       0  4840.2    0.16       0
  4999.3    0.07       0  5005.3    0.16       0  5086.9    0.05       0
  5309.2     0.1       0
Bank Sta=4999.3,5005.3
Exp/Cntr=0.3,0.1

Type RM Length L Ch R = 1,16446,106,106,106
BEGIN DESCRIPTION:
Mapping XS 29860dc4
END DESCRIPTION:
XS GIS Cut Line= 2
      3598115.75     10383978.49      3598243.78     10385191.56
#Sta/Elev= 30
  4572.3  455.84  4587.9  456.09  4615.7  454.39  4635.8  454.43  4675.8  452.33
  4680.8  452.63  4716.2  451.24  4766.5  450.45  4836.9  446.02  4866.6  443.29
  4947.5  440.25  4964.5  440.16  4969.5  438.56  4994.8  438.31  4997.5  437.81
  5000.8  438.31  5028.0  438.53  5062.4  440.47  5108.4  444.09  5148.6  446.18
  5178.8  447.25  5219.0  446.89  5239.1  448.65  5253.2  449.19  5450.3  448.78
  5500.6  449.20  5617.3  447.94  5707.3  449.02  5762.0  450.68  5792.1  450.45
#Mann=5,-1,0
  4572.3    0.05       0  4994.8    0.04       0  5000.8    0.05       0
  5617.3     0.1       0  5707.3    0.05       0
Bank Sta=4994.8,5000.8
Exp/Cntr=0.3,0.1

Type RM Length L Ch R = 1,16340,559,559,559
BEGIN DESCRIPTION:
SYCAMORE BRANCH 34.0
END DESCRIPTION:
XS GIS Cut Line= 2
      3598026.77     10383956.73      3598120.06     10385186.90
#Sta/Elev= 30
  4512.3  454.24  4519.5  454.64  4587.4  452.11  4690.3  449.96  4737.9  449.99
  4782.1  448.62  4828.1  445.37  4838.1  445.06  4848.2  443.79  4888.3  440.39
  4913.4  438.98  4938.4  439.01  4995.6  437.74  4998.4  437.24  5001.6  437.74
  5018.7  438.22  5038.7  437.80  5049.8  438.23  5118.9  442.84  5149.0  442.78
  5176.0  444.51  5219.2  445.72  5239.3  446.74  5312.4  448.12  5443.7  448.77
  5590.3  447.20  5630.4  447.62  5660.5  447.13  5720.7  448.31  5746.0  448.38
#Mann=4,-1,0
  4512.3    0.16       0  4690.3    0.05       0  4995.6    0.04       0
  5001.6    0.05       0
Bank Sta=4995.6,5001.6
Exp/Cntr=0.3,0.1

Type RM Length L Ch R = 1,15781,459,459,459
BEGIN DESCRIPTION:
SYCAMORE BRANCH 33.0
END DESCRIPTION:
XS GIS Cut Line= 3
      3597446.62     10384007.75      3597542.11     10384491.64
      3597661.89     10385132.73
#Sta/Elev= 30
  4537.3  442.30  4567.0  442.68  4697.0  444.44  4743.9  443.13  4765.5  441.91
  4845.8  434.62  4896.5  432.87  4996.8  431.69  4999.5  431.19  5002.8  431.69
  5050.9  433.89  5122.1  439.82  5193.3  442.82  5213.6  442.09  5254.3  442.71
  5335.7  441.88  5383.8  440.34  5396.7  440.48  5435.6  438.55  5440.7  439.30
  5457.8  437.32  5468.0  434.54  5478.1  433.39  5488.3  435.83  5493.4  434.69
  5498.5  436.35  5518.8  438.80  5546.0  440.32  5640.9  443.01  5682.7  442.99
#Mann=8,-1,0
  4537.3    0.05       0  4567.0    0.16       0  4743.9    0.05       0
  4896.5    0.16       0  4996.8    0.07       0  5002.8    0.16       0
  5122.1    0.05       0  5383.8    0.16       0
Bank Sta=4996.8,5002.8
Exp/Cntr=0.3,0.1

Type RM Length L Ch R = 1,15322,296,296,296
BEGIN DESCRIPTION:
Mapping XS 5d2d63e2
END DESCRIPTION:
XS GIS Cut Line= 3
      3597089.27     10384095.67      3597204.29     10385072.22
      3597321.46     10385623.40
#Sta/Elev= 30
  4470.1  438.40  4597.8  438.24  4674.4  438.22  4818.5  437.46  4888.9  432.93
  4965.1  429.76  4999.7  428.63  5150.7  427.63  5201.1  428.37  5223.6  429.98
  5262.3  429.68  5306.7  427.83  5308.9  426.71  5311.6  426.21  5314.9  426.71
  5422.6  434.33  5472.5  435.72  5561.6  434.64  5566.8  435.62  5578.0  435.50
  5606.1  434.99  5611.3  435.90  5679.2  436.80  5686.3  436.61  5718.6  436.22
  5804.6  437.76  5872.8  435.84  5898.6  435.14  5997.9  436.41  6016.9  435.67
#Mann=12,-1,0
  4470.1    0.05       0  4597.8    0.16       0  4674.4    0.05       0
  4965.1    0.16       0  5262.3    0.05       0  5308.9    0.07       0
  5314.9    0.05       0  5472.5    0.16       0  5578.0    0.05       0
  5679.2    0.08       0  5686.3    0.16       0  5872.8    0.05       0
Bank Sta=5308.9,5314.9
Exp/Cntr=0.3,0.1

Type RM Length L Ch R = 1,15026,720,720,720
BEGIN DESCRIPTION:
SYCAMORE BRANCH 32.0
END DESCRIPTION:
XS GIS Cut Line= 3
      3596950.38     10384114.60      3597049.34     10384671.89
      3597110.10     10385663.22
#Sta/Elev= 30
  4249.4  436.05  4297.2  437.05  4402.9  436.15  4478.8  436.31  4575.2  436.19
  4581.6  435.44  4634.2  434.99  4742.2  431.22  4784.7  430.59  4810.5  428.07
  4855.2  428.24  4941.4  426.60  5055.6  427.08  5118.6  425.51  5262.1  424.90
  5264.9  424.40  5268.1  424.90  5332.7  426.42  5431.3  431.40  5437.0  430.61
  5486.4  431.37  5506.5  432.65  5529.9  432.36  5593.9  436.35  5598.9  435.51
  5646.7  437.60  5707.1  438.19  5755.8  438.64  5787.0  436.51  5808.6  436.57
#Mann=11,-1,0
  4249.4    0.05       0  4402.9    0.16       0  4478.8    0.05       0
  4810.5    0.16       0  5118.6    0.05       0  5262.1    0.07       0
  5268.1    0.05       0  5332.7     0.1       0  5431.3    0.05       0
  5529.9     0.1       0  5707.1    0.08       0
Bank Sta=5262.1,5268.1
Exp/Cntr=0.3,0.1

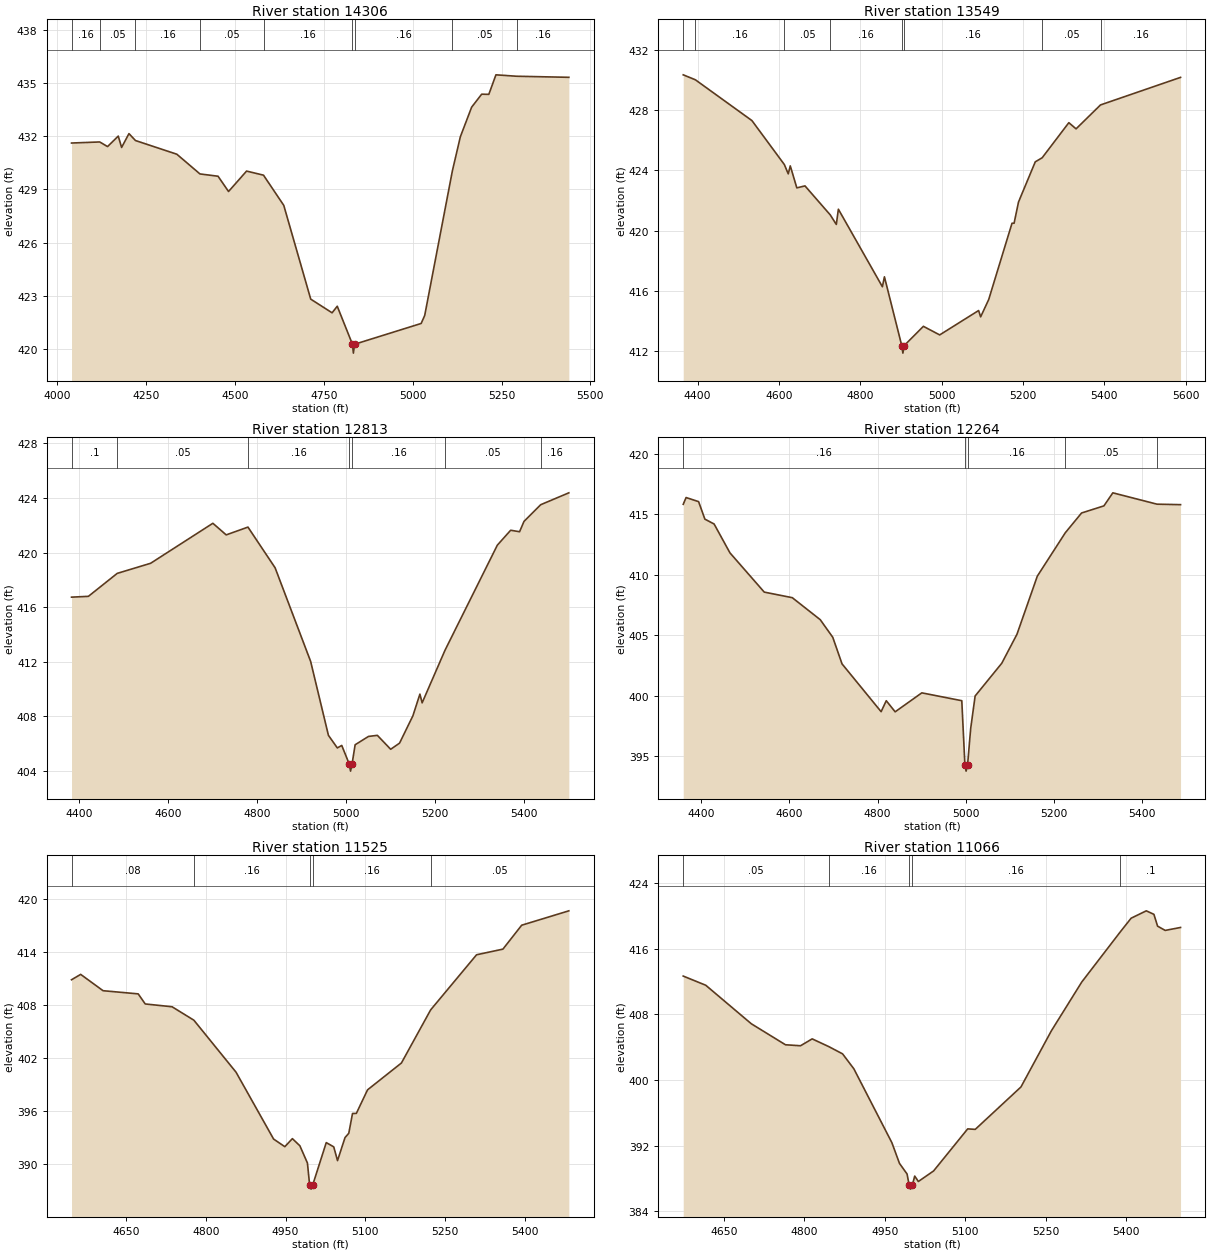
Type RM Length L Ch R = 1,14306,757,757,757
BEGIN DESCRIPTION:
SYCAMORE BRANCH 31.0
END DESCRIPTION:
XS GIS Cut Line= 3
      3596467.45     10384160.54      3596522.66     10384988.86
      3596550.79     10385556.40
#Sta/Elev= 30
  4040.9  431.61  4120.1  431.67  4142.2  431.41  4172.3  432.00  4181.7  431.36
  4202.4  432.14  4220.7  431.75  4337.0  430.98  4402.0  429.87  4452.9  429.74
  4482.4  428.88  4533.1  430.03  4580.7  429.80  4637.7  428.10  4713.5  422.82
  4773.6  422.05  4788.1  422.42  4830.8  420.28  4833.5  419.78  4836.8  420.28
  5024.0  421.45  5034.0  421.90  5111.9  430.05  5134.2  431.96  5166.0  433.63
  5194.2  434.36  5214.3  434.35  5234.3  435.45  5292.3  435.37  5439.3  435.31
#Mann=9,-1,0
  4040.9    0.16       0  4120.1    0.05       0  4220.7    0.16       0
  4402.0    0.05       0  4580.7    0.16       0  4830.8    0.07       0
  4836.8    0.16       0  5111.9    0.05       0  5292.3    0.16       0
Bank Sta=4830.8,4836.8
Exp/Cntr=0.3,0.1

Type RM Length L Ch R = 1,13549,736,736,736
BEGIN DESCRIPTION:
SYCAMORE BRANCH 29.0
END DESCRIPTION:
XS GIS Cut Line= 3
      3595939.67     10384313.35      3595869.88     10385120.81
      3595769.88     10385520.82
#Sta/Elev= 30
  4364.5  430.35  4394.4  430.02  4533.4  427.31  4613.1  424.39  4622.7  423.77
  4627.7  424.30  4643.8  422.84  4663.9  422.97  4726.1  421.04  4740.9  420.41
  4746.0  421.42  4854.2  416.27  4859.2  416.93  4901.8  412.36  4904.6  411.86
  4907.8  412.36  4955.0  413.64  4995.1  413.07  5090.8  414.69  5095.8  414.27
  5115.6  415.42  5172.9  420.49  5178.0  420.49  5188.9  421.90  5230.1  424.57
  5247.1  424.84  5312.6  427.17  5330.4  426.76  5390.5  428.35  5587.3  430.18
#Mann=8,-1,0
  4364.5    0.05       0  4394.4    0.16       0  4613.1    0.05       0
  4726.1    0.16       0  4901.8    0.07       0  4907.8    0.16       0
  5247.1    0.05       0  5390.5    0.16       0
Bank Sta=4901.8,4907.8
Exp/Cntr=0.3,0.1

Type RM Length L Ch R = 1,12813,549,549,549
BEGIN DESCRIPTION:
SYCAMORE BRANCH 28.0
END DESCRIPTION:
XS GIS Cut Line= 3
      3595225.44     10384423.60      3595225.44     10384623.59
      3595196.62     10385542.44
#Sta/Elev= 30
  4382.2  416.73  4420.2  416.79  4485.0  418.47  4560.2  419.21  4700.3  422.14
  4730.3  421.29  4779.3  421.86  4840.4  418.88  4920.4  412.02  4960.4  406.61
  4980.4  405.69  4990.4  405.87  5007.5  404.49  5010.2  403.99  5013.5  404.49
  5020.5  405.92  5050.5  406.53  5070.5  406.61  5100.5  405.59  5120.5  406.04
  5150.5  408.04  5166.3  409.63  5171.3  408.99  5222.9  412.85  5340.6  420.54
  5370.6  421.63  5390.6  421.52  5400.6  422.28  5438.2  423.50  5501.5  424.37
#Mann=7,-1,0
  4382.2     0.1       0  4485.0    0.05       0  4779.3    0.16       0
  5007.5    0.07       0  5013.5    0.16       0  5222.9    0.05       0
  5438.2    0.16       0
Bank Sta=5007.5,5013.5
Exp/Cntr=0.3,0.1

Type RM Length L Ch R = 1,12264,739,739,739
BEGIN DESCRIPTION:
SYCAMORE BRANCH 27.0
END DESCRIPTION:
XS GIS Cut Line= 3
      3594384.14     10384570.28      3594675.79     10384903.59
      3594766.06     10385584.14
#Sta/Elev= 30
  4358.7  415.84  4365.2  416.40  4393.6  416.06  4407.9  414.61  4428.8  414.21
  4464.8  411.82  4542.7  408.57  4606.3  408.11  4669.8  406.29  4698.3  404.83
  4719.3  402.63  4808.1  398.67  4819.8  399.58  4840.0  398.66  4900.5  400.23
  4991.3  399.58  4998.4  394.25  5001.1  393.75  5004.4  394.25  5011.5  397.28
  5021.6  399.97  5082.1  402.68  5116.6  405.08  5162.8  409.89  5226.3  413.48
  5263.3  415.12  5314.1  415.71  5334.3  416.79  5434.7  415.85  5488.1  415.81
#Mann=5,-1,0
  4358.7    0.16       0  4998.4    0.07       0  5004.4    0.16       0
  5226.3    0.05       0  5434.7    0.16       0
Bank Sta=4998.4,5004.4
Exp/Cntr=0.3,0.1

Type RM Length L Ch R = 1,11525,459,459,459
BEGIN DESCRIPTION:
SYCAMORE BRANCH 25.0
END DESCRIPTION:
XS GIS Cut Line= 3
      3593826.81     10385094.41      3593976.83     10385194.42
      3594516.05     10385723.03
#Sta/Elev= 30
  4547.4  410.90  4564.6  411.51  4606.7  409.66  4672.8  409.30  4686.0  408.16
  4736.5  407.84  4777.5  406.32  4856.8  400.43  4927.5  392.85  4948.6  391.99
  4962.8  392.90  4976.9  392.09  4991.1  390.14  4995.2  387.68  4998.0  387.18
  5001.2  387.68  5026.5  392.45  5040.6  391.97  5047.7  390.41  5061.8  393.02
  5068.9  393.51  5075.9  395.75  5083.1  395.76  5104.2  398.43  5167.9  401.47
  5222.9  407.49  5309.2  413.73  5358.8  414.37  5394.1  417.08  5482.8  418.71
#Mann=5,-1,0
  4547.4    0.08       0  4777.5    0.16       0  4995.2    0.07       0
  5001.2    0.16       0  5222.9    0.05       0
Bank Sta=4995.2,5001.2
Exp/Cntr=0.3,0.1

Type RM Length L Ch R = 1,11066,513,513,513
BEGIN DESCRIPTION:
SYCAMORE BRANCH 24.0
END DESCRIPTION:
XS GIS Cut Line= 3
      3593549.05     10385415.25      3593699.05     10385565.25
      3594224.42     10386049.45
#Sta/Elev= 30
  4574.5  412.67  4616.5  411.55  4701.4  406.85  4765.0  404.29  4793.1  404.17
  4814.7  405.01  4845.9  404.06  4871.4  403.18  4892.4  401.36  4963.3  392.34
  4977.4  389.82  4991.6  388.52  4995.4  387.18  4998.2  386.68  5001.4  387.18
  5005.8  388.27  5012.6  387.61  5041.0  388.90  5104.5  394.03  5118.6  393.97
  5203.7  399.14  5260.4  405.99  5317.1  411.95  5388.8  418.06  5409.0  419.73
  5437.3  420.63  5451.5  420.20  5458.3  418.76  5472.5  418.24  5501.1  418.60
#Mann=5,-1,0
  4574.5    0.05       0  4845.9    0.16       0  4995.4    0.07       0
  5001.4    0.16       0  5388.8     0.1       0
Bank Sta=4995.4,5001.4
Exp/Cntr=0.3,0.1

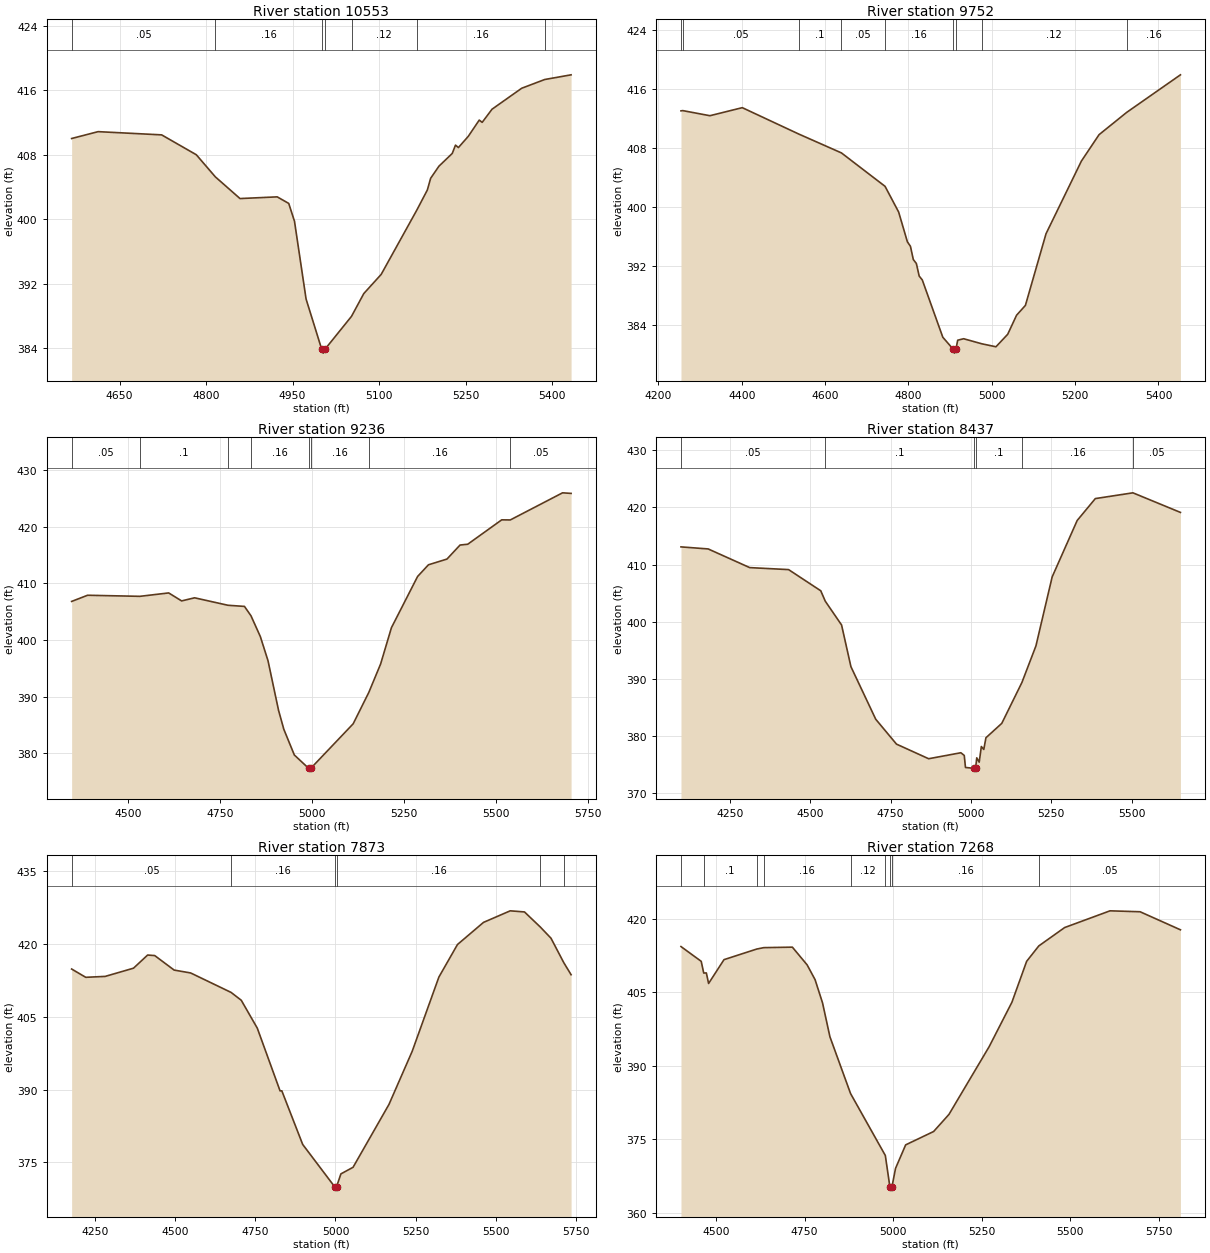
Type RM Length L Ch R = 1,10553,801,801,801
BEGIN DESCRIPTION:
SYCAMORE BRANCH 23.0
END DESCRIPTION:
XS GIS Cut Line= 3
      3593349.40     10385375.83      3593389.33     10386034.70
      3593339.34     10386234.67
#Sta/Elev= 30
  4566.8  410.00  4612.7  410.85  4722.9  410.45  4783.0  407.99  4816.0  405.25
  4858.8  402.56  4923.3  402.77  4943.3  401.96  4953.3  399.75  4973.4  390.11
  5000.4  383.91  5003.2  383.41  5006.4  383.91  5052.2  387.97  5073.5  390.79
  5103.6  393.16  5165.3  401.11  5183.7  403.62  5189.4  405.07  5203.8  406.57
  5226.9  408.15  5232.5  409.18  5237.6  408.88  5254.7  410.27  5273.7  412.28
  5278.8  412.00  5295.9  413.63  5347.4  416.23  5387.3  417.31  5433.0  417.89
#Mann=7,-1,0
  4566.8    0.05       0  4816.0    0.16       0  5000.4    0.07       0
  5006.4    0.16       0  5052.2    0.12       0  5165.3    0.16       0
  5387.3     0.1       0
Bank Sta=5000.4,5006.4
Exp/Cntr=0.3,0.1

Type RM Length L Ch R = 1,9752,516,516,516
BEGIN DESCRIPTION:
SYCAMORE BRANCH 21.0
END DESCRIPTION:
XS GIS Cut Line= 3
      3592300.82     10385514.74      3592792.11     10386041.64
      3593127.13     10386382.71
#Sta/Elev= 30
  4254.2  413.04  4258.6  413.07  4323.6  412.38  4401.3  413.47  4536.7  409.90
  4639.2  407.34  4743.9  402.81  4776.5  399.33  4797.5  395.29  4804.8  394.69
  4811.7  392.89  4819.0  392.36  4825.8  390.65  4833.2  390.13  4882.5  382.36
  4907.9  380.71  4910.6  380.21  4913.9  380.71  4918.2  381.96  4932.4  382.16
  4976.4  381.47  5010.0  381.07  5038.3  382.77  5059.4  385.34  5080.7  386.68
  5130.1  396.38  5215.0  406.23  5257.4  409.81  5323.7  412.83  5452.7  417.92
#Mann=9,-1,0
  4254.2     0.1       0  4258.6    0.05       0  4536.7     0.1       0
  4639.2    0.05       0  4743.9    0.16       0  4907.9    0.07       0
  4913.9    0.16       0  4976.4    0.12       0  5323.7    0.16       0
Bank Sta=4907.9,4913.9
Exp/Cntr=0.3,0.1

Type RM Length L Ch R = 1,9236,799,799,799
BEGIN DESCRIPTION:
SYCAMORE BRANCH 20.0
END DESCRIPTION:
XS GIS Cut Line= 3
      3591995.26     10386007.78      3592585.51     10386493.87
      3593064.68     10386841.10
#Sta/Elev= 30
  4347.5  406.81  4390.8  407.90  4532.9  407.71  4611.1  408.31  4646.2  406.90
  4681.4  407.45  4772.1  406.13  4816.9  405.93  4834.6  404.27  4860.0  400.60
  4880.8  396.34  4909.5  387.56  4923.8  384.22  4952.3  379.69  4991.1  377.34
  4993.9  376.84  4997.1  377.34  5112.1  385.20  5154.7  390.76  5186.6  395.76
  5216.0  402.17  5287.1  411.22  5316.5  413.28  5366.8  414.29  5402.4  416.77
  5423.2  416.91  5515.5  421.22  5538.8  421.20  5680.7  425.99  5703.9  425.89
#Mann=8,-1,0
  4347.5    0.05       0  4532.9     0.1       0  4772.1    0.05       0
  4834.6    0.16       0  4991.1    0.07       0  4997.1    0.16       0
  5154.7    0.16       0  5538.8    0.05       0
Bank Sta=4991.1,4997.1
Exp/Cntr=0.3,0.1

Type RM Length L Ch R = 1,8437,564,564,564
BEGIN DESCRIPTION:
SYCAMORE BRANCH 18.0
END DESCRIPTION:
XS GIS Cut Line= 3
      3591488.27     10386566.77      3592192.11     10387091.64
      3592701.82     10387535.53
#Sta/Elev= 30
  4097.7  413.10  4182.3  412.74  4311.6  409.47  4432.5  409.12  4532.6  405.41
  4546.6  403.59  4597.3  399.42  4626.4  392.12  4703.6  382.91  4768.2  378.55
  4868.3  375.99  4968.4  377.04  4979.0  376.57  4982.8  374.46  5008.3  374.32
  5011.1  373.82  5014.3  374.32  5017.9  376.15  5025.5  375.39  5032.2  378.13
  5039.8  377.62  5046.4  379.66  5095.8  382.19  5158.5  389.36  5202.1  395.77
  5252.5  407.84  5330.3  417.72  5386.8  421.56  5503.8  422.57  5651.6  419.14
#Mann=6,-1,0
  4097.7    0.05       0  4546.6     0.1       0  5008.3    0.07       0
  5014.3     0.1       0  5158.5    0.16       0  5503.8    0.05       0
Bank Sta=5008.3,5014.3
Exp/Cntr=0.3,0.1

Type RM Length L Ch R = 1,7873,605,605,605
BEGIN DESCRIPTION:
SYCAMORE BRANCH 17.0
END DESCRIPTION:
XS GIS Cut Line= 3
      3591113.24     10387118.85      3591691.41     10387420.96
      3592497.87     10387831.99
#Sta/Elev= 30
  4177.2  414.83  4221.2  413.12  4281.8  413.31  4370.1  415.00  4414.2  417.71
  4436.3  417.60  4496.9  414.61  4548.3  414.02  4674.4  410.01  4706.2  408.39
  4756.2  402.64  4827.1  389.73  4832.7  389.73  4897.7  378.69  4997.3  369.98
  5000.0  369.48  5003.3  369.98  5016.9  372.62  5054.8  373.98  5166.9  386.95
  5239.2  397.88  5322.5  413.18  5380.3  419.87  5461.6  424.44  5544.9  426.82
  5589.4  426.59  5638.6  423.49  5672.1  421.17  5711.8  416.15  5734.7  413.66
#Mann=6,-1,0
  4177.2    0.05       0  4674.4    0.16       0  4997.3    0.07       0
  5003.3    0.16       0  5638.6    0.05       0  5711.8    0.16       0
Bank Sta=4997.3,5003.3
Exp/Cntr=0.3,0.1

Type RM Length L Ch R = 1,7268,661,661,661
BEGIN DESCRIPTION:
SYCAMORE BRANCH 16.0
END DESCRIPTION:
XS GIS Cut Line= 3
      3590962.22     10387561.56      3591550.79     10388014.71
      3592071.62     10388431.37
#Sta/Elev= 30
  4401.0  414.29  4458.1  411.28  4465.2  408.89  4472.6  408.91  4478.9  406.76
  4522.4  411.62  4614.7  413.78  4634.7  414.07  4715.4  414.17  4757.1  410.55
  4779.5  407.54  4800.6  402.79  4821.4  395.89  4879.7  384.30  4977.8  371.67
  4990.6  365.31  4993.3  364.81  4996.6  365.31  5006.6  369.04  5035.2  373.84
  5114.1  376.56  5157.4  380.05  5271.1  393.90  5335.1  402.93  5376.7  411.28
  5411.0  414.42  5484.0  418.17  5612.0  421.58  5696.9  421.39  5810.8  417.71
#Mann=9,-1,0
  4401.0    0.05       0  4465.2     0.1       0  4614.7    0.05       0
  4634.7    0.16       0  4879.7    0.12       0  4977.8    0.16       0
  4990.6    0.07       0  4996.6    0.16       0  5411.0    0.05       0
Bank Sta=4990.6,4996.6
Exp/Cntr=0.3,0.1

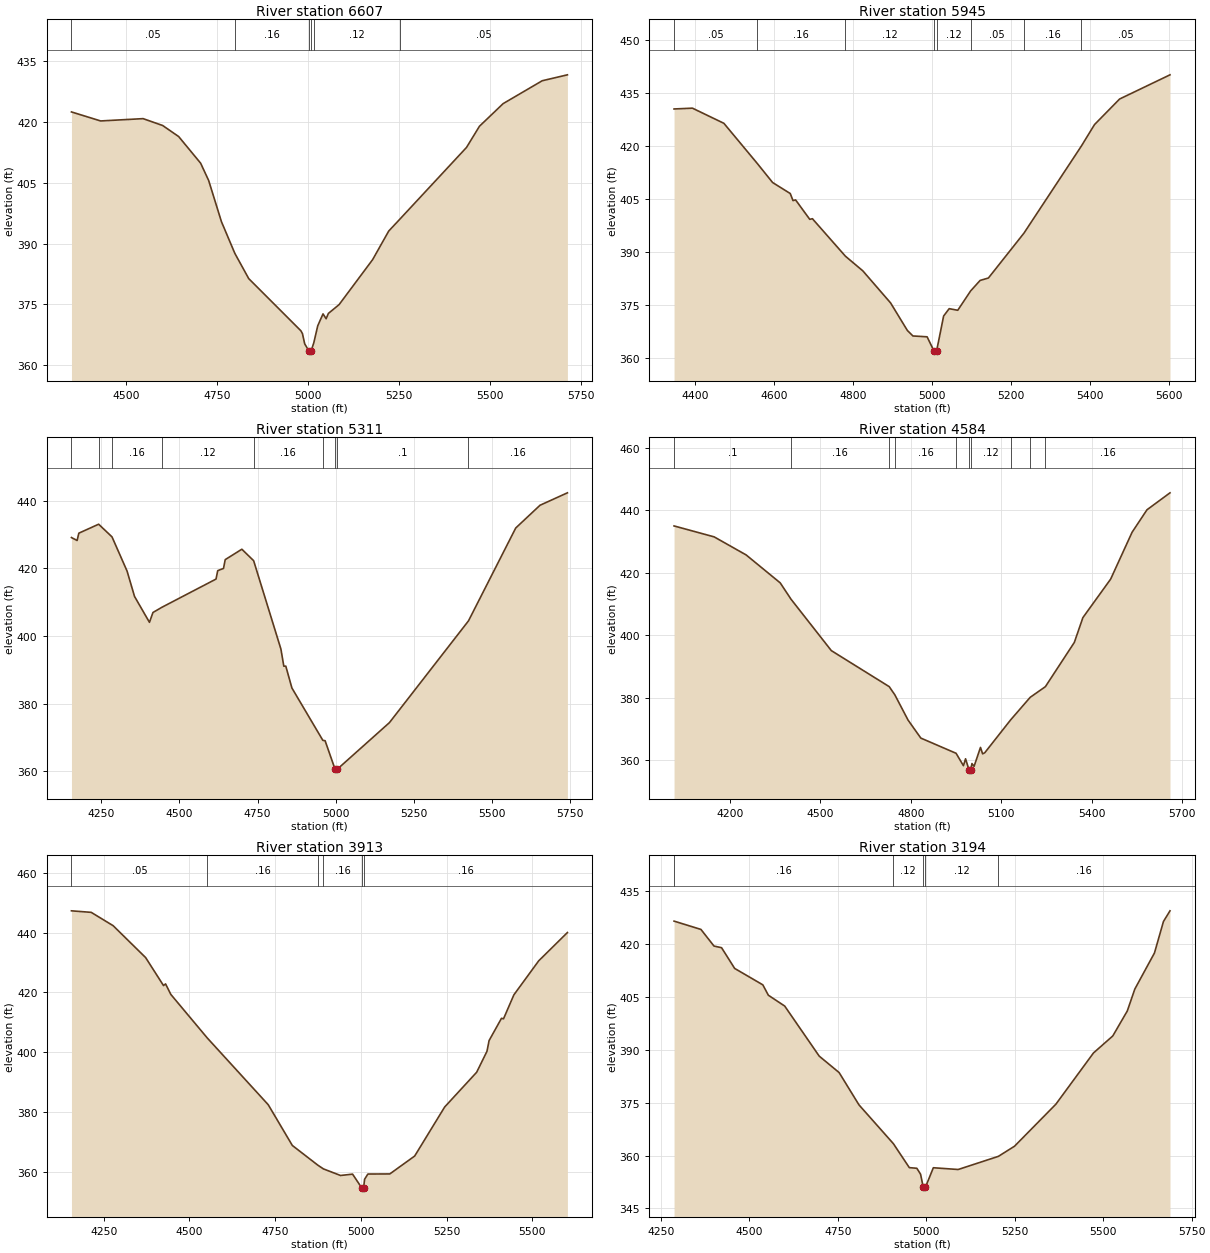
Type RM Length L Ch R = 1,6607,662,662,662
BEGIN DESCRIPTION:
SYCAMORE BRANCH 14.0
END DESCRIPTION:
XS GIS Cut Line= 3
      3590488.32     10388098.05      3591042.11     10388391.64
      3591638.25     10388821.22
#Sta/Elev= 30
  4350.3  422.41  4430.4  420.19  4547.0  420.76  4600.7  419.07  4644.7  416.34
  4705.0  409.78  4727.0  405.52  4762.0  395.40  4798.9  387.57  4837.0  381.36
  4980.2  368.51  4984.5  367.80  4990.6  365.31  5002.3  363.51  5005.1  363.01
  5008.3  363.51  5015.8  365.62  5026.4  369.73  5040.9  372.67  5049.5  371.48
  5055.6  372.78  5085.1  374.96  5177.1  386.03  5221.3  393.07  5252.5  396.06
  5434.9  413.67  5470.4  418.88  5535.5  424.46  5642.7  430.09  5711.9  431.55
#Mann=6,-1,0
  4350.3    0.05       0  4798.9    0.16       0  5002.3    0.07       0
  5008.3    0.16       0  5015.8    0.12       0  5252.5    0.05       0
Bank Sta=5002.3,5008.3
Exp/Cntr=0.3,0.1

Type RM Length L Ch R = 1,5945,634,634,634
BEGIN DESCRIPTION:
SYCAMORE BRANCH 13.0
END DESCRIPTION:
XS GIS Cut Line= 3
      3590282.71     10388337.44      3590432.73     10388587.48
      3591147.33     10389236.47
#Sta/Elev= 30
  4346.4  430.59  4393.0  430.82  4472.7  426.53  4557.1  415.19  4596.2  409.76
  4640.9  406.65  4647.8  404.66  4654.5  404.83  4690.3  399.34  4697.1  399.51
  4780.6  388.91  4824.8  384.75  4895.1  375.68  4937.7  367.87  4951.8  366.31
  4987.7  366.07  5005.6  361.95  5008.4  361.45  5011.6  361.95  5029.6  371.96
  5043.7  374.04  5065.4  373.58  5098.0  379.06  5122.1  382.04  5143.1  382.72
  5233.0  395.40  5378.7  420.09  5412.0  426.17  5475.6  433.41  5603.3  440.26
#Mann=8,-1,0
  4346.4    0.05       0  4557.1    0.16       0  4780.6    0.12       0
  5005.6    0.07       0  5011.6    0.12       0  5098.0    0.05       0
  5233.0    0.16       0  5378.7    0.05       0
Bank Sta=5005.6,5011.6
Exp/Cntr=0.3,0.1

Type RM Length L Ch R = 1,5311,727,727,727
BEGIN DESCRIPTION:
SYCAMORE BRANCH 11.0
END DESCRIPTION:
XS GIS Cut Line= 3
      3589899.75     10388420.96      3590160.07     10389049.44
      3590764.35     10389723.06
#Sta/Elev= 30
  4155.2  429.10  4173.3  428.23  4178.7  430.39  4242.1  433.04  4284.8  429.30
  4332.9  419.20  4356.8  411.69  4404.5  404.04  4415.7  406.95  4443.9  408.47
  4617.3  416.83  4622.7  419.32  4641.2  419.97  4646.6  422.57  4699.8  425.65
  4737.5  422.26  4824.7  396.13  4833.9  391.09  4840.3  391.09  4859.8  384.63
  4958.7  369.16  4965.9  369.05  4998.0  360.56  5000.8  360.06  5004.0  360.56
  5171.5  374.39  5424.2  404.47  5575.2  431.92  5652.9  438.65  5740.4  442.32
#Mann=9,-1,0
  4155.2    0.16       0  4242.1    0.05       0  4284.8    0.16       0
  4443.9    0.12       0  4737.5    0.16       0  4958.7     0.1       0
  4998.0    0.07       0  5004.0     0.1       0  5424.2    0.16       0
Bank Sta=4998,5004
Exp/Cntr=0.3,0.1

Type RM Length L Ch R = 1,4584,671,671,671
BEGIN DESCRIPTION:
SYCAMORE BRANCH 10.0
END DESCRIPTION:
XS GIS Cut Line= 3
      3589175.80     10388889.72      3589965.02     10389677.06
      3590364.79     10390026.85
#Sta/Elev= 30
  4014.2  434.94  4147.3  431.44  4253.4  425.66  4366.5  416.72  4402.5  411.47
  4536.2  395.02  4728.3  383.49  4747.1  380.85  4790.8  372.79  4833.2  367.02
  4950.2  362.15  4974.6  358.18  4981.7  360.39  4992.8  356.94  4995.6  356.44
  4998.8  356.94  5002.9  358.86  5010.0  357.97  5031.2  364.04  5038.3  361.97
  5045.3  362.31  5131.1  372.82  5196.2  380.07  5246.6  383.48  5342.7  397.65
  5371.1  405.59  5463.2  417.91  5534.4  432.92  5583.8  440.11  5660.2  445.54
#Mann=10,-1,0
  4014.2     0.1       0  4402.5    0.16       0  4728.3     0.1       0
  4747.1    0.16       0  4950.2    0.12       0  4992.8    0.07       0
  4998.8    0.12       0  5131.1    0.16       0  5196.2    0.12       0
  5246.6    0.16       0
Bank Sta=4992.8,4998.8
Exp/Cntr=0.3,0.1

Type RM Length L Ch R = 1,3913,719,719,719
BEGIN DESCRIPTION:
SYCAMORE BRANCH 9.0
END DESCRIPTION:
XS GIS Cut Line= 3
      3588832.05     10389624.09      3589634.12     10390113.66
      3590058.42     10390391.77
#Sta/Elev= 30
  4155.7  447.26  4213.3  446.75  4277.3  442.30  4372.1  431.65  4424.3  422.31
  4430.2  422.87  4445.6  419.36  4551.8  404.83  4729.8  382.53  4800.1  368.93
  4875.0  362.31  4890.9  361.10  4940.7  358.91  4975.9  359.35  5002.1  354.85
  5004.9  354.35  5008.1  354.85  5011.0  357.65  5020.6  359.39  5084.5  359.42
  5157.1  365.40  5244.6  381.77  5338.0  393.38  5368.0  400.36  5374.2  403.95
  5410.4  411.38  5416.3  411.21  5446.5  419.21  5518.9  430.56  5602.7  440.01
#Mann=6,-1,0
  4155.7    0.05       0  4551.8    0.16       0  4875.0    0.12       0
  4890.9    0.16       0  5002.1    0.07       0  5008.1    0.16       0
Bank Sta=5002.1,5008.1
Exp/Cntr=0.3,0.1

Type RM Length L Ch R = 1,3194,536,536,536
BEGIN DESCRIPTION:
SYCAMORE BRANCH 7.0
END DESCRIPTION:
XS GIS Cut Line= 3
      3588630.64     10390308.31      3588880.65     10390458.31
      3589925.76     10390832.40
#Sta/Elev= 30
  4287.2  426.54  4363.2  424.18  4400.1  419.46  4421.5  418.99  4458.5  413.11
  4538.1  408.45  4553.7  405.50  4599.9  402.43  4697.5  388.21  4753.7  383.55
  4809.9  374.37  4907.1  363.36  4952.1  356.56  4973.3  356.38  4983.9  354.70
  4991.5  350.96  4994.3  350.46  4997.5  350.96  5020.0  356.53  5090.1  356.03
  5203.8  359.76  5249.4  362.64  5366.3  374.57  5472.5  389.11  5527.1  393.94
  5568.1  401.03  5589.3  407.23  5644.9  417.50  5670.3  426.43  5688.8  429.46
#Mann=5,-1,0
  4287.2    0.16       0  4907.1    0.12       0  4991.5    0.07       0
  4997.5    0.12       0  5203.8    0.16       0
Bank Sta=4991.5,4997.5
Exp/Cntr=0.3,0.1

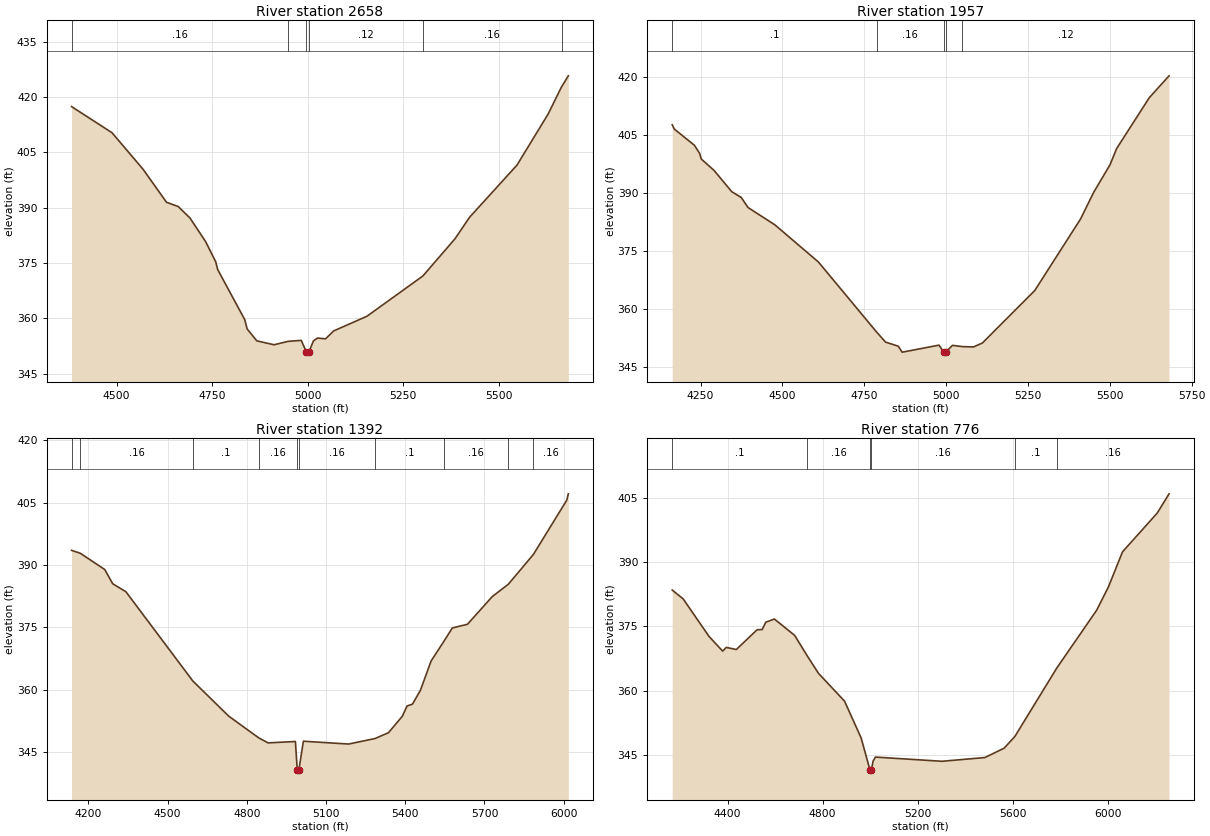
Type RM Length L Ch R = 1,2658,701,701,701
BEGIN DESCRIPTION:
SYCAMORE BRANCH 6.0
END DESCRIPTION:
XS GIS Cut Line= 3
      3588549.36     10390914.55      3588999.40     10391014.56
      3589792.14     10391291.66
#Sta/Elev= 30
  4381.9  417.44  4488.0  410.34  4569.1  400.46  4630.6  391.49  4661.3  390.33
  4692.0  387.23  4733.0  380.83  4759.5  375.35  4764.6  373.25  4835.5  359.66
  4841.7  357.16  4867.0  353.91  4912.2  352.85  4949.4  353.78  4983.5  354.04
  4997.1  350.81  4999.8  350.31  5003.1  350.81  5015.3  353.89  5025.8  354.66
  5047.1  354.46  5068.2  356.60  5155.3  360.57  5302.1  371.52  5386.0  381.59
  5424.1  387.42  5548.3  401.57  5629.7  415.39  5665.0  422.80  5682.7  425.77
#Mann=6,-1,0
  4381.9    0.16       0  4949.4    0.12       0  4997.1    0.07       0
  5003.1    0.12       0  5302.1    0.16       0  5665.0    0.12       0
Bank Sta=4997.1,5003.1
Exp/Cntr=0.3,0.1

Type RM Length L Ch R = 1,1957,565,565,565
BEGIN DESCRIPTION:
SYCAMORE BRANCH 4.0
END DESCRIPTION:
XS GIS Cut Line= 3
      3588175.82     10391488.67      3589072.31     10391684.35
      3589672.32     10391684.35
#Sta/Elev= 30
  4163.3  407.54  4169.7  406.45  4231.1  402.27  4247.0  400.18  4252.2  398.71
  4291.0  395.79  4345.1  390.29  4374.4  388.78  4394.9  386.20  4476.8  381.74
  4609.9  372.14  4787.5  354.08  4815.0  351.46  4853.8  350.41  4865.7  348.86
  4978.3  350.68  4992.8  348.86  4995.5  348.36  4998.8  348.86  5019.3  350.63
  5049.8  350.30  5083.3  350.21  5110.7  351.23  5270.7  364.77  5410.7  383.25
  5450.7  390.12  5500.7  397.25  5520.7  401.40  5620.7  414.56  5680.9  420.19
#Mann=5,-1,0
  4163.3     0.1       0  4787.5    0.16       0  4992.8    0.07       0
  4998.8    0.16       0  5049.8    0.12       0
Bank Sta=4992.8,4998.8
Exp/Cntr=0.3,0.1

Type RM Length L Ch R = 1,1392,616,616,616
BEGIN DESCRIPTION:
SYCAMORE BRANCH 3.0
END DESCRIPTION:
XS GIS Cut Line= 3
      3588016.09     10392204.14      3588616.06     10392204.14
      3589888.24     10392051.29
#Sta/Elev= 30
  4136.3  393.52  4169.4  392.82  4262.3  388.90  4292.3  385.48  4342.3  383.57
  4595.7  362.11  4731.8  353.65  4845.4  348.43  4880.7  347.23  4984.1  347.56
  4991.2  340.70  4993.9  340.20  4997.2  340.70  5014.3  347.63  5185.5  346.95
  5285.9  348.28  5336.6  349.68  5389.0  353.63  5407.1  356.11  5427.2  356.53
  5457.5  359.87  5497.8  366.90  5545.5  371.56  5578.3  374.86  5635.6  375.74
  5729.4  382.39  5790.4  385.37  5885.2  392.52  6011.4  405.55  6017.6  407.10
#Mann=10,-1,0
  4136.3     0.1       0  4169.4    0.16       0  4595.7     0.1       0
  4845.4    0.16       0  4991.2    0.07       0  4997.2    0.16       0
  5285.9     0.1       0  5545.5    0.16       0  5790.4     0.1       0
  5885.2    0.16       0
Bank Sta=4991.2,4997.2
Exp/Cntr=0.3,0.1

Type RM Length L Ch R = 1,776,0,0,0
BEGIN DESCRIPTION:
SYCAMORE BRANCH 1.0
END DESCRIPTION:
XS GIS Cut Line= 4
      3588108.06     10392441.78      3588484.27     10392684.68
      3589337.24     10392676.16      3590028.52     10392291.54
#Sta/Elev= 30
  4167.2  383.48  4213.4  381.41  4322.2  372.66  4379.6  369.23  4394.8  370.09
  4437.1  369.60  4524.8  374.22  4545.9  374.26  4561.1  375.97  4597.4  376.72
  4682.8  372.90  4736.1  368.09  4782.9  364.06  4892.9  357.55  4962.9  348.94
  4999.9  341.49  5002.6  340.99  5005.9  341.49  5012.9  343.55  5022.9  344.50
  5302.9  343.52  5483.5  344.39  5564.6  346.57  5610.0  349.32  5787.3  365.35
  5954.2  378.76  6003.8  384.19  6063.2  392.39  6209.6  401.46  6259.1  405.93
#Mann=6,-1,0
  4167.2     0.1       0  4736.1    0.16       0  4999.9    0.07       0
  5005.9    0.16       0  5610.0     0.1       0  5787.3    0.16       0
Bank Sta=4999.9,5005.9
Exp/Cntr=0.3,0.1

Chan Stop Cuts=-1