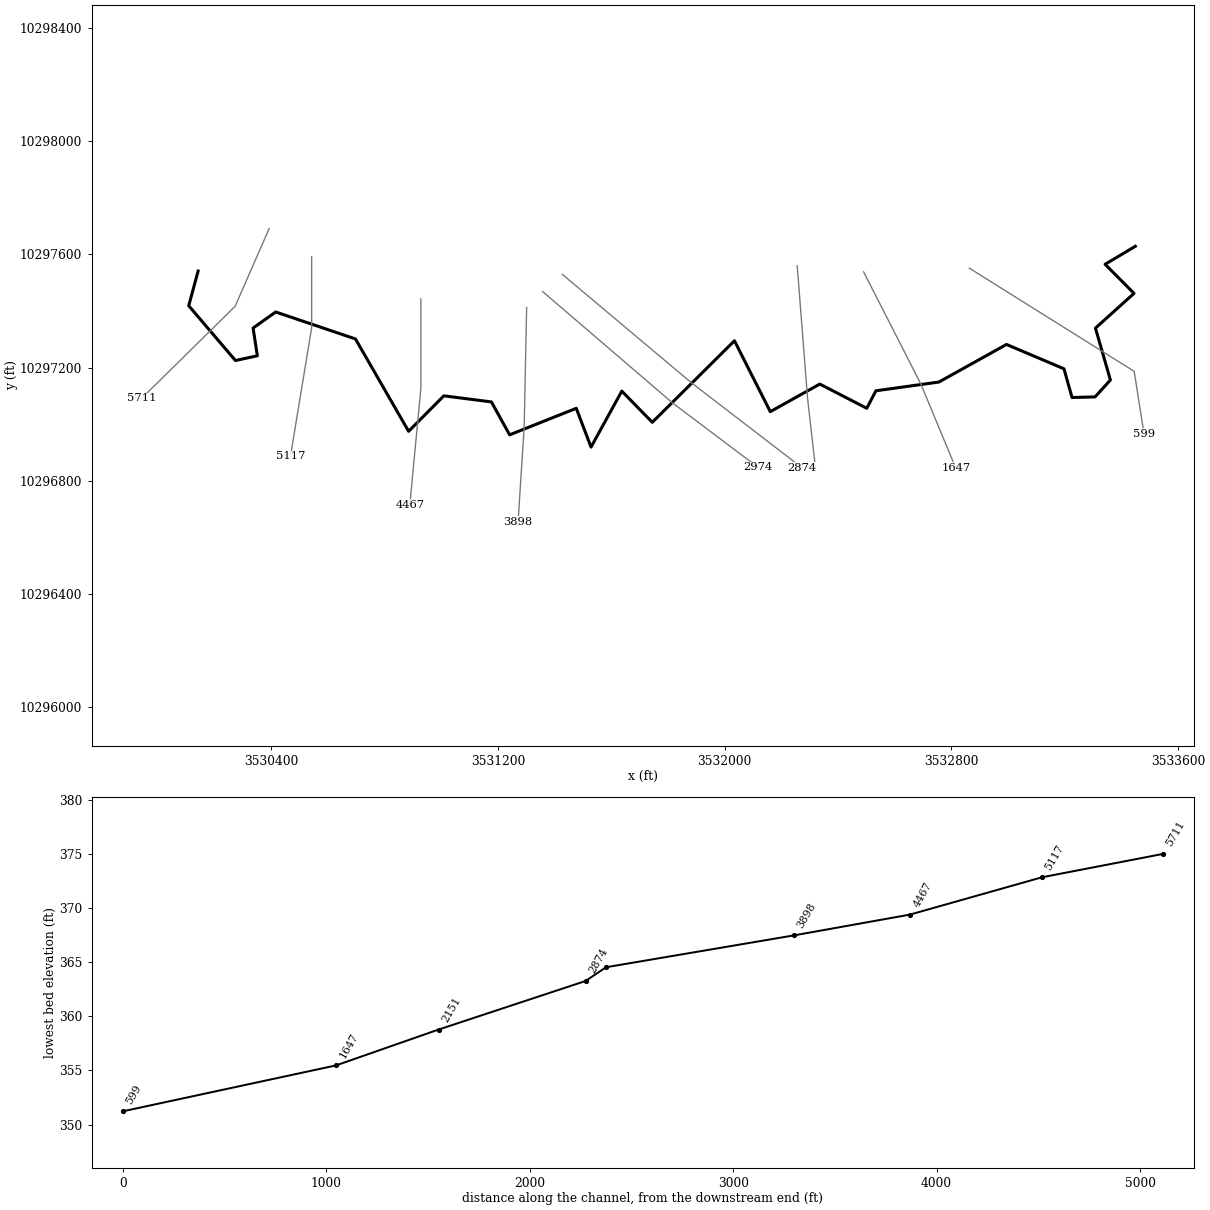
--- TIGER BRANCH TRIBUTARY 1.prj (project) ---

Proj Title=TIGER BRANCH TRIBUTARY 1 Base Level Engineering
Current Plan=p01
Default Exp/Contr=0.3,0.1
English Units
Geom File=g01
Flow File=f01
Plan File=p01
Y Axis Title=Elevation
X Axis Title(PF)=Main Channel Distance
X Axis Title(XS)=Station
BEGIN DESCRIPTION:
TIGER BRANCH TRIBUTARY 1
END DESCRIPTION:
DSS Export Rating Curves= 0
DSS Export Rating Curve Sorted= 0
DSS Export Volume Flow Curves= 0
DXF OffsetX= 0
DXF OffsetY= 0
DXF ScaleX= 1
DXF ScaleY= 10

--- TIGER BRANCH TRIBUTARY 1.p01 (plan) ---

Plan Title=Multiple Run
Short Identifier=Multiple
Geom File=g01
Flow File=f01
Subcritical Flow
K Sum by GR= 0
Std Step Tol= 0.01
Critical Tol= 0.01
Num of Std Step Trials= 20
Max Error Tol= 0.3
Flow Tol Ratio= 0.001
Split Flow NTrial= 30
Split Flow Tol= 0.02
Split Flow Ratio= 0.02
Log Output Level= 0
Friction Slope Method= 1
Unsteady Friction Slope Method= 2
Unsteady Bridges Friction Slope Method= 1
Parabolic Critical Depth
Global Vel Dist=  1 , 1 , 1
Global Log Level= 0
CheckData=True
Encroach Param= -1, 0, 0, 0
BEGIN DESCRIPTION:
Multiple Run
END DESCRIPTION:

--- TIGER BRANCH TRIBUTARY 1.f01 (steady flow) ---

Flow Title=Multiple
Number of Profiles=7
Profile Names=10-year,25-year,50-year,1pct_min,100-year,1pct_plu,500-year
River Rch & RM= TIGER BRANCH TRI,Reach-1,5711
     455     607     728     641     867    1172    1231
Boundary for River Rch & Prof#=TIGER BRANCH TRI,Reach-1,1
Up Type=0
Dn Type=3
Dn Slope=0.005
Boundary for River Rch & Prof#=TIGER BRANCH TRI,Reach-1,2
Up Type=0
Dn Type=3
Dn Slope=0.005
Boundary for River Rch & Prof#=TIGER BRANCH TRI,Reach-1,3
Up Type=0
Dn Type=3
Dn Slope=0.005
Boundary for River Rch & Prof#=TIGER BRANCH TRI,Reach-1,4
Up Type=0
Dn Type=3
Dn Slope=0.005
Boundary for River Rch & Prof#=TIGER BRANCH TRI,Reach-1,5
Up Type=0
Dn Type=3
Dn Slope=0.005
Boundary for River Rch & Prof#=TIGER BRANCH TRI,Reach-1,6
Up Type=0
Dn Type=3
Dn Slope=0.005
Boundary for River Rch & Prof#=TIGER BRANCH TRI,Reach-1,7
Up Type=0
Dn Type=3
Dn Slope=0.005

--- TIGER BRANCH TRIBUTARY 1.g01 (geometry) ---

Geom Title=Existing Conditions
Program Version=4.10

River Reach=TIGER BRANCH TRI,Reach-1
Reach XY= 30
      3530141.36     10297541.51       3530108.2     10297418.87
      3530273.09     10297225.28      3530350.45     10297242.06
      3530335.33     10297340.06      3530415.19     10297396.79
      3530696.65     10297301.51      3530884.16     10296975.18
      3531008.49     10297100.51       3531176.4     10297078.96
      3531240.64     10296962.64      3531475.88     10297056.39
      3531527.96     10296919.24      3531636.47     10297117.16
      3531744.11     10297006.91      3532034.04     10297295.11
      3532160.55     10297044.51      3532335.22      10297142.1
        3532501.     10297056.45      3532533.24     10297118.36
      3532755.52     10297149.21      3532994.11     10297282.09
      3533196.89     10297195.98      3533225.36     10297094.59
      3533306.61     10297096.67      3533360.77     10297156.39
        3533308.     10297339.73      3533444.11     10297462.64
      3533342.02     10297565.42      3533448.74     10297628.95

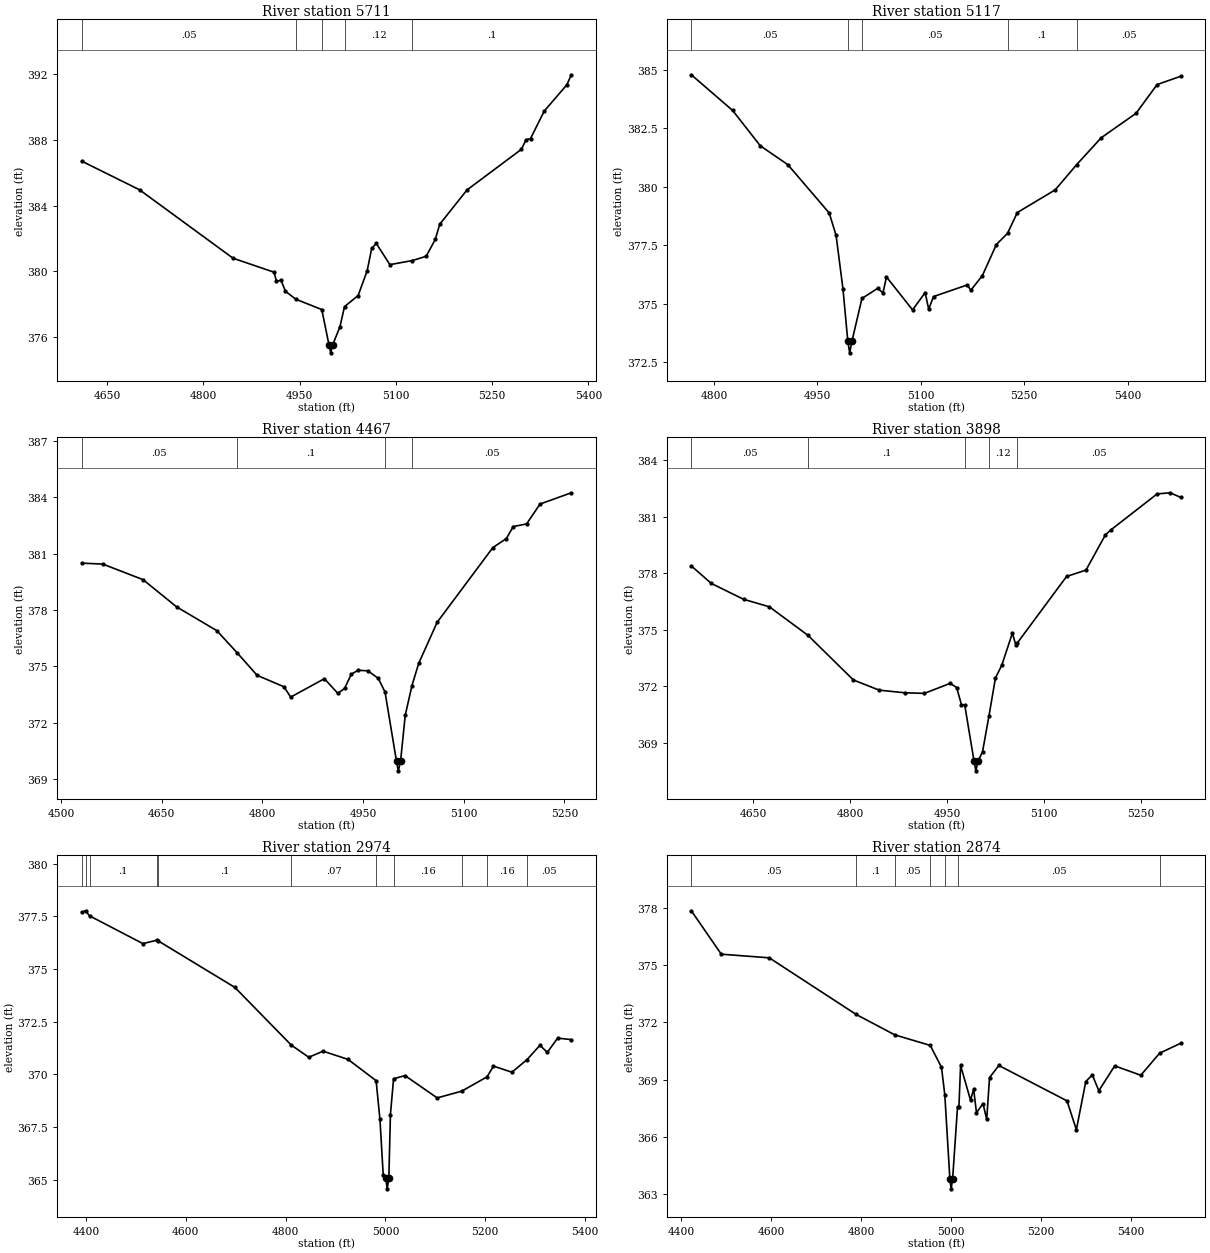
Type RM Length L Ch R = 1 ,5711    ,594,594,594
BEGIN DESCRIPTION:
TIGER BRANCH TRIBUTARY 1 9.0
END DESCRIPTION:
XS GIS Cut Line= 3
      3530392.12     10297691.66      3530272.02       10297417.
      3529942.13     10297091.66
#Sta/Elev= 30
  4610.3   386.7  4700.4  384.96  4846.2   380.8  4910.1  379.95  4913.8   379.4
  4920.9  379.46  4927.9  378.79    4944  378.31  4984.5  377.68  4995.6  375.55
  4998.4  375.05  5001.6  375.55  5012.8  376.64  5019.9  377.86  5041.1  378.53
  5055.2  380.04  5062.3   381.4  5069.4   381.7  5090.6  380.41  5125.8  380.66
  5147.2  380.92  5161.3  381.94  5168.4  382.87  5210.8  384.95  5295.6  387.42
  5302.8     388  5309.8  388.07  5331.1  389.74  5366.4  391.34  5373.4  391.95
#Mann= 5 ,-1 , 0
  4610.3     .05       0    4944     .12       0  4984.5     .07       0
  5019.9     .12       0  5125.8      .1       0
Bank Sta=4995.6,5001.6
XS Rating Curve= 0 ,0
Exp/Cntr=0.3,0.1

Type RM Length L Ch R = 1 ,5117    ,650,650,650
BEGIN DESCRIPTION:
TIGER BRANCH TRIBUTARY 1 8.0
END DESCRIPTION:
XS GIS Cut Line= 3
      3530542.11     10297591.59      3530542.11     10297341.64
      3530467.34     10296887.51
#Sta/Elev= 30
    4767   384.8    4827  383.27    4867  381.76    4907  380.95    4967  378.88
    4977  377.92    4987  375.62    4994  373.39  4996.7  372.89    5000  373.39
  5014.5  375.22  5037.2  375.65    5045  375.46  5050.1  376.14  5087.9  374.73
  5106.2  375.47  5111.3  374.76  5118.3   375.3  5167.4   375.8  5172.4  375.57
  5189.2   376.2  5209.5  377.53  5225.7  378.01  5239.9   378.9  5294.8  379.87
  5325.9  380.95  5361.5   382.1  5412.1  383.15  5442.6  384.38  5477.2  384.74
#Mann= 5 ,-1 , 0
    4767     .05       0    4994     .07       0  5014.5     .05       0
  5225.7      .1       0  5325.9     .05       0
Bank Sta=4994,5000
XS Rating Curve= 0 ,0
Exp/Cntr=0.3,0.1

Type RM Length L Ch R = 1 ,4467    ,569,569,569
BEGIN DESCRIPTION:
TIGER BRANCH TRIBUTARY 1 7.0
END DESCRIPTION:
XS GIS Cut Line= 3
      3530927.41       10297443.      3530927.41      10297126.2
      3530888.47     10296715.24
#Sta/Elev= 30
  4530.6   380.5    4562  380.45    4622  379.62    4672  378.17    4732   376.9
    4762  375.73    4792  374.52    4832  373.91    4842  373.36  4892.2  374.34
  4912.3  373.56  4922.3  373.82  4932.3  374.58  4942.4  374.79    4957  374.76
  4972.5  374.36  4982.6  373.63  4999.7  369.93  5002.4  369.43  5005.7  369.93
  5012.7  372.39  5022.7  373.97  5032.8  375.16  5060.3  377.35  5143.3  381.33
  5163.4  381.81  5173.6  382.45  5193.5  382.59  5213.6  383.65  5260.2  384.25
#Mann= 4 ,-1 , 0
  4530.6     .05       0    4762      .1       0  4982.6     .07       0
  5022.7     .05       0
Bank Sta=4999.7,5005.7
XS Rating Curve= 0 ,0
Exp/Cntr=0.3,0.1

Type RM Length L Ch R = 1 ,3898    ,924,924,924
BEGIN DESCRIPTION:
TIGER BRANCH TRIBUTARY 1 6.0
END DESCRIPTION:
XS GIS Cut Line= 3
      3531300.67     10297412.65      3531292.11     10296991.64
       3531270.4     10296654.84
#Sta/Elev= 30
    4554  378.38    4585  377.45    4635  376.61    4675  376.21    4735  374.69
  4805.1  372.33  4845.1  371.79  4885.1  371.65  4915.1  371.62  4955.1  372.15
  4965.1  371.93  4972.6  371.01  4977.6  371.01  4992.1  368.01  4994.9  367.51
  4998.1  368.01  5005.2  368.52  5015.2  370.43  5025.2  372.43  5035.2  373.13
  5051.5  374.82  5056.6   374.2  5058.6  374.27  5135.4  377.82  5165.5  378.16
  5195.6  380.03  5204.4   380.3  5275.7   382.2  5295.8  382.26  5312.6  382.01
#Mann= 5 ,-1 , 0
    4554     .05       0    4735      .1       0  4977.6     .07       0
  5015.2     .12       0  5058.6     .05       0
Bank Sta=4992.1,4998.1
XS Rating Curve= 0 ,0
Exp/Cntr=0.3,0.1

Type RM Length L Ch R = 1 ,2974    ,100,100,100
BEGIN DESCRIPTION:
TIGER BRANCH TRIBUTARY 1 5.0
END DESCRIPTION:
XS GIS Cut Line= 3
      3531357.07      10297469.1      3531817.16     10297074.12
      3532116.66     10296848.41
#Sta/Elev= 30
  4391.3   377.7  4398.9  377.77    4407  377.53  4513.9  376.21  4541.7  376.37
  4544.6  376.34  4698.3  374.13  4811.3  371.39  4846.5  370.81    4875   371.1
  4925.1  370.71  4981.4   369.7  4989.1  367.86  4995.7   365.2  5000.9  365.06
  5003.6  364.56  5006.9  365.06  5010.1  368.09  5016.4  369.79  5039.3  369.94
  5103.8  368.88    5153   369.2  5203.7  369.88  5216.7  370.39  5253.7   370.1
  5283.9   370.7  5309.9  371.38  5324.5  371.04  5345.3  371.72  5372.7  371.65
#Mann= 11 ,-1 , 0
  4391.3      .1       0  4398.9     .05       0    4407      .1       0
  4541.7     .05       0  4544.6      .1       0  4811.3     .07       0
  4981.4     .05       0  5016.4     .16       0    5153     .05       0
  5203.7     .16       0  5283.9     .05       0
Bank Sta=5000.9,5006.9
XS Rating Curve= 0 ,0
Exp/Cntr=0.3,0.1

Type RM Length L Ch R = 1 ,2874    ,723,723,723
BEGIN DESCRIPTION:
TIGER BRANCH TRIBUTARY 1 4.0
END DESCRIPTION:
XS GIS Cut Line= 3
      3531426.54     10297529.85      3531881.74     10297147.05
       3532272.8     10296846.13
#Sta/Elev= 30
  4423.1  377.83  4489.7  375.56  4596.3  375.37  4789.4  372.41  4875.4  371.34
  4954.1  370.79  4979.1  369.65  4986.5   368.2  4997.8  363.79  5000.6  363.29
  5003.8  363.79  5014.8  367.59  5017.9  367.59  5021.6  369.74  5043.6  367.93
  5050.6   368.5  5056.9  367.27  5071.4  367.75  5079.6  366.92  5085.9  369.11
  5106.7  369.74  5258.1  367.89  5278.9  366.38  5299.8   368.9  5314.3  369.25
  5328.8  368.42  5364.1  369.72  5422.1  369.23  5463.8  370.38  5511.3  370.91
#Mann= 7 ,-1 , 0
  4423.1     .05       0  4789.4      .1       0  4875.4     .05       0
  4954.1     .16       0  4986.5     .05       0  5014.8     .05       0
  5463.8     .08       0
Bank Sta=4997.8,5003.8
XS Rating Curve= 0 ,0
Exp/Cntr=0.3,0.1

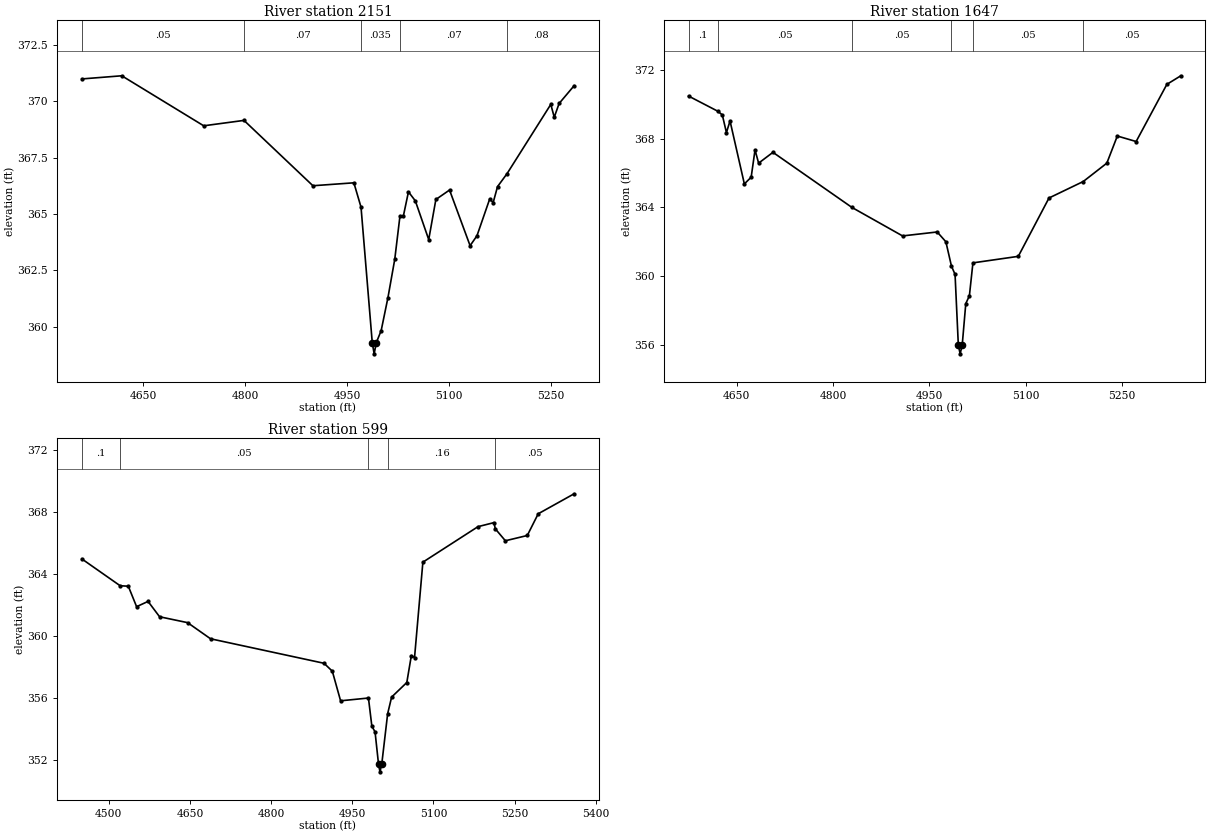
Type RM Length L Ch R = 1 ,2151    ,504,504,504
BEGIN DESCRIPTION:
TIGER BRANCH TRIBUTARY 1 3.0
END DESCRIPTION:
XS GIS Cut Line= 3
      3532255.53     10297560.19      3532292.11     10297091.64
      3532320.64     10296839.72
#Sta/Elev= 30
  4560.1  370.99  4618.8  371.13  4739.2  368.91  4798.4  369.15  4899.7  366.25
  4959.9  366.38  4970.4   365.3  4986.9  359.29  4989.7  358.79  4992.9  359.29
    5000  359.82    5010  361.29    5020  362.99  5027.6   364.9  5032.6   364.9
  5040.1  365.98  5050.2  365.58  5069.9  363.86  5080.4  365.64  5100.5  366.06
  5130.7  363.59  5140.8  364.03  5159.6  365.67  5164.6   365.5    5171  366.21
  5185.1  366.79  5249.3  369.86  5254.4  369.29  5261.5   369.9  5283.6  370.69
#Mann= 5 ,-1 , 0
  4560.1     .05       0  4798.4     .07       0  4970.4    .035       0
  5027.6     .07       0  5185.1     .08       0
Bank Sta=4986.9,4992.9
XS Rating Curve= 0 ,0
Exp/Cntr=0.3,0.1

Type RM Length L Ch R = 1 ,1647    ,1048,1048,1048
BEGIN DESCRIPTION:
TIGER BRANCH TRIBUTARY 1 2.0
END DESCRIPTION:
XS GIS Cut Line= 3
      3532489.93     10297538.49      3532692.11     10297141.64
       3532814.9     10296845.36
#Sta/Elev= 30
    4575  370.49  4620.3  369.61  4627.6  369.39    4634  368.36  4639.6  369.04
  4661.9  365.37  4672.5  365.76  4678.5  367.35  4684.1  366.58  4706.4  367.21
  4829.3     364  4908.1  362.34    4962  362.57  4975.5     362  4984.2  360.58
  4989.8   360.1  4994.9  355.97  4997.7  355.47  5000.9  355.97  5006.5   358.4
  5012.1  358.85  5017.6  360.77  5088.2  361.15    5136  364.55  5189.3  365.51
    5226  366.58  5242.3  368.16  5271.6  367.84  5319.4  371.17  5341.1  371.67
#Mann= 6 ,-1 , 0
    4575      .1       0  4620.3     .05       0  4829.3     .05       0
  4984.2    .035       0  5017.6     .05       0  5189.3     .05       0
Bank Sta=4994.9,5000.9
XS Rating Curve= 0 ,0
Exp/Cntr=0.3,0.1

Type RM Length L Ch R = 1 ,599     ,0,0,0
BEGIN DESCRIPTION:
TIGER BRANCH TRIBUTARY 1 1.0
END DESCRIPTION:
XS GIS Cut Line= 3
      3532863.17     10297551.55      3533444.77     10297186.97
      3533479.41     10296966.09
#Sta/Elev= 30
  4450.1  364.95  4520.9  363.22    4536  363.19  4551.3  361.87  4572.5  362.21
  4593.8  361.22  4645.6  360.84    4688   359.8  4897.8  358.22  4913.1  357.71
  4928.4   355.8  4979.9  355.98  4986.2  354.16  4992.1   353.8  4998.5  351.72
  5001.2  351.22  5004.5  351.72  5015.4  354.97  5022.7  356.04  5050.8  356.98
  5059.2  358.72  5065.1  358.59  5080.5  364.74  5182.4  367.03  5211.9  367.29
  5214.4  366.89    5233  366.12  5273.5  366.46  5293.7  367.86  5360.1  369.15
#Mann= 5 ,-1 , 0
  4450.1      .1       0  4520.9     .05       0  4979.9    .035       0
  5015.4     .16       0  5214.4     .05       0
Bank Sta=4998.5,5004.5
XS Rating Curve= 0 ,0
Exp/Cntr=0.3,0.1

Chan Stop Cuts=-1
Use User Specified Reach Order=0
Composite Channel Slope=5