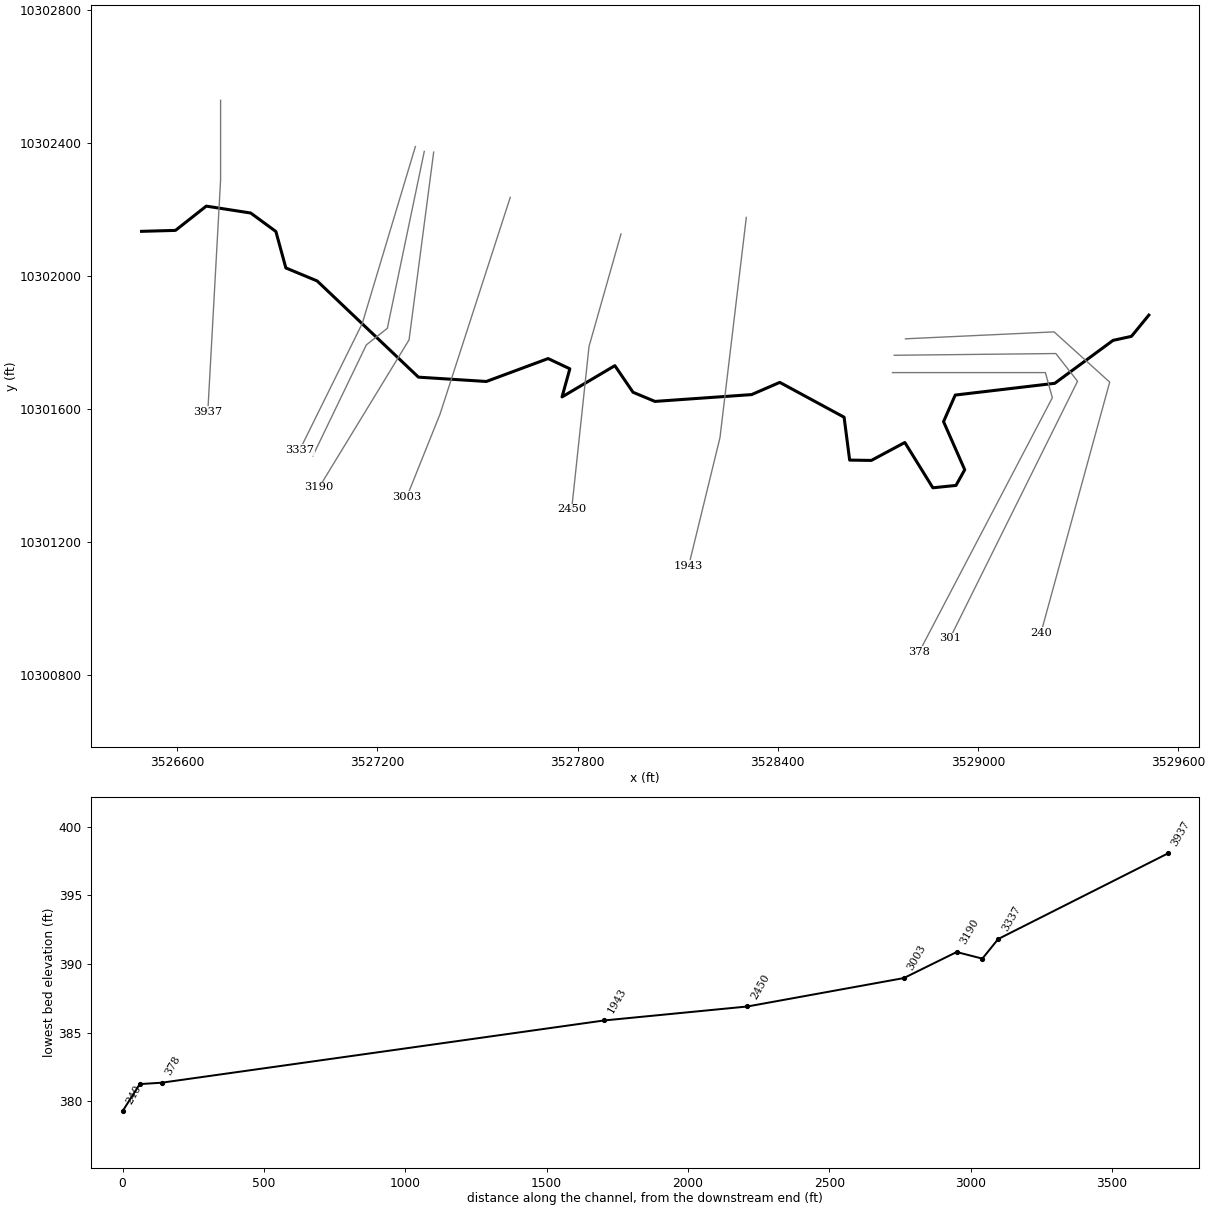
--- TIGER BRANCH TRIBUTARY 2.prj (project) ---

Proj Title=TIGER BRANCH TRIBUTARY 2 Base Level Engineering
Current Plan=p01
Default Exp/Contr=0.3,0.1
English Units
Geom File=g01
Flow File=f01
Plan File=p01
Y Axis Title=Elevation
X Axis Title(PF)=Main Channel Distance
X Axis Title(XS)=Station
BEGIN DESCRIPTION:
TIGER BRANCH TRIBUTARY 2
END DESCRIPTION:
DSS Export Rating Curves= 0
DSS Export Rating Curve Sorted= 0
DSS Export Volume Flow Curves= 0
DXF OffsetX= 0
DXF OffsetY= 0
DXF ScaleX= 1
DXF ScaleY= 10

--- TIGER BRANCH TRIBUTARY 2.p01 (plan) ---

Plan Title=Multiple Run
Short Identifier=Multiple
Geom File=g01
Flow File=f01
Subcritical Flow
K Sum by GR= 0
Std Step Tol= 0.01
Critical Tol= 0.01
Num of Std Step Trials= 20
Max Error Tol= 0.3
Flow Tol Ratio= 0.001
Split Flow NTrial= 30
Split Flow Tol= 0.02
Split Flow Ratio= 0.02
Log Output Level= 0
Friction Slope Method= 1
Unsteady Friction Slope Method= 2
Unsteady Bridges Friction Slope Method= 1
Parabolic Critical Depth
Global Vel Dist=  1 , 1 , 1
Global Log Level= 0
CheckData=True
Encroach Param= -1, 0, 0, 0
BEGIN DESCRIPTION:
Multiple Run
END DESCRIPTION:

--- TIGER BRANCH TRIBUTARY 2.f01 (steady flow) ---

Flow Title=Multiple
Number of Profiles=7
Profile Names=10-year,25-year,50-year,1pct_min,100-year,1pct_plu,500-year
River Rch & RM= TIGER BRANCH TRI,Reach-1,3937
     490     658     794     703     951    1286    1365
Boundary for River Rch & Prof#=TIGER BRANCH TRI,Reach-1,1
Up Type=0
Dn Type=3
Dn Slope=0.005
Boundary for River Rch & Prof#=TIGER BRANCH TRI,Reach-1,2
Up Type=0
Dn Type=3
Dn Slope=0.005
Boundary for River Rch & Prof#=TIGER BRANCH TRI,Reach-1,3
Up Type=0
Dn Type=3
Dn Slope=0.005
Boundary for River Rch & Prof#=TIGER BRANCH TRI,Reach-1,4
Up Type=0
Dn Type=3
Dn Slope=0.005
Boundary for River Rch & Prof#=TIGER BRANCH TRI,Reach-1,5
Up Type=0
Dn Type=3
Dn Slope=0.005
Boundary for River Rch & Prof#=TIGER BRANCH TRI,Reach-1,6
Up Type=0
Dn Type=3
Dn Slope=0.005
Boundary for River Rch & Prof#=TIGER BRANCH TRI,Reach-1,7
Up Type=0
Dn Type=3
Dn Slope=0.005

--- TIGER BRANCH TRIBUTARY 2.g01 (geometry) ---

Geom Title=Existing Conditions
Program Version=4.10

River Reach=TIGER BRANCH TRI,Reach-1
Reach XY= 30
      3526493.45     10302133.47      3526595.17     10302136.31
      3526687.45     10302209.24      3526820.66      10302188.5
      3526896.06     10302133.01      3526925.97     10302023.45
      3527019.72     10301984.38      3527323.25     10301695.17
      3527526.81     10301682.19      3527711.87     10301751.02
      3527776.98     10301720.28      3527753.63     10301635.78
      3527911.91     10301729.75      3527966.36     10301649.74
      3528031.99     10301622.27      3528321.69     10301642.75
      3528406.12     10301679.46      3528598.85     10301574.78
      3528615.52     10301445.87      3528680.48     10301444.89
      3528780.89     10301498.82      3528864.84     10301362.64
      3528934.16     10301369.73      3528960.36     10301416.92
      3528896.89     10301561.46      3528931.92     10301641.35
      3529230.22     10301676.66      3529404.92     10301805.78
      3529459.98     10301817.81      3529512.11     10301881.64

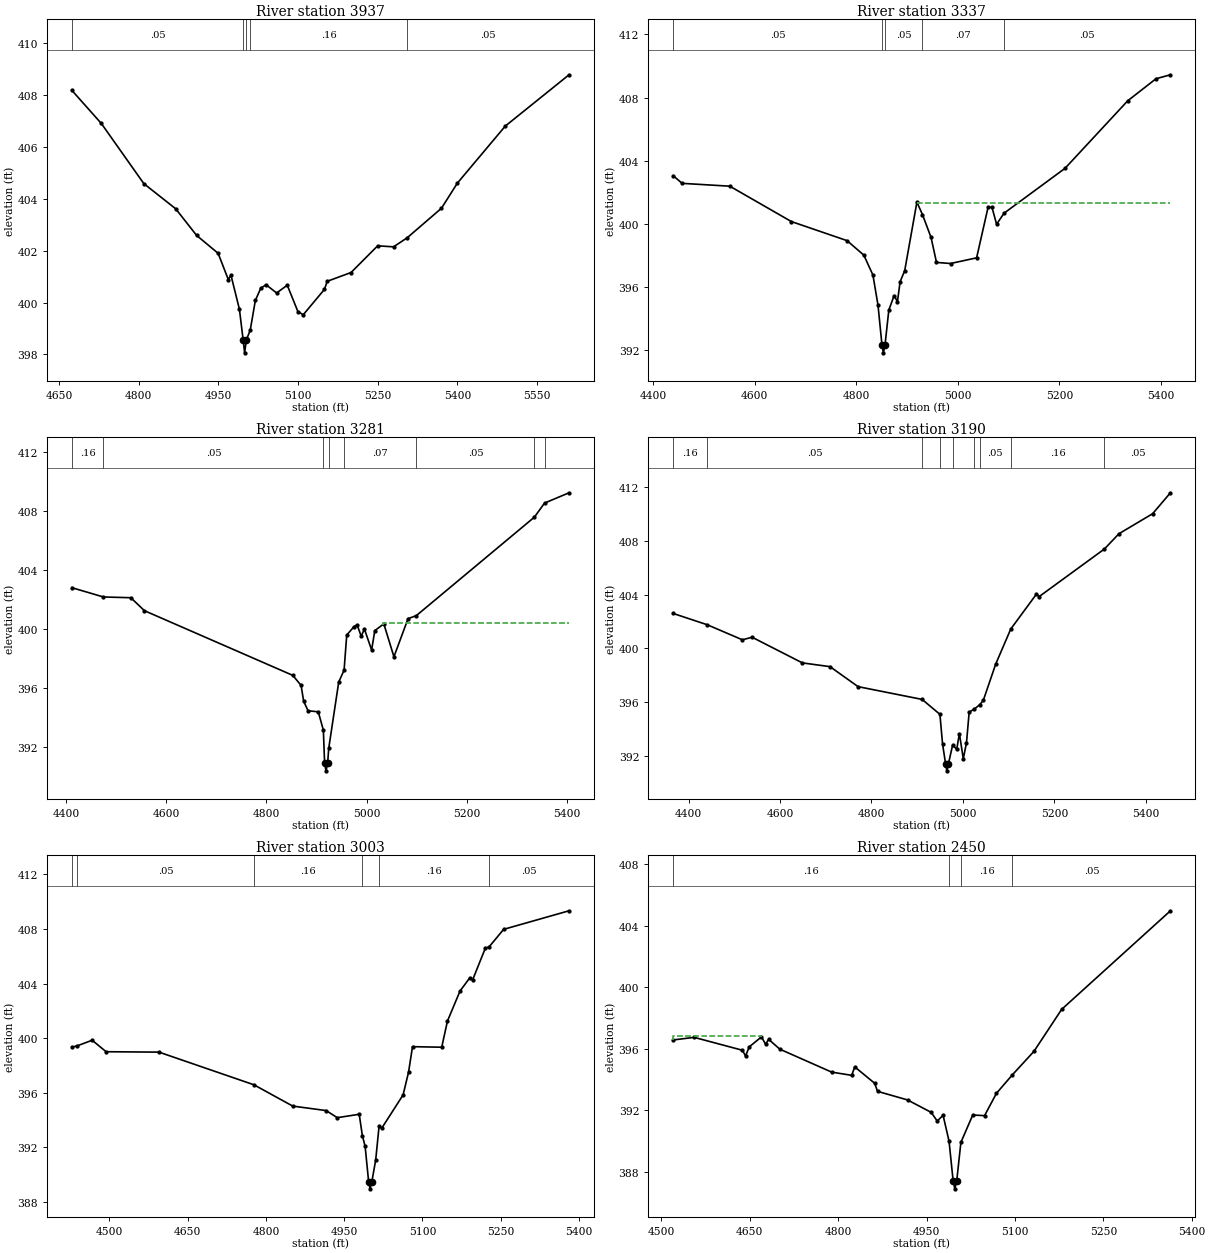
Type RM Length L Ch R = 1 ,3937    ,600,600,600
BEGIN DESCRIPTION:
TIGER BRANCH TRIBUTARY 2 6.0
END DESCRIPTION:
XS GIS Cut Line= 3
      3526730.36     10302527.23      3526730.36     10302287.66
      3526692.11     10301591.68
#Sta/Elev= 30
  4673.8  408.19  4729.4  406.91  4809.4  404.59  4869.4  403.62  4908.9  402.59
  4949.4   401.9  4968.5  400.89  4973.5  401.06  4989.5  399.74  4996.5  398.56
  4999.3  398.06  5002.5  398.56  5009.8  398.93  5019.5  400.08  5029.6  400.55
  5039.6  400.69  5059.6  400.37  5079.6  400.67  5099.7  399.65  5109.7  399.53
  5149.7  400.51  5154.8  400.82  5199.8  401.16  5249.9  402.19  5279.9  402.15
  5305.5   402.5  5370.1  403.64  5400.1  404.61  5490.3  406.81  5610.4  408.79
#Mann= 5 ,-1 , 0
  4673.8     .05       0  4996.5     .03       0  5002.5     .05       0
  5009.8     .16       0  5305.5     .05       0
Bank Sta=4996.5,5002.5
XS Rating Curve= 0 ,0
Exp/Cntr=0.3,0.1

Type RM Length L Ch R = 1 ,3337    ,56,56,56
BEGIN DESCRIPTION:
TIGER BRANCH TRIBUTARY 2 5.0
END DESCRIPTION:
XS GIS Cut Line= 3
      3527314.14     10302388.39      3527155.04     10301856.92
      3526967.38     10301476.13
#Sta/Elev= 30
  4439.3  403.04  4456.8  402.56  4550.7  402.38  4671.9  400.14  4781.6  398.93
  4814.7  398.01  4832.6  396.75  4842.6  394.84  4850.4  392.32  4853.2  391.82
  4856.4  392.32  4863.9  394.53  4874.3  395.45  4880.9  395.06  4886.1  396.32
  4895.2  397.03  4919.2  401.37  4930.2  400.58  4947.1  399.13  4957.8  397.55
  4985.4  397.48  5036.8  397.84  5059.3  401.03  5066.9  401.06  5076.2  399.97
  5090.9  400.67  5210.9  403.51  5334.4  407.79  5390.2  409.19  5418.6  409.44
#Mann= 5 ,-1 , 0
  4439.3     .05       0  4850.4     .07       0  4856.4     .05       0
  4930.2     .07       0  5090.9     .05       0
#XS Ineff= 2 , 0
                          4918.9          401.32
Permanent Ineff=
       F       F
Bank Sta=4850.4,4856.4
XS Rating Curve= 0 ,0
Exp/Cntr=0.3,0.1

Type RM Length L Ch R = 1 ,3281    ,91,91,91
BEGIN DESCRIPTION:
Mapping XS 85a7f2e2
END DESCRIPTION:
XS GIS Cut Line= 4
      3527340.74     10302373.73      3527230.07     10301842.05
      3527167.13     10301792.13      3527006.84     10301458.56
#Sta/Elev= 30
  4411.2   402.8  4474.3  402.17    4529  402.12  4556.3  401.24  4852.6  396.86
  4869.3  396.18  4874.4  395.11  4883.2  394.46  4903.6  394.39  4913.8  393.15
  4916.3  390.89  4919.1  390.39  4922.3  390.89  4924.5  391.91  4944.5  396.41
  4955.2  397.21  4960.5  399.59    4975  400.16  4981.3  400.28  4989.4  399.51
  4995.8     400  5010.2  398.58  5016.6  399.89  5034.6  400.35  5054.8  398.12
    5083   400.7  5099.7  400.91  5335.5  407.58  5355.7  408.53  5404.7  409.23
#Mann= 8 ,-1 , 0
  4411.2     .16       0  4474.3     .05       0  4913.8     .07       0
  4924.5     .05       0  4955.2     .07       0  5099.7     .05       0
  5335.5     .16       0  5355.7     .05       0
#XS Ineff= 2 , 0
                         5032.27          400.43
Permanent Ineff=
       F       F
Bank Sta=4916.3,4922.3
XS Rating Curve= 0 ,0
Exp/Cntr=0.3,0.1

Type RM Length L Ch R = 1 ,3190    ,187,187,187
BEGIN DESCRIPTION:
Mapping XS 1b8698d3
END DESCRIPTION:
XS GIS Cut Line= 3
      3527368.96      10302371.6      3527295.17     10301807.32
      3527026.05     10301364.58
#Sta/Elev= 30
  4366.6  402.59    4441  401.75  4517.8  400.63  4539.1  400.82  4648.9  398.91
  4709.4  398.63  4770.8  397.14  4910.8  396.19  4949.7  395.08  4955.5  392.87
  4962.2  391.37  4964.9  390.87  4968.2  391.37  4977.4  392.78  4986.5  392.48
  4992.3  393.65  5000.8  391.77  5007.8  392.96  5013.7  395.25  5024.5  395.46
  5036.9   395.8  5044.6  396.12  5071.8  398.83  5104.6  401.43  5160.9  404.04
  5166.8  403.85  5309.3  407.39  5341.2  408.53  5414.8  410.02  5453.8  411.58
#Mann= 9 ,-1 , 0
  4366.6     .16       0    4441     .05       0  4910.8     .16       0
  4949.7     .07       0  4977.4     .16       0  5024.5     .07       0
  5036.9     .05       0  5104.6     .16       0  5309.3     .05       0
Bank Sta=4962.2,4968.2
XS Rating Curve= 0 ,0
Exp/Cntr=0.3,0.1

Type RM Length L Ch R = 1 ,3003    ,553,553,553
BEGIN DESCRIPTION:
TIGER BRANCH TRIBUTARY 2 4.0
END DESCRIPTION:
XS GIS Cut Line= 3
      3527598.42     10302235.62      3527387.94       10301584.
      3527288.47     10301335.33
#Sta/Elev= 30
  4428.2  399.34  4438.5  399.44  4467.1  399.85  4493.9  399.01  4595.2  398.98
    4777  396.59  4851.4  395.03  4915.5   394.7  4936.8  394.18  4978.8  394.43
  4984.8  392.87  4990.1  392.09  4996.9  389.47  4999.6  388.97  5002.9  389.47
  5010.4  391.09  5016.8  393.54  5022.1  393.42  5062.9  395.85  5073.4  397.53
  5080.9  399.38  5136.9  399.34  5147.8  401.25  5171.9  403.45  5190.8  404.43
  5196.1  404.27  5220.4  406.59  5227.7  406.69  5255.5  407.97  5380.8  409.33
#Mann= 6 ,-1 , 0
  4428.2      .1       0  4438.5     .05       0    4777     .16       0
  4984.8     .07       0  5016.8     .16       0  5227.7     .05       0
Bank Sta=4996.9,5002.9
XS Rating Curve= 0 ,0
Exp/Cntr=0.3,0.1

Type RM Length L Ch R = 1 ,2450    ,507,507,507
BEGIN DESCRIPTION:
TIGER BRANCH TRIBUTARY 2 3.0
END DESCRIPTION:
XS GIS Cut Line= 3
       3527930.3     10302125.66      3527834.52     10301787.66
      3527782.43     10301298.03
#Sta/Elev= 30
  4520.2  396.58  4555.6  396.75  4637.7  395.91  4642.9  395.53  4649.1  396.13
  4669.9  396.78  4676.9   396.3  4682.1  396.62  4701.1  395.98    4789  394.49
    4823  394.28  4828.2  394.83  4862.1  393.76  4866.8  393.24  4917.8  392.68
    4958  391.87  4968.1  391.31  4978.1  391.68  4988.2     390  4995.2   387.4
    4998   386.9  5001.2   387.4  5008.3  389.92  5028.4   391.7  5048.5  391.66
  5068.6  393.11  5095.6  394.31  5132.3  395.84  5179.3  398.57  5363.9  404.98
#Mann= 4 ,-1 , 0
  4520.2     .16       0  4988.2     .07       0  5008.3     .16       0
  5095.6     .05       0
#XS Ineff= 2 , 0
         4669.62  396.84
Permanent Ineff=
       F       F
Bank Sta=4995.2,5001.2
XS Rating Curve= 0 ,0
Exp/Cntr=0.3,0.1

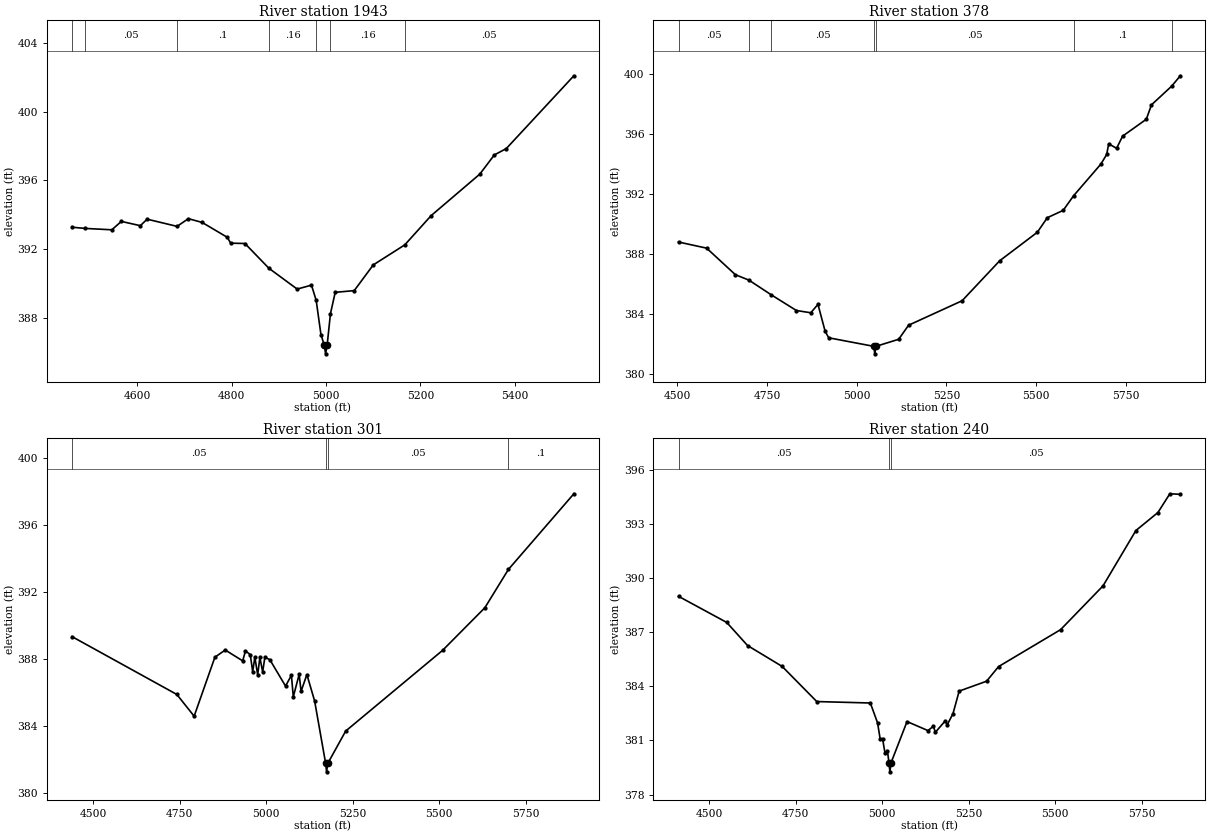
Type RM Length L Ch R = 1 ,1943    ,1565,1565,1565
BEGIN DESCRIPTION:
TIGER BRANCH TRIBUTARY 2 2.0
END DESCRIPTION:
XS GIS Cut Line= 3
      3528305.83     10302175.32      3528226.88     10301513.36
      3528133.14     10301127.95
#Sta/Elev= 30
    4462  393.27  4490.2   393.2  4546.3  393.12  4566.4  393.61  4606.7  393.36
    4621  393.74  4684.5  393.32  4708.5  393.77  4737.6  393.55    4791  392.68
    4798  392.34  4828.3  392.32  4879.3  390.87    4939  389.66  4969.3  389.89
  4979.3     389  4989.4     387  4996.5  386.38  4999.2  385.88  5002.5  386.38
  5009.5  388.22  5019.6  389.47  5059.9  389.57  5100.2  391.07    5167  392.24
    5223  393.95    5326  396.37  5356.8  397.49  5382.1  397.86  5525.3  402.11
#Mann= 7 ,-1 , 0
    4462      .1       0  4490.2     .05       0  4684.5      .1       0
  4879.3     .16       0  4979.3     .07       0  5009.5     .16       0
    5167     .05       0
Bank Sta=4996.5,5002.5
XS Rating Curve= 0 ,0
Exp/Cntr=0.3,0.1

Type RM Length L Ch R = 1 ,378     ,77,77,77
BEGIN DESCRIPTION:
Mapping XS 25be7484
END DESCRIPTION:
XS GIS Cut Line= 4
      3528743.77     10301708.87      3529202.09     10301708.87
      3529222.92     10301633.35      3528824.51     10300870.37
#Sta/Elev= 30
  4503.9   388.8  4582.2  388.39  4662.2  386.62  4699.7  386.26  4762.6  385.27
  4832.2  384.23  4872.2  384.08  4892.2  384.64  4912.2  382.84  4922.2  382.41
  5047.6  381.84  5050.4  381.34  5053.6  381.84  5116.9  382.31  5144.6  383.25
  5293.5  384.88  5398.3  387.55  5503.1  389.45  5530.8  390.42    5575  390.91
  5604.2  391.89  5679.8  393.99  5696.2  394.64  5701.8  395.35  5723.9  395.05
  5740.4  395.86  5806.6  396.99  5820.9  397.95  5877.3   399.2  5901.3  399.89
#Mann= 7 ,-1 , 0
  4503.9     .05       0  4699.7     .16       0  4762.6     .05       0
  5047.6     .03       0  5053.6     .05       0  5604.2      .1       0
  5877.3     .05       0
Bank Sta=5047.6,5053.6
XS Rating Curve= 0 ,0
Exp/Cntr=0.3,0.1

Type RM Length L Ch R = 1 ,301     ,61,61,61
BEGIN DESCRIPTION:
Mapping XS ec4d81f0
END DESCRIPTION:
XS GIS Cut Line= 4
      3528749.01     10301760.96      3529233.34     10301766.16
      3529298.44     10301682.83      3528916.39     10300910.92
#Sta/Elev= 30
  4438.2  389.33  4741.3  385.87  4791.3  384.57  4851.3   388.1  4881.3  388.53
  4931.7  387.88  4939.8  388.48  4953.7  388.25  4960.6  387.23  4966.9   388.1
  4975.1  387.04  4981.4  388.09  4989.5  387.22  4995.9   388.1  5010.3  387.95
  5055.7  386.37  5072.6  387.02  5078.1  385.73    5095  387.07  5100.6  386.06
  5117.4  387.06  5139.8  385.48  5171.7  381.74  5174.4  381.24  5177.7  381.74
  5229.6  383.68  5509.9  388.51  5632.2  391.06  5700.2  393.35  5889.6  397.88
#Mann= 4 ,-1 , 0
  4438.2     .05       0  5171.7     .03       0  5177.7     .05       0
  5700.2      .1       0
Bank Sta=5171.7,5177.7
XS Rating Curve= 0 ,0
Exp/Cntr=0.3,0.1

Type RM Length L Ch R = 1 ,240     ,0,0,0
BEGIN DESCRIPTION:
TIGER BRANCH TRIBUTARY 2 1.0
END DESCRIPTION:
XS GIS Cut Line= 4
      3528782.83     10301810.43      3529228.13     10301831.27
       3529394.8     10301680.23      3529189.08     10300927.65
#Sta/Elev= 30
  4410.9     389  4550.3  387.55  4610.4  386.27  4710.5  385.11  4810.6  383.16
  4965.5  383.08  4986.5  381.97  4993.9  381.08  5000.7  381.11  5008.1  380.28
  5014.9  380.44  5019.3  379.76  5022.1  379.26  5025.3  379.76  5071.6  382.05
    5132  381.55  5148.1  381.79  5153.3  381.45  5182.6   382.1  5187.8  381.87
  5204.5  382.49  5222.3  383.74  5301.7  384.29  5336.2   385.1  5515.6  387.15
  5638.3  389.58  5733.3  392.65    5797  393.65  5831.5  394.69  5861.8  394.66
#Mann= 3 ,-1 , 0
  4410.9     .05       0  5019.3     .03       0  5025.3     .05       0
Bank Sta=5019.3,5025.3
XS Rating Curve= 0 ,0
Exp/Cntr=0.3,0.1

Chan Stop Cuts=-1
Use User Specified Reach Order=0
Composite Channel Slope=5