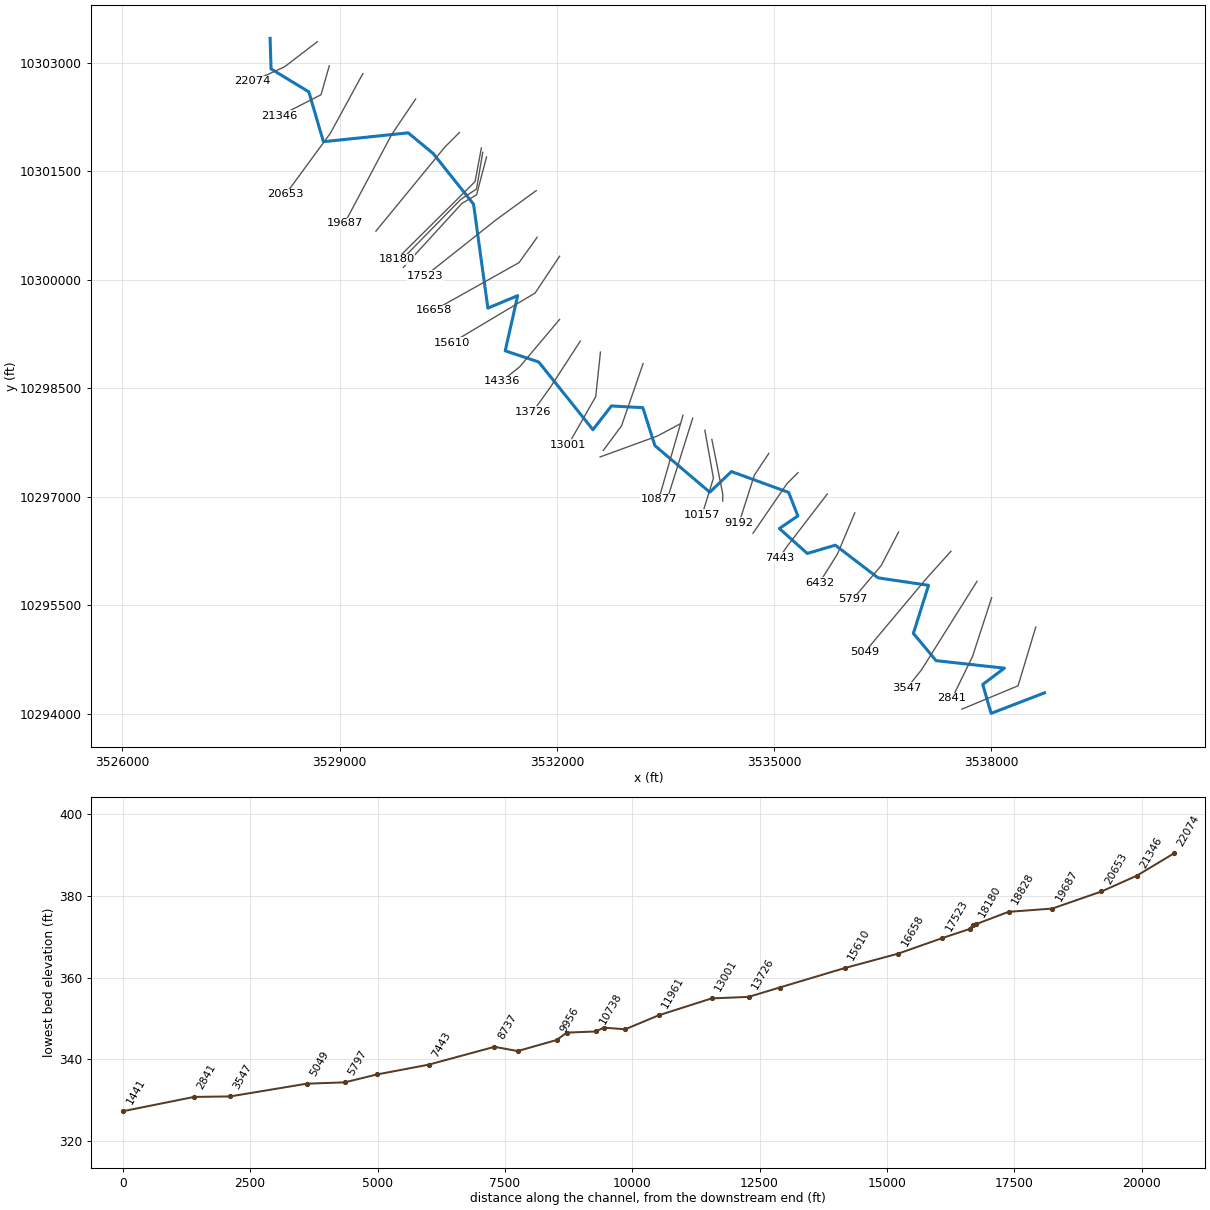
--- TIGER BRANCH.prj (project) ---

Proj Title=TIGER BRANCH Base Level Engineering
Current Plan=p01
Default Exp/Contr=0.3,0.1
English Units
Geom File=g01
Flow File=f01
Plan File=p01
Y Axis Title=Elevation
X Axis Title(PF)=Main Channel Distance
X Axis Title(XS)=Station
BEGIN DESCRIPTION:
TIGER BRANCH
END DESCRIPTION:
DSS Export Rating Curves= 0
DSS Export Rating Curve Sorted= 0
DSS Export Volume Flow Curves= 0
DXF OffsetX= 0
DXF OffsetY= 0
DXF ScaleX= 1
DXF ScaleY= 10

--- TIGER BRANCH.p01 (plan) ---

Plan Title=Multiple Run
Short Identifier=Multiple
Geom File=g01
Flow File=f01
Subcritical Flow
K Sum by GR= 0
Std Step Tol= 0.01
Critical Tol= 0.01
Num of Std Step Trials= 20
Max Error Tol= 0.3
Flow Tol Ratio= 0.001
Split Flow NTrial= 30
Split Flow Tol= 0.02
Split Flow Ratio= 0.02
Log Output Level= 0
Friction Slope Method= 1
Unsteady Friction Slope Method= 2
Unsteady Bridges Friction Slope Method= 1
Parabolic Critical Depth
Global Vel Dist=  1 , 1 , 1
Global Log Level= 0
CheckData=True
Encroach Param= -1, 0, 0, 0
BEGIN DESCRIPTION:
Multiple Run
END DESCRIPTION:

--- TIGER BRANCH.f01 (steady flow) ---

Flow Title=Multiple
Program Version=4.10
Number of Profiles= 7
Profile Names=10-year,25-year,50-year,1pct_min,100-year,1pct_plu,500-year
River Rch & RM=TIGER BRANCH,Reach-1         ,22074
     377     496     591     516     697     943     974
River Rch & RM=TIGER BRANCH,Reach-1         ,20653
     981    1362    1680    1515    2049    2770    3058
River Rch & RM=TIGER BRANCH,Reach-1         ,19687
     981    1362    1680    1515    2049    2770    3058
River Rch & RM=TIGER BRANCH,Reach-1         ,16658
    1029    1427    1758    1584    2142    2897    3190
River Rch & RM=TIGER BRANCH,Reach-1         ,10877
    1333    1864    2309    2089    2825    3821    4245
Boundary for River Rch & Prof#=TIGER BRANCH,Reach-1         , 1
Up Type= 0
Dn Type= 3
Dn Slope=0.005
Boundary for River Rch & Prof#=TIGER BRANCH,Reach-1         , 2
Up Type= 0
Dn Type= 3
Dn Slope=0.005
Boundary for River Rch & Prof#=TIGER BRANCH,Reach-1         , 3
Up Type= 0
Dn Type= 3
Dn Slope=0.005
Boundary for River Rch & Prof#=TIGER BRANCH,Reach-1         , 4
Up Type= 0
Dn Type= 3
Dn Slope=0.005
Boundary for River Rch & Prof#=TIGER BRANCH,Reach-1         , 5
Up Type= 0
Dn Type= 3
Dn Slope=0.005
Boundary for River Rch & Prof#=TIGER BRANCH,Reach-1         , 6
Up Type= 0
Dn Type= 3
Dn Slope=0.005
Boundary for River Rch & Prof#=TIGER BRANCH,Reach-1         , 7
Up Type= 0
Dn Type= 3
Dn Slope=0.005
DSS Import GetInterval= 0
DSS Import GetPeak= 0
DSS Import FillOption= 0

--- TIGER BRANCH.g01 (geometry) ---

Geom Title=Existing Conditions
Program Version=4.10

River Reach=TIGER BRANCH    ,Reach-1
Reach XY= 30
      3528039.29     10303338.01      3528052.38     10302915.39
      3528574.59     10302597.85       3528775.8     10301909.46
      3529946.81      10302031.6      3530292.75      10301745.1
       3530849.9     10301046.22      3531047.73      10299608.8
      3531459.59     10299780.91      3531287.34     10299018.58
      3531749.28     10298865.25      3532498.97     10297927.92
      3532753.83     10298256.39      3533188.55     10298232.78
      3533355.22     10297707.78      3534113.08     10297064.14
      3534411.88     10297349.75      3535202.35     10297061.26
      3535329.94     10296736.68      3535074.77     10296562.64
      3535459.81     10296217.48      3535847.33     10296331.83
       3536437.6     10295880.44      3537135.28     10295776.87
      3536925.53     10295112.78      3537239.26     10294735.87
      3538182.78     10294631.85      3537883.95     10294406.83
      3537999.37     10294007.01      3538737.08     10294290.93

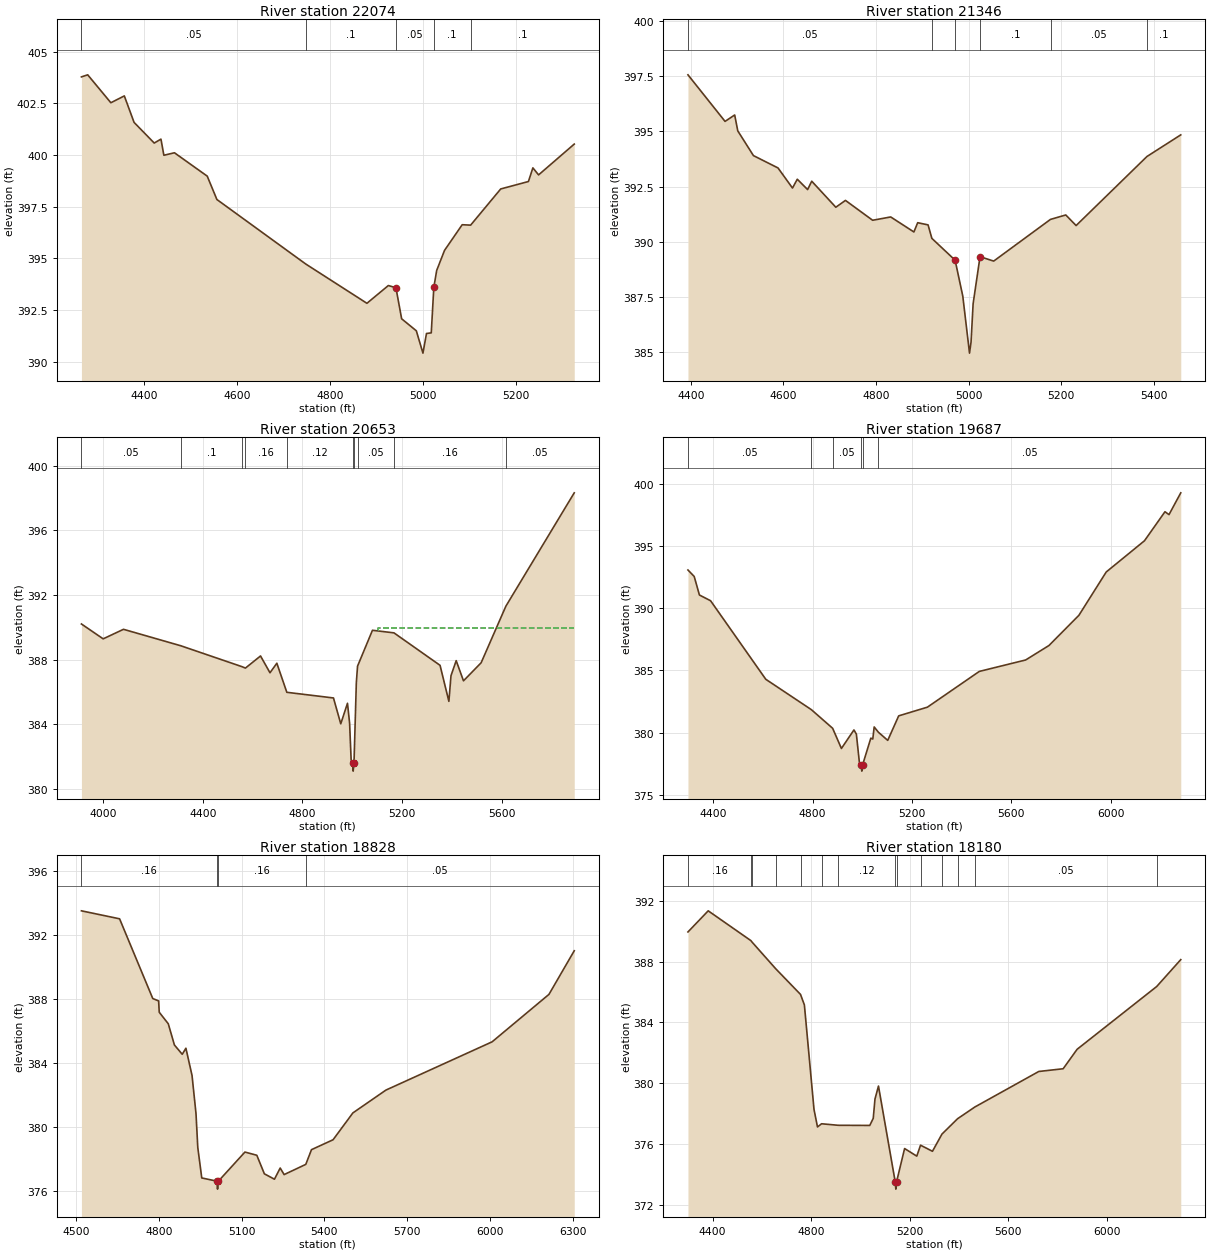
Type RM Length L Ch R = 1 ,22074   ,728,728,728
BEGIN DESCRIPTION:
TIGER BRANCH 34.0
END DESCRIPTION:
XS GIS Cut Line= 3
      3528692.08     10303291.62       3528237.3     10302943.04
      3527792.14     10302741.66
#Sta/Elev= 30
  4264.5  403.78    4278  403.88  4327.9  402.53  4356.9  402.86  4377.9  401.58
  4421.3  400.58  4435.8  400.77  4442.1  399.99  4464.9  400.11  4535.5  398.98
  4556.3  397.85  4747.7  394.73  4879.5  392.83  4925.7  393.69    4942  393.58
  4954.3  392.08  4985.9   391.5  5000.2  390.42  5007.8  391.37  5018.1   391.4
  5023.6   393.6  5029.8  394.42  5046.7  395.39  5084.7  396.63  5102.9  396.61
  5167.7  398.36  5227.4  398.72    5237  399.38  5249.3  399.04  5326.1  400.53
#Mann= 5 ,-1 , 0
  4264.5     .05       0  4747.7      .1       0    4942     .05       0
  5023.6      .1       0  5102.9      .1       0
Bank Sta=4942,5023.6
XS Rating Curve= 0 ,0
Exp/Cntr=0.3,0.1

Type RM Length L Ch R = 1 ,21346   ,693,693,693
BEGIN DESCRIPTION:
TIGER BRANCH 33.0
END DESCRIPTION:
XS GIS Cut Line= 3
      3528857.08     10302958.64      3528742.51     10302557.63
      3528165.78     10302264.07
#Sta/Elev= 30
  4394.1  397.56  4474.2  395.45    4495  395.74  4501.7  395.02  4535.5   393.9
  4588.6  393.34  4619.8  392.43  4630.2  392.83  4652.5  392.36  4661.4  392.74
  4713.4  391.56  4734.2  391.87  4792.9  390.97  4831.9  391.12    4882  390.44
  4890.2  390.86  4912.6  390.76  4920.8  390.15    4971  389.16  4987.6  387.53
  5002.1  384.95  5005.4  385.45  5009.9  387.19  5024.8  389.32  5054.3  389.12
    5177  391.01    5210  391.21  5232.3  390.73  5385.3  393.86  5458.3  394.84
#Mann= 6 ,-1 , 0
  4394.1     .05       0  4920.8      .1       0    4971     .05       0
  5024.8      .1       0    5177     .05       0  5385.3      .1       0
Bank Sta=4971,5024.8
XS Rating Curve= 0 ,0
Exp/Cntr=0.3,0.1

Type RM Length L Ch R = 1 ,20653   ,966,966,966
BEGIN DESCRIPTION:
TIGER BRANCH 32.0
END DESCRIPTION:
XS GIS Cut Line= 3
      3529320.63     10302850.16      3528872.72     10302027.25
      3528255.79     10301185.04
#Sta/Elev= 30
  3911.5   390.2  3998.9  389.28  4080.6  389.87  4311.2  388.85  4556.3  387.56
  4570.7  387.47  4631.4  388.22  4669.4  387.18    4697  387.77  4737.1  385.97
  4924.6  385.62  4953.9  384.02  4980.9  385.29  4989.4  384.07  4995.6  381.79
  5001.1  381.59  5003.8  381.09  5007.1  381.59  5016.5  386.57  5021.4  387.59
  5081.3  389.81  5167.8  389.65    5353  387.64  5388.5  385.41    5397     387
  5417.9  387.93  5447.2  386.68  5518.2   387.8  5617.5   391.3  5892.4  398.32
#Mann= 10 ,-1 , 0
  3911.5     .05       0  4311.2      .1       0  4556.3     .05       0
  4570.7     .16       0  4737.1     .12       0  5001.1     .07       0
  5007.1     .12       0  5021.4     .05       0  5167.8     .16       0
  5617.5     .05       0
#XS Ineff= 2 , 0
                         5105.11          389.94
Permanent Ineff=
       F       F
Bank Sta=5001.1,5007.1
XS Rating Curve= 0 ,0
Exp/Cntr=0.3,0.1

Type RM Length L Ch R = 1 ,19687   ,859,859,859
BEGIN DESCRIPTION:
TIGER BRANCH 31.0
END DESCRIPTION:
XS GIS Cut Line= 3
      3530049.78     10302499.44      3529719.94     10302009.88
      3529067.14     10300780.68
#Sta/Elev= 30
    4299  393.06  4324.1  392.54  4345.1  391.05    4390  390.59    4612  384.28
  4795.3  381.84    4881  380.34  4916.2  378.72  4966.6  380.21  4976.4  379.87
  4989.2  377.47  4995.4   377.4  4998.2   376.9  5001.4   377.4  5034.5  379.55
  5042.4  379.48    5048  380.45  5064.7  380.03  5102.5  379.37  5146.6  381.34
  5262.2  382.04  5470.7  384.91  5657.2  385.83  5750.8  386.99  5871.4  389.42
  5981.3   392.9  6135.2  395.41  6217.5  397.74  6233.8  397.51  6281.1  399.26
#Mann= 6 ,-1 , 0
    4299     .05       0  4795.3     .16       0    4881     .05       0
  4995.4     .07       0  5001.4     .05       0  5064.7     .05       0
Bank Sta=4995.4,5001.4
XS Rating Curve= 0 ,0
Exp/Cntr=0.3,0.1

Type RM Length L Ch R = 1 ,18828   ,648,648,648
BEGIN DESCRIPTION:
TIGER BRANCH 30.0
END DESCRIPTION:
XS GIS Cut Line= 3
      3530653.93     10302035.41      3530453.91     10301835.39
      3529501.22     10300673.12
#Sta/Elev= 30
  4519.5  393.52  4657.8  393.02    4778  388.03  4799.2  387.88  4801.5  387.17
  4834.2  386.45  4856.5  385.12  4884.8  384.54  4898.1  384.92  4920.3  383.21
  4934.7  380.82  4941.1  378.71  4955.5   376.8  5009.9   376.6  5012.7   376.1
  5015.9   376.6  5111.9  378.42    5155  378.22  5182.3  377.06  5218.9  376.72
  5239.7  377.42    5254  377.01  5332.5  377.65  5353.1  378.57  5431.3  379.19
  5503.1  380.87  5622.9   382.3  6007.6  385.32  6213.6  388.29  6305.2  391.02
#Mann= 4 ,-1 , 0
  4519.5     .16       0  5009.9     .07       0  5015.9     .16       0
  5332.5     .05       0
Bank Sta=5009.9,5015.9
XS Rating Curve= 0 ,0
Exp/Cntr=0.3,0.1

Type RM Length L Ch R = 1 ,18180   ,52,52,52
BEGIN DESCRIPTION:
TIGER BRANCH 29.0
END DESCRIPTION:
XS GIS Cut Line= 3
      3530957.79     10301822.42      3530870.98     10301357.97
      3529786.54      10300282.2
#Sta/Elev= 30
  4299.8  389.95    4382  391.34  4555.2  389.38  4560.1  389.28  4655.9  387.53
  4756.6  385.84  4772.3  385.15  4811.3  378.28  4825.5  377.12  4842.1  377.33
  4909.6  377.23  5037.6  377.22  5051.8  377.69  5058.8  378.96    5073  379.81
  5140.7  373.53  5143.4  373.03  5146.7  373.53    5179   375.7  5228.5   375.2
  5243.7  375.92  5292.1  375.52  5330.6  376.65  5393.9  377.66  5463.8  378.43
  5723.5  380.77  5822.5  380.95  5879.1  382.23  6202.1  386.36  6299.8  388.13
#Mann= 14 ,-1 , 0
  4299.8     .16       0  4555.2      .1       0  4560.1     .16       0
  4655.9      .1       0  4756.6     .16       0  4842.1      .1       0
  4909.6     .12       0  5140.7     .07       0  5146.7     .12       0
  5243.7      .1       0  5330.6     .05       0  5393.9      .1       0
  5463.8     .05       0  6202.1     .16       0
Bank Sta=5140.7,5146.7
XS Rating Curve= 0 ,0
Exp/Cntr=0.3,0.1

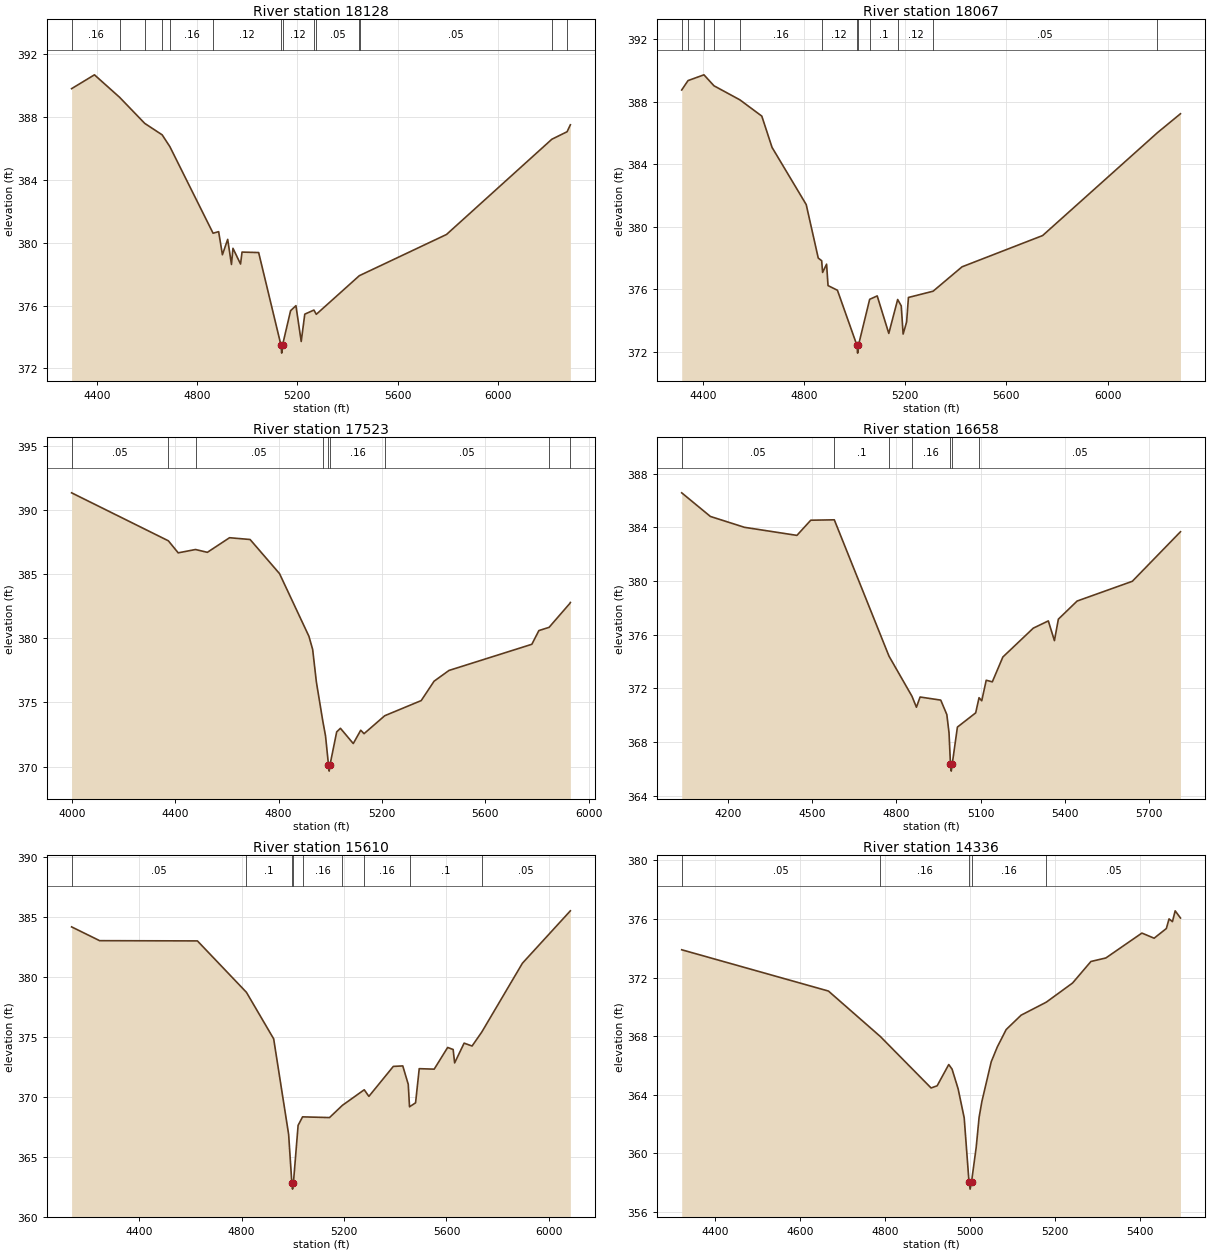
Type RM Length L Ch R = 1 ,18128   ,61,61,61
BEGIN DESCRIPTION:
Mapping XS d1ff910e
END DESCRIPTION:
XS GIS Cut Line= 4
      3530976.55      10301761.6      3530891.11     10301255.62
      3530675.18     10301113.47      3529822.07     10300242.55
#Sta/Elev= 30
  4298.9   389.8  4390.1  390.68  4490.5  389.25  4590.8  387.59  4660.4  386.86
  4691.1  386.11  4863.6   380.6  4885.8   380.7  4900.9  379.23  4921.9  380.21
    4937  378.61    4943  379.64  4973.2  378.64  4979.2   379.4  5045.5  379.37
  5134.7  373.47  5137.4  372.97  5140.7  373.47    5173  375.67  5194.3  375.99
  5215.4  373.71  5229.6  375.45  5266.1  375.71  5275.6  375.44  5447.5   377.9
    5449  377.91  5795.3  380.52  6215.7  386.58  6276.7  387.06  6289.7   387.5
#Mann= 14 ,-1 , 0
  4298.9     .16       0  4490.5      .1       0  4590.8     .16       0
  4660.4      .1       0  4691.1     .16       0  4863.6     .12       0
  5134.7     .07       0  5140.7     .12       0  5266.1      .1       0
  5275.6     .05       0  5447.5      .1       0    5449     .05       0
  6215.7     .16       0  6276.7     .05       0
Bank Sta=5134.7,5140.7
XS Rating Curve= 0 ,0
Exp/Cntr=0.3,0.1

Type RM Length L Ch R = 1 ,18067   ,544,544,544
BEGIN DESCRIPTION:
Mapping XS 03851246
END DESCRIPTION:
XS GIS Cut Line= 4
      3531029.34     10301698.07      3530891.33     10301174.67
       3530690.8     10301057.48      3529880.91     10300172.07
#Sta/Elev= 30
  4315.2  388.74  4340.1  389.34  4403.2  389.71  4442.8  389.01  4545.4  388.11
  4632.1  387.07  4672.6  385.07  4807.9  381.41  4855.5  377.99    4869  377.82
  4872.7  377.07  4888.4   377.6  4894.2  376.23  4931.4  375.93  5008.5  372.41
  5011.3  371.91  5014.5  372.41  5058.9  375.35  5088.7  375.57  5134.6  373.17
  5169.7  375.34  5183.9  374.93  5191.3  373.13  5205.1   373.9  5212.3  375.47
  5309.9  375.87  5424.4  377.43  5743.3  379.43  6197.6  386.01  6288.7  387.22
#Mann= 12 ,-1 , 0
  4315.2     .16       0  4340.1      .1       0  4403.2     .16       0
  4442.8      .1       0  4545.4     .16       0    4869     .12       0
  5008.5     .07       0  5014.5     .12       0  5058.9      .1       0
  5169.7     .12       0  5309.9     .05       0  6197.6     .16       0
Bank Sta=5008.5,5014.5
XS Rating Curve= 0 ,0
Exp/Cntr=0.3,0.1

Type RM Length L Ch R = 1 ,17523   ,865,865,865
BEGIN DESCRIPTION:
TIGER BRANCH 27.0
END DESCRIPTION:
XS GIS Cut Line= 3
      3531715.55      10301232.8      3531165.54     10300832.79
      3530186.65     10300057.03
#Sta/Elev= 30
  3999.5  391.34  4373.7   387.6  4411.8  386.66  4478.8  386.92  4524.6   386.7
  4610.4  387.84  4689.9   387.7  4803.7  385.04  4917.5  380.15  4931.9  379.12
  4946.3  376.58  4971.1  373.54  4981.6  372.39    4993  370.14  4995.7  369.64
    4999  370.14  5024.8   372.7  5039.3  372.98  5088.9  371.79  5117.8  372.83
  5130.6  372.56  5210.6  373.96  5351.7  375.14  5401.4  376.65  5459.1  377.49
  5779.6  379.53  5806.8   380.6  5846.2  380.85  5926.7  382.72  5928.6  382.79
#Mann= 9 ,-1 , 0
  3999.5     .05       0  4373.7     .16       0  4478.8     .05       0
  4971.1     .16       0    4993     .07       0    4999     .16       0
  5210.6     .05       0  5846.2     .16       0  5926.7     .05       0
Bank Sta=4993,4999
XS Rating Curve= 0 ,0
Exp/Cntr=0.3,0.1

Type RM Length L Ch R = 1 ,16658   ,1048,1048,1048
BEGIN DESCRIPTION:
TIGER BRANCH 26.0
END DESCRIPTION:
XS GIS Cut Line= 3
      3531728.24     10300587.51      3531478.22     10300237.48
      3530302.36     10299578.44
#Sta/Elev= 30
  4034.7  386.57    4137  384.81  4258.6     384  4445.4   383.4  4494.8  384.53
  4578.7  384.56  4773.6  374.41  4855.5  371.42  4871.5   370.6  4884.5  371.36
  4958.2  371.13  4979.9  370.05  4987.7  368.69  4992.9  366.34  4995.6  365.84
  4998.9  366.34  5017.6  369.12  5082.7  370.18  5094.7  371.31  5104.3  371.08
  5120.3  372.61    5142  372.49  5179.6  374.34  5288.1  376.49  5341.7  377.03
  5363.4  375.56  5377.5  377.16  5444.4  378.51  5641.1  379.98  5812.8  383.67
#Mann= 7 ,-1 , 0
  4034.7     .05       0  4578.7      .1       0  4773.6     .05       0
  4855.5     .16       0  4992.9     .07       0  4998.9     .16       0
  5094.7     .05       0
Bank Sta=4992.9,4998.9
XS Rating Curve= 0 ,0
Exp/Cntr=0.3,0.1

Type RM Length L Ch R = 1 ,15610   ,1274,1274,1274
BEGIN DESCRIPTION:
TIGER BRANCH 24.0
END DESCRIPTION:
XS GIS Cut Line= 3
      3532038.82     10300326.21      3531699.97     10299817.18
      3530553.26     10299132.62
#Sta/Elev= 30
  4136.7  384.19  4246.2  383.04  4627.9  383.02  4819.2  378.73  4925.5  374.85
  4983.9  366.88  4996.5  362.81  4999.2  362.31  5002.5  362.81  5020.9  367.63
  5038.3  368.34  5143.5  368.28  5193.7   369.3    5279   370.6  5297.2  370.05
  5392.6  372.55  5429.5  372.59  5450.9  371.05  5455.8  369.18  5479.4  369.51
  5493.7  372.36  5552.1  372.32  5604.7  374.13  5626.1  373.96  5631.9  372.84
  5668.9  374.49    5700  374.25  5737.7  375.41  5896.6  381.16  6083.7  385.53
#Mann= 9 ,-1 , 0
  4136.7     .05       0  4819.2      .1       0  4996.5     .07       0
  5002.5      .1       0  5038.3     .16       0  5193.7      .1       0
    5279     .16       0  5455.8      .1       0  5737.7     .05       0
Bank Sta=4996.5,5002.5
XS Rating Curve= 0 ,0
Exp/Cntr=0.3,0.1

Type RM Length L Ch R = 1 ,14336   ,610,610,610
BEGIN DESCRIPTION:
TIGER BRANCH 22.0
END DESCRIPTION:
XS GIS Cut Line= 3
      3532038.49     10299452.56      3531487.94     10298798.41
       3531237.9     10298598.38
#Sta/Elev= 30
  4320.5   373.9  4666.2  371.08  4788.7  367.97  4908.1  364.46  4922.4  364.61
  4949.7  366.06  4957.5  365.75  4971.8   364.4  4986.1  362.42  4997.4  358.05
  5000.1  357.55  5003.4  358.05  5014.4  360.41  5021.2  362.45  5027.8  363.54
  5049.8  366.25  5064.1  367.26    5085  368.45  5120.1  369.43  5179.5  370.32
  5241.5  371.63  5284.7   373.1  5319.9  373.34  5404.8  375.04  5433.6  374.69
  5462.4  375.35  5468.8  376.01  5476.8  375.82  5483.2  376.56  5495.7  376.07
#Mann= 5 ,-1 , 0
  4320.5     .05       0  4788.7     .16       0  4997.4     .07       0
  5003.4     .16       0  5179.5     .05       0
Bank Sta=4997.4,5003.4
XS Rating Curve= 0 ,0
Exp/Cntr=0.3,0.1

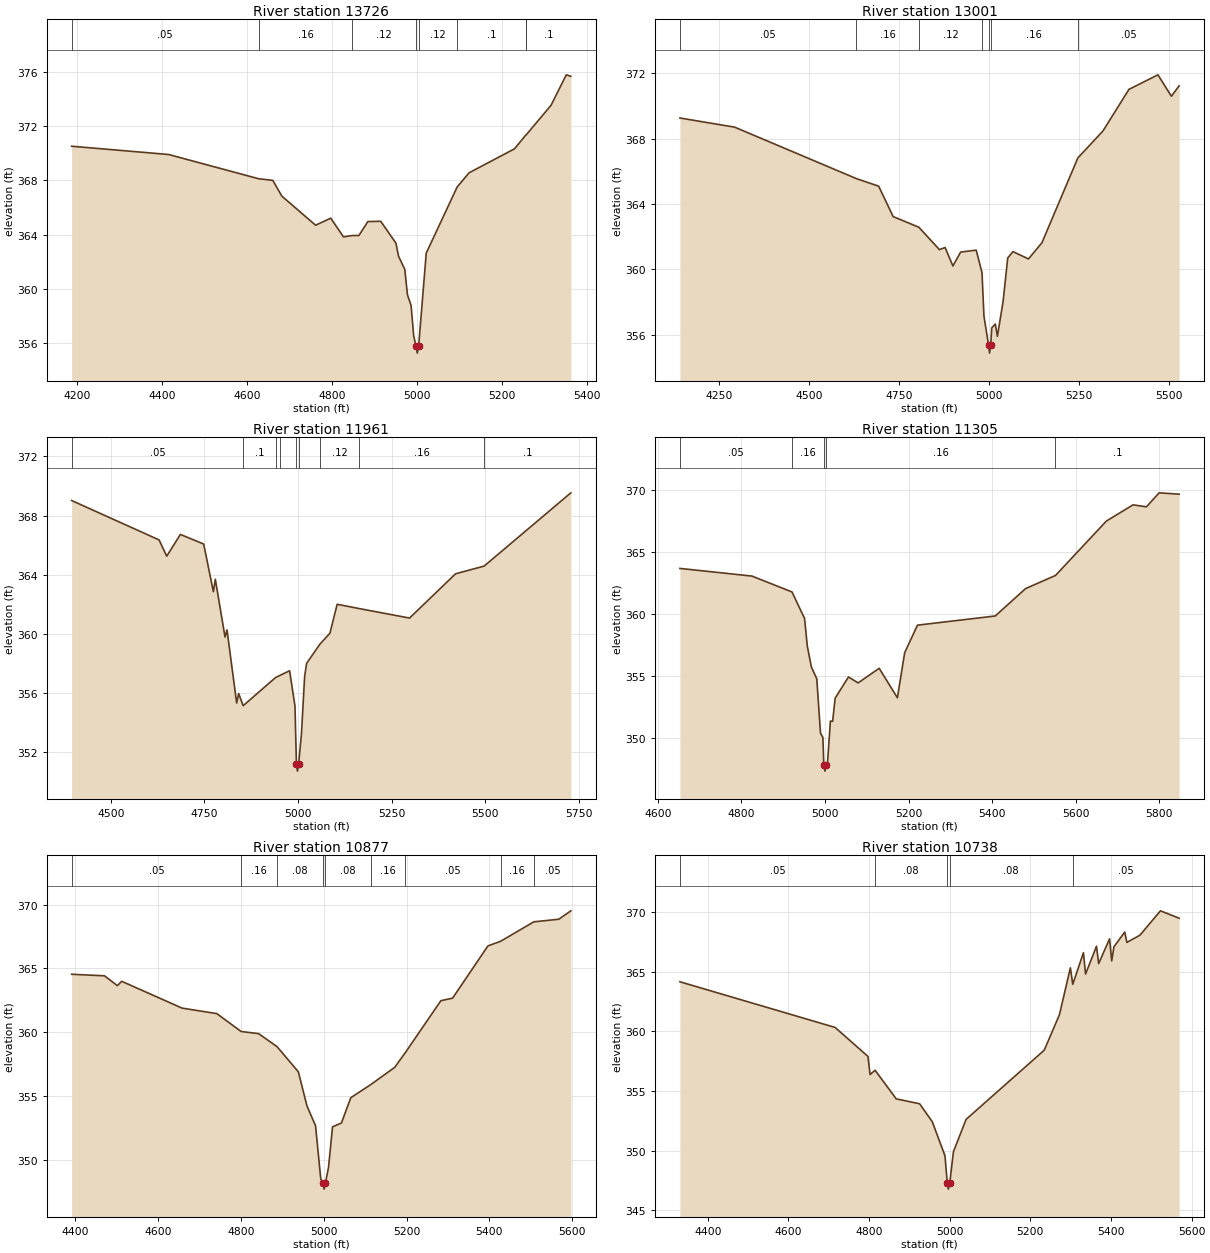
Type RM Length L Ch R = 1 ,13726   ,725,725,725
BEGIN DESCRIPTION:
TIGER BRANCH 21.0
END DESCRIPTION:
XS GIS Cut Line= 3
      3532324.95     10299153.08      3531920.23      10298528.8
      3531670.24      10298178.8
#Sta/Elev= 30
  4187.9  370.52    4416  369.91  4627.8  368.12  4661.1     368  4682.2  366.84
  4761.7  364.69  4797.4  365.21  4827.3  363.83  4847.9  363.93  4863.5  363.93
  4884.6  364.96  4914.9  364.98  4950.6  363.37  4956.8   362.4  4971.5  361.43
  4977.7  359.56  4986.3  358.76  4992.4  356.53    4998  355.75  5000.8  355.25
    5004  355.75  5021.9  362.63  5094.6  367.51  5122.7  368.56  5229.6  370.33
  5255.6  371.33  5256.8  371.35  5315.6  373.55  5351.3  375.79    5362  375.68
#Mann= 8 ,-1 , 0
  4187.9     .05       0  4627.8     .16       0  4847.9     .12       0
    4998     .07       0    5004     .12       0  5094.6      .1       0
  5255.6     .05       0  5256.8      .1       0
Bank Sta=4998,5004
XS Rating Curve= 0 ,0
Exp/Cntr=0.3,0.1

Type RM Length L Ch R = 1 ,13001   ,1040,1040,1040
BEGIN DESCRIPTION:
TIGER BRANCH 19.0
END DESCRIPTION:
XS GIS Cut Line= 3
      3532602.75     10299001.16      3532537.65     10298384.88
      3532156.47     10297717.82
#Sta/Elev= 30
  4141.3  369.26  4293.4   368.7  4632.2  365.55  4693.9  365.09  4734.1  363.23
  4805.5  362.58  4862.8  361.21  4878.6  361.34  4900.2  360.21  4921.8  361.06
    4965  361.18  4981.1  359.81  4986.6  357.14  4999.4  355.38  5002.2  354.88
  5005.4  355.38  5008.2  356.42  5018.1  356.66    5024  355.91  5039.8  358.04
  5052.7   360.7  5067.2  361.09  5110.4  360.64  5147.8  361.63  5247.7  366.82
  5317.6  368.47  5389.7  371.01  5470.3   371.9  5507.7  370.59  5529.3  371.23
#Mann= 7 ,-1 , 0
  4141.3     .05       0  4632.2     .16       0  4805.5     .12       0
  4981.1     .16       0  4999.4     .07       0  5005.4     .16       0
  5247.7     .05       0
Bank Sta=4999.4,5005.4
XS Rating Curve= 0 ,0
Exp/Cntr=0.3,0.1

Type RM Length L Ch R = 1 ,11961   ,656,656,656
BEGIN DESCRIPTION:
TIGER BRANCH 17.0
END DESCRIPTION:
XS GIS Cut Line= 3
      3533192.11     10298841.66      3532893.55     10297981.24
      3532642.11     10297641.64
#Sta/Elev= 30
  4395.2  369.02  4628.7  366.36  4649.2  365.26  4685.7  366.73  4747.9  366.08
  4773.8  362.86    4779   363.7  4804.9   359.8  4810.2  360.28    4836  355.34
  4841.3  355.98  4853.4  355.16  4939.8  357.06  4952.7  357.22  4977.4  357.52
  4991.7  355.14  4995.6  351.24  4998.3  350.74  5001.6  351.24  5009.1  353.29
  5017.5  357.13  5022.8  358.02  5058.1  359.31  5085.1  360.06  5104.4  362.01
  5163.5  361.72  5297.7  361.08  5420.6  364.07  5496.9  364.59  5728.5  369.54
#Mann= 9 ,-1 , 0
  4395.2     .05       0  4853.4      .1       0  4939.8     .12       0
  4952.7     .16       0  4995.6     .07       0  5001.6     .16       0
  5058.1     .12       0  5163.5     .16       0  5496.9      .1       0
Bank Sta=4995.6,5001.6
XS Rating Curve= 0 ,0
Exp/Cntr=0.3,0.1

Type RM Length L Ch R = 1 ,11305   ,428,428,428
BEGIN DESCRIPTION:
TIGER BRANCH 16.0
END DESCRIPTION:
XS GIS Cut Line= 3
      3533700.86     10298007.29      3533392.11     10297841.64
      3532598.44     10297551.56
#Sta/Elev= 30
  4652.6  363.67  4825.1  363.05    4921  361.77    4951  359.63  4957.6   357.4
  4967.3  355.72  4980.3  354.76  4989.2  350.37  4994.9  350.03  4997.1  347.81
  4999.9  347.31  5003.1  347.81  5005.6  347.81  5012.9  351.35  5018.2  351.33
  5024.3   353.2  5056.2  354.91  5079.3  354.43  5129.7  355.61  5173.3  353.23
  5190.8  356.87  5221.4  359.09  5407.6  359.83  5480.2  362.04  5551.9   363.1
  5673.7  367.49  5737.6   368.8  5769.6  368.64  5800.1  369.77    5848  369.66
#Mann= 5 ,-1 , 0
  4652.6     .05       0    4921     .16       0  4997.1     .07       0
  5003.1     .16       0  5551.9      .1       0
Bank Sta=4997.1,5003.1
XS Rating Curve= 0 ,0
Exp/Cntr=0.3,0.1

Type RM Length L Ch R = 1 ,10877   ,139,139,139
BEGIN DESCRIPTION:
Mapping XS 6adb1a17
END DESCRIPTION:
XS GIS Cut Line= 2
      3533743.04     10298127.91      3533408.86     10296969.13
#Sta/Elev= 30
  4390.8  364.54  4470.2  364.42  4501.4  363.65  4511.8  363.99  4657.5  361.89
  4741.5  361.46  4800.1  360.06  4842.5  359.89  4887.1  358.87  4938.5   356.9
  4959.3  354.23  4980.1  352.67  4992.7   348.5    4998  348.21  5000.7  347.71
    5004  348.21  5011.4  349.41  5021.1  352.59  5042.6  352.89  5065.2  354.87
  5113.5   355.9  5171.4  357.25  5197.3  358.42  5282.8  362.47  5311.2  362.67
  5396.4  366.76  5426.9  367.12  5507.5  368.65  5567.6  368.85  5596.8  369.51
#Mann= 9 ,-1 , 0
  4390.8     .05       0  4800.1     .16       0  4887.1     .08       0
    4998     .07       0    5004     .08       0  5113.5     .16       0
  5197.3     .05       0  5426.9     .16       0  5507.5     .05       0
Bank Sta=4998,5004
XS Rating Curve= 0 ,0
Exp/Cntr=0.3,0.1

Type RM Length L Ch R = 1 ,10738   ,581,581,581
BEGIN DESCRIPTION:
TIGER BRANCH 15.0
END DESCRIPTION:
XS GIS Cut Line= 2
       3533877.6     10298088.89      3533506.89     10296907.38
#Sta/Elev= 30
  4330.8  364.17  4715.7  360.34  4797.2  357.91  4802.4  356.39  4814.9  356.75
  4867.3  354.35  4925.3  353.94  4956.8  352.43  4988.2  349.58    4994  347.28
  4996.7  346.78    5000  347.28  5009.2  349.92  5040.6  352.63  5234.4  358.43
  5272.1   361.4  5299.3  365.34  5305.2  363.96  5331.7  366.61  5336.9  364.81
  5364.1  367.15  5369.4  365.69  5396.5  367.77  5401.8  365.92  5407.4  367.11
  5434.2  368.34  5439.4  367.47  5471.9  368.08  5522.7  370.12  5569.1   369.5
#Mann= 5 ,-1 , 0
  4330.8     .05       0  4814.9     .08       0    4994     .07       0
    5000     .08       0  5305.2     .05       0
Bank Sta=4994,5000
XS Rating Curve= 0 ,0
Exp/Cntr=0.3,0.1

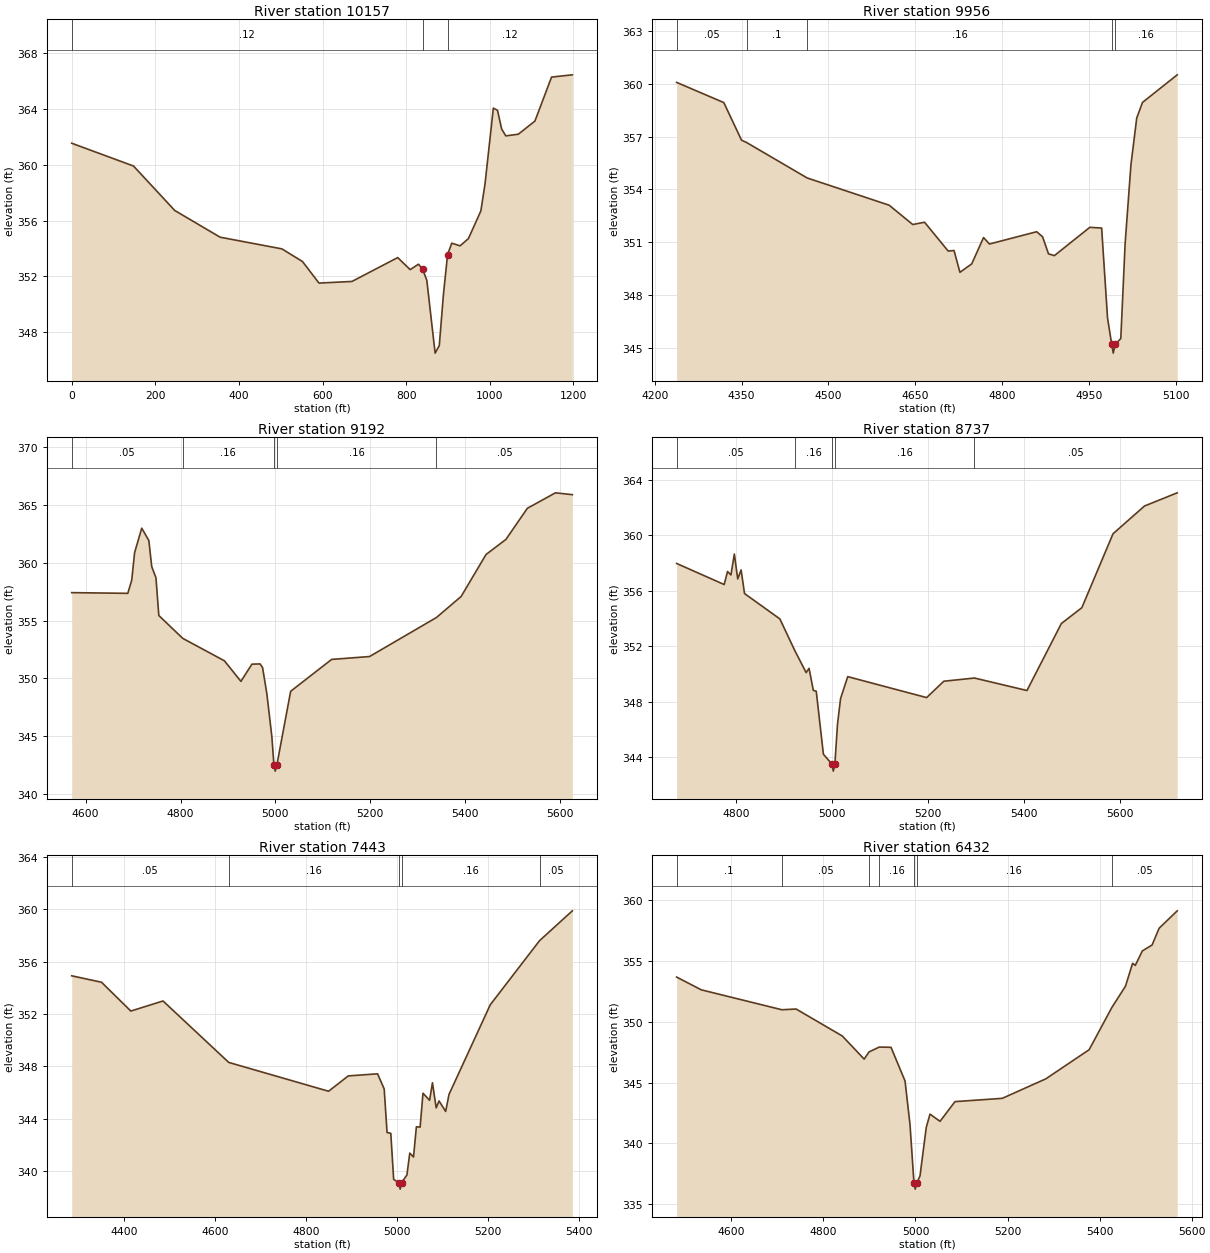
Type RM Length L Ch R = 1 ,10157   ,201,201,201
BEGIN DESCRIPTION:
TIGER BRANCH 14.0
END DESCRIPTION:
XS GIS Cut Line= 3
     3534045.351    10297920.252      3534163.52     10297258.15
      3534007.83     10296754.76
#Sta/Elev= 30
       0361.5433147.8895359.9072246.4825356.7211354.9348 354.806502.8243 353.967
552.1208353.0601 591.558351.5149670.4324351.6319779.8431353.3432809.6824352.4806
829.5753352.8686839.5217352.4977849.4681351.7191 869.361 346.493879.3074347.0311
889.2538350.7106899.2003353.5613909.1467354.3746929.0396354.1861948.9324354.7009
978.7717356.6888988.7181358.62261008.611364.06311018.557363.90361028.504362.5588
 1038.45362.0688 1068.29362.18731108.075363.12971147.861366.28281197.593366.4461
#Mann= 3 , 0 , 0
       0     .12       0839.5217     .07       0899.2003     .12       0
Bank Sta=839.5217,899.2003
XS Rating Curve= 0 ,0
Exp/Cntr=0.3,0.1

Type RM Length L Ch R = 1 ,9956    ,764,764,764
BEGIN DESCRIPTION:
TIGER BRANCH 13.0
END DESCRIPTION:
XS GIS Cut Line= 3
       3534142.1     10297791.68      3534292.11     10297041.64
      3534292.11     10296941.64
#Sta/Elev= 30
  4237.6  360.09  4319.2  358.94  4349.8   356.8  4358.4  356.67  4463.2  354.65
  4604.8   353.1  4645.6     352    4666  352.13  4706.8  350.49  4716.9  350.52
  4727.1  349.28  4747.5  349.76  4767.9  351.26  4778.1  350.89  4859.7  351.59
  4869.9   351.3  4880.1  350.33  4890.3  350.23  4951.5  351.84  4971.9   351.8
  4982.1  346.68  4989.3  345.18    4992  344.68  4995.3  345.18    5005  345.51
  5012.5  350.92  5022.5  355.39  5032.5  358.06  5042.5  358.95  5102.5  360.52
#Mann= 5 ,-1 , 0
  4237.6     .05       0  4358.4      .1       0  4463.2     .16       0
  4989.3     .07       0  4995.3     .16       0
Bank Sta=4989.3,4995.3
XS Rating Curve= 0 ,0
Exp/Cntr=0.3,0.1

Type RM Length L Ch R = 1 ,9192    ,455,455,455
BEGIN DESCRIPTION:
TIGER BRANCH 12.0
END DESCRIPTION:
XS GIS Cut Line= 3
      3534928.59     10297600.01      3534728.56     10297299.98
      3534517.69     10296638.36
#Sta/Elev= 30
  4570.7  357.42  4688.9  357.36  4697.2   358.5  4703.3  360.89  4718.3     363
  4733.3  361.93  4739.3  359.68  4748.3   358.7  4754.3  355.44  4804.8  353.46
  4892.5  351.52  4927.3  349.74  4950.5  351.23  4967.7  351.25  4972.9  350.94
    4982  348.66  4992.5  344.95  4996.9  342.47  4999.6  341.97  5002.9  342.47
  5032.1  348.88  5118.5  351.64  5198.4  351.89  5339.4  355.27  5391.4  357.09
  5443.8  360.72  5485.8  362.03  5530.9  364.72  5590.1  366.06  5625.7   365.9
#Mann= 5 ,-1 , 0
  4570.7     .05       0  4804.8     .16       0  4996.9     .07       0
  5002.9     .16       0  5339.4     .05       0
Bank Sta=4996.9,5002.9
XS Rating Curve= 0 ,0
Exp/Cntr=0.3,0.1

Type RM Length L Ch R = 1 ,8737    ,1294,1294,1294
BEGIN DESCRIPTION:
TIGER BRANCH 11.0
END DESCRIPTION:
XS GIS Cut Line= 3
      3535330.65     10297333.32      3535180.65     10297183.31
      3534710.39     10296497.73
#Sta/Elev= 30
  4676.6  357.98  4775.8  356.46  4782.8   357.4  4789.9  357.15    4797  358.66
    4804  356.86  4811.1  357.51  4818.2  355.81  4891.9  353.98    4923   351.7
  4946.7  350.11  4952.7  350.42  4961.6  348.83  4967.7  348.77  4982.6  344.23
  5000.5  343.51  5003.3  343.01  5006.5  343.51    5012   346.4  5018.4  348.24
  5033.3  349.82  5197.8  348.31  5233.6  349.49  5297.5  349.72  5406.9  348.82
  5478.6  353.65  5521.3  354.79  5586.3  360.12  5651.9  362.12  5720.1  363.07
#Mann= 5 ,-1 , 0
  4676.6     .05       0    4923     .16       0  5000.5     .07       0
  5006.5     .16       0  5297.5     .05       0
Bank Sta=5000.5,5006.5
XS Rating Curve= 0 ,0
Exp/Cntr=0.3,0.1

Type RM Length L Ch R = 1 ,7443    ,1011,1011,1011
BEGIN DESCRIPTION:
TIGER BRANCH 9.0
END DESCRIPTION:
XS GIS Cut Line= 3
      3535736.43     10297039.39      3535176.48     10296309.35
      3535076.77     10296159.79
#Sta/Elev= 30
  4284.9  354.91  4350.4  354.42  4414.8  352.22  4485.5  352.99  4629.9   348.3
  4849.2   346.1  4892.5  347.27  4956.9  347.43  4971.4  346.27  4977.7  342.95
  4985.9  342.89  4992.2  339.37  5003.7  339.13  5006.5  338.63  5009.7  339.13
  5021.3  339.71  5027.6  341.38  5035.8  341.08  5042.1  343.39  5050.3  343.36
  5056.6  345.95  5071.1  345.41  5077.4  346.75  5085.6  344.83  5091.9  345.36
  5106.4  344.56  5113.8  345.86  5204.4   352.7  5312.6  357.59  5384.7  359.87
#Mann= 5 ,-1 , 0
  4284.9     .05       0  4629.9     .16       0  5003.7     .07       0
  5009.7     .16       0  5312.6     .05       0
Bank Sta=5003.7,5009.7
XS Rating Curve= 0 ,0
Exp/Cntr=0.3,0.1

Type RM Length L Ch R = 1 ,6432    ,635,635,635
BEGIN DESCRIPTION:
TIGER BRANCH 7.0
END DESCRIPTION:
XS GIS Cut Line= 3
      3536116.65       10296779.      3535877.52     10296211.43
      3535627.51     10295811.42
#Sta/Elev= 30
  4481.1  353.69  4534.7  352.64  4709.8     351  4740.8  351.06  4841.1  348.84
  4888.6  346.94  4899.2  347.53  4921.4  347.93  4946.9  347.91  4977.4  345.14
  4988.2  341.55  4996.8  336.74  4999.5  336.24  5002.8  336.74  5009.9  337.33
  5023.5  341.32  5031.6  342.41  5053.4  341.82  5085.9  343.44  5188.6  343.71
    5283  345.31  5377.3  347.71  5426.6  351.18  5456.3  352.94  5471.7  354.82
  5477.6  354.65  5492.9  355.84  5514.1  356.33  5529.4  357.71  5568.7  359.14
#Mann= 7 ,-1 , 0
  4481.1      .1       0  4709.8     .05       0  4899.2      .1       0
  4921.4     .16       0  4996.8     .07       0  5002.8     .16       0
  5426.6     .05       0
Bank Sta=4996.8,5002.8
XS Rating Curve= 0 ,0
Exp/Cntr=0.3,0.1

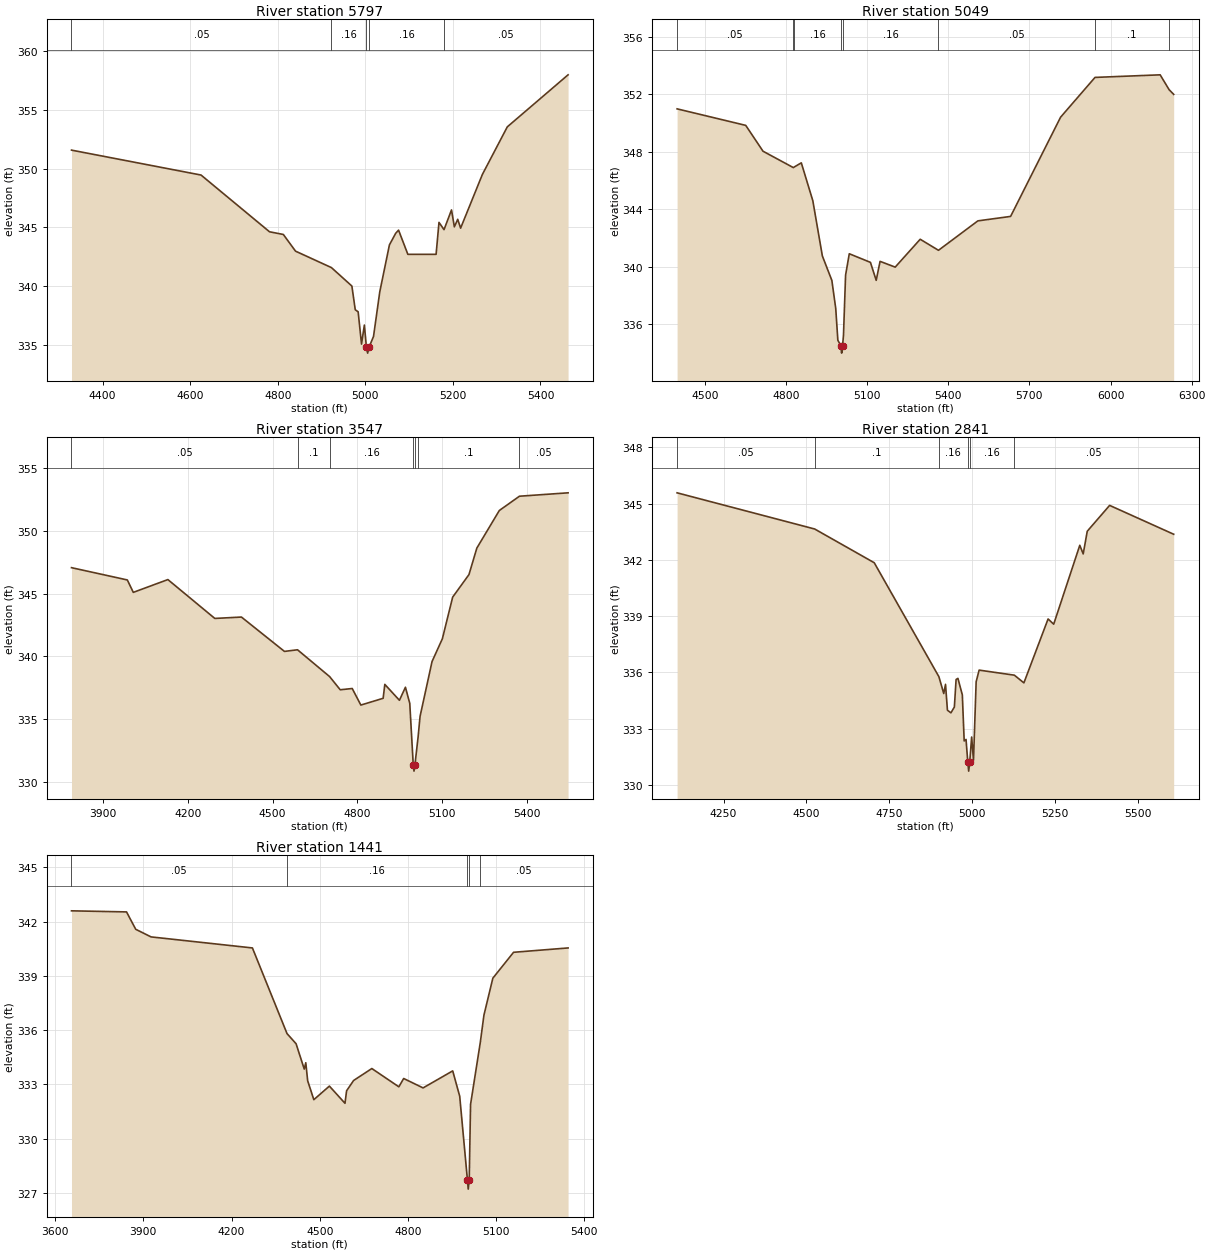
Type RM Length L Ch R = 1 ,5797    ,748,748,748
BEGIN DESCRIPTION:
TIGER BRANCH 5.0
END DESCRIPTION:
XS GIS Cut Line= 3
      3536720.83      10296513.4      3536481.22     10296049.82
      3536086.27     10295582.11
#Sta/Elev= 30
    4329  351.58  4624.8  349.46  4781.2  344.63  4812.8   344.4  4840.6  342.98
  4922.6  341.58  4969.3  340.01    4977  337.99  4983.6  337.82  4991.3  335.07
  4997.8  336.69  5002.5   334.8  5005.3   334.3  5008.5   334.8  5018.7  335.72
    5033  339.52    5055  343.51  5069.3   344.5  5075.9  344.77  5097.1  342.71
  5161.6  342.71  5168.2  345.43  5179.7  344.81  5196.8  346.49  5203.3  345.05
    5211  345.69  5217.6  344.94  5267.3  349.51  5324.2  353.56    5463  357.99
#Mann= 5 ,-1 , 0
    4329     .05       0  4922.6     .16       0  5002.5     .07       0
  5008.5     .16       0  5179.7     .05       0
Bank Sta=5002.5,5008.5
XS Rating Curve= 0 ,0
Exp/Cntr=0.3,0.1

Type RM Length L Ch R = 1 ,5049    ,1502,1502,1502
BEGIN DESCRIPTION:
TIGER BRANCH 4.0
END DESCRIPTION:
XS GIS Cut Line= 3
      3537444.74      10296247.7      3537102.52     10295867.68
      3536252.06      10294851.9
#Sta/Elev= 30
  4397.4  350.98  4651.2  349.83  4715.1  348.03  4827.2  346.89  4831.3  346.94
  4856.7  347.22  4899.3  344.58  4934.5  340.74  4969.7  339.03    4984  337.08
  4991.8  334.87  5003.1  334.47  5005.8  333.97  5009.1  334.47  5012.6  335.19
  5020.4   339.4  5034.1  340.89  5112.3  340.29  5133.6  339.04  5147.9  340.36
  5203.9  339.96  5296.3   341.9  5363.9  341.13  5509.6  343.18  5630.6  343.49
  5815.4   350.4  5942.7  353.17  6183.6  353.35  6216.5  352.32  6233.6  351.99
#Mann= 8 ,-1 , 0
  4397.4     .05       0  4827.2      .1       0  4831.3     .16       0
  5003.1     .07       0  5009.1     .16       0  5363.9     .05       0
  5942.7      .1       0  6216.5     .05       0
Bank Sta=5003.1,5009.1
XS Rating Curve= 0 ,0
Exp/Cntr=0.3,0.1

Type RM Length L Ch R = 1 ,3547    ,706,706,706
BEGIN DESCRIPTION:
TIGER BRANCH 3.0
END DESCRIPTION:
XS GIS Cut Line= 3
      3537804.13     10295831.06      3537040.02     10294611.43
      3536840.01     10294361.41
#Sta/Elev= 30
  3787.2  347.08    3985   346.1  4006.2  345.11  4128.7  346.13    4295  343.03
  4389.3  343.14  4541.7   340.4    4588  340.53  4701.8  338.39  4739.3  337.34
  4781.8  337.44  4812.4  336.12  4891.4  336.66  4897.3  337.77  4949.1   336.5
  4970.3  337.54  4985.7  336.26    4998  331.35  5000.7  330.85    5004  331.35
  5015.3  333.59  5022.2  335.22  5064.6  339.59  5101.2  341.41  5137.7  344.73
  5195.5  346.53  5223.3  348.64    5303  351.64  5374.3  352.78  5546.6  353.05
#Mann= 7 ,-1 , 0
  3787.2     .05       0    4588      .1       0  4701.8     .16       0
    4998     .07       0    5004     .16       0  5015.3      .1       0
  5374.3     .05       0
Bank Sta=4998,5004
XS Rating Curve= 0 ,0
Exp/Cntr=0.3,0.1

Type RM Length L Ch R = 1 ,2841    ,1400,1400,1400
BEGIN DESCRIPTION:
TIGER BRANCH 2.0
END DESCRIPTION:
XS GIS Cut Line= 3
      3538007.26     10295607.09      3537742.11     10294791.64
      3537460.45      10294216.6
#Sta/Elev= 30
  4109.8  345.58  4524.7  343.65  4704.4  341.85  4899.4  335.77  4914.1  334.87
  4919.4  335.36  4925.2  333.98  4935.7  333.84  4946.1  334.15  4951.3  335.62
  4956.8  335.68  4970.1   334.8  4975.7  332.34  4981.3  332.42  4986.5  331.23
  4989.3  330.73  4992.5  331.23  4998.2  332.55  5003.8  331.31  5011.8   335.5
  5020.8  336.12    5127  335.85  5155.8  335.44  5228.8  338.85  5245.7  338.57
  5324.4  342.78  5334.7  342.32  5346.9  343.53  5414.4  344.91  5607.6  343.37
#Mann= 6 ,-1 , 0
  4109.8     .05       0  4524.7      .1       0  4899.4     .16       0
  4986.5     .07       0  4992.5     .16       0    5127     .05       0
Bank Sta=4986.5,4992.5
XS Rating Curve= 0 ,0
Exp/Cntr=0.3,0.1

Type RM Length L Ch R = 1 ,1441    ,0,0,0
BEGIN DESCRIPTION:
TIGER BRANCH 1.0
END DESCRIPTION:
XS GIS Cut Line= 3
      3538616.64     10295200.86      3538371.85     10294388.36
      3537595.83     10294065.45
#Sta/Elev= 30
  3655.7  342.59  3842.9  342.53  3874.2  341.57  3926.3  341.15  4271.1  340.54
  4388.8  335.81  4419.6  335.25  4447.4  333.85  4452.6   334.2  4459.1   333.2
    4480  332.16  4532.9  332.91    4586  331.96  4591.4  332.65  4615.3  333.22
  4677.3  333.88  4769.2  332.87  4785.6  333.33  4851.6  332.81  4952.4  333.75
  4976.2  332.35  5002.5  327.72  5005.2  327.22  5008.5  327.72  5013.1   331.9
  5046.2  335.32  5058.6  336.83  5088.9  338.87  5159.4   340.3  5344.8  340.54
#Mann= 5 ,-1 , 0
  3655.7     .05       0  4388.8     .16       0  5002.5     .07       0
  5008.5     .16       0  5046.2     .05       0
Bank Sta=5002.5,5008.5
XS Rating Curve= 0 ,0
Exp/Cntr=0.3,0.1

Chan Stop Cuts=-1
Use User Specified Reach Order=0
Composite Channel Slope=5