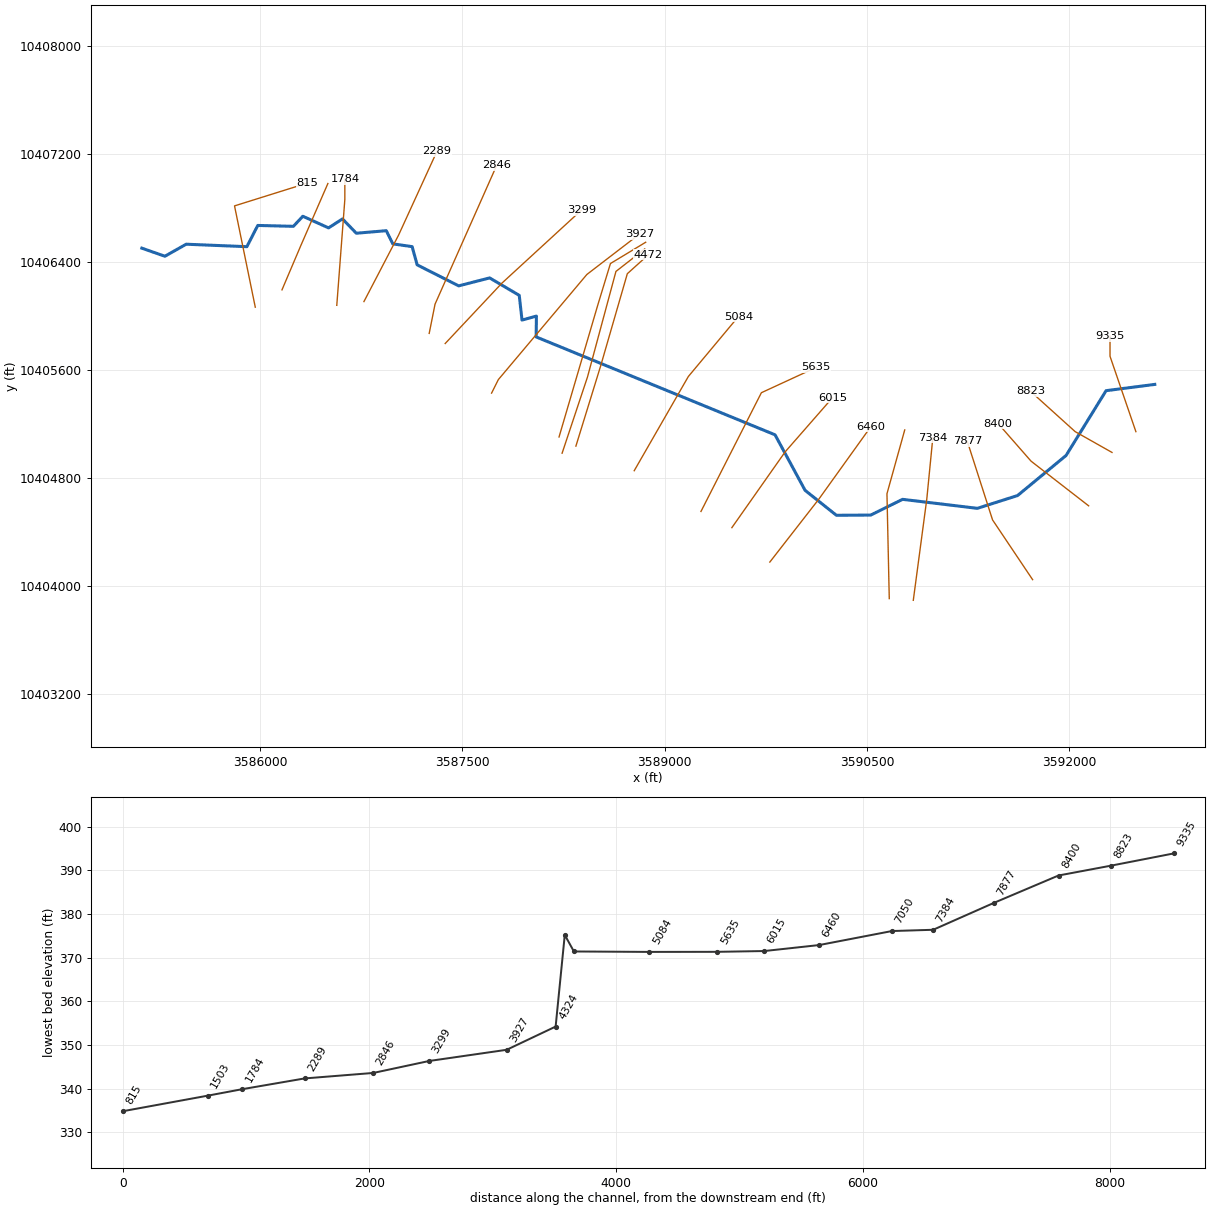
--- TOMLIN BRANCH.prj (project) ---

Proj Title=TOMLIN BRANCH Base Level Engineering
Current Plan=p01
Default Exp/Contr=0.3,0.1
English Units
Geom File=g01
Flow File=f01
Plan File=p01
BEGIN DESCRIPTION:
TOMLIN BRANCH
END DESCRIPTION:

--- TOMLIN BRANCH.p01 (plan) ---

Plan Title=Multiple Run
Short Identifier=Multiple
Geom File=g01
Flow File=f01
Subcritical Flow
K Sum by GR= 0
Std Step Tol= 0.01
Critical Tol= 0.01
Num of Std Step Trials= 20
Max Error Tol= 0.3
Flow Tol Ratio= 0.001
Split Flow NTrial= 30
Split Flow Tol= 0.02
Split Flow Ratio= 0.02
Log Output Level= 0
Friction Slope Method= 1
Unsteady Friction Slope Method= 2
Unsteady Bridges Friction Slope Method= 1
Parabolic Critical Depth
Global Vel Dist=  1 , 1 , 1
Global Log Level= 0
CheckData=True
Encroach Param= -1, 0, 0, 0
BEGIN DESCRIPTION:
Multiple Run
END DESCRIPTION:

--- TOMLIN BRANCH.f01 (steady flow) ---

Flow Title=Multiple
Number of Profiles=7
Profile Names=10-year,25-year,50-year,1pct_min,100-year,1pct_plu,500-year
River Rch & RM= TOMLIN BRANCH,Reach-1,9335
    1877    2688    3387    3110    4206    5688    6470
River Rch & RM= TOMLIN BRANCH,Reach-1,5084
    2316    3348    4245    3919    5300    7168    8245
Boundary for River Rch & Prof#=TOMLIN BRANCH,Reach-1,1
Up Type=0
Dn Type=3
Dn Slope=0.005
Boundary for River Rch & Prof#=TOMLIN BRANCH,Reach-1,2
Up Type=0
Dn Type=3
Dn Slope=0.005
Boundary for River Rch & Prof#=TOMLIN BRANCH,Reach-1,3
Up Type=0
Dn Type=3
Dn Slope=0.005
Boundary for River Rch & Prof#=TOMLIN BRANCH,Reach-1,4
Up Type=0
Dn Type=3
Dn Slope=0.005
Boundary for River Rch & Prof#=TOMLIN BRANCH,Reach-1,5
Up Type=0
Dn Type=3
Dn Slope=0.005
Boundary for River Rch & Prof#=TOMLIN BRANCH,Reach-1,6
Up Type=0
Dn Type=3
Dn Slope=0.005
Boundary for River Rch & Prof#=TOMLIN BRANCH,Reach-1,7
Up Type=0
Dn Type=3
Dn Slope=0.005

--- TOMLIN BRANCH.g01 (geometry) ---

Geom Title=Existing Conditions

River Reach=TOMLIN BRANCH,Reach-1
Reach XY= 30
      3592632.11     10405491.64      3592271.18     10405445.25
      3591974.74     10404965.01      3591615.15     10404668.04
      3591317.02     10404573.14      3590762.52     10404639.88
      3590526.59     10404523.26      3590272.11     10404521.64
      3590039.97     10404706.57      3589817.32     10405118.03
      3588046.63     10405843.45      3588048.36     10405997.97
      3587941.59     10405968.45      3587921.14     10406151.61
      3587701.65     10406280.80      3587472.20     10406221.96
      3587164.39     10406377.69      3587127.06     10406512.76
      3586984.01     10406533.25      3586935.40     10406630.82
      3586713.17     10406612.07      3586610.80     10406718.21
      3586507.59     10406651.56      3586316.92     10406737.76
      3586246.71     10406663.22      3585982.74     10406669.70
      3585902.00     10406512.36      3585452.28     10406530.61
      3585294.26     10406441.56      3585123.26     10406501.44

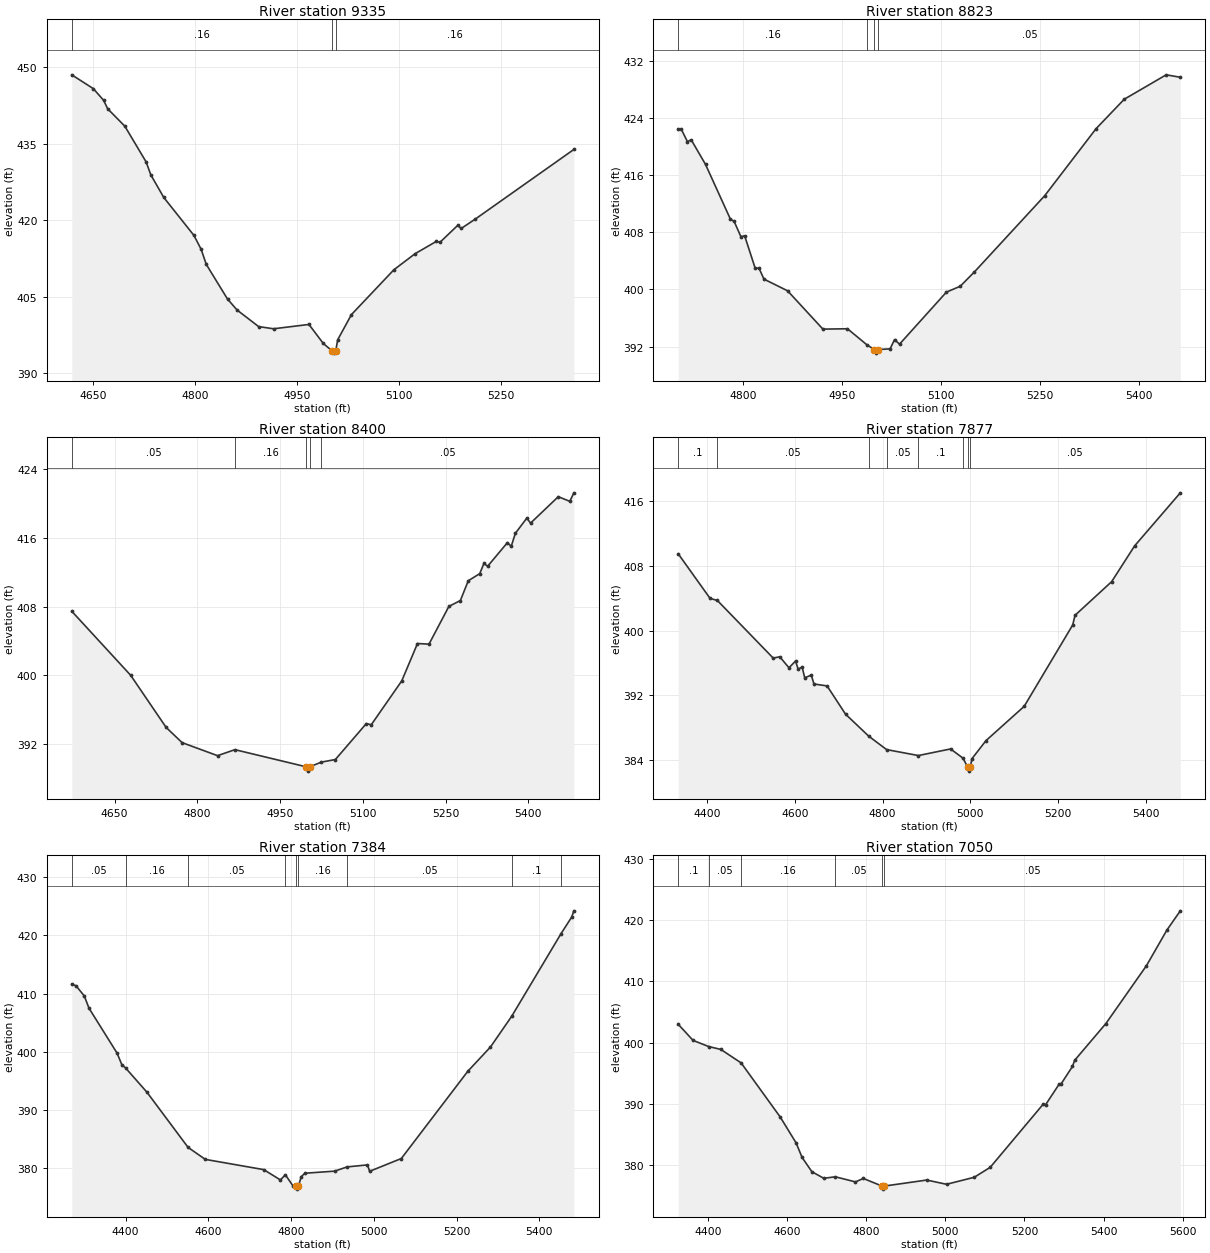
Type RM Length L Ch R = 1,9335,512,512,512
BEGIN DESCRIPTION:
TOMLIN BRANCH 19.0
END DESCRIPTION:
XS GIS Cut Line= 3
      3592492.10     10405141.67      3592300.44     10405699.98
      3592300.44     10405848.28
#Sta/Elev= 30
  4619.0  448.53  4650.7  445.82  4665.9  443.52  4671.8  441.87  4697.1  438.44
  4728.4  431.43  4735.3  428.89  4754.4  424.45  4798.7  417.01  4809.3  414.29
  4816.9  411.31  4848.1  404.52  4862.2  402.36  4893.9  399.11  4915.9  398.68
  4967.9  399.53  4989.0  395.80  5001.4  394.40  5004.2  393.90  5007.4  394.40
  5010.2  396.52  5030.4  401.46  5092.9  410.27  5124.2  413.43  5155.4  415.84
  5160.7  415.66  5186.7  418.97  5192.0  418.38  5212.6  420.21  5357.6  433.88
#Mann=3,-1,0
  4619.0    0.16       0  5001.4    0.07       0  5007.4    0.16       0
Bank Sta=5001.4,5007.4
Exp/Cntr=0.3,0.1

Type RM Length L Ch R = 1,8823,423,423,423
BEGIN DESCRIPTION:
TOMLIN BRANCH 18.0
END DESCRIPTION:
XS GIS Cut Line= 3
      3592315.07     10404987.46      3592042.11     10405141.64
      3591710.87     10405440.61
#Sta/Elev= 30
  4702.3  422.42  4706.9  422.42  4716.2  420.68  4721.9  420.94  4743.6  417.49
  4781.2  409.84  4786.9  409.52  4797.1  407.38  4802.8  407.50  4818.7  402.97
  4824.5  402.97  4832.0  401.44  4867.8  399.80  4921.2  394.44  4958.4  394.49
  4988.1  392.22  4999.1  391.58  5001.8  391.08  5005.1  391.58  5022.9  391.68
  5029.6  392.98  5037.1  392.33  5108.1  399.62  5129.0  400.44  5150.5  402.45
  5256.8  413.11  5334.5  422.49  5377.1  426.61  5440.6  430.03  5462.0  429.69
#Mann=4,-1,0
  4702.3    0.16       0  4988.1    0.05       0  4999.1    0.03       0
  5005.1    0.05       0
Bank Sta=4999.1,5005.1
Exp/Cntr=0.3,0.1

Type RM Length L Ch R = 1,8400,523,523,523
BEGIN DESCRIPTION:
TOMLIN BRANCH 17.0
END DESCRIPTION:
XS GIS Cut Line= 3
      3592142.10     10404591.65      3591715.03     10404922.88
      3591471.29     10405201.03
#Sta/Elev= 30
  4572.2  407.46  4679.0  400.00  4743.3  393.93  4772.2  392.16  4836.5  390.64
  4868.0  391.34  4997.4  389.34  5000.1  388.84  5003.4  389.34  5024.8  389.89
  5050.1  390.19  5106.3  394.38  5115.2  394.24  5170.5  399.35  5199.0  403.70
  5219.9  403.63  5255.9  408.02  5276.8  408.71  5291.1  411.01  5311.9  411.84
  5319.5  413.03  5326.2  412.70  5362.2  415.46  5368.9  415.01  5376.5  416.54
  5397.3  418.31  5404.0  417.72  5454.3  420.80  5475.2  420.26  5482.5  421.25
#Mann=5,-1,0
  4572.2    0.05       0  4868.0    0.16       0  4997.4    0.07       0
  5003.4    0.16       0  5024.8    0.05       0
Bank Sta=4997.4,5003.4
Exp/Cntr=0.3,0.1

Type RM Length L Ch R = 1,7877,493,493,493
BEGIN DESCRIPTION:
TOMLIN BRANCH 16.0
END DESCRIPTION:
XS GIS Cut Line= 3
      3591726.52     10404044.76      3591429.64     10404487.47
      3591242.13     10405070.84
#Sta/Elev= 30
  4333.6  409.51  4406.2  403.99  4422.9  403.73  4550.3  396.59  4565.3  396.75
  4586.3  395.39  4601.3  396.22  4607.3  395.22  4616.3  395.48  4622.3  394.15
  4637.3  394.48  4643.3  393.38  4673.3  393.14  4715.4  389.64  4768.4  386.91
  4809.1  385.25  4881.6  384.51  4955.1  385.33  4983.4  384.19  4994.1  383.08
  4996.8  382.58  5000.1  383.08  5004.0  384.13  5036.1  386.37  5123.1  390.61
  5233.9  400.70  5239.1  401.89  5322.7  406.06  5375.2  410.50  5479.4  417.07
#Mann=8,-1,0
  4333.6     0.1       0  4422.9    0.05       0  4768.4     0.1       0
  4809.1    0.05       0  4881.6     0.1       0  4983.4    0.05       0
  4994.1    0.03       0  5000.1    0.05       0
Bank Sta=4994.1,5000.1
Exp/Cntr=0.3,0.1

Type RM Length L Ch R = 1,7384,334,334,334
BEGIN DESCRIPTION:
TOMLIN BRANCH 15.0
END DESCRIPTION:
XS GIS Cut Line= 3
      3590842.10     10403891.64      3590942.11     10404641.64
      3590986.92     10405096.70
#Sta/Elev= 30
  4269.8  411.60  4279.9  411.35  4300.1  409.59  4311.4  407.49  4379.5  399.75
  4390.9  397.77  4399.8  397.23  4451.4  393.07  4551.0  383.58  4592.6  381.52
  4733.9  379.76  4774.2  377.99  4786.3  378.87  4804.5  376.98  4811.6  376.91
  4814.3  376.41  4817.6  376.91  4824.7  378.55  4833.5  379.14  4905.4  379.50
  4935.6  380.23  4984.8  380.57  4989.9  379.47  5066.6  381.67  5227.4  396.66
  5282.1  400.82  5333.8  406.14  5452.8  420.30  5478.6  423.15  5483.7  424.21
#Mann=9,-1,0
  4269.8    0.05       0  4399.8    0.16       0  4551.0    0.05       0
  4786.3    0.16       0  4811.6    0.03       0  4817.6    0.16       0
  4935.6    0.05       0  5333.8     0.1       0  5452.8    0.05       0
Bank Sta=4811.6,4817.6
Exp/Cntr=0.3,0.1

Type RM Length L Ch R = 1,7050,590,590,590
BEGIN DESCRIPTION:
TOMLIN BRANCH 14.0
END DESCRIPTION:
XS GIS Cut Line= 3
      3590664.01     10403904.11      3590646.87     10404681.32
      3590778.59     10405154.11
#Sta/Elev= 30
  4325.5  403.00  4363.0  400.37  4402.4  399.37  4433.1  398.90  4484.4  396.70
  4583.1  387.88  4623.1  383.67  4638.4  381.28  4663.1  378.96  4693.1  377.89
  4722.4  378.13  4773.1  377.30  4793.1  377.86  4840.2  376.62  4842.9  376.12
  4846.2  376.62  4953.2  377.60  5003.2  376.91  5073.2  378.05  5113.6  379.68
  5248.1  390.03  5253.3  389.87  5287.5  393.22  5292.7  393.29  5321.2  396.12
  5326.9  397.13  5405.7  403.12  5508.1  412.55  5560.0  418.38  5593.7  421.50
#Mann=6,-1,0
  4325.5     0.1       0  4402.4    0.05       0  4484.4    0.16       0
  4722.4    0.05       0  4840.2    0.03       0  4846.2    0.05       0
Bank Sta=4840.2,4846.2
Exp/Cntr=0.3,0.1

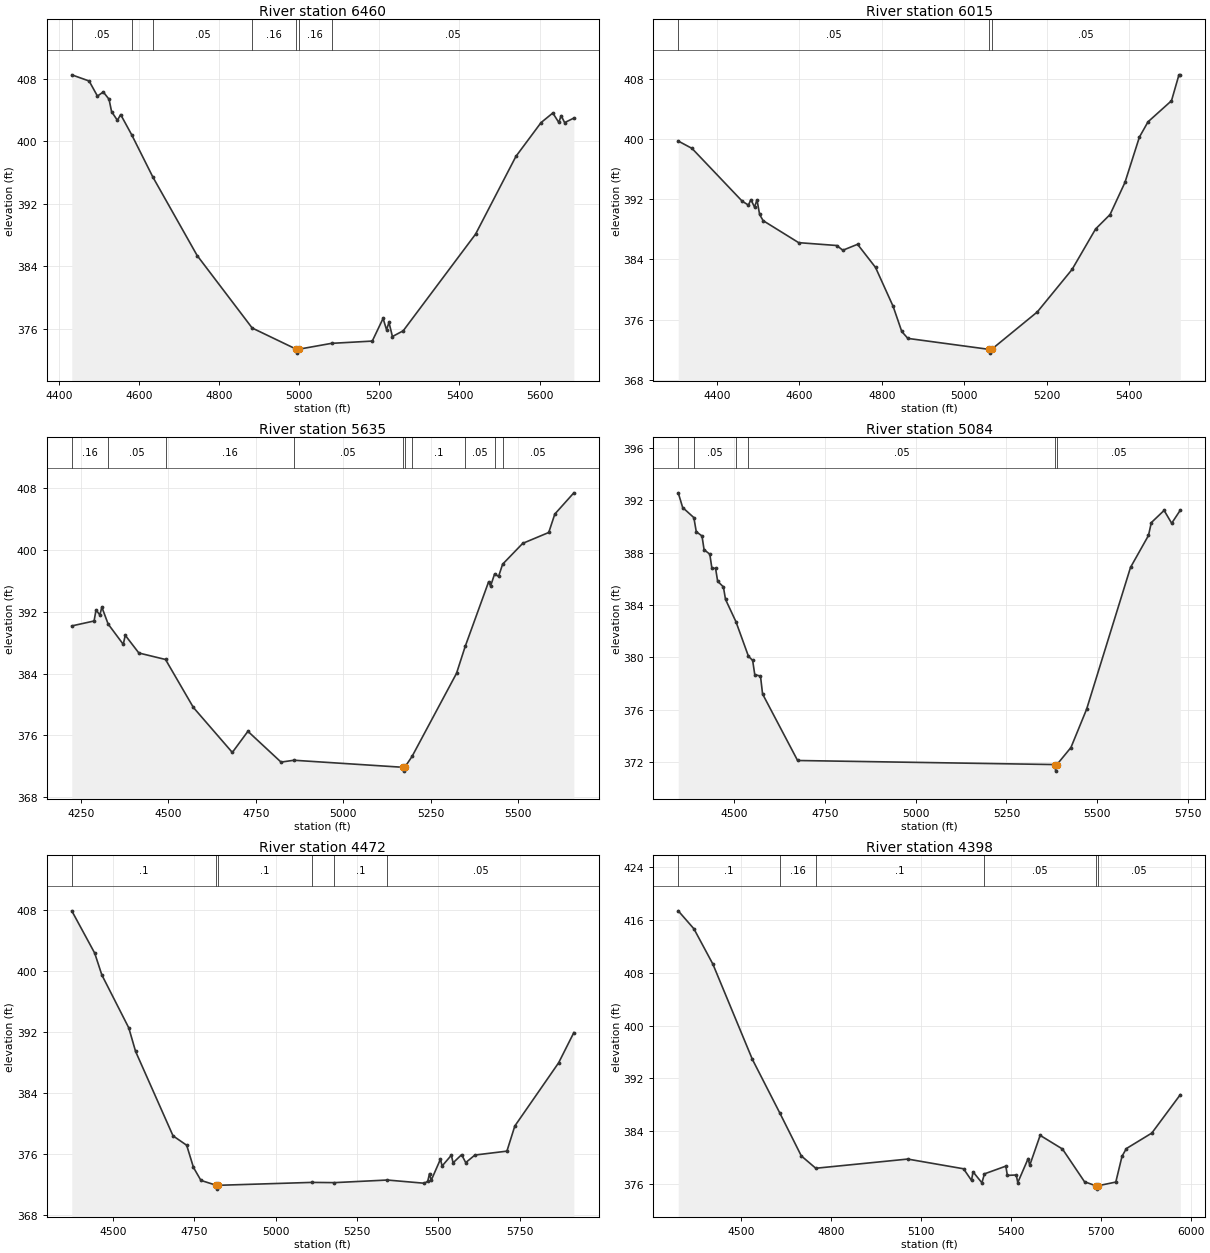
Type RM Length L Ch R = 1,6460,445,445,445
BEGIN DESCRIPTION:
TOMLIN BRANCH 13.0
END DESCRIPTION:
XS GIS Cut Line= 3
      3589778.59     10404174.96      3590142.11     10404641.64
      3590527.82     10405179.10
#Sta/Elev= 30
  4432.3  408.49  4475.6  407.70  4496.4  405.77  4510.9  406.30  4525.3  405.37
  4531.7  403.78  4546.2  402.67  4554.3  403.41  4582.1  400.80  4634.8  395.41
  4745.2  385.39  4882.6  376.12  4992.8  373.41  4995.6  372.91  4998.8  373.41
  5080.6  374.16  5182.3  374.45  5209.3  377.35  5217.9  375.90  5224.0  376.84
  5232.6  375.03  5259.6  375.77  5440.1  388.12  5540.8  398.06  5603.5  402.38
  5632.9  403.61  5647.7  402.41  5653.8  403.27  5662.4  402.38  5685.4  402.96
#Mann=7,-1,0
  4432.3    0.05       0  4582.1    0.16       0  4634.8    0.05       0
  4882.6    0.16       0  4992.8    0.07       0  4998.8    0.16       0
  5080.6    0.05       0
Bank Sta=4992.8,4998.8
Exp/Cntr=0.3,0.1

Type RM Length L Ch R = 1,6015,380,380,380
BEGIN DESCRIPTION:
TOMLIN BRANCH 12.0
END DESCRIPTION:
XS GIS Cut Line= 3
      3589497.33     10404430.16      3589892.11     10404991.64
      3590242.12     10405391.66
#Sta/Elev= 30
  4306.2  399.76  4339.6  398.78  4461.5  391.75  4476.4  391.24  4482.5  391.96
  4491.2  390.98  4497.3  391.92  4503.6  389.99  4512.1  389.17  4598.3  386.24
  4690.7  385.86  4705.5  385.23  4741.2  386.02  4784.8  382.94  4827.5  377.76
  4848.4  374.42  4863.2  373.50  5060.3  372.04  5063.0  371.54  5066.3  372.04
  5177.2  377.02  5261.6  382.68  5318.6  388.06  5353.7  389.98  5389.8  394.25
  5424.9  400.29  5445.8  402.32  5502.7  405.12  5520.8  408.57  5524.1  408.57
#Mann=3,-1,0
  4306.2    0.05       0  5060.3   0.033       0  5066.3    0.05       0
Bank Sta=5060.3,5066.3
Exp/Cntr=0.3,0.1

Type RM Length L Ch R = 1,5635,551,551,551
BEGIN DESCRIPTION:
TOMLIN BRANCH 11.0
END DESCRIPTION:
XS GIS Cut Line= 3
      3589268.18     10404549.96      3589716.10     10405430.18
      3590121.20     10405617.15
#Sta/Elev= 30
  4224.6  390.18  4288.3  390.82  4293.9  392.24  4304.9  391.60  4310.5  392.62
  4328.4  390.43  4371.7  387.79  4377.3  388.97  4416.2  386.67  4492.3  385.83
  4571.9  379.61  4683.1  373.78  4727.6  376.52  4822.2  372.53  4859.1  372.77
  5169.5  371.86  5172.2  371.36  5175.5  371.86  5196.3  373.26  5323.3  384.03
  5348.1  387.52  5415.1  395.91  5420.6  395.35  5432.0  396.90  5443.5  396.60
  5455.0  398.18  5512.4  400.88  5586.7  402.29  5604.1  404.68  5658.4  407.43
#Mann=10,-1,0
  4224.6    0.16       0  4328.4    0.05       0  4492.3    0.16       0
  4859.1    0.05       0  5169.5   0.033       0  5175.5    0.05       0
  5196.3     0.1       0  5348.1    0.05       0  5432.0    0.16       0
  5455.0    0.05       0
Bank Sta=5169.5,5175.5
Exp/Cntr=0.3,0.1

Type RM Length L Ch R = 1,5084,612,612,612
BEGIN DESCRIPTION:
TOMLIN BRANCH 10.0
END DESCRIPTION:
XS GIS Cut Line= 3
      3588773.37     10404852.02      3589174.43     10405549.97
      3589544.22     10405992.67
#Sta/Elev= 30
  4346.7  392.55  4358.9  391.43  4389.7  390.66  4396.3  389.59  4412.1  389.26
  4417.8  388.22  4433.6  387.87  4439.4  386.79  4449.4  386.80  4455.2  385.81
  4471.0  385.38  4476.8  384.43  4505.5  382.73  4540.0  380.09  4551.5  379.78
  4557.3  378.70  4573.1  378.58  4578.8  377.22  4675.2  372.15  5382.9  371.84
  5385.6  371.34  5388.9  371.84  5427.5  373.14  5470.5  376.05  5591.5  386.87
  5640.9  389.30  5648.7  390.28  5683.9  391.21  5704.7  390.23  5728.5  391.23
#Mann=6,-1,0
  4346.7    0.16       0  4389.7    0.05       0  4505.5     0.1       0
  4540.0    0.05       0  5382.9   0.033       0  5388.9    0.05       0
Bank Sta=5382.9,5388.9
Exp/Cntr=0.3,0.1

Type RM Length L Ch R = 1,4472,74,74,74
BEGIN DESCRIPTION:
TOMLIN BRANCH 9.1
END DESCRIPTION:
XS GIS Cut Line= 4
      3588341.09     10405034.34      3588525.78     10405632.79
      3588722.24     10406312.10      3588877.50     10406451.79
#Sta/Elev= 30
  4373.7  407.85  4444.1  402.32  4466.1  399.46  4548.8  392.54  4569.7  389.46
  4684.8  378.41  4726.7  377.18  4747.6  374.27  4770.5  372.58  4817.9  371.94
  4820.6  371.44  4823.9  371.94  5110.7  372.32  5180.7  372.29  5343.0  372.63
  5456.8  372.21  5467.2  372.47  5472.6  373.47  5477.8  372.59  5506.2  375.35
  5511.4  374.47  5539.8  375.88  5545.0  374.88  5571.3  375.95  5583.8  374.91
  5612.2  375.90  5710.4  376.41  5734.7  379.70  5869.3  387.97  5916.0  391.92
#Mann=6,-1,0
  4373.7     0.1       0  4817.9    0.07       0  4823.9     0.1       0
  5110.7    0.05       0  5180.7     0.1       0  5343.0    0.05       0
Bank Sta=4817.9,4823.9
Exp/Cntr=0.3,0.1

Type RM Length L Ch R = 1,4398,74,74,74
BEGIN DESCRIPTION:
TOMLIN BRANCH 9.0
END DESCRIPTION:
XS GIS Cut Line= 4
      3588238.82     10404981.88      3588426.95     10405546.34
      3588637.89     10406328.90      3588851.46     10406495.59
#Sta/Elev= 30
  4288.9  417.36  4341.4  414.63  4404.6  409.29  4536.4  394.88  4628.0  386.76
  4699.8  380.26  4748.1  378.39  5055.1  379.78  5241.5  378.31  5268.1  376.55
  5273.2  377.85  5302.8  376.19  5311.3  377.54  5382.7  378.71  5387.8  377.31
  5417.4  377.37  5422.6  376.22  5457.3  379.86  5462.5  378.83  5497.3  383.37
  5571.9  381.30  5645.4  376.35  5683.5  375.73  5686.3  375.23  5689.5  375.73
  5749.9  376.30  5770.7  380.21  5785.2  381.37  5870.2  383.72  5965.3  389.53
#Mann=6,-1,0
  4288.9     0.1       0  4628.0    0.16       0  4748.1     0.1       0
  5311.3    0.05       0  5683.5    0.07       0  5689.5    0.05       0
Bank Sta=5683.5,5689.5
Exp/Cntr=0.3,0.1

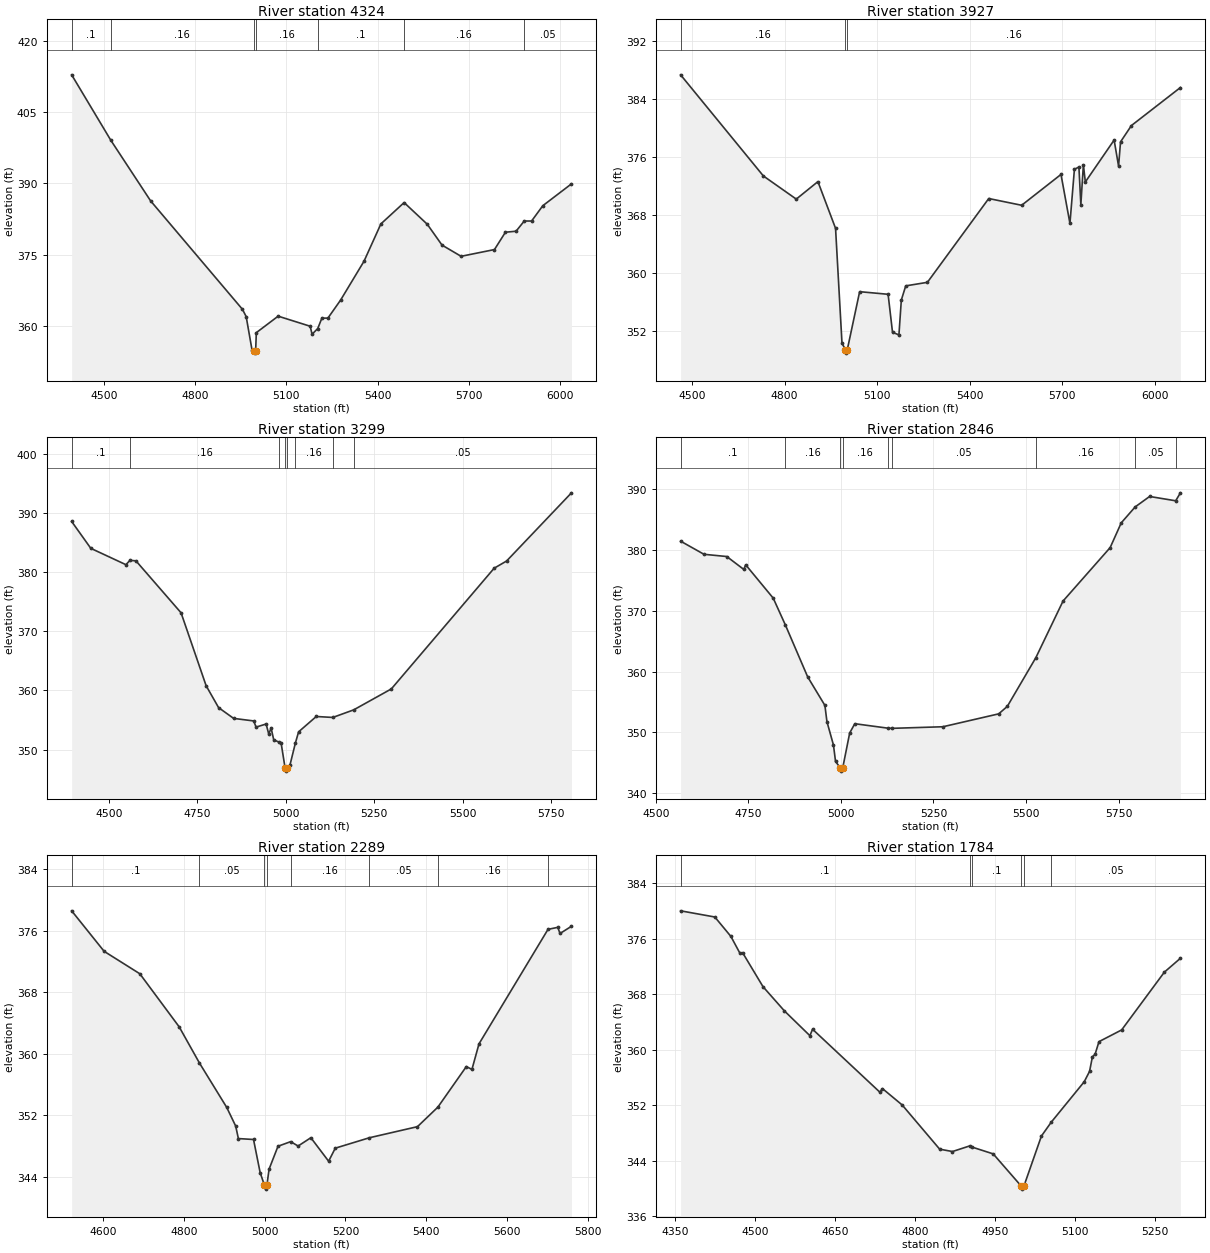
Type RM Length L Ch R = 1,4324,397,397,397
BEGIN DESCRIPTION:
TOMLIN BRANCH 8.0
END DESCRIPTION:
XS GIS Cut Line= 4
      3588216.09     10405102.03      3588503.77     10406081.50
      3588597.09     10406387.49      3588858.37     10406545.12
#Sta/Elev= 30
  4392.8  412.82  4521.8  399.04  4653.0  386.27  4955.2  363.46  4967.5  361.93
  4986.5  355.00  4992.7  354.74  4995.4  354.24  4998.7  354.74  5000.9  358.55
  5072.8  362.02  5178.2  359.90  5184.5  358.22  5203.1  359.41  5216.8  361.61
  5236.6  361.61  5278.3  365.39  5355.5  373.58  5411.1  381.44  5487.6  385.93
  5563.8  381.37  5612.4  376.98  5675.2  374.62  5785.1  376.04  5821.2  379.69
  5856.2  379.90  5883.2  382.05  5907.4  382.05  5944.3  385.27  6038.7  389.87
#Mann=7,-1,0
  4392.8     0.1       0  4521.8    0.16       0  4992.7    0.07       0
  4998.7    0.16       0  5203.1     0.1       0  5487.6    0.16       0
  5883.2    0.05       0
Bank Sta=4992.7,4998.7
Exp/Cntr=0.3,0.1

Type RM Length L Ch R = 1,3927,628,628,628
BEGIN DESCRIPTION:
TOMLIN BRANCH 7.0
END DESCRIPTION:
XS GIS Cut Line= 4
      3587716.05     10405427.02      3587766.06     10405527.06
      3588422.32     10406306.33      3588811.18     10406604.91
#Sta/Elev= 30
  4462.7  387.28  4731.1  373.34  4837.8  370.15  4908.0  372.56  4965.2  366.12
  4986.1  350.26  4997.4  349.42  5000.1  348.92  5003.4  349.42  5043.3  357.39
  5135.6  357.03  5149.9  351.80  5170.7  351.43  5178.5  356.24  5192.8  358.19
  5263.1  358.68  5462.0  370.23  5568.7  369.30  5696.3  373.55  5725.3  366.80
  5739.8  374.26  5754.4  374.57  5760.7  369.40  5768.9  374.89  5775.2  372.51
  5868.6  378.29  5883.0  374.70  5889.4  378.04  5924.7  380.29  6083.6  385.53
#Mann=3,-1,0
  4462.7    0.16       0  4997.4    0.07       0  5003.4    0.16       0
Bank Sta=4997.4,5003.4
Exp/Cntr=0.3,0.1

Type RM Length L Ch R = 1,3299,453,453,453
BEGIN DESCRIPTION:
TOMLIN BRANCH 6.0
END DESCRIPTION:
XS GIS Cut Line= 3
      3587372.32     10405794.74      3587792.11     10406241.64
      3588380.63     10406782.00
#Sta/Elev= 30
  4395.3  388.54  4449.4  384.00  4548.6  381.24  4560.0  381.97  4576.9  381.89
  4704.4  373.11  4775.2  360.79  4810.4  357.09  4852.9  355.27  4909.5  354.84
  4916.4  353.80  4944.7  354.32  4952.0  352.65  4958.9  353.61  4966.2  351.65
  4982.4  351.23  4987.2  351.06  4998.4  346.86  5001.1  346.36  5004.4  346.86
  5011.8  347.32  5027.4  351.11  5036.5  353.00  5086.4  355.59  5133.1  355.43
  5192.1  356.71  5298.5  360.25  5588.9  380.64  5624.1  381.86  5807.4  393.38
#Mann=8,-1,0
  4395.3     0.1       0  4560.0    0.16       0  4982.4    0.05       0
  4998.4    0.03       0  5004.4    0.05       0  5027.4    0.16       0
  5133.1     0.1       0  5192.1    0.05       0
Bank Sta=4998.4,5004.4
Exp/Cntr=0.3,0.1

Type RM Length L Ch R = 1,2846,557,557,557
BEGIN DESCRIPTION:
TOMLIN BRANCH 5.0
END DESCRIPTION:
XS GIS Cut Line= 3
      3587253.56     10405869.73      3587296.87     10406086.28
      3587755.16     10407117.71
#Sta/Elev= 30
  4567.2  381.45  4630.3  379.29  4691.9  378.92  4737.8  376.80  4742.9  377.56
  4817.3  372.07  4850.4  367.62  4910.3  359.12  4956.8  354.43  4962.3  351.76
  4979.9  347.91  4985.5  345.22  4998.8  344.12  5001.6  343.62  5004.8  344.12
  5023.7  349.89  5037.5  351.42  5126.6  350.69  5138.6  350.66  5275.4  350.92
  5426.0  353.04  5449.3  354.27  5526.4  362.29  5599.8  371.60  5727.0  380.39
  5756.9  384.46  5794.5  387.08  5833.5  388.80  5903.9  388.09  5916.7  389.40
#Mann=9,-1,0
  4567.2     0.1       0  4850.4    0.16       0  4998.8    0.07       0
  5004.8    0.16       0  5126.6     0.1       0  5138.6    0.05       0
  5526.4    0.16       0  5794.5    0.05       0  5903.9     0.1       0
Bank Sta=4998.8,5004.8
Exp/Cntr=0.3,0.1

Type RM Length L Ch R = 1,2289,505,505,505
BEGIN DESCRIPTION:
TOMLIN BRANCH 4.0
END DESCRIPTION:
XS GIS Cut Line= 3
      3586769.90     10406105.49      3587026.86     10406598.58
      3587310.80     10407218.41
#Sta/Elev= 30
  4522.1  378.58  4602.5  373.31  4690.9  370.39  4788.4  363.48  4838.5  358.78
  4906.2  352.99  4928.3  350.57  4935.0  348.94  4972.5  348.82  4988.9  344.51
  4999.6  342.86  5002.4  342.36  5005.6  342.86  5011.0  344.96  5033.1  347.94
  5064.5  348.54  5082.9  347.97  5114.5  349.05  5158.5  345.99  5174.9  347.69
  5259.7  349.05  5378.5  350.49  5429.0  353.03  5499.5  358.31  5513.4  357.94
  5530.9  361.27  5701.8  376.17  5726.0  376.43  5731.5  375.63  5759.9  376.57
#Mann=8,-1,0
  4522.1     0.1       0  4838.5    0.05       0  4999.6    0.04       0
  5005.6    0.05       0  5064.5    0.16       0  5259.7    0.05       0
  5429.0    0.16       0  5701.8    0.05       0
Bank Sta=4999.6,5005.6
Exp/Cntr=0.3,0.1

Type RM Length L Ch R = 1,1784,281,281,281
BEGIN DESCRIPTION:
TOMLIN BRANCH 3.0
END DESCRIPTION:
XS GIS Cut Line= 3
      3586568.53     10406077.73      3586628.22     10406861.78
      3586628.22     10407011.76
#Sta/Elev= 30
  4360.9  380.02  4425.0  379.13  4455.1  376.33  4472.0  373.91  4477.0  373.99
  4515.3  369.08  4555.4  365.59  4603.1  362.02  4608.1  362.95  4734.1  353.88
  4739.1  354.39  4776.0  352.03  4846.2  345.66  4870.2  345.32  4902.5  346.13
  4906.1  345.98  4946.5  344.98  4998.3  340.40  5001.0  339.90  5004.3  340.40
  5036.8  347.55  5055.2  349.55  5117.0  355.38  5127.0  356.88  5132.3  358.97
  5137.3  359.33  5144.6  361.16  5187.1  362.85  5267.1  371.18  5297.2  373.18
#Mann=6,-1,0
  4360.9     0.1       0  4902.5    0.05       0  4906.1     0.1       0
  4998.3    0.07       0  5004.3     0.1       0  5055.2    0.05       0
Bank Sta=4998.3,5004.3
Exp/Cntr=0.3,0.1

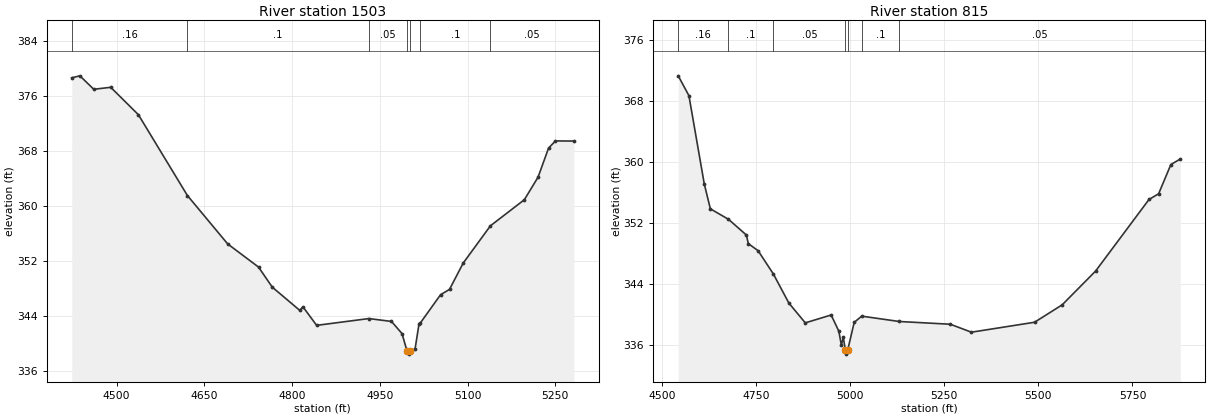
Type RM Length L Ch R = 1,1503,688,688,688
BEGIN DESCRIPTION:
TOMLIN BRANCH 2.0
END DESCRIPTION:
XS GIS Cut Line= 3
      3586162.28     10406192.34      3586301.17     10406518.72
      3586502.55     10406980.52
#Sta/Elev= 30
  4423.2  378.65  4437.1  378.94  4460.8  376.98  4489.8  377.27  4537.1  373.28
  4620.9  361.51  4689.8  354.46  4742.5  351.09  4766.1  348.16  4813.1  344.78
  4818.5  345.30  4841.9  342.60  4931.2  343.59  4969.9  343.17  4987.9  341.40
  4996.3  338.91  4999.0  338.41  5002.3  338.91  5010.2  339.16  5016.8  342.73
  5019.3  342.96  5053.8  347.06  5069.1  347.84  5092.5  351.67  5139.1  357.10
  5197.1  360.90  5220.5  364.18  5238.4  368.40  5250.2  369.46  5281.7  369.44
#Mann=7,-1,0
  4423.2    0.16       0  4620.9     0.1       0  4931.2    0.05       0
  4996.3    0.03       0  5002.3    0.05       0  5019.3     0.1       0
  5139.1    0.05       0
Bank Sta=4996.3,5002.3
Exp/Cntr=0.3,0.1

Type RM Length L Ch R = 1,815,0,0,0
BEGIN DESCRIPTION:
TOMLIN BRANCH 1.0
END DESCRIPTION:
XS GIS Cut Line= 3
      3585964.36     10406063.85      3585810.54     10406814.69
      3586351.53     10406984.00
#Sta/Elev= 30
  4543.7  371.26  4572.1  368.66  4612.9  357.10  4629.0  353.86  4677.1  352.49
  4724.7  350.43  4729.8  349.31  4755.8  348.38  4796.4  345.33  4837.5  341.53
  4881.1  338.94  4949.8  339.97  4970.2  337.85  4976.9  336.01  4982.0  337.07
  4987.6  335.35  4990.3  334.85  4993.6  335.35  5011.0  339.01  5031.0  339.82
  5130.4  339.12  5266.2  338.76  5322.3  337.72  5489.9  339.02  5563.3  341.30
  5651.9  345.71  5793.8  355.08  5819.4  355.83  5851.9  359.65  5877.0  360.38
#Mann=7,-1,0
  4543.7    0.16       0  4677.1     0.1       0  4796.4    0.05       0
  4987.6   0.035       0  4993.6    0.05       0  5031.0     0.1       0
  5130.4    0.05       0
Bank Sta=4987.6,4993.6
Exp/Cntr=0.3,0.1

Chan Stop Cuts=-1