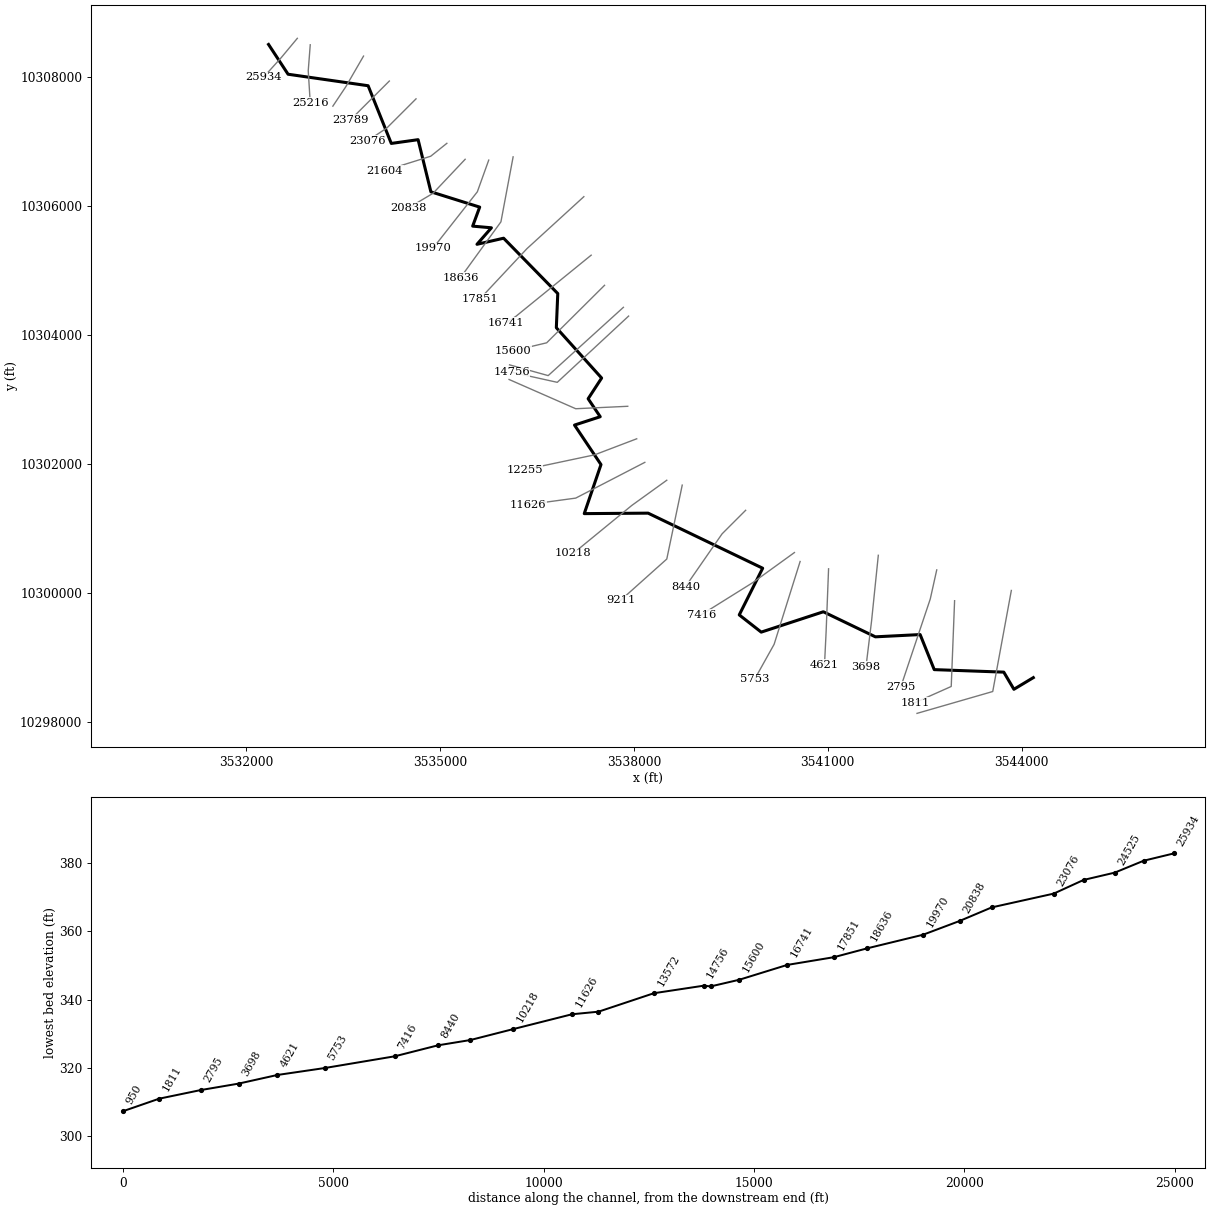
--- TOWN BRANCH.prj (project) ---

Proj Title=TOWN BRANCH Base Level Engineering
Current Plan=p01
Default Exp/Contr=0.3,0.1
English Units
Geom File=g01
Flow File=f01
Plan File=p01
BEGIN DESCRIPTION:
TOWN BRANCH
END DESCRIPTION:

--- TOWN BRANCH.p01 (plan) ---

Plan Title=Multiple Run
Short Identifier=Multiple
Geom File=g01
Flow File=f01
Subcritical Flow
K Sum by GR= 0
Std Step Tol= 0.01
Critical Tol= 0.01
Num of Std Step Trials= 20
Max Error Tol= 0.3
Flow Tol Ratio= 0.001
Split Flow NTrial= 30
Split Flow Tol= 0.02
Split Flow Ratio= 0.02
Log Output Level= 0
Friction Slope Method= 1
Unsteady Friction Slope Method= 2
Unsteady Bridges Friction Slope Method= 1
Parabolic Critical Depth
Global Vel Dist=  1 , 1 , 1
Global Log Level= 0
CheckData=True
Encroach Param= -1, 0, 0, 0
BEGIN DESCRIPTION:
Multiple Run
END DESCRIPTION:

--- TOWN BRANCH.f01 (steady flow) ---

Flow Title=Multiple
Number of Profiles=7
Profile Names=10-year,25-year,50-year,1pct_min,100-year,1pct_plu,500-year
River Rch & RM= TOWN BRANCH,Reach-1,25934
     544     734     888     788    1066    1442    1540
River Rch & RM= TOWN BRANCH,Reach-1,18636
     789    1082    1325    1187    1605    2170    2362
River Rch & RM= TOWN BRANCH,Reach-1,12255
    1057    1471    1818    1642    2221    3004    3326
River Rch & RM= TOWN BRANCH,Reach-1,8440
    1160    1616    1998    1805    2440    3300    3654
Boundary for River Rch & Prof#=TOWN BRANCH,Reach-1,1
Up Type=0
Dn Type=3
Dn Slope=0.005
Boundary for River Rch & Prof#=TOWN BRANCH,Reach-1,2
Up Type=0
Dn Type=3
Dn Slope=0.005
Boundary for River Rch & Prof#=TOWN BRANCH,Reach-1,3
Up Type=0
Dn Type=3
Dn Slope=0.005
Boundary for River Rch & Prof#=TOWN BRANCH,Reach-1,4
Up Type=0
Dn Type=3
Dn Slope=0.005
Boundary for River Rch & Prof#=TOWN BRANCH,Reach-1,5
Up Type=0
Dn Type=3
Dn Slope=0.005
Boundary for River Rch & Prof#=TOWN BRANCH,Reach-1,6
Up Type=0
Dn Type=3
Dn Slope=0.005
Boundary for River Rch & Prof#=TOWN BRANCH,Reach-1,7
Up Type=0
Dn Type=3
Dn Slope=0.005

--- TOWN BRANCH.g01 (geometry) ---

Geom Title=Existing Conditions

River Reach=TOWN BRANCH,Reach-1
Reach XY= 30
      3532346.85     10308496.71      3532648.88     10308035.82
      3533888.06     10307857.70      3534246.30     10306964.21
      3534661.23     10307022.37      3534859.06     10306215.17
      3535614.34     10305978.06      3535505.86     10305683.58
      3535796.05     10305657.67      3535572.47     10305402.19
      3535984.53     10305496.36      3536822.76     10304639.37
      3536800.54     10304110.21      3537501.51     10303331.15
      3537292.79     10303010.63      3537479.92     10302732.05
      3537081.97     10302602.69      3537491.56     10301991.13
      3537232.60     10301231.55      3538220.85     10301238.84
      3539993.64     10300386.08      3539631.17     10299663.19
      3539971.46     10299396.49      3540932.82     10299711.58
      3541738.11     10299323.57      3542430.73     10299358.53
      3542648.84     10298815.72      3543725.14     10298776.91
      3543881.95     10298511.24      3544182.11     10298691.64

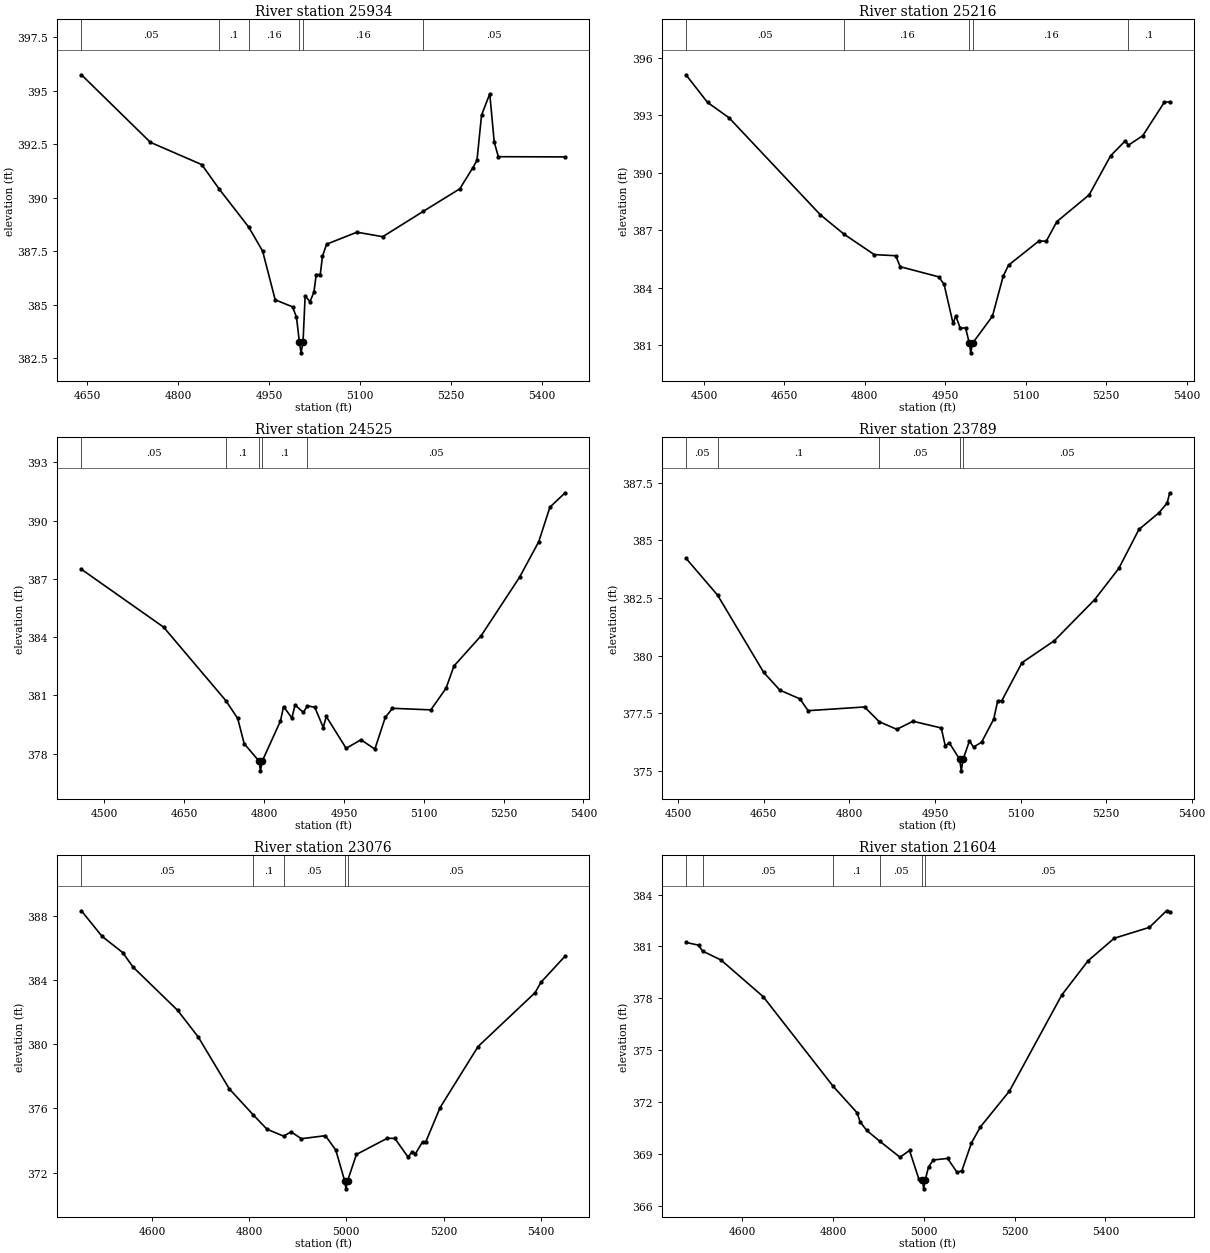
Type RM Length L Ch R = 1,25934,718,718,718
BEGIN DESCRIPTION:
TOWN BRANCH 43.0
END DESCRIPTION:
XS GIS Cut Line= 3
      3532792.11     10308591.65      3532542.11     10308291.64
      3532269.07     10307989.44
#Sta/Elev= 30
  4640.0  395.75  4753.9  392.59  4838.5  391.55  4867.7  390.39  4915.9  388.63
  4938.8  387.51  4959.6  385.23  4988.2  384.90  4994.7  384.42  4999.5  383.25
  5002.3  382.75  5005.5  383.25  5009.0  385.42  5016.9  385.14  5023.4  385.58
  5027.3  386.41  5033.9  386.41  5037.6  387.27  5044.4  387.83  5094.4  388.39
  5137.0  388.18  5204.1  389.37  5264.1  390.42  5285.7  391.41  5292.4  391.75
  5299.9  393.86  5313.5  394.86  5320.8  392.61  5327.6  391.92  5437.8  391.91
#Mann=6,-1,0
  4640.0    0.05       0  4867.7     0.1       0  4915.9    0.16       0
  4999.5    0.07       0  5005.5    0.16       0  5204.1    0.05       0
Bank Sta=4999.5,5005.5
Exp/Cntr=0.3,0.1

Type RM Length L Ch R = 1,25216,691,691,691
BEGIN DESCRIPTION:
TOWN BRANCH 41.0
END DESCRIPTION:
XS GIS Cut Line= 3
      3532992.11     10308491.68      3532961.06     10308090.07
      3532992.11     10307591.65
#Sta/Elev= 30
  4466.4  395.10  4506.6  393.66  4546.7  392.86  4717.2  387.80  4761.4  386.79
  4817.5  385.73  4857.6  385.67  4865.9  385.10  4937.8  384.57  4947.8  384.18
  4964.6  382.14  4969.6  382.54  4977.9  381.89  4987.9  381.91  4994.9  381.11
  4997.6  380.61  5000.9  381.11  5038.0  382.52  5058.0  384.60  5068.0  385.18
  5125.2  386.45  5138.2  386.42  5158.2  387.45  5218.3  388.84  5258.4  390.88
  5285.8  391.66  5291.6  391.43  5318.5  391.93  5358.6  393.67  5368.6  393.69
#Mann=5,-1,0
  4466.4    0.05       0  4761.4    0.16       0  4994.9    0.07       0
  5000.9    0.16       0  5291.6     0.1       0
Bank Sta=4994.9,5000.9
Exp/Cntr=0.3,0.1

Type RM Length L Ch R = 1,24525,736,736,736
BEGIN DESCRIPTION:
TOWN BRANCH 40.0
END DESCRIPTION:
XS GIS Cut Line= 3
      3533816.63     10308316.51      3533542.11     10307841.64
      3533342.09     10307541.61
#Sta/Elev= 30
  4456.7  387.50  4611.2  384.52  4728.0  380.74  4750.4  379.82  4762.6  378.52
  4790.5  377.62  4793.2  377.12  4796.5  377.62  4830.8  379.69  4836.6  380.43
  4852.3  379.84  4858.1  380.51  4873.9  380.13  4881.4  380.47  4895.4  380.39
  4911.2  379.35  4916.9  379.92  4954.2  378.28  4982.1  378.72  5008.2  378.24
  5027.7  379.87  5041.3  380.34  5113.4  380.26  5141.9  381.37  5156.9  382.52
  5208.0  384.08  5280.1  387.09  5316.2  388.92  5337.2  390.70  5365.8  391.44
#Mann=5,-1,0
  4456.7    0.05       0  4728.0     0.1       0  4790.5   0.035       0
  4796.5     0.1       0  4881.4    0.05       0
Bank Sta=4790.5,4796.5
Exp/Cntr=0.3,0.1

Type RM Length L Ch R = 1,23789,713,713,713
BEGIN DESCRIPTION:
TOWN BRANCH 38.0
END DESCRIPTION:
XS GIS Cut Line= 3
      3534215.97     10307930.39      3533915.95     10307630.38
      3533616.56     10307330.98
#Sta/Elev= 30
  4513.7  384.22  4569.1  382.62  4649.9  379.27  4678.2  378.50  4713.5  378.12
  4727.7  377.61  4826.7  377.77  4852.4  377.13  4883.2  376.80  4911.5  377.15
  4961.0  376.86  4968.1  376.09  4975.2  376.21  4993.4  375.50  4996.1  375.00
  4999.4  375.50  5010.5  376.30  5017.6  376.03  5031.7  376.24  5053.0  377.24
  5060.0  378.04  5067.1  378.04  5102.5  379.69  5159.0  380.64  5229.7  382.42
  5272.2  383.78  5307.5  385.47  5342.9  386.20  5357.0  386.62  5361.4  387.06
#Mann=5,-1,0
  4513.7    0.05       0  4569.1     0.1       0  4852.4    0.05       0
  4993.4   0.035       0  4999.4    0.05       0
Bank Sta=4993.4,4999.4
Exp/Cntr=0.3,0.1

Type RM Length L Ch R = 1,23076,1472,1472,1472
BEGIN DESCRIPTION:
TOWN BRANCH 37.0
END DESCRIPTION:
XS GIS Cut Line= 3
      3534629.20     10307654.55      3534179.19     10307204.55
      3533880.74     10307005.58
#Sta/Elev= 30
  4455.0  388.30  4497.4  386.71  4539.9  385.70  4561.1  384.80  4653.0  382.10
  4695.4  380.44  4759.1  377.22  4808.0  375.61  4836.8  374.70  4871.1  374.27
  4886.3  374.54  4907.5  374.11  4957.0  374.30  4978.3  373.40  4996.5  371.49
  4999.2  370.99  5002.5  371.49  5020.7  373.13  5084.3  374.14  5099.8  374.13
  5126.8  372.97  5135.8  373.30  5141.8  373.16  5156.9  373.92  5162.9  373.88
  5192.9  376.05  5271.0  379.85  5388.2  383.20  5400.4  383.85  5450.1  385.48
#Mann=5,-1,0
  4455.0    0.05       0  4808.0     0.1       0  4871.1    0.05       0
  4996.5   0.035       0  5002.5    0.05       0
Bank Sta=4996.5,5002.5
Exp/Cntr=0.3,0.1

Type RM Length L Ch R = 1,21604,766,766,766
BEGIN DESCRIPTION:
TOWN BRANCH 36.0
END DESCRIPTION:
XS GIS Cut Line= 3
      3535106.30     10306965.79      3534856.33     10306765.82
      3534145.46     10306542.98
#Sta/Elev= 30
  4476.3  381.23  4503.9  381.07  4512.7  380.73  4553.5  380.21  4646.4  378.09
  4800.5  372.90  4853.2  371.37  4859.5  370.86  4874.2  370.35  4902.8  369.73
  4947.6  368.80  4968.5  369.19  4989.2  367.53  4997.0  367.47  4999.7  366.97
  5003.0  367.47  5010.4  368.24  5020.9  368.64  5052.4  368.73  5073.3  367.92
  5083.8  368.02  5104.8  369.62  5124.2  370.54  5188.6  372.63  5303.9  378.19
  5361.8  380.17  5419.2  381.47  5496.7  382.10  5534.4  383.06  5541.4  383.00
#Mann=6,-1,0
  4476.3     0.1       0  4512.7    0.05       0  4800.5     0.1       0
  4902.8    0.05       0  4997.0   0.035       0  5003.0    0.05       0
Bank Sta=4997,5003
Exp/Cntr=0.3,0.1

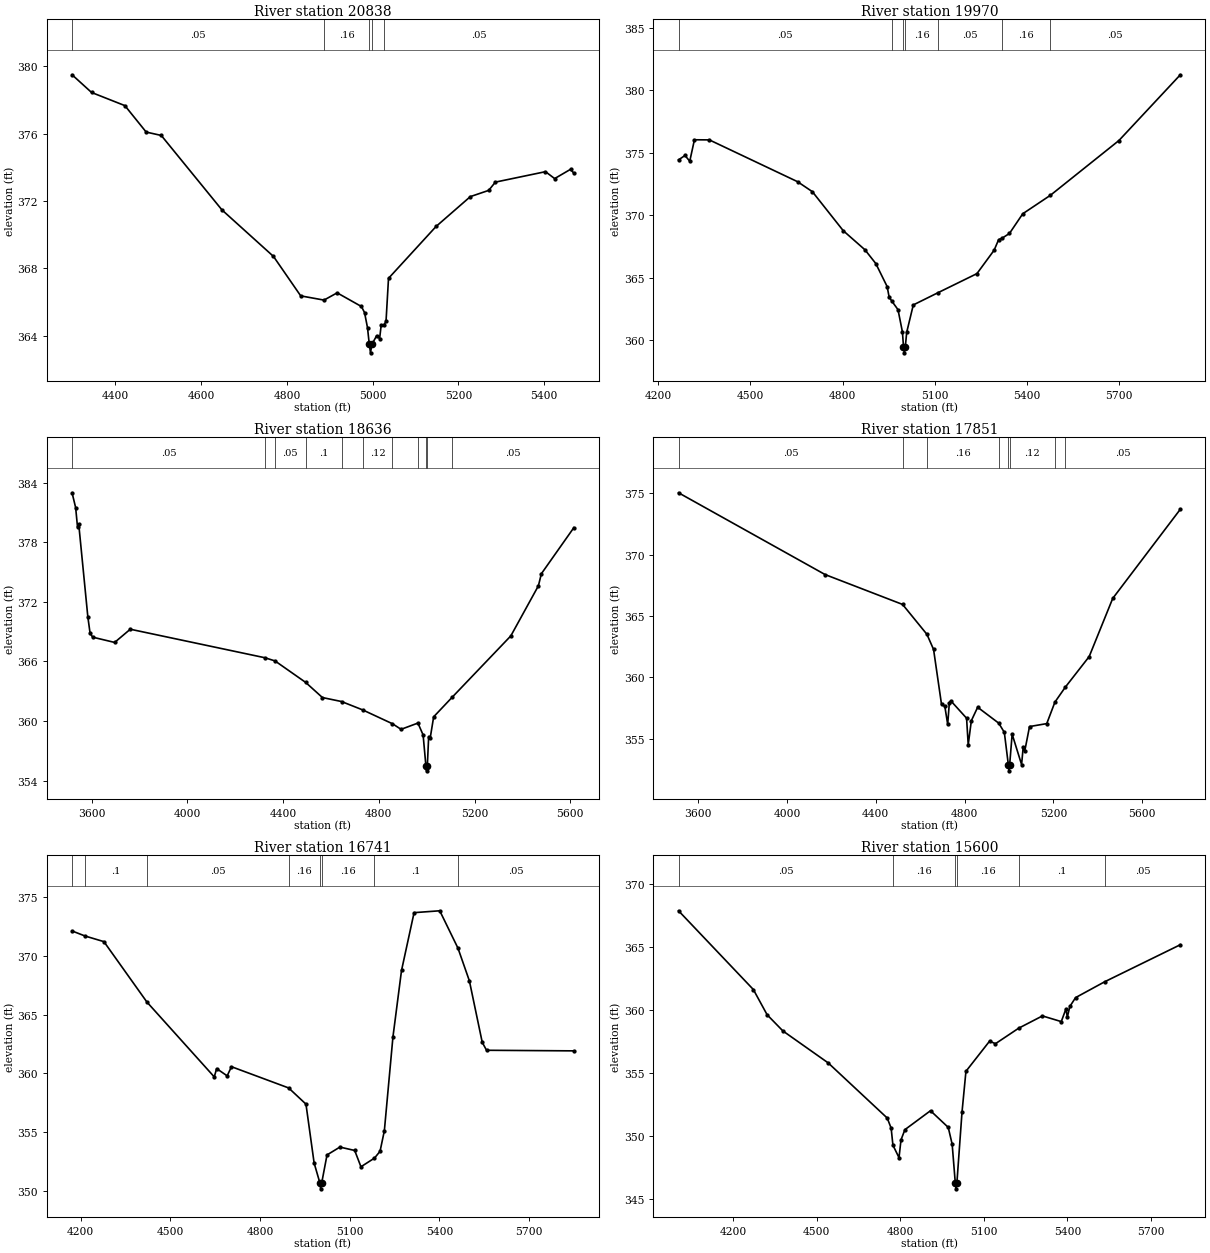
Type RM Length L Ch R = 1,20838,868,868,868
BEGIN DESCRIPTION:
TOWN BRANCH 34.0
END DESCRIPTION:
XS GIS Cut Line= 3
      3535389.42     10306718.59      3534892.11     10306191.64
      3534508.71     10305963.69
#Sta/Elev= 30
  4298.8  379.49  4344.3  378.44  4422.0  377.66  4471.7  376.09  4506.9  375.89
  4648.5  371.47  4768.7  368.71  4832.2  366.37  4886.5  366.12  4917.2  366.55
  4973.8  365.74  4981.1  365.38  4988.0  364.48  4992.2  363.49  4995.0  362.99
  4998.2  363.49  5009.4  364.01  5016.3  363.84  5019.9  364.63  5025.7  364.63
  5031.2  364.85  5037.0  367.41  5148.0  370.49  5227.9  372.26  5270.7  372.63
  5286.3  373.12  5403.2  373.74  5424.6  373.33  5461.6  373.88  5469.4  373.65
#Mann=5,-1,0
  4298.8    0.05       0  4886.5    0.16       0  4992.2    0.07       0
  4998.2    0.16       0  5025.7    0.05       0
Bank Sta=4992.2,4998.2
Exp/Cntr=0.3,0.1

Type RM Length L Ch R = 1,19970,1334,1334,1334
BEGIN DESCRIPTION:
TOWN BRANCH 33.0
END DESCRIPTION:
XS GIS Cut Line= 3
      3535754.32     10306706.02      3535578.17     10306215.32
      3534892.11     10305341.65
#Sta/Elev= 30
  4266.3  374.44  4287.3  374.79  4302.8  374.33  4318.0  376.05  4366.6  376.04
  4653.4  372.69  4701.6  371.89  4802.1  368.76  4872.7  367.23  4907.9  366.13
  4944.9  364.28  4951.3  363.44  4959.4  363.14  4980.2  362.43  4994.6  360.64
  4998.0  359.47  5000.8  358.97  5004.0  359.47  5008.5  360.62  5029.9  362.81
  5109.4  363.78  5236.9  365.32  5292.9  367.20  5307.4  368.04  5319.3  368.17
  5342.7  368.54  5386.0  370.12  5475.9  371.60  5698.8  375.99  5898.5  381.26
#Mann=7,-1,0
  4266.3    0.05       0  4959.4    0.16       0  4998.0    0.07       0
  5004.0    0.16       0  5109.4    0.05       0  5319.3    0.16       0
  5475.9    0.05       0
Bank Sta=4998,5004
Exp/Cntr=0.3,0.1

Type RM Length L Ch R = 1,18636,785,785,785
BEGIN DESCRIPTION:
TOWN BRANCH 31.0
END DESCRIPTION:
XS GIS Cut Line= 3
      3536131.80     10306756.39      3535943.05     10305749.77
      3535313.95     10304881.61
#Sta/Elev= 30
  3518.6  382.98  3533.6  381.48  3541.4  379.51  3546.5  379.81  3584.5  370.48
  3593.9  368.83  3604.8  368.44  3696.4  367.91  3761.8  369.24  4323.9  366.37
  4366.3  366.05  4494.2  363.89  4564.5  362.36  4644.2  361.96  4732.3  361.12
  4857.2  359.72  4893.1  359.16  4963.4  359.79  4985.1  358.60  4996.8  355.48
  4999.5  354.98  5002.8  355.48  5008.3  358.43  5014.5  358.25  5029.2  360.42
  5106.9  362.40  5351.6  368.57  5466.7  373.61  5479.2  374.83  5614.9  379.47
#Mann=11,-1,0
  3518.6    0.05       0  4323.9     0.1       0  4366.3    0.05       0
  4494.2     0.1       0  4644.2    0.16       0  4732.3    0.12       0
  4857.2    0.16       0  4963.4    0.12       0  4996.8    0.07       0
  5002.8    0.12       0  5106.9    0.05       0
Bank Sta=4996.8,5002.8
Exp/Cntr=0.3,0.1

Type RM Length L Ch R = 1,17851,1110,1110,1110
BEGIN DESCRIPTION:
TOWN BRANCH 30.0
END DESCRIPTION:
XS GIS Cut Line= 3
      3537226.45     10306139.83      3536345.69     10305334.56
      3535617.51     10304556.16
#Sta/Elev= 30
  3512.2  375.02  4172.1  368.37  4521.0  365.94  4630.6  363.51  4660.5  362.28
  4696.3  357.81  4711.0  357.67  4724.1  356.19  4731.5  357.95  4738.3  358.10
  4809.1  356.69  4816.5  354.53  4830.6  356.49  4859.0  357.58  4953.7  356.29
  4979.1  355.54  4997.1  352.91  4999.9  352.41  5003.1  352.91  5014.3  355.39
  5056.8  352.92  5064.1  354.35  5071.0  354.02  5092.5  356.01  5170.1  356.25
  5206.9  358.00  5253.5  359.21  5361.1  361.70  5467.1  366.43  5771.5  373.68
#Mann=8,-1,0
  3512.2    0.05       0  4521.0     0.1       0  4630.6    0.16       0
  4953.7    0.12       0  4997.1    0.07       0  5003.1    0.12       0
  5206.9    0.16       0  5253.5    0.05       0
Bank Sta=4997.1,5003.1
Exp/Cntr=0.3,0.1

Type RM Length L Ch R = 1,16741,1141,1141,1141
BEGIN DESCRIPTION:
TOWN BRANCH 28.0
END DESCRIPTION:
XS GIS Cut Line= 3
      3537339.68     10305233.90      3536177.22     10304288.68
      3536027.24     10304188.70
#Sta/Elev= 30
  4171.1  372.13  4214.5  371.70  4277.6  371.22  4421.5  366.07  4646.8  359.69
  4654.7  360.40  4689.9  359.78  4704.3  360.56  4895.5  358.75  4953.5  357.37
  4980.8  352.35  5000.1  350.65  5002.8  350.15  5006.1  350.65  5023.9  353.04
  5067.0  353.71  5116.5  353.42  5137.4  352.03  5182.7  352.77  5201.3  353.35
  5215.7  355.10  5244.4  363.09  5273.1  368.76  5315.1  373.69  5401.0  373.85
  5462.0  370.66  5500.1  367.88  5543.2  362.63  5557.6  361.96  5849.6  361.91
#Mann=8,-1,0
  4171.1    0.05       0  4214.5     0.1       0  4421.5    0.05       0
  4895.5    0.16       0  5000.1    0.07       0  5006.1    0.16       0
  5182.7     0.1       0  5462.0    0.05       0
Bank Sta=5000.1,5006.1
Exp/Cntr=0.3,0.1

Type RM Length L Ch R = 1,15600,678,678,678
BEGIN DESCRIPTION:
Mapping XS 57081c5f
END DESCRIPTION:
XS GIS Cut Line= 3
      3537546.70     10304767.24      3536650.89     10303876.64
      3536125.99     10303751.91
#Sta/Elev= 30
  4003.1  367.84  4271.9  361.60  4321.4  359.60  4378.0  358.32  4540.6  355.79
  4752.8  351.42  4766.9  350.62  4773.3  349.27  4795.2  348.28  4802.3  349.69
  4816.4  350.50  4908.3  352.00  4972.0  350.68  4986.1  349.35  4997.2  346.31
  5000.0  345.81  5003.2  346.31  5021.5  351.89  5035.6  355.12  5120.5  357.51
  5141.7  357.31  5225.3  358.54  5310.4  359.51  5378.1  359.06  5394.8  360.06
  5399.9  359.42  5408.9  360.26  5429.5  360.96  5534.4  362.22  5805.8  365.15
#Mann=6,-1,0
  4003.1    0.05       0  4773.3    0.16       0  4997.2    0.07       0
  5003.2    0.16       0  5225.3     0.1       0  5534.4    0.05       0
Bank Sta=4997.2,5003.2
Exp/Cntr=0.3,0.1

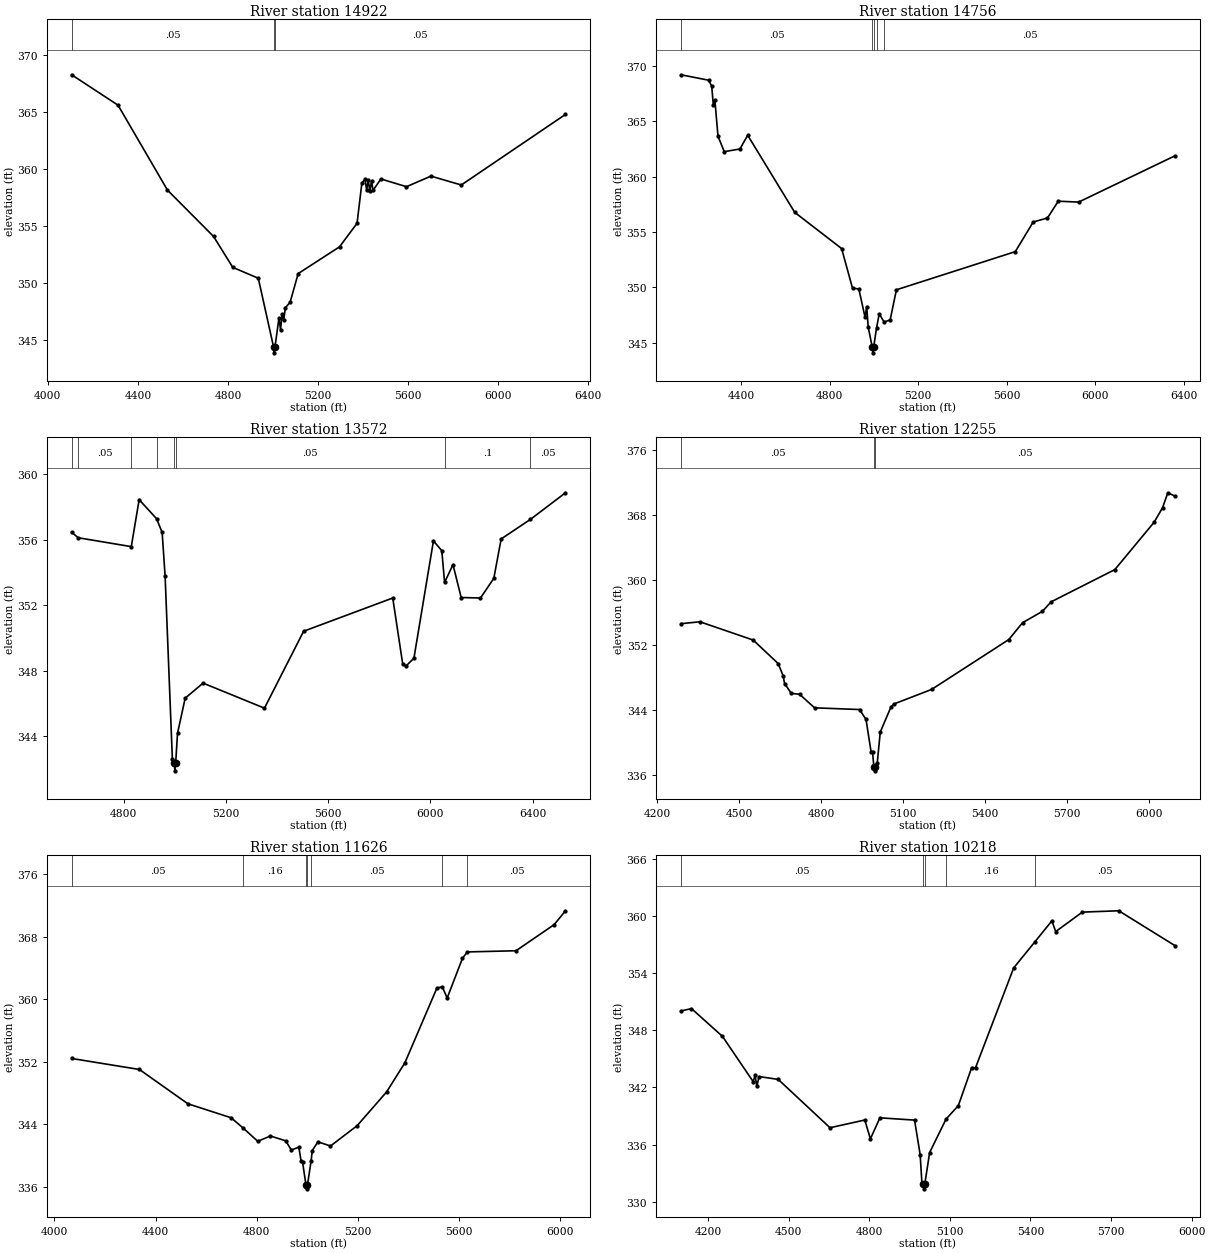
Type RM Length L Ch R = 1,14922,166,166,166
BEGIN DESCRIPTION:
TOWN BRANCH 26.0
END DESCRIPTION:
XS GIS Cut Line= 3
      3537838.38     10304426.11      3536674.33     10303368.83
      3536076.29     10303535.24
#Sta/Elev= 30
  4106.0  368.29  4311.9  365.62  4531.5  358.16  4736.3  354.09  4821.4  351.38
  4934.9  350.42  5002.9  344.37  5005.7  343.87  5008.9  344.37  5026.9  346.96
  5033.6  345.90  5041.0  347.24  5047.8  346.75  5055.2  347.83  5076.2  348.31
  5112.0  350.83  5295.8  353.18  5373.5  355.25  5395.1  358.80  5409.3  359.12
  5416.1  358.15  5423.5  359.02  5430.3  358.05  5437.7  358.95  5444.5  358.14
  5479.6  359.14  5593.1  358.46  5701.6  359.39  5836.5  358.61  6299.3  364.81
#Mann=3,-1,0
  4106.0    0.05       0  5002.9    0.04       0  5008.9    0.05       0
Bank Sta=5002.9,5008.9
Exp/Cntr=0.3,0.1

Type RM Length L Ch R = 1,14756,1184,1184,1184
BEGIN DESCRIPTION:
TOWN BRANCH 24.0
END DESCRIPTION:
XS GIS Cut Line= 3
      3537919.11     10304290.69      3536814.95     10303264.66
      3536106.91     10303422.00
#Sta/Elev= 30
  4128.3  369.22  4252.8  368.73  4267.0  368.19  4274.4  366.46  4281.2  366.96
  4295.3  363.67  4323.7  362.27  4394.5  362.51  4429.7  363.75  4642.3  356.78
  4854.3  353.51  4903.6  349.92  4932.0  349.86  4960.3  347.30  4967.7  348.26
  4974.5  346.40  4993.0  344.58  4995.8  344.08  4999.0  344.58  5012.3  346.34
  5024.4  347.61  5046.2  346.87  5073.7  347.05  5102.0  349.78  5639.6  353.23
  5720.5  355.91  5785.0  356.27  5833.7  357.79  5925.9  357.71  6360.9  361.89
#Mann=5,-1,0
  4128.3    0.05       0  4993.0    0.04       0  4999.0    0.05       0
  5012.3    0.16       0  5046.2    0.05       0
Bank Sta=4993,4999
Exp/Cntr=0.3,0.1

Type RM Length L Ch R = 1,13572,1317,1317,1317
BEGIN DESCRIPTION:
TOWN BRANCH 22.0
END DESCRIPTION:
XS GIS Cut Line= 3
      3537905.90     10302893.61      3537100.62     10302855.86
      3536068.84     10303308.84
#Sta/Elev= 30
  4595.7  356.45  4621.8  356.12  4829.1  355.58  4859.8  358.45  4927.8  357.29
  4949.9  356.45  4961.5  353.76  4989.9  342.60  4996.9  342.38  4999.7  341.88
  5002.9  342.38  5010.0  344.17  5040.0  346.32  5110.1  347.24  5350.3  345.71
  5503.7  350.41  5852.5  352.44  5891.7  348.39  5904.7  348.29  5935.4  348.76
  6011.8  355.93  6044.6  355.33  6055.4  353.39  6088.3  354.48  6120.4  352.47
  6195.9  352.44  6248.1  353.64  6276.9  356.05  6391.1  357.24  6528.7  358.87
#Mann=8,-1,0
  4595.7     0.1       0  4621.8    0.05       0  4829.1     0.1       0
  4927.8    0.05       0  4996.9   0.035       0  5002.9    0.05       0
  6055.4     0.1       0  6391.1    0.05       0
Bank Sta=4996.9,5002.9
Exp/Cntr=0.3,0.1

Type RM Length L Ch R = 1,12255,629,629,629
BEGIN DESCRIPTION:
TOWN BRANCH 21.0
END DESCRIPTION:
XS GIS Cut Line= 3
      3538044.32     10302390.33      3537392.11     10302141.64
      3536307.93     10301912.19
#Sta/Elev= 30
  4287.3  354.63  4356.5  354.86  4551.1  352.61  4642.8  349.70  4660.7  348.20
  4666.1  347.24  4690.8  346.03  4720.9  345.92  4775.7  344.25  4940.2  344.04
  4963.9  342.82  4982.6  338.78  4987.9  338.78  4992.5  336.98  4995.3  336.48
  4998.5  336.98  5005.1  337.50  5016.0  341.26  5054.8  344.33  5067.1  344.74
  5203.9  346.52  5486.2  352.67  5536.5  354.75  5608.8  356.14  5641.0  357.32
  5874.1  361.30  6017.7  367.14  6048.4  368.92  6067.8  370.77  6093.5  370.37
#Mann=3,-1,0
  4287.3    0.05       0  4992.5   0.035       0  4998.5    0.05       0
Bank Sta=4992.5,4998.5
Exp/Cntr=0.3,0.1

Type RM Length L Ch R = 1,11626,1408,1408,1408
BEGIN DESCRIPTION:
TOWN BRANCH 19.0
END DESCRIPTION:
XS GIS Cut Line= 3
      3538170.13     10302025.44      3537100.62     10301471.81
      3536358.22     10301371.15
#Sta/Elev= 30
  4068.3  352.43  4336.3  351.02  4527.9  346.63  4699.4  344.83  4746.5  343.52
  4804.5  341.82  4854.4  342.50  4915.1  341.88  4937.3  340.70  4966.9  341.07
  4975.9  339.29  4981.6  339.19  4995.1  336.23  4997.8  335.73  5001.1  336.23
  5015.6  339.33  5020.2  340.64  5042.3  341.75  5092.2  341.22  5197.3  343.81
  5313.8  348.13  5386.3  351.86  5513.3  361.46  5534.5  361.61  5553.7  360.17
  5614.2  365.26  5633.6  366.08  5826.1  366.23  5976.7  369.57  6021.8  371.35
#Mann=7,-1,0
  4068.3    0.05       0  4746.5    0.16       0  4995.1    0.07       0
  5001.1    0.16       0  5015.6    0.05       0  5534.5     0.1       0
  5633.6    0.05       0
Bank Sta=4995.1,5001.1
Exp/Cntr=0.3,0.1

Type RM Length L Ch R = 1,10218,1007,1007,1007
BEGIN DESCRIPTION:
TOWN BRANCH 18.0
END DESCRIPTION:
XS GIS Cut Line= 3
      3538509.80     10301748.60      3537968.79     10301358.57
      3537063.16     10300616.46
#Sta/Elev= 30
  4099.7  350.02  4138.6  350.27  4254.0  347.35  4368.1  342.61  4375.4  343.26
  4381.6  342.13  4390.2  343.14  4461.3  342.84  4654.0  337.77  4783.6  338.58
  4804.4  336.60  4839.9  338.81  4968.8  338.57  4989.6  334.95  4996.1  331.99
  5000.9  331.86  5003.7  331.36  5006.9  331.86  5024.8  335.16  5086.0  338.68
  5131.7  340.09  5181.2  344.07  5195.6  344.06  5337.7  354.54  5416.6  357.27
  5479.8  359.47  5494.1  358.35  5593.2  360.39  5728.8  360.53  5937.5  356.88
#Mann=5,-1,0
  4099.7    0.05       0  5000.9    0.03       0  5006.9    0.05       0
  5086.0    0.16       0  5416.6    0.05       0
Bank Sta=5000.9,5006.9
Exp/Cntr=0.3,0.1

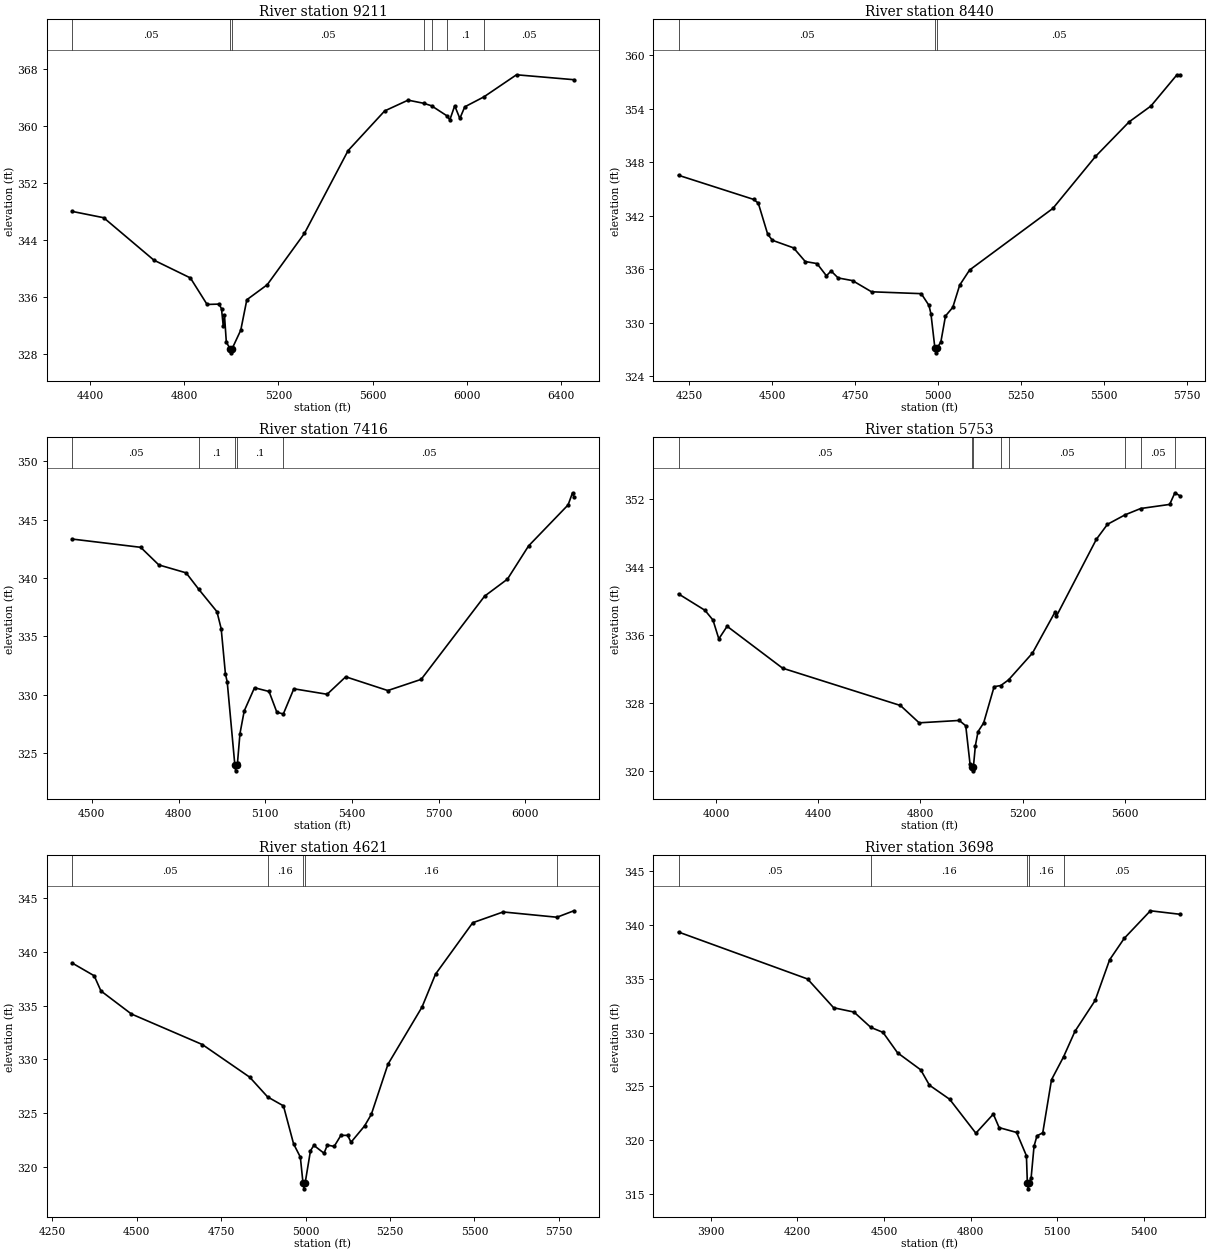
Type RM Length L Ch R = 1,9211,771,771,771
BEGIN DESCRIPTION:
TOWN BRANCH 16.0
END DESCRIPTION:
XS GIS Cut Line= 3
      3538748.90     10301673.18      3538509.83     10300528.15
      3537792.78     10299886.57
#Sta/Elev= 30
  4323.2  348.05  4457.6  347.16  4670.7  341.21  4825.9  338.71  4896.8  334.99
  4947.9  335.04  4958.1  334.38  4965.6  331.93  4970.8  333.44  4978.6  329.69
  4996.0  328.70  4998.8  328.20  5002.0  328.70  5039.9  331.38  5065.7  335.65
  5152.2  337.75  5310.6  344.97  5495.9  356.58  5651.4  362.15  5750.8  363.66
  5816.9  363.22  5850.3  362.87  5917.2  361.43  5928.0  360.88  5948.9  362.87
  5970.7  361.09  5991.6  362.72  6072.9  364.12  6211.4  367.22  6455.1  366.53
#Mann=7,-1,0
  4323.2    0.05       0  4996.0    0.03       0  5002.0    0.05       0
  5816.9     0.1       0  5850.3    0.05       0  5917.2     0.1       0
  6072.9    0.05       0
Bank Sta=4996,5002
Exp/Cntr=0.3,0.1

Type RM Length L Ch R = 1,8440,1024,1024,1024
BEGIN DESCRIPTION:
TOWN BRANCH 14.0
END DESCRIPTION:
XS GIS Cut Line= 3
      3539730.27     10301283.05      3539365.42     10300918.20
      3538799.22     10300100.34
#Sta/Elev= 30
  4218.2  346.54  4444.2  343.84  4458.3  343.42  4486.6  339.94  4500.7  339.26
  4564.4  338.41  4599.7  336.88  4635.1  336.65  4663.4  335.28  4677.5  335.82
  4698.7  335.04  4742.1  334.74  4799.2  333.49  4948.9  333.28  4972.2  331.96
  4978.2  331.00  4990.1  327.15  4992.9  326.65  4996.1  327.15  5008.0  327.88
  5021.9  330.78  5043.8  331.74  5064.7  334.24  5094.5  335.93  5345.2  342.83
  5473.5  348.65  5574.9  352.53  5640.4  354.30  5718.1  357.77  5728.9  357.80
#Mann=3,-1,0
  4218.2    0.05       0  4990.1    0.03       0  4996.1    0.05       0
Bank Sta=4990.1,4996.1
Exp/Cntr=0.3,0.1

Type RM Length L Ch R = 1,7416,1663,1663,1663
BEGIN DESCRIPTION:
TOWN BRANCH 13.0
END DESCRIPTION:
XS GIS Cut Line= 3
      3540485.26     10300628.82      3539842.76     10300164.50
      3539042.77     10299664.51
#Sta/Elev= 30
  4431.6  343.34  4669.0  342.63  4731.7  341.12  4826.1  340.44  4870.2  339.02
  4932.8  337.11  4947.5  335.65  4962.2  331.76  4968.4  331.08  4994.8  323.95
  4997.5  323.45  5000.8  323.95  5004.0  324.16  5012.5  326.65  5027.2  328.59
  5062.8  330.58  5113.1  330.26  5140.1  328.48  5162.5  328.33  5198.9  330.49
  5314.1  330.02  5378.4  331.52  5524.0  330.34  5639.5  331.30  5858.9  338.44
  5937.9  339.90  6011.0  342.75  6147.8  346.27  6163.1  347.31  6167.7  346.97
#Mann=5,-1,0
  4431.6    0.05       0  4870.2     0.1       0  4994.8    0.07       0
  5000.8     0.1       0  5162.5    0.05       0
Bank Sta=4994.8,5000.8
Exp/Cntr=0.3,0.1

Type RM Length L Ch R = 1,5753,1132,1132,1132
BEGIN DESCRIPTION:
TOWN BRANCH 12.0
END DESCRIPTION:
XS GIS Cut Line= 3
      3540573.31     10300490.39      3540170.69     10299207.01
      3539868.88     10298666.28
#Sta/Elev= 30
  3852.9  340.84  3956.4  338.91  3987.8  337.76  4010.6  335.55  4043.1  337.03
  4260.3  332.10  4721.5  327.71  4794.8  325.67  4952.0  325.95  4977.2  325.32
  4994.0  320.82  5001.3  320.52  5004.1  320.02  5007.3  320.52  5014.9  322.98
  5025.4  324.64  5047.2  325.65  5088.3  329.92  5114.5  330.06  5144.7  330.72
  5238.5  333.88  5326.4  338.69  5332.1  338.22  5488.6  347.27  5532.0  349.03
  5601.3  350.15  5662.2  350.89  5775.4  351.37  5796.0  352.74  5817.2  352.35
#Mann=8,-1,0
  3852.9    0.05       0  5001.3   0.035       0  5007.3    0.05       0
  5114.5    0.16       0  5144.7    0.05       0  5601.3     0.1       0
  5662.2    0.05       0  5796.0     0.1       0
Bank Sta=5001.3,5007.3
Exp/Cntr=0.3,0.1

Type RM Length L Ch R = 1,4621,923,923,923
BEGIN DESCRIPTION:
TOWN BRANCH 10.0
END DESCRIPTION:
XS GIS Cut Line= 3
      3541013.69     10300377.13      3540975.95     10299408.33
      3540950.79     10298892.47
#Sta/Elev= 30
  4308.5  338.97  4374.0  337.78  4394.0  336.37  4484.1  334.23  4694.3  331.39
  4834.4  328.36  4887.7  326.52  4934.5  325.69  4964.5  322.16  4984.5  320.93
  4992.5  318.48  4995.2  317.98  4998.5  318.48  5014.5  321.52  5024.5  322.02
  5054.6  321.29  5064.6  322.05  5084.6  321.92  5104.6  322.95  5124.6  322.95
  5134.6  322.31  5174.6  323.82  5194.7  324.90  5244.0  329.56  5344.8  334.87
  5384.8  337.93  5495.0  342.71  5585.1  343.71  5744.4  343.22  5794.5  343.82
#Mann=5,-1,0
  4308.5    0.05       0  4887.7    0.16       0  4992.5    0.07       0
  4998.5    0.16       0  5744.4    0.05       0
Bank Sta=4992.5,4998.5
Exp/Cntr=0.3,0.1

Type RM Length L Ch R = 1,3698,903,903,903
BEGIN DESCRIPTION:
TOWN BRANCH 7.0
END DESCRIPTION:
XS GIS Cut Line= 3
      3541783.39     10300586.18      3541679.22     10299570.51
      3541592.41     10298858.68
#Sta/Elev= 30
  3788.4  339.36  4235.3  334.99  4325.7  332.31  4396.1  331.91  4454.5  330.48
  4496.6  330.02  4546.9  328.12  4627.3  326.53  4657.5  325.10  4727.5  323.79
  4818.3  320.63  4878.8  322.41  4898.9  321.15  4959.4  320.70  4993.4  318.53
  4996.7  315.95  4999.4  315.45  5002.7  315.95  5009.7  316.47  5019.8  319.42
  5029.9  320.38  5050.0  320.67  5080.3  325.61  5122.0  327.74  5161.6  330.12
  5231.4  332.99  5281.7  336.78  5332.1  338.77  5422.8  341.34  5526.5  341.01
#Mann=5,-1,0
  3788.4    0.05       0  4454.5    0.16       0  4996.7    0.07       0
  5002.7    0.16       0  5122.0    0.05       0
Bank Sta=4996.7,5002.7
Exp/Cntr=0.3,0.1

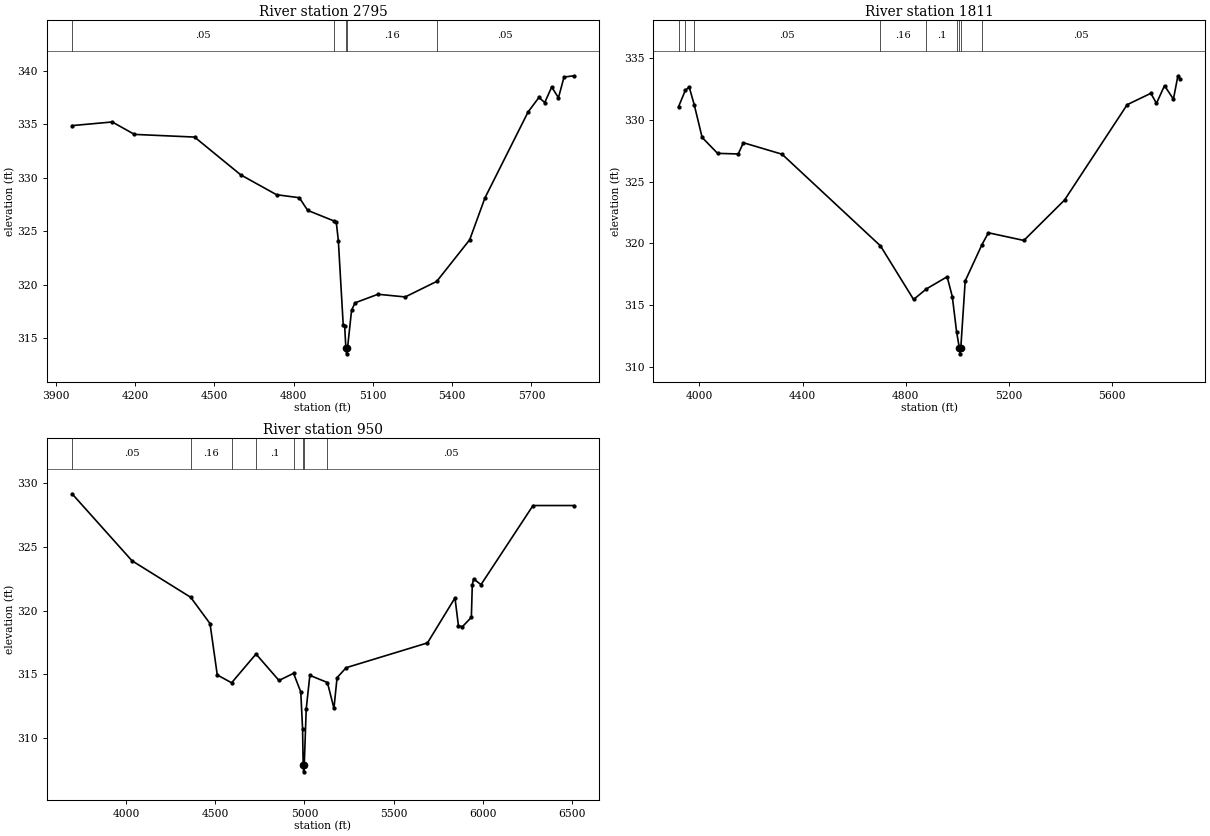
Type RM Length L Ch R = 1,2795,984,984,984
BEGIN DESCRIPTION:
TOWN BRANCH 5.0
END DESCRIPTION:
XS GIS Cut Line= 3
      3542687.60     10300360.09      3542587.59     10299910.05
      3542130.67     10298546.38
#Sta/Elev= 30
  3961.2  334.86  4113.3  335.20  4197.2  334.04  4424.8  333.79  4599.8  330.26
  4735.1  328.41  4821.3  328.13  4852.9  326.95  4953.5  325.95  4961.3  325.83
  4969.0  324.12  4987.5  316.24  4992.8  316.19  4997.6  314.06  5000.3  313.56
  5003.6  314.06  5019.1  317.63  5032.2  318.32  5119.0  319.12  5222.1  318.87
  5341.4  320.32  5466.2  324.21  5524.0  328.12  5687.1  336.13  5728.3  337.49
  5750.2  337.01  5776.5  338.46  5802.1  337.46  5823.2  339.39  5860.4  339.51
#Mann=5,-1,0
  3961.2    0.05       0  4953.5    0.16       0  4997.6    0.07       0
  5003.6    0.16       0  5341.4    0.05       0
Bank Sta=4997.6,5003.6
Exp/Cntr=0.3,0.1

Type RM Length L Ch R = 1,1811,861,861,861
BEGIN DESCRIPTION:
TOWN BRANCH 3.0
END DESCRIPTION:
XS GIS Cut Line= 3
      3542963.94     10299883.06      3542911.86     10298554.88
      3542347.66     10298303.16
#Sta/Elev= 30
  3918.9  331.05  3945.2  332.38  3960.3  332.65  3980.0  331.20  4010.4  328.57
  4070.4  327.28  4150.5  327.23  4170.5  328.14  4320.6  327.21  4702.4  319.79
  4831.0  315.45  4880.1  316.30  4961.1  317.29  4981.1  315.69  4997.8  312.84
  5008.2  311.55  5010.9  311.05  5014.2  311.55  5031.2  316.95  5096.2  319.89
  5121.2  320.85  5258.8  320.23  5416.6  323.50  5659.7  331.22  5751.5  332.14
  5773.4  331.33  5804.5  332.76  5839.1  331.67  5856.5  333.56  5865.9  333.26
#Mann=9,-1,0
  3918.9    0.05       0  3945.2    0.07       0  3980.0    0.05       0
  4702.4    0.16       0  4880.1     0.1       0  4997.8    0.16       0
  5008.2    0.07       0  5014.2    0.16       0  5096.2    0.05       0
Bank Sta=5008.2,5014.2
Exp/Cntr=0.3,0.1

Type RM Length L Ch R = 1,950,0,0,0
BEGIN DESCRIPTION:
TOWN BRANCH 1.0
END DESCRIPTION:
XS GIS Cut Line= 3
      3543842.11     10300041.67      3543554.22     10298476.76
      3542382.31     10298138.21
#Sta/Elev= 30
  3698.0  329.14  4033.6  323.90  4362.5  321.04  4470.8  318.98  4511.4  314.96
  4591.8  314.35  4728.4  316.60  4857.2  314.53  4938.8  315.09  4979.2  313.63
  4989.3  310.74  4992.6  307.88  4995.4  307.38  4998.6  307.88  5009.7  312.30
  5030.0  314.93  5128.5  314.37  5165.0  312.35  5182.5  314.75  5233.4  315.53
  5689.0  317.47  5843.0  320.99  5862.4  318.81  5884.7  318.74  5934.8  319.47
  5940.0  321.99  5947.1  322.48  5988.8  322.03  6280.2  328.22  6509.0  328.22
#Mann=8,-1,0
  3698.0    0.05       0  4362.5    0.16       0  4591.8    0.05       0
  4728.4     0.1       0  4938.8    0.16       0  4992.6    0.07       0
  4998.6    0.16       0  5128.5    0.05       0
Bank Sta=4992.6,4998.6
Exp/Cntr=0.3,0.1

Chan Stop Cuts=-1