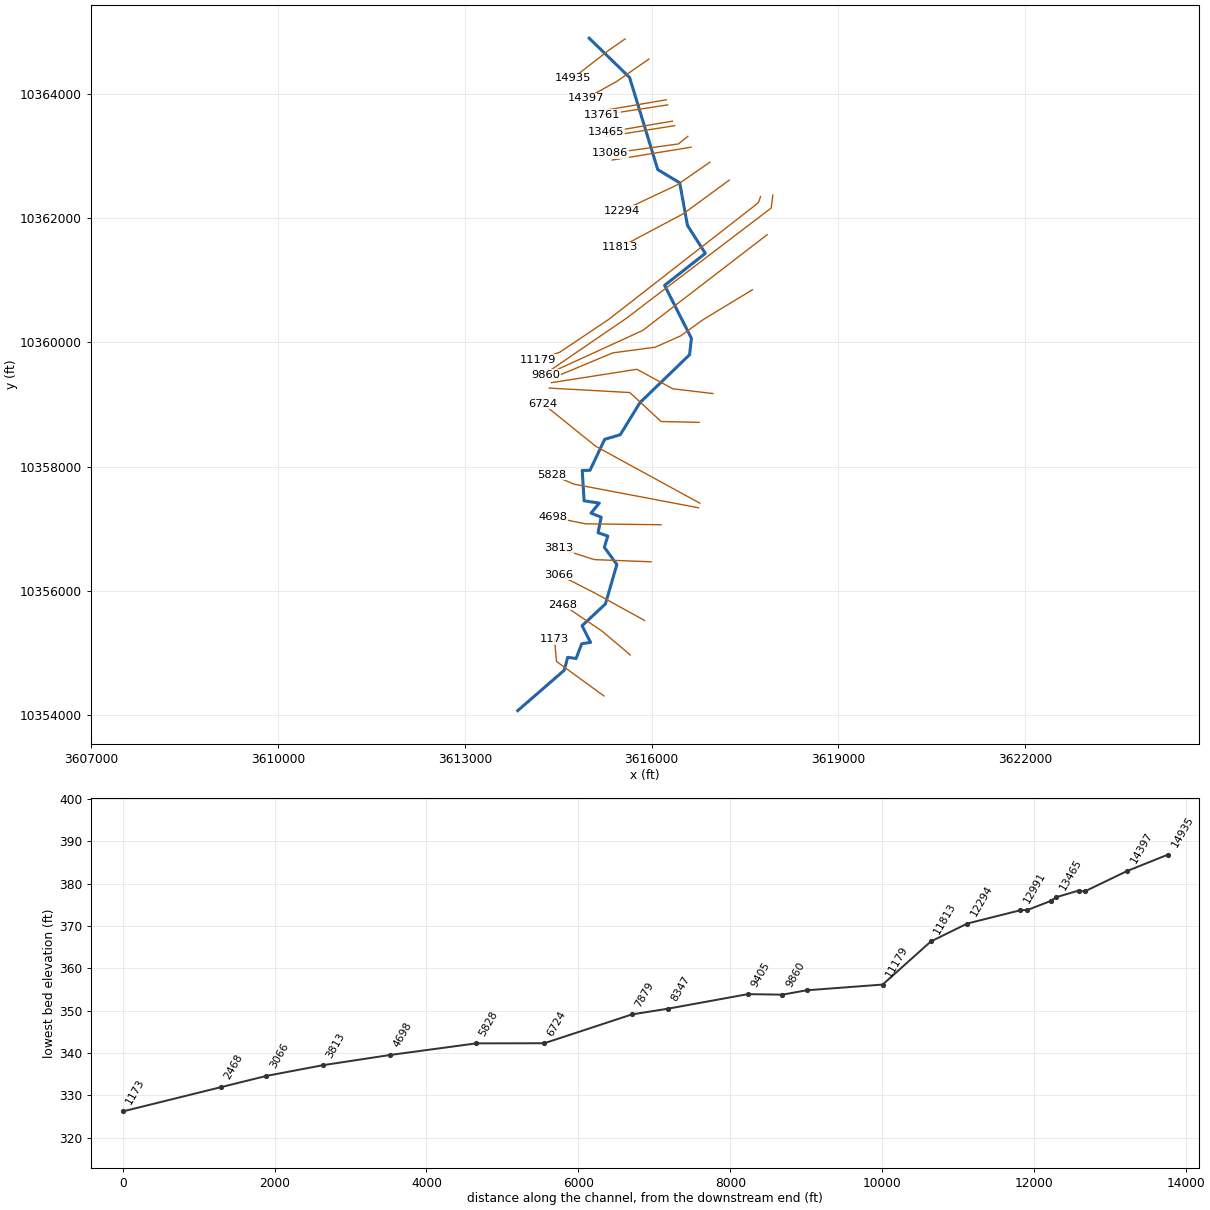
--- UNNAMED TRIB TO WEST CANEY CREEK.prj (project) ---

Proj Title=UNNAMED TRIB TO WEST CANEY CREEK Base Level Engineering
Current Plan=p01
Default Exp/Contr=0.3,0.1
English Units
Geom File=g01
Flow File=f01
Plan File=p01
Y Axis Title=Elevation
X Axis Title(PF)=Main Channel Distance
X Axis Title(XS)=Station
BEGIN DESCRIPTION:
UNNAMED TRIB TO WEST CANEY CREEK
END DESCRIPTION:
DSS Export Rating Curves= 0
DSS Export Rating Curve Sorted= 0
DSS Export Volume Flow Curves= 0
DXF OffsetX= 0
DXF OffsetY= 0
DXF ScaleX= 1
DXF ScaleY= 10

--- UNNAMED TRIB TO WEST CANEY CREEK.p01 (plan) ---

Plan Title=Multiple Run
Short Identifier=Multiple
Geom File=g01
Flow File=f01
Subcritical Flow
K Sum by GR= 0
Std Step Tol= 0.01
Critical Tol= 0.01
Num of Std Step Trials= 20
Max Error Tol= 0.3
Flow Tol Ratio= 0.001
Split Flow NTrial= 30
Split Flow Tol= 0.02
Split Flow Ratio= 0.02
Log Output Level= 0
Friction Slope Method= 1
Unsteady Friction Slope Method= 2
Unsteady Bridges Friction Slope Method= 1
Parabolic Critical Depth
Global Vel Dist=  1 , 1 , 1
Global Log Level= 0
CheckData=True
Encroach Param= -1, 0, 0, 0
BEGIN DESCRIPTION:
Multiple Run
END DESCRIPTION:

--- UNNAMED TRIB TO WEST CANEY CREEK.f01 (steady flow) ---

Flow Title=Multiple
Program Version=4.10
Number of Profiles= 7
Profile Names=10-year,25-year,50-year,1pct_min,100-year,1pct_plu,500-year
River Rch & RM=UNNAMED TRIB TO,Reach-1         ,14935
     834    1126    1362    1204    1628    2202    2316
River Rch & RM=UNNAMED TRIB TO,Reach-1         ,11179
    1411    1957    2411    2164    2926    3957    4299
River Rch & RM=UNNAMED TRIB TO,Reach-1         ,6724
    1411    1957    2411    2164    2926    3957    4299
Boundary for River Rch & Prof#=UNNAMED TRIB TO,Reach-1         , 1
Up Type= 0
Dn Type= 3
Dn Slope=0.005
Boundary for River Rch & Prof#=UNNAMED TRIB TO,Reach-1         , 2
Up Type= 0
Dn Type= 3
Dn Slope=0.005
Boundary for River Rch & Prof#=UNNAMED TRIB TO,Reach-1         , 3
Up Type= 0
Dn Type= 3
Dn Slope=0.005
Boundary for River Rch & Prof#=UNNAMED TRIB TO,Reach-1         , 4
Up Type= 0
Dn Type= 3
Dn Slope=0.005
Boundary for River Rch & Prof#=UNNAMED TRIB TO,Reach-1         , 5
Up Type= 0
Dn Type= 3
Dn Slope=0.005
Boundary for River Rch & Prof#=UNNAMED TRIB TO,Reach-1         , 6
Up Type= 0
Dn Type= 3
Dn Slope=0.005
Boundary for River Rch & Prof#=UNNAMED TRIB TO,Reach-1         , 7
Up Type= 0
Dn Type= 3
Dn Slope=0.005
DSS Import GetInterval= 0
DSS Import GetPeak= 0
DSS Import FillOption= 0

--- UNNAMED TRIB TO WEST CANEY CREEK.g01 (geometry) ---

Geom Title=Existing Conditions
Program Version=4.10

River Reach=UNNAMED TRIB TO ,Reach-1
Reach XY= 30
      3614997.11     10364896.64      3615645.55     10364264.61
      3616098.04     10362782.17      3616451.26     10362569.18
      3616575.71     10361883.14       3616862.3     10361433.61
      3616207.97     10360918.63      3616639.24     10360066.78
      3616609.58      10359802.7      3615812.53     10359031.61
       3615495.8     10358515.09      3615244.86     10358440.79
      3615009.97     10357942.87      3614884.57     10357940.72
      3614915.03     10357451.67      3615159.13     10357414.86
      3615025.79      10357253.4      3615188.99     10357188.12
      3615139.26     10356938.38      3615296.74      10356883.9
      3615239.28     10356704.37      3615441.27     10356426.39
      3615257.54      10355792.2       3614882.1     10355441.07
      3615018.86       10355173.      3614877.33     10355152.01
      3614786.18     10354913.73      3614651.63     10354932.83
       3614594.7     10354723.71      3613848.95     10354075.15

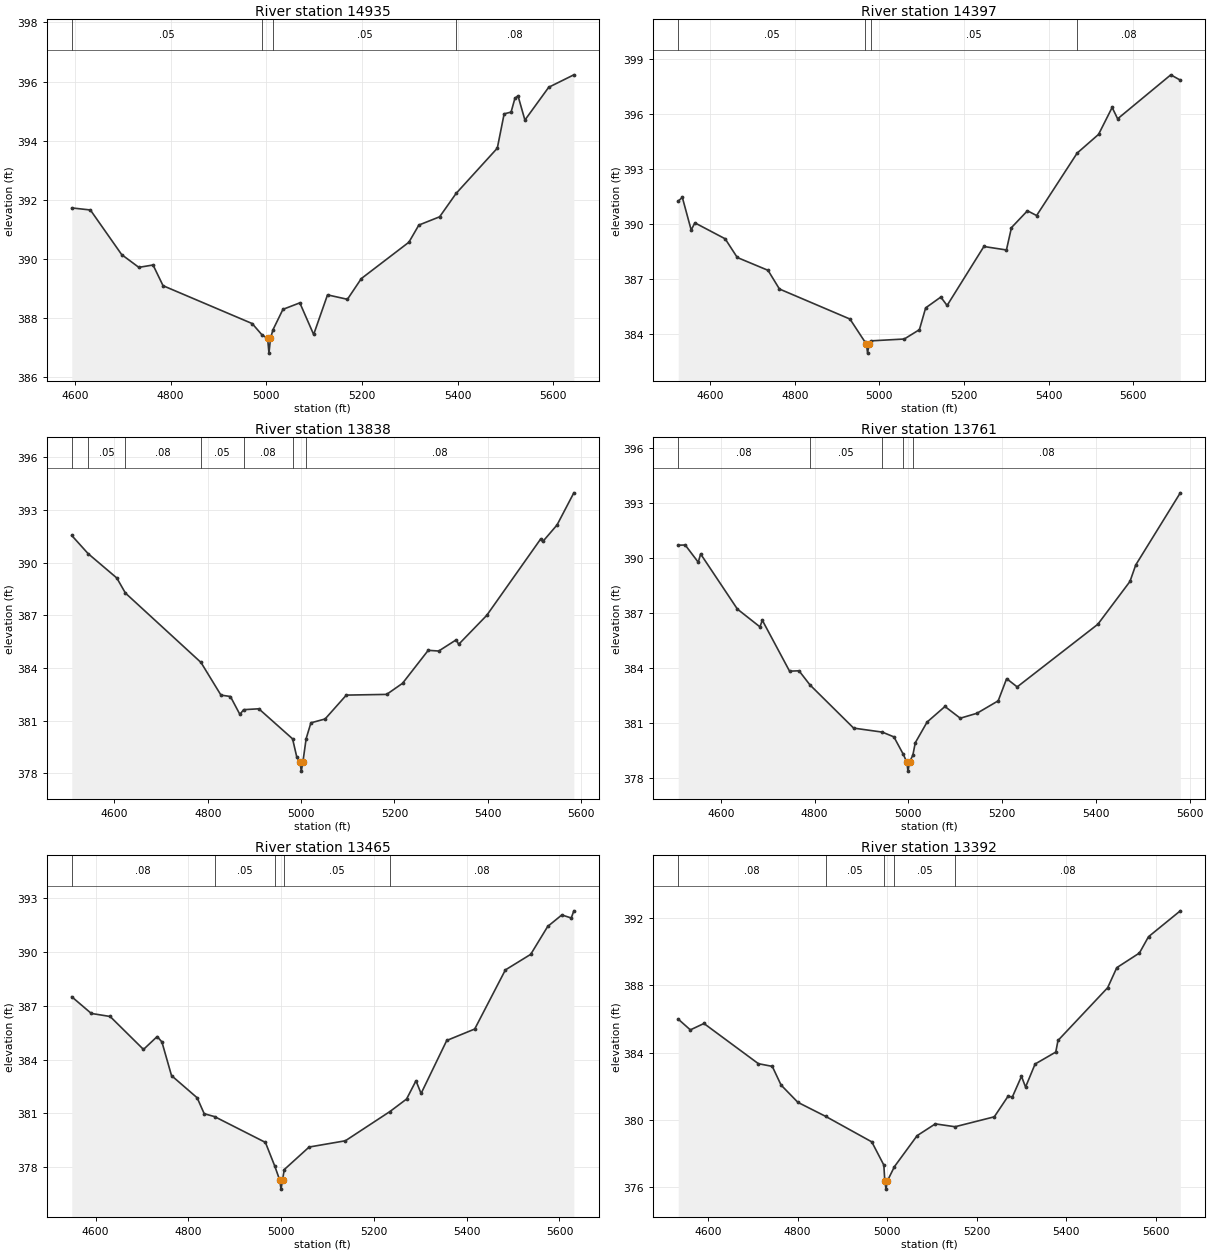
Type RM Length L Ch R = 1 ,14935   ,538,538,538
BEGIN DESCRIPTION:
UNNAMED TRIB TO WEST CANEY CREEK 9.0
END DESCRIPTION:
XS GIS Cut Line= 3
        3615574.     10364885.36      3615323.97     10364711.73
      3614735.81      10364254.3
#Sta/Elev= 30
  4593.4  391.73  4632.3  391.66  4697.8  390.15  4733.6  389.72  4763.3   389.8
  4784.2   389.1  4970.5  387.82  4991.4  387.43  5002.8  387.32  5005.6  386.82
  5008.8  387.32    5014  387.61  5034.8   388.3  5070.1  388.52    5099  387.45
    5128  388.79  5169.6  388.64  5198.6  389.34  5298.1  390.57  5318.9  391.15
  5362.4  391.43  5396.8  392.22  5482.9  393.75  5497.2  394.91  5511.7  394.97
  5519.8  395.44  5526.2  395.52  5540.6   394.7  5590.4  395.81  5642.9  396.23
#Mann= 4 ,-1 , 0
  4593.4     .05       0  4991.4     .04       0    5014     .05       0
  5396.8     .08       0
Bank Sta=5002.8,5008.8
XS Rating Curve= 0 ,0
Exp/Cntr=0.3,0.1

Type RM Length L Ch R = 1 ,14397   ,559,559,559
BEGIN DESCRIPTION:
UNNAMED TRIB TO WEST CANEY CREEK 8.8
END DESCRIPTION:
XS GIS Cut Line= 3
      3615956.78     10364560.98      3615429.87     10364195.24
      3614952.46      10363930.5
#Sta/Elev= 30
  4524.3  391.25    4534  391.45  4554.9  389.67  4563.7  390.06  4635.3  389.19
  4663.9  388.17  4736.6  387.47  4763.6  386.45  4930.4  384.81  4966.2  383.55
  4969.3  383.45  4972.1  382.95  4975.3  383.45  4980.4  383.62  5058.8  383.72
  5094.6  384.23  5109.4  385.42  5145.2  386.01  5160.1  385.55  5247.1  388.77
  5300.4  388.58  5312.3   389.8  5350.1  390.72  5371.8  390.46  5467.7  393.87
  5518.3  394.89  5550.4  396.36  5563.4  395.74  5689.1  398.14  5711.6  397.85
#Mann= 4 ,-1 , 0
  4524.3     .05       0  4966.2     .04       0  4980.4     .05       0
  5467.7     .08       0
Bank Sta=4969.3,4975.3
XS Rating Curve= 0 ,0
Exp/Cntr=0.3,0.1

Type RM Length L Ch R = 1 ,13838   ,77,77,77
BEGIN DESCRIPTION:
UNNAMED TRIB TO WEST CANEY CREEK 8.9
END DESCRIPTION:
XS GIS Cut Line= 2
      3616237.27     10363905.55      3615176.59     10363724.65
#Sta/Elev= 30
  4508.6  391.54  4543.5  390.51  4605.1  389.12  4623.6  388.26  4785.5  384.31
  4828.3  382.45  4848.6  382.37  4868.9  381.35  4876.9  381.62  4909.5  381.67
  4981.8  379.96  4990.6  378.95  4997.8  378.62  5000.5  378.12  5003.8  378.62
  5010.9  379.97  5021.1  380.87  5051.5  381.09    5097  382.45  5183.4  382.49
  5217.4  383.12  5272.5     385    5295  384.96  5332.6   385.6  5337.7  385.34
  5397.9  386.99  5513.2  391.33  5518.2   391.2  5548.6  392.14  5584.6  393.97
#Mann= 7 ,-1 , 0
  4508.6     .08       0  4543.5     .05       0  4623.6     .08       0
  4785.5     .05       0  4876.9     .08       0  4981.8     .07       0
  5010.9     .08       0
Bank Sta=4997.8,5003.8
XS Rating Curve= 0 ,0
Exp/Cntr=0.3,0.1

Type RM Length L Ch R = 1 ,13761   ,296,296,296
BEGIN DESCRIPTION:
Mapping XS 2561ad2c
END DESCRIPTION:
XS GIS Cut Line= 2
      3616256.82     10363823.52      3615198.16     10363660.75
#Sta/Elev= 30
  4509.1  390.69    4524   390.7  4551.8  389.76  4556.9  390.21  4635.3   387.2
  4683.4  386.23  4688.5  386.59  4746.6  383.81  4766.8  383.83  4790.1  383.06
  4883.3   380.7  4944.6  380.48  4969.2  380.22  4989.4  379.26  4996.5  378.85
  4999.3  378.35  5002.5  378.85  5009.6  379.22  5014.8   379.9    5040  381.03
  5078.1  381.88  5110.8  381.24  5146.4  381.51  5191.7  382.19  5209.7   383.4
  5232.2  382.95  5404.2  386.37  5472.8  388.71  5485.1  389.61  5580.2  393.55
#Mann= 5 ,-1 , 0
  4509.1     .08       0  4790.1     .05       0  4944.6     .08       0
  4989.4     .07       0  5009.6     .08       0
Bank Sta=4996.5,5002.5
XS Rating Curve= 0 ,0
Exp/Cntr=0.3,0.1

Type RM Length L Ch R = 1 ,13465   ,73,73,73
BEGIN DESCRIPTION:
Mapping XS 1a7f83c9
END DESCRIPTION:
XS GIS Cut Line= 2
      3616333.63      10363561.8      3615266.55     10363380.92
#Sta/Elev= 30
  4548.7  387.51  4590.8  386.58  4631.4  386.41  4703.3  384.57  4732.8  385.29
    4743  384.99  4763.7  383.11    4819  381.87  4834.2  380.98  4856.5  380.82
  4966.1  379.38  4986.4  378.05    4997  377.27  4999.8  376.77    5003  377.27
  5006.7  377.86  5060.3  379.12  5138.5  379.47  5234.4   381.1  5270.4   381.8
  5290.7  382.82  5301.7  382.11    5357  385.07  5417.3  385.71  5483.4  389.01
    5538  389.88  5574.7  391.44  5605.1  392.08  5625.4  391.91    5631  392.31
#Mann= 5 ,-1 , 0
  4548.7     .08       0  4856.5     .05       0  4986.4     .04       0
  5006.7     .05       0  5234.4     .08       0
Bank Sta=4997,5003
XS Rating Curve= 0 ,0
Exp/Cntr=0.3,0.1

Type RM Length L Ch R = 1 ,13392   ,306,306,306
BEGIN DESCRIPTION:
Mapping XS 274dc394
END DESCRIPTION:
XS GIS Cut Line= 2
      3616368.75     10363488.88      3615262.03     10363313.11
#Sta/Elev= 30
  4533.7     386  4560.7  385.36  4591.1  385.74  4712.6  383.35  4743.6  383.19
  4763.2  382.08  4800.8  381.05  4862.5  380.22  4965.7   378.7  4992.6  377.32
  4994.7  376.39  4997.4  375.89  5000.7  376.39  5016.3  377.23  5066.9  379.07
  5107.5  379.77  5151.6   379.6  5239.1  380.19  5269.5   381.4  5279.6  381.38
  5299.8   382.6  5308.9  381.96  5330.2  383.33  5376.3  384.04  5381.3  384.73
  5492.2  387.87  5512.5  389.06    5563  389.93  5583.3   390.9  5654.3  392.44
#Mann= 5 ,-1 , 0
  4533.7     .08       0  4862.5     .05       0  4992.6     .04       0
  5016.3     .05       0  5151.6     .08       0
Bank Sta=4994.7,5000.7
XS Rating Curve= 0 ,0
Exp/Cntr=0.3,0.1

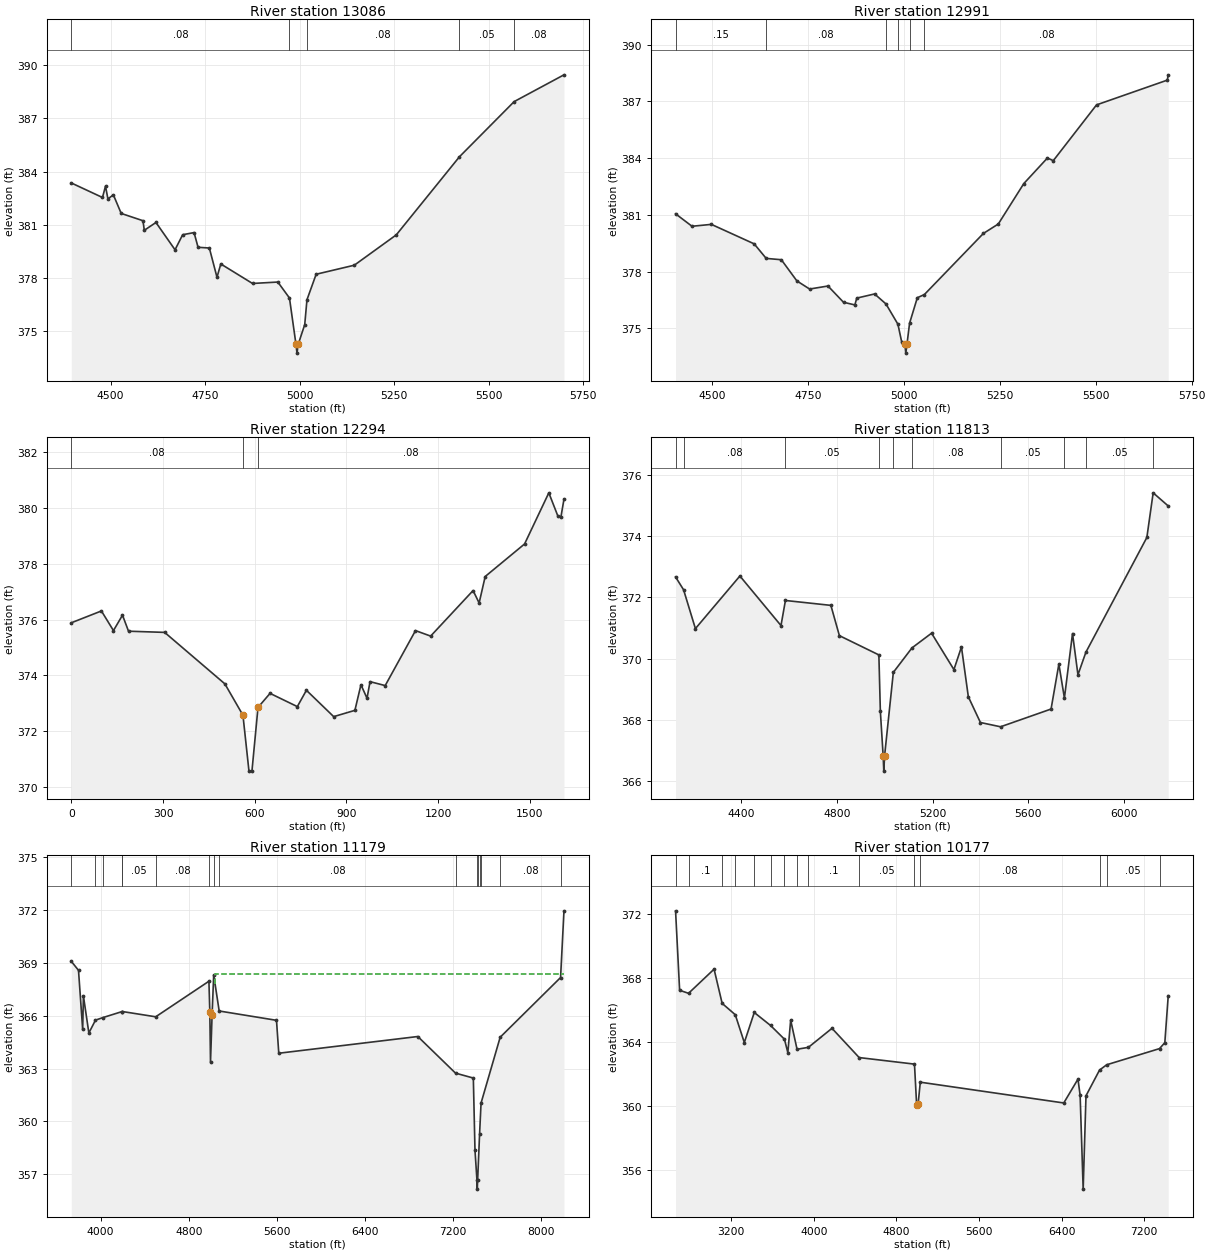
Type RM Length L Ch R = 1 ,13086   ,95,95,95
BEGIN DESCRIPTION:
UNNAMED TRIB TO WEST CANEY CREEK 8.7
END DESCRIPTION:
XS GIS Cut Line= 3
      3616582.47     10363317.58      3616431.46     10363195.21
      3615332.46     10363044.16
#Sta/Elev= 30
    4396  383.36  4478.5  382.54  4486.5  383.18  4492.9  382.46  4507.3  382.69
  4528.1  381.64  4585.6  381.23  4589.2  380.69    4620  381.13  4670.5  379.59
  4690.7  380.44  4720.9  380.56  4731.4  379.73  4761.3  379.69  4781.5  378.04
  4791.6  378.79  4875.5  377.69  4942.5  377.77  4973.3  376.87  4990.5  374.26
  4993.2  373.76  4996.5  374.26  5013.7  375.37  5019.6  376.77  5043.9  378.21
  5144.9  378.72  5255.9  380.43  5423.2  384.84  5567.9  387.95  5699.7  389.46
#Mann= 5 ,-1 , 0
    4396     .08       0  4973.3     .07       0  5019.6     .08       0
  5423.2     .05       0  5567.9     .08       0
Bank Sta=4990.5,4996.5
XS Rating Curve= 0 ,0
Exp/Cntr=0.3,0.1

Type RM Length L Ch R = 1 ,12991   ,697,697,697
BEGIN DESCRIPTION:
UNNAMED TRIB TO WEST CANEY CREEK 8.71
END DESCRIPTION:
XS GIS Cut Line= 2
      3616634.44     10363142.45      3615366.23       10362936.
#Sta/Elev= 30
    4404  381.06  4446.9   380.4  4497.4   380.5    4609  379.47  4640.4   378.7
  4679.9  378.63  4720.4  377.51  4753.6  377.08  4801.5  377.24    4842  376.38
  4871.6  376.24  4876.6   376.6  4923.1  376.82  4952.8  376.29  4983.9  375.22
    4994  374.26  5001.7  374.19  5004.5  373.69  5007.7  374.19  5014.3  375.27
  5034.5  376.62    5053  376.79  5206.8  380.02  5245.7  380.52  5312.3  382.66
  5373.8  384.01  5389.1  383.87  5501.9  386.82  5686.5  388.13  5688.9  388.41
#Mann= 6 ,-1 , 0
    4404     .15       0  4640.4     .08       0  4952.8     .05       0
  4983.9     .04       0  5014.3     .05       0    5053     .08       0
Bank Sta=5001.7,5007.7
XS Rating Curve= 0 ,0
Exp/Cntr=0.3,0.1

Type RM Length L Ch R = 1 ,12294   ,481,481,481
BEGIN DESCRIPTION:
UNNAMED TRIB TO WEST CANEY CREEK 8.6
END DESCRIPTION:
XS GIS Cut Line= 3
      3616934.19     10362900.08      3616407.25     10362534.31
     3615525.649    10362118.391
#Sta/Elev= 30
       0375.8821 98.5051376.3069137.9071375.6027167.4587376.1558187.1597375.5807
305.3658375.5381 502.376373.6914561.4791372.5669581.1801370.5615591.0306370.5771
610.7316372.8465650.1336373.3506739.3415372.8761769.0774373.4615858.2853372.5162
927.6691372.7416947.4931  373.66967.3171373.1747977.2291373.77091026.789373.6301
1125.909375.60211175.469375.40521314.236377.0385 1334.06 376.5931353.884377.5425
 1482.74378.71021562.036380.54411591.772379.70751601.684379.68311611.596380.3163
#Mann= 3 , 0 , 0
       0     .08       0561.4791     .05       0610.7316     .08       0
Bank Sta=561.4791,610.7316
XS Rating Curve= 0 ,0
Exp/Cntr=0.3,0.1

Type RM Length L Ch R = 1 ,11813   ,634,634,634
BEGIN DESCRIPTION:
UNNAMED TRIB TO WEST CANEY CREEK 8.5
END DESCRIPTION:
XS GIS Cut Line= 3
      3617247.53     10362613.16      3616510.45     10362072.43
      3615498.81     10361534.33
#Sta/Elev= 30
  4124.6  372.67  4158.1  372.25  4207.6  370.98  4393.6   372.7  4565.4  371.08
    4584   371.9    4774  371.74  4809.6  370.75  4974.7  370.12  4980.9  368.28
  4992.6  366.82  4995.3  366.32  4998.6  366.82  5035.2  369.55  5113.2  370.35
    5195  370.83  5288.5  369.64    5320  370.38  5348.8  368.75  5399.3  367.91
  5483.5  367.77  5694.7  368.35  5727.3  369.82  5750.5  368.71  5784.4  370.82
  5807.1  369.47  5840.4  370.21  6095.2  373.96  6121.6  375.42  6184.6  374.99
#Mann= 10 ,-1 , 0
  4124.6      .1       0  4158.1     .08       0    4584     .05       0
  4974.7     .04       0  5035.2     .05       0  5113.2     .08       0
  5483.5     .05       0  5750.5     .08       0  5840.4     .05       0
  6121.6     .08       0
Bank Sta=4992.6,4998.6
XS Rating Curve= 0 ,0
Exp/Cntr=0.3,0.1

Type RM Length L Ch R = 1 ,11179   ,1002,1002,1002
BEGIN DESCRIPTION:
UNNAMED TRIB TO WEST CANEY CREEK 8.501
END DESCRIPTION:
XS GIS Cut Line= 6
      3617749.21     10362346.44      3617717.95     10362256.15
      3617646.77     10362195.25      3615306.38     10360368.39
      3614523.51     10359842.96       3614172.8      10359724.9
#Sta/Elev= 30
  3734.3  369.09  3799.7  368.58  3837.5  365.22  3844.3  367.12  3893.7  365.02
  3953.7  365.75  4023.6   365.9  4191.6  366.23  4196.9  366.24  4500.3  365.94
  4983.2  367.96  4991.3  366.23  4997.6  363.37  5012.1  366.06  5026.6  368.32
  5076.3  366.27  5596.4  365.74  5617.2  363.87    6879  364.82  7221.1  362.74
  7382.8  362.46  7397.8  358.36  7415.8  356.65  7418.5  356.15  7421.8  356.65
  7439.4  359.26  7452.9  361.04  7626.5  364.78  8174.5  368.17  8205.4  371.96
#Mann= 16 ,-1 , 0
  3734.3      .1       0  3953.7     .08       0  4023.6      .1       0
  4191.6     .08       0  4196.9     .05       0  4500.3     .08       0
  4983.2     .05       0  5026.6     .08       0  5076.3     .08       0
  7221.1     .05       0  7415.8     .07       0  7421.8     .05       0
  7439.4     .08       0  7452.9     .05       0  7626.5     .08       0
  8174.5     .05       0
#XS Ineff= 2 , 0
                         5038.64          368.38
Permanent Ineff=
       F       F
#Block Obstruct= 2 , 0
                         5007.95          363.35
Bank Sta=4991.3,5012.1
XS Rating Curve= 0 ,0
Exp/Cntr=0.3,0.1

Type RM Length L Ch R = 1 ,10177   ,317,317,317
BEGIN DESCRIPTION:
UNNAMED TRIB TO WEST CANEY CREEK 8.4
END DESCRIPTION:
XS GIS Cut Line= 5
      3617947.12     10362370.75      3617921.19     10362163.99
      3615592.95      10360388.1      3614315.17      10359513.1
      3614229.43     10359526.81
#Sta/Elev= 30
    2660  372.21  2699.4  367.24  2785.7  367.05    3033  368.56  3111.3  366.42
  3238.4  365.71    3326  363.97  3422.4  365.85  3579.7  365.04  3714.5  364.18
  3747.6  363.34    3775  365.37  3836.8  363.55  3946.8  363.67  4175.2  364.86
  4438.4  363.03  4974.2  362.62    4995  360.08  5009.6  360.14  5030.5  361.49
  6420.2  360.19  6557.7  361.68  6578.6  360.68  6608.2   354.8  6635.5  360.64
  6766.9  362.25  6836.2  362.58  7347.5  363.59    7399  363.96  7432.1   366.9
#Mann= 15 ,-1 , 0
    2660     .08       0  2785.7      .1       0  3111.3     .08       0
  3238.4     .08       0  3422.4     .08       0  3579.7     .05       0
  3714.5     .08       0  3836.8     .05       0  3946.8      .1       0
  4438.4     .05       0  4974.2     .05       0  5030.5     .08       0
  6766.9     .05       0  6836.2     .05       0  7347.5     .08       0
#Block Obstruct= 2 , 0
                         5013.64          359.13
Bank Sta=4995,5009.6
XS Rating Curve= 0 ,0
Exp/Cntr=0.3,0.1

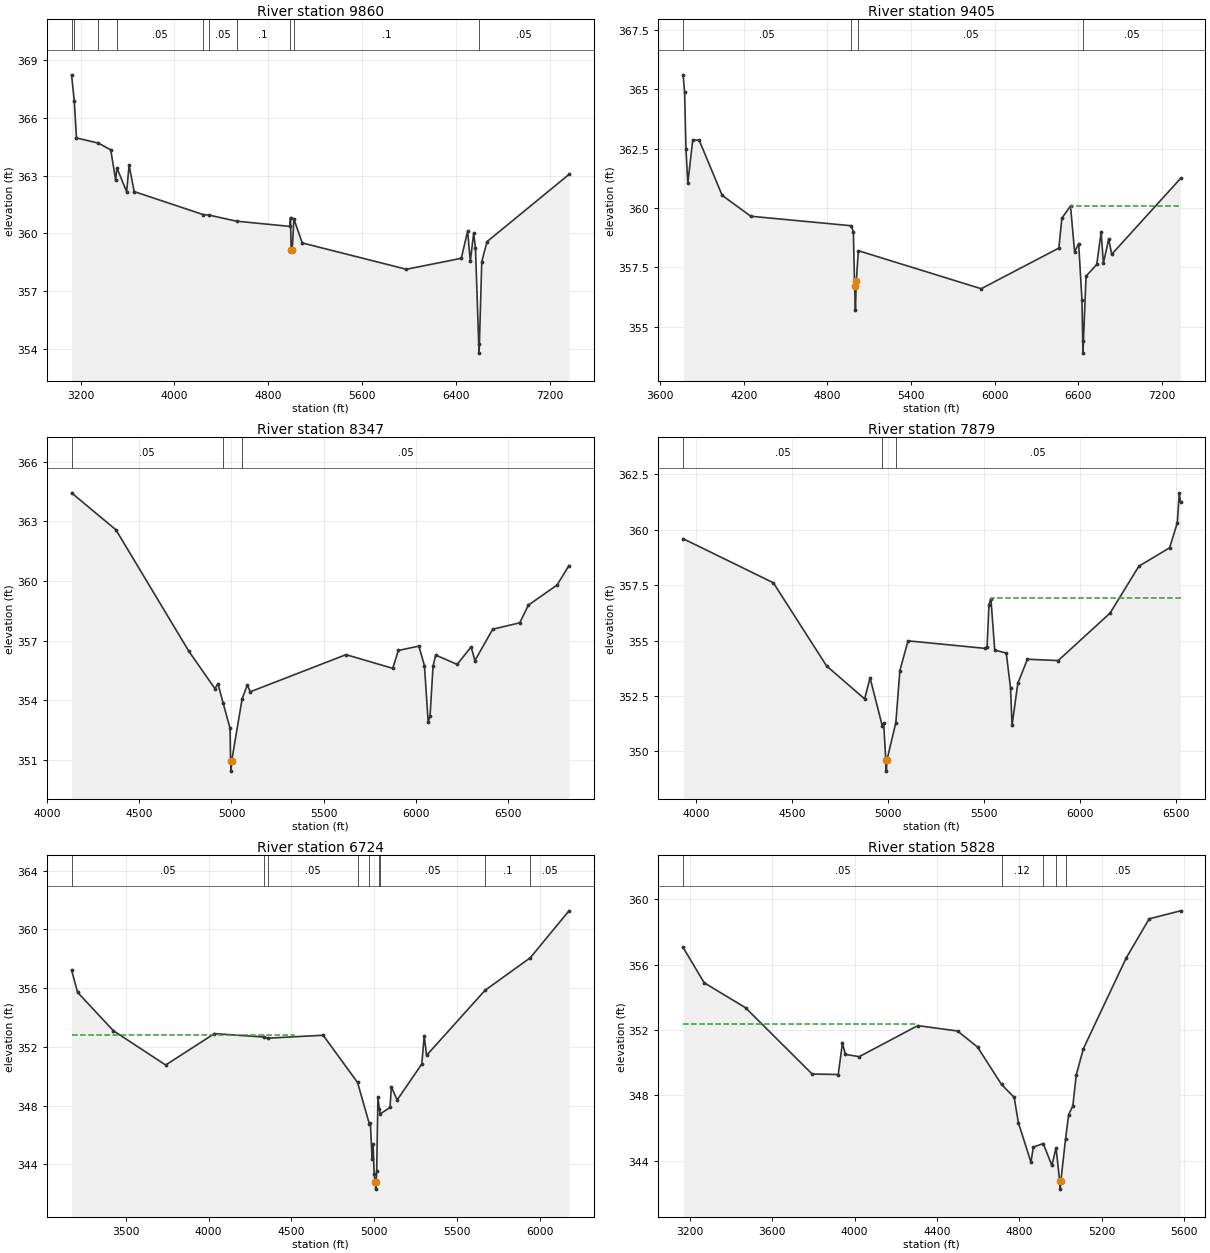
Type RM Length L Ch R = 1 ,9860    ,455,455,455
BEGIN DESCRIPTION:
UNNAMED TRIB TO WEST CANEY CREEK 8.31
END DESCRIPTION:
XS GIS Cut Line= 3
      3617856.83     10361735.31      3615856.84     10360193.65
       3614297.8     10359478.37
#Sta/Elev= 30
  3122.5  368.24  3145.7   366.9  3164.7  364.96  3350.8  364.69  3456.7  364.34
    3499  362.75    3509  363.41  3592.3  362.16  3613.1  363.54  3656.6  362.17
    4247  360.97    4293  360.95  4529.6  360.63  4982.9  360.36  4989.2  360.82
 4994.71  359.14  5003.7  359.14  5018.2  360.75  5088.9   359.5  5976.9  358.13
  6445.1   358.7  6499.2  360.11  6522.1  358.55  6550.7  360.01  6566.1  359.24
  6596.4  353.77  6599.7  354.27  6619.7  358.53  6665.1  359.57    7363  363.06
#Mann= 10 ,-1 , 0
  3122.5     .08       0  3145.7     .15       0  3350.8      .1       0
    3509     .05       0    4247      .1       0    4293     .05       0
  4529.6      .1       0  4982.9     .05       0  5018.2      .1       0
  6599.7     .05       0
#Block Obstruct= 2 , 0
                            5000          358.38
Bank Sta=4994.71,5003.7
XS Rating Curve= 0 ,0
Exp/Cntr=0.3,0.1

Type RM Length L Ch R = 1 ,9405    ,1058,1058,1058
BEGIN DESCRIPTION:
UNNAMED TRIB TO WEST CANEY CREEK 8.3
END DESCRIPTION:
XS GIS Cut Line= 6
      3617620.94     10360849.36      3616824.52     10360365.81
       3616467.2      10360106.7      3616057.73     10359923.99
      3615374.39     10359831.98      3614396.16     10359422.66
#Sta/Elev= 30
  3764.1   365.6  3774.8  364.86  3784.4  362.49  3797.8  361.04    3833  362.86
  3879.4  362.85  4044.2  360.53  4249.6  359.65  4971.8  359.25  4986.5  358.98
  4995.1  356.72  5001.2   355.7  5007.6  356.92  5022.1   358.2  5904.1   356.6
  6461.8  358.31  6483.5  359.57  6545.6  360.08  6574.8  358.15    6604   358.5
  6627.8  356.11    6635  353.89  6638.3  354.39    6657  357.13  6733.8  357.62
  6765.4  358.99  6781.4  357.67  6819.6  358.69  6841.3  358.05  7335.5  361.24
#Mann= 4 ,-1 , 0
  3764.1     .05       0  4971.8     .05       0  5022.1     .05       0
  6638.3     .05       0
#XS Ineff= 2 , 0
                         6547.73          360.08
Permanent Ineff=
       F       F
#Block Obstruct= 2 , 0
                         5004.55          355.64
Bank Sta=4995.1,5007.6
XS Rating Curve= 0 ,0
Exp/Cntr=0.3,0.1

Type RM Length L Ch R = 1 ,8347    ,468,468,468
BEGIN DESCRIPTION:
UNNAMED TRIB TO WEST CANEY CREEK 8.2
END DESCRIPTION:
XS GIS Cut Line= 4
      3616983.65     10359177.88      3616339.59     10359254.63
      3615763.28      10359568.1      3614388.29     10359352.82
#Sta/Elev= 30
  4132.9  364.44  4373.5  362.58  4768.9  356.47  4910.4  354.59  4926.6  354.84
  4954.1  353.88  4992.1   352.6  4994.8  350.94  4997.6  350.44  5000.8  350.94
  5057.7  354.08    5086  354.78  5101.4  354.43  5620.9   356.3    5874  355.61
  5904.5  356.51  6015.7  356.73  6046.1  355.74  6066.3  352.89  6076.4  353.22
  6092.5  355.72  6106.8  356.28    6223  355.81  6299.1  356.69  6319.4     356
  6416.1  357.58  6562.3   357.9  6609.2  358.79  6764.7   359.8  6829.3  360.78
#Mann= 3 ,-1 , 0
  4132.9     .05       0  4954.1     .03       0  5057.7     .05       0
Bank Sta=4994.8,5000.8
XS Rating Curve= 0 ,0
Exp/Cntr=0.3,0.1

Type RM Length L Ch R = 1 ,7879    ,1155,1155,1155
BEGIN DESCRIPTION:
UNNAMED TRIB TO WEST CANEY CREEK 8.1
END DESCRIPTION:
XS GIS Cut Line= 4
      3616762.32     10358713.83      3616151.55      10358727.8
      3615649.44     10359194.13      3614355.31     10359265.81
#Sta/Elev= 30
  3933.9   359.6  4404.2  357.61  4681.4  353.86  4879.8  352.37  4908.1  353.32
  4971.6  351.16    4979  351.27  4990.1  349.61  4992.9  349.11  4996.1  349.61
  5042.5   351.3  5063.5  353.65    5106  354.99  5507.8  354.65  5517.9  354.72
  5527.9  356.63  5537.9  356.89  5557.9  354.57    5618  354.44  5640.1  352.87
  5648.1  351.18  5678.1  353.07  5728.2  354.16  5888.4   354.1  6158.8  356.24
  6309.1  358.36  6469.3  359.19  6509.4  360.32  6519.4  361.67  6526.2  361.24
#Mann= 3 ,-1 , 0
  3933.9     .05       0  4971.6     .03       0  5042.5     .05       0
#XS Ineff= 2 , 0
                         5536.36          356.94
Permanent Ineff=
       F       F
Bank Sta=4990.1,4996.1
XS Rating Curve= 0 ,0
Exp/Cntr=0.3,0.1

Type RM Length L Ch R = 1 ,6724    ,896,896,896
BEGIN DESCRIPTION:
UNNAMED TRIB TO WEST CANEY CREEK 8.0
END DESCRIPTION:
XS GIS Cut Line= 3
      3616774.39      10357413.2      3615103.48     10358327.88
      3614249.49     10359017.26
#Sta/Elev= 30
  3173.1  357.23  3209.9  355.71  3425.5   353.1  3741.3  350.76  4035.3   352.9
    4332  352.67    4359  352.59  4691.9  352.79  4899.5  349.57  4971.3  346.72
    4977   346.8  4987.4  344.33  4993.1  345.36  4999.7   343.3  5006.2   342.8
  5008.9   342.3  5012.2   342.8  5014.9  343.54  5022.5  348.59    5031  347.76
  5036.4  347.43  5095.5  347.87  5103.4  349.27  5138.6  348.38  5287.4  350.83
  5301.8  352.75  5316.2  351.42  5668.7  355.85    5942  358.07  6175.5  361.27
#Mann= 9 ,-1 , 0
  3173.1     .05       0    4332      .1       0    4359     .05       0
  4899.5     .16       0  4971.3     .03       0    5031     .16       0
  5036.4     .05       0  5668.7      .1       0    5942     .05       0
#XS Ineff= 2 , 0
         4513.35  352.83
Permanent Ineff=
       F       F
Bank Sta=5006.2,5012.2
XS Rating Curve= 0 ,0
Exp/Cntr=0.3,0.1

Type RM Length L Ch R = 1 ,5828    ,1130,1130,1130
BEGIN DESCRIPTION:
UNNAMED TRIB TO WEST CANEY CREEK 7.0
END DESCRIPTION:
XS GIS Cut Line= 3
      3616752.66     10357339.42      3614751.91     10357719.81
      3614401.89     10357869.82
#Sta/Elev= 30
  3166.7  357.05  3269.1  354.89  3470.3  353.36  3793.8  349.31  3920.5  349.28
  3940.9   351.2  3955.5  350.51  4022.3  350.37  4307.3  352.27  4500.7  351.94
  4597.4  350.96  4714.1  348.67  4775.6  347.88  4795.9  346.34    4857  343.92
  4868.7  344.84  4916.7  345.06  4958.8  343.72  4979.1   344.8  4996.5  342.77
  4999.3  342.27  5002.5  342.77  5025.3  345.35  5040.2  346.82  5060.6  347.36
  5077.5  349.26  5111.5  350.85  5319.7   356.4  5431.5   358.8  5584.1  359.29
#Mann= 5 ,-1 , 0
  3166.7     .05       0  4714.1     .12       0  4916.7     .16       0
  4979.1     .07       0  5025.3     .05       0
#XS Ineff= 2 , 0
         4303.98  352.36
Permanent Ineff=
       F       F
Bank Sta=4996.5,5002.5
XS Rating Curve= 0 ,0
Exp/Cntr=0.3,0.1

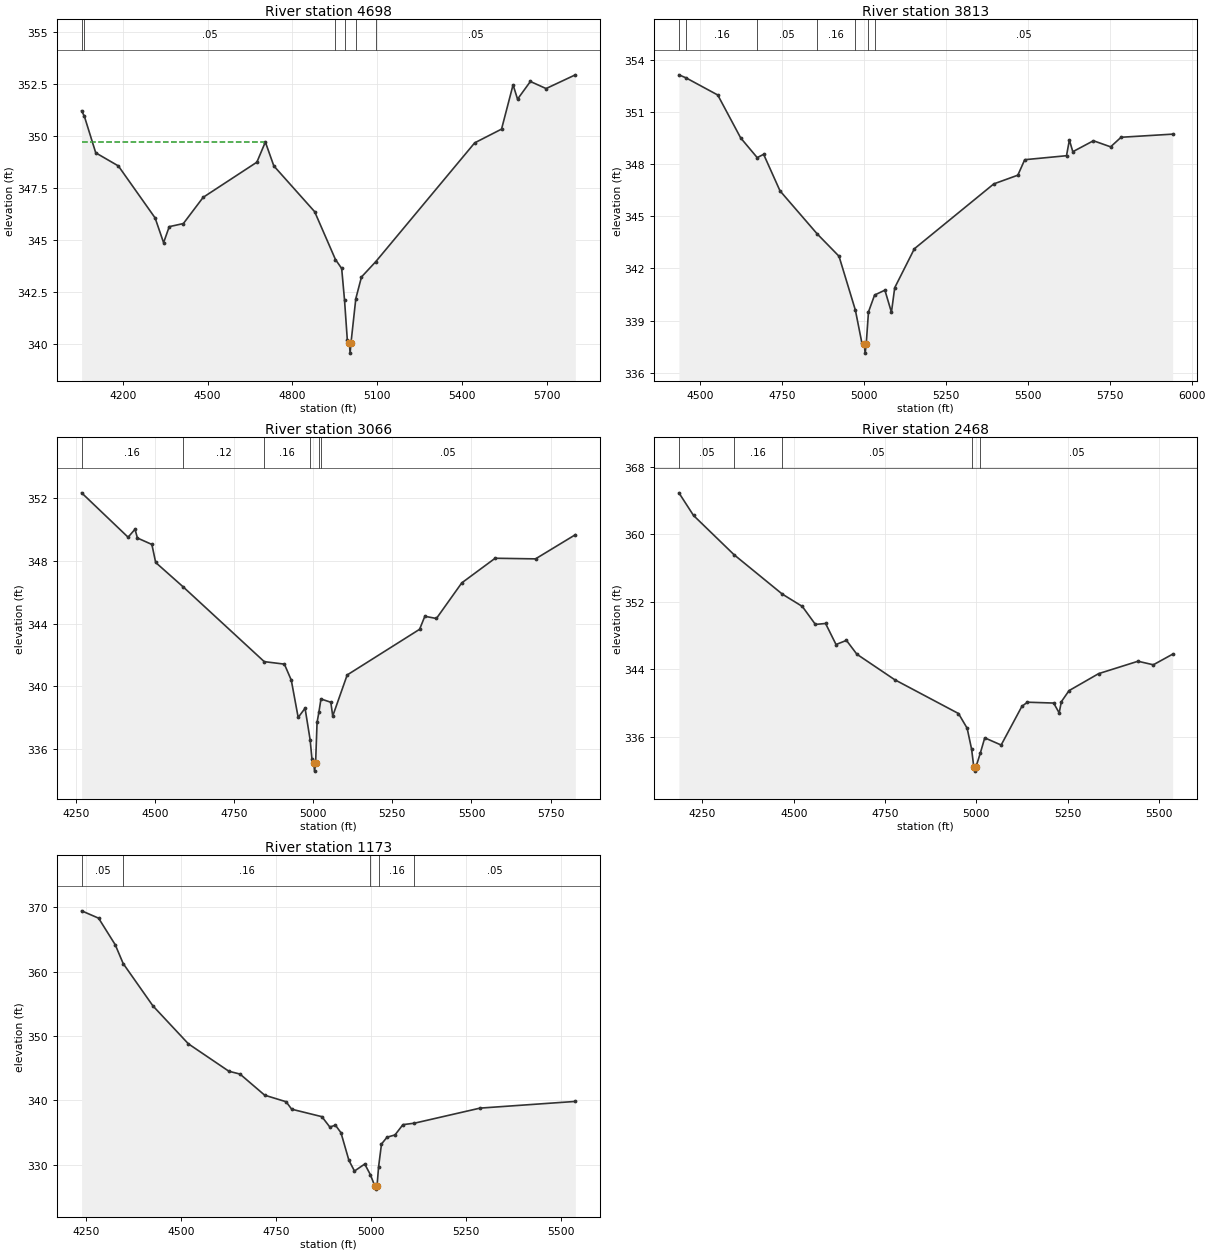
Type RM Length L Ch R = 1 ,4698    ,885,885,885
BEGIN DESCRIPTION:
UNNAMED TRIB TO WEST CANEY CREEK 6.0
END DESCRIPTION:
XS GIS Cut Line= 3
      3616152.05     10357066.42      3614935.08     10357081.53
      3614416.26     10357187.48
#Sta/Elev= 30
  4054.6  351.19  4064.3  350.93  4104.6  349.17  4184.6  348.54  4314.6  346.04
  4344.6  344.85  4364.6  345.62  4414.6  345.77  4484.6  347.03  4674.6  348.72
  4704.6  349.69  4734.6  348.54    4879  346.34  4952.6  344.04  4974.6  343.61
  4984.6   342.1  4994.6  340.16  5001.6  340.04  5004.4  339.54  5007.6  340.04
  5024.6  342.16  5044.6   343.2  5095.3  343.94  5445.1  349.65  5540.1  350.31
  5580.9  352.44  5596.7  351.75  5642.1   352.6  5697.7  352.26  5801.2  352.92
#Mann= 6 ,-1 , 0
  4054.6     .12       0  4064.3     .05       0  4952.6     .16       0
  4984.6     .07       0  5024.6     .16       0  5095.3     .05       0
#XS Ineff= 2 , 0
            4700  349.71
Permanent Ineff=
       F       F
Bank Sta=5001.6,5007.6
XS Rating Curve= 0 ,0
Exp/Cntr=0.3,0.1

Type RM Length L Ch R = 1 ,3813    ,747,747,747
BEGIN DESCRIPTION:
UNNAMED TRIB TO WEST CANEY CREEK 5.0
END DESCRIPTION:
XS GIS Cut Line= 3
      3615990.63     10356470.41      3615080.91     10356505.14
      3614511.43      10356685.7
#Sta/Elev= 30
  4434.2  353.13  4455.5  352.96  4552.8  351.97  4622.9   349.5  4673.3  348.37
  4692.9  348.56  4742.9  346.46  4856.7  343.98  4923.1   342.7  4973.1   339.6
  4993.1   337.7  5000.1  337.63  5002.9  337.13  5006.1  337.63  5013.1   339.5
  5031.8  340.47  5063.2  340.75  5083.2  339.48  5093.2  340.89  5153.2  343.13
  5395.8  346.86  5469.2  347.36  5490.2  348.25  5617.8  348.48  5626.6  349.38
  5637.1  348.71    5700  349.34  5752.5  348.99  5784.4  349.54    5942  349.72
#Mann= 7 ,-1 , 0
  4434.2     .12       0  4455.5     .16       0  4673.3     .05       0
  4856.7     .16       0  4973.1     .07       0  5013.1     .16       0
  5031.8     .05       0
Bank Sta=5000.1,5006.1
XS Rating Curve= 0 ,0
Exp/Cntr=0.3,0.1

Type RM Length L Ch R = 1 ,3066    ,598,598,598
BEGIN DESCRIPTION:
UNNAMED TRIB TO WEST CANEY CREEK 4.0
END DESCRIPTION:
XS GIS Cut Line= 3
      3615886.43     10355525.99       3615094.8     10355963.47
      3614511.46     10356262.09
#Sta/Elev= 30
  4268.4  352.33  4415.3   349.5  4437.1  350.01  4444.7  349.45  4490.4  349.04
  4502.4  347.89    4589  346.34  4845.3  341.57    4909  341.41  4930.8  340.39
  4952.6  338.01  4974.3   338.6  4990.4  336.58  4996.1  335.37  5001.6  335.09
  5004.3  334.59  5007.6  335.09  5012.2  337.69  5017.9  338.33  5024.6  339.19
  5055.7  338.98  5061.7   338.1  5107.4  340.72  5336.1  343.63  5352.7  344.46
  5389.3  344.32  5469.4  346.59  5574.8  348.16  5702.4  348.12  5828.2  349.66
#Mann= 6 ,-1 , 0
  4268.4     .16       0    4589     .12       0  4845.3     .16       0
  4990.4     .07       0  5017.9     .16       0  5024.6     .05       0
Bank Sta=5001.6,5007.6
XS Rating Curve= 0 ,0
Exp/Cntr=0.3,0.1

Type RM Length L Ch R = 1 ,2468    ,1295,1295,1295
BEGIN DESCRIPTION:
UNNAMED TRIB TO WEST CANEY CREEK 3.0
END DESCRIPTION:
XS GIS Cut Line= 3
      3615657.27     10354970.44      3615205.91     10355352.36
      3614575.91     10355778.04
#Sta/Elev= 30
  4185.7  364.89  4225.7  362.21  4336.7  357.56  4468.7   352.9  4523.5  351.44
  4559.3  349.31  4587.2  349.42  4615.8  346.93  4644.3  347.42  4672.9  345.78
  4776.2  342.77    4951  338.76  4974.7  337.02  4986.9  334.54  4992.9  332.44
  4995.6  331.94  4998.9  332.44  5010.8  334.08  5022.9  335.88  5067.8  335.03
  5124.7  339.62  5139.7   340.1  5211.6     340  5226.6  338.83  5232.6  340.16
  5253.6  341.47  5334.5  343.48  5442.4  344.95  5484.4  344.53  5537.3  345.79
#Mann= 5 ,-1 , 0
  4185.7     .05       0  4336.7     .16       0  4468.7     .05       0
  4986.9     .03       0  5010.8     .05       0
Bank Sta=4992.9,4998.9
XS Rating Curve= 0 ,0
Exp/Cntr=0.3,0.1

Type RM Length L Ch R = 1 ,1173    ,0,0,0
BEGIN DESCRIPTION:
UNNAMED TRIB TO WEST CANEY CREEK 1.0
END DESCRIPTION:
XS GIS Cut Line= 3
      3615233.72     10354310.67      3614471.67     10354866.42
      3614439.39     10355221.48
#Sta/Elev= 30
  4238.4  369.45  4283.1  368.31    4327  364.17  4347.8  361.26  4426.1  354.68
  4519.5  348.78  4626.1  344.52  4655.4  344.08  4720.3   340.8  4776.7  339.78
  4791.4  338.62  4870.9  337.46  4891.8  335.85  4906.5  336.14  4921.1  334.97
    4942  330.68  4956.7  329.01  4983.7   330.1  4998.4  328.46  5010.1   326.7
  5012.8   326.2  5016.1   326.7  5020.1  329.65  5027.8  333.21  5042.4  334.27
  5063.3  334.62  5084.2  336.22  5114.6  336.45  5287.2  338.79  5538.1  339.83
#Mann= 5 ,-1 , 0
  4238.4     .05       0  4347.8     .16       0  4998.4     .07       0
  5020.1     .16       0  5114.6     .05       0
Bank Sta=5010.1,5016.1
XS Rating Curve= 0 ,0
Exp/Cntr=0.3,0.1

Chan Stop Cuts=-1
Use User Specified Reach Order=0
Composite Channel Slope=5