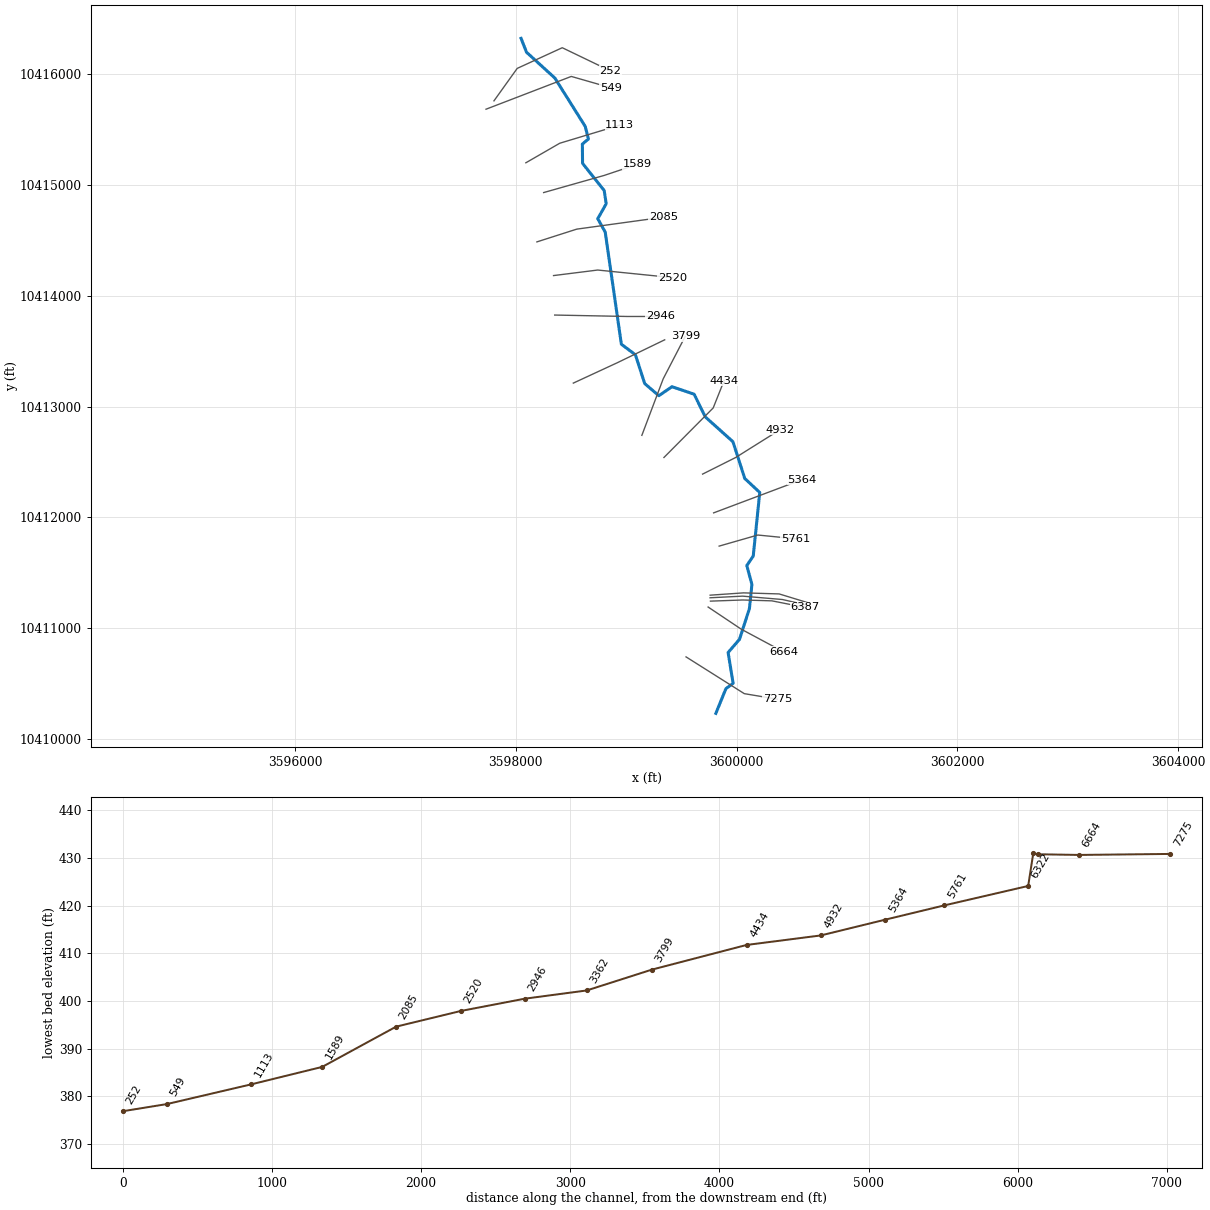
--- UNT0347 IN CEDR CR.prj (project) ---

Proj Title=UNT0347 IN CEDR CR Base Level Engineering
Current Plan=p01
Default Exp/Contr=0.3,0.1
English Units
Geom File=g01
Flow File=f01
Plan File=p01
Y Axis Title=Elevation
X Axis Title(PF)=Main Channel Distance
X Axis Title(XS)=Station
BEGIN DESCRIPTION:
UNT0347 IN CEDR CR
END DESCRIPTION:
DSS Export Rating Curves= 0
DSS Export Rating Curve Sorted= 0
DSS Export Volume Flow Curves= 0
DXF OffsetX= 0
DXF OffsetY= 0
DXF ScaleX= 1
DXF ScaleY= 10

--- UNT0347 IN CEDR CR.p01 (plan) ---

Plan Title=Multiple Run
Short Identifier=Multiple
Geom File=g01
Flow File=f01
Subcritical Flow
K Sum by GR= 0
Std Step Tol= 0.01
Critical Tol= 0.01
Num of Std Step Trials= 20
Max Error Tol= 0.3
Flow Tol Ratio= 0.001
Split Flow NTrial= 30
Split Flow Tol= 0.02
Split Flow Ratio= 0.02
Log Output Level= 0
Friction Slope Method= 1
Unsteady Friction Slope Method= 2
Unsteady Bridges Friction Slope Method= 1
Parabolic Critical Depth
Global Vel Dist=  1 , 1 , 1
Global Log Level= 0
CheckData=True
Encroach Param= -1, 0, 0, 0
BEGIN DESCRIPTION:
Multiple Run
END DESCRIPTION:

--- UNT0347 IN CEDR CR.f01 (steady flow) ---

Flow Title=Multiple
Program Version=4.10
Number of Profiles= 7
Profile Names=10-year,25-year,50-year,1pct_min,100-year,1pct_plu,500-year
River Rch & RM=UNT0347 IN CEDR,Reach-1         ,7275
    1667    2365    2959    2700    3651    4937    5542
Boundary for River Rch & Prof#=UNT0347 IN CEDR,Reach-1         , 1
Up Type= 0
Dn Type= 3
Dn Slope=0.0075
Boundary for River Rch & Prof#=UNT0347 IN CEDR,Reach-1         , 2
Up Type= 0
Dn Type= 3
Dn Slope=0.0075
Boundary for River Rch & Prof#=UNT0347 IN CEDR,Reach-1         , 3
Up Type= 0
Dn Type= 3
Dn Slope=0.0075
Boundary for River Rch & Prof#=UNT0347 IN CEDR,Reach-1         , 4
Up Type= 0
Dn Type= 3
Dn Slope=0.0075
Boundary for River Rch & Prof#=UNT0347 IN CEDR,Reach-1         , 5
Up Type= 0
Dn Type= 3
Dn Slope=0.0075
Boundary for River Rch & Prof#=UNT0347 IN CEDR,Reach-1         , 6
Up Type= 0
Dn Type= 3
Dn Slope=0.0075
Boundary for River Rch & Prof#=UNT0347 IN CEDR,Reach-1         , 7
Up Type= 0
Dn Type= 3
Dn Slope=0.0075
DSS Import GetInterval= 0
DSS Import GetPeak= 0
DSS Import FillOption= 0

--- UNT0347 IN CEDR CR.g01 (geometry) ---

Geom Title=Existing Conditions
Program Version=4.10

River Reach=UNT0347 IN CEDR ,Reach-1
Reach XY= 30
      3599812.11     10410231.64      3599903.52     10410455.07
      3599968.39     10410502.91      3599923.23     10410781.28
       3600026.1     10410899.38      3600116.17     10411177.56
      3600138.74     10411395.44      3600092.57     10411566.36
      3600150.81     10411651.52       3600209.8     10412225.72
        3600074.     10412352.29      3599966.82     10412684.18
      3599716.24     10412908.08      3599615.74     10413112.64
      3599414.95     10413180.65      3599295.86     10413099.34
      3599167.59     10413209.11      3599083.84     10413468.29
      3598956.41     10413564.13       3598810.2     10414575.93
      3598742.61     10414696.99      3598819.13     10414832.47
       3598800.7     10414951.57      3598604.91     10415197.14
      3598603.24      10415370.9       3598658.1     10415416.43
      3598629.08     10415530.37      3598353.76     10415967.17
      3598097.36      10416199.9       3598047.9     10416325.39

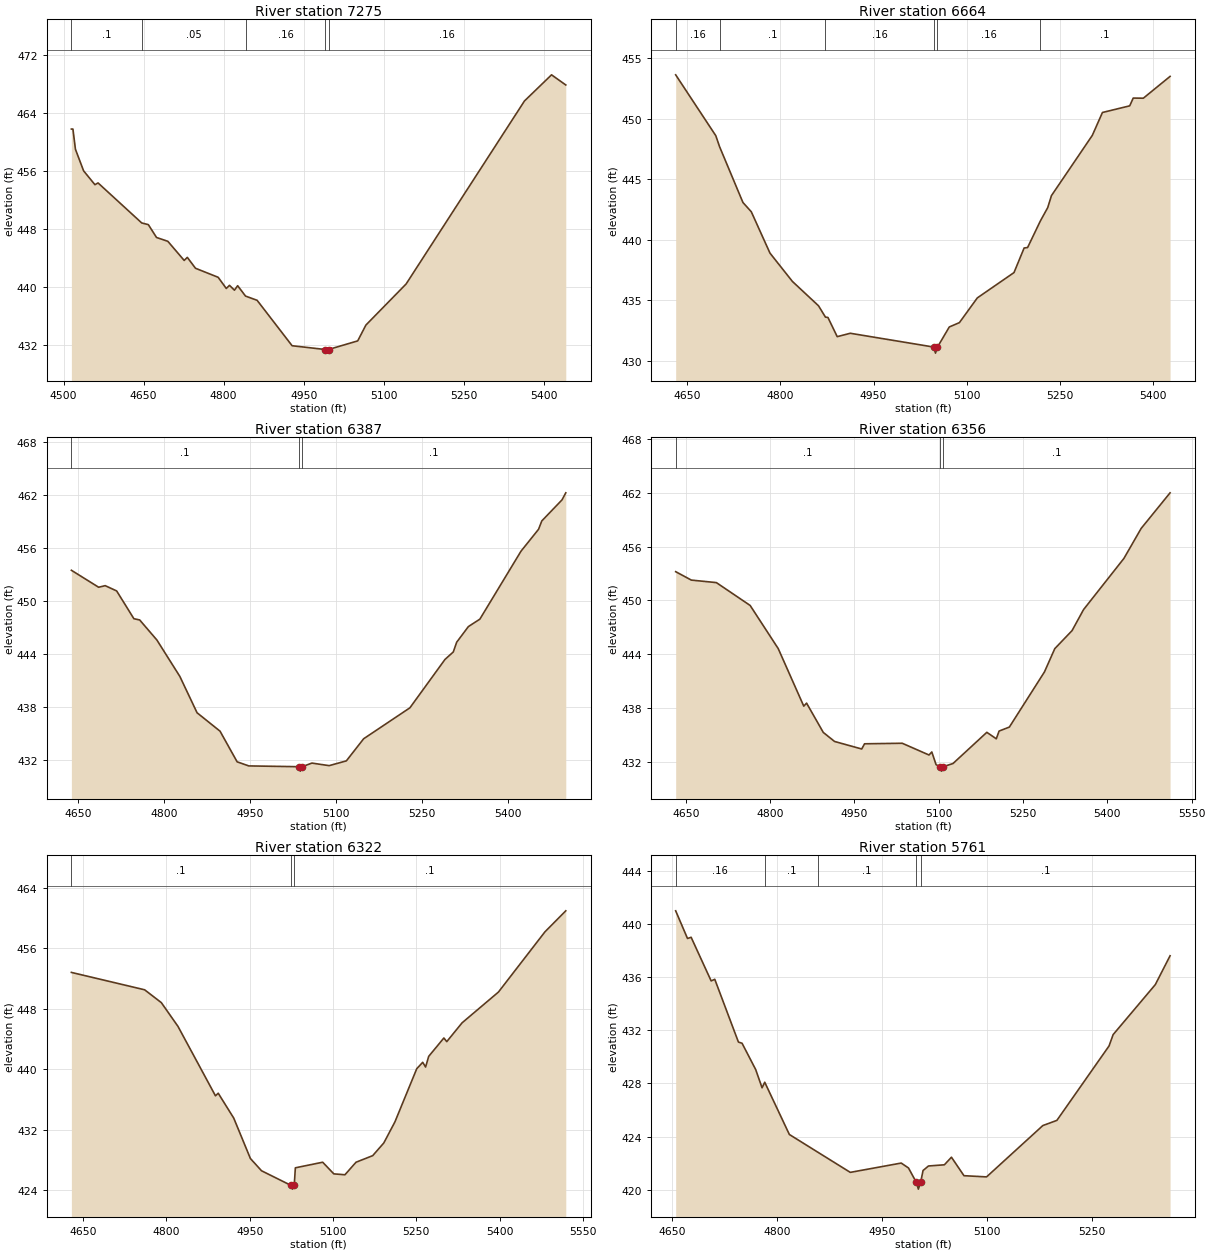
Type RM Length L Ch R = 1 ,7275    ,611,611,611
BEGIN DESCRIPTION:
UNT0347 IN CEDR CR 16.0
END DESCRIPTION:
XS GIS Cut Line= 3
      3599542.12     10410741.63      3600069.84     10410409.64
      3600368.46     10410359.87
#Sta/Elev= 30
  4514.7  461.78  4517.6  461.78  4522.3  458.99  4537.6  456.01  4558.8   454.1
  4564.7  454.34  4646.4  448.82  4658.9  448.58  4674.2  446.81  4695.4  446.28
    4726  443.64  4731.9  444.06  4747.2  442.56  4789.7  441.31  4804.9  439.77
  4810.9   440.2  4820.2  439.53  4826.2  440.15  4840.9  438.72  4862.7  438.13
  4928.2  431.86  4990.4  431.34  4993.1  430.84  4996.4  431.34  5051.1  432.53
  5066.4  434.71  5141.8  440.39  5363.5  465.66  5414.2  469.27  5440.9  467.87
#Mann= 5 ,-1 , 0
  4514.7      .1       0  4646.4     .05       0  4840.9     .16       0
  4990.4     .07       0  4996.4     .16       0
Bank Sta=4990.4,4996.4
XS Rating Curve= 0 ,0
Exp/Cntr=0.3,0.1

Type RM Length L Ch R = 1 ,6664    ,277,277,277
BEGIN DESCRIPTION:
UNT0347 IN CEDR CR 15.0
END DESCRIPTION:
XS GIS Cut Line= 3
      3599742.12     10411191.63      3600042.11     10410991.64
      3600425.67     10410786.75
#Sta/Elev= 30
  4631.6  453.61  4696.2  448.58  4702.2  447.68  4739.8  443.07  4753.3   442.3
  4783.3  438.89  4819.4  436.55  4861.4  434.54  4872.6   433.6  4876.5  433.58
  4891.5  431.99  4912.5  432.27  5046.8  431.13  5049.6  430.63  5052.8  431.13
  5071.8  432.79  5088.1  433.15  5116.9  435.19  5175.9  437.28  5192.2  439.31
  5197.8  439.35  5218.2  441.53  5230.2  442.65  5236.1  443.63  5301.9  448.61
  5318.2   450.5  5362.1  451.05  5367.7  451.69    5384  451.68    5427  453.48
#Mann= 6 ,-1 , 0
  4631.6     .16       0  4702.2      .1       0  4872.6     .16       0
  5046.8     .07       0  5052.8     .16       0  5218.2      .1       0
Bank Sta=5046.8,5052.8
XS Rating Curve= 0 ,0
Exp/Cntr=0.3,0.1

Type RM Length L Ch R = 1 ,6387    ,31,31,31
BEGIN DESCRIPTION:
Mapping XS f1d897d9
END DESCRIPTION:
XS GIS Cut Line= 4
      3599763.22     10411244.83      3600056.65     10411255.25
      3600319.67     10411247.44      3600618.61     10411188.68
#Sta/Elev= 30
    4639  453.49  4686.5  451.57  4697.9  451.75  4717.9  451.15  4747.9  448.01
    4758  447.87    4788   445.6    4828  441.48    4858  437.37    4898  435.29
  4927.8  431.82  4948.1  431.36  5035.1  431.27  5037.9  430.77  5041.1  431.27
  5058.1  431.68  5088.1  431.39  5118.1  431.93  5148.2  434.43  5228.8  437.93
  5289.9   443.4  5304.4  444.25  5310.3  445.35  5330.7  447.12  5350.7  447.96
  5422.4  455.65    5453  458.13  5458.6  459.07  5493.8  461.45  5500.4  462.25
#Mann= 3 ,-1 , 0
    4639      .1       0  5035.1     .07       0  5041.1      .1       0
Bank Sta=5035.1,5041.1
XS Rating Curve= 0 ,0
Exp/Cntr=0.3,0.1

Type RM Length L Ch R = 1 ,6356    ,34,34,34
BEGIN DESCRIPTION:
Mapping XS ca80314b
END DESCRIPTION:
XS GIS Cut Line= 4
       3599759.8     10411275.21      3600054.05     10411289.97
      3600414.29     10411259.59      3600632.21      10411210.1
#Sta/Elev= 30
    4632  453.21  4659.9  452.27  4704.4  451.99  4764.5  449.44  4814.5  444.62
  4859.9   438.2  4864.9  438.54  4894.6  435.27  4914.7  434.26    4963  433.42
    4968     434  5035.1  434.06  5082.7  432.75  5087.7  433.09  5095.3  431.67
  5102.3  431.45  5105.1  430.95  5108.3  431.45  5125.4   431.8  5185.6  435.28
  5202.4  434.56  5207.4  435.42  5225.7  435.87  5288.1  442.02  5306.5  444.62
  5337.2  446.63  5357.7  448.98  5429.5  454.69  5460.2  458.04  5511.6  462.01
#Mann= 3 ,-1 , 0
    4632      .1       0  5102.3     .07       0  5108.3      .1       0
Bank Sta=5102.3,5108.3
XS Rating Curve= 0 ,0
Exp/Cntr=0.3,0.1

Type RM Length L Ch R = 1 ,6322    ,561,561,561
BEGIN DESCRIPTION:
UNT0347 IN CEDR CR 14.0
END DESCRIPTION:
XS GIS Cut Line= 4
      3599760.61     10411298.65      3600062.73     10411319.48
      3600385.64     10411309.94      3600638.09     10411232.99
#Sta/Elev= 30
  4629.2   452.8    4761   450.5  4791.1   448.8  4821.1  445.65  4888.5  436.47
  4893.5  436.81  4921.4  433.52  4951.4  428.17  4971.4  426.55  5024.3  424.62
  5027.1  424.12  5030.3  424.62  5032.3  426.94  5081.5  427.68  5101.5  426.14
  5121.5  426.02  5141.5  427.68  5171.5  428.55  5191.5  430.23  5211.5  433.02
  5250.8  440.06  5261.5   440.9  5266.7  440.28  5272.3  441.69  5299.6  444.12
  5304.8  443.64  5332.4  446.13  5397.8   450.2  5481.4  458.16    5519  460.95
#Mann= 3 ,-1 , 0
  4629.2      .1       0  5024.3     .07       0  5030.3      .1       0
Bank Sta=5024.3,5030.3
XS Rating Curve= 0 ,0
Exp/Cntr=0.3,0.1

Type RM Length L Ch R = 1 ,5761    ,397,397,397
BEGIN DESCRIPTION:
UNT0347 IN CEDR CR 13.0
END DESCRIPTION:
XS GIS Cut Line= 3
       3599842.1     10411741.64      3600192.11     10411841.64
      3600533.14       10411808.
#Sta/Elev= 30
    4655  440.98  4671.9   438.9  4677.1  438.99  4705.7  435.71  4710.9  435.83
  4744.7  431.11  4749.9  431.02  4769.4  429.04  4778.5  427.67  4782.3  428.09
  4817.5  424.16  4858.4  422.82  4904.6  421.31  4977.4  422.01  4987.8  421.64
  4999.1  420.55  5001.9  420.05  5005.1  420.55  5008.6  421.45  5016.4  421.79
  5039.1  421.88  5049.2  422.45  5067.1  421.06  5099.4  420.97  5179.8  424.83
  5199.9  425.22  5274.5  430.82  5280.3  431.67  5340.6  435.43  5361.7   437.6
#Mann= 5 ,-1 , 0
    4655     .16       0  4782.3      .1       0  4858.4      .1       0
  4999.1     .07       0  5005.1      .1       0
Bank Sta=4999.1,5005.1
XS Rating Curve= 0 ,0
Exp/Cntr=0.3,0.1

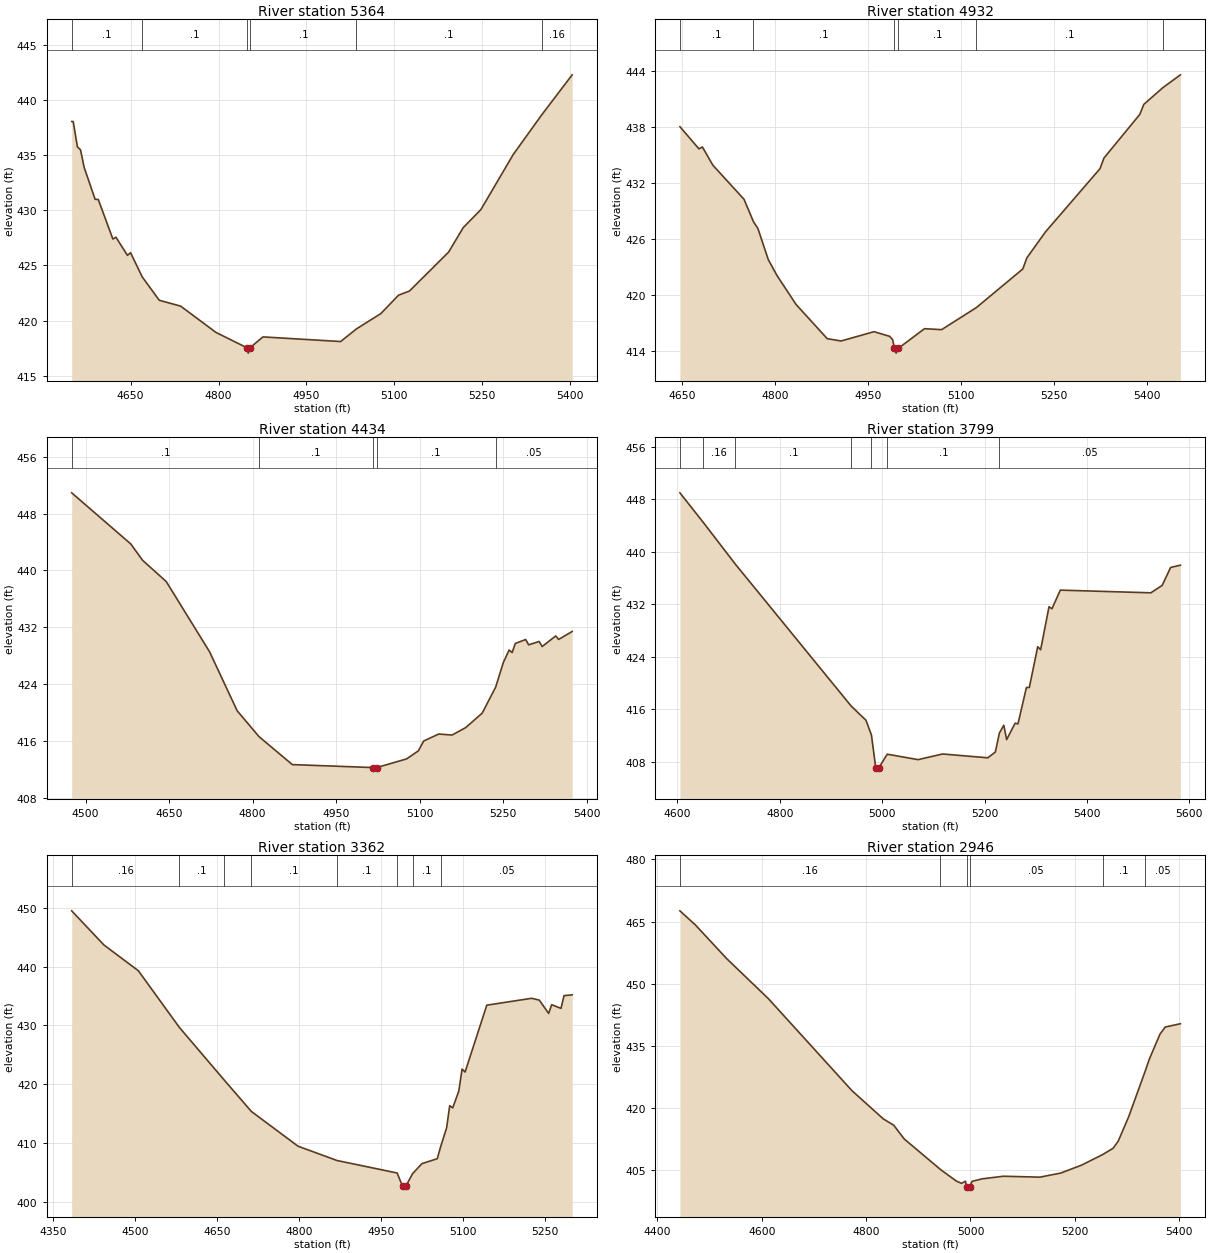
Type RM Length L Ch R = 1 ,5364    ,432,432,432
BEGIN DESCRIPTION:
UNT0347 IN CEDR CR 12.0
END DESCRIPTION:
XS GIS Cut Line= 3
      3599792.13     10412041.65      3600192.11     10412191.64
      3600592.13     10412341.65
#Sta/Elev= 30
  4549.3  438.04  4551.9  438.04  4559.1  435.74  4564.4  435.47  4570.6  433.88
  4589.3  430.99  4594.7  430.97  4619.6  427.39  4624.9  427.55  4644.5  425.91
  4649.8  426.15  4669.7  423.96  4698.8  421.84  4735.3  421.31  4795.8  418.92
    4848  417.55  4850.7  417.05    4854  417.55  4875.9  418.52  5008.5   418.1
  5035.3  419.24    5077  420.63  5107.3   422.3    5126  422.68  5192.7   426.2
  5217.7  428.42  5247.9  430.06  5303.1  435.05    5352  438.66  5403.7  442.27
#Mann= 6 ,-1 , 0
  4549.3      .1       0  4669.7      .1       0    4848     .07       0
    4854      .1       0  5035.3      .1       0    5352     .16       0
Bank Sta=4848,4854
XS Rating Curve= 0 ,0
Exp/Cntr=0.3,0.1

Type RM Length L Ch R = 1 ,4932    ,498,498,498
BEGIN DESCRIPTION:
UNT0347 IN CEDR CR 11.0
END DESCRIPTION:
XS GIS Cut Line= 3
      3599692.12     10412391.65      3599992.11     10412541.64
      3600392.11     10412791.64
#Sta/Elev= 30
  4646.5  438.03  4677.2  435.65  4682.8  435.85  4699.6   433.9  4749.9  430.24
  4765.1  427.84  4772.3  427.11    4789  423.77    4803  422.07  4833.8  418.96
  4884.1  415.29  4906.4  415.04  4959.5  416.04  4984.8  415.54  4989.6  415.18
  4992.5  414.24  4995.2  413.74  4998.5  414.24  5040.9  416.36  5068.6  416.26
  5124.7  418.63  5199.5  422.77    5206  423.96    5236  426.74  5323.9  433.52
  5330.4  434.67  5388.1  439.34  5394.6  440.42  5425.3  442.21  5453.6  443.59
#Mann= 6 ,-1 , 0
  4646.5      .1       0  4765.1      .1       0  4992.5     .05       0
  4998.5      .1       0  5124.7      .1       0  5425.3     .16       0
Bank Sta=4992.5,4998.5
XS Rating Curve= 0 ,0
Exp/Cntr=0.3,0.1

Type RM Length L Ch R = 1 ,4434    ,635,635,635
BEGIN DESCRIPTION:
UNT0347 IN CEDR CR 10.0
END DESCRIPTION:
XS GIS Cut Line= 3
      3599342.08     10412541.61       3599788.2     10412989.05
      3599887.16     10413236.45
#Sta/Elev= 30
  4475.2  450.92  4581.3  443.72  4602.5  441.42  4644.9  438.43  4722.7  428.54
  4772.2  420.24  4811.4   416.6  4871.2  412.66  5016.7  412.24  5019.5  411.74
  5022.7  412.24  5076.3  413.46  5097.5   414.6    5107  415.98  5133.9  416.96
  5158.1  416.82  5182.4  417.87    5212   419.9  5236.2  423.57  5249.9  427.02
  5260.4  428.79  5265.8  428.43  5271.4  429.71  5290.1  430.27  5295.4  429.52
  5314.3  429.99  5319.7  429.28  5343.9  430.77  5349.3  430.28  5373.5   431.4
#Mann= 5 ,-1 , 0
  4475.2      .1       0  4811.4      .1       0  5016.7     .05       0
  5022.7      .1       0  5236.2     .05       0
Bank Sta=5016.7,5022.7
XS Rating Curve= 0 ,0
Exp/Cntr=0.3,0.1

Type RM Length L Ch R = 1 ,3799    ,437,437,437
BEGIN DESCRIPTION:
UNT0347 IN CEDR CR 9.0
END DESCRIPTION:
XS GIS Cut Line= 3
      3599142.11     10412741.65       3599335.3     10413251.55
      3599534.94     10413635.48
#Sta/Elev= 30
  4604.8  448.95  4650.3  444.46  4713.1  438.09  4939.6  416.46  4968.4  414.31
  4979.1  412.05  4987.5  407.06  4990.2  406.56  4993.5  407.06  5009.9  409.14
  5070.2  408.31  5118.1  409.17  5206.5  408.59  5221.2  409.47  5229.1  412.36
  5237.7  413.55  5243.3  411.36  5259.8  413.86  5265.4  413.75  5281.9  419.29
  5287.6   419.3    5304  425.51  5309.7  425.05  5326.1  431.61  5331.8  431.29
  5348.2  434.13  5525.1  433.72  5547.2  434.85  5563.7  437.58  5582.8  437.93
#Mann= 7 ,-1 , 0
  4604.8      .1       0  4650.3     .16       0  4713.1      .1       0
  4939.6      .1       0  4979.1     .04       0  5009.9      .1       0
  5229.1     .05       0
Bank Sta=4987.5,4993.5
XS Rating Curve= 0 ,0
Exp/Cntr=0.3,0.1

Type RM Length L Ch R = 1 ,3362    ,416,416,416
BEGIN DESCRIPTION:
UNT0347 IN CEDR CR 8.0
END DESCRIPTION:
XS GIS Cut Line= 3
      3598521.39     10413213.17      3598920.66     10413397.45
      3599348.85     10413603.89
#Sta/Elev= 30
  4384.1  449.47  4442.8  443.69    4506  439.29  4581.1  429.65  4663.3  420.69
  4712.6  415.39    4798  409.48  4869.3  407.05  4979.2  404.93    4989  402.69
  4991.7  402.19    4995  402.69  5007.4  404.81  5024.5  406.52  5052.6  407.36
  5058.6  409.36  5069.7  412.63  5075.3  416.37  5080.8  415.99  5091.9  418.84
  5097.9  422.58  5103.4  422.08  5143.1  433.44  5225.1  434.61  5239.1   434.3
  5256.2  432.04  5261.7  433.52  5278.8   432.9  5284.3  435.06  5299.2   435.2
#Mann= 8 ,-1 , 0
  4384.1     .16       0  4581.1      .1       0  4663.3     .16       0
  4712.6      .1       0  4869.3      .1       0  4979.2     .04       0
  5007.4      .1       0  5058.6     .05       0
Bank Sta=4989,4995
XS Rating Curve= 0 ,0
Exp/Cntr=0.3,0.1

Type RM Length L Ch R = 1 ,2946    ,426,426,426
BEGIN DESCRIPTION:
UNT0347 IN CEDR CR 7.0
END DESCRIPTION:
XS GIS Cut Line= 3
      3598352.48     10413827.44      3599011.21      10413814.5
      3599311.25      10413814.5
#Sta/Elev= 30
  4443.3  467.61  4472.9  464.21  4532.9  456.08    4613  446.39    4773  424.21
    4833  417.41    4853  415.88    4873  412.57  4942.5   405.2    4973   402.4
    4983  401.86  4990.5  402.37  4992.5  400.96  4995.3  400.46  4998.5  400.96
    5003  402.34    5023  402.95    5063  403.57  5133.1  403.35  5173.1  404.34
  5213.1  406.26  5253.1  408.79  5273.1   410.3  5283.1  412.04  5303.1  417.92
    5334  428.66  5343.1  431.95  5363.1  437.86  5373.1  439.56  5402.2  440.37
#Mann= 6 ,-1 , 0
  4443.3     .16       0  4942.5     .05       0  4992.5     .03       0
  4998.5     .05       0  5253.1      .1       0    5334     .05       0
Bank Sta=4992.5,4998.5
XS Rating Curve= 0 ,0
Exp/Cntr=0.3,0.1

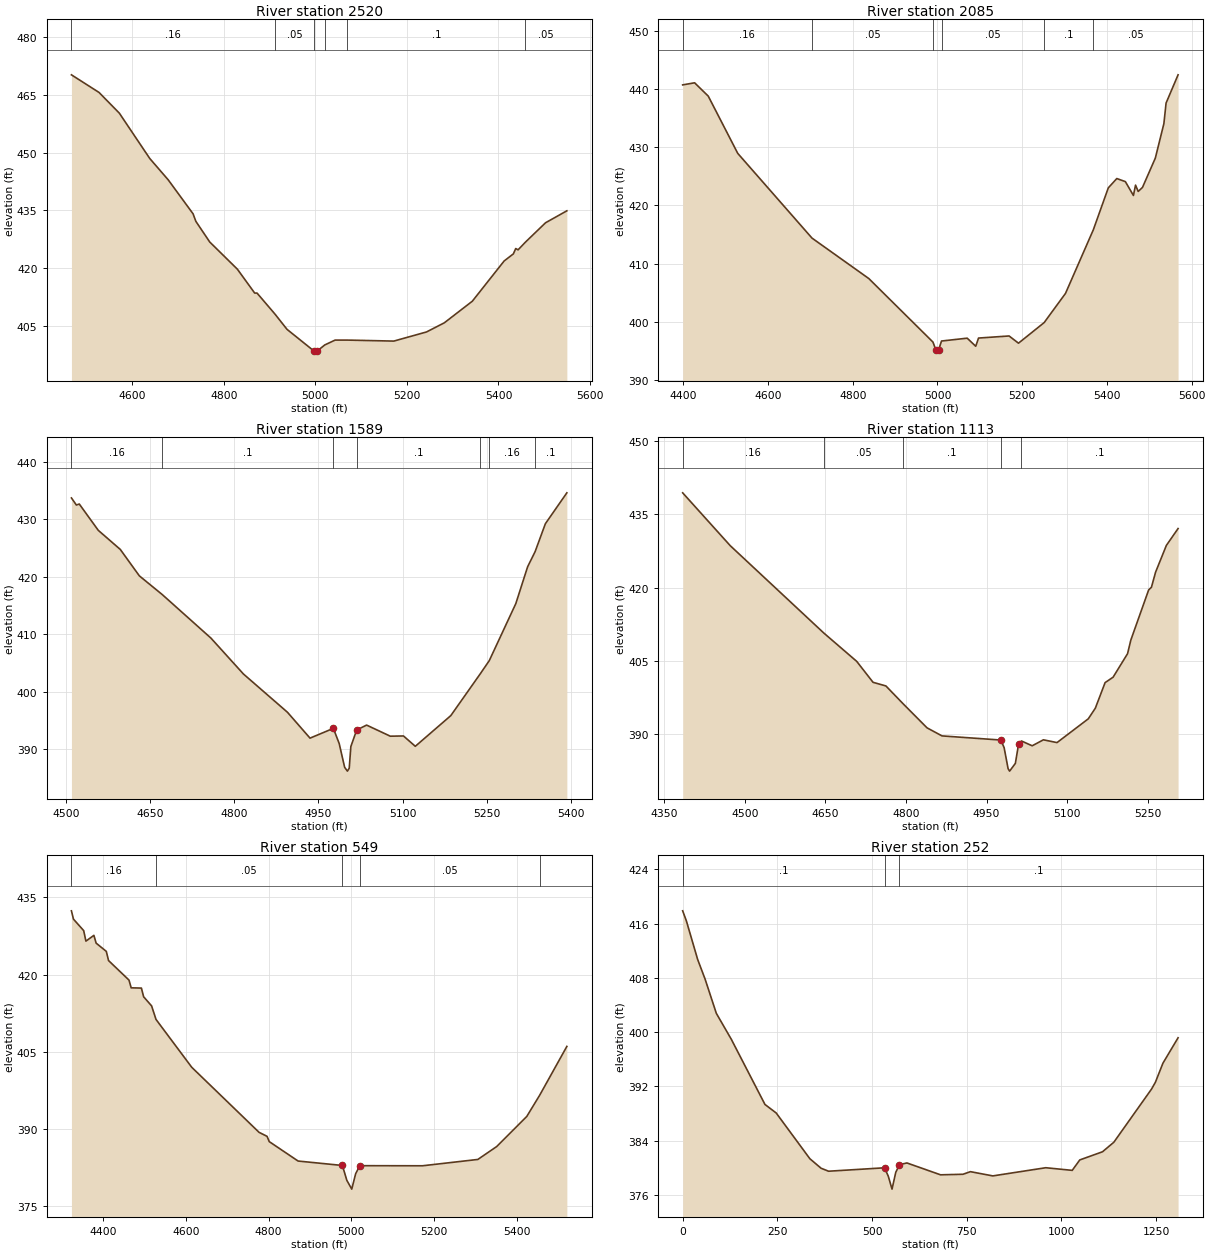
Type RM Length L Ch R = 1 ,2520    ,435,435,435
BEGIN DESCRIPTION:
UNT0347 IN CEDR CR 6.0
END DESCRIPTION:
XS GIS Cut Line= 3
      3598342.27     10414183.78      3598742.29     10414233.78
      3599418.41     10414165.43
#Sta/Elev= 30
  4466.8  470.28  4527.1   465.7  4571.5  460.31    4638  448.52  4678.3  442.97
  4732.7  434.12  4738.7  432.18    4769  426.81  4829.4  419.74  4867.3  413.52
  4872.4  413.52  4911.3   408.1    4938  404.08  4997.4   398.4  5000.2   397.9
  5003.4   398.4  5020.5  400.03    5043  401.29  5070.1  401.29  5171.3  401.03
  5242.9  403.41  5281.8  405.79  5342.9   411.4  5412.5  421.87  5432.6  423.71
  5437.8   425.1  5442.9  424.76  5459.1  426.78    5503  431.81  5549.5  434.91
#Mann= 6 ,-1 , 0
  4466.8     .16       0  4911.3     .05       0  4997.4    .035       0
  5020.5     .05       0  5070.1      .1       0  5459.1     .05       0
Bank Sta=4997.4,5003.4
XS Rating Curve= 0 ,0
Exp/Cntr=0.3,0.1

Type RM Length L Ch R = 1 ,2085    ,496,496,496
BEGIN DESCRIPTION:
UNT0347 IN CEDR CR 5.0
END DESCRIPTION:
XS GIS Cut Line= 3
      3598191.19     10414487.79      3598552.09     10414602.97
      3599335.31     10414710.47
#Sta/Elev= 30
  4398.6  440.71  4426.8  441.07    4459  438.78  4528.6  428.94  4703.8  414.38
    4838  407.42  4989.4   396.5  4996.5   395.1  4999.3   394.6  5002.5   395.1
  5009.6  396.68  5070.2  397.17  5090.4  395.78    5097  397.19  5169.1  397.55
  5191.3  396.31  5251.9  399.85  5302.3  404.87    5368  415.81  5403.3  423.01
  5423.4  424.61  5443.6  424.08  5462.6   421.7  5467.6  423.48  5473.9  422.39
    5484  423.09  5514.3  428.12  5534.5  434.05  5539.7  437.59    5568  442.44
#Mann= 6 ,-1 , 0
  4398.6     .16       0  4703.8     .05       0  4989.4    .035       0
  5009.6     .05       0  5251.9      .1       0    5368     .05       0
Bank Sta=4996.5,5002.5
XS Rating Curve= 0 ,0
Exp/Cntr=0.3,0.1

Type RM Length L Ch R = 1 ,1589    ,476,476,476
BEGIN DESCRIPTION:
UNT0347 IN CEDR CR 4.0
END DESCRIPTION:
XS GIS Cut Line= 3
      3598252.64     10414933.14      3598799.78     10415087.53
      3599098.43     10415187.08
#Sta/Elev= 30
  4509.7  433.69  4518.5  432.46  4523.7  432.63  4557.6  428.05  4596.8  424.73
  4630.8  420.13  4671.8  416.86  4758.5  409.29  4816.4  403.05  4894.8   396.4
  4935.1  391.89  4976.7  393.59  4987.1  390.95  4996.8  386.82  5001.7  386.15
    5005  386.65  5007.9  390.43  5018.3  393.31    5036  394.16  5078.2  392.23
  5101.7  392.27  5122.8  390.47  5186.1  395.81  5238.8  403.11  5254.7  405.38
    5302   415.3  5323.1  421.72  5336.4  424.34  5354.7   429.2    5393  434.58
#Mann= 7 ,-1 , 0
  4509.7     .16       0  4671.8      .1       0  4976.7    .035       0
  5018.3      .1       0  5238.8      .1       0  5254.7     .16       0
  5336.4      .1       0
Bank Sta=4976.7,5018.3
XS Rating Curve= 0 ,0
Exp/Cntr=0.3,0.1

Type RM Length L Ch R = 1 ,1113    ,564,564,564
BEGIN DESCRIPTION:
UNT0347 IN CEDR CR 3.0
END DESCRIPTION:
XS GIS Cut Line= 3
      3598091.36     10415201.87      3598398.52     10415378.49
      3598942.14     10415541.65
#Sta/Elev= 30
  4384.4  439.37    4473  428.56    4647  410.72  4708.3  404.92  4738.7  400.64
  4762.6   399.9  4794.7  396.25  4839.1  391.34    4867  389.69  4976.6  388.84
  4982.6  387.29    4990  382.99  4992.8  382.49  5003.5  384.07  5009.6  388.07
  5014.9  388.65  5034.8  387.67  5055.7  388.89    5081  388.32  5139.2  393.18
  5152.3  395.35  5170.5  400.58  5185.4  401.69  5212.3   406.5  5218.4  409.28
  5251.5  419.51  5256.7  420.07  5264.5  423.17  5284.5  428.62  5306.3  432.07
#Mann= 5 ,-1 , 0
  4384.4     .16       0    4647     .05       0  4794.7      .1       0
  4976.6    .035       0  5014.9      .1       0
Bank Sta=4976.6,5009.6
XS Rating Curve= 0 ,0
Exp/Cntr=0.3,0.1

Type RM Length L Ch R = 1 ,549     ,297,297,297
BEGIN DESCRIPTION:
UNT0347 IN CEDR CR 1.0
END DESCRIPTION:
XS GIS Cut Line= 3
      3597730.52     10415685.64      3598502.79     10415981.45
      3598858.95     10415879.69
#Sta/Elev= 30
  4323.3  432.36  4328.2  430.75  4352.9  428.52  4358.3  426.48  4377.6   427.6
    4383  426.09  4407.6  424.49    4413  422.71  4462.4  418.92  4467.7  417.42
  4492.4  417.37  4497.8  415.68  4517.1  413.91  4527.7  411.29  4614.1     402
  4776.8  389.38  4796.1   388.6  4801.4  387.58  4871.1  383.81  4978.2  382.95
  4988.9  380.08  5000.8  378.36  5010.3  381.36  5020.4  382.91  5171.7  382.89
  5305.6  384.12  5351.1  386.62  5423.9  392.47  5455.1  396.59  5520.7  406.05
#Mann= 5 ,-1 , 0
  4323.3     .16       0  4527.7     .05       0  4978.2    .035       0
  5020.4     .05       0  5455.1     .16       0
Bank Sta=4978.2,5020.4
XS Rating Curve= 0 ,0
Exp/Cntr=0.3,0.1

Type RM Length L Ch R = 1 ,252     ,0,0,0
XS GIS Cut Line= 4
     3597802.584    10415761.064     3598013.088    10416054.033
     3598421.074    10416240.665     3598855.102    10416032.331
#Sta/Elev= 30
       0417.86929.879579416.373339.51831410.715359.27747407.796488.91621402.7577
128.4345398.9401217.3507389.3288246.9895388.0742335.9057381.3322365.5444379.9302
385.2617379.4919533.1411 379.995542.9996378.7531552.8583376.8524562.7169 379.327
572.5756380.4605592.2928380.7088681.0204378.9607740.1721379.0422759.8894379.4256
819.0411378.8015958.8089380.00611028.693379.6173 1048.66381.1543 1108.56382.3561
 1138.51 383.7561238.344391.61631248.328392.60261268.295395.42091308.228399.1602
#Mann= 3 , 0 , 0
       0      .1       0533.1411     .05       0572.5756      .1       0
Bank Sta=533.1411,572.5756
XS Rating Curve= 0 ,0
Exp/Cntr=0.3,0.1

Chan Stop Cuts=-1
Use User Specified Reach Order=0
Composite Channel Slope=5