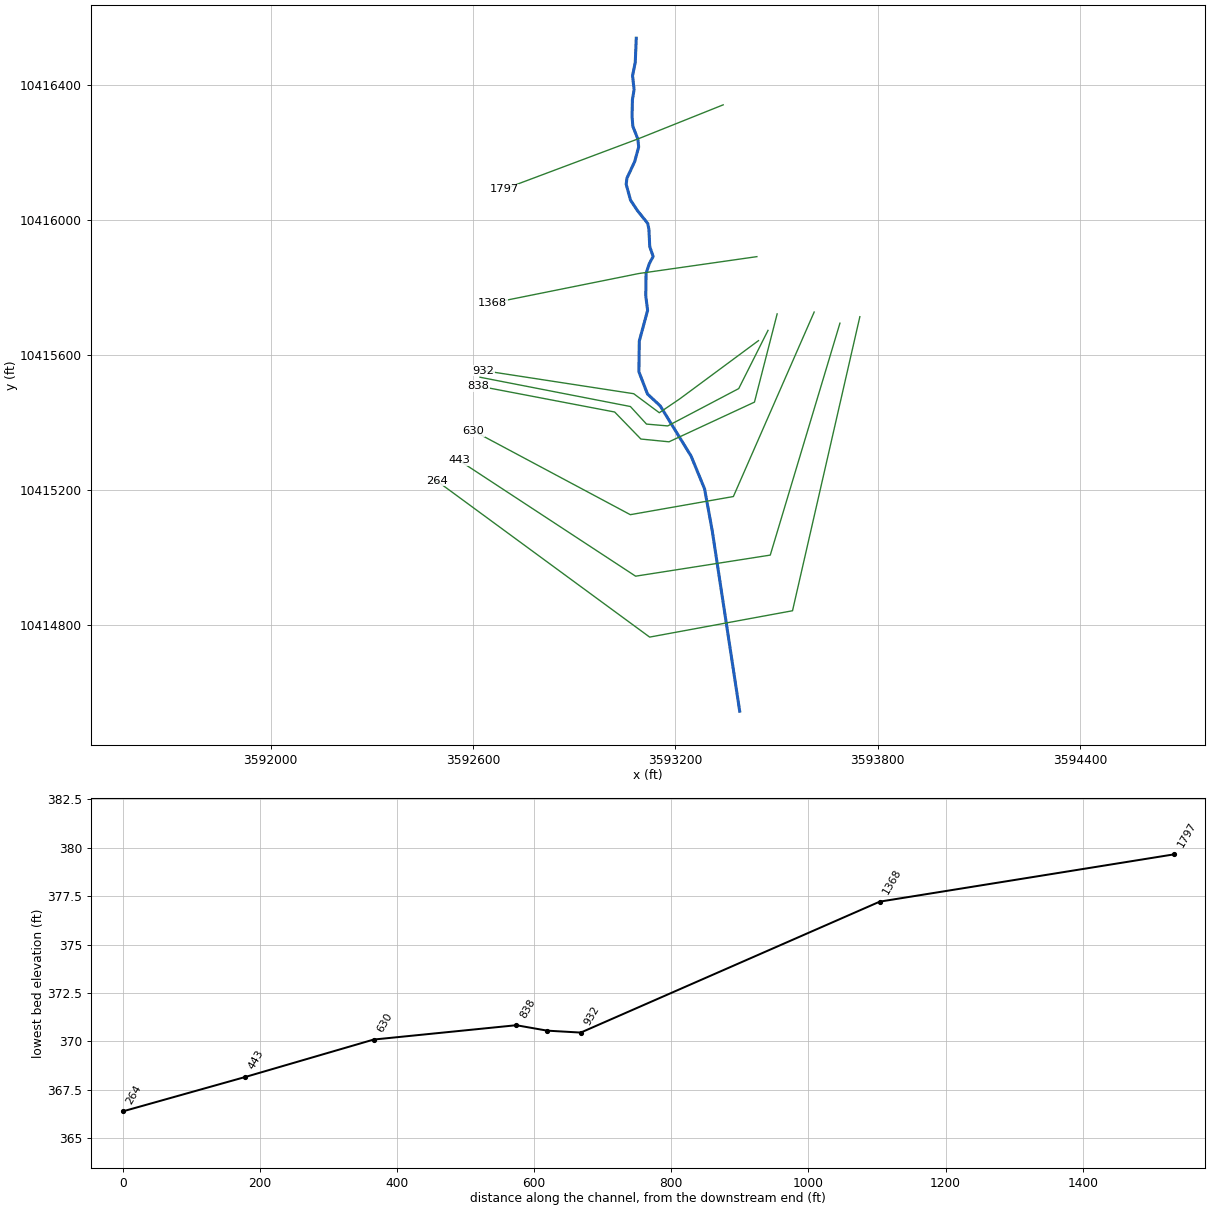
--- UNT0349 IN CEDR CR.prj (project) ---

Proj Title=UNT0349 IN CEDR CR Base Level Engineering
Current Plan=p01
Default Exp/Contr=0.3,0.1
English Units
Geom File=g01
Flow File=f01
Plan File=p01
Y Axis Title=Elevation
X Axis Title(PF)=Main Channel Distance
X Axis Title(XS)=Station
BEGIN DESCRIPTION:
UNT0349 IN CEDR CR
END DESCRIPTION:
DSS Export Rating Curves= 0
DSS Export Rating Curve Sorted= 0
DSS Export Volume Flow Curves= 0
DXF OffsetX= 0
DXF OffsetY= 0
DXF ScaleX= 1
DXF ScaleY= 10

--- UNT0349 IN CEDR CR.p01 (plan) ---

Plan Title=Multiple Run
Short Identifier=Multiple
Geom File=g01
Flow File=f01
Subcritical Flow
K Sum by GR= 0
Std Step Tol= 0.01
Critical Tol= 0.01
Num of Std Step Trials= 20
Max Error Tol= 0.3
Flow Tol Ratio= 0.001
Split Flow NTrial= 30
Split Flow Tol= 0.02
Split Flow Ratio= 0.02
Log Output Level= 0
Friction Slope Method= 1
Unsteady Friction Slope Method= 2
Unsteady Bridges Friction Slope Method= 1
Parabolic Critical Depth
Global Vel Dist=  1 , 1 , 1
Global Log Level= 0
CheckData=True
Encroach Param= -1, 0, 0, 0
BEGIN DESCRIPTION:
Multiple Run
END DESCRIPTION:

--- UNT0349 IN CEDR CR.f01 (steady flow) ---

Flow Title=Multiple
Program Version=4.10
Number of Profiles= 7
Profile Names=10-year,25-year,50-year,1pct_min,100-year,1pct_plu,500-year
River Rch & RM=UNT0349 IN CEDR,Reach-1         ,1797
    1352    1914    2392    2184    2954    3995    4488
Boundary for River Rch & Prof#=UNT0349 IN CEDR,Reach-1         , 1
Up Type= 0
Dn Type= 3
Dn Slope=0.01024
Boundary for River Rch & Prof#=UNT0349 IN CEDR,Reach-1         , 2
Up Type= 0
Dn Type= 3
Dn Slope=0.01024
Boundary for River Rch & Prof#=UNT0349 IN CEDR,Reach-1         , 3
Up Type= 0
Dn Type= 3
Dn Slope=0.01024
Boundary for River Rch & Prof#=UNT0349 IN CEDR,Reach-1         , 4
Up Type= 0
Dn Type= 3
Dn Slope=0.01024
Boundary for River Rch & Prof#=UNT0349 IN CEDR,Reach-1         , 5
Up Type= 0
Dn Type= 3
Dn Slope=0.01024
Boundary for River Rch & Prof#=UNT0349 IN CEDR,Reach-1         , 6
Up Type= 0
Dn Type= 3
Dn Slope=0.01024
Boundary for River Rch & Prof#=UNT0349 IN CEDR,Reach-1         , 7
Up Type= 0
Dn Type= 3
Dn Slope=0.01024
DSS Import GetInterval= 0
DSS Import GetPeak= 0
DSS Import FillOption= 0

--- UNT0349 IN CEDR CR.g01 (geometry) ---

Geom Title=Existing Conditions
Program Version=4.10

River Reach=UNT0349 IN CEDR ,Reach-1
Reach XY= 30
      3593084.37     10416539.07      3593081.28     10416467.03
      3593073.33     10416427.95      3593077.87     10416386.69
      3593072.86     10416356.33       3593071.9     10416306.63
      3593074.28      10416277.5      3593089.04     10416240.18
      3593091.49     10416216.83      3593079.42     10416172.79
       3593056.7     10416124.46      3593054.41     10416106.21
      3593067.31     10416059.22      3593087.13     10416029.04
      3593118.31     10415990.03      3593121.85     10415972.61
      3593124.27     10415921.63      3593134.25     10415892.29
      3593122.95     10415870.52      3593113.38     10415841.76
      3593112.44     10415775.55      3593117.92     10415732.29
      3593093.36     10415641.52      3593092.15     10415550.33
      3593117.63     10415484.42      3593155.39     10415449.26
      3593246.97     10415300.39       3593286.9     10415203.17
      3593309.47      10415079.9        3593391.     10414544.33

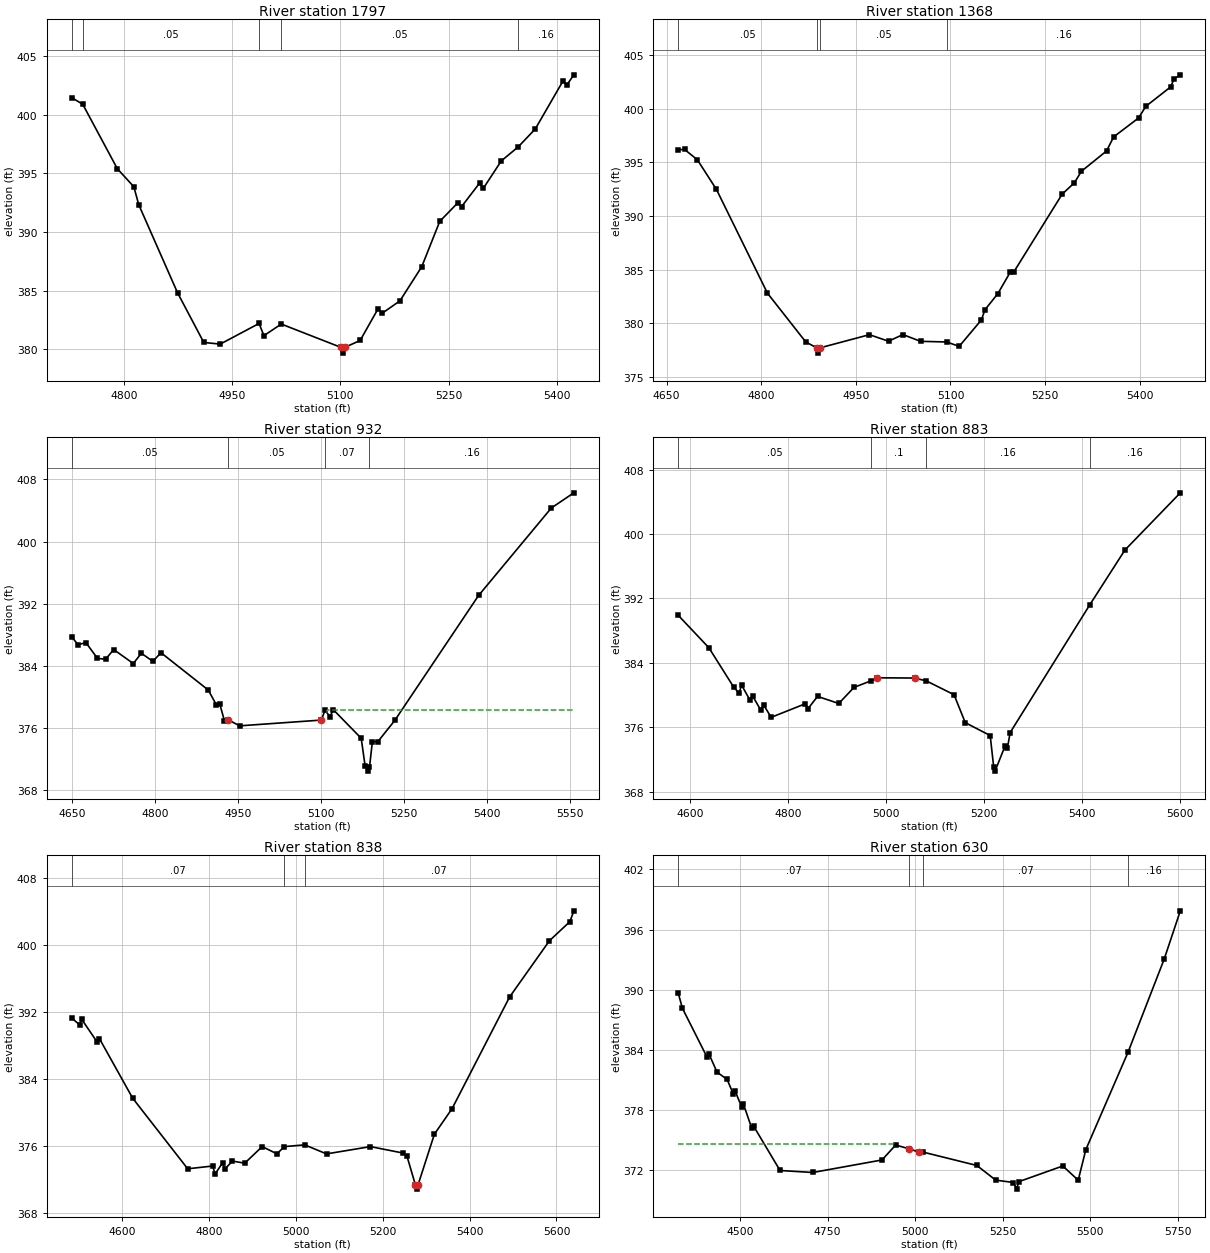
Type RM Length L Ch R = 1 ,1797    ,429,429,429
BEGIN DESCRIPTION:
UNT0349 IN CEDR CR 4.0
END DESCRIPTION:
XS GIS Cut Line= 3
      3593342.07     10416341.63      3593092.11     10416241.64
      3592692.12     10416091.65
#Sta/Elev= 30
  4727.4  401.45  4742.6  400.89  4790.6  395.39  4813.5  393.85  4820.3  392.32
  4874.1  384.81  4910.5  380.57  4933.3  380.43  4987.2  382.19  4993.9  381.15
    5018  382.14  5100.4  380.16  5103.2  379.66  5106.4  380.16  5127.4  380.74
  5152.4  383.46  5157.7  383.05  5182.6  384.12  5212.9  387.04  5237.8   390.9
  5262.7  392.47  5268.1  392.16    5293  394.16  5298.3  393.72  5323.2  396.06
  5346.6  397.25  5370.4  398.79  5408.7  402.87    5414  402.53  5423.8   403.4
#Mann= 5 ,-1 , 0
  4727.4     .16       0  4742.6     .05       0  4987.2     .03       0
    5018     .05       0  5346.6     .16       0
Bank Sta=5100.4,5106.4
XS Rating Curve= 0 ,0
Exp/Cntr=0.3,0.1

Type RM Length L Ch R = 1 ,1368    ,436,436,436
BEGIN DESCRIPTION:
UNT0349 IN CEDR CR 3.0
END DESCRIPTION:
XS GIS Cut Line= 3
      3593442.07     10415891.64      3593092.11     10415841.64
      3592658.52     10415754.38
#Sta/Elev= 30
  4668.5  396.19  4678.6  396.21  4698.8  395.25  4729.1  392.48  4809.9  382.81
  4870.5  378.27  4887.7  377.72  4890.4  377.22  4893.7  377.72  4971.5  378.94
  5001.8  378.33  5024.6  378.95  5052.6  378.32    5094  378.26  5113.8  377.85
  5149.1  380.32  5154.6  381.26    5175  382.76  5194.9  384.78    5200  384.75
    5277  392.04  5296.5  393.11  5307.6  394.18  5347.4  396.07  5358.6  397.38
  5398.2  399.15  5409.6  400.23  5449.1  402.05  5454.2  402.78  5464.3  403.17
#Mann= 4 ,-1 , 0
  4668.5     .05       0  4887.7     .03       0  4893.7     .05       0
    5094     .16       0
Bank Sta=4887.7,4893.7
XS Rating Curve= 0 ,0
Exp/Cntr=0.3,0.1

Type RM Length L Ch R = 1 ,932     ,49,49,49
BEGIN DESCRIPTION:
UNT0349 IN CEDR CR 2.0
END DESCRIPTION:
XS GIS Cut Line= 5
      3593446.73     10415642.68      3593213.45     10415470.16
      3593152.69     10415428.93      3593076.73     10415485.35
      3592631.84     10415553.72
#Sta/Elev= 30
  4649.4  387.75  4660.5  386.74  4675.1  386.99  4695.9  384.97  4710.6  384.86
  4725.2  386.11  4760.7  384.31  4775.3  385.63  4796.1  384.59  4810.8   385.7
  4896.3   380.9    4911  378.99  4917.2  379.08  4925.6  376.94  4931.8  377.08
  4953.2  376.29  5100.9  377.03  5107.4  378.29  5116.7  377.47  5122.4  378.38
    5173  374.69    5180  371.17  5184.8  370.46    5188  370.96  5193.2  374.24
  5203.3  374.27  5233.7  376.98  5385.4  393.07    5517  404.33  5557.7  406.28
#Mann= 4 ,-1 , 0
  4649.4     .05       0  4931.8     .05       0  5107.4     .07       0
    5188     .16       0
#XS Ineff= 2 , 0
                          5110.8          378.36
Permanent Ineff=
       F       F
Bank Sta=4931.8,5100.9
XS Rating Curve= 0 ,0
Exp/Cntr=0.3,0.1

Type RM Length L Ch R = 1 ,883     ,45,45,45
BEGIN DESCRIPTION:
Mapping XS 11e924bf
END DESCRIPTION:
XS GIS Cut Line= 6
      3593474.97      10415673.1      3593388.15     10415500.55
      3593177.64     10415389.87      3593114.71     10415395.29
      3593066.96     10415447.38      3592620.97     10415534.19
#Sta/Elev= 30
  4575.1  389.91  4637.7  385.88  4688.7  380.96  4699.1  380.27  4704.7  381.22
  4721.4   379.4    4727  379.89  4743.7  378.13  4749.3   378.8  4764.9  377.24
  4834.8  378.93  4840.1  378.31  4859.6  379.84    4903  378.96  4934.1  380.96
  4969.4  381.79  4980.6  382.15    5058  382.12    5082  381.76  5138.4  380.05
  5161.3  376.58  5212.2  374.98  5219.4  371.06  5222.1  370.56  5242.3  373.64
  5247.4  373.44    5253  375.35    5416  391.25  5487.3  398.01  5600.5  405.12
#Mann= 4 ,-1 , 0
  4575.1     .05       0  4969.4      .1       0    5082     .16       0
    5416     .16       0
#Block Obstruct= 2 , 0
                         5027.61          381.76
Bank Sta=4980.6,5058
XS Rating Curve= 0 ,0
Exp/Cntr=0.3,0.1

Type RM Length L Ch R = 1 ,838     ,208,208,208
BEGIN DESCRIPTION:
Mapping XS 335e8b3f
END DESCRIPTION:
XS GIS Cut Line= 6
      3593502.09     10415721.95       3593434.8      10415460.4
      3593181.33     10415342.78        3593098.     10415351.02
      3593020.31      10415431.1      3592616.91     10415508.09
#Sta/Elev= 30
  4484.5  391.26  4502.4  390.49  4507.6  391.11  4543.1   388.4  4548.3  388.81
  4624.6  381.71  4751.3  373.27  4808.8   373.6  4814.3  372.64  4831.6  373.99
  4837.1  373.26  4854.3  374.19  4882.6  373.94  4922.7  375.92  4956.6  375.06
    4974  375.92  5020.6  376.13  5070.8  375.05  5171.9  375.92  5247.9  375.14
  5255.9  374.79  5275.4  371.34  5278.1  370.84  5281.4  371.34  5319.1  377.41
  5359.8  380.46  5492.2   393.8  5583.9  400.52  5630.9   402.8    5640  404.09
#Mann= 3 ,-1 , 0
  4484.5     .07       0    4974    .035       0  5020.6     .07       0
Bank Sta=5275.4,5281.4
XS Rating Curve= 0 ,0
Exp/Cntr=0.3,0.1

Type RM Length L Ch R = 1 ,630     ,187,187,187
BEGIN DESCRIPTION:
Mapping XS 51654200
END DESCRIPTION:
XS GIS Cut Line= 4
      3593611.88     10415727.47      3593372.29     10415180.57
      3593066.73     10415126.76      3592601.46     10415375.02
#Sta/Elev= 30
    4323  389.66  4334.9  388.15    4405  383.29  4410.5  383.61  4433.8  381.78
  4462.7  381.04  4480.6  379.58    4486  379.85    4504  378.31  4509.4  378.58
  4532.8   376.2  4538.3  376.39  4613.9  371.96  4707.4  371.76  4905.3  373.01
  4944.2   374.5  4981.2  374.14  5011.6  373.79  5021.8   373.8  5176.3  372.46
  5230.1     371  5280.9  370.76    5290   370.1  5295.9  370.84  5421.9  372.41
  5465.9  370.99  5487.8  374.05  5608.2  383.75  5711.6  393.05  5757.7  397.87
#Mann= 4 ,-1 , 0
    4323     .07       0  4981.2    .035       0  5021.8     .07       0
  5608.2     .16       0
#XS Ineff= 2 , 0
         4938.37  374.58
Permanent Ineff=
       F       F
Bank Sta=4981.2,5011.6
XS Rating Curve= 0 ,0
Exp/Cntr=0.3,0.1

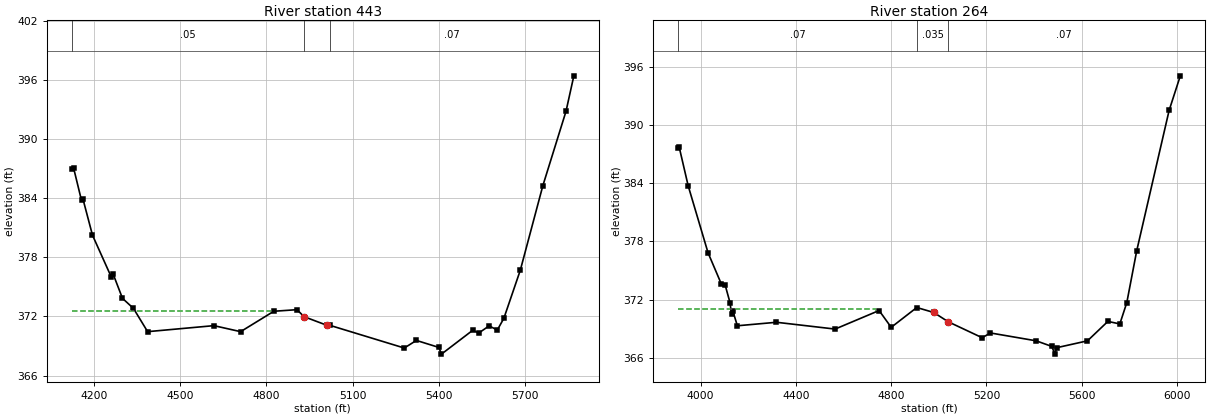
Type RM Length L Ch R = 1 ,443     ,179,179,179
BEGIN DESCRIPTION:
Mapping XS dfc98948
END DESCRIPTION:
XS GIS Cut Line= 4
      3593688.25     10415694.44      3593481.66     10415006.96
      3593082.36     10414944.46      3592559.27     10415287.41
#Sta/Elev= 30
  4122.9  386.96    4129  387.09  4156.8  383.76    4162  383.89    4195  380.24
  4261.1  375.95  4266.3  376.34  4299.4  373.83  4337.6  372.81  4386.9  370.45
  4617.6  371.06  4710.6  370.45  4826.2  372.52  4906.8  372.68  4931.4  371.97
  5012.4  371.08  5022.5  371.08  5280.2  368.79  5322.4  369.56  5400.7  368.85
  5409.6  368.17  5518.4  370.59  5539.4  370.31  5575.6  371.04  5603.9  370.61
  5626.9  371.81  5684.1  376.69  5762.5  385.26  5843.1  392.81  5870.4  396.41
#Mann= 3 ,-1 , 0
  4122.9     .05       0  4931.4    .035       0  5022.5     .07       0
#XS Ineff= 2 , 0
         4825.58  372.56
Permanent Ineff=
       F       F
Bank Sta=4931.4,5012.4
XS Rating Curve= 0 ,0
Exp/Cntr=0.3,0.1

Type RM Length L Ch R = 1 ,264     ,0,0,0
BEGIN DESCRIPTION:
UNT0349 IN CEDR CR 1.0
END DESCRIPTION:
XS GIS Cut Line= 4
       3593747.3     10415713.61      3593547.64     10414842.03
      3593124.02     10414763.91      3592492.67     10415227.02
#Sta/Elev= 30
  3906.1  387.58  3910.1  387.71  3947.9  383.72  4031.2  376.83  4086.9  373.62
    4103  373.51  4123.6  371.68  4129.8  370.51  4134.9  370.87  4154.3  369.31
  4318.5  369.67  4564.7  368.97  4749.4  370.88  4800.2  369.15  4907.6  371.19
  4978.7  370.68  5039.8  369.72  5182.1  368.08  5216.8  368.57    5409  367.76
  5473.8  367.19  5488.2  366.39  5494.6  367.05  5624.3  367.76  5709.9  369.76
  5760.1   369.5  5789.4   371.7  5831.1  377.05    5967  391.49    6014  395.05
#Mann= 3 ,-1 , 0
  3906.1     .07       0  4907.6    .035       0  5039.8     .07       0
#XS Ineff= 2 , 0
         4738.37     371
Permanent Ineff=
       F       F
Bank Sta=4978.7,5039.8
XS Rating Curve= 0 ,0
Exp/Cntr=0.3,0.1

Chan Stop Cuts=-1
Use User Specified Reach Order=0
Composite Channel Slope=5