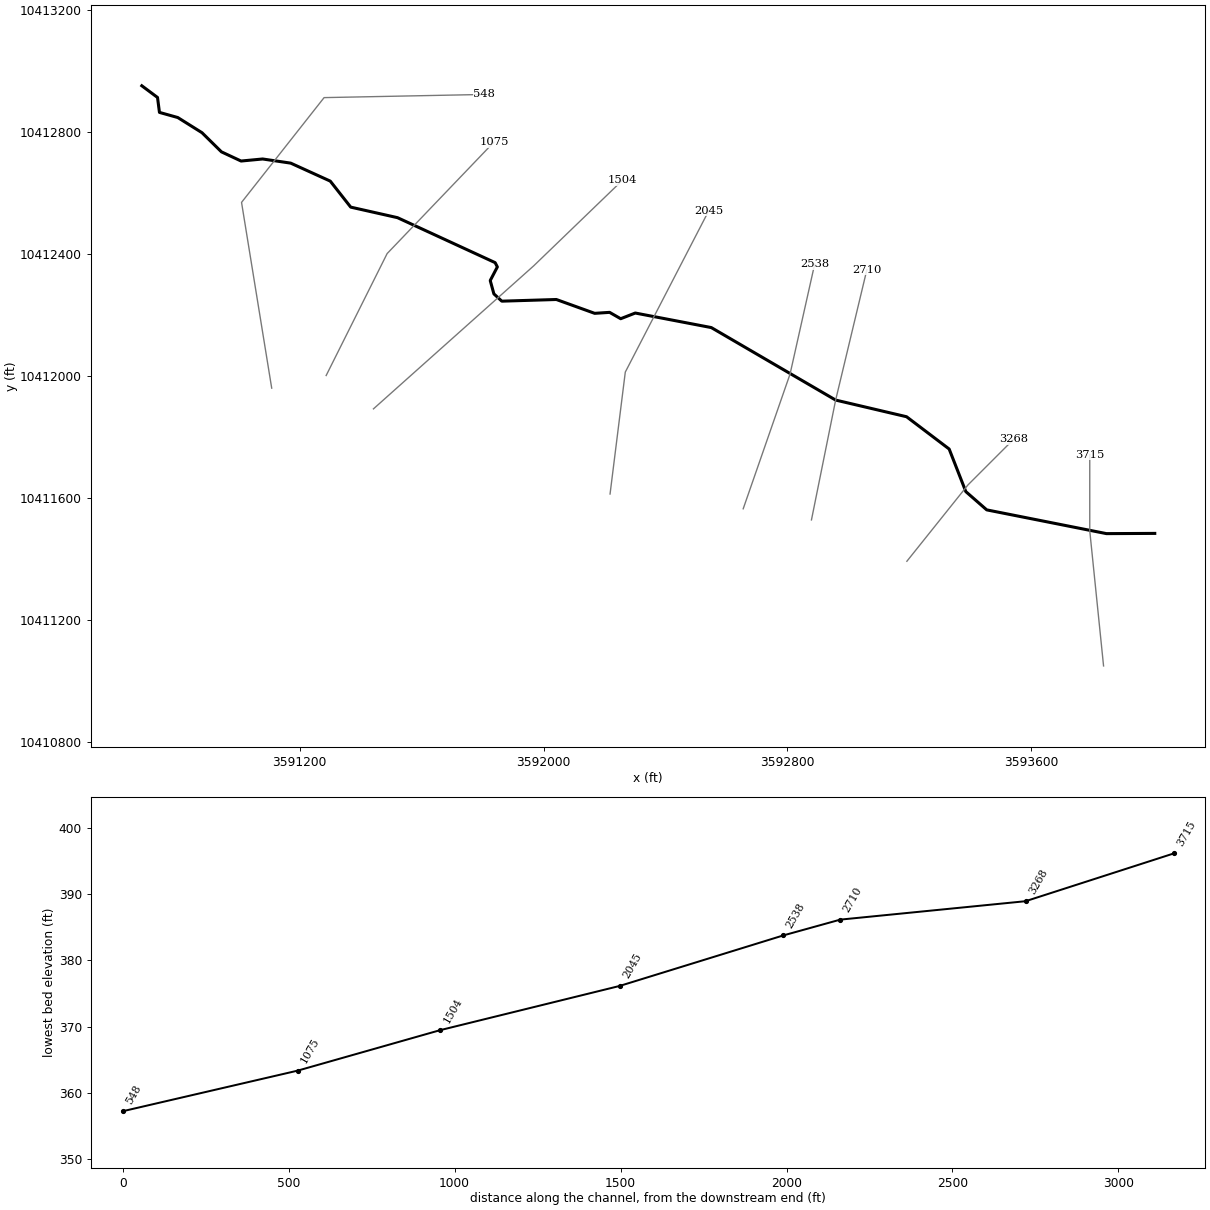
--- UNT0350 IN CEDR CR.prj (project) ---

Proj Title=UNT0350 IN CEDR CR Base Level Engineering
Current Plan=p01
Default Exp/Contr=0.3,0.1
English Units
Geom File=g01
Flow File=f01
Plan File=p01
BEGIN DESCRIPTION:
UNT0350 IN CEDR CR
END DESCRIPTION:

--- UNT0350 IN CEDR CR.p01 (plan) ---

Plan Title=Multiple Run
Short Identifier=Multiple
Geom File=g01
Flow File=f01
Subcritical Flow
K Sum by GR= 0
Std Step Tol= 0.01
Critical Tol= 0.01
Num of Std Step Trials= 20
Max Error Tol= 0.3
Flow Tol Ratio= 0.001
Split Flow NTrial= 30
Split Flow Tol= 0.02
Split Flow Ratio= 0.02
Log Output Level= 0
Friction Slope Method= 1
Unsteady Friction Slope Method= 2
Unsteady Bridges Friction Slope Method= 1
Parabolic Critical Depth
Global Vel Dist=  1 , 1 , 1
Global Log Level= 0
CheckData=True
Encroach Param= -1, 0, 0, 0
BEGIN DESCRIPTION:
Multiple Run
END DESCRIPTION:

--- UNT0350 IN CEDR CR.f01 (steady flow) ---

Flow Title=Multiple
Number of Profiles=7
Profile Names=10-year,25-year,50-year,1pct_min,100-year,1pct_plu,500-year
River Rch & RM= UNT0350 IN CEDR ,Reach-1,3715
    1228    1718    2130    1929    2608    3527    3897
Boundary for River Rch & Prof#=UNT0350 IN CEDR ,Reach-1,1
Up Type=0
Dn Type=3
Dn Slope=0.005
Boundary for River Rch & Prof#=UNT0350 IN CEDR ,Reach-1,2
Up Type=0
Dn Type=3
Dn Slope=0.005
Boundary for River Rch & Prof#=UNT0350 IN CEDR ,Reach-1,3
Up Type=0
Dn Type=3
Dn Slope=0.005
Boundary for River Rch & Prof#=UNT0350 IN CEDR ,Reach-1,4
Up Type=0
Dn Type=3
Dn Slope=0.005
Boundary for River Rch & Prof#=UNT0350 IN CEDR ,Reach-1,5
Up Type=0
Dn Type=3
Dn Slope=0.005
Boundary for River Rch & Prof#=UNT0350 IN CEDR ,Reach-1,6
Up Type=0
Dn Type=3
Dn Slope=0.005
Boundary for River Rch & Prof#=UNT0350 IN CEDR ,Reach-1,7
Up Type=0
Dn Type=3
Dn Slope=0.005

--- UNT0350 IN CEDR CR.g01 (geometry) ---

Geom Title=Existing Conditions

River Reach=UNT0350 IN CEDR ,Reach-1
Reach XY= 30
      3594005.39     10411483.07      3593846.81     10411482.33
      3593454.09     10411560.24      3593385.51     10411620.14
      3593330.83     10411759.89      3593191.07     10411865.80
      3592958.43     10411920.48      3592550.44     10412158.33
      3592301.00     10412206.05      3592253.19     10412187.39
      3592216.81     10412208.24      3592167.89     10412205.04
      3592042.04     10412250.44      3591863.15     10412244.97
      3591837.21     10412268.85      3591825.18     10412312.64
      3591848.55     10412357.25      3591841.32     10412371.35
      3591520.95     10412518.92      3591367.44     10412553.49
      3591300.41     10412638.82      3591170.53     10412697.84
      3591078.58     10412711.43      3591007.72     10412704.72
      3590943.34     10412734.83      3590879.58     10412797.63
      3590800.10     10412847.43      3590739.98     10412864.27
      3590733.61     10412913.26      3590682.11     10412951.64

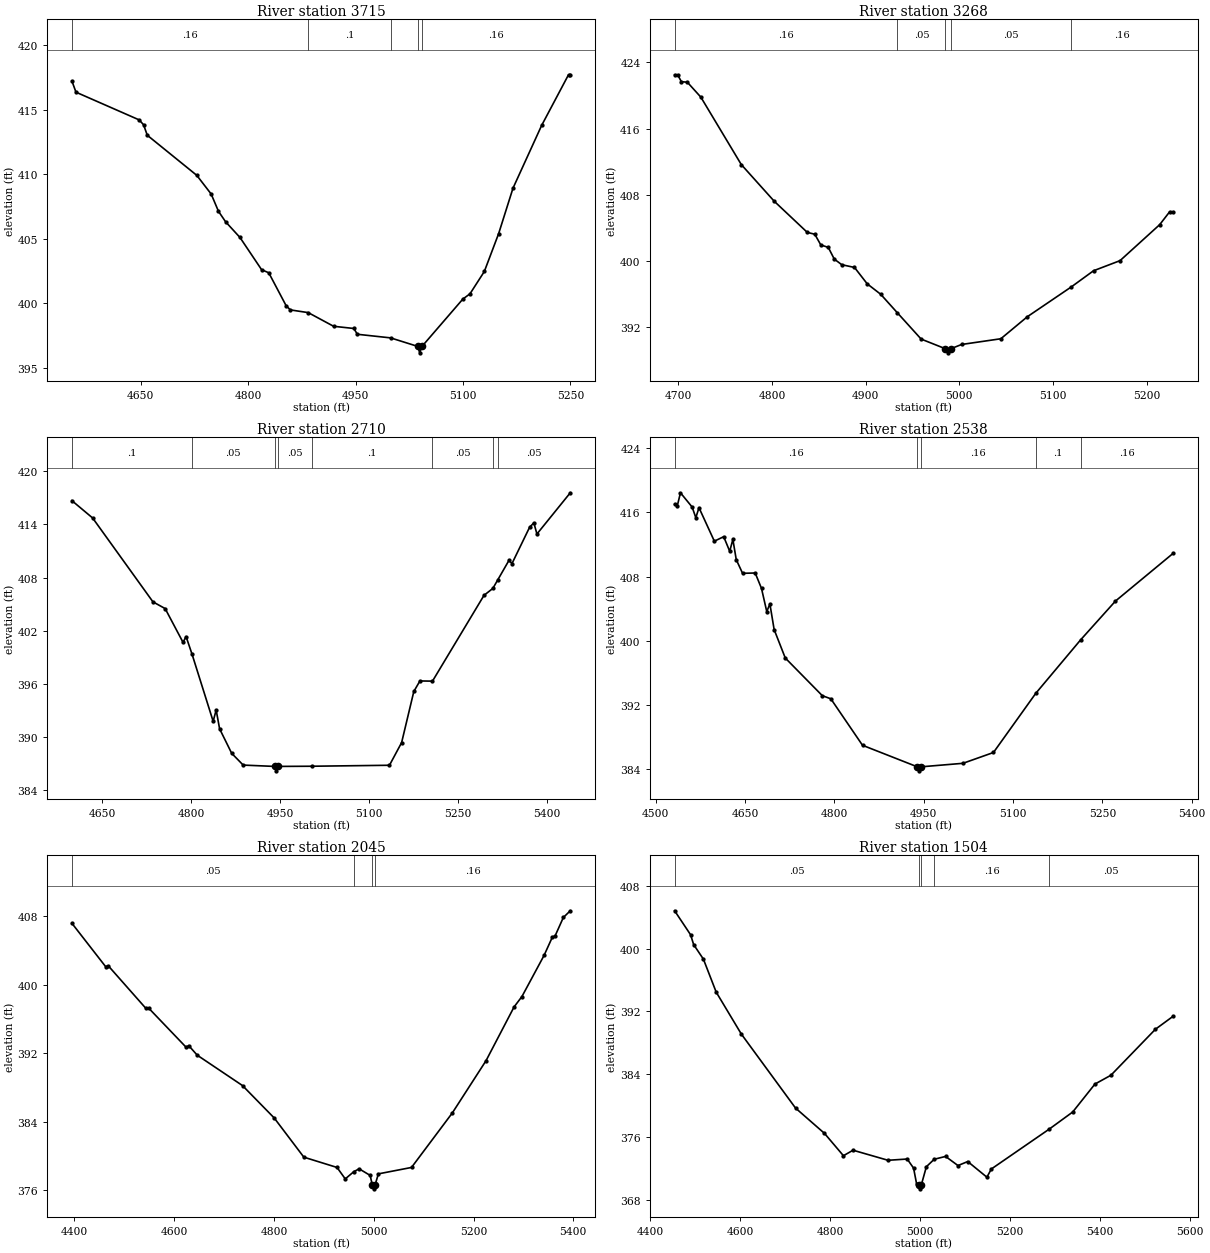
Type RM Length L Ch R = 1,3715,447,447,447
BEGIN DESCRIPTION:
UNT0350 IN CEDR CR 8.0
END DESCRIPTION:
XS GIS Cut Line= 3
      3593837.40     10411048.22      3593792.11     10411491.64
      3593792.11     10411741.61
#Sta/Elev= 30
  4554.1  417.24  4559.8  416.37  4648.0  414.22  4654.2  413.84  4659.3  413.03
  4728.4  409.92  4748.5  408.47  4758.7  407.13  4768.6  406.32  4788.7  405.10
  4818.9  402.60  4828.9  402.36  4853.2  399.80  4859.1  399.48  4884.0  399.27
  4919.4  398.21  4947.6  398.04  4952.6  397.59  4999.0  397.31  5036.8  396.65
  5039.6  396.15  5042.8  396.65  5099.8  400.32  5109.8  400.73  5129.8  402.46
  5149.8  405.40  5169.8  408.92  5209.8  413.79  5247.3  417.72  5249.8  417.72
#Mann=5,-1,0
  4554.1    0.16       0  4884.0     0.1       0  4999.0    0.16       0
  5036.8    0.07       0  5042.8    0.16       0
Bank Sta=5036.8,5042.8
Exp/Cntr=0.3,0.1

Type RM Length L Ch R = 1,3268,558,558,558
BEGIN DESCRIPTION:
UNT0350 IN CEDR CR 7.0
END DESCRIPTION:
XS GIS Cut Line= 3
      3593192.11     10411391.65      3593392.11     10411641.64
      3593542.12     10411791.65
#Sta/Elev= 30
  4695.9  422.50  4699.1  422.50  4703.1  421.67  4709.5  421.60  4723.9  419.80
  4767.1  411.66  4802.3  407.23  4837.6  403.47  4845.6  403.25  4852.0  401.96
  4860.0  401.66  4866.4  400.25  4874.4  399.57  4888.0  399.24  4901.6  397.26
  4916.0  396.00  4933.9  393.75  4959.2  390.59  4985.0  389.43  4987.8  388.93
  4991.0  389.43  5002.4  389.94  5044.3  390.63  5072.6  393.29  5119.7  396.90
  5143.3  398.84  5171.6  400.06  5214.0  404.41  5224.6  405.96  5228.2  405.96
#Mann=5,-1,0
  4695.9    0.16       0  4933.9    0.05       0  4985.0   0.033       0
  4991.0    0.05       0  5119.7    0.16       0
Bank Sta=4985,4991
Exp/Cntr=0.3,0.1

Type RM Length L Ch R = 1,2710,172,172,172
BEGIN DESCRIPTION:
UNT0350 IN CEDR CR 6.0
END DESCRIPTION:
XS GIS Cut Line= 3
      3592879.07     10411527.31      3592958.43     10411920.48
      3593060.94     10412348.48
#Sta/Elev= 30
  4598.9  416.69  4633.9  414.73  4735.7  405.25  4756.3  404.49  4786.5  400.67
  4791.6  401.33  4801.8  399.31  4837.3  391.75  4842.4  393.02  4848.2  390.90
  4868.6  388.13  4888.0  386.80  4940.9  386.65  4943.7  386.15  4946.9  386.65
  5003.7  386.67  5134.9  386.78  5155.4  389.34  5176.0  395.12  5186.3  396.31
  5207.5  396.29  5294.5  405.99  5309.4  406.77  5317.3  407.69  5336.6  409.94
  5341.7  409.58  5371.4  413.68  5378.6  414.18  5383.8  412.92  5440.1  417.58
#Mann=8,-1,0
  4598.9     0.1       0  4801.8    0.05       0  4940.9   0.033       0
  4946.9    0.05       0  5003.7     0.1       0  5207.5    0.05       0
  5309.4    0.16       0  5317.3    0.05       0
Bank Sta=4940.9,4946.9
Exp/Cntr=0.3,0.1

Type RM Length L Ch R = 1,2538,493,493,493
BEGIN DESCRIPTION:
UNT0350 IN CEDR CR 5.0
END DESCRIPTION:
XS GIS Cut Line= 3
      3592655.13     10411563.85      3592808.94     10412006.17
      3592889.48     10412365.86
#Sta/Elev= 30
  4531.7  417.05  4536.2  416.84  4541.5  418.46  4561.1  416.68  4567.3  415.35
  4572.6  416.60  4598.4  412.42  4614.1  412.98  4624.2  411.16  4629.5  412.64
  4635.2  410.11  4645.8  408.41  4667.0  408.45  4677.6  406.52  4686.4  403.64
  4691.7  404.58  4698.8  401.39  4717.5  397.84  4779.7  393.14  4794.0  392.75
  4847.2  386.95  4939.3  384.26  4942.0  383.76  4945.3  384.26  5015.9  384.70
  5067.1  386.05  5138.1  393.43  5213.5  400.11  5272.0  404.95  5368.6  410.89
#Mann=5,-1,0
  4531.7    0.16       0  4939.3    0.07       0  4945.3    0.16       0
  5138.1     0.1       0  5213.5    0.16       0
Bank Sta=4939.3,4945.3
Exp/Cntr=0.3,0.1

Type RM Length L Ch R = 1,2045,541,541,541
BEGIN DESCRIPTION:
UNT0350 IN CEDR CR 4.0
END DESCRIPTION:
XS GIS Cut Line= 3
      3592218.30     10411612.31      3592268.31     10412012.33
      3592542.12     10412541.67
#Sta/Elev= 30
  4394.9  407.17  4462.8  402.08  4467.8  402.20  4543.4  397.21  4548.5  397.27
  4624.0  392.67  4629.1  392.87  4646.2  391.75  4736.9  388.20  4800.5  384.41
  4859.9  379.83  4926.4  378.63  4942.9  377.29  4960.1  378.14  4970.7  378.47
  4992.8  377.70  4996.9  376.63  4999.7  376.13  5002.9  376.63  5009.3  377.88
  5075.7  378.63  5157.5  385.00  5225.1  391.11  5281.4  397.40  5297.1  398.61
  5341.4  403.41  5357.9  405.53  5363.6  405.70  5380.1  407.85  5394.0  408.63
#Mann=4,-1,0
  4394.9    0.05       0  4960.1    0.16       0  4996.9    0.07       0
  5002.9    0.16       0
Bank Sta=4996.9,5002.9
Exp/Cntr=0.3,0.1

Type RM Length L Ch R = 1,1504,429,429,429
BEGIN DESCRIPTION:
UNT0350 IN CEDR CR 3.0
END DESCRIPTION:
XS GIS Cut Line= 3
      3591442.09     10411891.63      3591967.62     10412360.69
      3592258.21     10412640.90
#Sta/Elev= 30
  4454.7  404.80  4490.2  401.75  4497.0  400.50  4518.7  398.65  4547.1  394.46
  4603.1  389.12  4723.5  379.72  4787.9  376.50  4830.0  373.66  4851.4  374.36
  4929.2  373.08  4971.8  373.24  4986.0  372.08  4992.7  370.08  4997.2  369.95
  5000.0  369.45  5003.2  369.95  5014.4  372.26  5031.8  373.21  5057.1  373.57
  5084.7  372.41  5106.4  372.92  5149.0  370.93  5158.8  371.97  5288.0  377.06
  5339.8  379.22  5389.2  382.77  5424.7  383.89  5523.7  389.74  5562.8  391.38
#Mann=5,-1,0
  4454.7    0.05       0  4997.2    0.03       0  5003.2    0.05       0
  5031.8    0.16       0  5288.0    0.05       0
Bank Sta=4997.2,5003.2
Exp/Cntr=0.3,0.1

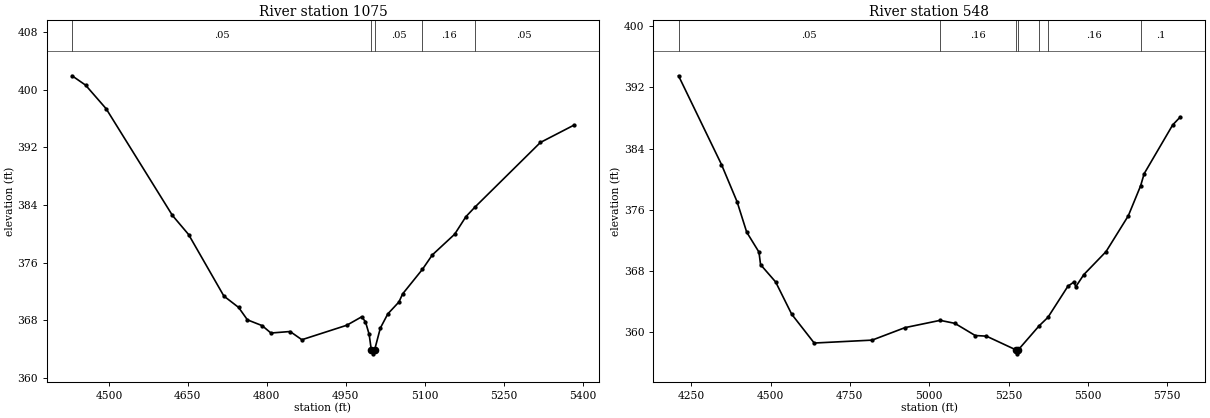
Type RM Length L Ch R = 1,1075,527,527,527
BEGIN DESCRIPTION:
UNT0350 IN CEDR CR 2.0
END DESCRIPTION:
XS GIS Cut Line= 3
      3591286.91     10412001.04      3591486.90     10412401.02
      3591837.13     10412766.65
#Sta/Elev= 30
  4430.0  401.95  4455.7  400.65  4494.8  397.37  4620.7  382.56  4651.4  379.91
  4718.5  371.36  4746.4  369.79  4763.2  368.06  4791.1  367.26  4807.9  366.23
  4844.3  366.44  4866.7  365.30  4952.0  367.31  4980.3  368.48  4987.5  367.80
  4994.5  366.05  4998.7  363.84  5001.4  363.34  5004.7  363.84  5015.8  366.92
  5030.0  368.89  5051.1  370.54  5058.1  371.66  5095.6  375.06  5114.6  377.08
  5157.0  379.95  5178.4  382.39  5195.2  383.69  5319.9  392.69  5383.5  395.09
#Mann=5,-1,0
  4430.0    0.05       0  4998.7    0.03       0  5004.7    0.05       0
  5095.6    0.16       0  5195.2    0.05       0
Bank Sta=4998.7,5004.7
Exp/Cntr=0.3,0.1

Type RM Length L Ch R = 1,548,0,0,0
BEGIN DESCRIPTION:
UNT0350 IN CEDR CR 1.0
END DESCRIPTION:
XS GIS Cut Line= 4
      3591108.24     10411959.63      3591009.28     10412569.02
      3591280.12     10412912.77      3591806.12     10412923.18
#Sta/Elev= 30
  4210.2  393.50  4345.5  381.92  4394.6  377.07  4425.0  373.09  4463.6  370.49
  4468.7  368.85  4516.2  366.59  4566.8  362.38  4637.7  358.62  4820.1  359.00
  4923.7  360.63  5034.5  361.58  5080.9  361.19  5145.0  359.60  5180.3  359.52
  5274.2  357.71  5276.9  357.21  5280.2  357.71  5346.5  360.87  5374.1  361.97
  5437.2  366.04  5456.6  366.60  5461.6  365.95  5487.2  367.55  5557.2  370.55
  5627.3  375.22  5666.2  379.14  5677.3  380.72  5767.3  387.09  5791.3  388.13
#Mann=7,-1,0
  4210.2    0.05       0  5034.5    0.16       0  5274.2    0.03       0
  5280.2    0.16       0  5346.5    0.05       0  5374.1    0.16       0
  5666.2     0.1       0
Bank Sta=5274.2,5280.2
Exp/Cntr=0.3,0.1

Chan Stop Cuts=-1