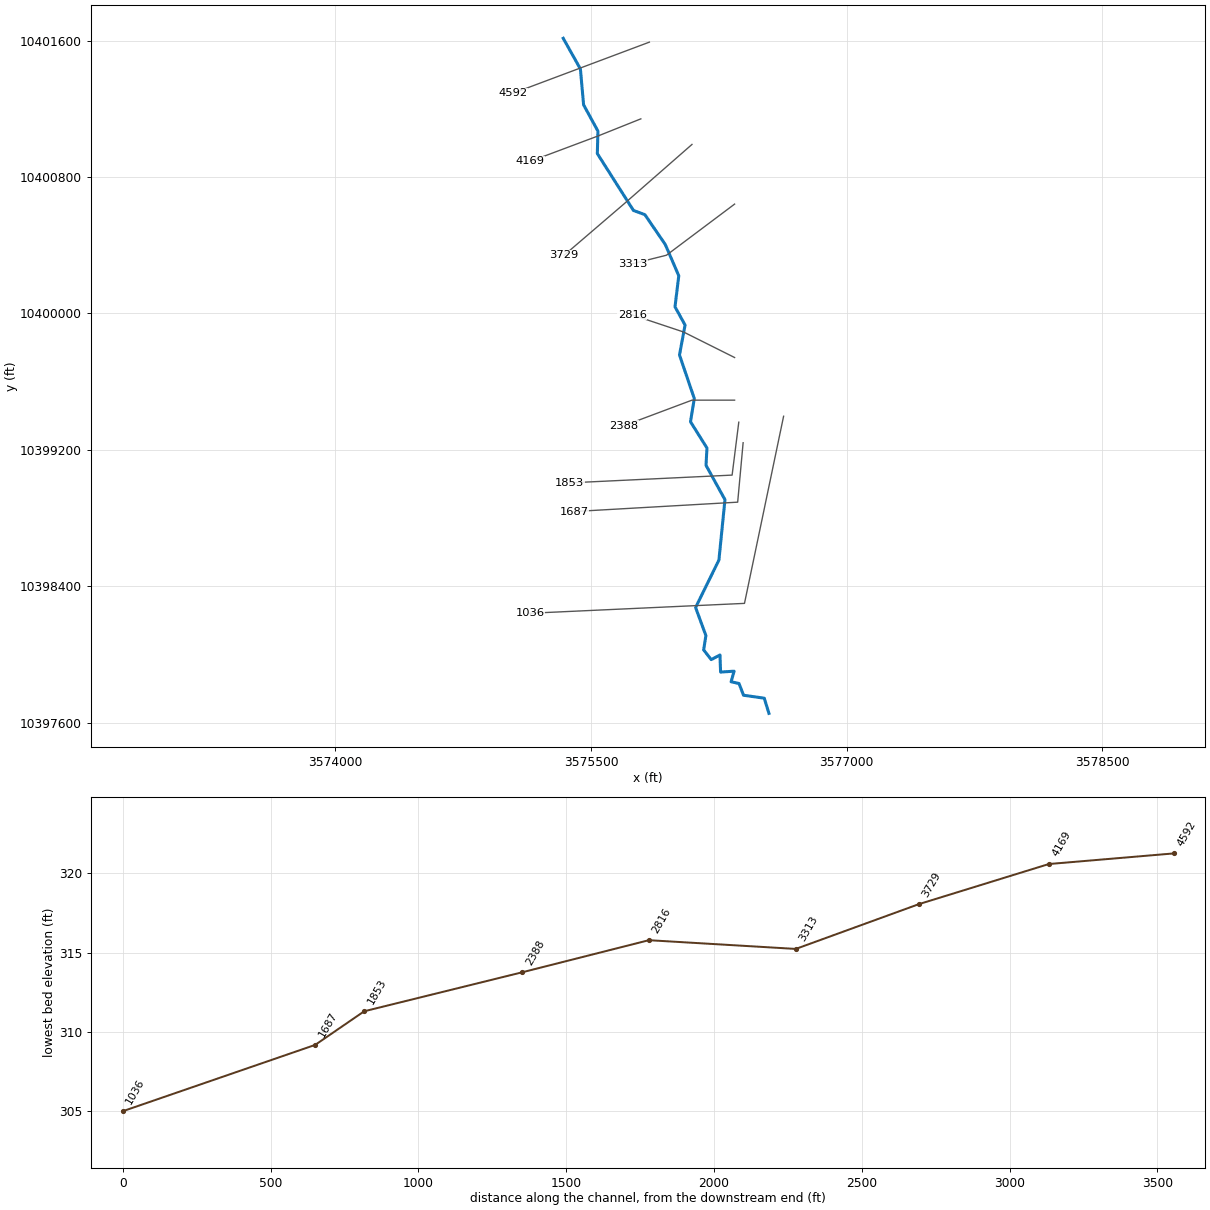
--- UNT0352 IN CEDR CR.prj (project) ---

Proj Title=UNT0352 IN CEDR CR Base Level Engineering
Current Plan=p01
Default Exp/Contr=0.3,0.1
English Units
Geom File=g01
Flow File=f01
Plan File=p01
BEGIN DESCRIPTION:
UNT0352 IN CEDR CR
END DESCRIPTION:

--- UNT0352 IN CEDR CR.p01 (plan) ---

Plan Title=Multiple Run
Short Identifier=Multiple
Geom File=g01
Flow File=f01
Subcritical Flow
K Sum by GR= 0
Std Step Tol= 0.01
Critical Tol= 0.01
Num of Std Step Trials= 20
Max Error Tol= 0.3
Flow Tol Ratio= 0.001
Split Flow NTrial= 30
Split Flow Tol= 0.02
Split Flow Ratio= 0.02
Log Output Level= 0
Friction Slope Method= 1
Unsteady Friction Slope Method= 2
Unsteady Bridges Friction Slope Method= 1
Parabolic Critical Depth
Global Vel Dist=  1 , 1 , 1
Global Log Level= 0
CheckData=True
Encroach Param= -1, 0, 0, 0
BEGIN DESCRIPTION:
Multiple Run
END DESCRIPTION:

--- UNT0352 IN CEDR CR.f01 (steady flow) ---

Flow Title=Multiple
Number of Profiles=7
Profile Names=10-year,25-year,50-year,1pct_min,100-year,1pct_plu,500-year
River Rch & RM= UNT0352 IN CEDR ,Reach-1,4592
    1276    1785    2212    2001    2706    3660    4037
Boundary for River Rch & Prof#=UNT0352 IN CEDR ,Reach-1,1
Up Type=0
Dn Type=3
Dn Slope=0.005
Boundary for River Rch & Prof#=UNT0352 IN CEDR ,Reach-1,2
Up Type=0
Dn Type=3
Dn Slope=0.005
Boundary for River Rch & Prof#=UNT0352 IN CEDR ,Reach-1,3
Up Type=0
Dn Type=3
Dn Slope=0.005
Boundary for River Rch & Prof#=UNT0352 IN CEDR ,Reach-1,4
Up Type=0
Dn Type=3
Dn Slope=0.005
Boundary for River Rch & Prof#=UNT0352 IN CEDR ,Reach-1,5
Up Type=0
Dn Type=3
Dn Slope=0.005
Boundary for River Rch & Prof#=UNT0352 IN CEDR ,Reach-1,6
Up Type=0
Dn Type=3
Dn Slope=0.005
Boundary for River Rch & Prof#=UNT0352 IN CEDR ,Reach-1,7
Up Type=0
Dn Type=3
Dn Slope=0.005

--- UNT0352 IN CEDR CR.g01 (geometry) ---

Geom Title=Existing Conditions

River Reach=UNT0352 IN CEDR ,Reach-1
Reach XY= 30
      3575336.95     10401613.93      3575437.60     10401434.32
      3575456.35     10401223.90      3575540.38     10401069.74
      3575536.90     10400937.79      3575748.71     10400604.46
      3575816.07     10400579.46      3575935.52     10400404.46
      3576014.68     10400221.13      3575992.46     10400039.18
      3576051.49     10399932.24      3576018.85     10399756.54
      3576105.65     10399500.99      3576083.43     10399364.88
      3576179.96     10399210.71      3576174.40     10399109.32
      3576285.52     10398907.93      3576250.10     10398553.77
      3576113.29     10398275.29      3576173.71     10398110.71
      3576160.52     10398026.68      3576204.96     10397969.74
      3576256.35     10397996.82      3576259.82     10397896.82
      3576338.99     10397901.68      3576321.63     10397839.88
      3576368.15     10397829.46      3576394.54     10397760.71
      3576516.07     10397743.35      3576543.52     10397654.38

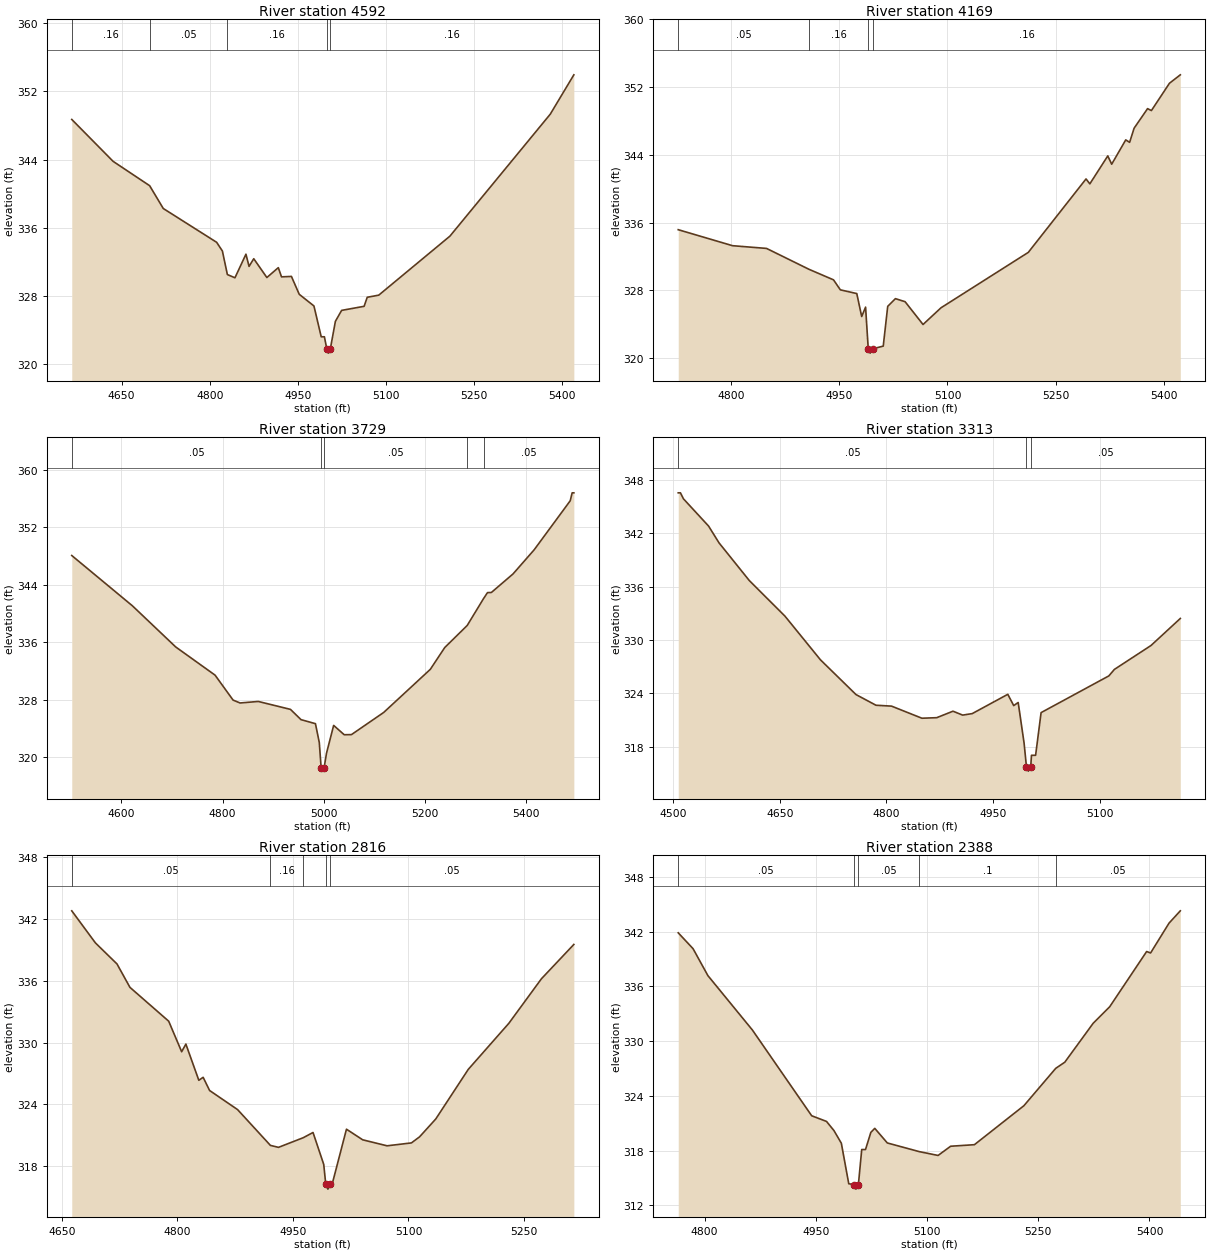
Type RM Length L Ch R = 1,4592,423,423,423
BEGIN DESCRIPTION:
UNT0352 IN CEDR CR 8.0
END DESCRIPTION:
XS GIS Cut Line= 3
      3575842.10     10401591.64      3575442.11     10401441.64
      3575042.10     10401291.64
#Sta/Elev= 30
  4565.3  348.71  4635.6  343.79  4697.8  340.93  4721.0  338.25  4811.8  334.28
  4821.6  333.26  4830.1  330.49  4843.0  330.11  4861.7  332.88  4867.0  331.45
  4875.0  332.35  4897.3  330.14  4916.8  331.30  4922.2  330.22  4939.1  330.27
  4952.4  328.17  4977.4  326.80  4989.8  323.18  4995.2  323.18  4999.3  321.76
  5002.0  321.26  5005.3  321.76  5013.9  324.99  5024.5  326.28  5062.8  326.76
  5068.1  327.82  5087.7  328.07  5208.8  335.00  5379.6  349.33  5419.7  353.95
#Mann=5,-1,0
  4565.3    0.16       0  4697.8    0.05       0  4830.1    0.16       0
  4999.3    0.07       0  5005.3    0.16       0
Bank Sta=4999.3,5005.3
Exp/Cntr=0.3,0.1

Type RM Length L Ch R = 1,4169,440,440,440
BEGIN DESCRIPTION:
UNT0352 IN CEDR CR 7.0
END DESCRIPTION:
XS GIS Cut Line= 3
      3575792.13     10401141.65      3575542.11     10401041.64
      3575142.09     10400891.64
#Sta/Elev= 30
  4726.5  335.16  4801.9  333.27  4849.0  332.95  4908.0  330.48  4941.9  329.24
  4951.4  328.06  4974.2  327.62  4981.0  324.91  4986.4  326.02  4990.1  321.09
  4992.8  320.59  4996.1  321.09  5010.9  321.42  5017.1  326.11  5027.8  327.02
  5041.2  326.66  5066.1  323.97  5091.0  325.94  5212.1  332.48  5292.2  341.15
  5297.5  340.57  5322.4  343.87  5327.8  342.89  5347.3  345.76  5352.7  345.47
  5358.9  347.14  5377.6  349.45  5382.9  349.22  5407.9  352.44  5423.0  353.44
#Mann=4,-1,0
  4726.5    0.05       0  4908.0    0.16       0  4990.1    0.07       0
  4996.1    0.16       0
Bank Sta=4990.1,4996.1
Exp/Cntr=0.3,0.1

Type RM Length L Ch R = 1,3729,416,416,416
BEGIN DESCRIPTION:
UNT0352 IN CEDR CR 6.0
END DESCRIPTION:
XS GIS Cut Line= 3
      3576092.10     10400991.64      3575692.11     10400641.64
      3575342.09     10400341.63
#Sta/Elev= 30
  4501.8  348.05  4621.9  341.04  4707.3  335.33  4785.1  331.41  4820.7  327.94
  4834.5  327.54  4870.5  327.75  4934.1  326.65  4955.0  325.22  4983.5  324.66
  4991.1  322.04  4994.7  318.56  4997.5  318.06  5000.7  318.56  5005.3  320.53
  5019.5  324.42  5040.4  323.12  5054.7  323.14  5118.4  326.22  5210.6  332.22
  5239.1  335.25  5283.5  338.32  5315.9  342.07  5323.6  342.89  5331.3  342.91
  5374.1  345.49  5415.8  348.84  5487.1  355.66  5491.0  356.77  5494.3  356.77
#Mann=5,-1,0
  4501.8    0.05       0  4994.7    0.03       0  5000.7    0.05       0
  5283.5    0.16       0  5315.9    0.05       0
Bank Sta=4994.7,5000.7
Exp/Cntr=0.3,0.1

Type RM Length L Ch R = 1,3313,497,497,497
BEGIN DESCRIPTION:
UNT0352 IN CEDR CR 5.0
END DESCRIPTION:
XS GIS Cut Line= 3
      3576342.08     10400641.63      3575942.11     10400341.64
      3575742.13     10400291.65
#Sta/Elev= 30
  4507.2  346.54  4510.3  346.54  4514.5  345.87  4549.9  342.80  4564.5  340.92
  4607.2  336.67  4657.2  332.68  4707.2  327.76  4757.2  323.85  4785.3  322.65
  4807.2  322.55  4849.9  321.19  4870.7  321.25  4893.6  321.98  4907.2  321.54
  4920.7  321.71  4970.7  323.88  4979.0  322.61  4985.3  322.96  4993.6  318.39
  4996.9  315.74  4999.6  315.24  5002.9  315.74  5004.0  317.02  5009.8  317.02
  5017.5  321.82  5112.8  325.95  5120.6  326.68  5172.1  329.37  5213.3  332.41
#Mann=3,-1,0
  4507.2    0.05       0  4996.9    0.03       0  5002.9    0.05       0
Bank Sta=4996.9,5002.9
Exp/Cntr=0.3,0.1

Type RM Length L Ch R = 1,2816,428,428,428
BEGIN DESCRIPTION:
UNT0352 IN CEDR CR 4.0
END DESCRIPTION:
XS GIS Cut Line= 3
      3576342.11     10399741.64      3576042.11     10399891.64
      3575742.14     10399991.63
#Sta/Elev= 30
  4663.0  342.77  4693.7  339.66  4721.7  337.62  4738.5  335.35  4788.8  332.07
  4805.6  329.11  4811.1  329.85  4827.9  326.34  4833.5  326.63  4841.9  325.35
  4878.2  323.50  4920.8  320.03  4931.3  319.84  4963.6  320.78  4976.1  321.28
  4990.0  318.19  4992.6  316.29  4995.4  315.79  4998.6  316.29  5001.0  316.29
  5019.5  321.60  5040.6  320.57  5072.2  319.99  5103.8  320.27  5114.4  320.86
  5135.4  322.59  5177.6  327.40  5230.3  331.87  5272.5  336.18  5314.6  339.51
#Mann=5,-1,0
  4663.0    0.05       0  4920.8    0.16       0  4963.6    0.05       0
  4992.6    0.03       0  4998.6    0.05       0
Bank Sta=4992.6,4998.6
Exp/Cntr=0.3,0.1

Type RM Length L Ch R = 1,2388,535,535,535
BEGIN DESCRIPTION:
UNT0352 IN CEDR CR 3.0
END DESCRIPTION:
XS GIS Cut Line= 3
      3576342.07     10399491.64      3576092.11     10399491.64
      3575692.07     10399341.63
#Sta/Elev= 30
  4764.4  341.86  4784.4  340.12  4804.4  337.17  4864.4  331.21  4944.4  321.81
  4964.4  321.19  4974.4  320.19  4984.4  318.80  4994.4  314.36  5001.4  314.27
  5004.1  313.77  5007.4  314.27  5011.9  318.11  5017.0  318.11  5024.2  319.99
  5029.5  320.43  5046.4  318.83  5089.5  317.88  5114.9  317.46  5131.8  318.47
  5163.9  318.64  5230.6  322.91  5273.6  327.01  5285.8  327.68  5324.1  331.95
  5346.3  333.75  5396.2  339.81  5401.5  339.65  5426.4  342.92  5441.6  344.27
#Mann=5,-1,0
  4764.4    0.05       0  5001.4   0.035       0  5007.4    0.05       0
  5089.5     0.1       0  5273.6    0.05       0
Bank Sta=5001.4,5007.4
Exp/Cntr=0.3,0.1

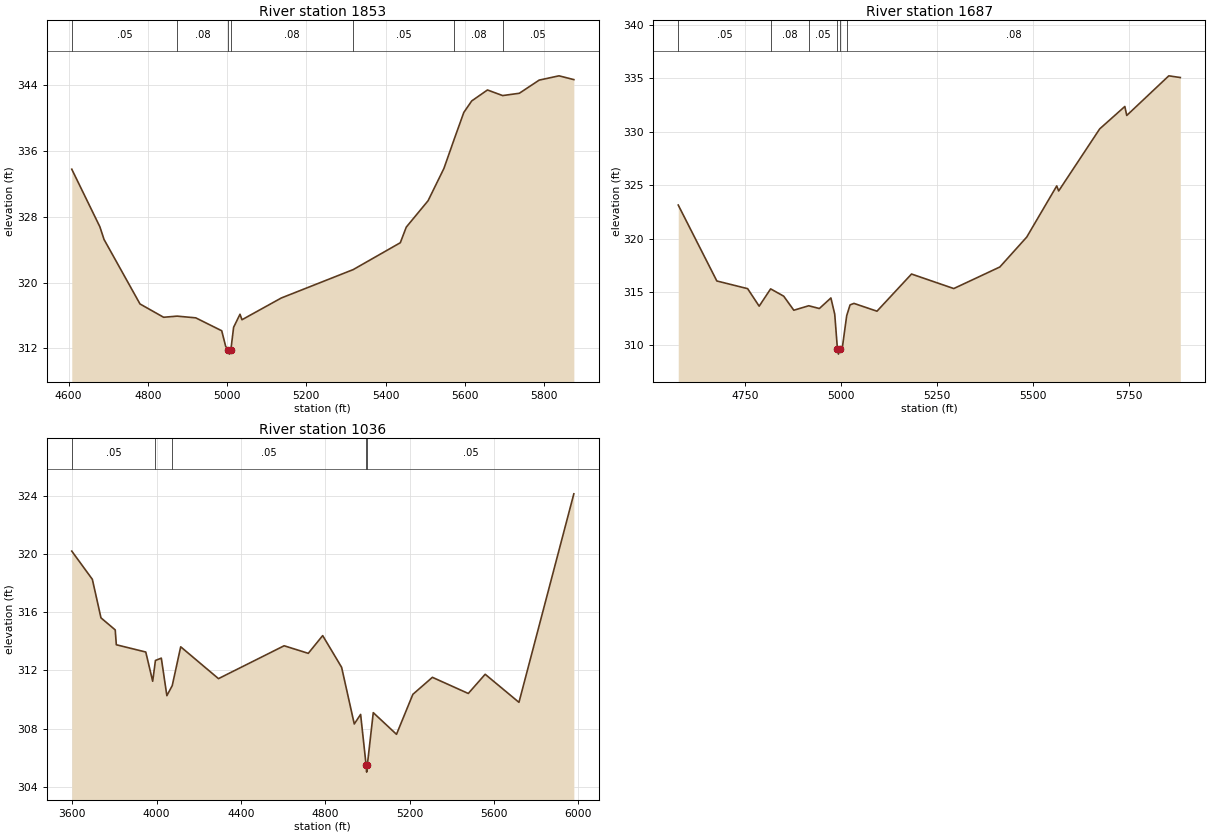
Type RM Length L Ch R = 1,1853,166,166,166
BEGIN DESCRIPTION:
Mapping XS bc763f24
END DESCRIPTION:
XS GIS Cut Line= 3
      3576366.58     10399362.37      3576327.51     10399052.03
      3575374.79     10399006.45
#Sta/Elev= 30
  4608.2  333.79  4679.2  326.78  4689.6  325.25  4780.3  317.41  4839.9  315.79
  4874.0  315.93  4921.0  315.72  4986.5  314.15  4996.5  312.25  5003.5  311.81
  5006.2  311.31  5009.5  311.81  5016.5  314.57  5032.6  316.16  5037.6  315.49
  5136.6  318.13  5318.4  321.59  5437.0  324.85  5452.1  326.75  5507.1  329.96
  5547.1  333.89  5572.4  337.36  5597.2  340.69  5617.2  342.09  5656.9  343.42
  5695.2  342.74  5737.3  343.02  5787.4  344.62  5837.4  345.14  5874.8  344.68
#Mann=7,-1,0
  4608.2    0.05       0  4874.0    0.08       0  5003.5    0.07       0
  5009.5    0.08       0  5318.4    0.05       0  5572.4    0.08       0
  5695.2    0.05       0
Bank Sta=5003.5,5009.5
Exp/Cntr=0.3,0.1

Type RM Length L Ch R = 1,1687,651,651,651
BEGIN DESCRIPTION:
UNT0352 IN CEDR CR 2.0
END DESCRIPTION:
XS GIS Cut Line= 3
      3576392.11     10399241.88      3576360.12     10398893.27
      3575402.16     10398838.39
#Sta/Elev= 30
  4575.2  323.15  4675.9  316.04  4756.2  315.32  4786.3  313.68  4816.2  315.30
  4850.2  314.62  4876.7  313.30  4915.6  313.72  4943.3  313.46  4973.4  314.45
  4983.4  312.93  4990.4  309.69  4993.1  309.19  4996.4  309.69  5003.4  309.84
  5014.6  312.79  5023.4  313.80  5033.5  313.94  5093.6  313.21  5183.7  316.69
  5293.9  315.33  5414.1  317.35  5484.2  320.15  5562.5  324.94  5567.5  324.47
  5674.5  330.28  5740.1  332.38  5745.1  331.54  5854.8  335.25  5884.8  335.09
#Mann=6,-1,0
  4575.2    0.05       0  4816.2    0.08       0  4915.6    0.05       0
  4990.4   0.035       0  4996.4    0.05       0  5014.6    0.08       0
Bank Sta=4990.4,4996.4
Exp/Cntr=0.3,0.1

Type RM Length L Ch R = 1,1036,0,0,0
BEGIN DESCRIPTION:
UNT0352 IN CEDR CR 1.0
END DESCRIPTION:
XS GIS Cut Line= 3
      3576629.54     10399397.21      3576400.03     10398299.57
      3575142.14     10398241.64
#Sta/Elev= 30
  3597.7  320.21  3695.3  318.27  3736.2  315.62  3803.8  314.79  3808.9  313.77
  3948.6  313.27  3981.4  311.26  3994.4  312.69  4022.3  312.85  4048.6  310.27
  4074.1  310.96  4114.2  313.63  4293.3  311.44  4604.6  313.70  4719.1  313.18
  4787.4  314.40  4877.2  312.22  4937.2  308.32  4967.3  308.98  4993.2  305.51
  4995.9  305.01  4999.2  305.51  5027.3  309.10  5137.4  307.61  5215.0  310.36
  5307.6  311.53  5477.8  310.42  5557.9  311.74  5718.1  309.81  5978.3  324.15
#Mann=5,-1,0
  3597.7    0.05       0  3994.4    0.08       0  4074.1    0.05       0
  4993.2   0.035       0  4999.2    0.05       0
Bank Sta=4993.2,4999.2
Exp/Cntr=0.3,0.1

Chan Stop Cuts=-1