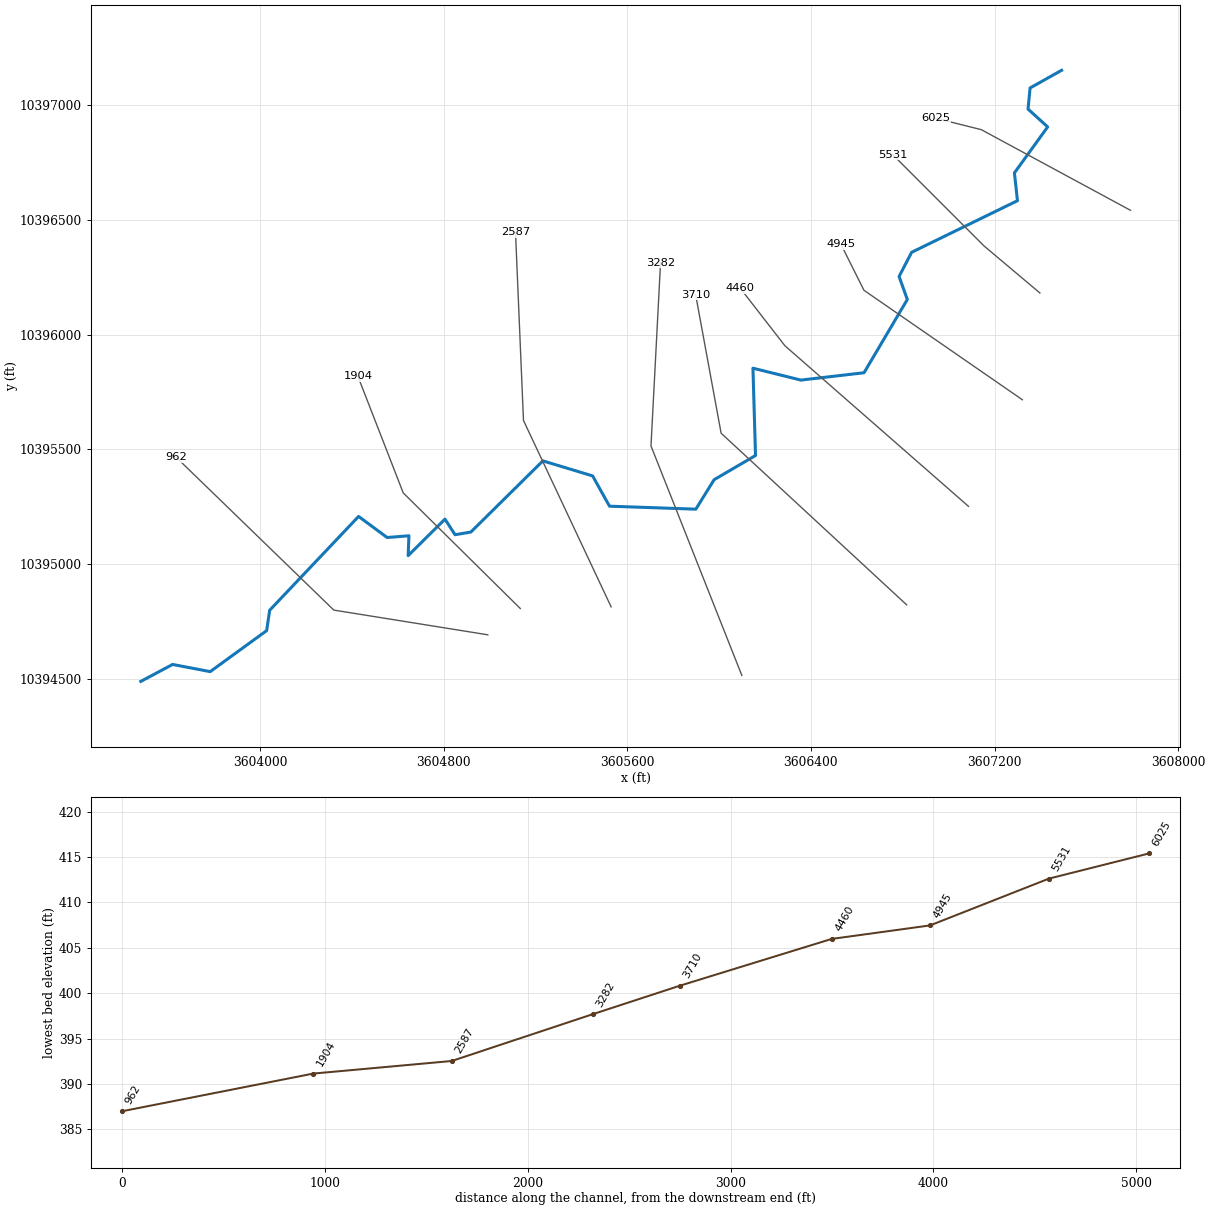
--- UNT0354 IN CEDR CR.prj (project) ---

Proj Title=UNT0354 IN CEDR CR Base Level Engineering
Current Plan=p01
Default Exp/Contr=0.3,0.1
English Units
Geom File=g01
Flow File=f01
Plan File=p01
Y Axis Title=Elevation
X Axis Title(PF)=Main Channel Distance
X Axis Title(XS)=Station
BEGIN DESCRIPTION:
UNT0354 IN CEDR CR
END DESCRIPTION:
DSS Export Rating Curves= 0
DSS Export Rating Curve Sorted= 0
DSS Export Volume Flow Curves= 0
DXF OffsetX= 0
DXF OffsetY= 0
DXF ScaleX= 1
DXF ScaleY= 10

--- UNT0354 IN CEDR CR.p01 (plan) ---

Plan Title=Multiple Run
Short Identifier=Multiple
Geom File=g01
Flow File=f01
Subcritical Flow
K Sum by GR= 0
Std Step Tol= 0.01
Critical Tol= 0.01
Num of Std Step Trials= 20
Max Error Tol= 0.3
Flow Tol Ratio= 0.001
Split Flow NTrial= 30
Split Flow Tol= 0.02
Split Flow Ratio= 0.02
Log Output Level= 0
Friction Slope Method= 1
Unsteady Friction Slope Method= 2
Unsteady Bridges Friction Slope Method= 1
Parabolic Critical Depth
Global Vel Dist=  1 , 1 , 1
Global Log Level= 0
CheckData=True
Encroach Param= -1, 0, 0, 0
BEGIN DESCRIPTION:
Multiple Run
END DESCRIPTION:

--- UNT0354 IN CEDR CR.f01 (steady flow) ---

Flow Title=Multiple
Number of Profiles=7
Profile Names=10-year,25-year,50-year,1pct_min,100-year,1pct_plu,500-year
River Rch & RM= UNT0354 IN CEDR ,Reach-1,6025
    1892    2717    3429    3157    4269    5773    6595
Boundary for River Rch & Prof#=UNT0354 IN CEDR ,Reach-1,1
Up Type=0
Dn Type=3
Dn Slope=0.005
Boundary for River Rch & Prof#=UNT0354 IN CEDR ,Reach-1,2
Up Type=0
Dn Type=3
Dn Slope=0.005
Boundary for River Rch & Prof#=UNT0354 IN CEDR ,Reach-1,3
Up Type=0
Dn Type=3
Dn Slope=0.005
Boundary for River Rch & Prof#=UNT0354 IN CEDR ,Reach-1,4
Up Type=0
Dn Type=3
Dn Slope=0.005
Boundary for River Rch & Prof#=UNT0354 IN CEDR ,Reach-1,5
Up Type=0
Dn Type=3
Dn Slope=0.005
Boundary for River Rch & Prof#=UNT0354 IN CEDR ,Reach-1,6
Up Type=0
Dn Type=3
Dn Slope=0.005
Boundary for River Rch & Prof#=UNT0354 IN CEDR ,Reach-1,7
Up Type=0
Dn Type=3
Dn Slope=0.005

--- UNT0354 IN CEDR CR.g01 (geometry) ---

Geom Title=Existing Conditions
Program Version=4.10

River Reach=UNT0354 IN CEDR ,Reach-1
Reach XY= 30
      3607492.11     10397151.64      3607354.83     10397074.62
      3607345.94     10396982.67      3607431.39     10396904.96
      3607286.57      10396704.5      3607299.81     10396583.39
      3606838.75     10396358.55      3606784.06     10396253.22
      3606820.01     10396152.97      3606631.35     10395833.67
      3606356.19     10395801.66      3606147.38     10395853.46
      3606158.58     10395473.01      3605978.06     10395367.43
      3605898.54     10395239.14      3605522.41     10395252.11
      3605448.86     10395384.07      3605232.15     10395449.62
      3604918.22     10395139.31      3604849.48     10395127.82
      3604805.48     10395195.66      3604645.14     10395036.65
      3604648.59     10395123.12      3604553.43     10395115.62
      3604429.22     10395207.54      3604041.75     10394798.51
      3604028.61     10394709.81      3603782.72     10394531.15
      3603618.83      10394562.4      3603480.21     10394488.53

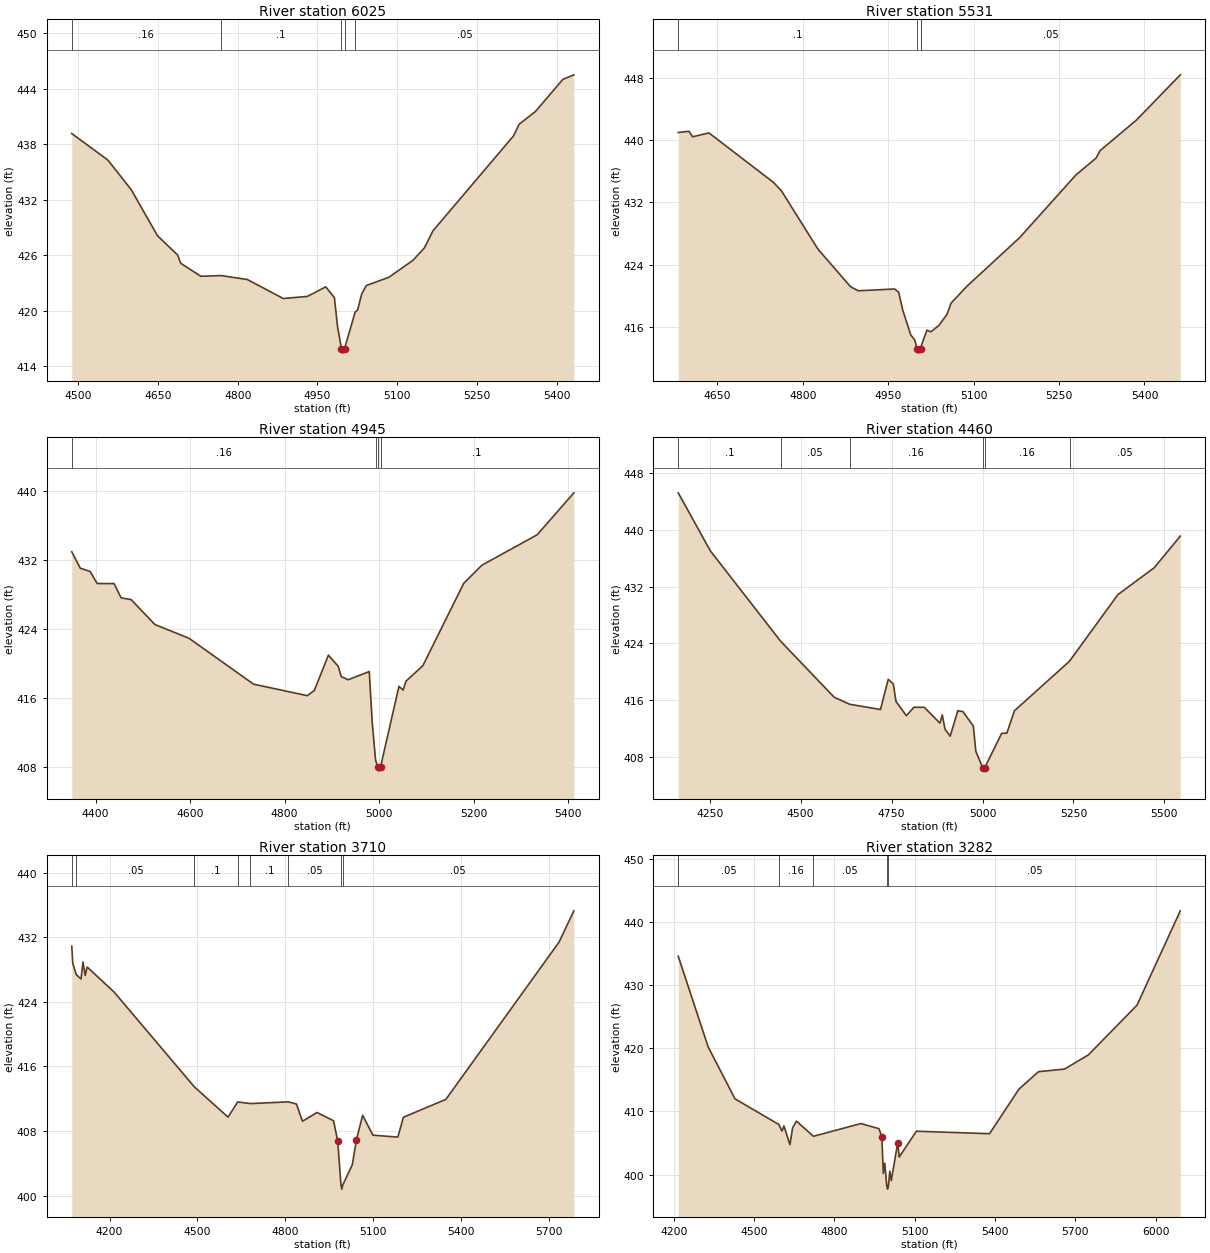
Type RM Length L Ch R = 1 ,6025    ,494,494,494
BEGIN DESCRIPTION:
UNT0354 IN CEDR CR 11.0
END DESCRIPTION:
XS GIS Cut Line= 3
      3607792.09     10396541.65      3607142.11     10396893.03
      3606942.15     10396943.02
#Sta/Elev= 30
  4487.5  439.16  4555.5  436.29  4599.3   433.1  4648.8  428.11  4686.8  426.02
  4692.5  425.13  4730.6  423.72  4768.3   423.8  4818.1  423.37  4885.4  421.32
  4930.8  421.54  4965.6  422.58  4981.8  421.41  4987.7   418.3    4995  415.91
  4997.8  415.41    5001  415.91  5020.8  419.83  5025.6  420.09  5033.1  421.78
  5041.8  422.72  5084.3  423.61  5129.3  425.43  5151.2  426.79  5167.4  428.64
  5318.9   438.9  5329.5  440.16  5360.1  441.54  5411.9  445.02  5432.5  445.51
#Mann= 5 ,-1 , 0
  4487.5     .16       0  4768.3      .1       0    4995     .07       0
    5001      .1       0  5020.8     .05       0
Bank Sta=4995,5001
XS Rating Curve= 0 ,0
Exp/Cntr=0.3,0.1

Type RM Length L Ch R = 1 ,5531    ,586,586,586
BEGIN DESCRIPTION:
UNT0354 IN CEDR CR 10.0
END DESCRIPTION:
XS GIS Cut Line= 3
      3607397.58     10396181.29      3607154.48     10396385.92
      3606755.78     10396784.62
#Sta/Elev= 30
  4581.3  440.97  4600.1  441.13  4606.6  440.42  4635.2  440.92  4748.4  434.57
  4762.7  433.46  4826.4  426.01  4883.6  421.18  4897.3  420.64  4961.4  420.87
  4968.4  420.44  4975.5  418.16  4989.6  414.96  4996.7  414.31  5000.8  413.13
  5003.5  412.63  5006.8  413.13  5008.3  413.62  5017.9  415.58    5025  415.37
  5039.1  416.19  5053.3  417.62  5060.3  419.05  5088.6  421.25  5180.6  427.45
  5279.5  435.51  5314.9  437.68    5322  438.64  5385.6  442.55  5462.9  448.38
#Mann= 4 ,-1 , 0
  4581.3      .1       0  5000.8     .07       0  5006.8      .1       0
  5008.3     .05       0
Bank Sta=5000.8,5006.8
XS Rating Curve= 0 ,0
Exp/Cntr=0.3,0.1

Type RM Length L Ch R = 1 ,4945    ,485,485,485
BEGIN DESCRIPTION:
UNT0354 IN CEDR CR 8.0
END DESCRIPTION:
XS GIS Cut Line= 3
      3607321.25     10395715.97      3606630.99     10396193.03
      3606530.98     10396393.05
#Sta/Elev= 30
  4349.4  432.96  4367.4  431.05  4388.3  430.67  4403.2  429.27    4439  429.26
  4453.9   427.6  4474.8  427.41  4525.5   424.5  4597.2  422.92  4734.4  417.57
  4847.9  416.24  4862.8  416.84  4892.6  420.95  4913.5  419.64  4919.7  418.46
  4934.5  418.09  4979.1  419.04  4985.2  413.22  4992.5  408.73    4997  407.97
  4999.8  407.47    5003  407.97  5041.9  417.32  5050.7  416.89  5056.8  417.92
  5092.6  419.73  5179.1   429.3  5217.2  431.39  5334.6  434.94  5412.1  439.81
#Mann= 4 ,-1 , 0
  4349.4     .16       0  4992.5      .1       0    4997     .07       0
    5003      .1       0
Bank Sta=4997,5003
XS Rating Curve= 0 ,0
Exp/Cntr=0.3,0.1

Type RM Length L Ch R = 1 ,4460    ,750,750,750
BEGIN DESCRIPTION:
UNT0354 IN CEDR CR 7.0
END DESCRIPTION:
XS GIS Cut Line= 3
      3607086.53     10395251.38      3606286.55     10395951.36
      3606092.06     10396202.08
#Sta/Elev= 30
  4163.5  445.27  4251.6  437.09    4445  424.32  4592.3  416.41  4634.8  415.42
  4719.5  414.68  4740.8  418.94  4754.6   418.3  4762.2  415.82  4790.7  413.81
  4811.6     415    4840  414.99  4882.8  412.76  4889.4  413.91    4897  411.89
  4911.2  410.91  4932.1  414.51  4946.3  414.38  4974.8  412.34  4981.5  408.81
  5000.3  406.48    5003  405.98  5006.3  406.48  5052.6   411.3  5066.9  411.35
  5087.8   414.5  5239.2   421.5  5372.4  430.91    5472  434.69  5543.8  439.16
#Mann= 6 ,-1 , 0
  4163.5      .1       0    4445     .05       0  4634.8     .16       0
  5000.3     .07       0  5006.3     .16       0  5239.2     .05       0
Bank Sta=5000.3,5006.3
XS Rating Curve= 0 ,0
Exp/Cntr=0.3,0.1

Type RM Length L Ch R = 1 ,3710    ,428,428,428
BEGIN DESCRIPTION:
UNT0354 IN CEDR CR 6.0
END DESCRIPTION:
XS GIS Cut Line= 3
       3606817.1     10394822.21      3606008.71     10395570.16
       3605897.6      10396174.3
#Sta/Elev= 30
    4071  430.88  4074.3  428.76  4086.6  427.35  4102.6  426.82  4109.4  428.93
  4116.8  427.27  4123.6   428.3  4215.4  425.22  4489.8  413.47    4605  409.72
  4637.9   411.6  4681.1   411.4  4811.3  411.61  4838.6  411.35  4859.5  409.21
  4908.9   410.3  4965.6  409.27  4979.8  406.74  4990.9  401.31  4993.7  400.81
  4996.9  401.31  5029.6  403.82  5043.8  406.93  5064.8  409.94    5100  407.49
  5185.1  407.25  5204.3  409.71  5349.4  411.92  5736.1  431.39  5786.6  435.26
#Mann= 8 ,-1 , 0
    4071      .1       0  4086.6     .05       0  4489.8      .1       0
  4637.9     .05       0  4681.1      .1       0  4811.3     .05       0
  4990.9     .03       0  4996.9     .05       0
Bank Sta=4979.8,5043.8
XS Rating Curve= 0 ,0
Exp/Cntr=0.3,0.1

Type RM Length L Ch R = 1 ,3282    ,695,695,695
BEGIN DESCRIPTION:
UNT0354 IN CEDR CR 5.0
END DESCRIPTION:
XS GIS Cut Line= 3
        3606099.     10394514.56      3605703.15     10395514.61
      3605744.82     10396313.18
#Sta/Elev= 30
  4216.5  434.63  4328.3  420.24  4428.5     412  4592.4  407.93    4604  406.88
  4611.3  407.71  4633.7  404.73  4643.6  407.39    4658  408.47  4721.4  406.06
  4898.6  408.08  4966.2  407.27    4977  405.98  4982.4  400.17  4987.8   401.8
  4995.5  398.18  4998.2  397.68  5001.5  398.18  5006.7  400.53  5012.1  399.02
  5036.4  405.05  5041.8  402.77    5106  406.87  5379.2  406.47  5489.3  413.56
  5562.1  416.31  5659.6  416.73  5748.2  418.97  5929.9  426.86  6091.7  441.83
#Mann= 5 ,-1 , 0
  4216.5     .05       0  4592.4     .16       0  4721.4     .05       0
  4995.5     .03       0  5001.5     .05       0
Bank Sta=4977,5036.4
XS Rating Curve= 0 ,0
Exp/Cntr=0.3,0.1

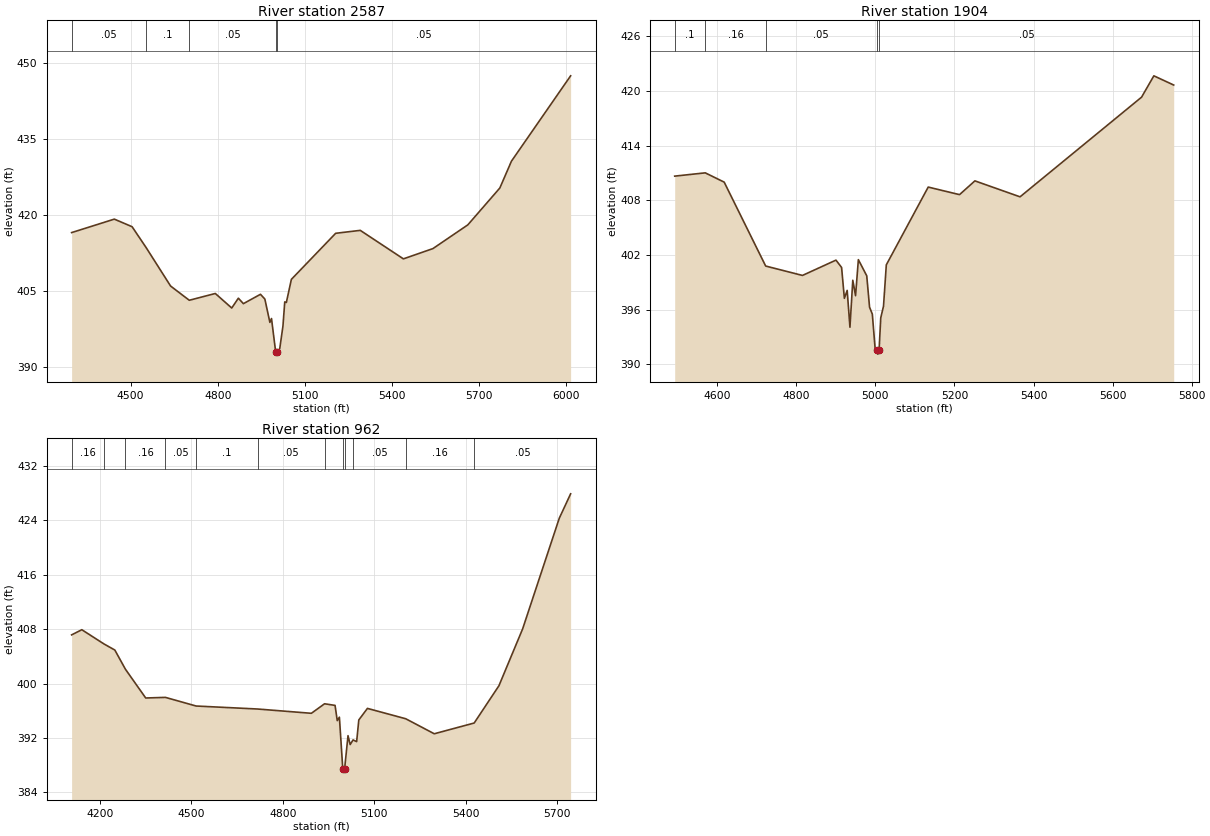
Type RM Length L Ch R = 1 ,2587    ,683,683,683
BEGIN DESCRIPTION:
UNT0354 IN CEDR CR 4.0
END DESCRIPTION:
XS GIS Cut Line= 3
      3605529.55      10394813.2       3605147.6     10395625.72
      3605112.88     10396445.17
#Sta/Elev= 30
    4297  416.53  4444.1  419.19  4505.2  417.69  4553.3  413.59  4637.8  405.97
  4702.1  403.16  4791.7   404.5  4848.3  401.63  4871.1  403.57  4888.4  402.49
  4947.2  404.34  4962.3   403.4  4979.6  398.79  4985.2  399.55  4999.4  393.02
  5002.2  392.52  5005.4  393.02  5013.5  393.58  5024.6  398.06  5030.8  402.84
  5036.3  402.72  5053.6  407.29  5206.1  416.39  5290.8  416.97  5439.3  411.34
    5541  413.37  5661.2  418.06  5771.3  425.34  5811.3  430.64    6015   447.5
#Mann= 5 ,-1 , 0
    4297     .05       0  4553.3      .1       0  4702.1     .05       0
  4999.4     .03       0  5005.4     .05       0
Bank Sta=4999.4,5005.4
XS Rating Curve= 0 ,0
Exp/Cntr=0.3,0.1

Type RM Length L Ch R = 1 ,1904    ,942,942,942
BEGIN DESCRIPTION:
UNT0354 IN CEDR CR 3.0
END DESCRIPTION:
XS GIS Cut Line= 3
      3605133.72     10394806.26      3604623.65      10395310.1
      3604426.06     10395818.39
#Sta/Elev= 30
  4492.3  410.65  4569.6  411.01  4617.5  409.99  4722.4  400.79  4815.5  399.76
  4900.3  401.44  4914.5  400.63  4921.5  397.25  4928.6  398.12  4935.6  394.08
  4942.8  399.23  4949.8  397.54  4956.9  401.49  4978.1  399.72  4985.2  396.28
  4992.2  395.52  4999.3  391.75  5003.4  391.63  5006.1  391.13  5009.4  391.63
  5013.5   395.1  5020.5  396.39  5027.6  400.92  5133.6  409.45  5212.8  408.62
  5251.7  410.13  5365.9  408.38  5673.3  419.31  5704.4  421.65  5754.6  420.64
#Mann= 5 ,-1 , 0
  4492.3      .1       0  4569.6     .16       0  4722.4     .05       0
  5003.4     .03       0  5009.4     .05       0
Bank Sta=5003.4,5009.4
XS Rating Curve= 0 ,0
Exp/Cntr=0.3,0.1

Type RM Length L Ch R = 1 ,962     ,0,0,0
BEGIN DESCRIPTION:
UNT0354 IN CEDR CR 1.0
END DESCRIPTION:
XS GIS Cut Line= 3
       3604992.1     10394691.64      3604321.21     10394799.33
      3603633.73     10395465.98
#Sta/Elev= 30
  4107.4  407.16  4140.9  407.92  4213.8  405.82  4249.2  404.93  4284.1   402.1
  4350.5  397.88  4415.2  397.97  4515.9   396.7  4717.3  396.26    4894  395.63
  4937.3  397.03  4971.7  396.79  4978.9  394.55  4985.9  395.06    4997  387.48
  4999.8  386.98    5003  387.48  5014.2  392.34  5021.3  391.03  5030.8  391.72
  5042.5  391.46  5049.6  394.65  5077.9  396.35  5203.5  394.83  5297.1  392.62
  5428.1   394.2  5509.3  399.68    5587  408.03  5707.2   424.3  5744.5   427.9
#Mann= 12 ,-1 , 0
  4107.4     .16       0  4213.8     .05       0  4284.1     .16       0
  4415.2     .05       0  4515.9      .1       0  4717.3     .05       0
  4937.3      .1       0    4997     .07       0    5003      .1       0
  5030.8     .05       0  5203.5     .16       0  5428.1     .05       0
Bank Sta=4997,5003
XS Rating Curve= 0 ,0
Exp/Cntr=0.3,0.1

Chan Stop Cuts=-1
Use User Specified Reach Order=0
Composite Channel Slope=5