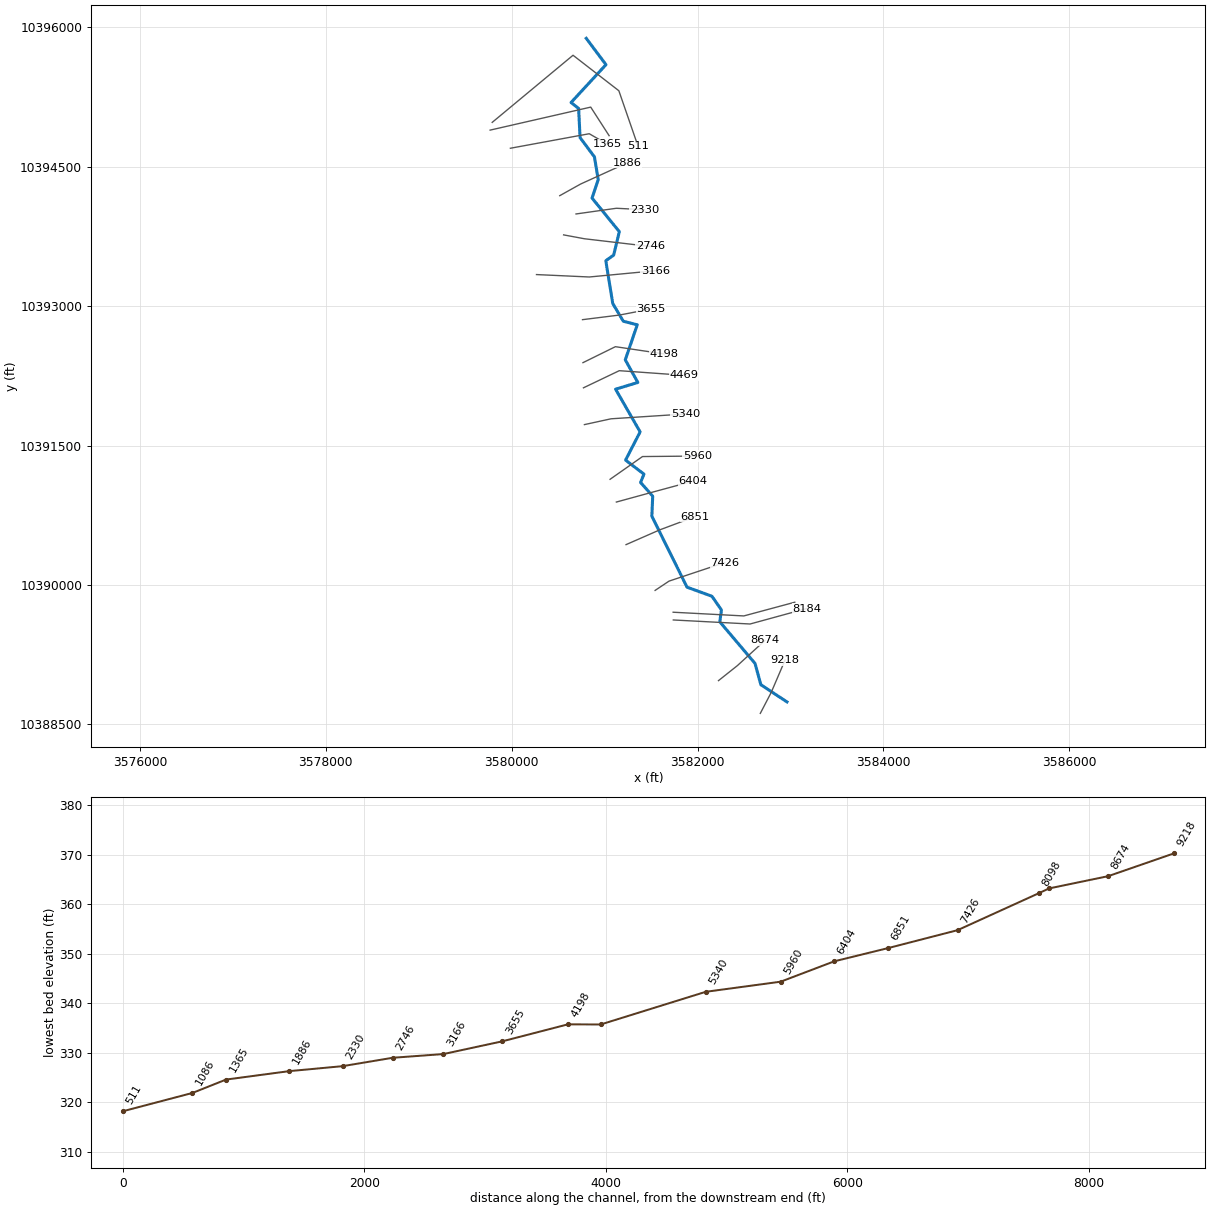
--- UNT0360 IN CEDR CR.prj (project) ---

Proj Title=UNT0360 IN CEDR CR Base Level Engineering
Current Plan=p01
Default Exp/Contr=0.3,0.1
English Units
Geom File=g01
Flow File=f01
Plan File=p01
Y Axis Title=Elevation
X Axis Title(PF)=Main Channel Distance
X Axis Title(XS)=Station
BEGIN DESCRIPTION:
UNT0360 IN CEDR CR
END DESCRIPTION:
DSS Export Rating Curves= 0
DSS Export Rating Curve Sorted= 0
DSS Export Volume Flow Curves= 0
DXF OffsetX= 0
DXF OffsetY= 0
DXF ScaleX= 1
DXF ScaleY= 10

--- UNT0360 IN CEDR CR.p01 (plan) ---

Plan Title=Multiple Run
Short Identifier=Multiple
Geom File=g01
Flow File=f01
Subcritical Flow
K Sum by GR= 0
Std Step Tol= 0.01
Critical Tol= 0.01
Num of Std Step Trials= 20
Max Error Tol= 0.3
Flow Tol Ratio= 0.001
Split Flow NTrial= 30
Split Flow Tol= 0.02
Split Flow Ratio= 0.02
Log Output Level= 0
Friction Slope Method= 1
Unsteady Friction Slope Method= 2
Unsteady Bridges Friction Slope Method= 1
Parabolic Critical Depth
Global Vel Dist=  1 , 1 , 1
Global Log Level= 0
CheckData=True
Encroach Param= -1, 0, 0, 0
BEGIN DESCRIPTION:
Multiple Run
END DESCRIPTION:

--- UNT0360 IN CEDR CR.f01 (steady flow) ---

Flow Title=Multiple
Number of Profiles=7
Profile Names=10-year,25-year,50-year,1pct_min,100-year,1pct_plu,500-year
River Rch & RM= UNT0360 IN CEDR ,Reach-1,9218
    1803    2573    3232    2960    4003    5414    6125
Boundary for River Rch & Prof#=UNT0360 IN CEDR ,Reach-1,1
Up Type=0
Dn Type=3
Dn Slope=0.005
Boundary for River Rch & Prof#=UNT0360 IN CEDR ,Reach-1,2
Up Type=0
Dn Type=3
Dn Slope=0.005
Boundary for River Rch & Prof#=UNT0360 IN CEDR ,Reach-1,3
Up Type=0
Dn Type=3
Dn Slope=0.005
Boundary for River Rch & Prof#=UNT0360 IN CEDR ,Reach-1,4
Up Type=0
Dn Type=3
Dn Slope=0.005
Boundary for River Rch & Prof#=UNT0360 IN CEDR ,Reach-1,5
Up Type=0
Dn Type=3
Dn Slope=0.005
Boundary for River Rch & Prof#=UNT0360 IN CEDR ,Reach-1,6
Up Type=0
Dn Type=3
Dn Slope=0.005
Boundary for River Rch & Prof#=UNT0360 IN CEDR ,Reach-1,7
Up Type=0
Dn Type=3
Dn Slope=0.005

--- UNT0360 IN CEDR CR.g01 (geometry) ---

Geom Title=Existing Conditions
Program Version=4.10

River Reach=UNT0360 IN CEDR ,Reach-1
Reach XY= 30
      3582962.29     10388740.49      3582681.31     10388925.58
      3582618.35     10389154.71      3582239.24     10389602.97
      3582257.09     10389729.95      3582154.63     10389877.73
      3581886.59     10389975.55      3581508.18     10390739.01
      3581517.31     10390954.56       3581386.6     10391102.56
      3581423.23     10391191.79      3581225.39     10391342.86
       3581381.9     10391646.41      3581118.02     10392105.81
      3581357.34     10392178.46      3581222.35     10392421.67
      3581351.13     10392798.83      3581201.08      10392837.3
      3581087.24     10393028.25      3581012.69     10393488.25
      3581097.08     10393548.79      3581158.24     10393800.87
      3580864.71     10394162.88      3580931.13     10394362.13
      3580890.43     10394605.81      3580735.59     10394813.02
       3580720.3     10395126.52      3580638.54     10395190.74
      3581014.41     10395598.21      3580802.11     10395881.64

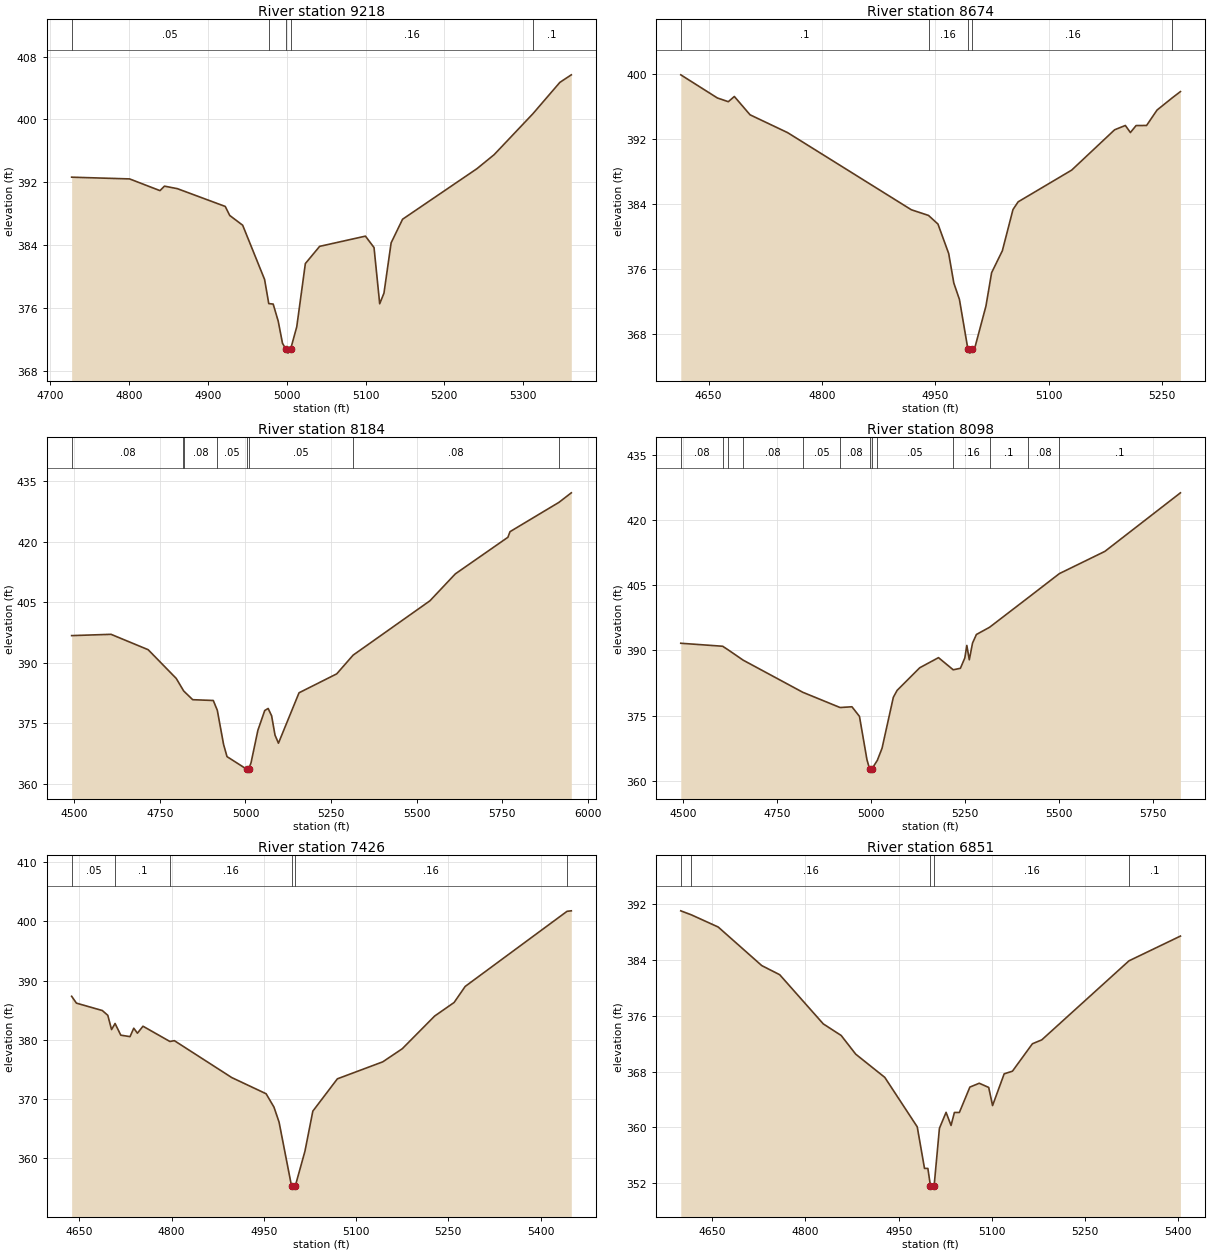
Type RM Length L Ch R = 1 ,9218    ,544,544,544
BEGIN DESCRIPTION:
UNT0360 IN CEDR CR 19.0
END DESCRIPTION:
XS GIS Cut Line= 3
      3582675.37      10388617.3      3582792.11     10388841.64
      3582942.11     10389191.66
#Sta/Elev= 30
  4727.3  392.66  4800.8  392.44  4839.3  390.95    4845  391.52  4861.4   391.2
  4922.1  388.94  4927.8  387.79  4944.2  386.55    4972  379.65  4977.3  376.58
  4982.9  376.52  4989.3  374.34  4994.7  371.54    4999  370.78  5001.7  370.28
    5005  370.78  5012.8  373.63  5023.7  381.67  5041.8  383.86  5099.9  385.16
  5110.8  383.71    5118  376.56  5123.4  377.91  5132.5  384.31    5147  387.31
  5241.3  393.74  5263.1  395.52  5312.2  400.72  5346.5  404.72    5361  405.68
#Mann= 5 ,-1 , 0
  4727.3     .05       0  4977.3     .16       0    4999     .07       0
    5005     .16       0  5312.2      .1       0
Bank Sta=4999,5005
XS Rating Curve= 0 ,0
Exp/Cntr=0.3,0.1

Type RM Length L Ch R = 1 ,8674    ,490,490,490
BEGIN DESCRIPTION:
UNT0360 IN CEDR CR 18.0
END DESCRIPTION:
XS GIS Cut Line= 3
      3582225.24     10388969.65      3582428.36      10389131.1
      3582725.22     10389401.92
#Sta/Elev= 30
  4613.3  399.86  4661.7  397.02  4676.2  396.56  4684.2   397.2    4705  394.95
  4754.7  392.76  4918.4  383.29  4941.2  382.59  4953.7  381.53  4967.9  377.91
  4974.7  374.28  4982.1  372.28  4993.3  366.18    4996  365.68  4999.3  366.18
  5003.1  366.55  5017.2  371.46  5024.7  375.56  5038.9  378.25    5053  383.32
  5059.8  384.26  5130.7  388.16  5187.5  393.11  5201.7  393.64  5208.4  392.77
  5215.9  393.63  5229.8  393.64  5243.6  395.53    5264  397.05  5274.6   397.8
#Mann= 5 ,-1 , 0
  4613.3      .1       0  4941.2     .16       0  4993.3     .07       0
  4999.3     .16       0    5264      .1       0
Bank Sta=4993.3,4999.3
XS Rating Curve= 0 ,0
Exp/Cntr=0.3,0.1

Type RM Length L Ch R = 1 ,8184    ,86,86,86
BEGIN DESCRIPTION:
UNT0360 IN CEDR CR 17.0
END DESCRIPTION:
XS GIS Cut Line= 3
      3581738.96      10389622.5       3582565.4      10389579.1
      3583174.74     10389745.76
#Sta/Elev= 30
  4492.4  396.76  4607.4  397.08  4715.9  393.27  4797.9  386.15  4818.6   383.2
  4819.7  383.04    4846  380.89  4906.1  380.69  4917.8  378.27  4936.2  369.78
  4946.2  366.79  5003.3   363.7    5006   363.2  5009.3   363.7  5016.3  365.26
  5036.3   373.3  5056.3  378.21  5066.3  378.72  5076.4  376.91  5086.4  372.11
  5096.4  370.12  5156.5   382.6  5266.6  387.29  5314.4  391.92  5538.8  405.38
    5613  412.05  5766.5  421.11  5772.7   422.5  5915.6  429.76  5951.7  432.12
#Mann= 8 ,-1 , 0
  4492.4     .08       0  4818.6     .05       0  4819.7     .08       0
  4917.8     .05       0  5003.3     .04       0  5009.3     .05       0
  5314.4     .08       0  5915.6      .1       0
Bank Sta=5003.3,5009.3
XS Rating Curve= 0 ,0
Exp/Cntr=0.3,0.1

Type RM Length L Ch R = 1 ,8098    ,672,672,672
BEGIN DESCRIPTION:
UNT0360 IN CEDR CR 16.0
END DESCRIPTION:
XS GIS Cut Line= 3
      3581737.27     10389705.84      3582497.69     10389665.91
      3583046.32     10389813.48
#Sta/Elev= 30
  4492.9  391.65  4604.4  390.96  4619.2  390.12  4659.1  387.75  4817.5  380.37
  4916.7  376.86  4948.4  377.03  4968.4  374.82  4988.4  364.83  4995.4  362.72
  4998.2  362.22  5001.4  362.72  5015.8  364.68  5028.5  367.49  5058.5   379.2
  5068.5   380.8  5128.6     386  5178.7  388.34  5217.9  385.54    5237  385.89
  5248.8  388.28  5254.1  391.15  5260.7  387.85  5269.3   391.7  5279.6  393.67
  5314.5  395.32  5415.8  402.04  5500.4  407.68  5621.4  412.79  5822.5  426.27
#Mann= 13 ,-1 , 0
  4492.9     .08       0  4604.4     .05       0  4619.2     .16       0
  4659.1     .08       0  4817.5     .05       0  4916.7     .08       0
  4995.4     .07       0  5001.4     .08       0  5015.8     .05       0
  5217.9     .16       0  5314.5      .1       0  5415.8     .08       0
  5500.4      .1       0
Bank Sta=4995.4,5001.4
XS Rating Curve= 0 ,0
Exp/Cntr=0.3,0.1

Type RM Length L Ch R = 1 ,7426    ,575,575,575
BEGIN DESCRIPTION:
UNT0360 IN CEDR CR 15.0
END DESCRIPTION:
XS GIS Cut Line= 3
      3581543.15      10389940.6      3581693.15      10390040.6
      3582292.95     10390240.47
#Sta/Elev= 30
  4637.5  387.35  4645.3  386.19  4687.4  384.94  4696.3  384.13  4702.4  381.72
  4708.1  382.75  4717.4  380.78  4732.4  380.53  4738.5  381.95  4744.5  381.11
  4753.5  382.29  4797.3  379.71  4804.5  379.85  4897.9  373.61  4953.7  370.88
  4966.5  368.62  4974.8  366.08  4995.1  355.26  4997.8  354.76  5001.1  355.26
  5016.9  361.18  5029.7  367.94  5069.6   373.4  5143.4  376.27  5175.1  378.48
  5227.8  384.01  5259.4   386.3  5277.5  389.02  5443.1  401.71    5450  401.79
#Mann= 6 ,-1 , 0
  4637.5     .05       0  4708.1      .1       0  4797.3     .16       0
  4995.1     .07       0  5001.1     .16       0  5443.1      .1       0
Bank Sta=4995.1,5001.1
XS Rating Curve= 0 ,0
Exp/Cntr=0.3,0.1

Type RM Length L Ch R = 1 ,6851    ,447,447,447
BEGIN DESCRIPTION:
UNT0360 IN CEDR CR 14.0
END DESCRIPTION:
XS GIS Cut Line= 3
      3581230.42     10390433.17      3581592.11     10390591.64
      3581975.19     10390735.25
#Sta/Elev= 30
  4599.4  391.04  4616.3  390.47  4659.6  388.72  4729.7  383.19  4758.6  381.88
  4828.7  374.83  4857.5  373.17  4880.9  370.49  4927.7  367.16  4979.9  360.07
  4991.6  354.11    4997  354.11  5001.1  351.64  5003.8  351.14  5007.1  351.64
  5015.6  359.86  5026.3  362.15  5034.3  360.27  5039.7  362.13  5047.7  362.13
  5064.6  365.77  5079.7  366.32  5094.9  365.72  5101.1  363.12  5119.8  367.67
  5133.1  368.05  5165.2  371.98  5180.3  372.54  5320.6  383.87  5403.4  387.42
#Mann= 5 ,-1 , 0
  4599.4     .05       0  4616.3     .16       0  5001.1     .07       0
  5007.1     .16       0  5320.6      .1       0
Bank Sta=5001.1,5007.1
XS Rating Curve= 0 ,0
Exp/Cntr=0.3,0.1

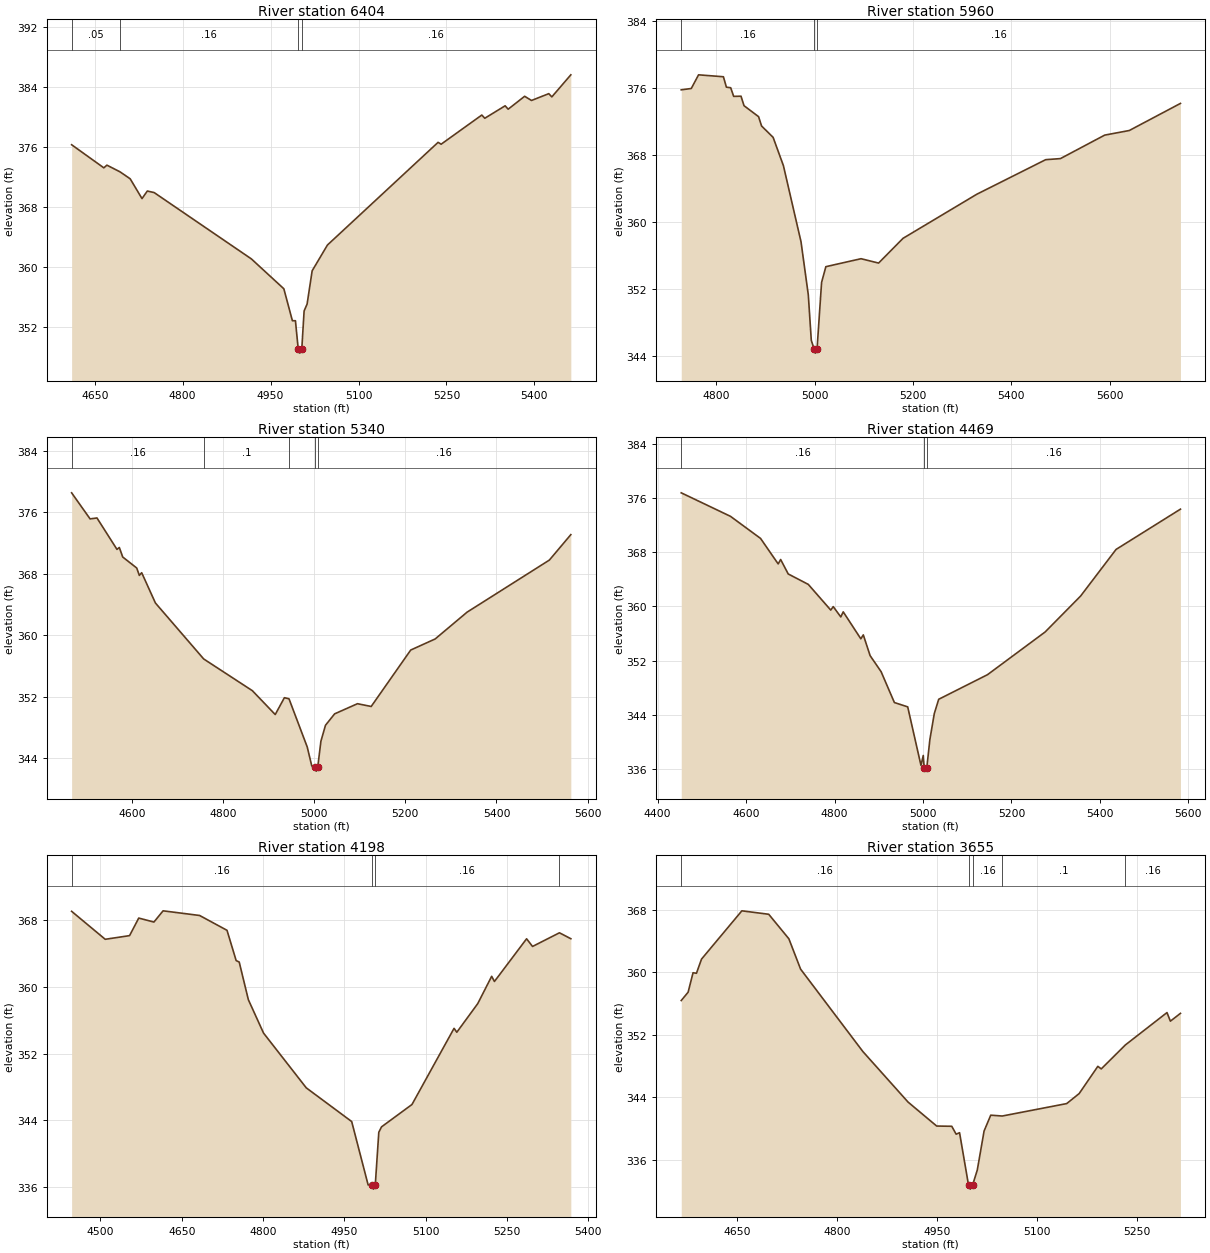
Type RM Length L Ch R = 1 ,6404    ,444,444,444
BEGIN DESCRIPTION:
UNT0360 IN CEDR CR 13.0
END DESCRIPTION:
XS GIS Cut Line= 3
      3581126.24      10390891.5      3581492.11     10390991.64
      3581948.15     10391115.19
#Sta/Elev= 30
  4610.5  376.24  4665.5  373.16  4670.7  373.52  4693.2  372.62  4710.4   371.7
  4730.6  369.06  4739.7  370.07  4751.4  369.86  4917.2  361.02  4972.6  357.04
  4987.2  352.78  4992.4  352.78  4997.2  348.96  4999.9  348.46  5003.2  348.96
  5007.2  354.08  5012.3     355  5020.9  359.43    5047  362.87  5235.8  376.56
    5241  376.31  5310.4   380.2  5315.5  379.77  5350.2  381.43  5355.4  380.98
  5383.5   382.7  5395.2  382.14  5424.7  383.05  5429.9  382.62  5462.3  385.56
#Mann= 4 ,-1 , 0
  4610.5     .05       0  4693.2     .16       0  4997.2     .07       0
  5003.2     .16       0
Bank Sta=4997.2,5003.2
XS Rating Curve= 0 ,0
Exp/Cntr=0.3,0.1

Type RM Length L Ch R = 1 ,5960    ,620,620,620
BEGIN DESCRIPTION:
UNT0360 IN CEDR CR 12.0
END DESCRIPTION:
XS GIS Cut Line= 3
      3581058.54     10391136.29      3581407.52      10391381.1
      3581996.11      10391386.3
#Sta/Elev= 30
  4729.1  375.74  4749.5   375.9  4764.3  377.53  4814.8   377.3  4820.9  376.06
  4829.6  375.99  4835.7  374.96  4850.6  374.98  4856.7  373.85  4886.3  372.54
  4892.4  371.43  4915.9  370.07  4936.8   366.7  4972.6  357.62  4987.4  351.29
  4993.5  345.86  4999.2  344.84  5001.9  344.34  5005.2  344.84  5014.4  352.77
  5023.1  354.65  5094.6   355.6  5130.3  355.08    5180  358.03    5330  363.29
    5470  367.41    5500  367.54    5590  370.34    5640  370.89    5744  374.12
#Mann= 3 ,-1 , 0
  4729.1     .16       0  4999.2     .07       0  5005.2     .16       0
Bank Sta=4999.2,5005.2
XS Rating Curve= 0 ,0
Exp/Cntr=0.3,0.1

Type RM Length L Ch R = 1 ,5340    ,871,871,871
BEGIN DESCRIPTION:
UNT0360 IN CEDR CR 11.0
END DESCRIPTION:
XS GIS Cut Line= 3
      3580782.55     10391724.85      3581068.98     10391787.35
      3581869.13      10391839.3
#Sta/Elev= 30
  4468.1   378.5  4508.6  375.11  4523.7  375.23  4567.6  371.14  4572.7  371.39
  4580.2  370.15  4610.9  368.72  4616.6  367.76  4621.8  368.11  4651.9  364.17
  4757.8  356.89  4864.6  352.76  4914.7  349.66  4934.8  351.85  4944.9  351.71
  4984.9  345.44  4994.9  342.97  5001.9   342.8  5004.7   342.3  5007.9   342.8
  5014.9  346.19  5024.9  348.26    5045  349.75  5095.1  351.07  5125.2  350.71
  5211.9  358.05  5265.5  359.49  5335.6  362.98    5516  369.75  5563.1  373.06
#Mann= 5 ,-1 , 0
  4468.1     .16       0  4757.8      .1       0  4944.9     .16       0
  5001.9     .07       0  5007.9     .16       0
Bank Sta=5001.9,5007.9
XS Rating Curve= 0 ,0
Exp/Cntr=0.3,0.1

Type RM Length L Ch R = 1 ,4469    ,271,271,271
BEGIN DESCRIPTION:
UNT0360 IN CEDR CR 10.0
END DESCRIPTION:
XS GIS Cut Line= 3
      3580772.12     10392120.69      3581157.73     10392305.18
      3581857.37     10392255.21
#Sta/Elev= 30
  4453.3  376.75  4564.7  373.28  4632.7  370.02  4672.5  366.26  4678.1  366.91
  4695.2  364.78  4740.6  363.24  4791.4  359.45    4797  359.96  4814.1  358.44
  4819.6  359.19  4859.4  355.21    4865  355.79  4880.4  352.73  4905.2  350.37
  4935.3  345.81  4965.4  345.17  4995.4  336.54  5000.6     338  5002.6  336.19
  5005.3  335.69  5008.6  336.19  5015.5  340.33  5025.5  344.17  5035.5  346.29
  5145.9  349.92  5276.2  356.22  5356.4  361.52  5436.6   368.4  5582.2  374.34
#Mann= 3 ,-1 , 0
  4453.3     .16       0  5002.6     .07       0  5008.6     .16       0
Bank Sta=5002.6,5008.6
XS Rating Curve= 0 ,0
Exp/Cntr=0.3,0.1

Type RM Length L Ch R = 1 ,4198    ,543,543,543
BEGIN DESCRIPTION:
UNT0360 IN CEDR CR 9.0
END DESCRIPTION:
XS GIS Cut Line= 3
       3580766.9     10392391.51      3581115.86     10392563.39
       3581641.9     10392485.26
#Sta/Elev= 30
  4446.9   369.1  4508.9  365.74  4553.8  366.18  4570.7  368.29  4598.7  367.81
  4615.6  369.16    4683   368.6  4733.5  366.82  4750.4  363.18    4756  363.01
  4772.9  358.48  4800.9  354.47  4879.7  347.89  4963.5  343.84  4993.8  336.23
    5001  336.22  5003.7  335.72    5007  336.22  5013.5  342.55  5018.5   343.2
  5074.7  345.89  5152.3  355.04  5157.4  354.57    5196  358.01  5221.7  361.29
  5226.8  360.67  5286.1   365.8  5297.1  364.88  5346.7  366.52  5367.7  365.81
#Mann= 4 ,-1 , 0
  4446.9     .16       0    5001     .07       0    5007     .16       0
  5346.7      .1       0
Bank Sta=5001,5007
XS Rating Curve= 0 ,0
Exp/Cntr=0.3,0.1

Type RM Length L Ch R = 1 ,3655    ,489,489,489
BEGIN DESCRIPTION:
UNT0360 IN CEDR CR 8.0
END DESCRIPTION:
XS GIS Cut Line= 3
      3580761.92     10392854.14       3581161.9     10392904.14
      3581501.24     10392969.63
#Sta/Elev= 30
  4566.3  356.39  4576.6  357.45    4584  359.94  4589.1  359.87  4596.7  361.68
  4657.2  367.85  4697.5  367.41  4727.7  364.28  4745.3   360.4  4838.6  349.88
  4906.5  343.41  4949.4  340.35    4972  340.32  4978.6  339.31  4983.7   339.5
  4997.2  332.79  4999.9  332.29  5003.2  332.79  5010.3  334.73  5020.5  339.72
  5030.5  341.74  5047.7  341.63  5144.4  343.22  5163.1   344.5  5191.1  347.98
  5196.2  347.65  5232.5  350.72  5294.8  354.85  5299.9  353.75    5315  354.75
#Mann= 5 ,-1 , 0
  4566.3     .16       0  4997.2     .07       0  5003.2     .16       0
  5047.7      .1       0  5232.5     .16       0
Bank Sta=4997.2,5003.2
XS Rating Curve= 0 ,0
Exp/Cntr=0.3,0.1

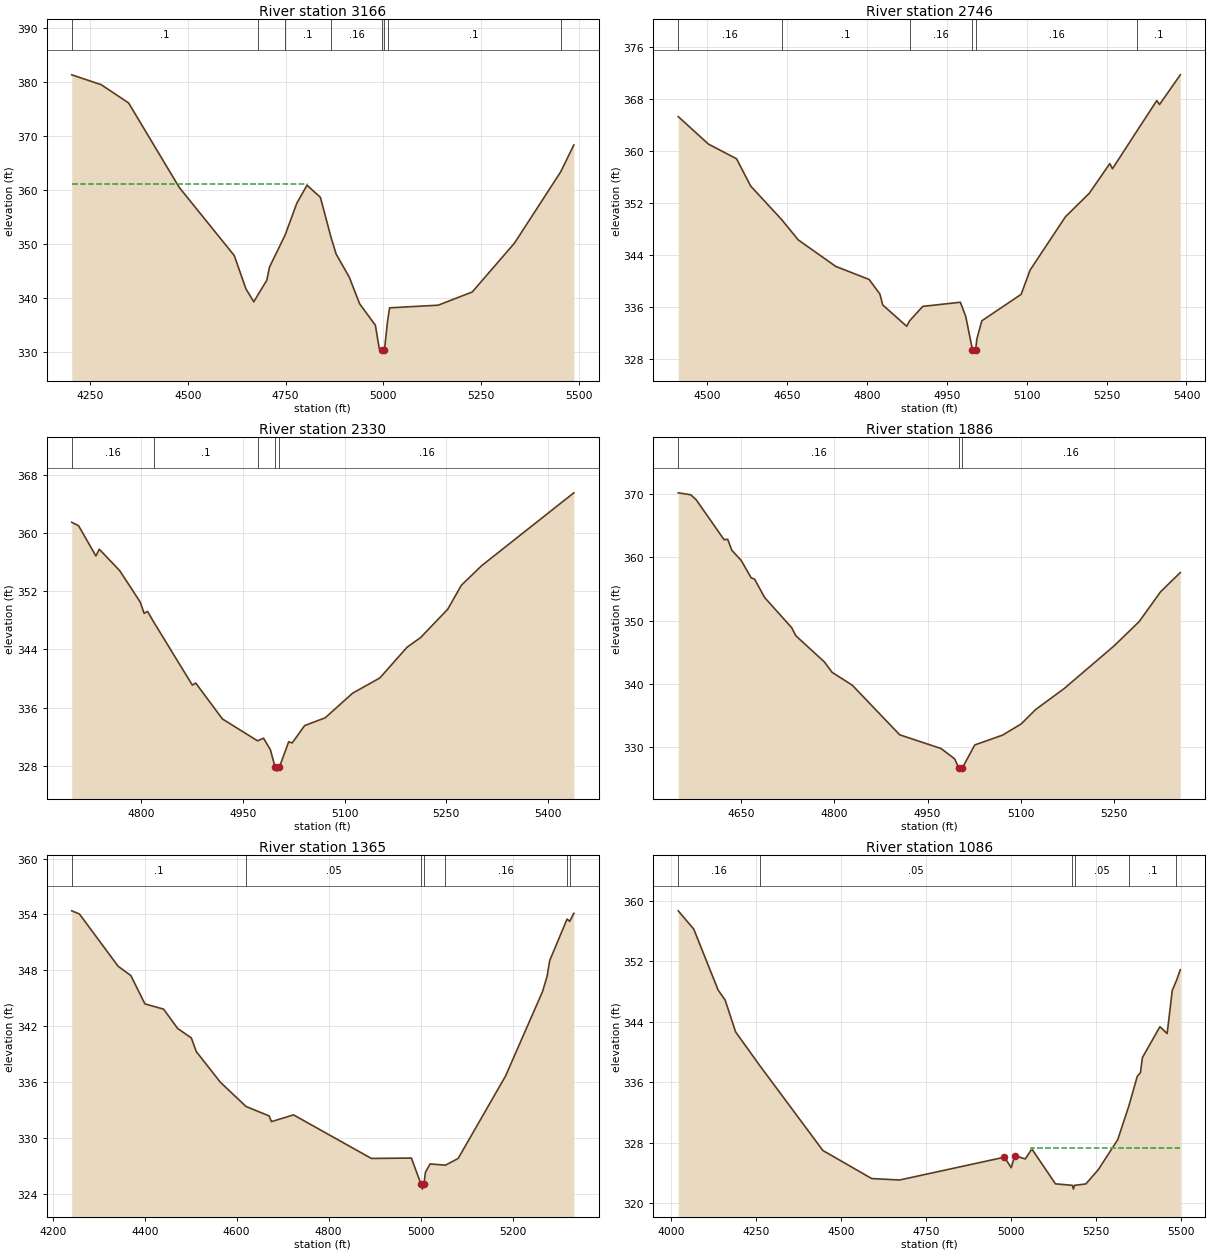
Type RM Length L Ch R = 1 ,3166    ,420,420,420
BEGIN DESCRIPTION:
UNT0360 IN CEDR CR 7.0
END DESCRIPTION:
XS GIS Cut Line= 3
      3580266.86     10393339.43      3580834.61     10393313.39
      3581547.66     10393381.05
#Sta/Elev= 30
  4202.7  381.32    4278  379.49  4348.1  376.11  4477.5  360.46  4618.4  347.81
  4648.4  341.62  4668.4  339.22  4678.6  340.47  4701.7  343.23  4708.5  345.65
  4748.5   351.6  4778.6  357.52  4804.6  360.85  4838.8  358.61    4866  351.19
    4879   348.1  4912.8  343.79  4939.3  338.85  4979.5  334.89  4989.5  330.54
  4996.6  330.21  4999.3  329.71  5002.6  330.21  5010.6  335.59  5015.9  338.11
  5140.2   338.6  5227.3  341.05  5335.4  350.11  5453.6  363.32  5487.3  368.31
#Mann= 8 ,-1 , 0
  4202.7      .1       0  4678.6     .16       0  4748.5      .1       0
    4866     .16       0  4996.6     .07       0  5002.6     .16       0
  5010.6      .1       0  5453.6     .16       0
#XS Ineff= 2 , 0
         4805.34     361
Permanent Ineff=
       F       F
Bank Sta=4996.6,5002.6
XS Rating Curve= 0 ,0
Exp/Cntr=0.3,0.1

Type RM Length L Ch R = 1 ,2746    ,416,416,416
BEGIN DESCRIPTION:
UNT0360 IN CEDR CR 6.0
END DESCRIPTION:
XS GIS Cut Line= 3
      3580558.57     10393766.51      3580782.52     10393724.85
      3581492.07     10393641.65
#Sta/Elev= 30
  4446.3  365.25    4503  361.03  4555.8  358.78  4582.1  354.61  4640.7  349.42
  4671.3  346.35  4741.8  342.27  4804.6  340.26  4824.7  338.03  4830.1  336.35
    4875  333.08  4880.6  333.93  4905.2  336.13  4975.7  336.77  4985.8  334.61
  4998.5  329.46  5001.3  328.96  5004.5  329.46  5006.6  331.09    5016  333.92
  5089.8  337.98  5106.6   341.7    5173  349.89  5217.4  353.46  5256.2  358.04
  5261.2  357.25  5307.4  363.08  5344.4  367.71  5349.5   367.1  5388.5  371.66
#Mann= 6 ,-1 , 0
  4446.3     .16       0  4640.7      .1       0  4880.6     .16       0
  4998.5     .07       0  5004.5     .16       0  5307.4      .1       0
Bank Sta=4998.5,5004.5
XS Rating Curve= 0 ,0
Exp/Cntr=0.3,0.1

Type RM Length L Ch R = 1 ,2330    ,444,444,444
BEGIN DESCRIPTION:
UNT0360 IN CEDR CR 5.0
END DESCRIPTION:
XS GIS Cut Line= 3
      3580692.09     10393991.64      3581126.27     10394052.97
      3581427.78     10394037.38
#Sta/Elev= 30
  4697.8  361.47  4707.9  360.99  4733.4  356.84  4738.4  357.77  4768.5  354.82
  4798.8   350.5  4804.5  348.95  4809.5  349.22  4818.4   347.8  4875.6  339.09
  4880.6  339.37    4920  334.43  4971.7  331.43  4980.6  331.79  4990.7   330.2
  4997.8  327.76  5000.5  327.26  5003.8  327.76  5017.7   331.3  5022.8  331.13
  5041.2  333.52  5071.5  334.59  5111.9  337.97  5152.1  340.07  5192.2  344.29
  5212.2  345.62  5252.3  349.53  5272.3  352.81  5302.3  355.51  5438.2  365.52
#Mann= 5 ,-1 , 0
  4697.8     .16       0  4818.4      .1       0  4971.7     .16       0
  4997.8     .07       0  5003.8     .16       0
Bank Sta=4997.8,5003.8
XS Rating Curve= 0 ,0
Exp/Cntr=0.3,0.1

Type RM Length L Ch R = 1 ,1886    ,521,521,521
BEGIN DESCRIPTION:
UNT0360 IN CEDR CR 4.0
END DESCRIPTION:
XS GIS Cut Line= 3
      3580516.88     10394188.38      3580740.86     10394313.39
      3581242.13     10394541.65
#Sta/Elev= 30
  4549.1  370.14  4569.2  369.83    4578  369.05  4622.8  362.75  4628.6  362.81
  4635.3  361.08  4650.3  359.49  4666.3  356.75    4672  356.51    4688  353.63
  4731.4  348.89  4738.3  347.59  4784.1  343.47  4796.5  341.83    4829   339.8
  4905.2  331.98  4971.8  329.81  4993.8  328.16  4999.9  326.75  5002.6  326.25
  5005.9  326.75  5025.9  330.38  5070.7  331.93  5100.6   333.7  5123.6  335.95
  5169.6  339.27  5249.9     346  5290.4  349.85  5324.5  354.51  5356.4  357.57
#Mann= 3 ,-1 , 0
  4549.1     .16       0  4999.9     .07       0  5005.9     .16       0
Bank Sta=4999.9,5005.9
XS Rating Curve= 0 ,0
Exp/Cntr=0.3,0.1

Type RM Length L Ch R = 1 ,1365    ,279,279,279
BEGIN DESCRIPTION:
UNT0360 IN CEDR CR 2.0
END DESCRIPTION:
XS GIS Cut Line= 3
      3579985.68     10394698.81      3580834.61     10394855.05
      3581032.54     10394740.46
#Sta/Elev= 30
  4241.4  354.39  4258.1  354.05  4342.2  348.45  4369.9  347.45  4400.5  344.41
  4441.1  343.85  4471.6  341.78  4501.4  340.76  4512.3  339.29  4564.6  336.01
  4620.4  333.41  4670.6   332.4  4675.7  331.79  4723.7  332.51    4893  327.84
    4980  327.88  5001.2  325.05  5003.9  324.55  5007.2  325.05  5010.5  326.35
  5020.7  327.25  5054.1  327.12  5081.7  327.84  5184.8  336.68  5265.2  345.73
    5275  347.35  5280.9  349.07  5318.6  353.51  5324.2  353.26  5333.3  354.12
#Mann= 7 ,-1 , 0
  4241.4      .1       0  4620.4     .05       0  5001.2     .03       0
  5007.2     .05       0  5054.1     .16       0  5318.6      .1       0
  5324.2     .16       0
Bank Sta=5001.2,5007.2
XS Rating Curve= 0 ,0
Exp/Cntr=0.3,0.1

Type RM Length L Ch R = 1 ,1086    ,575,575,575
BEGIN DESCRIPTION:
UNT0360 IN CEDR CR 1.0
END DESCRIPTION:
XS GIS Cut Line= 3
      3579767.62     10394893.94      3580850.23     10395141.51
      3581048.16      10394834.2
#Sta/Elev= 30
  4020.8  358.71  4066.4  356.29  4138.2  348.21  4158.8  346.88  4189.5  342.67
  4261.2  338.17    4446  326.96  4589.6  323.24  4671.7  323.05  4979.7  326.07
  4999.9  324.68  5010.2  326.28    5041  325.84  5060.5  327.16  5129.8  322.54
  5179.9  322.34  5182.6  321.84  5185.9  322.34  5219.2  322.53  5255.5   324.4
  5312.9  328.39  5345.5  332.84  5370.4  336.79  5379.6  337.26  5385.5  339.27
    5437  343.36  5458.2  342.45  5473.3  348.18  5485.6  349.48  5496.9   350.9
#Mann= 6 ,-1 , 0
  4020.8     .16       0  4261.2     .05       0  5179.9     .03       0
  5185.9     .05       0  5345.5      .1       0  5485.6     .16       0
#XS Ineff= 2 , 0
                         5059.09          327.26
Permanent Ineff=
       F       F
Bank Sta=4979.7,5010.2
XS Rating Curve= 0 ,0
Exp/Cntr=0.3,0.1

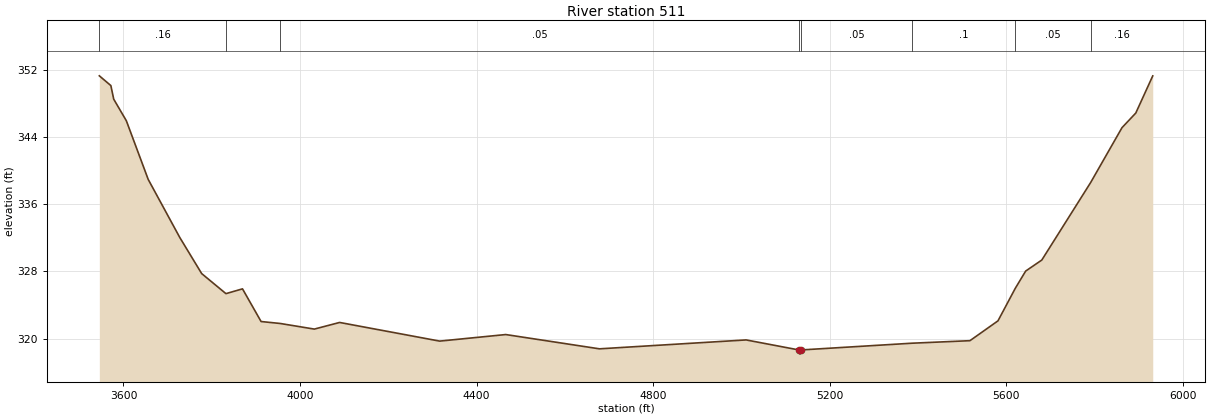
Type RM Length L Ch R = 1 ,511     ,0,0,0
BEGIN DESCRIPTION:
UNT0360 IN CEDR CR 1.011
END DESCRIPTION:
XS GIS Cut Line= 4
      3579790.24     10394977.35        3580660.     10395699.55
      3581153.06     10395317.61      3581359.67     10394720.34
#Sta/Elev= 30
  3545.4  351.28  3571.5  350.12    3578   348.5  3606.6  345.93  3656.1  338.95
  3727.7  332.03  3777.2  327.74  3832.2  325.35  3869.7  325.92  3911.8  322.03
    3955   321.8  4032.4  321.13  4089.7  321.92  4316.3   319.7    4466  320.48
  4678.3  318.78  5010.5  319.84  5129.8  318.65  5132.5  318.15  5135.8  318.65
  5386.4  319.45  5517.5  319.75    5581  322.11  5620.4     326  5643.8  328.04
  5680.3  329.35  5791.1  338.59    5862  345.11  5893.2  346.85  5931.6  351.27
#Mann= 8 ,-1 , 0
  3545.4     .16       0  3832.2      .1       0    3955     .05       0
  5129.8     .03       0  5135.8     .05       0  5386.4      .1       0
  5620.4     .05       0  5791.1     .16       0
Bank Sta=5129.8,5135.8
XS Rating Curve= 0 ,0
Exp/Cntr=0.3,0.1

Chan Stop Cuts=-1
Use User Specified Reach Order=0
Composite Channel Slope=5