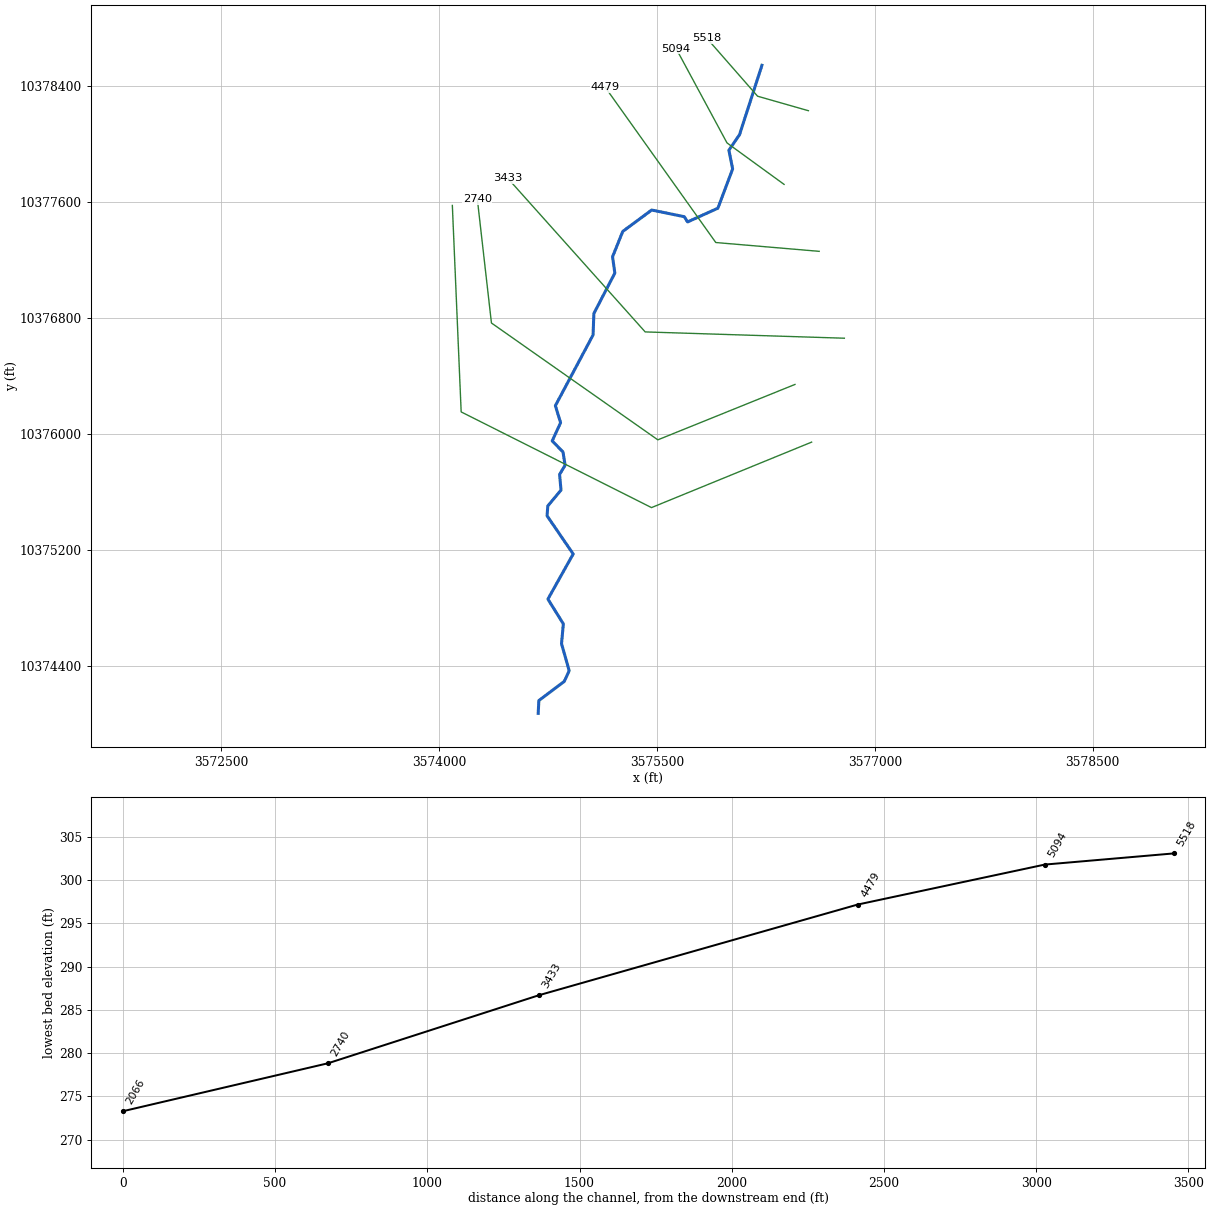
--- UNT0363 IN CEDR CR.prj (project) ---

Proj Title=UNT0363 IN CEDR CR Base Level Engineering
Current Plan=p01
Default Exp/Contr=0.3,0.1
English Units
Geom File=g01
Flow File=f01
Plan File=p01
Y Axis Title=Elevation
X Axis Title(PF)=Main Channel Distance
X Axis Title(XS)=Station
BEGIN DESCRIPTION:
UNT0363 IN CEDR CR
END DESCRIPTION:
DSS Export Rating Curves= 0
DSS Export Rating Curve Sorted= 0
DSS Export Volume Flow Curves= 0
DXF OffsetX= 0
DXF OffsetY= 0
DXF ScaleX= 1
DXF ScaleY= 10

--- UNT0363 IN CEDR CR.p01 (plan) ---

Plan Title=Multiple Run
Short Identifier=Multiple
Geom File=g01
Flow File=f01
Subcritical Flow
K Sum by GR= 0
Std Step Tol= 0.01
Critical Tol= 0.01
Num of Std Step Trials= 20
Max Error Tol= 0.3
Flow Tol Ratio= 0.001
Split Flow NTrial= 30
Split Flow Tol= 0.02
Split Flow Ratio= 0.02
Log Output Level= 0
Friction Slope Method= 1
Unsteady Friction Slope Method= 2
Unsteady Bridges Friction Slope Method= 1
Parabolic Critical Depth
Global Vel Dist=  1 , 1 , 1
Global Log Level= 0
CheckData=True
Encroach Param= -1, 0, 0, 0
BEGIN DESCRIPTION:
Multiple Run
END DESCRIPTION:

--- UNT0363 IN CEDR CR.f01 (steady flow) ---

Flow Title=Multiple
Number of Profiles=7
Profile Names=10-year,25-year,50-year,1pct_min,100-year,1pct_plu,500-year
River Rch & RM= UNT0363 IN CEDR ,Reach-1,5518
    2318    3381    4311    4009    5421    7332    8550
Boundary for River Rch & Prof#=UNT0363 IN CEDR ,Reach-1,1
Up Type=0
Dn Type=3
Dn Slope=0.005
Boundary for River Rch & Prof#=UNT0363 IN CEDR ,Reach-1,2
Up Type=0
Dn Type=3
Dn Slope=0.005
Boundary for River Rch & Prof#=UNT0363 IN CEDR ,Reach-1,3
Up Type=0
Dn Type=3
Dn Slope=0.005
Boundary for River Rch & Prof#=UNT0363 IN CEDR ,Reach-1,4
Up Type=0
Dn Type=3
Dn Slope=0.005
Boundary for River Rch & Prof#=UNT0363 IN CEDR ,Reach-1,5
Up Type=0
Dn Type=3
Dn Slope=0.005
Boundary for River Rch & Prof#=UNT0363 IN CEDR ,Reach-1,6
Up Type=0
Dn Type=3
Dn Slope=0.005
Boundary for River Rch & Prof#=UNT0363 IN CEDR ,Reach-1,7
Up Type=0
Dn Type=3
Dn Slope=0.005

--- UNT0363 IN CEDR CR.g01 (geometry) ---

Geom Title=Existing Conditions
Program Version=4.10

River Reach=UNT0363 IN CEDR ,Reach-1
Reach XY= 30
      3576222.12     10378541.78      3576067.59     10378063.15
       3575994.6     10377956.59      3576020.32     10377827.54
       3575918.7     10377556.68      3575709.93     10377462.07
      3575687.36     10377498.09      3575462.97      10377544.1
      3575263.77     10377396.64      3575193.39     10377222.02
      3575209.08     10377109.31       3575064.7     10376830.67
      3575059.23     10376682.83      3574799.58     10376194.96
      3574835.59     10376077.96       3574777.7     10375952.25
        3574852.     10375876.57      3574866.71     10375784.83
      3574828.59     10375721.41      3574838.44     10375613.23
      3574747.49       10375504.      3574742.36     10375436.12
      3574922.27     10375172.73      3574748.28     10374861.63
      3574854.53      10374690.8      3574842.03     10374554.69
       3574894.8     10374367.88      3574860.78     10374294.27
      3574685.78     10374162.33      3574681.35     10374073.94

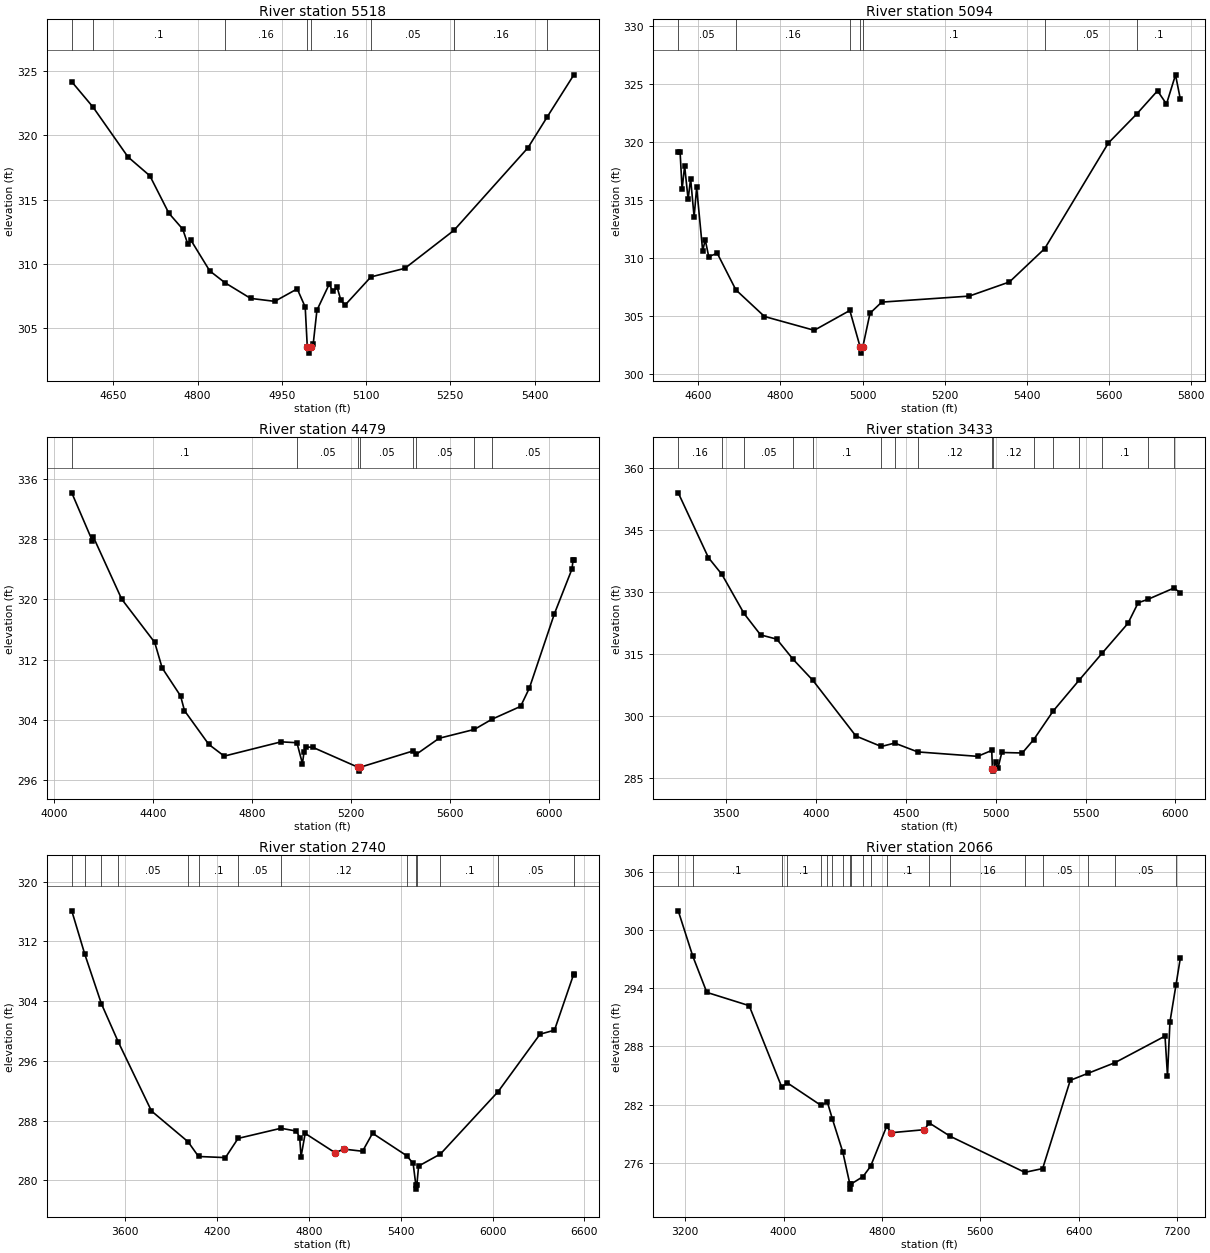
Type RM Length L Ch R = 1 ,5518    ,424,424,424
BEGIN DESCRIPTION:
UNT0363 IN CEDR CR 10.0
END DESCRIPTION:
XS GIS Cut Line= 3
      3576542.11     10378228.79      3576192.11      10378328.8
      3575843.04     10378727.73
#Sta/Elev= 30
  4575.9  324.18  4613.9   322.2    4676  318.33    4715  316.86  4748.8  313.95
  4773.5  312.71  4782.6  311.54  4787.8  311.87  4821.6  309.46  4848.7  308.54
  4894.4  307.32  4937.3  307.09  4977.4  308.06  4991.6  306.65  4995.3  303.56
    4998  303.06  5001.3  303.56  5005.9  303.79  5012.5   306.4  5034.3  308.42
    5041  307.86  5048.6  308.17  5055.2  307.16  5062.8  306.81  5108.6  308.99
  5169.1  309.66  5256.6  312.62  5388.4  319.05  5422.8  321.46    5470  324.72
#Mann= 8 ,-1 , 0
  4575.9     .05       0  4613.9      .1       0  4848.7     .16       0
  4995.3     .07       0  5001.3     .16       0  5108.6     .05       0
  5256.6     .16       0  5422.8      .1       0
Bank Sta=4995.3,5001.3
XS Rating Curve= 0 ,0
Exp/Cntr=0.3,0.1

Type RM Length L Ch R = 1 ,5094    ,615,615,615
BEGIN DESCRIPTION:
UNT0363 IN CEDR CR 9.0
END DESCRIPTION:
XS GIS Cut Line= 3
      3576374.46     10377720.95      3575981.34     10378006.92
      3575631.42     10378656.77
#Sta/Elev= 30
  4550.7  319.15  4555.2  319.15  4560.1   315.9  4566.3  317.92  4574.8  315.04
  4580.9  316.82  4589.4  313.51  4595.6  316.06  4610.3  310.59  4616.5  311.55
    4625   310.1  4645.9  310.38  4691.2  307.23    4761  304.93  4882.3  303.74
  4969.1  305.45  4994.5  302.27  4997.2  301.77  5000.5  302.27  5018.3  305.21
  5046.8  306.17  5260.2  306.69  5358.3  307.91  5444.3  310.79  5599.3  319.89
  5669.1  322.42  5719.3   324.4  5741.2  323.26  5763.2  325.78  5774.9  323.69
#Mann= 7 ,-1 , 0
  4550.7     .05       0  4691.2     .16       0  4969.1      .1       0
  4994.5     .07       0  5000.5      .1       0  5444.3     .05       0
  5669.1      .1       0
Bank Sta=4994.5,5000.5
XS Rating Curve= 0 ,0
Exp/Cntr=0.3,0.1

Type RM Length L Ch R = 1 ,4479    ,1046,1046,1046
BEGIN DESCRIPTION:
UNT0363 IN CEDR CR 8.0
END DESCRIPTION:
XS GIS Cut Line= 3
      3576616.06      10377259.3      3575904.28     10377320.06
      3575142.08     10378391.68
#Sta/Elev= 30
  4070.2   334.2    4153  327.84    4158  328.28    4272  320.05  4405.4  314.29
  4435.5  310.89    4510  307.16  4525.8   305.2    4624  300.71  4686.4  299.15
  4916.5  301.05  4980.3  300.93  5002.6  298.15  5008.8  299.66  5017.4  300.37
  5044.4  300.32  5228.3  297.65  5231.1  297.15  5234.3  297.65  5449.1  299.83
  5462.8  299.39  5554.8  301.52  5697.3   302.7  5768.7  304.06  5884.4  305.77
    5920  308.22  6020.9  318.09  6092.2  324.07  6096.5   325.3  6099.6   325.3
#Mann= 8 ,-1 , 0
  4070.2      .1       0  4980.3     .05       0  5228.3    .035       0
  5234.3     .05       0  5449.1      .1       0  5462.8     .05       0
  5697.3      .1       0  5768.7     .05       0
Bank Sta=5228.3,5234.3
XS Rating Curve= 0 ,0
Exp/Cntr=0.3,0.1

Type RM Length L Ch R = 1 ,3433    ,693,693,693
BEGIN DESCRIPTION:
UNT0363 IN CEDR CR 1.0
END DESCRIPTION:
XS GIS Cut Line= 3
      3576789.69     10376660.34      3575418.17     10376703.74
      3574472.02     10377762.73
#Sta/Elev= 30
  3234.9  353.89  3402.6  338.25  3478.1  334.17  3600.7  324.76  3692.7  319.59
  3782.8  318.56    3874  313.68  3984.2  308.58    4223  295.17    4364  292.64
  4438.6  293.46  4566.8  291.33    4900  290.26  4978.5  291.69  4982.2  287.19
    4985  286.69  4988.2  287.19  4999.4   288.8  5013.6  287.51  5034.5  291.19
  5148.2  291.07  5211.6  294.28  5319.6  301.17    5466  308.73  5593.2  315.21
  5735.9  322.37  5792.8  327.34  5847.6  328.18  5991.9   330.9  6027.2  329.74
#Mann= 16 ,-1 , 0
  3234.9     .16       0  3478.1      .1       0  3600.7     .05       0
    3874     .16       0  3984.2      .1       0    4364     .05       0
  4438.6      .1       0  4566.8     .12       0  4982.2     .07       0
  4988.2     .12       0  5211.6     .16       0  5319.6     .12       0
    5466     .16       0  5593.2      .1       0  5847.6     .05       0
  5991.9     .16       0
Bank Sta=4982.2,4988.2
XS Rating Curve= 0 ,0
Exp/Cntr=0.3,0.1

Type RM Length L Ch R = 1 ,2740    ,674,674,674
BEGIN DESCRIPTION:
UNT0363 IN CEDR CR 1.0111
END DESCRIPTION:
XS GIS Cut Line= 4
      3576449.62     10376341.67      3575505.21     10375959.74
      3574359.38      10376765.3      3574262.32     10377618.02
#Sta/Elev= 30
  3253.2  316.09  3338.2  310.28  3446.8  303.64  3556.2  298.56  3773.5  289.29
  4011.9  285.18  4080.7   283.2  4256.3  283.05  4338.9  285.62    4619  286.98
  4720.2   286.6  4741.2  285.71  4749.9  283.17  4776.9  286.29  4972.5   283.7
  5029.5  284.19  5151.5   283.9  5216.8  286.31  5440.6  283.29  5481.7  282.27
  5499.6  279.33  5502.4  278.83  5505.6  279.33  5517.4  281.92  5660.3  283.54
  6036.7  291.89  6309.8  299.57  6404.4  300.11  6528.6  307.54  6530.8   307.6
#Mann= 14 ,-1 , 0
  3253.2      .1       0  3338.2     .05       0  3446.8      .1       0
  3556.2     .05       0  4011.9     .12       0  4080.7      .1       0
  4338.9     .05       0    4619     .12       0  5440.6     .16       0
  5499.6     .07       0  5505.6     .16       0  5660.3      .1       0
  6036.7     .05       0  6528.6     .16       0
Bank Sta=4972.5,5029.5
XS Rating Curve= 0 ,0
Exp/Cntr=0.3,0.1

Type RM Length L Ch R = 1 ,2066    ,0,0,0
BEGIN DESCRIPTION:
UNT0363 IN CEDR CR 1.0222
END DESCRIPTION:
XS GIS Cut Line= 4
      3576564.13     10375943.99      3575461.67     10375492.58
       3574150.9     10376152.31      3574090.14     10377575.89
#Sta/Elev= 30
  3142.8  301.99  3261.2  297.31  3375.3  293.58  3719.7  292.21  3984.1  283.83
  4029.8  284.25  4303.4  281.93  4355.8  282.26  4396.2  280.54  4481.6   277.1
    4539  273.79  4541.8  273.29    4545  273.79  4645.4  274.58  4707.2  275.64
  4837.7  279.76  4876.8  279.11  5144.6  279.42  5183.6  280.12  5354.7  278.74
  5961.7  275.02  6106.7  275.41  6331.3  284.51  6474.7  285.23  6694.6  286.33
    7102  289.07  7122.1  284.98  7142.1  290.53  7191.1  294.34  7226.4   297.1
#Mann= 20 ,-1 , 0
  3142.8     .05       0  3261.2      .1       0  3984.1     .12       0
  4029.8      .1       0  4303.4     .16       0  4355.8      .1       0
  4396.2     .16       0  4481.6     .12       0    4539     .07       0
    4545     .12       0  4645.4     .16       0  4707.2     .12       0
  4837.7      .1       0  5183.6     .16       0  5354.7     .16       0
  5961.7     .07       0  6106.7     .05       0  6474.7      .1       0
  6694.6     .05       0  7191.1     .16       0
Bank Sta=4876.8,5144.6
XS Rating Curve= 0 ,0
Exp/Cntr=0.3,0.1

Chan Stop Cuts=-1
Use User Specified Reach Order=0
Composite Channel Slope=5