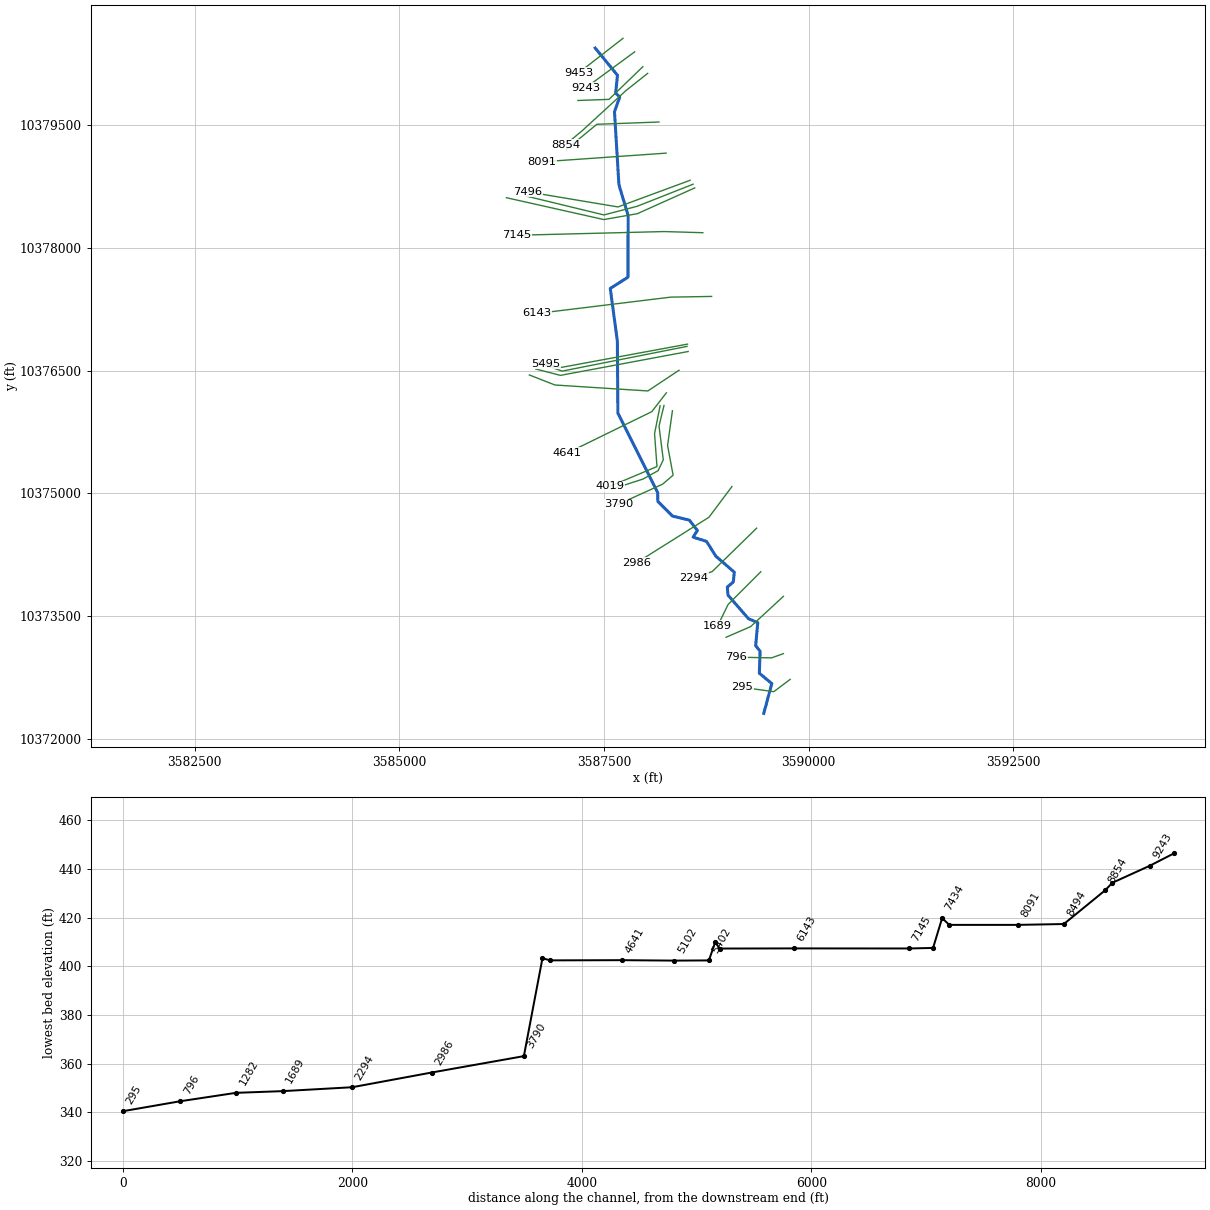
--- UNT0380 IN CEDR CR.prj (project) ---

Proj Title=UNT0380 IN CEDR CR Base Level Engineering
Current Plan=p01
Default Exp/Contr=0.3,0.1
English Units
Geom File=g01
Flow File=f01
Plan File=p01
Y Axis Title=Elevation
X Axis Title(PF)=Main Channel Distance
X Axis Title(XS)=Station
BEGIN DESCRIPTION:
UNT0380 IN CEDR CR
END DESCRIPTION:
DSS Export Rating Curves= 0
DSS Export Rating Curve Sorted= 0
DSS Export Volume Flow Curves= 0
DXF OffsetX= 0
DXF OffsetY= 0
DXF ScaleX= 1
DXF ScaleY= 10

--- UNT0380 IN CEDR CR.p01 (plan) ---

Plan Title=Multiple Run
Short Identifier=Multiple
Geom File=g01
Flow File=f01
Subcritical Flow
K Sum by GR= 0
Std Step Tol= 0.01
Critical Tol= 0.01
Num of Std Step Trials= 20
Max Error Tol= 0.3
Flow Tol Ratio= 0.001
Split Flow NTrial= 30
Split Flow Tol= 0.02
Split Flow Ratio= 0.02
Log Output Level= 0
Friction Slope Method= 1
Unsteady Friction Slope Method= 2
Unsteady Bridges Friction Slope Method= 1
Parabolic Critical Depth
Global Vel Dist=  1 , 1 , 1
Global Log Level= 0
CheckData=True
Encroach Param= -1, 0, 0, 0
BEGIN DESCRIPTION:
Multiple Run
END DESCRIPTION:

--- UNT0380 IN CEDR CR.f01 (steady flow) ---

Flow Title=Multiple
Program Version=4.10
Number of Profiles= 7
Profile Names=10-year,25-year,50-year,1pct_min,100-year,1pct_plu,500-year
River Rch & RM=UNT0380 IN CEDR,Reach-1         ,9453
    1322    1849    2293    2074    2805    3794    4185
Boundary for River Rch & Prof#=UNT0380 IN CEDR,Reach-1         , 1
Up Type= 0
Dn Type= 3
Dn Slope=0.00817
Boundary for River Rch & Prof#=UNT0380 IN CEDR,Reach-1         , 2
Up Type= 0
Dn Type= 3
Dn Slope=0.00817
Boundary for River Rch & Prof#=UNT0380 IN CEDR,Reach-1         , 3
Up Type= 0
Dn Type= 3
Dn Slope=0.00817
Boundary for River Rch & Prof#=UNT0380 IN CEDR,Reach-1         , 4
Up Type= 0
Dn Type= 3
Dn Slope=0.00817
Boundary for River Rch & Prof#=UNT0380 IN CEDR,Reach-1         , 5
Up Type= 0
Dn Type= 3
Dn Slope=0.00817
Boundary for River Rch & Prof#=UNT0380 IN CEDR,Reach-1         , 6
Up Type= 0
Dn Type= 3
Dn Slope=0.00817
Boundary for River Rch & Prof#=UNT0380 IN CEDR,Reach-1         , 7
Up Type= 0
Dn Type= 3
Dn Slope=0.00817
DSS Import GetInterval= 0
DSS Import GetPeak= 0
DSS Import FillOption= 0

--- UNT0380 IN CEDR CR.g01 (geometry) ---

Geom Title=Existing Conditions
Program Version=4.10

River Reach=UNT0380 IN CEDR ,Reach-1
Reach XY= 30
      3587392.11     10380441.64      3587664.59     10380108.77
      3587642.11     10379891.64      3587692.11     10379841.64
      3587628.09     10379664.03      3587682.11     10378771.64
      3587794.32     10378396.89      3587793.46     10377641.68
      3587576.54     10377503.69      3587663.34     10376859.23
      3587669.42     10375980.32      3588155.53     10375009.14
      3588157.61      10374902.2        3588338.     10374721.64
      3588542.16     10374673.73      3588640.77     10374546.64
      3588588.69     10374465.39      3588753.27     10374412.62
      3588865.18     10374233.71      3589092.11      10374036.6
      3589080.03     10373918.01      3589007.15     10373855.08
      3589014.26      10373757.3      3589264.55     10373468.99
      3589379.07     10373419.86      3589353.03      10373138.4
      3589407.22     10373070.88      3589397.96     10372802.17
      3589550.49     10372676.07      3589452.11     10372311.64

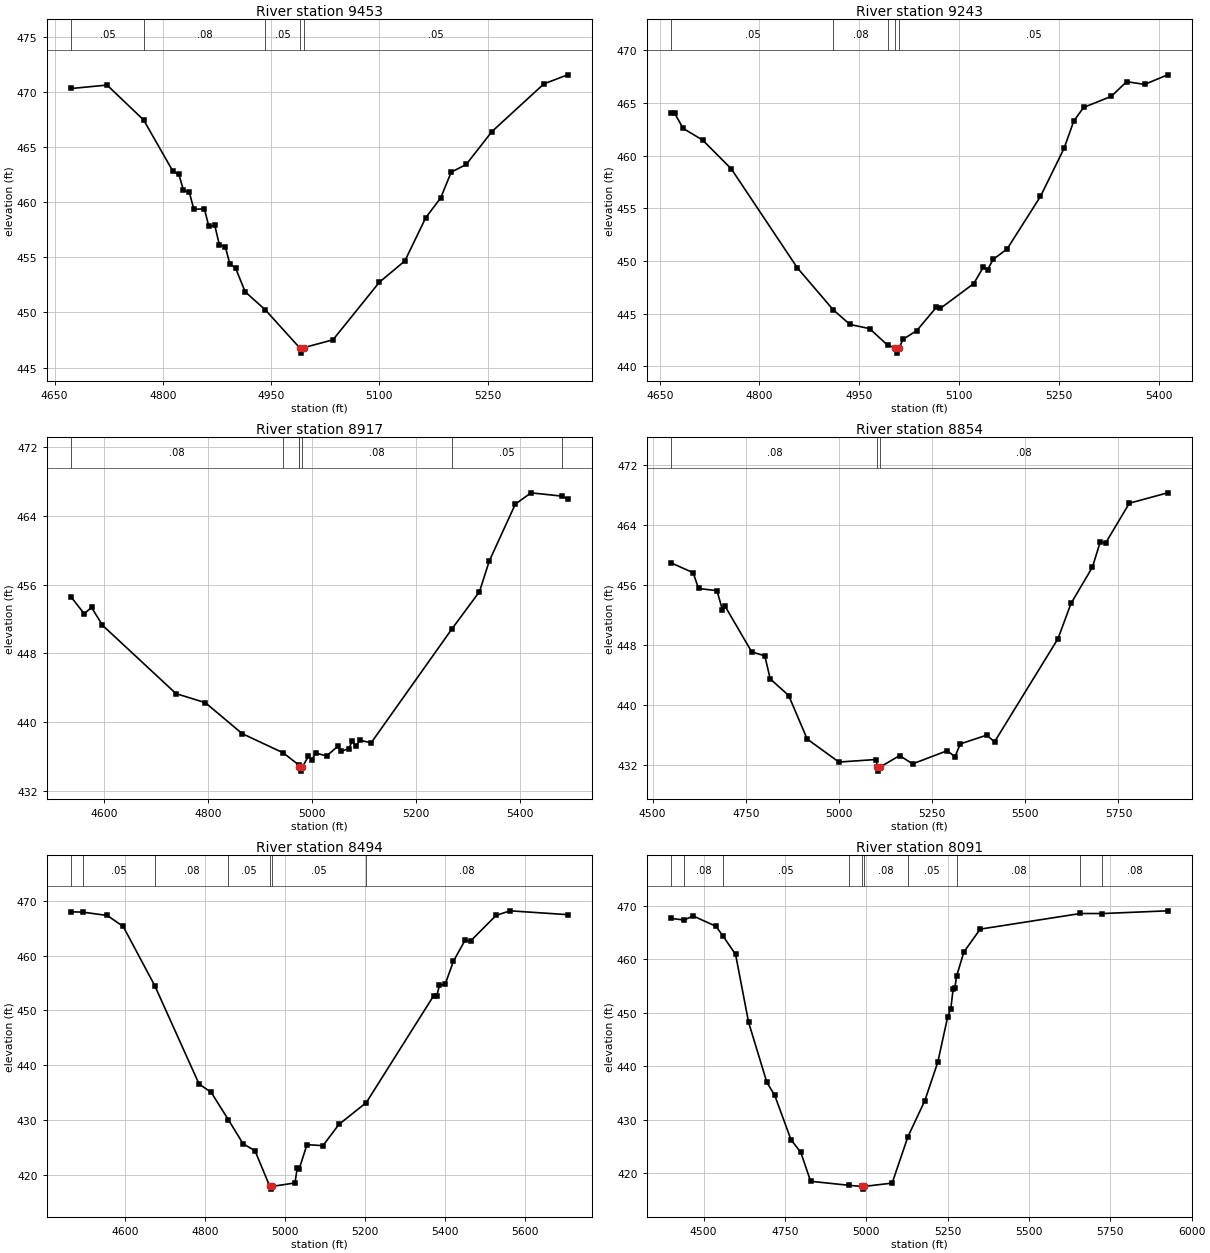
Type RM Length L Ch R = 1 ,9453    ,210,210,210
BEGIN DESCRIPTION:
Mapping XS 9317187f
END DESCRIPTION:
XS GIS Cut Line= 2
      3587732.21     10380559.82      3587189.24     10380137.95
#Sta/Elev= 30
  4673.4  470.34  4722.7  470.65  4773.4  467.48  4814.1  462.81  4822.2  462.55
  4828.6   461.1  4836.7  460.92    4843  459.36  4857.5  459.42  4863.8  457.81
    4872  457.91  4878.3  456.15  4886.5  455.98  4892.8  454.44    4901     454
  4914.1  451.88    4942  450.24  4989.4  446.81  4992.1  446.31  4995.4  446.81
  5035.8  447.52  5100.1  452.75  5135.4  454.68  5164.3   458.6  5185.1  460.41
  5199.6  462.74  5220.4  463.44  5256.1  466.43  5328.1  470.76    5361  471.58
#Mann= 5 ,-1 , 0
  4673.4     .05       0  4773.4     .08       0    4942     .05       0
  4989.4     .03       0  4995.4     .05       0
Bank Sta=4989.4,4995.4
XS Rating Curve= 0 ,0
Exp/Cntr=0.3,0.1

Type RM Length L Ch R = 1 ,9243    ,326,326,326
BEGIN DESCRIPTION:
Mapping XS b4700212
END DESCRIPTION:
XS GIS Cut Line= 2
      3587874.78     10380394.66      3587273.24     10379953.28
#Sta/Elev= 30
  4667.6  464.01  4672.4  464.01  4685.3  462.58  4714.6  461.47  4757.7  458.73
    4857  449.33  4910.9  445.35  4936.1  443.96  4965.5  443.57  4992.7  441.99
  5004.2  441.74  5006.9  441.24  5010.2  441.74  5015.6  442.54  5036.5  443.38
  5065.8  445.58    5072  445.49  5122.1  447.84  5136.8  449.42    5143  449.17
  5151.5  450.15  5172.3  451.13  5222.5  456.12    5258  460.69  5272.6  463.28
  5287.3  464.57    5329  465.63  5352.1  467.02  5379.2  466.76  5413.7  467.67
#Mann= 5 ,-1 , 0
  4667.6     .05       0  4910.9     .08       0  4992.7     .05       0
  5004.2    .035       0  5010.2     .05       0
Bank Sta=5004.2,5010.2
XS Rating Curve= 0 ,0
Exp/Cntr=0.3,0.1

Type RM Length L Ch R = 1 ,8917    ,63,63,63
BEGIN DESCRIPTION:
Mapping XS 11df8300
END DESCRIPTION:
XS GIS Cut Line= 3
      3587974.83     10380213.52      3587561.61      10379814.2
       3587181.4     10379800.31
#Sta/Elev= 30
  4537.3  454.49  4561.8   452.6  4575.9  453.33    4597  451.25  4738.5  443.29
  4795.1  442.23  4865.8  438.63  4944.6   436.4  4974.6  434.99    4976  434.76
  4978.8  434.26    4982  434.76  4993.2  435.98  5000.1  435.55  5007.3  436.37
  5028.4  436.03  5049.8  437.14  5056.7  436.57  5070.9  436.88  5078.1  437.78
    5085  437.14  5092.2  437.86  5114.2  437.56  5269.2  450.79  5322.7  455.17
  5341.6  458.75  5391.6  465.35  5421.7  466.68  5480.8   466.3  5492.4  465.96
#Mann= 7 ,-1 , 0
  4537.3     .08       0  4944.6     .05       0  4974.6     .08       0
    4976     .07       0    4982     .08       0  5269.2     .05       0
  5480.8     .08       0
Bank Sta=4976,4982
XS Rating Curve= 0 ,0
Exp/Cntr=0.3,0.1

Type RM Length L Ch R = 1 ,8854    ,360,360,360
BEGIN DESCRIPTION:
Mapping XS 1b90aace
END DESCRIPTION:
XS GIS Cut Line= 4
      3588033.81     10380131.88      3587764.74     10379918.36
      3587236.96     10379433.99      3587028.66      10379260.4
#Sta/Elev= 30
  4550.8  458.92    4609  457.62  4623.4  455.52    4673  455.23  4687.5  452.68
  4693.9  453.22    4766  447.07  4801.2  446.54  4815.7  443.47  4865.3  441.24
  4914.9  435.44    5000  432.37  5099.3  432.71  5103.1  431.66  5105.8  431.16
  5109.1  431.66  5162.8  433.23  5197.9  432.13  5290.4  433.88  5311.4  433.08
  5325.6  434.79  5396.5  435.96  5417.4  435.06  5587.6  448.82  5622.8  453.54
  5680.1  458.37  5700.9  461.71  5715.2  461.56    5779  466.89  5881.8  468.28
#Mann= 3 ,-1 , 0
  4550.8     .08       0  5103.1     .07       0  5109.1     .08       0
Bank Sta=5103.1,5109.1
XS Rating Curve= 0 ,0
Exp/Cntr=0.3,0.1

Type RM Length L Ch R = 1 ,8494    ,403,403,403
BEGIN DESCRIPTION:
Mapping XS ed6c84e3
END DESCRIPTION:
XS GIS Cut Line= 3
      3588171.49     10379537.36      3587412.78     10379509.58
      3587039.51     10379202.28
#Sta/Elev= 30
  4465.1     468  4493.6  467.94  4554.5  467.33  4594.6  465.33  4673.8  454.49
  4784.7  436.53  4814.7  435.04  4857.8  430.04  4894.8  425.63  4924.8  424.33
  4961.8  417.83  4964.6  417.33  4967.8  417.83  5024.9  418.46  5030.6  421.23
  5035.6  421.06  5054.9  425.46  5094.9  425.27  5134.9  429.15  5203.6  433.15
  5372.3  452.68  5380.2  452.68  5386.7  454.57    5401  454.75  5421.8  458.98
  5450.5  462.76  5464.9  462.68  5528.7  467.36  5563.9  468.18  5707.8  467.48
#Mann= 7 ,-1 , 0
  4465.1     .08       0  4493.6     .05       0  4673.8     .08       0
  4857.8     .05       0  4961.8     .04       0  4967.8     .05       0
  5203.6     .08       0
Bank Sta=4961.8,4967.8
XS Rating Curve= 0 ,0
Exp/Cntr=0.3,0.1

Type RM Length L Ch R = 1 ,8091    ,595,595,595
BEGIN DESCRIPTION:
Mapping XS 98f41786
END DESCRIPTION:
XS GIS Cut Line= 2
      3588258.74     10379157.15      3586737.45     10379050.81
#Sta/Elev= 30
  4401.1  467.68  4439.9  467.39  4467.9  468.15  4538.1   466.2  4558.8  464.46
  4598.2  460.94  4638.3  448.21  4694.3  436.98  4718.5  434.55  4768.6  426.22
  4798.7  423.86  4828.8  418.45  4947.4  417.69  4986.2  417.48  4988.9  416.98
  4992.2  417.48  5079.4  418.11  5127.9   426.8  5179.6  433.51  5219.7  440.77
  5249.8  449.17  5259.8  450.81  5266.9  454.46  5271.9  454.62  5277.6  456.89
  5299.9   461.4    5350  465.68  5658.3  468.61  5725.5   468.6  5926.1  469.11
#Mann= 10 ,-1 , 0
  4401.1     .05       0  4439.9     .08       0  4558.8     .05       0
  4947.4     .08       0  4986.2     .07       0  4992.2     .08       0
  5127.9     .05       0  5277.6     .08       0  5658.3     .05       0
  5725.5     .08       0
Bank Sta=4986.2,4992.2
XS Rating Curve= 0 ,0
Exp/Cntr=0.3,0.1

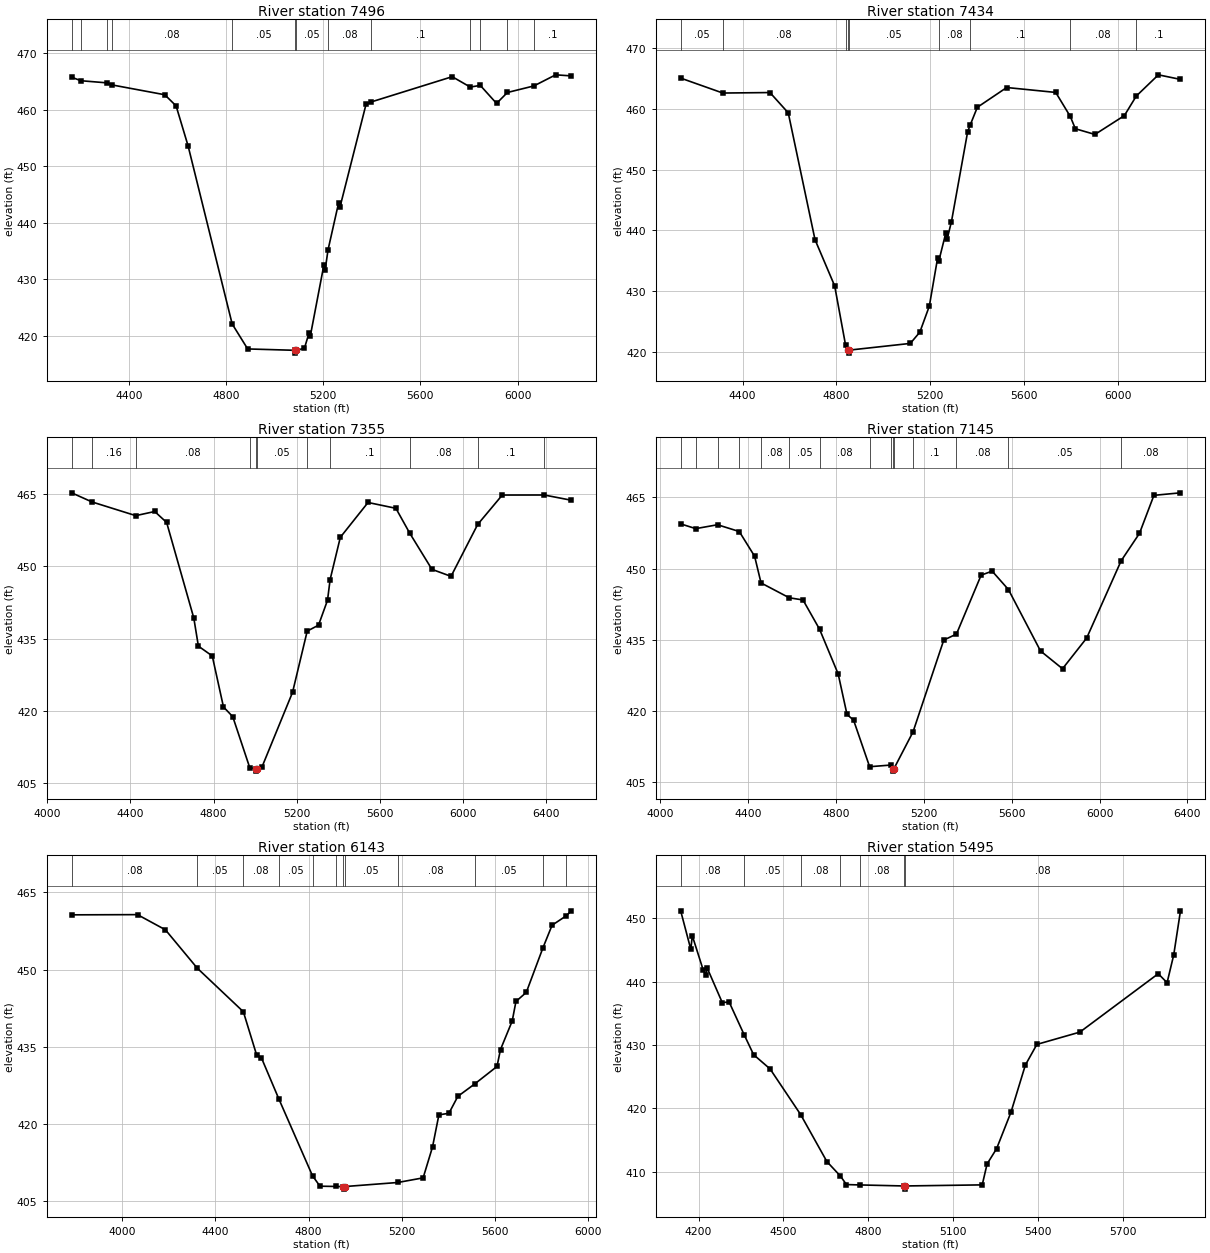
Type RM Length L Ch R = 1 ,7496    ,62,62,62
BEGIN DESCRIPTION:
Mapping XS 23642809
END DESCRIPTION:
XS GIS Cut Line= 3
      3588551.67     10378825.12      3587670.59      10378499.6
      3586568.21     10378684.05
#Sta/Elev= 30
  4164.8  465.73  4202.5  465.11  4310.4  464.73  4331.7  464.36  4548.1  462.63
  4594.7  460.66  4644.1  453.59  4825.4  422.14  4889.3  417.72  5082.1  417.48
  5084.9  416.98  5088.1  417.48  5122.8  417.83  5142.4  420.61  5147.5  420.08
  5203.1  432.58  5208.2  431.68    5220  435.21  5263.8  443.57  5268.9  442.73
  5376.3  460.91  5395.6  461.33  5731.2  465.82  5805.4  463.99  5846.8  464.28
  5913.7   461.1  5958.4  463.03  6067.5  464.19    6157  466.15  6221.8  465.96
#Mann= 13 ,-1 , 0
  4164.8     .05       0  4202.5     .08       0  4310.4     .05       0
  4331.7     .08       0  4825.4     .05       0  5082.1    .033       0
  5088.1     .05       0    5220     .08       0  5395.6      .1       0
  5805.4     .08       0  5846.8      .1       0  5958.4     .08       0
  6067.5      .1       0
Bank Sta=5082.1,5088.1
XS Rating Curve= 0 ,0
Exp/Cntr=0.3,0.1

Type RM Length L Ch R = 1 ,7434    ,79,79,79
BEGIN DESCRIPTION:
Mapping XS 00424dfd
END DESCRIPTION:
XS GIS Cut Line= 4
      3588588.52     10378777.36      3587907.14     10378508.28
      3587499.15     10378401.94      3586550.76     10378631.99
#Sta/Elev= 30
  4136.4  465.06    4316   462.6  4516.9  462.68  4594.9  459.34  4708.9  438.46
  4792.8  430.83    4839  421.13  4849.9  420.26  4852.6  419.76  4855.9  420.26
  5115.2  421.36  5155.7  423.21  5196.2   427.5  5231.5  435.42  5236.9  434.97
  5266.8   439.6    5272  438.52  5290.6  441.43  5359.6  456.23  5370.8  457.37
  5400.8  460.25    5526  463.51    5735   462.7  5797.1  458.74  5818.6  456.72
  5902.1  455.78  6027.5  458.88  6078.3   462.1  6172.5   465.6  6266.5  464.85
#Mann= 9 ,-1 , 0
  4136.4     .05       0    4316     .08       0    4839     .05       0
  4849.9    .033       0  4855.9     .05       0  5236.9     .08       0
  5370.8      .1       0  5797.1     .08       0  6078.3      .1       0
Bank Sta=4849.9,4855.9
XS Rating Curve= 0 ,0
Exp/Cntr=0.3,0.1

Type RM Length L Ch R = 1 ,7355    ,210,210,210
BEGIN DESCRIPTION:
Mapping XS 7bc75afc
END DESCRIPTION:
XS GIS Cut Line= 4
      3588608.13     10378731.82      3587907.14     10378417.13
      3587496.98     10378345.52      3586307.72     10378612.45
#Sta/Elev= 30
    4117   465.2  4214.9  463.31  4425.4  460.47  4516.5  461.33  4573.8  459.06
  4704.6  439.23  4726.5  433.43  4793.3  431.39  4847.1  420.83  4891.9   418.8
  4973.9  408.19  5002.9  408.02  5005.6  407.52  5008.9  408.02  5032.6   408.4
  5179.4  423.85  5249.9  436.54  5304.3  437.77  5347.6  442.94  5360.1  447.23
  5409.2  455.98  5542.5   463.2  5676.5  461.99  5742.7  456.86  5849.8  449.34
  5941.6  447.89  6069.9  458.65  6188.1  464.74  6389.9  464.75  6520.6  463.66
#Mann= 11 ,-1 , 0
    4117     .05       0  4214.9     .16       0  4425.4     .08       0
  4973.9     .05       0  5002.9     .04       0  5008.9     .05       0
  5249.9     .08       0  5360.1      .1       0  5742.7     .08       0
  6069.9      .1       0  6389.9     .08       0
Bank Sta=5002.9,5008.9
XS Rating Curve= 0 ,0
Exp/Cntr=0.3,0.1

Type RM Length L Ch R = 1 ,7145    ,1002,1002,1002
BEGIN DESCRIPTION:
Mapping XS 1ea62e0e
END DESCRIPTION:
XS GIS Cut Line= 3
      3588708.26     10378184.84      3588234.41     10378198.94
      3586435.94     10378153.62
#Sta/Elev= 30
  4094.8  459.43  4163.4  458.43  4262.4  459.25  4361.3  457.82  4431.1  452.61
  4460.3  446.98  4588.7  443.85  4651.2  443.39  4726.6  437.21  4811.2  427.79
  4851.3  419.26  4881.3  418.04  4954.2  408.23    5053  408.59  5058.6   407.8
  5061.4   407.3  5064.6   407.8  5151.7  415.58  5291.4  434.93  5349.2   436.2
  5461.4  448.62  5511.5  449.47  5585.5  445.59  5731.5  432.64  5831.6  428.89
  5941.6  435.37  6098.1  451.64  6181.7  457.44  6247.3  465.45  6367.9  465.98
#Mann= 15 ,-1 , 0
  4094.8     .05       0  4163.4     .16       0  4262.4     .08       0
  4361.3     .05       0  4460.3     .08       0  4588.7     .05       0
  4726.6     .08       0  4954.2      .1       0    5053     .05       0
  5058.6     .07       0  5064.6     .05       0  5151.7      .1       0
  5349.2     .08       0  5585.5     .05       0  6098.1     .08       0
Bank Sta=5058.6,5064.6
XS Rating Curve= 0 ,0
Exp/Cntr=0.3,0.1

Type RM Length L Ch R = 1 ,6143    ,648,648,648
BEGIN DESCRIPTION:
Mapping XS e8a9fd83
END DESCRIPTION:
XS GIS Cut Line= 3
      3588815.08      10377406.2      3588315.45     10377397.66
      3586679.61     10377197.86
#Sta/Elev= 30
  3782.1  460.63  4065.1  460.67  4185.1  457.72  4321.9  450.27    4520   441.8
  4577.3  433.36  4597.5  432.86    4672  424.91  4817.2  409.92  4849.3   407.9
  4916.2  407.85  4949.6  407.83  4952.3  407.33  4955.6  407.83  5183.7  408.62
  5292.6  409.52  5332.9  415.52  5360.3  421.76  5403.4  422.07  5441.8  425.36
    5514  427.76  5609.9  431.16  5625.1  434.46  5675.4     440  5691.5   443.8
  5735.9  445.56  5807.8  454.26  5846.7  458.61  5906.8  460.42  5929.8  461.41
#Mann= 12 ,-1 , 0
  3782.1     .08       0  4321.9     .05       0    4520     .08       0
    4672     .05       0  4817.2     .08       0  4916.2     .05       0
  4949.6    .033       0  4955.6     .05       0  5183.7     .08       0
    5514     .05       0  5807.8     .08       0  5906.8     .05       0
Bank Sta=4949.6,4955.6
XS Rating Curve= 0 ,0
Exp/Cntr=0.3,0.1

Type RM Length L Ch R = 1 ,5495    ,37,37,37
BEGIN DESCRIPTION:
Mapping XS 2c58db4b
END DESCRIPTION:
XS GIS Cut Line= 3
      3588520.59      10376823.5      3586958.09      10376535.3
      3586786.67     10376583.79
#Sta/Elev= 30
  4136.8  451.17  4172.7  445.07  4177.8  447.26  4216.6  441.81  4225.7  441.06
  4230.8  442.13  4283.8   436.7  4308.1  436.79  4361.5   431.6  4394.8  428.47
  4452.9  426.23    4561  419.03  4653.9  411.61  4701.6  409.33  4722.9  407.99
  4770.8  407.93  4925.4  407.77  4928.2  407.27  4931.4  407.77    5203  407.94
  5220.2  411.24  5253.8  413.65  5304.7  419.41  5355.5  426.84  5396.2   430.1
  5548.3  432.04  5825.4  441.25  5856.6  439.83  5880.1  444.22  5903.8  451.12
#Mann= 7 ,-1 , 0
  4136.8     .08       0  4361.5     .05       0    4561     .08       0
  4701.6     .05       0  4770.8     .08       0  4925.4     .07       0
  4931.4     .08       0
Bank Sta=4925.4,4931.4
XS Rating Curve= 0 ,0
Exp/Cntr=0.3,0.1

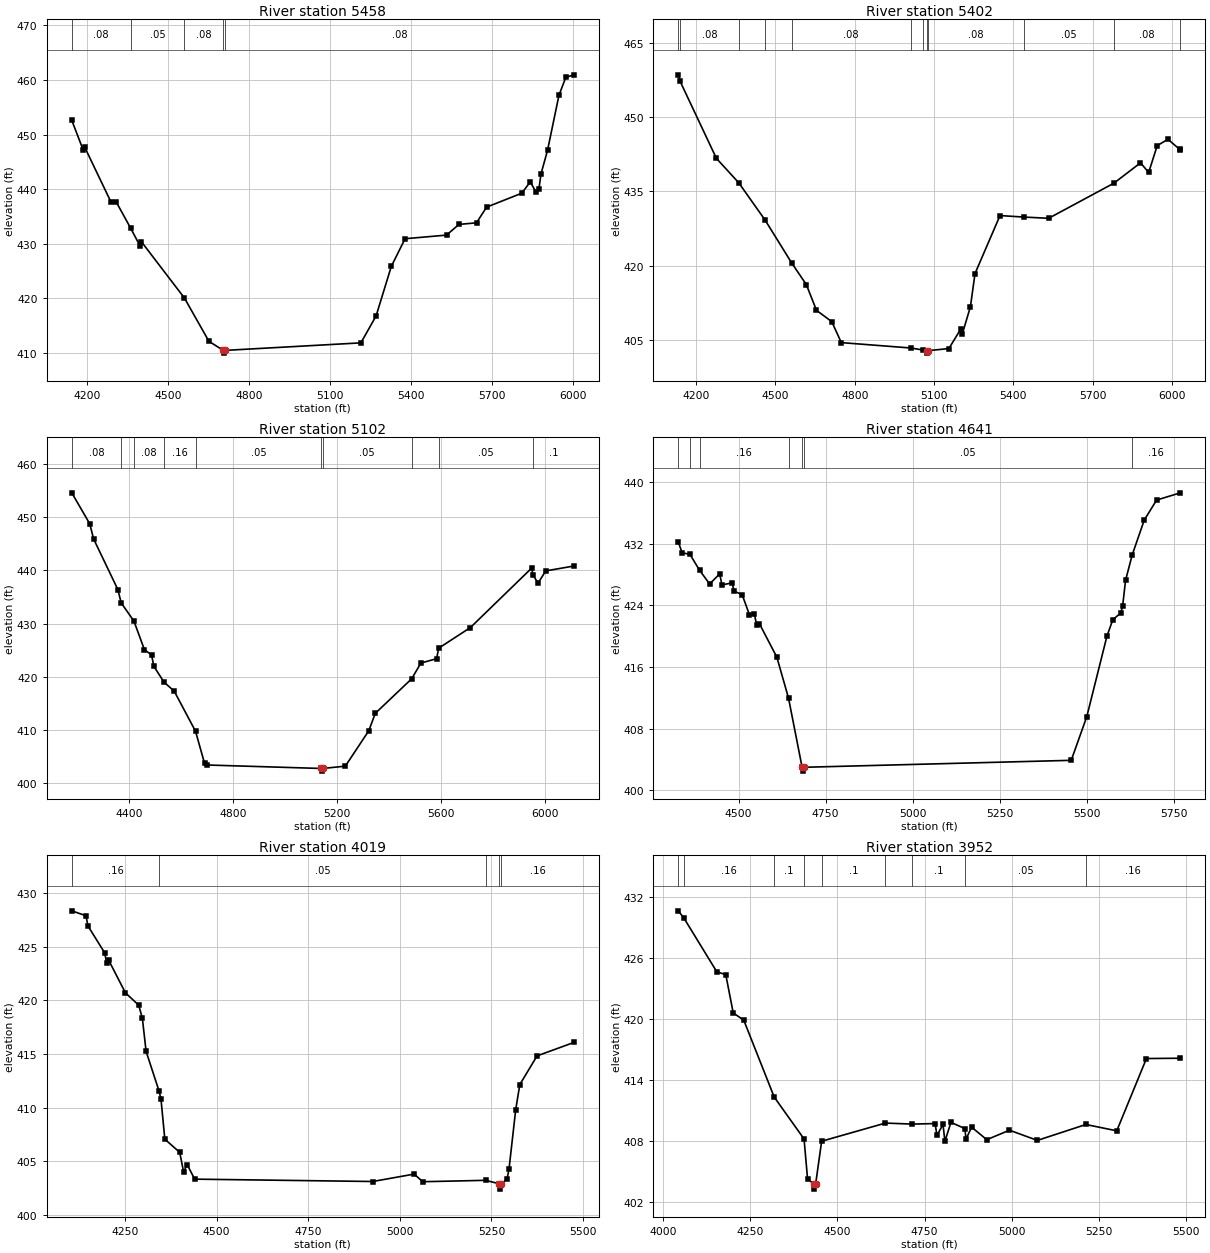
Type RM Length L Ch R = 1 ,5458    ,56,56,56
BEGIN DESCRIPTION:
Mapping XS 68e98f94
END DESCRIPTION:
XS GIS Cut Line= 3
      3588514.53     10376795.72      3586988.48     10376493.64
      3586700.18     10376597.22
#Sta/Elev= 30
  4142.5  452.61    4185  447.14  4190.1  447.72  4287.4  437.69  4308.1  437.59
  4360.4  432.89    4395  429.66  4400.1  430.41  4560.3  420.06  4651.2  412.13
  4704.5  410.47  4707.2  409.97  4710.5  410.47  5214.7  411.85  5271.1  416.78
  5327.5  425.85  5378.6  430.92  5532.3  431.58  5578.5  433.54  5643.5  433.83
  5680.9   436.7  5811.2  439.25  5843.1  441.34  5864.3  439.41  5874.9  439.95
  5882.4  442.74  5906.8  447.08  5949.3  457.19  5974.6  460.46  6004.5  460.93
#Mann= 5 ,-1 , 0
  4142.5     .08       0  4360.4     .05       0  4560.3     .08       0
  4704.5     .07       0  4710.5     .08       0
Bank Sta=4704.5,4710.5
XS Rating Curve= 0 ,0
Exp/Cntr=0.3,0.1

Type RM Length L Ch R = 1 ,5402    ,300,300,300
BEGIN DESCRIPTION:
Mapping XS e8cd161d
END DESCRIPTION:
XS GIS Cut Line= 3
       3588528.4     10376733.22      3586967.64     10376441.55
      3586666.33     10376519.48
#Sta/Elev= 30
  4132.6  458.52  4138.9   457.3  4276.8  441.69  4361.6  436.74  4461.4  429.21
  4561.2  420.62  4617.1  416.22  4655.5  411.03  4713.3  408.75  4749.4  404.52
  5011.1  403.44  5060.1  403.02  5071.9   402.9  5074.7   402.4  5077.9   402.9
  5156.3  403.32  5202.4  407.36  5207.5  406.35  5237.7  411.76  5255.1  418.44
  5349.6  430.14  5438.9  429.84  5533.6  429.59  5780.1  436.66    5881  440.77
    5912  438.84  5944.3  444.25  5984.9  445.52  6029.6  443.47  6031.6  443.34
#Mann= 12 ,-1 , 0
  4132.6     .16       0  4138.9     .08       0  4361.6     .05       0
  4461.4     .16       0  4561.2     .08       0  5011.1     .05       0
  5060.1     .08       0  5071.9     .07       0  5077.9     .08       0
  5438.9     .05       0  5780.1     .08       0  6029.6      .1       0
Bank Sta=5071.9,5077.9
XS Rating Curve= 0 ,0
Exp/Cntr=0.3,0.1

Type RM Length L Ch R = 1 ,5102    ,461,461,461
BEGIN DESCRIPTION:
Mapping XS 22f5c40b
END DESCRIPTION:
XS GIS Cut Line= 4
      3588416.07     10376503.87      3588035.87     10376251.28
      3586900.61     10376323.95      3586587.95     10376446.59
#Sta/Elev= 30
  4180.1  454.55  4249.1  448.75  4264.2  445.88  4357.4  436.38    4370   433.9
  4419.1  430.47  4459.6  425.08  4486.7  424.14  4495.7  421.98  4534.7  419.02
  4573.9  417.33  4655.9  409.79  4690.4  403.79  4700.5  403.47  5138.4  402.82
  5141.1  402.32  5144.4  402.82  5231.5  403.25  5321.7  409.89  5346.7  413.16
  5486.6  419.65  5522.1   422.6  5582.3  423.42  5590.6   425.4  5712.5  429.27
  5947.8  440.42  5952.8  439.18  5972.2  437.59    6002   439.9    6110  440.81
#Mann= 10 ,-1 , 0
  4180.1     .08       0    4370     .16       0  4419.1     .08       0
  4534.7     .16       0  4655.9     .05       0  5138.4    .033       0
  5144.4     .05       0  5486.6     .08       0  5590.6     .05       0
  5952.8      .1       0
Bank Sta=5138.4,5144.4
XS Rating Curve= 0 ,0
Exp/Cntr=0.3,0.1

Type RM Length L Ch R = 1 ,4641    ,622,622,622
BEGIN DESCRIPTION:
Mapping XS 1b77ee26
END DESCRIPTION:
XS GIS Cut Line= 3
      3588261.91     10376228.33      3588083.93     10375998.26
      3587050.92     10375492.61
#Sta/Elev= 30
    4327  432.21  4338.3  430.79  4360.6   430.6  4388.1  428.54  4417.1  426.76
  4446.1  428.07  4452.4  426.63  4481.4   426.9  4487.7  425.81  4510.4  425.38
  4531.2  422.78  4545.7  422.83    4552  421.44  4560.2  421.59    4610  417.27
  4643.5  411.97  4682.5     403  4685.2   402.5  4688.5     403  5454.9   403.9
  5499.5  409.55  5557.4  419.99  5574.4  422.14  5596.9  422.98  5602.4  423.87
  5610.8  427.22    5630  430.53  5664.4  435.03  5699.9  437.63    5768  438.57
#Mann= 7 ,-1 , 0
    4327     .16       0  4360.6     .05       0  4388.1     .16       0
  4643.5     .05       0  4682.5    .033       0  4688.5     .05       0
    5630     .16       0
Bank Sta=4682.5,4688.5
XS Rating Curve= 0 ,0
Exp/Cntr=0.3,0.1

Type RM Length L Ch R = 1 ,4019    ,67,67,67
BEGIN DESCRIPTION:
Mapping XS bd848b9a
END DESCRIPTION:
XS GIS Cut Line= 4
      3588185.49     10376070.64      3588117.78     10375728.64
      3588147.29      10375327.6      3587576.15     10375087.03
#Sta/Elev= 30
  4104.5  428.34  4143.4  427.88  4148.5  426.94  4194.6  424.41  4199.7  423.46
  4205.4  423.73    4251   420.7    4287  419.56  4297.1  418.36  4307.4  415.25
  4342.7  411.56  4348.1  410.78  4358.5  407.07  4399.1  405.85  4409.8  404.02
  4419.5  404.71  4439.9  403.35    4926  403.13    5039  403.82  5062.7  403.11
  5234.3  403.24  5271.3  402.92    5274  402.42  5277.3  402.92  5292.6  403.36
    5298  404.28  5316.3  409.82  5327.5  412.16  5374.6  414.83    5475  416.08
#Mann= 5 ,-1 , 0
  4104.5     .16       0  4342.7     .05       0  5234.3     .16       0
  5271.3    .033       0  5277.3     .16       0
Bank Sta=5271.3,5277.3
XS Rating Curve= 0 ,0
Exp/Cntr=0.3,0.1

Type RM Length L Ch R = 1 ,3952    ,162,162,162
BEGIN DESCRIPTION:
Mapping XS 6caa3668
END DESCRIPTION:
XS GIS Cut Line= 6
      3588233.05     10376074.07      3588172.28     10375822.31
      3588224.37     10375409.98      3588161.43     10375277.61
      3587979.14     10375175.61      3587590.64     10375049.72
#Sta/Elev= 30
  4043.9   430.6  4059.8  429.91  4154.4  424.62  4180.1  424.34  4201.5  420.58
  4231.6  419.88  4318.9  412.33  4404.4  408.22  4414.4  404.33  4431.6   403.8
  4434.3   403.3  4437.6   403.8  4454.8     408  4637.7  409.78  4712.8  409.68
  4779.8  409.73  4785.3  408.57  4802.5  409.65    4808  407.99  4825.2  409.85
  4865.3  409.24  4868.5   408.2  4884.5  409.38  4927.9  408.15    4993  409.08
  5072.9  408.08  5211.9  409.64  5300.4  409.02  5385.4  416.11  5482.5  416.14
#Mann= 9 ,-1 , 0
  4043.9     .05       0  4059.8     .16       0  4318.9      .1       0
  4404.4    .033       0  4454.8      .1       0  4637.7     .05       0
  4712.8      .1       0  4865.3     .05       0  5211.9     .16       0
Bank Sta=4431.6,4437.6
XS Rating Curve= 0 ,0
Exp/Cntr=0.3,0.1

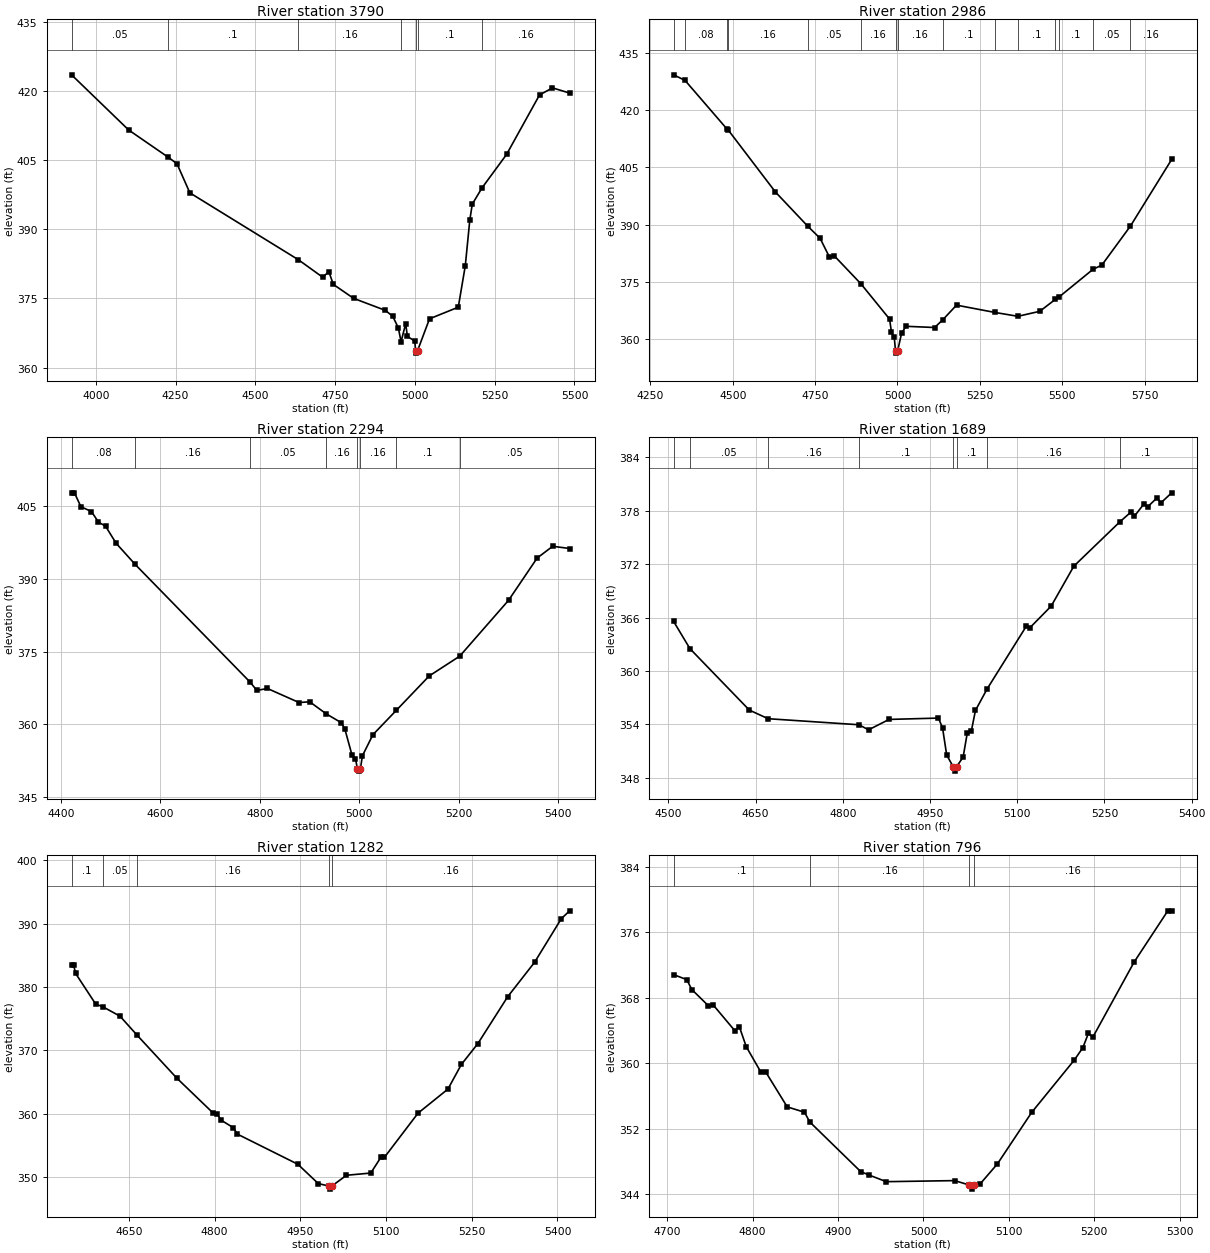
Type RM Length L Ch R = 1 ,3790    ,804,804,804
BEGIN DESCRIPTION:
Mapping XS f41c6021
END DESCRIPTION:
XS GIS Cut Line= 5
      3588335.81     10376008.79      3588276.78     10375585.17
      3588344.49     10375222.32      3588216.96     10375112.92
      3587674.54     10374866.07
#Sta/Elev= 30
  3924.1  423.46    4103   411.5  4226.6  405.61  4254.4  404.19  4294.8  397.87
  4634.6  383.38  4711.4  379.56  4730.2  380.81  4744.4  378.02  4808.1  374.99
  4907.4  372.39  4930.5  371.11  4948.1  368.61  4956.7  365.58  4971.1  369.51
  4976.6  366.75  4999.7  365.72  5002.2  363.62  5004.9  363.12  5008.2  363.62
  5045.8  370.56    5136  373.08    5158  382.09  5172.1  391.99  5179.9  395.43
  5210.4  398.95  5287.3   406.2  5390.6   419.1  5431.2  420.63  5484.9  419.51
#Mann= 7 ,-1 , 0
  3924.1     .05       0  4226.6      .1       0  4634.6     .16       0
  4956.7      .1       0  5002.2     .07       0  5008.2      .1       0
  5210.4     .16       0
Bank Sta=5002.2,5008.2
XS Rating Curve= 0 ,0
Exp/Cntr=0.3,0.1

Type RM Length L Ch R = 1 ,2986    ,692,692,692
BEGIN DESCRIPTION:
Mapping XS 1e9a73c5
END DESCRIPTION:
XS GIS Cut Line= 3
      3589063.37     10375082.76      3588782.09     10374707.73
      3587899.28     10374153.04
#Sta/Elev= 30
  4320.6  429.18  4355.2  427.73  4481.6   415.1  4485.4  414.85  4629.6  398.53
  4727.4  389.61  4765.1  386.43  4793.4  381.53  4808.7  381.79  4889.1  374.51
  4975.9  365.31  4981.8  361.86  4990.1  360.64  4994.1  356.89  4996.9  356.39
  5000.1  356.89  5012.4  361.58  5025.6  363.41  5112.6  363.09  5137.5  365.11
  5179.1  368.94  5294.5  367.05  5365.3  366.02  5431.8  367.33  5479.2  370.46
  5491.3  371.14    5593  378.29  5620.2  379.42  5706.9  389.62    5832  407.04
#Mann= 15 ,-1 , 0
  4320.6     .05       0  4355.2     .08       0  4481.6     .05       0
  4485.4     .16       0  4727.4     .05       0  4889.1     .16       0
  4994.1     .07       0  5000.1     .16       0  5137.5      .1       0
  5294.5     .05       0  5365.3      .1       0  5479.2     .05       0
  5491.3      .1       0    5593     .05       0  5706.9     .16       0
Bank Sta=4994.1,5000.1
XS Rating Curve= 0 ,0
Exp/Cntr=0.3,0.1

Type RM Length L Ch R = 1 ,2294    ,605,605,605
BEGIN DESCRIPTION:
Mapping XS c150feaa
END DESCRIPTION:
XS GIS Cut Line= 3
      3589365.41      10374574.9      3588821.15     10374043.66
      3588593.65     10373966.11
#Sta/Elev= 30
  4421.8  407.74  4427.6  407.74  4440.5  404.88  4461.8  403.88  4475.9  401.69
  4490.1  400.87  4511.2  397.36  4549.7  392.97  4780.8  368.69  4794.1     367
  4815.4   367.4    4879   364.5  4900.3  364.66  4933.6  362.17  4963.9  360.34
    4971  359.04  4985.2  353.73  4992.2  352.96  4996.3  350.86  4999.1  350.36
  5002.3  350.86  5006.3  353.53  5027.4  357.87  5074.4  362.89  5140.6  369.99
  5201.8  374.06    5300  385.58  5357.4  394.29  5388.7  396.72  5422.7  396.26
#Mann= 8 ,-1 , 0
  4421.8     .08       0  4549.7     .16       0  4780.8     .05       0
  4933.6     .16       0  4996.3     .07       0  5002.3     .16       0
  5074.4      .1       0  5201.8     .05       0
Bank Sta=4996.3,5002.3
XS Rating Curve= 0 ,0
Exp/Cntr=0.3,0.1

Type RM Length L Ch R = 1 ,1689    ,407,407,407
BEGIN DESCRIPTION:
UNT0380 IN CEDR CR 4.0
END DESCRIPTION:
XS GIS Cut Line= 3
      3589416.04     10374041.79      3589016.06     10373641.82
      3588888.24     10373380.57
#Sta/Elev= 30
  4509.1  365.58  4537.2  362.52  4639.3  355.62  4671.6  354.65    4828  353.97
  4844.3   353.4  4879.7  354.57  4964.5  354.72  4971.6  353.62  4978.7  350.58
  4989.8  349.26  4992.6  348.76  4995.8  349.26    5007  350.34    5014     353
  5021.1  353.26  5028.2  355.58  5048.1  357.98  5115.9  365.07  5121.5  364.85
  5158.4   367.3  5197.4  371.79  5276.5  376.77    5296  377.89  5301.5   377.4
  5318.5  378.83  5324.1  378.44    5341   379.5  5346.6  378.87  5365.6  380.03
#Mann= 8 ,-1 , 0
  4509.1      .1       0  4537.2     .05       0  4671.6     .16       0
    4828      .1       0  4989.8     .07       0  4995.8      .1       0
  5048.1     .16       0  5276.5      .1       0
Bank Sta=4989.8,4995.8
XS Rating Curve= 0 ,0
Exp/Cntr=0.3,0.1

Type RM Length L Ch R = 1 ,1282    ,486,486,486
BEGIN DESCRIPTION:
UNT0380 IN CEDR CR 3.0
END DESCRIPTION:
XS GIS Cut Line= 3
      3589692.13     10373741.67      3589291.86     10373371.84
      3588992.09     10373241.63
#Sta/Elev= 30
  4549.5  383.55  4552.9  383.55  4556.6  382.14  4591.8  377.29  4604.2  376.88
  4634.3  375.39  4664.2  372.39  4733.5  365.62    4797  360.11  4804.4  359.93
  4811.2  358.96  4832.8  357.76  4839.6  356.76  4945.6  351.99  4981.3  348.94
  4999.3  348.56  5002.1  348.06  5005.3  348.56  5030.7  350.25  5073.2   350.6
  5090.9  353.08  5097.1  353.08  5155.9  360.06  5208.3  363.87  5231.8  367.76
  5260.7  371.06    5313  378.48  5359.9   383.9  5406.8   390.8  5421.3  392.04
#Mann= 5 ,-1 , 0
  4549.5      .1       0  4604.2     .05       0  4664.2     .16       0
  4999.3     .07       0  5005.3     .16       0
Bank Sta=4999.3,5005.3
XS Rating Curve= 0 ,0
Exp/Cntr=0.3,0.1

Type RM Length L Ch R = 1 ,796     ,501,501,501
BEGIN DESCRIPTION:
UNT0380 IN CEDR CR 2.0
END DESCRIPTION:
XS GIS Cut Line= 3
      3589692.13     10373041.65      3589547.94      10372989.9
      3589118.22     10372998.58
#Sta/Elev= 30
  4707.5   370.8  4722.9  370.19  4728.8  368.98  4748.3  366.99  4753.6  367.13
  4779.1  363.96  4784.4  364.46  4792.5  362.01  4809.8  358.87  4815.1  358.95
  4840.5  354.65  4860.7     354  4866.9  352.81  4926.5  346.75  4936.5  346.32
  4956.5  345.52  5036.6  345.65  5053.6  345.11  5056.3  344.61  5059.6  345.11
  5066.6  345.28  5086.6   347.7  5126.6  353.97  5176.6  360.38  5186.6  361.89
  5193.1  363.65  5198.1  363.14  5246.6  372.34    5286  378.59  5290.5  378.59
#Mann= 4 ,-1 , 0
  4707.5      .1       0  4866.9     .16       0  5053.6     .07       0
  5059.6     .16       0
Bank Sta=5053.6,5059.6
XS Rating Curve= 0 ,0
Exp/Cntr=0.3,0.1

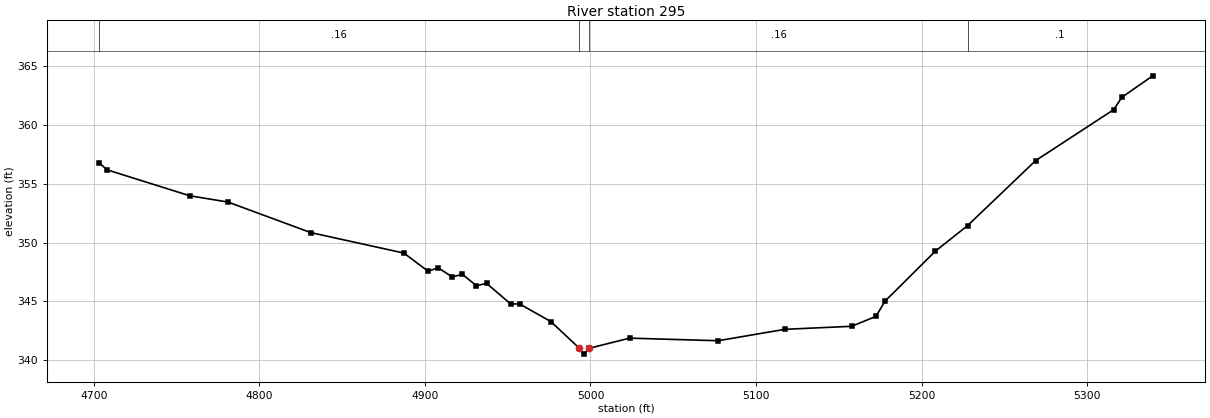
Type RM Length L Ch R = 1 ,295     ,0,0,0
BEGIN DESCRIPTION:
UNT0380 IN CEDR CR 1.0
END DESCRIPTION:
XS GIS Cut Line= 3
      3589774.59     10372726.73      3589574.57     10372576.71
      3589192.04     10372629.65
#Sta/Elev= 30
  4703.4  356.77  4708.1  356.19  4758.1  353.98  4781.1  353.45  4831.1  350.85
  4887.3  349.11  4901.9  347.57  4908.1  347.85  4916.5  347.08  4922.7   347.3
  4931.1  346.33  4937.3  346.53  4951.8  344.78  4957.2  344.78  4976.1  343.28
  4993.3  341.01    4996  340.51  4999.3  341.01  5023.7  341.87  5077.1  341.65
  5117.4  342.62  5157.8  342.88  5172.4  343.72    5178  345.03  5208.3  349.27
  5227.8  351.45  5268.9  356.98    5316  361.31    5321  362.37  5339.6  364.19
#Mann= 4 ,-1 , 0
  4703.4     .16       0  4993.3     .07       0  4999.3     .16       0
  5227.8      .1       0
Bank Sta=4993.3,4999.3
XS Rating Curve= 0 ,0
Exp/Cntr=0.3,0.1

Chan Stop Cuts=-1
Use User Specified Reach Order=0
Composite Channel Slope=5