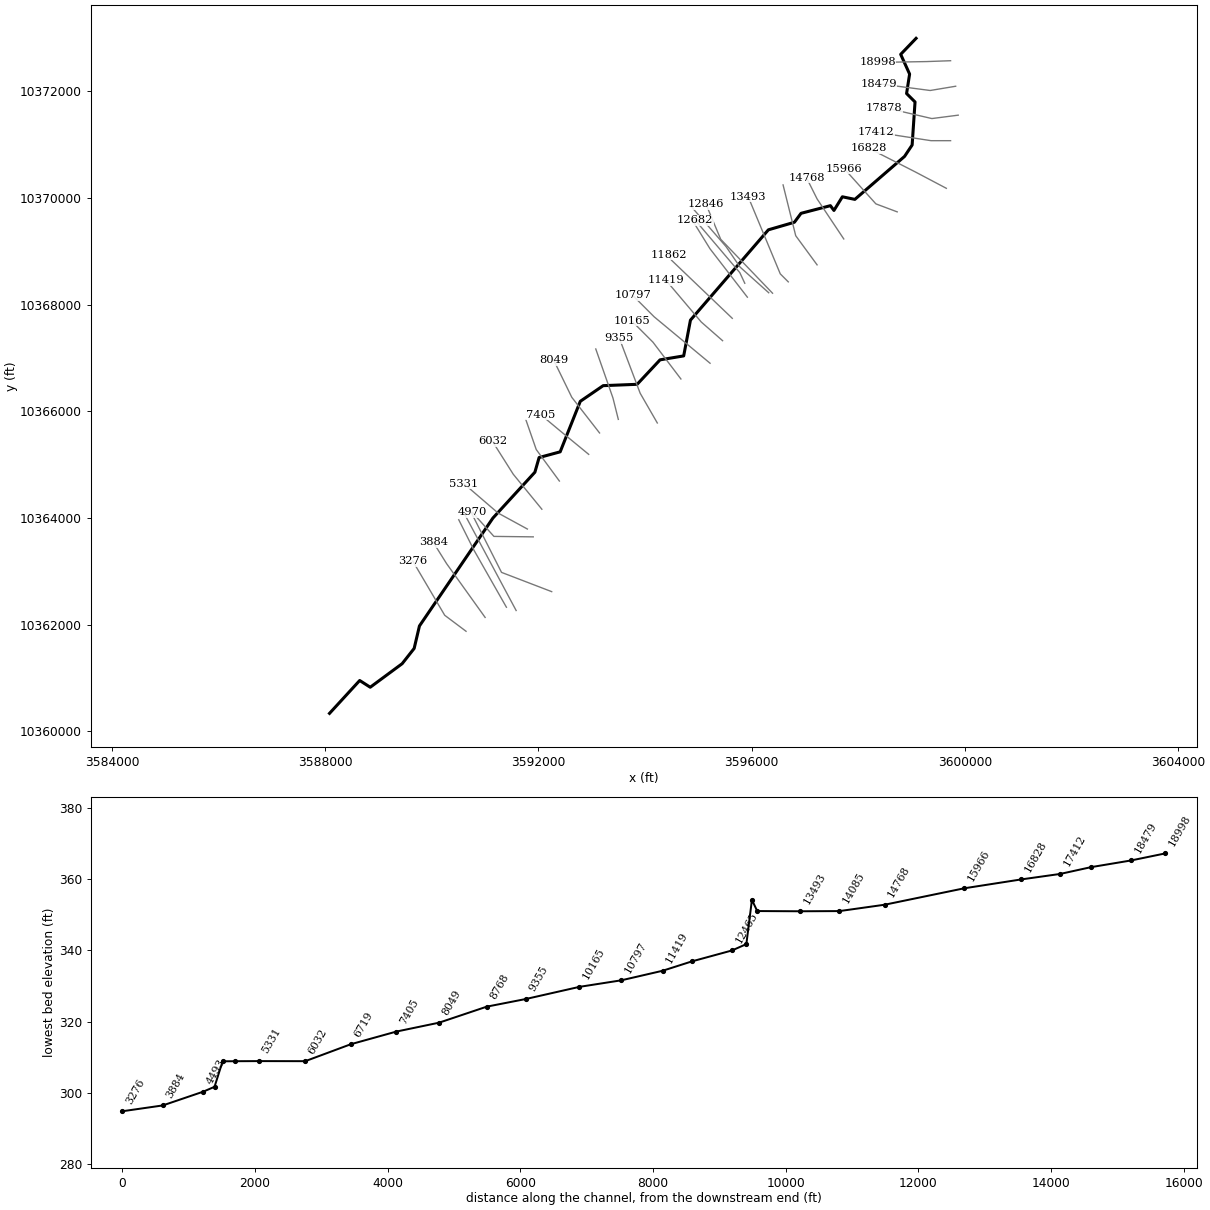
--- UNT0381 IN CEDR CR.prj (project) ---

Proj Title=UNT0381 IN CEDR CR Base Level Engineering
Current Plan=p01
Default Exp/Contr=0.3,0.1
English Units
Geom File=g01
Flow File=f01
Plan File=p01
Y Axis Title=Elevation
X Axis Title(PF)=Main Channel Distance
X Axis Title(XS)=Station
BEGIN DESCRIPTION:
UNT0381 IN CEDR CR
END DESCRIPTION:
DSS Export Rating Curves= 0
DSS Export Rating Curve Sorted= 0
DSS Export Volume Flow Curves= 0
DXF OffsetX= 0
DXF OffsetY= 0
DXF ScaleX= 1
DXF ScaleY= 10

--- UNT0381 IN CEDR CR.p01 (plan) ---

Plan Title=Multiple Run
Short Identifier=Multiple
Geom File=g01
Flow File=f01
Subcritical Flow
K Sum by GR= 0
Std Step Tol= 0.01
Critical Tol= 0.01
Num of Std Step Trials= 20
Max Error Tol= 0.3
Flow Tol Ratio= 0.001
Split Flow NTrial= 30
Split Flow Tol= 0.02
Split Flow Ratio= 0.02
Log Output Level= 0
Friction Slope Method= 1
Unsteady Friction Slope Method= 2
Unsteady Bridges Friction Slope Method= 1
Parabolic Critical Depth
Global Vel Dist=  1 , 1 , 1
Global Log Level= 0
CheckData=True
Encroach Param= -1, 0, 0, 0
BEGIN DESCRIPTION:
Multiple Run
END DESCRIPTION:

--- UNT0381 IN CEDR CR.f01 (steady flow) ---

Flow Title=Multiple
Number of Profiles=7
Profile Names=10-year,25-year,50-year,1pct_min,100-year,1pct_plu,500-year
River Rch & RM= UNT0381 IN CEDR ,Reach-1,18998
    1965    2811    3537    3243    4386    5931    6726
River Rch & RM= UNT0381 IN CEDR ,Reach-1,12766
    2557    3706    4705    4348    5880    7952    9163
River Rch & RM= UNT0381 IN CEDR ,Reach-1,7405
    2732    3967    5041    4663    6306    8528    9845
River Rch & RM= UNT0381 IN CEDR ,Reach-1,4970
    3237    4730    6037    5604    7579   10250   11919
Boundary for River Rch & Prof#=UNT0381 IN CEDR ,Reach-1,1
Up Type=0
Dn Type=3
Dn Slope=0.005
Boundary for River Rch & Prof#=UNT0381 IN CEDR ,Reach-1,2
Up Type=0
Dn Type=3
Dn Slope=0.005
Boundary for River Rch & Prof#=UNT0381 IN CEDR ,Reach-1,3
Up Type=0
Dn Type=3
Dn Slope=0.005
Boundary for River Rch & Prof#=UNT0381 IN CEDR ,Reach-1,4
Up Type=0
Dn Type=3
Dn Slope=0.005
Boundary for River Rch & Prof#=UNT0381 IN CEDR ,Reach-1,5
Up Type=0
Dn Type=3
Dn Slope=0.005
Boundary for River Rch & Prof#=UNT0381 IN CEDR ,Reach-1,6
Up Type=0
Dn Type=3
Dn Slope=0.005
Boundary for River Rch & Prof#=UNT0381 IN CEDR ,Reach-1,7
Up Type=0
Dn Type=3
Dn Slope=0.005

--- UNT0381 IN CEDR CR.g01 (geometry) ---

Geom Title=Existing Conditions
Program Version=4.10

River Reach=UNT0381 IN CEDR ,Reach-1
Reach XY= 30
      3599082.11     10372991.64      3598793.55     10372691.39
      3598960.76     10372321.83      3598904.03     10371956.87
      3599062.59      10371798.5      3599008.16     10370991.61
       3598865.8     10370777.72      3597933.97     10369972.24
      3597699.59     10370020.85      3597541.61     10369764.77
      3597475.63     10369854.18      3596924.42     10369710.95
      3596800.29     10369543.42      3596312.11     10369401.64
      3594850.36     10367707.95      3594723.61     10367037.59
      3594280.04     10366963.74      3593851.03     10366505.11
      3593213.53     10366479.76      3592784.27     10366185.92
      3592407.12       10365239.      3592011.94     10365132.09
      3591932.97     10364857.05      3591145.27     10363997.01
      3589767.79     10361974.32      3589668.68     10361553.15
      3589443.42     10361267.04       3588844.8     10360825.43
      3588647.12     10360951.91      3588081.11     10360335.42

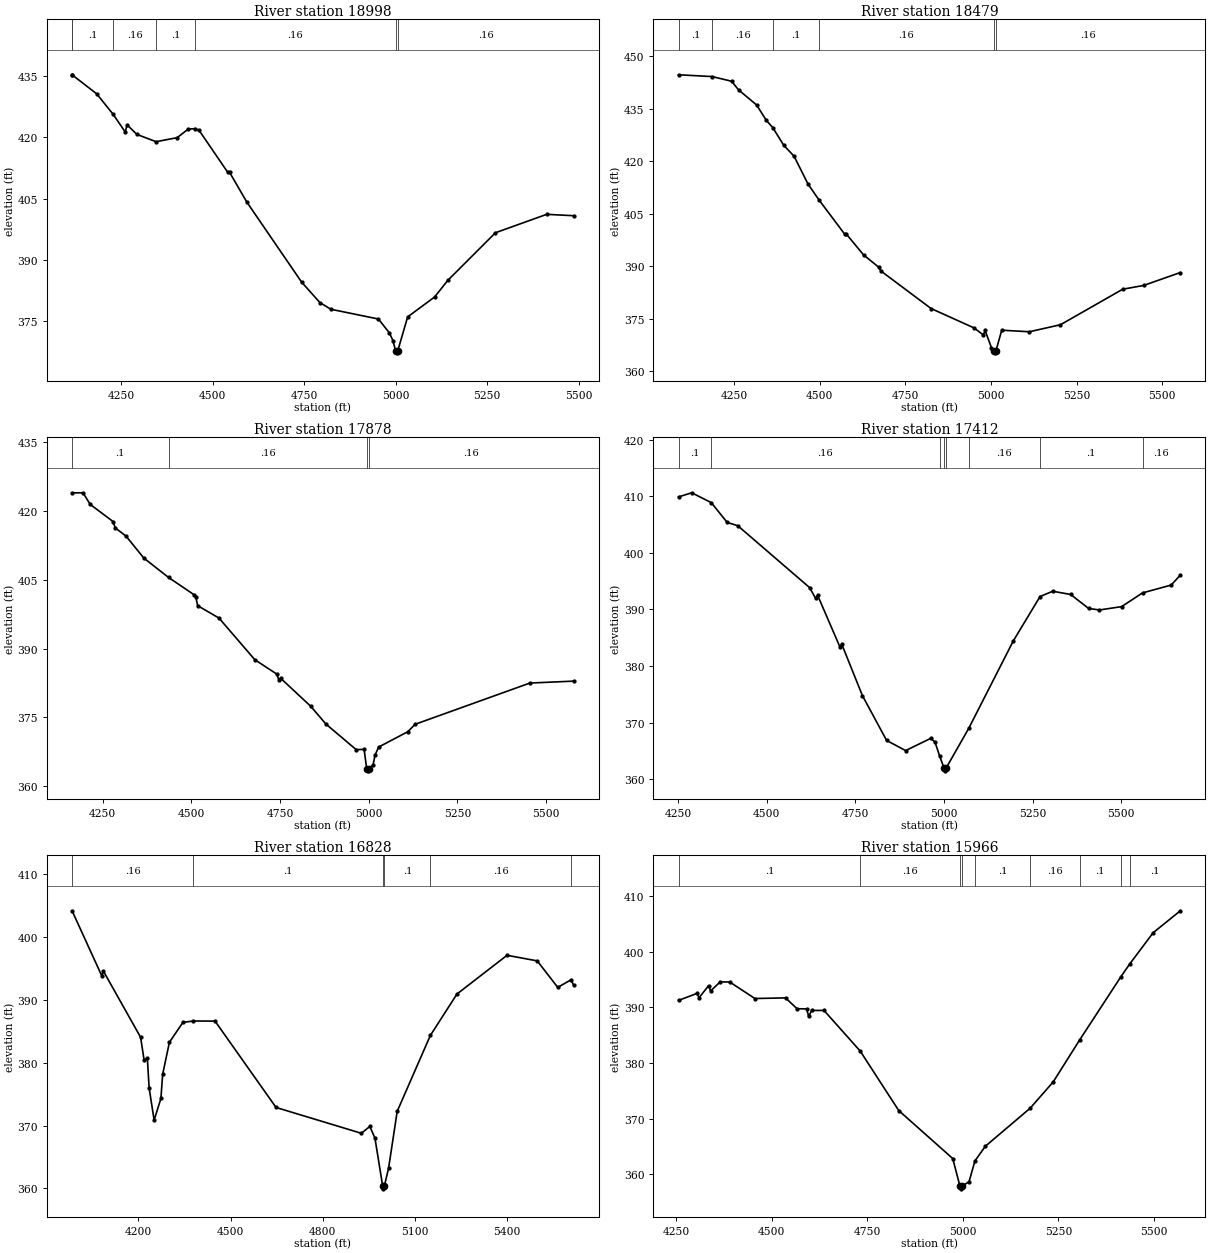
Type RM Length L Ch R = 1 ,18998   ,519,519,519
BEGIN DESCRIPTION:
UNT0381 IN CEDR CR 35.0
END DESCRIPTION:
XS GIS Cut Line= 3
      3599729.25     10372571.94       3599282.7       10372556.
      3598357.77     10372540.05
#Sta/Elev= 30
  4115.3  435.36  4116.2  435.29  4182.5   430.7  4227.2  425.72  4260.7  421.33
  4265.7  423.09  4292.6  420.74    4345  418.96  4402.6  419.95  4432.6  422.03
  4451.7  422.17  4462.7  421.73  4540.9  411.46  4545.9  411.46  4592.7  404.22
  4742.8  384.56  4792.8  379.54  4822.8   377.9  4952.8  375.51  4982.8  372.12
  4992.8  370.17  4999.8  367.72  5002.5  367.22  5005.8  367.72  5032.8  376.03
  5106.3  380.89  5142.8     385  5272.8  396.65  5412.9  401.16  5487.2  400.82
#Mann= 7 ,-1 , 0
  4115.3     .16       0  4116.2      .1       0  4227.2     .16       0
    4345      .1       0  4451.7     .16       0  4999.8     .07       0
  5005.8     .16       0
Bank Sta=4999.8,5005.8
XS Rating Curve= 0 ,0
Exp/Cntr=0.3,0.1

Type RM Length L Ch R = 1 ,18479   ,601,601,601
BEGIN DESCRIPTION:
UNT0381 IN CEDR CR 34.0
END DESCRIPTION:
XS GIS Cut Line= 3
      3599824.86     10372093.52      3599346.49     10372013.79
      3598375.38     10372141.15
#Sta/Elev= 30
  4088.1  444.74  4186.2  444.23    4243  442.89  4263.2  440.43  4315.7  436.13
  4344.3  431.71  4363.2  429.62    4395   424.6  4425.4  421.43    4466  413.49
  4497.5  409.02  4572.8  399.19  4577.8  399.19  4627.9  393.25  4672.6   389.7
  4678.3  388.66  4825.1   377.9  4950.7  372.35  4977.7  370.33  4982.7  371.65
  5001.1  366.75  5008.2  365.73  5010.9  365.23  5014.2  365.73  5031.3   371.7
    5112  371.26  5202.8  373.27  5384.3  383.42  5445.4   384.5  5552.5  388.19
#Mann= 6 ,-1 , 0
  4088.1      .1       0  4186.2     .16       0  4363.2      .1       0
  4497.5     .16       0  5008.2     .07       0  5014.2     .16       0
Bank Sta=5008.2,5014.2
XS Rating Curve= 0 ,0
Exp/Cntr=0.3,0.1

Type RM Length L Ch R = 1 ,17878   ,466,466,466
BEGIN DESCRIPTION:
UNT0381 IN CEDR CR 33.0
END DESCRIPTION:
XS GIS Cut Line= 3
      3599872.74     10371551.33      3599378.39     10371487.54
      3598486.26     10371694.64
#Sta/Elev= 30
  4163.8  423.96  4194.7  423.98  4214.9  421.45  4279.5   417.7  4285.4  416.33
  4315.7  414.55  4366.1  409.74  4435.7  405.52  4507.3  401.77  4512.6  401.28
  4517.7  399.37  4577.8  396.67    4679  387.58  4740.6  384.46  4746.2  383.26
  4751.4  383.57  4836.6  377.42  4879.3  373.56  4964.6  367.98  4986.9  368.04
  4994.2  363.86    4997  363.36  5000.2  363.86  5012.3  364.66  5017.7   366.8
    5028  368.55  5110.1  371.89  5130.7  373.51  5454.2   382.5  5578.1  382.92
#Mann= 4 ,-1 , 0
  4163.8      .1       0  4435.7     .16       0  4994.2     .07       0
  5000.2     .16       0
Bank Sta=4994.2,5000.2
XS Rating Curve= 0 ,0
Exp/Cntr=0.3,0.1

Type RM Length L Ch R = 1 ,17412   ,584,584,584
BEGIN DESCRIPTION:
UNT0381 IN CEDR CR 32.0
END DESCRIPTION:
XS GIS Cut Line= 3
      3599729.25     10371072.91      3599362.44     10371072.91
      3598326.54     10371232.28
#Sta/Elev= 30
  4251.6  409.91  4288.7  410.64  4343.9   408.9  4388.7   405.4  4418.7  404.81
  4621.1  393.87  4638.4  391.94  4643.5  392.54  4706.7  383.36  4711.8  383.86
    4770  374.77  4838.3  366.83  4891.9  365.03  4962.8   367.2  4974.8  366.53
  4987.6  364.11  5000.2  361.95    5003  361.45  5006.2  361.95    5070  368.98
  5195.5  384.43    5271  392.29  5306.8  393.22  5357.3  392.65  5407.9  390.18
  5438.3  389.91    5501   390.5  5559.9  392.93  5640.6  394.31  5666.5  396.07
#Mann= 8 ,-1 , 0
  4251.6      .1       0  4343.9     .16       0  4987.6      .1       0
  5000.2     .07       0  5006.2      .1       0    5070     .16       0
    5271      .1       0  5559.9     .16       0
Bank Sta=5000.2,5006.2
XS Rating Curve= 0 ,0
Exp/Cntr=0.3,0.1

Type RM Length L Ch R = 1 ,16828   ,862,862,862
BEGIN DESCRIPTION:
UNT0381 IN CEDR CR 31.0
END DESCRIPTION:
XS GIS Cut Line= 3
      3599649.45     10370179.89      3599075.39     10370482.87
      3598198.32     10370929.38
#Sta/Elev= 30
  3984.1  404.21  4080.7  393.86  4086.4  394.57  4207.2  384.06  4218.6  380.41
  4229.2   380.7  4234.9     376  4251.2  370.86  4273.3  374.32  4278.9  378.15
  4300.9  383.26    4345  386.44  4378.8  386.65  4449.4  386.64  4648.1  372.88
  4925.6  368.77  4953.4  369.86    4970  367.99  4994.9  360.42  4997.6  359.92
  5000.9  360.42  5014.5  363.26  5042.4  372.27  5150.3  384.35  5236.9  390.95
  5399.9  397.12  5498.2  396.23    5565  392.01  5607.8  393.21  5617.4  392.31
#Mann= 6 ,-1 , 0
  3984.1     .16       0  4378.8      .1       0  4994.9     .07       0
  5000.9      .1       0  5150.3     .16       0  5607.8      .1       0
Bank Sta=4994.9,5000.9
XS Rating Curve= 0 ,0
Exp/Cntr=0.3,0.1

Type RM Length L Ch R = 1 ,15966   ,1198,1198,1198
BEGIN DESCRIPTION:
UNT0381 IN CEDR CR 30.0
END DESCRIPTION:
XS GIS Cut Line= 3
       3598728.2     10369738.16      3598328.18     10369888.16
      3597736.46     10370545.96
#Sta/Elev= 30
  4256.7  391.27    4305  392.53  4310.3  391.74  4335.2  393.91  4340.6  392.97
  4365.5  394.59  4390.4  394.58  4456.3  391.61  4536.4  391.72  4566.6  389.78
  4591.6  389.74  4596.9  388.41    4605  389.46    4637  389.47  4731.7  382.17
  4832.4  371.49  4973.7  362.86  4992.4  357.92  4995.1  357.42  4998.4  357.92
  5016.3   358.7  5031.6  362.43  5058.9  365.07    5176   371.9  5236.1  376.61
  5305.9  384.21  5412.7  395.46  5437.2  397.89  5497.7  403.43  5568.7  407.37
#Mann= 9 ,-1 , 0
  4256.7      .1       0  4731.7     .16       0  4992.4     .07       0
  4998.4     .16       0  5031.6      .1       0    5176     .16       0
  5305.9      .1       0  5412.7     .16       0  5437.2      .1       0
Bank Sta=4992.4,4998.4
XS Rating Curve= 0 ,0
Exp/Cntr=0.3,0.1

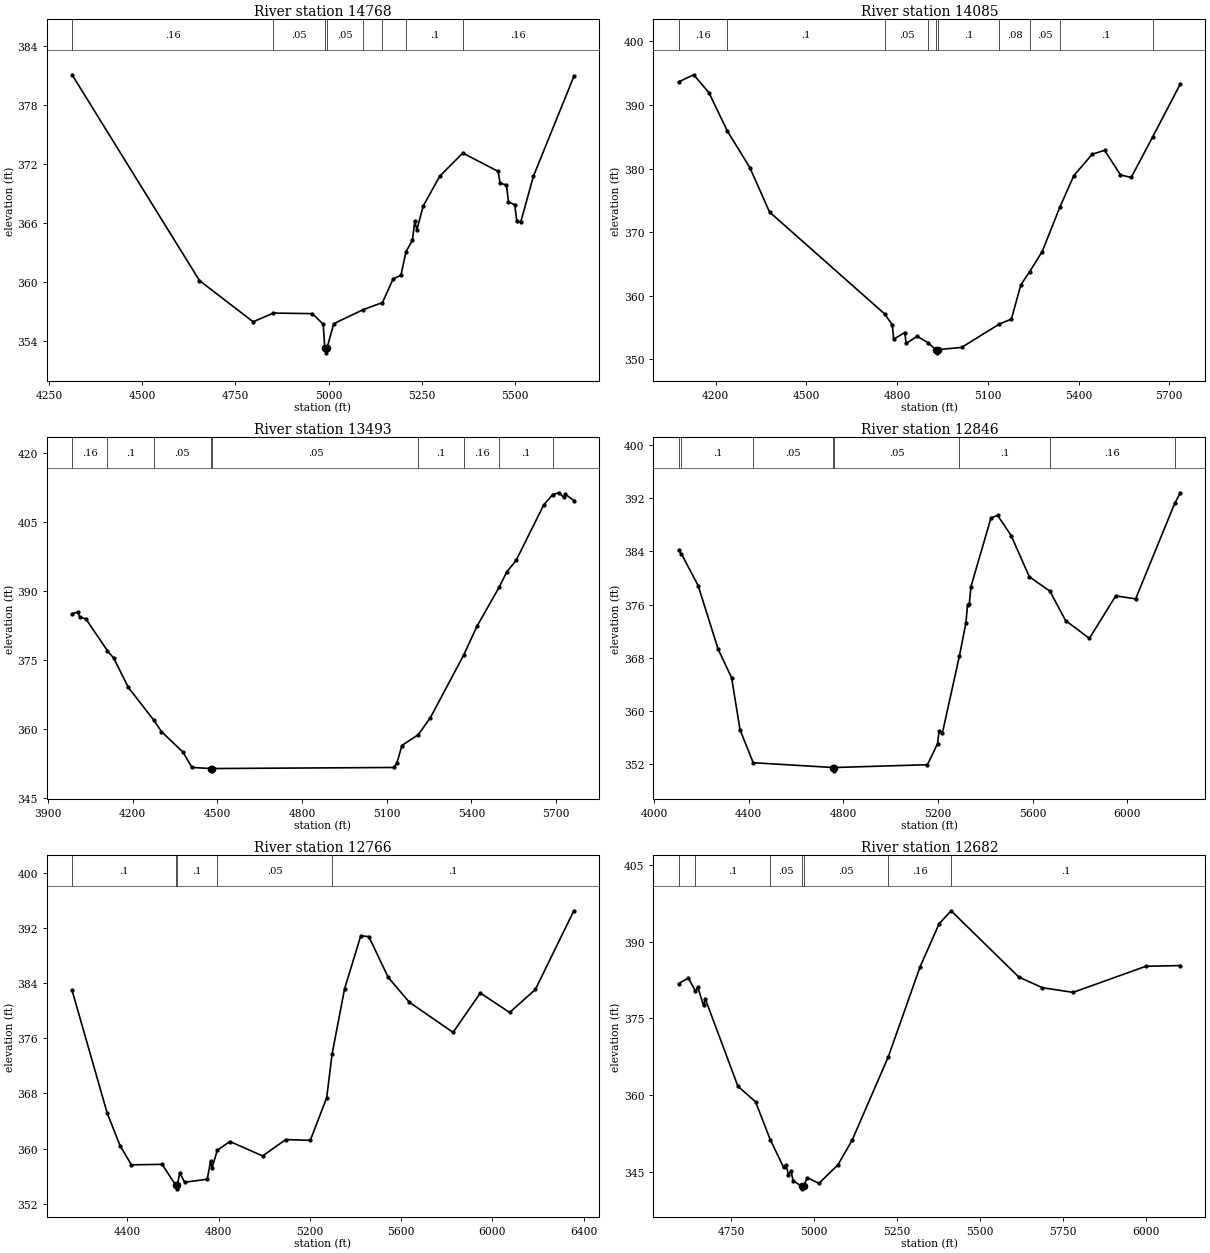
Type RM Length L Ch R = 1 ,14768   ,683,683,683
BEGIN DESCRIPTION:
UNT0381 IN CEDR CR 29.0
END DESCRIPTION:
XS GIS Cut Line= 3
      3597725.82     10369230.55      3597225.81     10369980.57
      3597026.44      10370379.3
#Sta/Elev= 30
  4311.5  381.12  4653.5  360.17  4797.7  355.97    4852  356.86    4957   356.8
  4985.8  355.72    4990  353.31  4992.8  352.81    4996  353.31  5014.1  355.78
  5093.1  357.21  5144.9  357.93  5173.3  360.33  5194.4  360.71  5208.1  363.12
  5225.3  364.26  5231.6  366.23  5237.2  365.33    5254  367.74  5298.7   370.8
  5360.5  373.15  5455.2  371.29  5460.8  370.07  5477.6  369.91  5483.2  368.17
    5500  367.89  5505.5  366.21    5516  366.13  5550.3  370.81  5658.7  380.95
#Mann= 8 ,-1 , 0
  4311.5     .16       0    4852     .05       0    4990    .035       0
    4996     .05       0  5093.1      .1       0  5144.9     .05       0
  5208.1      .1       0  5360.5     .16       0
Bank Sta=4990,4996
XS Rating Curve= 0 ,0
Exp/Cntr=0.3,0.1

Type RM Length L Ch R = 1 ,14085   ,592,592,592
BEGIN DESCRIPTION:
UNT0381 IN CEDR CR 28.0
END DESCRIPTION:
XS GIS Cut Line= 3
      3597225.54     10368744.61      3596824.72     10369290.83
      3596587.64     10370243.67
#Sta/Elev= 30
  4077.2  393.62  4127.3  394.74  4177.5  391.94  4238.9  385.88  4313.3  380.12
  4378.1  373.16  4758.5  357.15  4783.8  355.46  4788.9  353.17  4825.1  354.21
  4830.2   352.5  4866.4  353.62  4903.7  352.57  4927.7  351.52  4930.5  351.02
  4933.7  351.52  5013.2  351.87  5137.8  355.54    5178  356.33    5209  361.69
    5238  363.76  5279.6  366.92  5338.2  373.92  5384.1  378.86  5444.9  382.23
  5486.2  382.87  5538.7     379    5574  378.59  5645.4  384.99  5736.6   393.3
#Mann= 10 ,-1 , 0
  4077.2     .16       0  4238.9      .1       0  4758.5     .05       0
  4903.7      .1       0  4927.7     .07       0  4933.7      .1       0
  5137.8     .08       0    5238     .05       0  5338.2      .1       0
  5645.4     .16       0
Bank Sta=4927.7,4933.7
XS Rating Curve= 0 ,0
Exp/Cntr=0.3,0.1

Type RM Length L Ch R = 1 ,13493   ,647,647,647
BEGIN DESCRIPTION:
UNT0381 IN CEDR CR 27.0
END DESCRIPTION:
XS GIS Cut Line= 3
      3596685.13     10368425.71      3596535.14      10368575.7
       3595933.8     10370020.43
#Sta/Elev= 30
  3985.6  385.08  4006.1   385.4  4013.1   384.3  4034.4  383.97    4111  377.03
  4133.4  375.41  4184.9  369.07  4275.7  361.92  4301.9  359.51  4378.8     355
    4410  351.71  4476.6  351.47  4479.4  350.97  4482.6  351.47  5124.4   351.7
  5135.7   352.6  5153.7  356.47  5211.9  358.84  5254.5  362.52  5373.4  376.22
  5419.2  382.33  5497.5  390.78  5525.6  394.21  5558.1  396.66  5655.6  408.67
  5687.5  410.95  5709.8  411.34    5727  410.36  5732.4  411.03  5762.6  409.66
#Mann= 9 ,-1 , 0
  3985.6     .16       0    4111      .1       0  4275.7     .05       0
  4476.6    .035       0  4482.6     .05       0  5211.9      .1       0
  5373.4     .16       0  5497.5      .1       0  5687.5     .16       0
Bank Sta=4476.6,4482.6
XS Rating Curve= 0 ,0
Exp/Cntr=0.3,0.1

Type RM Length L Ch R = 1 ,12846   ,80,80,80
BEGIN DESCRIPTION:
Mapping XS da4aea62
END DESCRIPTION:
XS GIS Cut Line= 3
      3596390.34     10368212.71      3595418.14     10369223.97
      3595140.37     10369885.86
#Sta/Elev= 30
  4103.8  384.18  4116.1  383.62  4186.6  378.87  4271.5  369.28  4328.1  365.01
  4363.6  357.21  4419.3  352.25  4756.5  351.53  4759.3  351.03  4762.5  351.53
  5155.7  351.95  5198.2  355.09  5205.1  357.04  5219.2  356.77  5290.6  368.26
  5318.3  373.26  5325.2  376.02  5332.5  376.03  5339.4  378.69  5424.3  389.05
  5452.6   389.4  5509.4  386.39  5586.1   380.2  5673.2  378.03  5739.5  373.61
    5840  370.93  5951.4  377.32  6035.5  376.87  6200.9  391.23  6224.4  392.81
#Mann= 8 ,-1 , 0
  4103.8     .16       0  4116.1      .1       0  4419.3     .05       0
  4756.5     .03       0  4762.5     .05       0  5290.6      .1       0
  5673.2     .16       0  6200.9      .1       0
Bank Sta=4756.5,4762.5
XS Rating Curve= 0 ,0
Exp/Cntr=0.3,0.1

Type RM Length L Ch R = 1 ,12766   ,84,84,84
BEGIN DESCRIPTION:
Mapping XS 878517b5
END DESCRIPTION:
XS GIS Cut Line= 4
      3596318.74     10368221.38      3595780.55     10368703.14
      3595517.97     10369087.26      3594853.89     10369851.16
#Sta/Elev= 30
  4157.5  382.94  4311.3  365.17  4367.7  360.45  4417.5  357.65  4552.1  357.72
  4612.6  354.67  4615.4  354.17  4618.6  354.67  4629.8  356.49  4650.7  355.13
  4750.2  355.56  4764.4  358.14  4771.1  357.18  4794.1  359.77  4849.6  361.03
  4992.7  358.94  5094.3  361.31  5201.9   361.2  5273.7  367.38  5297.3  373.69
    5352  383.15  5423.2  390.86  5458.3  390.74  5543.8  384.81  5635.9  381.23
  5827.7  376.85  5947.3  382.56  6075.6  379.74  6188.5  383.07  6357.3  394.48
#Mann= 5 ,-1 , 0
  4157.5      .1       0  4612.6     .03       0  4618.6      .1       0
  4794.1     .05       0  5297.3      .1       0
Bank Sta=4612.6,4618.6
XS Rating Curve= 0 ,0
Exp/Cntr=0.3,0.1

Type RM Length L Ch R = 1 ,12682   ,217,217,217
BEGIN DESCRIPTION:
Mapping XS ba36f3c0
END DESCRIPTION:
XS GIS Cut Line= 3
      3595869.51     10368399.35      3595776.21     10368598.97
      3594938.52     10369584.24
#Sta/Elev= 30
  4591.3   381.8    4621   382.9  4642.3  380.31  4649.4  381.12  4666.7  377.53
  4672.2  378.78  4770.4  361.77  4823.7  358.73  4867.9  351.35  4908.3  345.94
    4916  346.43  4922.5  344.45  4930.3  345.29  4936.8  343.37  4962.4  342.25
  4965.1  341.75  4968.4  342.25  4979.7  343.93  5014.8  342.82  5071.9  346.42
  5114.8  351.22  5224.2  367.55  5320.1  385.11  5377.2  393.47  5413.4  396.01
  5617.7  383.08  5689.1  380.99  5781.4  380.09    6001  385.18  6104.9  385.32
#Mann= 7 ,-1 , 0
  4591.3     .16       0  4642.3      .1       0  4867.9     .05       0
  4962.4     .03       0  4968.4     .05       0  5224.2     .16       0
  5413.4      .1       0
Bank Sta=4962.4,4968.4
XS Rating Curve= 0 ,0
Exp/Cntr=0.3,0.1

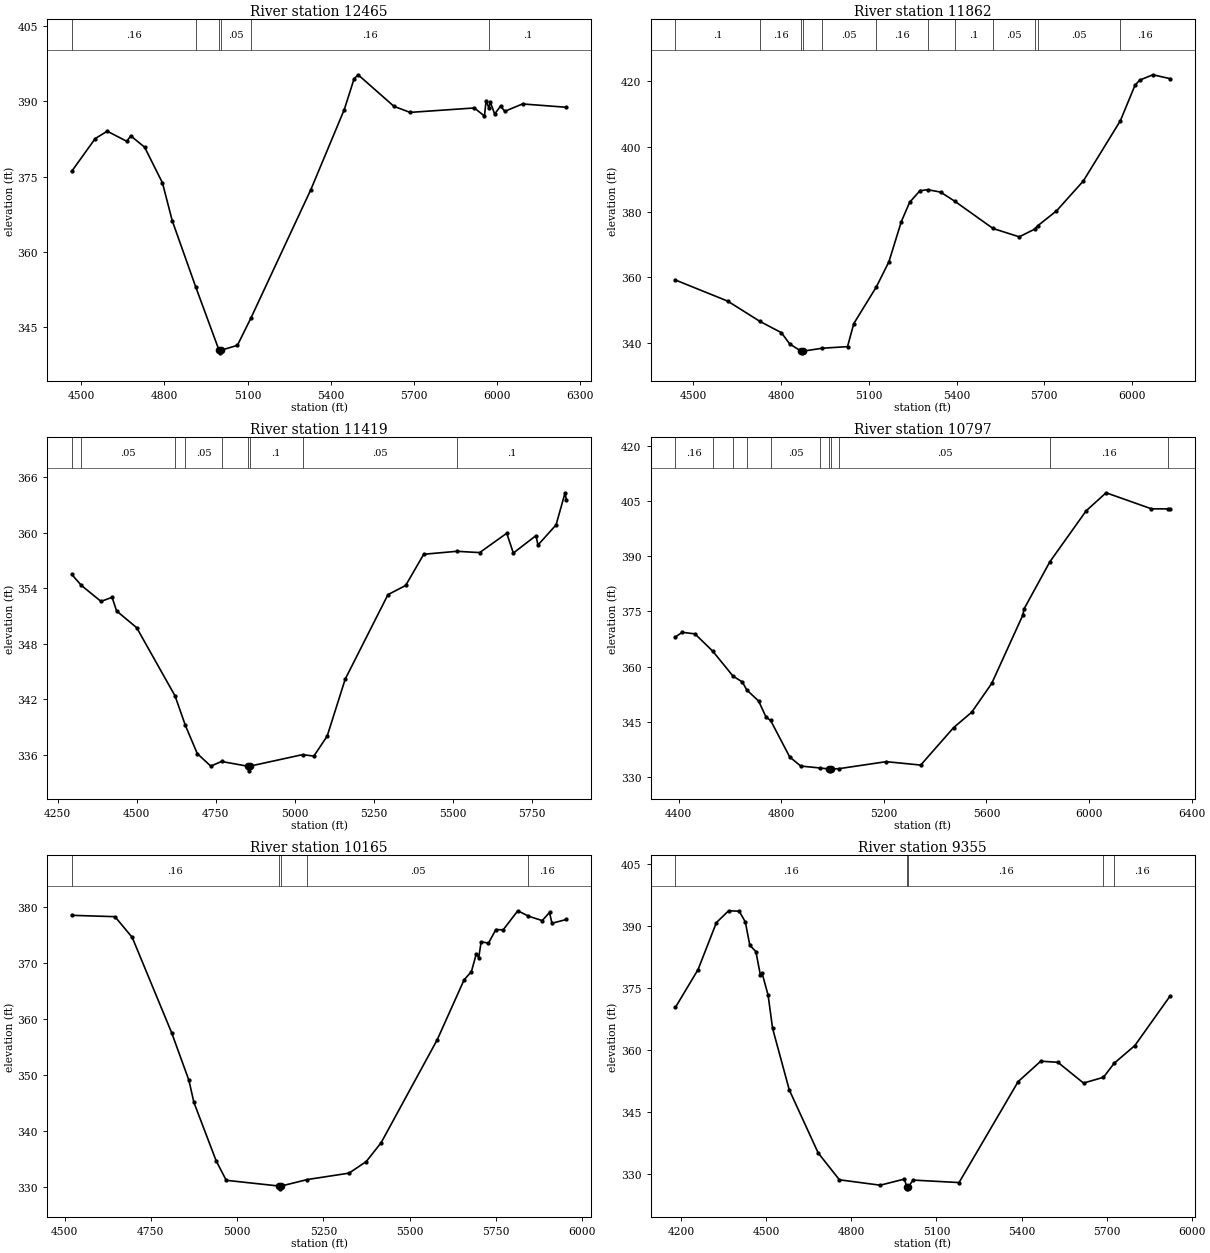
Type RM Length L Ch R = 1 ,12465   ,603,603,603
BEGIN DESCRIPTION:
UNT0381 IN CEDR CR 26.0
END DESCRIPTION:
XS GIS Cut Line= 3
      3595917.86     10368138.64      3595216.19     10369047.63
      3594882.29     10369588.22
#Sta/Elev= 30
  4465.5  376.06    4550  382.56  4593.5  384.04  4664.1  382.03  4678.6  383.11
  4728.4  380.86  4792.7  373.77    4828  366.24  4912.5   353.1  4996.9  340.46
  4999.6  339.96  5002.9  340.46    5063  341.45  5111.8  346.88    5328  372.44
  5448.5  388.35  5483.8  394.46  5498.3  395.26  5627.7  388.98  5685.7  387.78
  5917.4  388.66    5954  387.05  5959.9  390.14  5969.9  388.67  5975.3   389.8
  5990.7  387.45    6012  389.03  6027.4  387.99  6091.2  389.46  6249.2   388.8
#Mann= 6 ,-1 , 0
  4465.5     .16       0  4912.5     .05       0  4996.9     .03       0
  5002.9     .05       0  5111.8     .16       0  5969.9      .1       0
Bank Sta=4996.9,5002.9
XS Rating Curve= 0 ,0
Exp/Cntr=0.3,0.1

Type RM Length L Ch R = 1 ,11862   ,443,443,443
BEGIN DESCRIPTION:
UNT0381 IN CEDR CR 25.0
END DESCRIPTION:
XS GIS Cut Line= 3
      3595635.03     10367742.11      3594493.15     10368833.66
      3594443.14     10368933.68
#Sta/Elev= 30
  4438.2   359.2  4616.8  352.75  4727.8   346.5  4800.8  343.07  4829.1  339.63
  4868.2   337.4    4871   336.9  4874.2   337.4  4939.8  338.31  5026.9   338.8
  5048.3  345.85  5125.5  357.09  5168.4  364.77  5210.9  377.08  5239.2  382.96
  5274.4  386.52  5301.3  386.85  5345.2   386.1  5393.3  383.33  5524.5  374.97
  5614.1  372.41  5666.5  374.75  5676.7  375.75  5741.5  380.35  5833.3  389.51
  5959.8  407.92  6010.1  418.83  6026.3  420.39    6071  422.02  6129.7  420.84
#Mann= 12 ,-1 , 0
  4438.2      .1       0  4727.8     .16       0  4868.2     .03       0
  4874.2     .16       0  4939.8     .05       0  5125.5     .16       0
  5301.3     .05       0  5393.3      .1       0  5524.5     .05       0
  5666.5      .1       0  5676.7     .05       0  5959.8     .16       0
Bank Sta=4868.2,4874.2
XS Rating Curve= 0 ,0
Exp/Cntr=0.3,0.1

Type RM Length L Ch R = 1 ,11419   ,622,622,622
BEGIN DESCRIPTION:
UNT0381 IN CEDR CR 24.0
END DESCRIPTION:
XS GIS Cut Line= 3
      3595453.39     10367322.72      3595053.36     10367672.75
      3594386.07     10368461.37
#Sta/Elev= 30
  4294.8  355.48  4324.9   354.3  4387.4  352.56  4422.5     353  4436.7  351.53
  4500.3  349.72  4621.7  342.35  4654.3  339.17    4692  336.12  4734.7  334.77
  4768.7  335.27  4851.6  334.76  4854.3  334.26  4857.6  334.76    5025  336.01
  5060.7  335.85  5102.9  338.01    5160  344.17  5295.2  353.29  5351.2  354.28
  5408.3  357.65    5513  357.97  5585.2  357.83  5670.9  359.92  5691.8  357.78
  5763.2  359.66  5769.8  358.65  5826.9  360.82  5855.5  364.29  5859.4  363.54
#Mann= 9 ,-1 , 0
  4294.8      .1       0  4324.9     .05       0  4621.7      .1       0
  4654.3     .05       0  4768.7      .1       0  4851.6     .07       0
  4857.6      .1       0    5025     .05       0    5513      .1       0
Bank Sta=4851.6,4857.6
XS Rating Curve= 0 ,0
Exp/Cntr=0.3,0.1

Type RM Length L Ch R = 1 ,10797   ,632,632,632
BEGIN DESCRIPTION:
UNT0381 IN CEDR CR 23.0
END DESCRIPTION:
XS GIS Cut Line= 3
      3595218.34     10366900.12      3594169.19     10367771.16
      3593769.18     10368171.16
#Sta/Elev= 30
  4386.8  368.06  4413.5  369.32    4463   368.9  4532.5  364.19  4611.5   357.4
  4647.9  355.79  4665.2  353.63  4711.7  350.58  4740.4  346.22  4758.3   345.3
  4832.8  335.36  4875.8  332.88  4952.5  332.35  4986.1  332.08  4988.8  331.58
  4992.1  332.08  5024.8  332.17  5209.2  334.08  5343.7  333.15  5472.2  343.37
  5542.5  347.54  5620.6  355.38  5741.7  373.95  5746.9  375.71  5847.7  388.56
  5989.1  402.43  6066.9  407.34  6243.7  402.97  6306.6  402.95  6316.1  402.87
#Mann= 11 ,-1 , 0
  4386.8     .16       0  4532.5     .05       0  4611.5     .16       0
  4665.2      .1       0  4758.3     .05       0  4952.5      .1       0
  4986.1     .07       0  4992.1      .1       0  5024.8     .05       0
  5847.7     .16       0  6306.6      .1       0
Bank Sta=4986.1,4992.1
XS Rating Curve= 0 ,0
Exp/Cntr=0.3,0.1

Type RM Length L Ch R = 1 ,10165   ,810,810,810
BEGIN DESCRIPTION:
UNT0381 IN CEDR CR 22.0
END DESCRIPTION:
XS GIS Cut Line= 3
      3594671.47     10366604.98      3594146.97     10367295.46
      3593747.03      10367695.4
#Sta/Elev= 30
  4520.8  378.51  4646.1  378.27    4696  374.58  4810.4  357.55  4860.3  349.09
  4874.8  345.14  4939.3  334.72  4968.4  331.26  5121.4  330.24  5124.2  329.74
  5127.4  330.24  5203.5   331.4  5324.1  332.54    5374  334.61  5416.9  337.95
  5579.6  356.33  5657.3     367  5678.6  368.48  5692.7  371.64  5699.8  370.98
  5706.8  373.79    5728  373.55  5749.3  375.97  5770.5  375.92  5812.9  379.32
  5843.9  378.36  5883.6  377.57  5904.8  379.02  5911.9  377.09  5953.5  377.77
#Mann= 5 ,-1 , 0
  4520.8     .16       0  5121.4     .07       0  5127.4     .16       0
  5203.5     .05       0  5843.9     .16       0
Bank Sta=5121.4,5127.4
XS Rating Curve= 0 ,0
Exp/Cntr=0.3,0.1

Type RM Length L Ch R = 1 ,9355    ,587,587,587
BEGIN DESCRIPTION:
UNT0381 IN CEDR CR 20.0
END DESCRIPTION:
XS GIS Cut Line= 3
      3594228.78      10365780.3       3593907.4     10366337.91
      3593517.46     10367367.55
#Sta/Elev= 30
    4179  370.24    4259  379.42  4323.7  390.79  4366.8  393.65  4404.1  393.55
  4425.7  390.94  4441.5  385.32    4463  383.75  4478.8  378.08  4484.6  378.61
  4506.1  373.19  4521.9  365.17  4580.8  350.26  4682.8     335  4757.5  328.51
  4901.4   327.2    4987  328.69  4994.9  326.82  4997.7  326.32  5000.9  326.82
  5017.4  328.44  5179.5  327.84  5388.1  352.29  5467.8  357.23  5528.1  356.96
  5618.6  351.93    5689  353.33  5726.1  356.69  5799.7  361.02  5923.6  372.98
#Mann= 5 ,-1 , 0
    4179     .16       0  4994.9     .07       0  5000.9     .16       0
    5689     .05       0  5726.1     .16       0
Bank Sta=4994.9,5000.9
XS Rating Curve= 0 ,0
Exp/Cntr=0.3,0.1

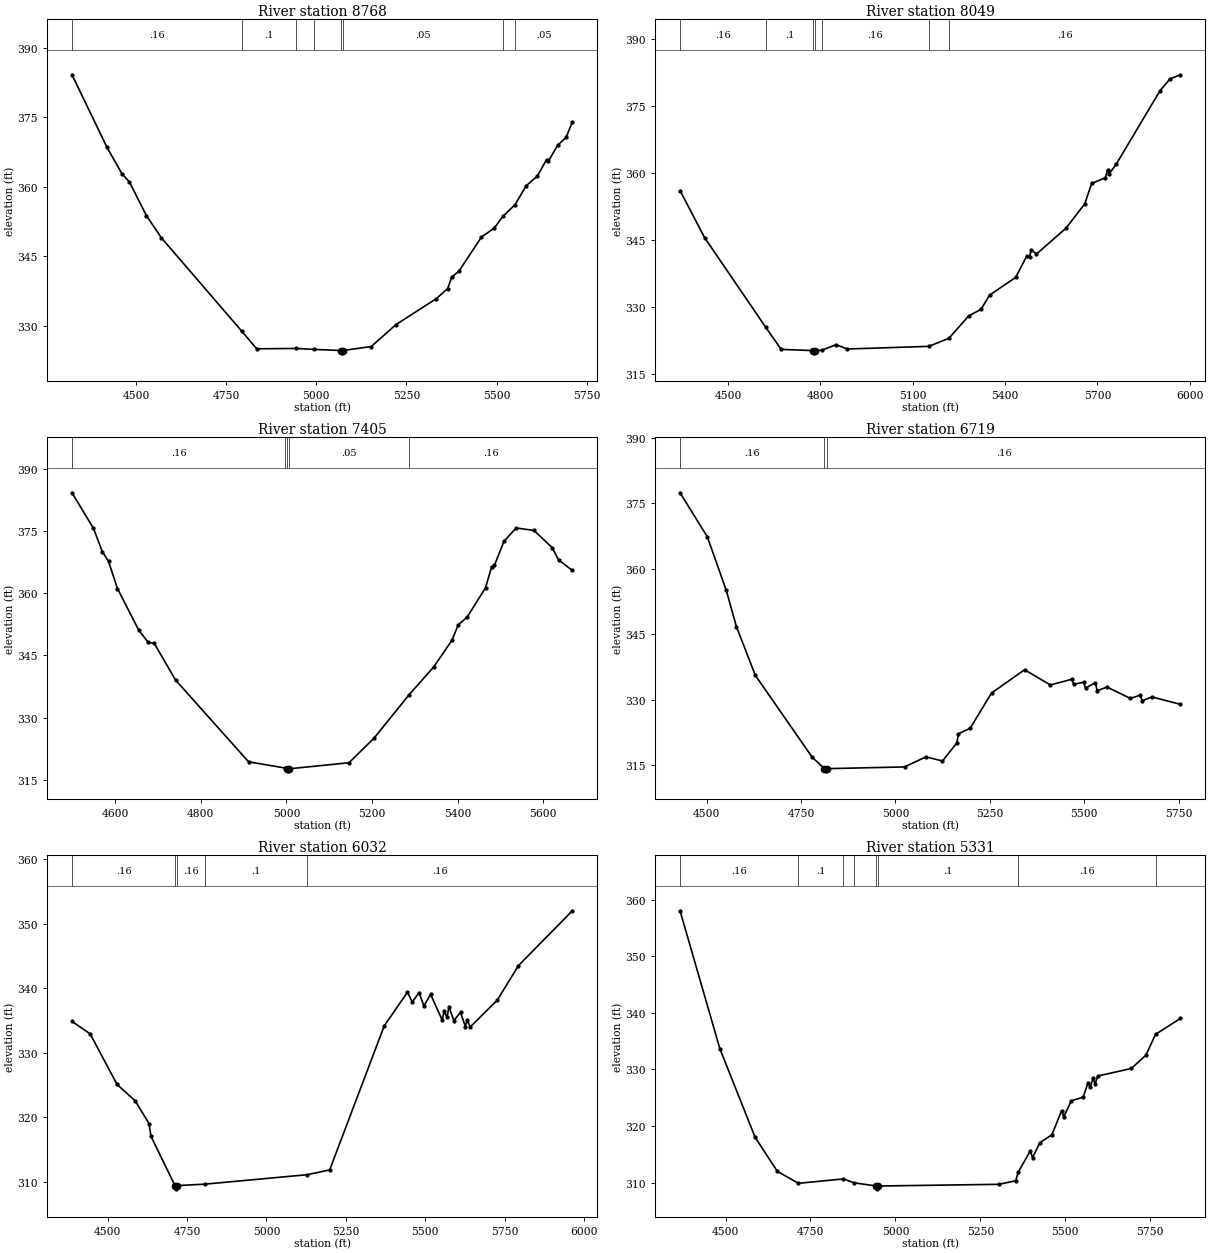
Type RM Length L Ch R = 1 ,8768    ,719,719,719
BEGIN DESCRIPTION:
UNT0381 IN CEDR CR 19.0
END DESCRIPTION:
XS GIS Cut Line= 3
      3593497.47     10365847.37      3593397.46     10366247.41
      3593074.71     10367167.91
#Sta/Elev= 30
  4322.3  384.13  4419.5  368.46  4460.7  362.81  4481.3  361.06  4528.8  353.76
  4570.1  348.99  4793.6  328.81  4834.5  325.05  4942.6  325.13  4992.3  324.93
  5067.6  324.68  5070.3  324.18  5073.6  324.68  5152.4  325.54  5220.3  330.23
  5332.6  335.85  5364.4  338.04  5375.3   340.5  5395.7  341.81  5457.7  349.11
  5494.1  351.13  5517.2  353.59  5551.2  356.12  5581.8  360.19  5612.8  362.27
  5638.5  365.83  5643.8  365.53  5669.5  368.94  5692.9  370.66  5710.1  373.97
#Mann= 8 ,-1 , 0
  4322.3     .16       0  4793.6      .1       0  4942.6     .16       0
  4992.3     .05       0  5067.6     .03       0  5073.6     .05       0
  5517.2      .1       0  5551.2     .05       0
Bank Sta=5067.6,5073.6
XS Rating Curve= 0 ,0
Exp/Cntr=0.3,0.1

Type RM Length L Ch R = 1 ,8049    ,644,644,644
BEGIN DESCRIPTION:
UNT0381 IN CEDR CR 17.0
END DESCRIPTION:
XS GIS Cut Line= 3
       3593145.6     10365593.01      3592625.08     10366261.39
      3592284.33     10366960.85
#Sta/Elev= 30
  4344.2     356    4424  345.47  4622.4  325.42  4672.8  320.45  4777.5  320.18
  4780.2  319.68  4783.5  320.18  4804.9  320.28    4851   321.5  4887.5  320.54
  5151.9  321.13  5217.2  322.92  5282.1  327.97  5321.6   329.4  5349.7   332.6
  5434.3  336.56  5469.7  341.26  5479.4  341.17    5485  342.75    5502   341.8
  5597.7  347.58  5658.8  353.04  5681.1   357.6  5725.6  358.87  5732.9  360.56
  5738.5   359.8    5761  361.92  5903.5   378.4  5935.8  381.02  5969.4  381.93
#Mann= 7 ,-1 , 0
  4344.2     .16       0  4622.4      .1       0  4777.5     .07       0
  4783.5      .1       0  4804.9     .16       0  5151.9     .05       0
  5217.2     .16       0
Bank Sta=4777.5,4783.5
XS Rating Curve= 0 ,0
Exp/Cntr=0.3,0.1

Type RM Length L Ch R = 1 ,7405    ,686,686,686
BEGIN DESCRIPTION:
UNT0381 IN CEDR CR 16.0
END DESCRIPTION:
XS GIS Cut Line= 3
       3592942.1     10365191.65      3592397.21       10365640.
       3592041.3     10365936.54
#Sta/Elev= 30
    4499  384.22  4549.2  375.63    4570  369.98  4584.4  367.67  4605.2  361.13
  4654.7  351.14  4676.9  348.16  4691.2  347.91  4740.8  339.09  4911.5  319.36
  4997.4  317.85    5001  317.68  5003.8  317.18    5007  317.68  5146.1  319.13
  5204.6  325.06  5285.6  335.41    5344  342.23  5386.9  348.69  5401.2  352.38
  5422.1  354.23    5465  361.32  5479.4  366.38  5485.9  366.73    5508  372.48
  5536.6  375.74  5578.3  375.14  5621.2  370.95  5635.6  368.03  5667.9  365.51
#Mann= 5 ,-1 , 0
    4499     .16       0  4997.4     .05       0    5001    .035       0
    5007     .05       0  5285.6     .16       0
Bank Sta=5001,5007
XS Rating Curve= 0 ,0
Exp/Cntr=0.3,0.1

Type RM Length L Ch R = 1 ,6719    ,687,687,687
BEGIN DESCRIPTION:
UNT0381 IN CEDR CR 14.0
END DESCRIPTION:
XS GIS Cut Line= 3
      3592392.08     10364691.68      3591958.19     10365282.25
      3591763.49     10365841.08
#Sta/Elev= 30
  4429.9  377.46    4502  367.37  4552.1  355.11  4579.2  346.73  4629.3  335.53
  4779.8  316.75  4812.3  314.13    4815  313.63  4818.3  314.13  5024.4  314.53
  5080.7  316.84  5124.7  315.89  5162.7  320.03  5166.7  322.12  5197.8  323.39
  5254.6  331.51  5342.1  336.84  5410.1  333.35  5466.9  334.64  5472.2  333.49
    5498  333.96  5503.3  332.62  5529.1  333.86  5534.4  332.04  5560.2  332.86
  5622.3  330.26  5648.1     331  5653.4  329.69  5679.2  330.59  5754.5   328.9
#Mann= 3 ,-1 , 0
  4429.9     .16       0  4812.3     .07       0  4818.3     .16       0
Bank Sta=4812.3,4818.3
XS Rating Curve= 0 ,0
Exp/Cntr=0.3,0.1

Type RM Length L Ch R = 1 ,6032    ,701,701,701
BEGIN DESCRIPTION:
UNT0381 IN CEDR CR 12.0
END DESCRIPTION:
XS GIS Cut Line= 3
      3592063.65     10364163.15      3591527.33     10364818.84
      3591138.48     10365433.11
#Sta/Elev= 30
  4388.3  334.85  4445.3  332.93    4530  325.08  4587.4  322.51  4630.5  319.01
  4636.9  317.01  4712.2  309.37  4714.9  308.87  4718.2  309.37  4806.7   309.6
  5127.6  311.06    5199  311.81  5370.8  334.19  5443.7  339.39  5458.9  337.87
  5480.1  339.34  5495.4  337.27  5516.5  339.05    5553  335.06  5558.9  336.45
  5568.3  335.49  5574.2  337.15  5589.4  334.98  5610.6  336.26  5625.9  334.06
  5631.8  335.05  5641.1  333.99  5725.9  338.14  5792.9  343.52  5962.4  352.03
#Mann= 5 ,-1 , 0
  4388.3     .16       0  4712.2     .07       0  4718.2     .16       0
  4806.7      .1       0  5127.6     .16       0
Bank Sta=4712.2,4718.2
XS Rating Curve= 0 ,0
Exp/Cntr=0.3,0.1

Type RM Length L Ch R = 1 ,5331    ,361,361,361
BEGIN DESCRIPTION:
UNT0381 IN CEDR CR 11.0
END DESCRIPTION:
XS GIS Cut Line= 3
      3591792.15     10363791.62      3591242.11     10364091.64
      3590600.27     10364643.18
#Sta/Elev= 30
  4366.1  358.05  4483.4  333.65  4586.8  318.04  4652.3  311.99  4714.6  309.87
  4847.1  310.64    4879  309.95  4944.1  309.39  4946.8  308.89  4950.1  309.39
  5304.8  309.69  5354.2  310.32  5361.2  311.81    5397  315.59  5403.6  314.42
  5425.5  317.06  5460.7  318.45  5489.2  322.71  5495.8  321.65  5517.7  324.46
  5552.8  325.09  5567.1  327.67  5573.7  326.83  5581.4  328.44    5588  327.44
  5595.6  328.83  5694.4  330.17  5737.2  332.51  5765.7   336.2  5838.9  339.02
#Mann= 8 ,-1 , 0
  4366.1     .16       0  4714.6      .1       0  4847.1     .16       0
    4879      .1       0  4944.1     .07       0  4950.1      .1       0
  5361.2     .16       0  5765.7     .05       0
Bank Sta=4944.1,4950.1
XS Rating Curve= 0 ,0
Exp/Cntr=0.3,0.1

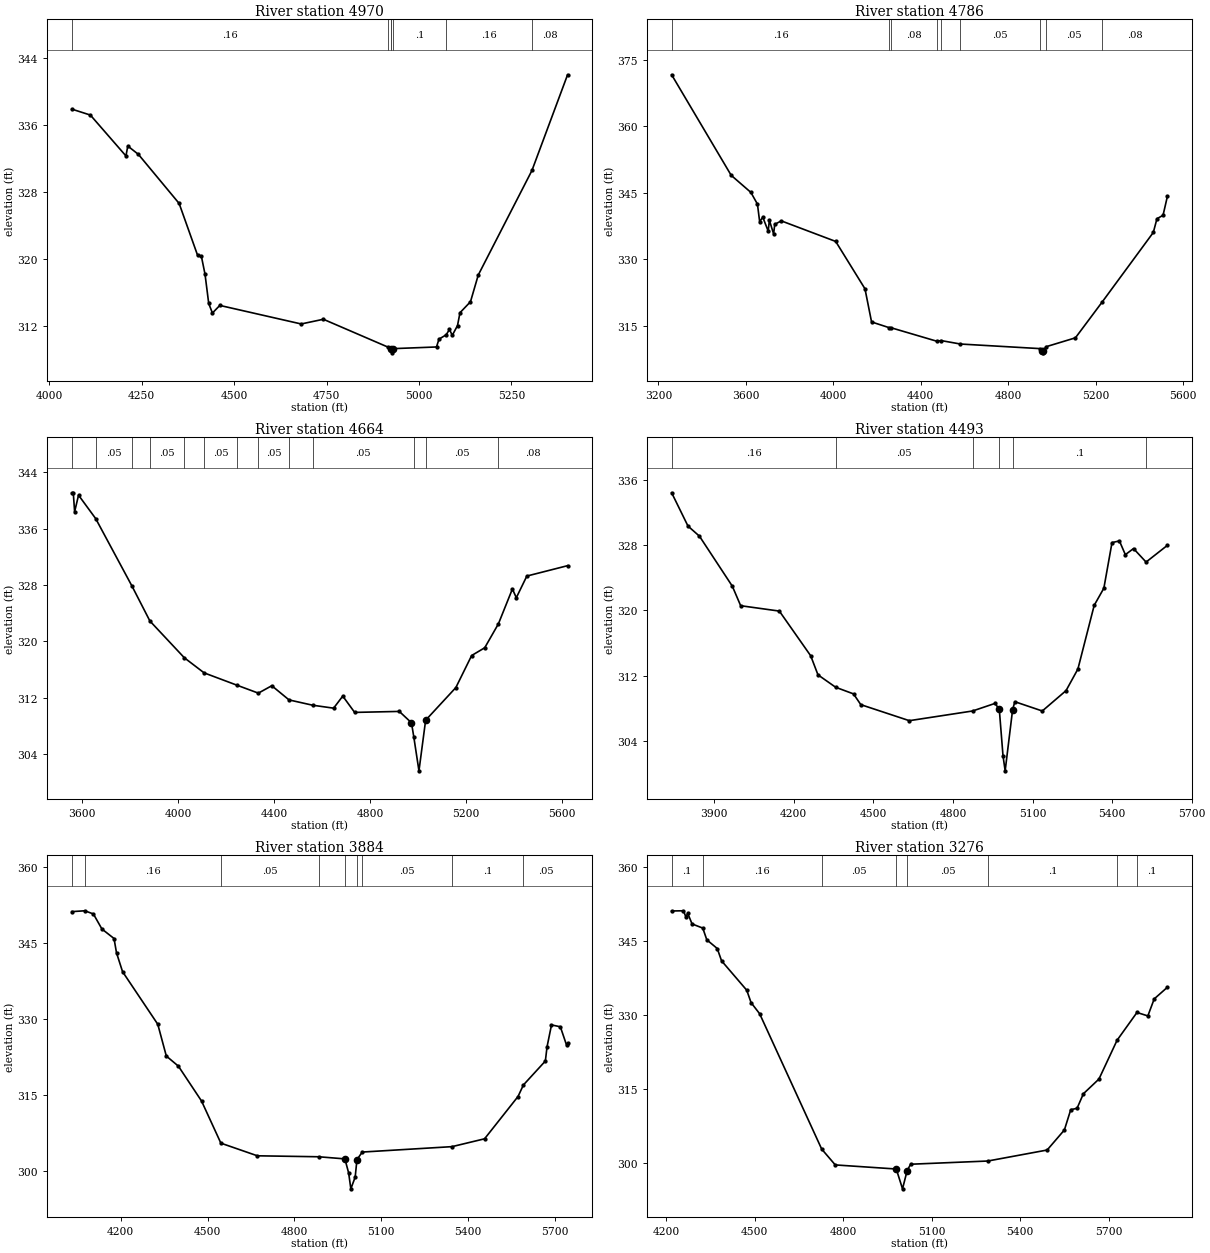
Type RM Length L Ch R = 1 ,4970    ,184,184,184
BEGIN DESCRIPTION:
UNT0381 IN CEDR CR 10.0
END DESCRIPTION:
XS GIS Cut Line= 3
      3591902.36      10363644.9      3591164.53     10363653.58
      3590761.93     10364102.12
#Sta/Elev= 30
  4061.2   337.9  4111.5  337.19  4207.7  332.32  4212.7   333.5  4241.5   332.5
  4351.5  326.66  4401.5  320.47  4411.5   320.4  4421.5  318.23  4431.5  314.74
  4441.5   313.6  4461.5  314.51  4681.5   312.3  4741.5  312.86  4916.9  309.53
  4923.6  309.37    4924  309.36  4926.8  308.86    4930  309.36  5047.4  309.56
  5054.1  310.49  5073.6  311.01  5082.5  311.65    5090  310.94  5104.2  312.11
  5110.9  313.64  5139.3  314.95  5160.3  318.13  5305.5  330.59  5401.8  341.99
#Mann= 7 ,-1 , 0
  4061.2     .16       0  4916.9     .05       0  4923.6      .1       0
    4924     .07       0    4930      .1       0  5073.6     .16       0
  5305.5     .08       0
Bank Sta=4924,4930
XS Rating Curve= 0 ,0
Exp/Cntr=0.3,0.1

Type RM Length L Ch R = 1 ,4786    ,122,122,122
BEGIN DESCRIPTION:
Mapping XS b4183728
END DESCRIPTION:
XS GIS Cut Line= 3
      3592248.08     10362617.71      3591307.09     10362978.83
      3590737.65     10364103.82
#Sta/Elev= 30
  3260.2  371.63  3532.7  348.92  3622.7  345.07  3652.8  342.42  3662.9  338.47
  3677.4  339.45  3702.1  336.31  3707.4  338.78  3726.8  335.69  3732.1  337.86
  3762.1  338.63  4010.9  333.99  4144.9  323.29    4175  315.81  4255.9  314.51
  4262.6  314.52  4473.8  311.45  4493.2   311.6  4581.7  310.82  4943.7  309.79
  4954.5  309.33  4957.3  308.83  4960.5  309.33  4974.2  310.22  5107.9  312.22
  5229.1  320.23  5464.3  336.02    5481  339.12  5508.9   339.9    5529  344.22
#Mann= 9 ,-1 , 0
  3260.2     .16       0  4255.9     .05       0  4262.6     .08       0
  4473.8     .05       0  4493.2     .08       0  4581.7     .05       0
  4943.7     .04       0  4974.2     .05       0  5229.1     .08       0
Bank Sta=4954.5,4960.5
XS Rating Curve= 0 ,0
Exp/Cntr=0.3,0.1

Type RM Length L Ch R = 1 ,4664    ,171,171,171
BEGIN DESCRIPTION:
Mapping XS 7edc3faa
END DESCRIPTION:
XS GIS Cut Line= 2
      3591581.38     10362263.58       3590606.4     10364085.17
#Sta/Elev= 30
  3556.1  341.01  3562.4  341.07    3568  338.38  3584.3  340.73  3655.8  337.41
    3807  327.85  3881.7   322.9  4025.2  317.69  4107.7  315.55  4243.3  313.82
  4333.6  312.68  4389.6  313.73  4461.5  311.72  4559.6  310.97  4647.2  310.55
  4685.4  312.26  4734.9  309.95    4921  310.09  4971.7  308.48  4981.2  306.52
  5002.9  301.67  5030.7  308.84  5156.7  313.47  5222.5  318.01    5277  319.11
    5334   322.5  5392.3  327.44  5408.6   326.2  5452.5  329.27  5622.2  330.74
#Mann= 13 ,-1 , 0
  3556.1     .08       0  3655.8     .05       0    3807     .08       0
  3881.7     .05       0  4025.2     .08       0  4107.7     .05       0
  4243.3     .08       0  4333.6     .05       0  4461.5     .08       0
  4559.6     .05       0  4981.2     .04       0  5030.7     .05       0
    5334     .08       0
Bank Sta=4971.7,5030.7
XS Rating Curve= 0 ,0
Exp/Cntr=0.3,0.1

Type RM Length L Ch R = 1 ,4493    ,609,609,609
BEGIN DESCRIPTION:
UNT0381 IN CEDR CR 9.0
END DESCRIPTION:
XS GIS Cut Line= 3
       3591398.9     10362325.47      3590792.11     10363391.64
      3590504.82     10363966.05
#Sta/Elev= 30
  3739.7  334.45  3801.3  330.36  3844.5  329.12  3968.4  322.98  3999.9  320.58
  4145.7  319.92  4263.9  314.43  4291.3  312.09  4358.2  310.56  4425.3  309.75
  4452.7  308.43  4635.7  306.46    4874  307.65  4958.5  308.58  4974.8  307.87
  4988.8  302.16  4996.9   300.3  5025.1  307.83  5033.5  308.79  5136.9  307.65
  5226.4  310.15  5271.1   312.8  5332.6  320.63    5369  322.73  5399.7  328.33
  5427.6  328.54    5450  326.85  5480.8   327.6  5528.1  325.94  5608.7     328
#Mann= 6 ,-1 , 0
  3739.7     .16       0  4358.2     .05       0    4874      .1       0
  4974.8     .04       0  5025.1      .1       0  5528.1     .08       0
Bank Sta=4974.8,5025.1
XS Rating Curve= 0 ,0
Exp/Cntr=0.3,0.1

Type RM Length L Ch R = 1 ,3884    ,608,608,608
BEGIN DESCRIPTION:
UNT0381 IN CEDR CR 8.0
END DESCRIPTION:
XS GIS Cut Line= 3
      3590999.59      10362134.5      3590277.06     10363142.79
      3590027.08     10363542.76
#Sta/Elev= 30
    4031  351.23  4075.9   351.4  4105.7  350.77  4135.2  347.79  4176.9  345.92
  4185.5  343.09  4206.4  339.36    4328  328.97  4357.5  322.69  4399.2  320.69
  4479.1   313.8  4545.9  305.47  4671.9  302.97  4883.5  302.78  4974.1  302.36
  4987.1  299.59  4994.7  296.44  5009.7  298.76  5015.8  302.22  5034.2  303.71
  5344.1  304.78  5456.5  306.33    5572  314.69  5590.6  316.97  5666.4   321.7
  5672.3  324.54  5687.6  328.84  5718.2  328.47  5739.5  324.87  5743.1  325.26
#Mann= 9 ,-1 , 0
    4031      .1       0  4075.9     .16       0  4545.9     .05       0
  4883.5      .1       0  4974.1     .04       0  5015.8      .1       0
  5034.2     .05       0  5344.1      .1       0  5590.6     .05       0
Bank Sta=4974.1,5015.8
XS Rating Curve= 0 ,0
Exp/Cntr=0.3,0.1

Type RM Length L Ch R = 1 ,3276    ,656,656,656
BEGIN DESCRIPTION:
UNT0381 IN CEDR CR 6.0
END DESCRIPTION:
XS GIS Cut Line= 3
      3590641.74     10361874.64      3590241.76     10362174.63
      3589642.12     10363191.63
#Sta/Elev= 30
  4219.1  351.15  4259.1  351.19  4267.4  349.94  4273.7  350.66  4288.3  348.52
  4324.6  347.68  4338.3   345.3  4373.7  343.54  4388.3  341.04  4473.7  335.08
  4488.3  332.57  4517.4  330.31  4727.7  302.87  4773.7  299.66  4980.5  298.83
  5001.7  294.81  5017.4  298.51  5029.2   299.8  5290.7  300.45  5491.9  302.68
  5550.4  306.75  5571.9  310.86  5593.3  311.14  5614.8  314.09  5667.5  317.07
    5729  324.94  5796.4  330.57  5833.3  329.87  5854.8  333.32  5899.7  335.69
#Mann= 8 ,-1 , 0
  4219.1      .1       0  4324.6     .16       0  4727.7     .05       0
  4980.5     .03       0  5017.4     .05       0  5290.7      .1       0
    5729     .05       0  5796.4      .1       0
Bank Sta=4980.5,5017.4
XS Rating Curve= 0 ,0
Exp/Cntr=0.3,0.1