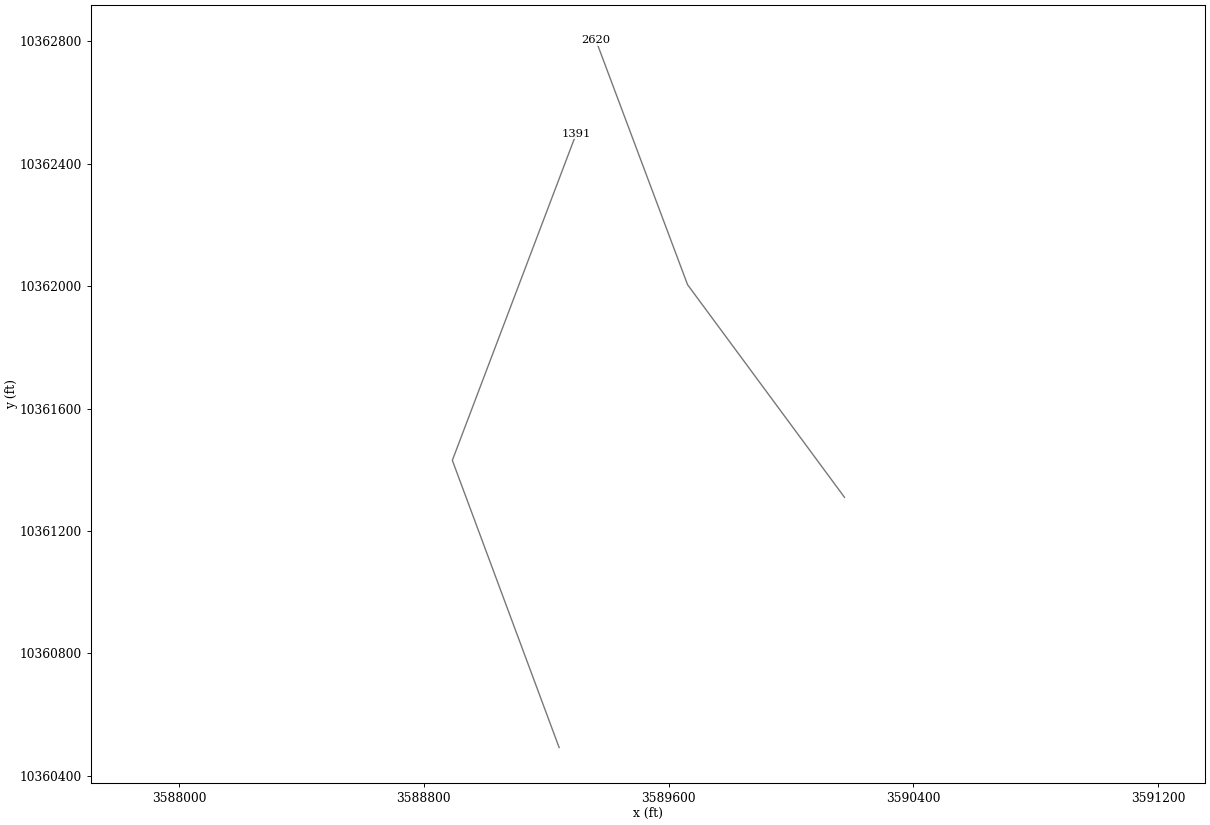
HEC-RAS study UNT0381 IN CEDR CR.prj: UNT0381 IN CEDR CR Base Level Engineering

--- UNT0381 IN CEDR CR.g01 (geometry) --- (continued)

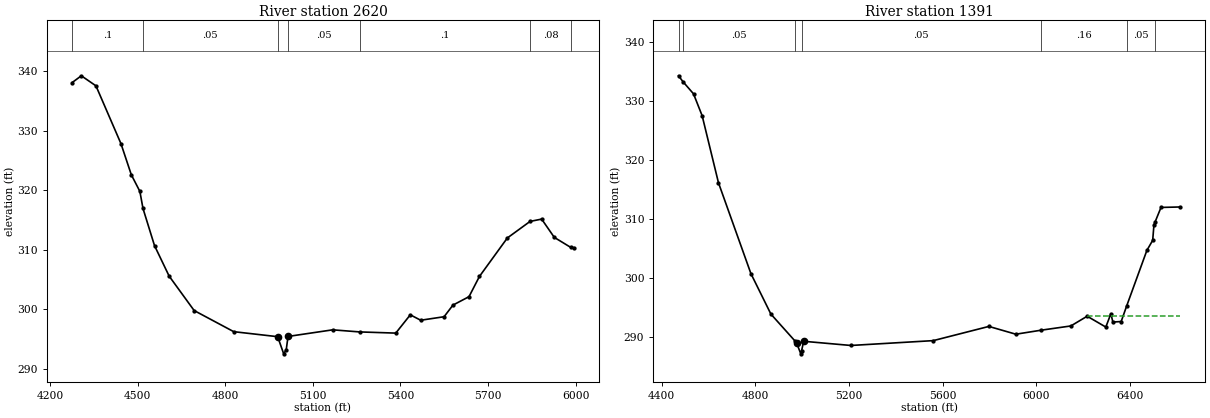
Type RM Length L Ch R = 1 ,2620    ,1229,1229,1229
BEGIN DESCRIPTION:
UNT0381 IN CEDR CR 4.0
END DESCRIPTION:
XS GIS Cut Line= 3
      3590174.97      10361309.8      3589661.91     10362004.94
       3589361.9     10362804.96
#Sta/Elev= 30
  4275.9  338.04  4307.6  339.19  4357.7   337.5  4443.3   327.8  4478.8  322.57
  4508.1  319.78  4518.8  316.91  4558.2  310.68  4608.3  305.56  4693.9  299.78
  4829.6  296.23    4980  295.39  5000.6  292.51  5009.3  293.19  5015.5  295.43
  5168.4  296.54  5260.5  296.19  5384.4  295.99  5434.2  299.06  5469.8  298.15
  5549.9  298.74  5580.2  300.69  5635.3  302.11  5670.9   305.5  5766.5  311.96
  5844.3  314.74    5884  315.13  5927.3  312.06  5983.9  310.37  5994.3  310.33
#Mann= 7 ,-1 , 0
  4275.9      .1       0  4518.8     .05       0    4980     .03       0
  5015.5     .05       0  5260.5      .1       0  5844.3     .08       0
  5983.9     .05       0
Bank Sta=4980,5015.5
XS Rating Curve= 0 ,0
Exp/Cntr=0.3,0.1

Type RM Length L Ch R = 1 ,1391    ,0,0,0
BEGIN DESCRIPTION:
UNT0381 IN CEDR CR 1.0
END DESCRIPTION:
XS GIS Cut Line= 3
      3589242.12     10360491.62      3588892.94     10361430.63
      3589298.23     10362499.11
#Sta/Elev= 30
  4471.5  334.31    4490  333.33  4535.5  331.25  4572.4  327.54  4642.2  316.16
  4780.9  300.75  4866.3  293.89  4970.6  289.27    4976     289  4994.1  287.15
  4997.3  287.65  5006.3  289.28  5208.1  288.57    5560  289.39  5797.9   291.8
  5913.1  290.48  6021.2  291.16  6148.2  291.88    6218  293.53  6297.7  291.69
  6319.3  293.96  6327.8  292.54  6363.3  292.63  6387.4  295.34  6473.2   304.7
    6498   306.4  6503.3  308.99  6508.9  309.58  6533.5  311.98  6616.1  312.06
#Mann= 7 ,-1 , 0
  4471.5      .1       0    4490     .05       0  4970.6     .03       0
  4997.3     .05       0  6021.2     .16       0  6387.4     .05       0
  6508.9     .08       0
#XS Ineff= 2 , 0
                         6221.02          293.52
Permanent Ineff=
       F       F
Bank Sta=4976,5006.3
XS Rating Curve= 0 ,0
Exp/Cntr=0.3,0.1

Chan Stop Cuts=-1
Use User Specified Reach Order=0
Composite Channel Slope=5