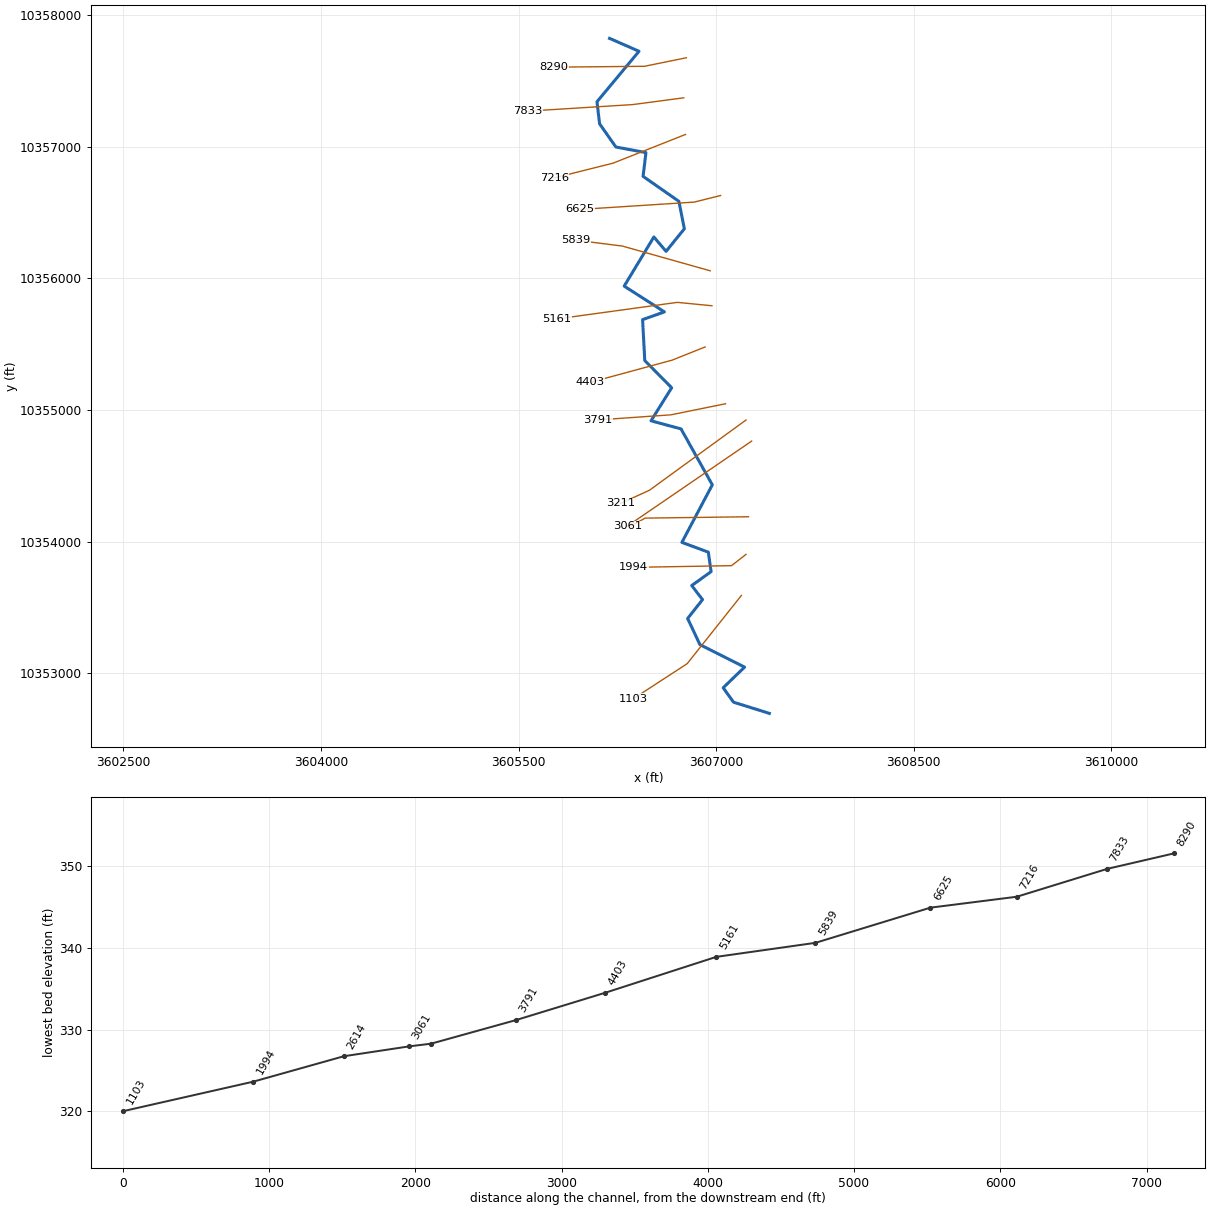
--- UNT0388 IN CEDR CR.prj (project) ---

Proj Title=UNT0388 IN CEDR CR Base Level Engineering
Current Plan=p01
Default Exp/Contr=0.3,0.1
English Units
Geom File=g01
Flow File=f01
Plan File=p01
BEGIN DESCRIPTION:
UNT0388 IN CEDR CR
END DESCRIPTION:

--- UNT0388 IN CEDR CR.p01 (plan) ---

Plan Title=Multiple Run
Short Identifier=Multiple
Geom File=g01
Flow File=f01
Subcritical Flow
K Sum by GR= 0
Std Step Tol= 0.01
Critical Tol= 0.01
Num of Std Step Trials= 20
Max Error Tol= 0.3
Flow Tol Ratio= 0.001
Split Flow NTrial= 30
Split Flow Tol= 0.02
Split Flow Ratio= 0.02
Log Output Level= 0
Friction Slope Method= 1
Unsteady Friction Slope Method= 2
Unsteady Bridges Friction Slope Method= 1
Parabolic Critical Depth
Global Vel Dist=  1 , 1 , 1
Global Log Level= 0
CheckData=True
Encroach Param= -1, 0, 0, 0
BEGIN DESCRIPTION:
Multiple Run
END DESCRIPTION:

--- UNT0388 IN CEDR CR.f01 (steady flow) ---

Flow Title=Multiple
Number of Profiles=7
Profile Names=10-year,25-year,50-year,1pct_min,100-year,1pct_plu,500-year
River Rch & RM= UNT0388 IN CEDR ,Reach-1,8290
    1082    1479    1805    1606    2173    2938    3137
River Rch & RM= UNT0388 IN CEDR ,Reach-1,3061
    1163    1595    1951    1740    2353    3182    3410
Boundary for River Rch & Prof#=UNT0388 IN CEDR ,Reach-1,1
Up Type=0
Dn Type=3
Dn Slope=0.005
Boundary for River Rch & Prof#=UNT0388 IN CEDR ,Reach-1,2
Up Type=0
Dn Type=3
Dn Slope=0.005
Boundary for River Rch & Prof#=UNT0388 IN CEDR ,Reach-1,3
Up Type=0
Dn Type=3
Dn Slope=0.005
Boundary for River Rch & Prof#=UNT0388 IN CEDR ,Reach-1,4
Up Type=0
Dn Type=3
Dn Slope=0.005
Boundary for River Rch & Prof#=UNT0388 IN CEDR ,Reach-1,5
Up Type=0
Dn Type=3
Dn Slope=0.005
Boundary for River Rch & Prof#=UNT0388 IN CEDR ,Reach-1,6
Up Type=0
Dn Type=3
Dn Slope=0.005
Boundary for River Rch & Prof#=UNT0388 IN CEDR ,Reach-1,7
Up Type=0
Dn Type=3
Dn Slope=0.005

--- UNT0388 IN CEDR CR.g01 (geometry) ---

Geom Title=Existing Conditions

River Reach=UNT0388 IN CEDR ,Reach-1
Reach XY= 30
      3606190.75     10357822.06      3606414.67     10357723.80
      3606095.47     10357340.23      3606115.72     10357172.87
      3606239.07     10356996.85      3606467.52     10356954.32
      3606445.61     10356774.06      3606717.75     10356584.42
      3606759.12     10356375.99      3606620.37     10356204.48
      3606527.52     10356313.64      3606302.26     10355940.56
      3606607.76     10355744.97      3606441.93     10355686.13
      3606458.59     10355375.37      3606662.76     10355168.77
      3606506.01     10354917.73      3606733.78     10354856.53
      3606971.40     10354431.85      3606740.47     10353994.90
      3606941.31     10353920.38      3606962.12     10353772.63
      3606815.21     10353666.95      3606897.16     10353560.00
      3606784.07     10353417.19      3606877.12     10353218.40
      3607216.36     10353047.57      3607053.89     10352890.76
      3607132.60     10352781.34      3607404.55     10352696.37

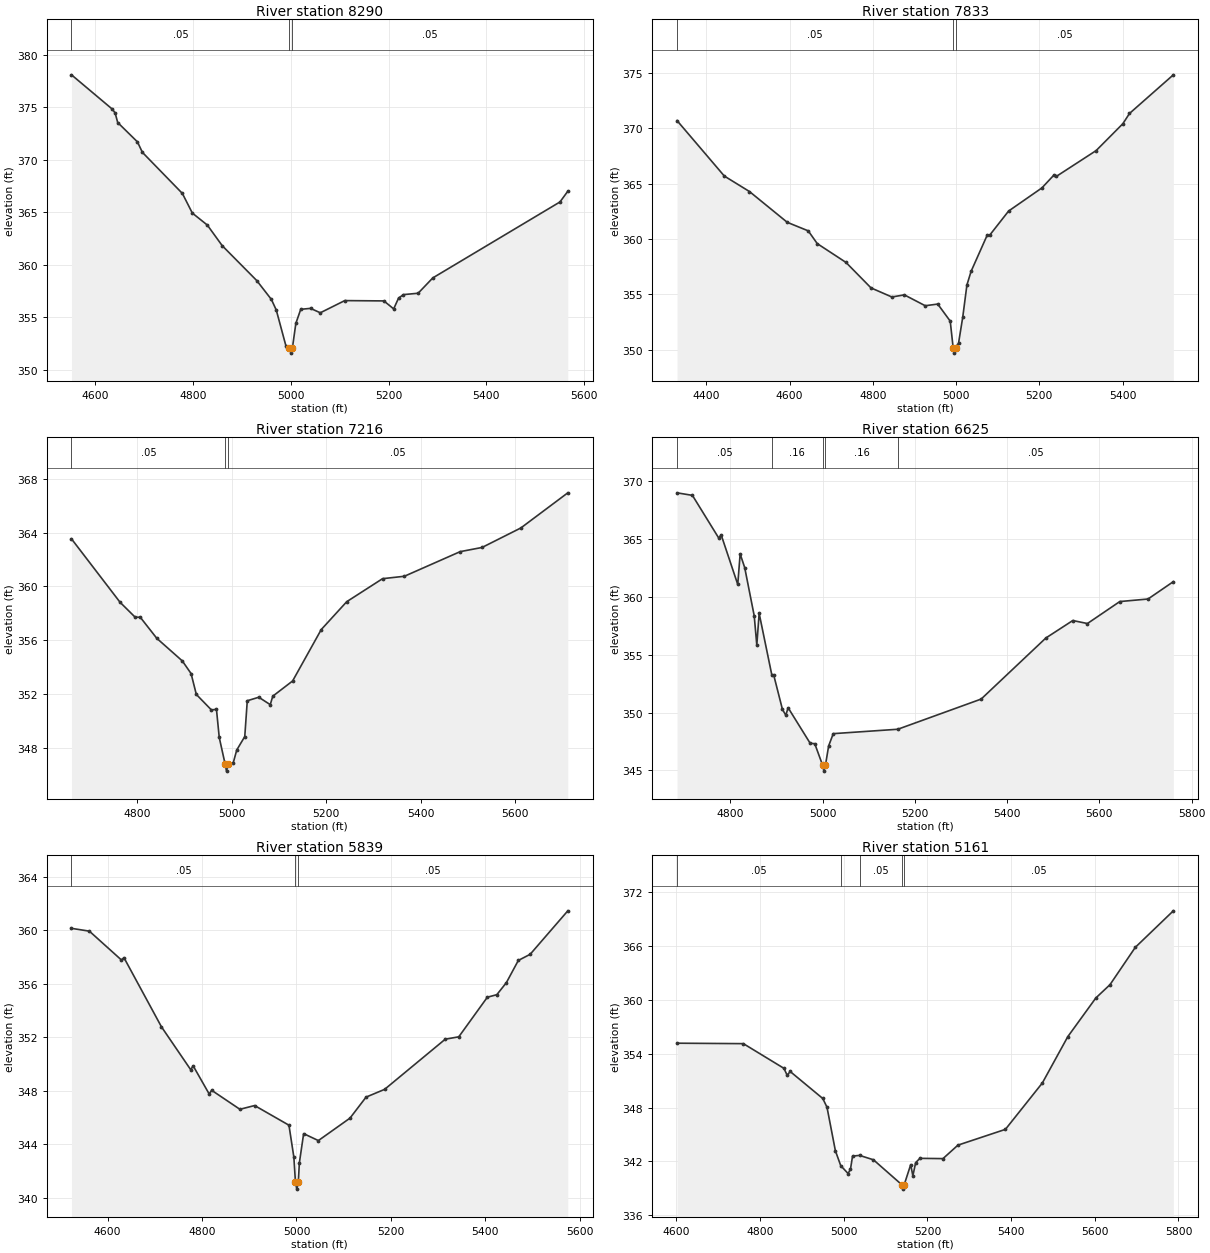
Type RM Length L Ch R = 1,8290,457,457,457
BEGIN DESCRIPTION:
UNT0388 IN CEDR CR 14.0
END DESCRIPTION:
XS GIS Cut Line= 3
      3606774.22     10357674.60      3606457.18     10357609.89
      3605766.09     10357603.09
#Sta/Elev= 30
  4551.7  378.08  4635.5  374.80  4641.0  374.44  4646.2  373.54  4686.5  371.70
  4696.7  370.70  4778.4  366.79  4798.8  364.92  4829.4  363.78  4860.0  361.81
  4930.4  358.50  4960.4  356.70  4970.4  355.69  4990.4  352.23  4997.4  352.09
  5000.1  351.59  5003.4  352.09  5010.4  354.42  5020.4  355.76  5040.4  355.85
  5060.4  355.43  5110.4  356.59  5190.4  356.56  5210.4  355.80  5220.4  356.83
  5230.4  357.16  5260.4  357.29  5290.4  358.75  5550.4  365.98  5566.4  367.00
#Mann=3,-1,0
  4551.7    0.05       0  4997.4    0.03       0  5003.4    0.05       0
Bank Sta=4997.4,5003.4
Exp/Cntr=0.3,0.1

Type RM Length L Ch R = 1,7833,617,617,617
BEGIN DESCRIPTION:
UNT0388 IN CEDR CR 13.0
END DESCRIPTION:
XS GIS Cut Line= 3
      3606754.80     10357370.47      3606366.71     10357319.01
      3605566.96     10357269.03
#Sta/Elev= 30
  4329.3  370.69  4443.0  365.68  4503.5  364.28  4594.3  361.50  4644.7  360.73
  4666.3  359.58  4735.4  357.88  4795.5  355.58  4845.6  354.76  4875.7  354.95
  4925.8  353.97  4955.9  354.12  4985.9  352.58  4992.9  350.19  4995.7  349.69
  4998.9  350.19  5005.9  350.59  5016.0  352.94  5026.0  355.84  5036.0  357.07
  5075.2  360.38  5080.3  360.32  5126.2  362.52  5206.3  364.61  5235.6  365.79
  5240.6  365.64  5336.6  367.98  5400.9  370.41  5416.7  371.33  5522.1  374.82
#Mann=3,-1,0
  4329.3    0.05       0  4992.9    0.03       0  4998.9    0.05       0
Bank Sta=4992.9,4998.9
Exp/Cntr=0.3,0.1

Type RM Length L Ch R = 1,7216,591,591,591
BEGIN DESCRIPTION:
UNT0388 IN CEDR CR 12.0
END DESCRIPTION:
XS GIS Cut Line= 3
      3606767.79     10357092.24      3606218.42     10356874.54
      3605771.25     10356762.22
#Sta/Elev= 30
  4660.2  363.54  4763.1  358.83  4795.4  357.71  4805.9  357.72  4841.0  356.15
  4895.1  354.47  4913.7  353.53  4924.8  351.98  4956.7  350.83  4967.5  350.87
  4973.4  348.78  4986.0  346.78  4988.8  346.28  4992.0  346.78  5003.1  346.90
  5010.5  347.85  5027.5  348.85  5032.8  351.51  5057.2  351.77  5081.5  351.22
  5086.9  351.85  5128.9  352.98  5189.6  356.80  5243.6  358.87  5319.5  360.58
  5365.8  360.76  5484.1  362.59  5530.4  362.90  5612.7  364.35  5712.2  366.96
#Mann=3,-1,0
  4660.2    0.05       0  4986.0    0.03       0  4992.0    0.05       0
Bank Sta=4986,4992
Exp/Cntr=0.3,0.1

Type RM Length L Ch R = 1,6625,786,786,786
BEGIN DESCRIPTION:
UNT0388 IN CEDR CR 10.0
END DESCRIPTION:
XS GIS Cut Line= 3
      3607034.48     10356628.71      3606834.46     10356578.70
      3605966.23     10356522.86
#Sta/Elev= 30
  4684.1  369.00  4717.5  368.78  4774.6  365.09  4779.8  365.37  4815.8  361.08
  4821.0  363.72  4830.9  362.53  4851.5  358.37  4857.1  355.84  4862.2  358.58
  4889.9  353.21  4894.0  353.21  4912.7  350.28  4920.0  349.77  4925.0  350.42
  4972.8  347.35  4982.8  347.31  4999.9  345.44  5002.6  344.94  5005.9  345.44
  5012.9  347.12  5022.9  348.18  5162.8  348.56  5343.6  351.17  5483.9  356.45
  5542.3  357.96  5574.0  357.70  5644.2  359.60  5705.4  359.82  5760.3  361.32
#Mann=5,-1,0
  4684.1    0.05       0  4889.9    0.16       0  4999.9    0.07       0
  5005.9    0.16       0  5162.8    0.05       0
Bank Sta=4999.9,5005.9
Exp/Cntr=0.3,0.1

Type RM Length L Ch R = 1,5839,678,678,678
BEGIN DESCRIPTION:
UNT0388 IN CEDR CR 9.0
END DESCRIPTION:
XS GIS Cut Line= 3
      3606955.45     10356056.91      3606288.94     10356244.57
      3605933.03     10356289.86
#Sta/Elev= 30
  4523.5  360.13  4561.4  359.92  4629.4  357.76  4634.6  357.94  4714.0  352.77
  4776.0  349.56  4781.2  349.85  4815.2  347.74  4820.4  348.02  4880.2  346.60
  4911.4  346.88  4984.1  345.41  4994.5  343.02  4997.9  341.13  5000.7  340.63
  5003.9  341.13  5006.1  342.58  5015.2  344.78  5046.4  344.26  5113.4  345.94
  5147.4  347.51  5186.7  348.09  5315.1  351.84  5343.8  352.02  5404.3  354.98
  5424.4  355.17  5444.6  356.07  5469.9  357.73  5495.0  358.19  5574.7  361.44
#Mann=3,-1,0
  4523.5    0.05       0  4997.9    0.03       0  5003.9    0.05       0
Bank Sta=4997.9,5003.9
Exp/Cntr=0.3,0.1

Type RM Length L Ch R = 1,5161,758,758,758
BEGIN DESCRIPTION:
UNT0388 IN CEDR CR 8.0
END DESCRIPTION:
XS GIS Cut Line= 3
      3606968.34     10355791.62      3606705.43     10355817.19
      3605792.07     10355691.64
#Sta/Elev= 30
  4601.6  355.17  4760.2  355.12  4857.1  352.37  4864.9  351.59  4872.0  352.02
  4949.9  349.01  4960.0  348.04  4980.1  343.18  4992.9  341.52  5010.4  340.65
  5016.1  341.12  5021.1  342.59  5037.8  342.67  5071.0  342.18  5138.6  339.41
  5141.4  338.91  5144.6  339.41  5160.1  341.64  5165.2  340.39  5171.9  341.86
  5182.0  342.34  5237.2  342.31  5272.9  343.81  5386.4  345.57  5474.7  350.74
  5535.5  355.90  5602.5  360.21  5636.3  361.69  5696.8  365.85  5787.7  369.92
#Mann=5,-1,0
  4601.6    0.05       0  4992.9    0.16       0  5037.8    0.05       0
  5138.6    0.07       0  5144.6    0.05       0
Bank Sta=5138.6,5144.6
Exp/Cntr=0.3,0.1

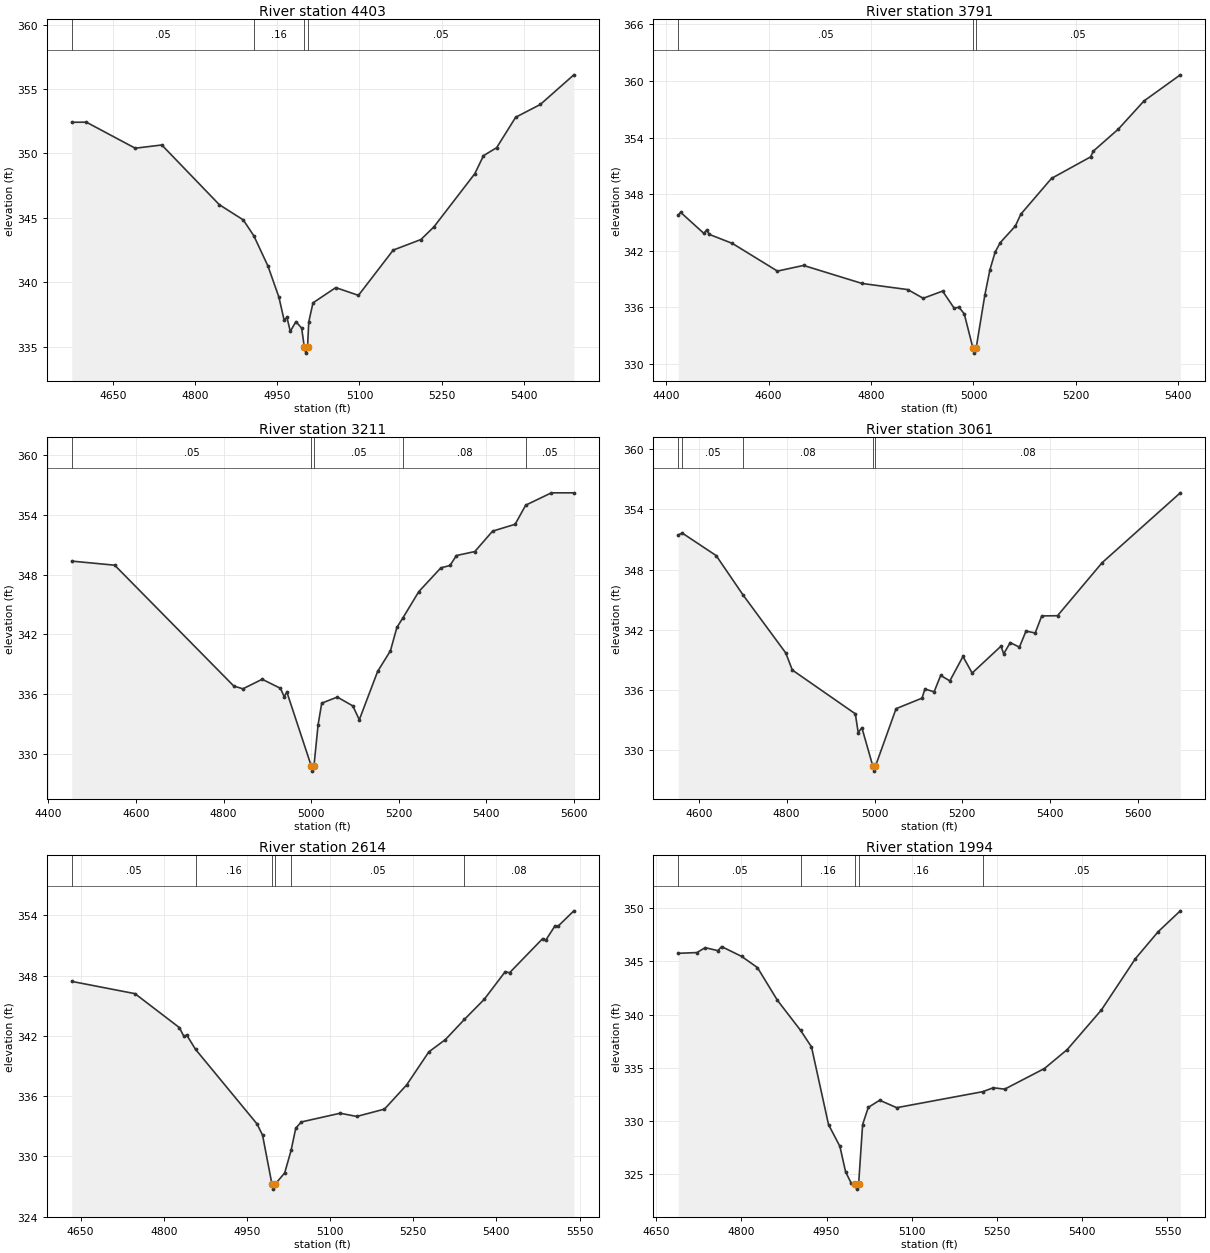
Type RM Length L Ch R = 1,4403,612,612,612
BEGIN DESCRIPTION:
UNT0388 IN CEDR CR 7.0
END DESCRIPTION:
XS GIS Cut Line= 3
      3606916.81     10355478.70      3606666.82     10355378.70
      3606043.07     10355209.25
#Sta/Elev= 30
  4575.3  352.42  4601.9  352.43  4691.0  350.41  4739.5  350.66  4844.4  346.03
  4888.1  344.85  4907.3  343.62  4933.1  341.27  4953.1  338.85  4962.5  337.09
  4967.7  337.29  4973.8  336.21  4984.1  336.96  4994.5  336.46  4999.3  335.02
  5002.1  334.52  5005.3  335.02  5007.5  336.94  5015.2  338.42  5056.7  339.60
  5098.1  339.00  5161.5  342.51  5212.1  343.33  5235.9  344.32  5310.4  348.44
  5326.1  349.83  5350.1  350.45  5384.8  352.81  5429.7  353.80  5490.9  356.10
#Mann=4,-1,0
  4575.3    0.05       0  4907.3    0.16       0  4999.3    0.07       0
  5005.3    0.05       0
Bank Sta=4999.3,5005.3
Exp/Cntr=0.3,0.1

Type RM Length L Ch R = 1,3791,580,580,580
BEGIN DESCRIPTION:
UNT0388 IN CEDR CR 6.0
END DESCRIPTION:
XS GIS Cut Line= 3
      3607071.93     10355047.49      3606657.77     10354963.36
      3606101.24     10354924.53
#Sta/Elev= 30
  4423.5  345.78  4428.1  346.08  4473.6  343.84  4478.7  344.19  4484.5  343.73
  4529.3  342.78  4617.2  339.85  4668.2  340.45  4782.5  338.54  4871.8  337.89
  4901.9  336.97  4939.8  337.73  4962.1  335.94  4972.1  336.01  4982.1  335.31
  4999.2  331.66  5001.9  331.16  5005.2  331.66  5022.2  337.29  5032.2  339.99
  5042.3  341.85  5052.3  342.86  5081.8  344.62  5092.4  345.87  5152.5  349.67
  5228.9  351.95  5233.9  352.55  5282.8  354.88  5333.0  357.87  5404.0  360.64
#Mann=3,-1,0
  4423.5    0.05       0  4999.2    0.03       0  5005.2    0.05       0
Bank Sta=4999.2,5005.2
Exp/Cntr=0.3,0.1

Type RM Length L Ch R = 1,3211,150,150,150
BEGIN DESCRIPTION:
UNT0388 IN CEDR CR 3.01
END DESCRIPTION:
XS GIS Cut Line= 3
      3607227.07     10354923.76      3606494.41     10354390.76
      3606275.48     10354290.78
#Sta/Elev= 30
  4453.3  349.37  4551.3  348.96  4823.3  336.82  4844.2  336.54  4888.2  337.50
  4929.9  336.59  4938.4  335.75  4944.6  336.21  5000.4  328.77  5003.1  328.27
  5006.4  328.77  5015.9  332.93  5024.2  335.10  5059.8  335.71  5095.3  334.82
  5110.0  333.43  5151.9  338.29  5181.1  340.36  5195.8  342.70  5209.9  343.69
  5246.0  346.31  5296.2  348.69  5317.1  348.93  5331.8  349.93  5373.8  350.33
  5414.4  352.38  5465.9  353.07  5490.0  354.99  5548.7  356.23  5600.0  356.23
#Mann=5,-1,0
  4453.3    0.05       0  5000.4    0.04       0  5006.4    0.05       0
  5209.9    0.08       0  5490.0    0.05       0
Bank Sta=5000.4,5006.4
Exp/Cntr=0.3,0.1

Type RM Length L Ch R = 1,3061,447,447,447
BEGIN DESCRIPTION:
UNT0388 IN CEDR CR 5.0
END DESCRIPTION:
XS GIS Cut Line= 2
      3607270.44     10354764.02      3606326.53     10354118.55
#Sta/Elev= 30
  4553.0  351.47  4562.2  351.65  4639.4  349.41  4700.9  345.47  4797.9  339.71
  4812.8  338.01  4956.3  333.65  4962.9  331.77  4971.2  332.27  4996.2  328.44
  4999.0  327.94  5002.2  328.44  5049.1  334.16  5108.3  335.21  5114.8  336.12
  5135.8  335.84  5150.7  337.47  5171.6  336.93  5201.5  339.36  5222.4  337.71
  5288.2  340.39  5294.2  339.62  5309.1  340.74  5330.1  340.29  5345.0  341.89
  5366.0  341.70  5380.9  343.40  5416.8  343.42  5518.4  348.70  5696.5  355.66
#Mann=5,-1,0
  4553.0    0.08       0  4562.2    0.05       0  4700.9    0.08       0
  4996.2    0.07       0  5002.2    0.08       0
Bank Sta=4996.2,5002.2
Exp/Cntr=0.3,0.1

Type RM Length L Ch R = 1,2614,620,620,620
BEGIN DESCRIPTION:
UNT0388 IN CEDR CR 3.0
END DESCRIPTION:
XS GIS Cut Line= 3
      3607246.14     10354189.37      3606461.43     10354178.96
      3606355.41     10354120.81
#Sta/Elev= 30
  4634.1  347.42  4748.1  346.20  4828.2  342.82  4836.4  341.94  4841.4  342.08
  4857.4  340.65  4968.2  333.23  4978.2  332.12  4995.2  327.23  4997.9  326.73
  5001.2  327.23  5018.2  328.35  5029.7  330.58  5038.2  332.81  5048.2  333.42
  5118.2  334.29  5148.2  333.97  5198.2  334.70  5238.2  337.11  5278.2  340.40
  5308.2  341.63  5342.3  343.63  5378.2  345.64  5416.0  348.39  5423.8  348.28
  5483.5  351.68  5489.2  351.53  5505.3  352.91  5511.0  352.90  5539.8  354.45
#Mann=6,-1,0
  4634.1    0.05       0  4857.4    0.16       0  4995.2    0.07       0
  5001.2    0.16       0  5029.7    0.05       0  5342.3    0.08       0
Bank Sta=4995.2,5001.2
Exp/Cntr=0.3,0.1

Type RM Length L Ch R = 1,1994,891,891,891
BEGIN DESCRIPTION:
UNT0388 IN CEDR CR 2.0
END DESCRIPTION:
XS GIS Cut Line= 3
      3607227.27     10353903.55      3607117.19     10353818.04
      3606373.09     10353805.10
#Sta/Elev= 30
  4689.0  345.76  4721.9  345.83  4736.4  346.29  4758.8  346.01  4765.3  346.39
  4800.6  345.47  4828.4  344.42  4863.5  341.35  4904.2  338.53  4923.5  336.97
  4953.5  329.67  4973.5  327.63  4983.5  325.24  4993.5  324.16  5000.5  324.11
  5003.2  323.61  5006.5  324.11  5013.5  329.68  5023.5  331.29  5043.5  331.96
  5073.5  331.26  5224.6  332.76  5243.5  333.13  5263.5  333.00  5333.5  334.94
  5373.6  336.72  5433.6  340.43  5493.6  345.26  5533.6  347.79  5572.6  349.75
#Mann=5,-1,0
  4689.0    0.05       0  4904.2    0.16       0  5000.5    0.07       0
  5006.5    0.16       0  5224.6    0.05       0
Bank Sta=5000.5,5006.5
Exp/Cntr=0.3,0.1

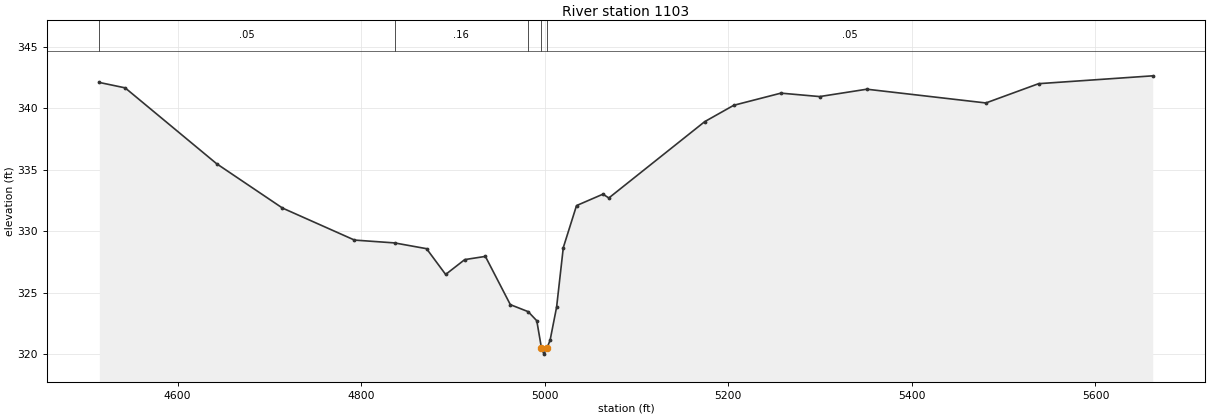
Type RM Length L Ch R = 1,1103,0,0,0
BEGIN DESCRIPTION:
UNT0388 IN CEDR CR 1.0
END DESCRIPTION:
XS GIS Cut Line= 3
      3607192.14     10353591.68      3606780.71     10353073.90
      3606373.07     10352808.61
#Sta/Elev= 30
  4514.7  342.12  4542.8  341.68  4642.5  335.50  4714.2  331.89  4792.7  329.28
  4836.3  329.05  4871.2  328.58  4892.0  326.48  4912.8  327.69  4935.3  327.95
  4962.5  324.02  4981.9  323.45  4991.3  322.71  4996.4  320.49  4999.1  319.99
  5002.4  320.49  5005.8  321.12  5012.9  323.82  5020.2  328.67  5034.6  332.09
  5063.4  333.02  5069.8  332.71  5174.3  338.93  5205.9  340.26  5257.3  341.25
  5299.5  340.97  5350.9  341.57  5480.6  340.45  5538.0  342.02  5662.4  342.66
#Mann=5,-1,0
  4514.7    0.05       0  4836.3    0.16       0  4981.9    0.05       0
  4996.4    0.03       0  5002.4    0.05       0
Bank Sta=4996.4,5002.4
Exp/Cntr=0.3,0.1

Chan Stop Cuts=-1