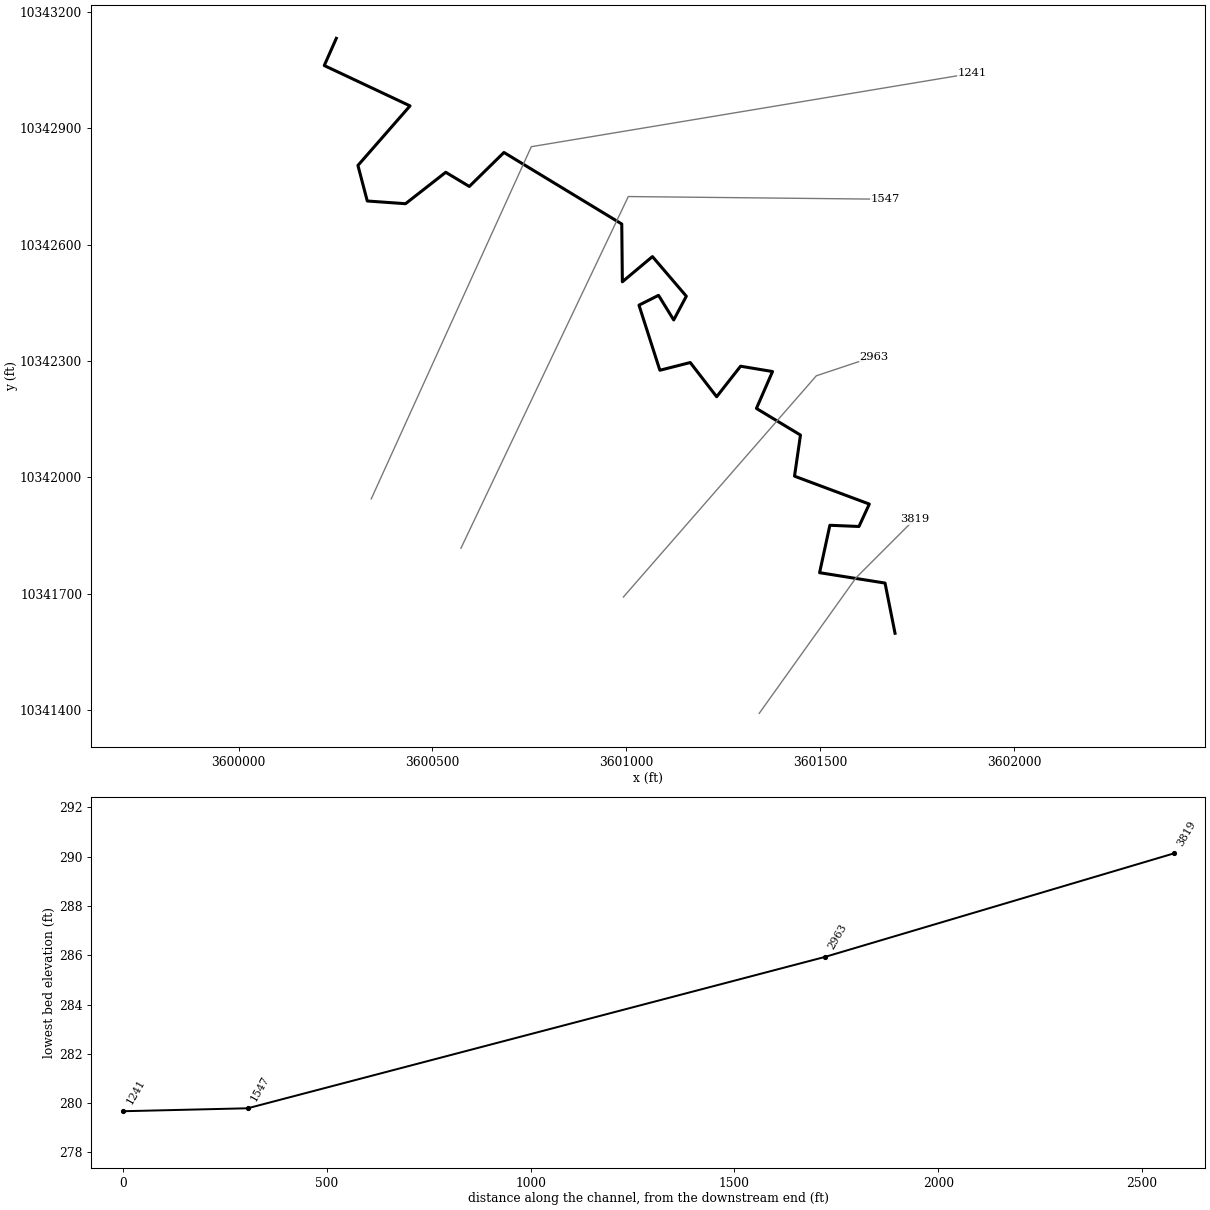
--- UNT0393 IN CEDR CR.prj (project) ---

Proj Title=UNT0393 IN CEDR CR Base Level Engineering
Current Plan=p01
Default Exp/Contr=0.3,0.1
English Units
Geom File=g01
Flow File=f01
Plan File=p01
Y Axis Title=Elevation
X Axis Title(PF)=Main Channel Distance
X Axis Title(XS)=Station
BEGIN DESCRIPTION:
UNT0393 IN CEDR CR
END DESCRIPTION:
DSS Export Rating Curves= 0
DSS Export Rating Curve Sorted= 0
DSS Export Volume Flow Curves= 0
DXF OffsetX= 0
DXF OffsetY= 0
DXF ScaleX= 1
DXF ScaleY= 10

--- UNT0393 IN CEDR CR.p01 (plan) ---

Plan Title=Multiple Run
Short Identifier=Multiple
Geom File=g01
Flow File=f01
Subcritical Flow
K Sum by GR= 0
Std Step Tol= 0.01
Critical Tol= 0.01
Num of Std Step Trials= 20
Max Error Tol= 0.3
Flow Tol Ratio= 0.001
Split Flow NTrial= 30
Split Flow Tol= 0.02
Split Flow Ratio= 0.02
Log Output Level= 0
Friction Slope Method= 1
Unsteady Friction Slope Method= 2
Unsteady Bridges Friction Slope Method= 1
Parabolic Critical Depth
Global Vel Dist=  1 , 1 , 1
Global Log Level= 0
CheckData=True
Encroach Param= -1, 0, 0, 0
BEGIN DESCRIPTION:
Multiple Run
END DESCRIPTION:

--- UNT0393 IN CEDR CR.f01 (steady flow) ---

Flow Title=Multiple
Number of Profiles=7
Profile Names=10-year,25-year,50-year,1pct_min,100-year,1pct_plu,500-year
River Rch & RM= UNT0393 IN CEDR ,Reach-1,3819
     616     830    1005     892    1207    1632    1742
Boundary for River Rch & Prof#=UNT0393 IN CEDR ,Reach-1,1
Up Type=0
Dn Type=3
Dn Slope=0.005
Boundary for River Rch & Prof#=UNT0393 IN CEDR ,Reach-1,2
Up Type=0
Dn Type=3
Dn Slope=0.005
Boundary for River Rch & Prof#=UNT0393 IN CEDR ,Reach-1,3
Up Type=0
Dn Type=3
Dn Slope=0.005
Boundary for River Rch & Prof#=UNT0393 IN CEDR ,Reach-1,4
Up Type=0
Dn Type=3
Dn Slope=0.005
Boundary for River Rch & Prof#=UNT0393 IN CEDR ,Reach-1,5
Up Type=0
Dn Type=3
Dn Slope=0.005
Boundary for River Rch & Prof#=UNT0393 IN CEDR ,Reach-1,6
Up Type=0
Dn Type=3
Dn Slope=0.005
Boundary for River Rch & Prof#=UNT0393 IN CEDR ,Reach-1,7
Up Type=0
Dn Type=3
Dn Slope=0.005

--- UNT0393 IN CEDR CR.g01 (geometry) ---

Geom Title=Existing Conditions
Program Version=4.10

River Reach=UNT0393 IN CEDR ,Reach-1
Reach XY= 30
      3601692.23     10341598.13      3601666.49     10341727.56
      3601497.78     10341754.32       3601524.3     10341876.51
       3601599.3     10341873.39      3601625.95     10341931.16
      3601433.16     10342003.08      3601448.52     10342109.04
      3601334.98     10342177.71      3601376.44     10342272.78
      3601294.08     10342286.51      3601232.42     10342207.87
      3601164.37     10342295.99      3601086.08     10342276.07
      3601032.25     10342443.88      3601082.64     10342469.22
      3601121.72     10342405.74      3601154.27     10342466.92
      3601066.96     10342569.07      3600989.41     10342504.12
      3600987.85     10342653.08       3600684.2     10342837.45
      3600594.88     10342749.82       3600534.2     10342786.41
      3600430.54      10342705.4      3600331.91     10342712.33
      3600307.81     10342804.01      3600442.07     10342957.53
      3600221.01     10343061.53      3600252.11     10343131.64

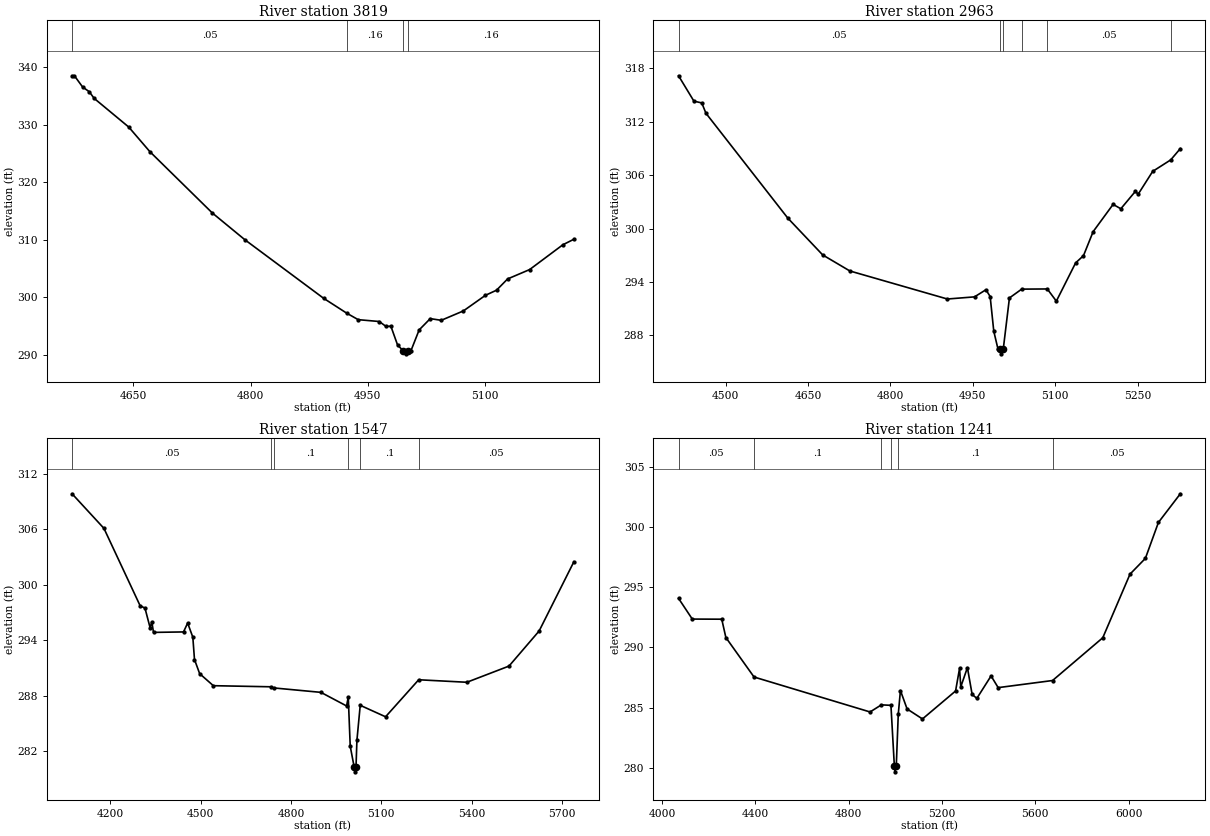
Type RM Length L Ch R = 1 ,3819    ,856,856,856
BEGIN DESCRIPTION:
UNT0393 IN CEDR CR 5.0
END DESCRIPTION:
XS GIS Cut Line= 3
      3601342.13     10341391.67      3601592.11     10341741.64
       3601742.1     10341891.63
#Sta/Elev= 30
  4571.5  338.47  4574.5  338.47    4585  336.52  4593.6  335.69  4599.7  334.55
    4644  329.56    4671  325.29  4750.9  314.63  4792.7  309.96  4893.4  299.79
    4923   297.2  4937.7  296.07  4964.7  295.75  4973.3  294.89  4979.5  294.94
  4988.1  291.66  4995.5  290.63  4998.3  290.13  5001.5  290.63  5005.1  290.63
  5015.7  294.29  5029.9  296.25    5044  295.96  5072.3  297.59  5100.6  300.31
  5114.7  301.19  5128.9  303.15  5157.1  304.78  5199.6  309.09  5213.7  310.05
#Mann= 4 ,-1 , 0
  4571.5     .05       0    4923     .16       0  4995.5     .07       0
  5001.5     .16       0
Bank Sta=4995.5,5001.5
XS Rating Curve= 0 ,0
Exp/Cntr=0.3,0.1

Type RM Length L Ch R = 1 ,2963    ,1416,1416,1416
BEGIN DESCRIPTION:
UNT0393 IN CEDR CR 4.0
END DESCRIPTION:
XS GIS Cut Line= 3
      3600992.09     10341691.62      3601489.33     10342261.78
      3601638.25     10342311.42
#Sta/Elev= 30
  4414.3  317.17  4442.3  314.32  4456.6  314.12  4464.2  312.96  4613.2  301.18
  4676.8  297.04  4726.2  295.24  4903.7  292.09  4953.1  292.33  4973.9  293.13
  4981.6  292.37  4988.2  288.47  4995.8  286.48  4999.4  286.43  5002.2  285.93
  5005.4  286.43  5016.7  292.21    5039   293.2  5085.6  293.22  5102.1  291.85
  5137.2  296.15  5151.5  296.96  5169.1  299.66  5205.4  302.72  5219.5  302.23
  5245.9  304.18  5251.1  303.87  5277.5  306.43  5310.3  307.72  5327.8  308.99
#Mann= 6 ,-1 , 0
  4414.3     .05       0  4999.4     .03       0  5005.4     .05       0
    5039     .16       0  5085.6     .05       0  5310.3     .16       0
Bank Sta=4999.4,5005.4
XS Rating Curve= 0 ,0
Exp/Cntr=0.3,0.1

Type RM Length L Ch R = 1 ,1547    ,306,306,306
BEGIN DESCRIPTION:
UNT0393 IN CEDR CR 2.0
END DESCRIPTION:
XS GIS Cut Line= 3
      3600573.37     10341817.37       3601004.7     10342723.85
      3601667.49     10342716.91
#Sta/Elev= 30
  4072.7  309.84  4178.6   306.1  4298.9  297.73  4314.8  297.49    4332  295.35
  4337.5  296.01  4343.2  294.86  4442.9  294.91  4456.6  295.87  4473.8  294.34
  4479.3  291.93  4496.5   290.4  4541.9   289.1  4734.5  288.98  4741.9  288.86
  4899.2  288.38  4984.5  286.91  4990.1  287.87  4996.6  282.56  5009.8  280.29
  5012.5  279.79  5015.8  280.29  5018.8  283.19  5029.8  286.98    5114  285.74
    5224  289.74    5384  289.47    5524  291.22    5624  295.01  5739.4  302.49
#Mann= 6 ,-1 , 0
  4072.7     .05       0  4734.5     .12       0  4741.9      .1       0
  4990.1     .05       0  5029.8      .1       0    5224     .05       0
Bank Sta=5009.8,5015.8
XS Rating Curve= 0 ,0
Exp/Cntr=0.3,0.1

Type RM Length L Ch R = 1 ,1241    ,0,0,0
BEGIN DESCRIPTION:
UNT0393 IN CEDR CR 1.0
END DESCRIPTION:
XS GIS Cut Line= 3
      3600342.12     10341944.45       3600754.7     10342852.33
      3601892.13     10343041.65
#Sta/Elev= 30
  4071.3  294.07  4130.2  292.35  4256.5  292.34  4274.1  290.82  4394.9  287.54
    4892  284.64  4940.6  285.23  4981.5  285.19  4996.1  280.17  4998.9  279.67
  5002.1  280.17  5004.6  280.26  5012.9  284.44  5022.2  286.42  5050.7  284.89
  5116.6  284.06  5258.5  286.38  5275.6  288.26  5280.7  286.72  5309.2  288.32
  5329.5  286.09  5349.7  285.77  5410.6  287.63    5441  286.66  5674.1  287.25
  5889.3   290.8    6006  296.08  6071.9  297.39  6127.7  300.37  6221.6  302.75
#Mann= 6 ,-1 , 0
  4071.3     .05       0  4394.9      .1       0  4940.6     .16       0
  4981.5     .05       0  5012.9      .1       0  5674.1     .05       0
Bank Sta=4996.1,5002.1
XS Rating Curve= 0 ,0
Exp/Cntr=0.3,0.1

Chan Stop Cuts=-1
Use User Specified Reach Order=0
Composite Channel Slope=5