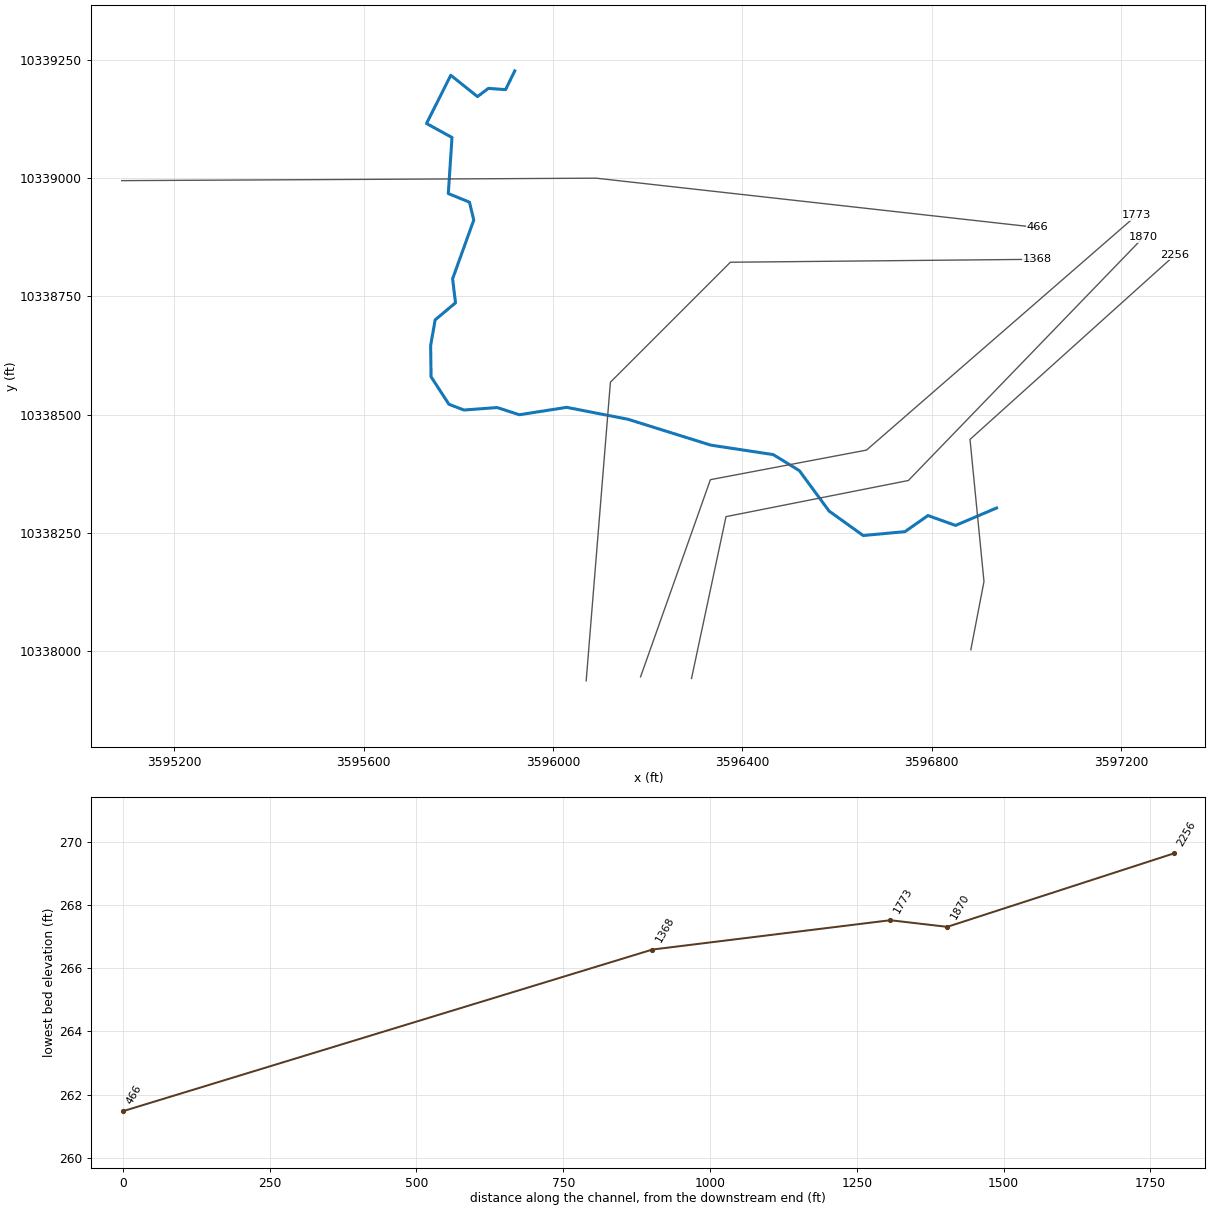
--- UNT0394 IN CEDR CR.prj (project) ---

Proj Title=UNT0394 IN CEDR CR Base Level Engineering
Current Plan=p01
Default Exp/Contr=0.3,0.1
English Units
Geom File=g01
Flow File=f01
Plan File=p01
Y Axis Title=Elevation
X Axis Title(PF)=Main Channel Distance
X Axis Title(XS)=Station
BEGIN DESCRIPTION:
UNT0394 IN CEDR CR
END DESCRIPTION:
DSS Export Rating Curves= 0
DSS Export Rating Curve Sorted= 0
DSS Export Volume Flow Curves= 0
DXF OffsetX= 0
DXF OffsetY= 0
DXF ScaleX= 1
DXF ScaleY= 10

--- UNT0394 IN CEDR CR.p01 (plan) ---

Plan Title=Multiple Run
Short Identifier=Multiple
Geom File=g01
Flow File=f01
Subcritical Flow
K Sum by GR= 0
Std Step Tol= 0.01
Critical Tol= 0.01
Num of Std Step Trials= 20
Max Error Tol= 0.3
Flow Tol Ratio= 0.001
Split Flow NTrial= 30
Split Flow Tol= 0.02
Split Flow Ratio= 0.02
Log Output Level= 0
Friction Slope Method= 1
Unsteady Friction Slope Method= 2
Unsteady Bridges Friction Slope Method= 1
Parabolic Critical Depth
Global Vel Dist=  1 , 1 , 1
Global Log Level= 0
CheckData=True
Encroach Param= -1, 0, 0, 0
BEGIN DESCRIPTION:
Multiple Run
END DESCRIPTION:

--- UNT0394 IN CEDR CR.f01 (steady flow) ---

Flow Title=Multiple
Number of Profiles=7
Profile Names=10-year,25-year,50-year,1pct_min,100-year,1pct_plu,500-year
River Rch & RM= UNT0394 IN CEDR ,Reach-1,2256
     646     877    1066     951    1287    1740    1875
Boundary for River Rch & Prof#=UNT0394 IN CEDR ,Reach-1,1
Up Type=0
Dn Type=3
Dn Slope=0.005
Boundary for River Rch & Prof#=UNT0394 IN CEDR ,Reach-1,2
Up Type=0
Dn Type=3
Dn Slope=0.005
Boundary for River Rch & Prof#=UNT0394 IN CEDR ,Reach-1,3
Up Type=0
Dn Type=3
Dn Slope=0.005
Boundary for River Rch & Prof#=UNT0394 IN CEDR ,Reach-1,4
Up Type=0
Dn Type=3
Dn Slope=0.005
Boundary for River Rch & Prof#=UNT0394 IN CEDR ,Reach-1,5
Up Type=0
Dn Type=3
Dn Slope=0.005
Boundary for River Rch & Prof#=UNT0394 IN CEDR ,Reach-1,6
Up Type=0
Dn Type=3
Dn Slope=0.005
Boundary for River Rch & Prof#=UNT0394 IN CEDR ,Reach-1,7
Up Type=0
Dn Type=3
Dn Slope=0.005

--- UNT0394 IN CEDR CR.g01 (geometry) ---

Geom Title=Existing Conditions
Program Version=4.10

River Reach=UNT0394 IN CEDR ,Reach-1
Reach XY= 30
      3596937.35     10338302.49       3596850.8     10338265.71
      3596792.46     10338286.54      3596743.85     10338252.51
      3596655.57     10338244.35      3596583.52       10338296.
      3596520.59     10338381.51      3596465.47     10338415.36
      3596333.52     10338435.33      3596158.61     10338490.01
      3596028.84     10338515.19      3595929.01     10338499.56
      3595882.13     10338514.75      3595811.82     10338509.54
      3595780.14      10338521.7      3595742.38     10338579.86
      3595741.51     10338645.83      3595751.06     10338700.08
      3595794.03     10338736.11      3595787.95     10338786.89
      3595832.65     10338911.02      3595823.54     10338948.78
      3595778.84     10338967.01      3595786.65      10339085.5
      3595732.83     10339115.01      3595784.04     10339217.01
      3595840.47     10339171.87      3595863.47     10339189.23
      3595899.93     10339186.63      3595919.22     10339226.15

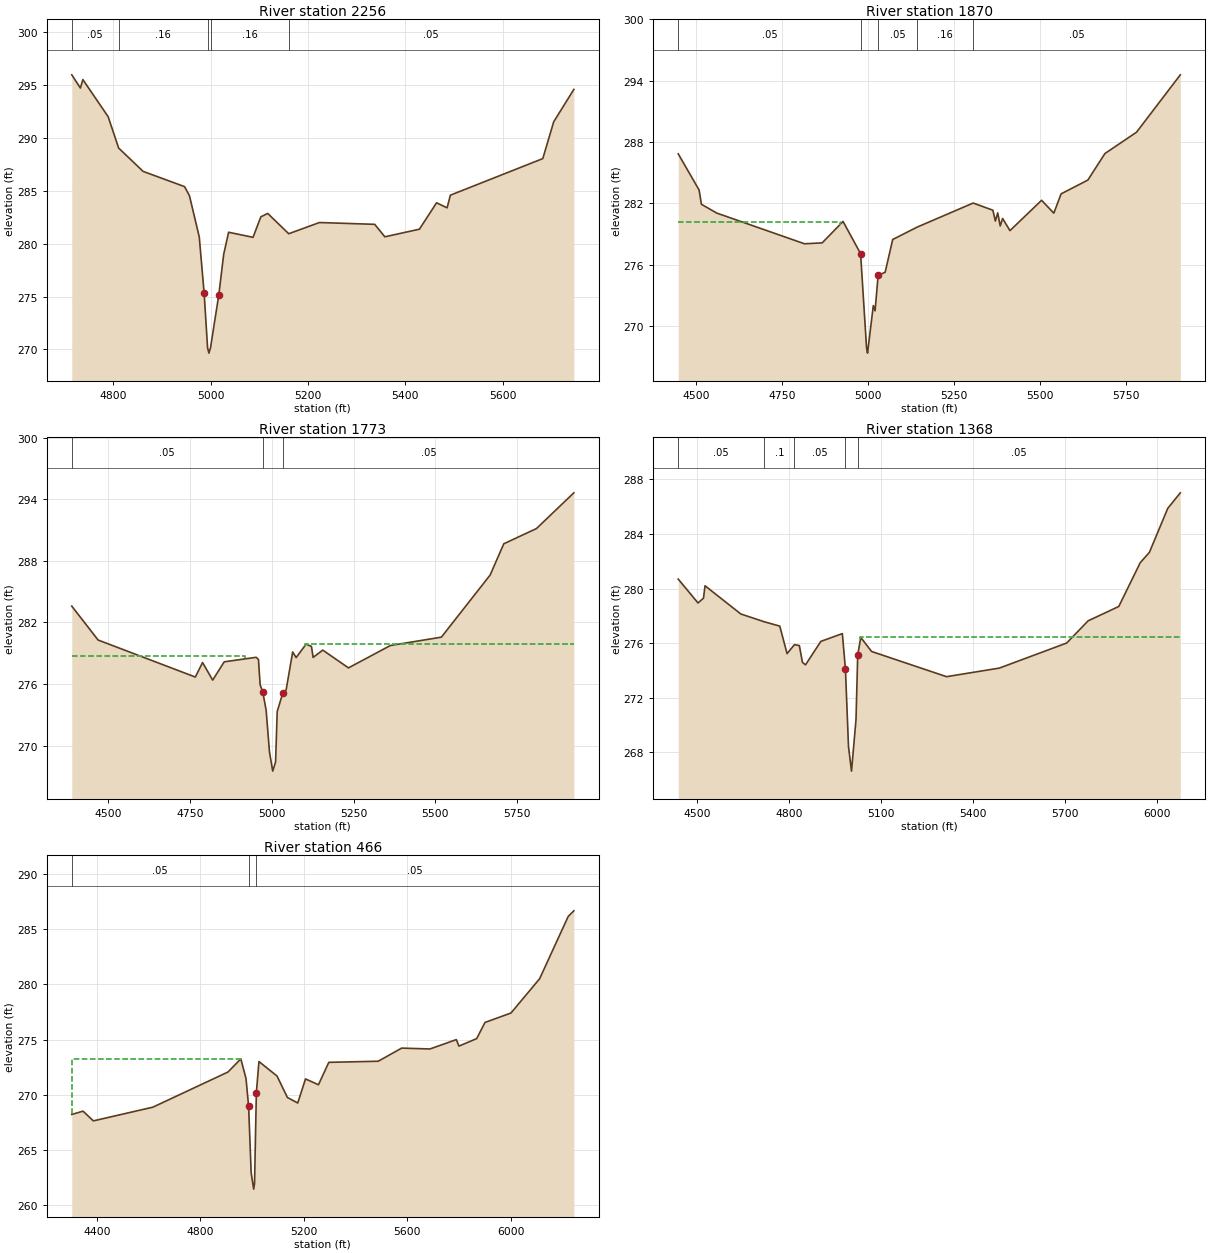
Type RM Length L Ch R = 1 ,2256    ,386,386,386
BEGIN DESCRIPTION:
UNT0394 IN CEDR CR 3.0
END DESCRIPTION:
XS GIS Cut Line= 4
      3596883.04     10338002.96      3596910.82     10338147.09
      3596881.31     10338447.44      3597314.51     10338837.33
#Sta/Elev= 30
  4714.6  295.99  4732.3  294.74  4737.4  295.54  4789.3  292.03  4810.9  289.06
  4861.2  286.85  4946.3  285.41  4956.4  284.54  4976.5  280.65  4986.5  275.34
  4993.6  270.15  4996.3  269.65  4999.6  270.15  5016.7  275.18  5026.7     279
  5036.8  281.09    5087  280.61    5103  282.55  5117.2  282.87  5160.3  280.95
  5223.3  282.01  5336.9  281.84  5357.8  280.66  5428.8  281.38    5464  283.88
  5485.6   283.4  5492.4   284.6  5682.2  288.06  5704.6  291.54    5746  294.61
#Mann= 5 ,-1 , 0
  4714.6     .05       0  4810.9     .16       0  4993.6     .07       0
  4999.6     .16       0  5160.3     .05       0
Bank Sta=4986.5,5016.7
XS Rating Curve= 0 ,0
Exp/Cntr=0.3,0.1

Type RM Length L Ch R = 1 ,1870    ,97,97,97
BEGIN DESCRIPTION:
Mapping XS 16c5ba15
END DESCRIPTION:
XS GIS Cut Line= 4
      3596292.77     10337942.24      3596365.68     10338284.25
       3596751.1     10338360.64      3597248.22     10338875.08
#Sta/Elev= 30
  4448.8  286.84  4509.5  283.29  4516.1   281.9  4560.5  281.04  4815.6  278.03
  4866.8  278.12  4927.4  280.22  4978.4  277.06  4995.7  267.82  4998.5  267.32
  5015.3  271.98  5020.4  271.46  5029.3  274.94  5049.7  275.24  5071.6  278.45
  5143.1  279.67  5305.3  282.02  5362.5  281.32  5369.7  280.26  5376.6  281.06
  5383.8  279.78  5390.8  280.51  5412.1  279.32    5504  282.29  5539.5  281.03
  5560.6  282.92  5638.3  284.27  5687.9  286.87  5779.7  288.96  5906.8  294.58
#Mann= 5 ,-1 , 0
  4448.8     .05       0  4978.4    .035       0  5029.3     .05       0
  5143.1     .16       0  5305.3     .05       0
#XS Ineff= 2 , 0
         4918.28  280.19
Permanent Ineff=
       F       F
Bank Sta=4978.4,5029.3
XS Rating Curve= 0 ,0
Exp/Cntr=0.3,0.1

Type RM Length L Ch R = 1 ,1773    ,405,405,405
BEGIN DESCRIPTION:
Mapping XS 16678eeb
END DESCRIPTION:
XS GIS Cut Line= 4
      3596185.11     10337945.66       3596332.7     10338362.37
      3596662.56     10338424.87      3597233.71     10338921.38
#Sta/Elev= 30
  4388.6  283.59  4469.2  280.29  4766.2  276.69  4788.4   278.1  4819.3  276.39
  4854.6  278.17  4952.2  278.61  4959.2   278.4  4964.3  275.95  4972.6   275.2
  4982.7  273.46  4992.9   269.4  5002.8  267.53  5011.5  268.42  5016.6  273.34
  5033.6  275.13  5043.8  275.43  5063.8  279.13  5074.3  278.58  5104.9  279.89
  5121.2  279.67  5126.3   278.6  5155.8  279.31  5234.4  277.58  5362.6  279.76
  5518.3  280.57  5667.4  286.62  5709.1  289.66  5808.9  291.14  5923.2  294.62
#Mann= 3 , 0 , 0
  4388.6     .05       0  4972.6     .04       0  5033.6     .05       0
#XS Ineff= 2 , 0
         4918.55  278.69 5101.21          279.94
Permanent Ineff=
       F       F
Bank Sta=4972.6,5033.6
XS Rating Curve= 0 ,0
Exp/Cntr=0.3,0.1

Type RM Length L Ch R = 1 ,1368    ,902,902,902
BEGIN DESCRIPTION:
UNT0394 IN CEDR CR 2.0
END DESCRIPTION:
XS GIS Cut Line= 4
      3596070.19     10337937.35      3596121.39     10338568.32
      3596374.92     10338821.85       3597023.1     10338828.07
#Sta/Elev= 30
  4437.4  280.69  4501.9  278.94  4519.9  279.29  4524.9   280.2  4641.9  278.13
  4718.2  277.56    4769  277.24  4792.9  275.22    4817  275.88    4833  275.81
    4843  274.58  4853.1   274.4  4903.2  276.12  4973.4  276.69  4983.5  274.08
  4993.5   268.4  5003.3   266.6    5018  270.38  5023.6  275.12  5033.6  276.41
  5068.8  275.38  5313.7  273.53  5486.2  274.16  5706.2     276  5776.2  277.63
  5876.2  278.68  5946.2  281.89  5976.2  282.65  6036.2  285.88  6077.2  287.02
#Mann= 5 ,-1 , 0
  4437.4     .05       0  4718.2      .1       0    4817     .05       0
  4983.5    .035       0  5023.6     .05       0
#XS Ineff= 2 , 0
         4969.76  276.65 5032.66          276.41
Permanent Ineff=
       F       F
Bank Sta=4983.5,5023.6
XS Rating Curve= 0 ,0
Exp/Cntr=0.3,0.1

Type RM Length L Ch R = 1 ,466     ,0,0,0
BEGIN DESCRIPTION:
UNT0394 IN CEDR CR 1.0
END DESCRIPTION:
XS GIS Cut Line= 3
      3595088.65     10338994.27      3596091.28     10338999.48
      3597023.54     10338895.32
#Sta/Elev= 30
  4303.6  268.23  4347.1  268.53  4387.1  267.65  4617.1  268.89  4907.1  272.07
  4957.1  273.26  4977.1  271.49  4987.1  268.99  4997.1  262.93  5006.8  261.47
  5010.1  261.97  5017.1  270.21  5027.1  273.02  5097.1  271.71  5137.1  269.77
  5177.1  269.27  5207.1  271.45  5257.1  270.92  5297.1  272.95  5488.2  273.05
  5578.8  274.24  5688.2  274.16  5790.1  275.01  5800.1  274.42  5868.8   275.1
  5900.7  276.56  6001.4  277.42    6112  280.52  6222.7  286.17  6244.3  286.67
#Mann= 3 , 0 , 0
  4303.6     .05       0  4987.1    .035       0  5017.1     .05       0
#XS Ineff= 2 , 0
         4957.66  273.28 5033.27           272.9
Permanent Ineff=
       F       F
Bank Sta=4987.1,5017.1
XS Rating Curve= 0 ,0
Exp/Cntr=0.3,0.1

Chan Stop Cuts=-1
Use User Specified Reach Order=0
Composite Channel Slope=5