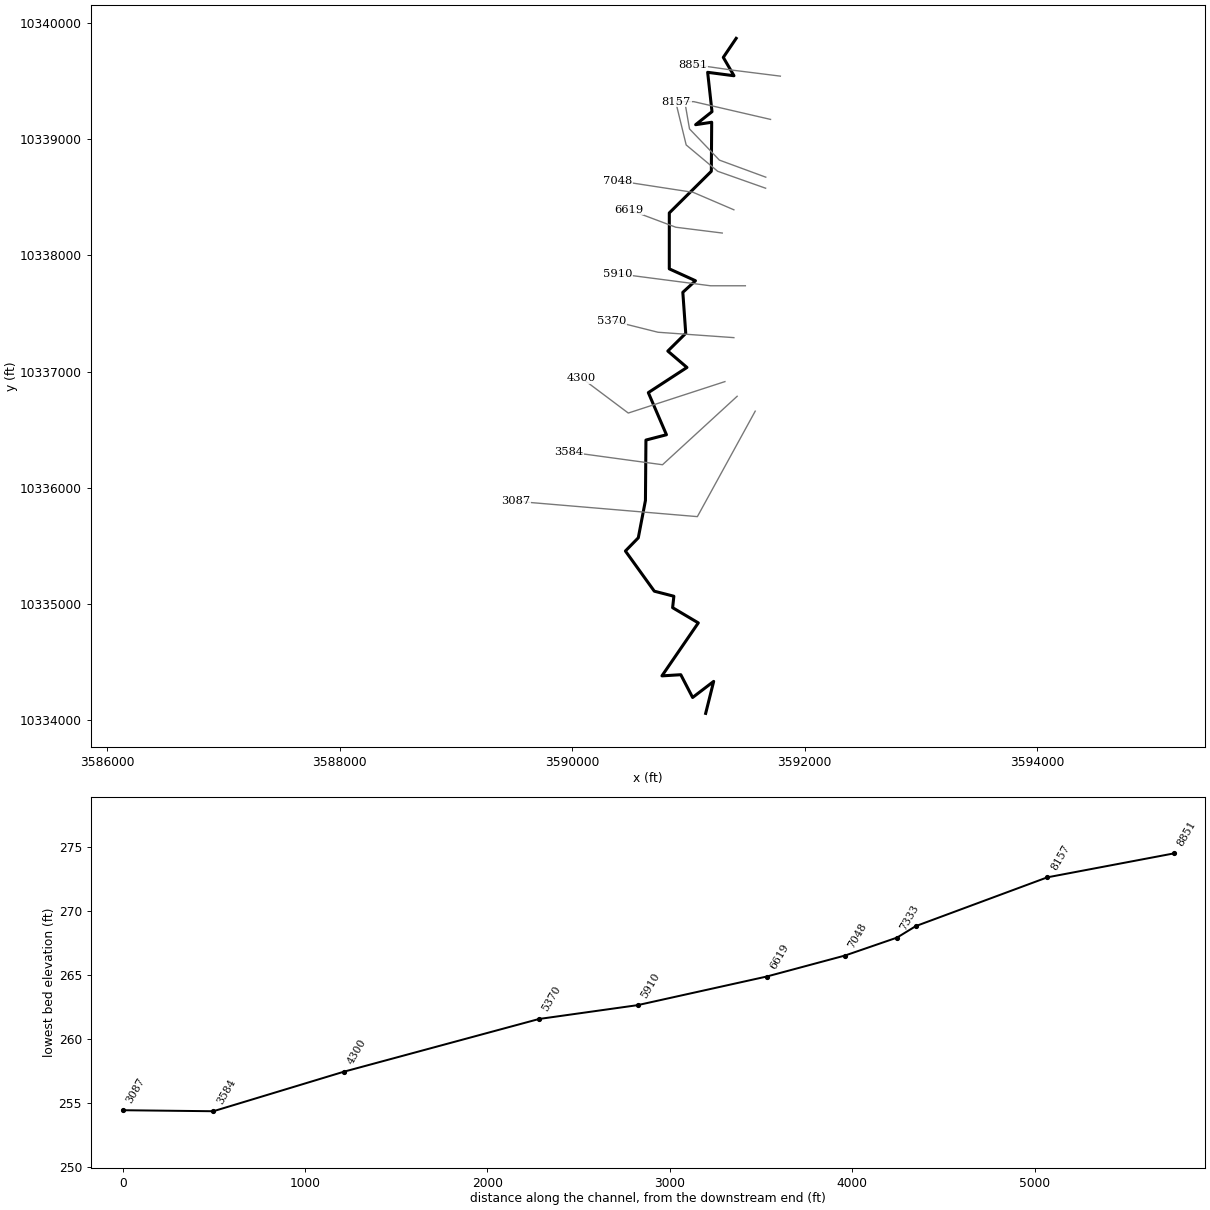
--- UNT0397 IN CEDR CR.prj (project) ---

Proj Title=UNT0397 IN CEDR CR Base Level Engineering
Current Plan=p01
Default Exp/Contr=0.3,0.1
English Units
Geom File=g01
Flow File=f01
Plan File=p01
BEGIN DESCRIPTION:
UNT0397 IN CEDR CR
END DESCRIPTION:

--- UNT0397 IN CEDR CR.p01 (plan) ---

Plan Title=Multiple Run
Short Identifier=Multiple
Geom File=g01
Flow File=f01
Subcritical Flow
K Sum by GR= 0
Std Step Tol= 0.01
Critical Tol= 0.01
Num of Std Step Trials= 20
Max Error Tol= 0.3
Flow Tol Ratio= 0.001
Split Flow NTrial= 30
Split Flow Tol= 0.02
Split Flow Ratio= 0.02
Log Output Level= 0
Friction Slope Method= 1
Unsteady Friction Slope Method= 2
Unsteady Bridges Friction Slope Method= 1
Parabolic Critical Depth
Global Vel Dist=  1 , 1 , 1
Global Log Level= 0
CheckData=True
Encroach Param= -1, 0, 0, 0
BEGIN DESCRIPTION:
Multiple Run
END DESCRIPTION:

--- UNT0397 IN CEDR CR.f01 (steady flow) ---

Flow Title=Multiple
Number of Profiles=7
Profile Names=10-year,25-year,50-year,1pct_min,100-year,1pct_plu,500-year
River Rch & RM= UNT0397 IN CEDR ,Reach-1,8851
     829    1137    1391    1247    1686    2280    2481
Boundary for River Rch & Prof#=UNT0397 IN CEDR ,Reach-1,1
Up Type=0
Dn Type=3
Dn Slope=0.005
Boundary for River Rch & Prof#=UNT0397 IN CEDR ,Reach-1,2
Up Type=0
Dn Type=3
Dn Slope=0.005
Boundary for River Rch & Prof#=UNT0397 IN CEDR ,Reach-1,3
Up Type=0
Dn Type=3
Dn Slope=0.005
Boundary for River Rch & Prof#=UNT0397 IN CEDR ,Reach-1,4
Up Type=0
Dn Type=3
Dn Slope=0.005
Boundary for River Rch & Prof#=UNT0397 IN CEDR ,Reach-1,5
Up Type=0
Dn Type=3
Dn Slope=0.005
Boundary for River Rch & Prof#=UNT0397 IN CEDR ,Reach-1,6
Up Type=0
Dn Type=3
Dn Slope=0.005
Boundary for River Rch & Prof#=UNT0397 IN CEDR ,Reach-1,7
Up Type=0
Dn Type=3
Dn Slope=0.005

--- UNT0397 IN CEDR CR.g01 (geometry) ---

Geom Title=Existing Conditions

River Reach=UNT0397 IN CEDR ,Reach-1
Reach XY= 30
      3591411.95     10339866.88      3591301.03     10339702.96
      3591393.04     10339544.97      3591166.48     10339574.49
      3591203.80     10339235.95      3591063.18     10339123.97
      3591201.20     10339144.80      3591198.17     10338723.23
      3590836.55     10338364.67      3590836.44     10337883.48
      3591061.61     10337781.33      3590952.84     10337681.51
      3590977.94     10337328.87      3590823.83     10337176.20
      3590988.42     10337035.12      3590655.95     10336818.59
      3590812.00     10336456.17      3590635.42     10336410.42
      3590631.21     10335891.04      3590569.67     10335569.38
      3590458.77     10335455.76      3590707.54     10335110.17
      3590875.77     10335066.71      3590865.05     10334968.22
      3591085.92     10334837.37      3590773.14     10334381.58
      3590935.36     10334391.49      3591037.15     10334195.59
      3591218.24     10334334.09      3591149.36     10334058.87

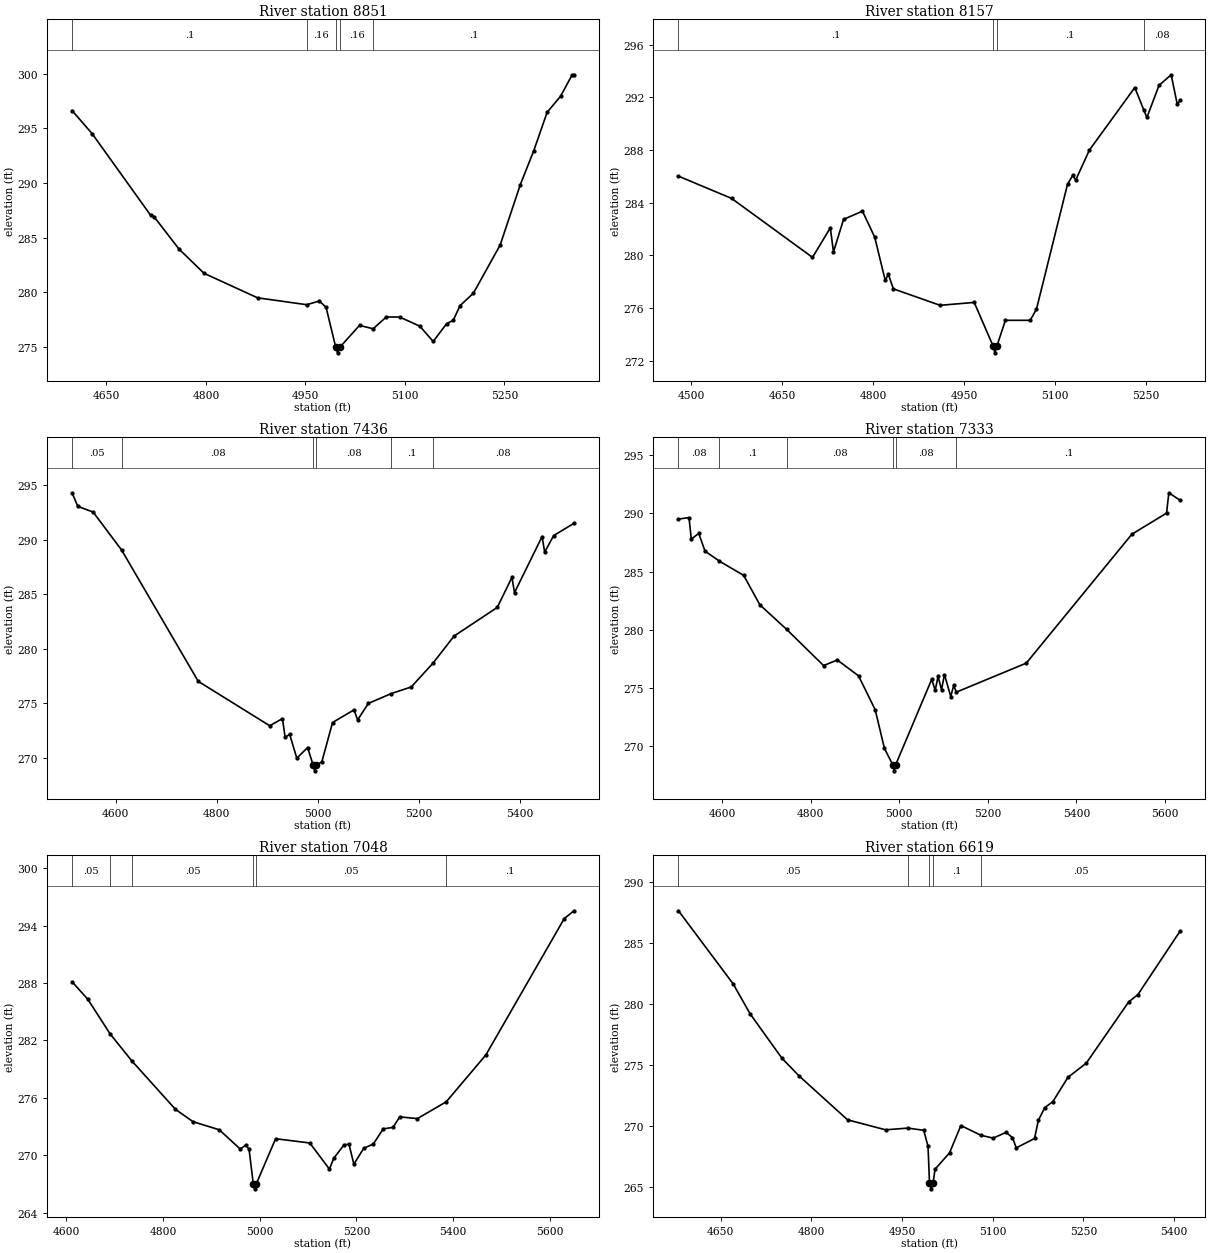
Type RM Length L Ch R = 1,8851,694,694,694
BEGIN DESCRIPTION:
UNT0397 IN CEDR CR 12.0
END DESCRIPTION:
XS GIS Cut Line= 3
      3591792.10     10339541.64      3591392.11     10339591.64
      3591042.07     10339641.65
#Sta/Elev= 30
  4598.2  296.62  4628.4  294.51  4716.6  287.05  4721.7  286.92  4759.4  283.96
  4797.2  281.74  4877.9  279.50  4952.0  278.87  4971.1  279.21  4981.2  278.63
  4995.8  274.97  4998.5  274.47  5001.8  274.97  5031.6  276.98  5052.2  276.67
  5072.0  277.75  5092.2  277.74  5122.5  276.91  5142.7  275.51  5162.9  277.13
  5173.0  277.45  5183.1  278.78  5203.3  279.92  5243.7  284.33  5274.1  289.85
  5294.3  292.94  5314.5  296.46  5334.7  297.92  5352.3  299.89  5354.9  299.89
#Mann=5,-1,0
  4598.2     0.1       0  4952.0    0.16       0  4995.8    0.07       0
  5001.8    0.16       0  5052.2     0.1       0
Bank Sta=4995.8,5001.8
Exp/Cntr=0.3,0.1

Type RM Length L Ch R = 1,8157,721,721,721
BEGIN DESCRIPTION:
UNT0397 IN CEDR CR 11.0
END DESCRIPTION:
XS GIS Cut Line= 3
      3591707.48     10339169.31      3591046.97     10339322.14
      3590897.03     10339322.14
#Sta/Elev= 30
  4479.1  286.02  4566.7  284.33  4700.2  279.85  4729.6  282.09  4734.8  280.27
  4751.5  282.74  4782.6  283.36  4802.8  281.39  4820.2  278.10  4825.3  278.57
  4833.6  277.46  4910.7  276.21  4967.0  276.43  4998.3  273.10  5001.0  272.60
  5004.3  273.10  5018.4  275.07  5059.4  275.07  5069.7  275.92  5121.0  285.42
  5129.4  286.07  5134.5  285.73  5157.0  288.00  5231.9  292.75  5246.6  291.06
  5251.9  290.48  5271.9  292.92  5291.9  293.72  5301.9  291.48  5307.0  291.80
#Mann=4,-1,0
  4479.1     0.1       0  4998.3    0.07       0  5004.3     0.1       0
  5246.6    0.08       0
Bank Sta=4998.3,5004.3
Exp/Cntr=0.3,0.1

Type RM Length L Ch R = 1,7436,103,103,103
BEGIN DESCRIPTION:
UNT0397 IN CEDR CR 10.0
END DESCRIPTION:
XS GIS Cut Line= 4
      3591666.54     10338672.33      3591267.23     10338819.22
      3591010.30     10339087.69      3590976.77     10339281.13
#Sta/Elev= 30
  4513.8  294.33  4525.1  293.08  4555.5  292.56  4612.1  289.05  4763.6  277.01
  4905.1  272.93  4930.3  273.59  4935.5  271.87  4944.5  272.14  4958.7  269.95
  4980.0  270.93  4991.2  269.29  4993.9  268.79  4997.2  269.29  5008.3  269.63
  5029.4  273.23  5071.9  274.39  5079.1  273.47  5100.2  274.98  5145.7  275.89
  5185.1  276.49  5227.7  278.65  5270.0  281.17  5355.5  283.80  5384.5  286.56
  5389.6  285.16  5444.2  290.31  5449.3  288.88  5467.1  290.40  5507.2  291.52
#Mann=6,-1,0
  4513.8    0.05       0  4612.1    0.08       0  4991.2    0.07       0
  4997.2    0.08       0  5145.7     0.1       0  5227.7    0.08       0
Bank Sta=4991.2,4997.2
Exp/Cntr=0.3,0.1

Type RM Length L Ch R = 1,7333,285,285,285
BEGIN DESCRIPTION:
Mapping XS 1f46f5d8
END DESCRIPTION:
XS GIS Cut Line= 4
      3591665.22     10338577.28      3591252.49     10338723.11
      3590981.65     10338949.67      3590900.94     10339281.65
#Sta/Elev= 30
  4501.8  289.51  4525.5  289.64  4530.8  287.79  4547.5  288.28  4561.7  286.76
  4594.1  285.90  4649.1  284.67  4685.4  282.15  4745.8  280.04  4829.3  276.93
  4860.2  277.41  4908.1  276.05  4945.8  273.13  4966.6  269.81  4985.7  268.39
  4988.5  267.89  4991.7  268.39  5073.3  275.75  5081.1  274.80  5087.6  276.00
  5095.4  274.86  5102.0  276.16  5116.3  274.27  5122.8  275.22  5128.9  274.65
  5286.7  277.14  5524.9  288.21  5603.2  290.02  5608.4  291.77  5634.3  291.11
#Mann=6,-1,0
  4501.8    0.08       0  4594.1     0.1       0  4745.8    0.08       0
  4985.7    0.07       0  4991.7    0.08       0  5128.9     0.1       0
Bank Sta=4985.7,4991.7
Exp/Cntr=0.3,0.1

Type RM Length L Ch R = 1,7048,429,429,429
BEGIN DESCRIPTION:
UNT0397 IN CEDR CR 9.0
END DESCRIPTION:
XS GIS Cut Line= 3
      3591392.07     10338391.66      3591042.11     10338541.64
      3590392.10     10338641.64
#Sta/Elev= 30
  4611.8  288.13  4644.4  286.30  4690.3  282.70  4735.0  279.89  4825.7  274.80
  4862.0  273.51  4916.4  272.66  4959.9  270.64  4970.8  271.06  4978.0  270.64
  4986.8  266.99  4989.6  266.49  4992.8  266.99  5033.0  271.73  5103.8  271.28
  5144.3  268.55  5153.2  269.68  5174.7  271.10  5184.8  271.14  5194.9  269.07
  5215.1  270.71  5235.4  271.19  5255.6  272.76  5275.8  272.91  5289.8  274.01
  5326.4  273.83  5386.1  275.59  5468.1  280.49  5630.0  294.72  5650.2  295.55
#Mann=6,-1,0
  4611.8    0.05       0  4690.3     0.1       0  4735.0    0.05       0
  4986.8    0.03       0  4992.8    0.05       0  5386.1     0.1       0
Bank Sta=4986.8,4992.8
Exp/Cntr=0.3,0.1

Type RM Length L Ch R = 1,6619,709,709,709
BEGIN DESCRIPTION:
UNT0397 IN CEDR CR 8.0
END DESCRIPTION:
XS GIS Cut Line= 3
      3591292.12     10338191.64      3590892.11     10338241.64
      3590492.13     10338391.63
#Sta/Elev= 30
  4580.0  287.65  4670.7  281.64  4698.4  279.21  4751.3  275.55  4779.1  274.13
  4859.7  270.51  4922.7  269.69  4959.6  269.83  4985.8  269.65  4992.9  268.33
  4995.3  265.35  4998.0  264.85  5001.3  265.35  5004.5  266.46  5028.5  267.80
  5047.2  270.04  5080.5  269.24  5100.6  269.01  5122.0  269.48  5132.6  269.05
  5138.9  268.21  5169.1  268.98  5175.4  270.46  5186.0  271.51  5199.4  272.00
  5224.3  273.99  5254.6  275.15  5324.9  280.18  5340.0  280.77  5410.3  286.01
#Mann=5,-1,0
  4580.0    0.05       0  4959.6     0.1       0  4995.3    0.07       0
  5001.3     0.1       0  5080.5    0.05       0
Bank Sta=4995.3,5001.3
Exp/Cntr=0.3,0.1

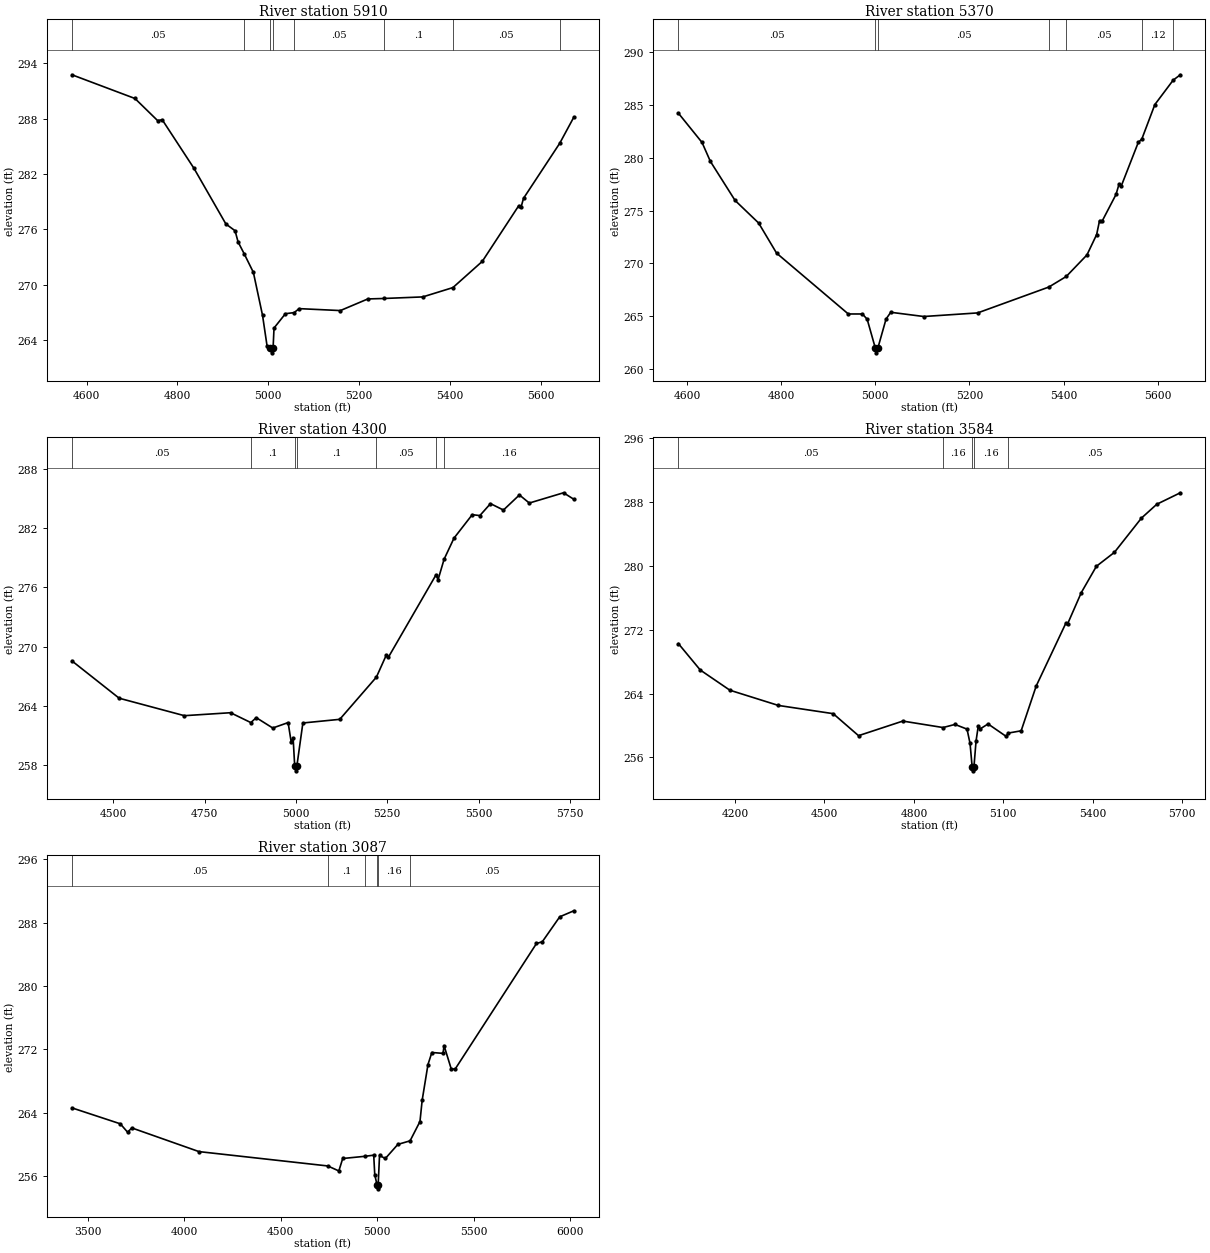
Type RM Length L Ch R = 1,5910,540,540,540
BEGIN DESCRIPTION:
UNT0397 IN CEDR CR 7.0
END DESCRIPTION:
XS GIS Cut Line= 3
      3591490.92     10337737.96      3591190.93     10337737.96
      3590392.12     10337841.64
#Sta/Elev= 30
  4567.8  292.74  4706.6  290.17  4756.6  287.77  4766.6  287.87  4836.6  282.60
  4906.9  276.57  4927.1  275.84  4933.7  274.63  4947.3  273.33  4967.4  271.33
  4987.6  266.67  4997.7  263.31  5004.8  263.11  5007.5  262.61  5010.8  263.11
  5012.9  265.30  5038.0  266.85  5057.2  266.97  5068.3  267.40  5159.0  267.19
  5219.5  268.45  5254.8  268.50  5340.5  268.67  5406.9  269.68  5471.6  272.52
  5552.0  278.56  5557.1  278.41  5562.4  279.35  5642.1  285.31  5673.3  288.15
#Mann=8,-1,0
  4567.8    0.05       0  4947.3     0.1       0  5004.8    0.07       0
  5010.8     0.1       0  5057.2    0.05       0  5254.8     0.1       0
  5406.9    0.05       0  5642.1     0.1       0
Bank Sta=5004.8,5010.8
Exp/Cntr=0.3,0.1

Type RM Length L Ch R = 1,5370,1070,1070,1070
BEGIN DESCRIPTION:
UNT0397 IN CEDR CR 5.0
END DESCRIPTION:
XS GIS Cut Line= 3
      3591392.15     10337291.64      3590739.65     10337338.01
      3590339.61     10337438.02
#Sta/Elev= 30
  4581.6  284.22  4631.8  281.45  4649.5  279.66  4702.0  275.96  4752.1  273.82
  4790.2  270.97  4942.6  265.21  4972.6  265.21  4982.7  264.71  4999.7  262.03
  5002.5  261.53  5005.7  262.03  5022.8  264.73  5032.8  265.37  5103.0  264.97
  5217.4  265.31  5368.7  267.76  5405.7  268.76  5449.7  270.80  5470.3  272.73
  5476.5  274.06  5481.6  273.97  5511.5  276.53  5517.7  277.48  5522.9  277.36
  5558.9  281.47  5566.1  281.75  5594.0  285.04  5632.9  287.35  5648.1  287.86
#Mann=7,-1,0
  4581.6    0.05       0  4999.7    0.03       0  5005.7    0.05       0
  5368.7    0.16       0  5405.7    0.05       0  5566.1    0.12       0
  5632.9    0.05       0
Bank Sta=4999.7,5005.7
Exp/Cntr=0.3,0.1

Type RM Length L Ch R = 1,4300,716,716,716
BEGIN DESCRIPTION:
UNT0397 IN CEDR CR 4.0
END DESCRIPTION:
XS GIS Cut Line= 3
      3591315.05     10336913.46      3590483.51     10336642.82
      3590083.49     10336942.84
#Sta/Elev= 30
  4386.5  268.55  4515.8  264.77  4694.3  263.00  4820.8  263.30  4876.4  262.30
  4891.2  262.80  4936.4  261.75  4978.5  262.30  4987.0  260.31  4992.2  260.74
  4996.5  257.91  4999.3  257.41  5002.5  257.91  5018.9  262.26  5119.9  262.63
  5220.3  266.91  5247.7  269.17  5252.9  268.91  5383.8  277.29  5389.0  276.76
  5405.6  278.85  5432.7  280.99  5482.7  283.37  5503.6  283.28  5532.7  284.49
  5568.2  283.84  5611.9  285.37  5639.0  284.55  5732.7  285.59  5761.0  284.93
#Mann=7,-1,0
  4386.5    0.05       0  4876.4     0.1       0  4996.5    0.07       0
  5002.5     0.1       0  5220.3    0.05       0  5383.8     0.1       0
  5405.6    0.16       0
Bank Sta=4996.5,5002.5
Exp/Cntr=0.3,0.1

Type RM Length L Ch R = 1,3584,497,497,497
BEGIN DESCRIPTION:
UNT0397 IN CEDR CR 3.0
END DESCRIPTION:
XS GIS Cut Line= 3
      3591420.29     10336787.15      3590778.02     10336198.12
      3589973.04     10336307.89
#Sta/Elev= 30
  4009.9  270.27  4083.3  266.96  4182.6  264.43  4345.4  262.52  4529.2  261.49
  4614.2  258.73  4762.8  260.56  4897.7  259.75  4937.8  260.14  4978.2  259.55
  4988.3  257.77  4995.4  254.82  4998.1  254.32  5001.4  254.82  5008.5  258.06
  5016.0  259.96  5021.0  259.55  5048.8  260.20  5109.4  258.64  5117.1  259.06
  5159.8  259.34  5210.3  264.96  5310.3  272.88  5315.4  272.73  5361.7  276.68
  5412.2  279.97  5472.7  281.72  5563.5  286.02  5614.8  287.75  5693.8  289.19
#Mann=5,-1,0
  4009.9    0.05       0  4897.7    0.16       0  4995.4    0.07       0
  5001.4    0.16       0  5117.1    0.05       0
Bank Sta=4995.4,5001.4
Exp/Cntr=0.3,0.1

Type RM Length L Ch R = 1,3087,0,0,0
BEGIN DESCRIPTION:
UNT0397 IN CEDR CR 1.0
END DESCRIPTION:
XS GIS Cut Line= 3
      3591575.72     10336659.20      3591078.07     10335751.71
      3589519.31     10335883.44
#Sta/Elev= 30
  3418.9  264.62  3669.2  262.61  3707.1  261.55  3728.9  262.09  4076.7  259.10
  4743.5  257.29  4801.1  256.66  4821.2  258.23  4937.6  258.51  4981.7  258.65
  4987.1  256.19  4998.8  254.90  5001.5  254.40  5004.8  254.90  5011.8  258.61
  5041.9  258.23  5106.7  260.01  5170.0  260.46  5221.3  262.90  5232.6  265.58
  5262.7  270.09  5282.8  271.61  5340.9  271.50  5345.9  272.49  5383.1  269.54
  5403.2  269.51  5824.7  285.37  5854.8  285.59  5945.1  288.74  6018.2  289.50
#Mann=6,-1,0
  3418.9    0.05       0  4743.5     0.1       0  4937.6    0.16       0
  4998.8    0.07       0  5004.8    0.16       0  5170.0    0.05       0
Bank Sta=4998.8,5004.8
Exp/Cntr=0.3,0.1

Chan Stop Cuts=-1