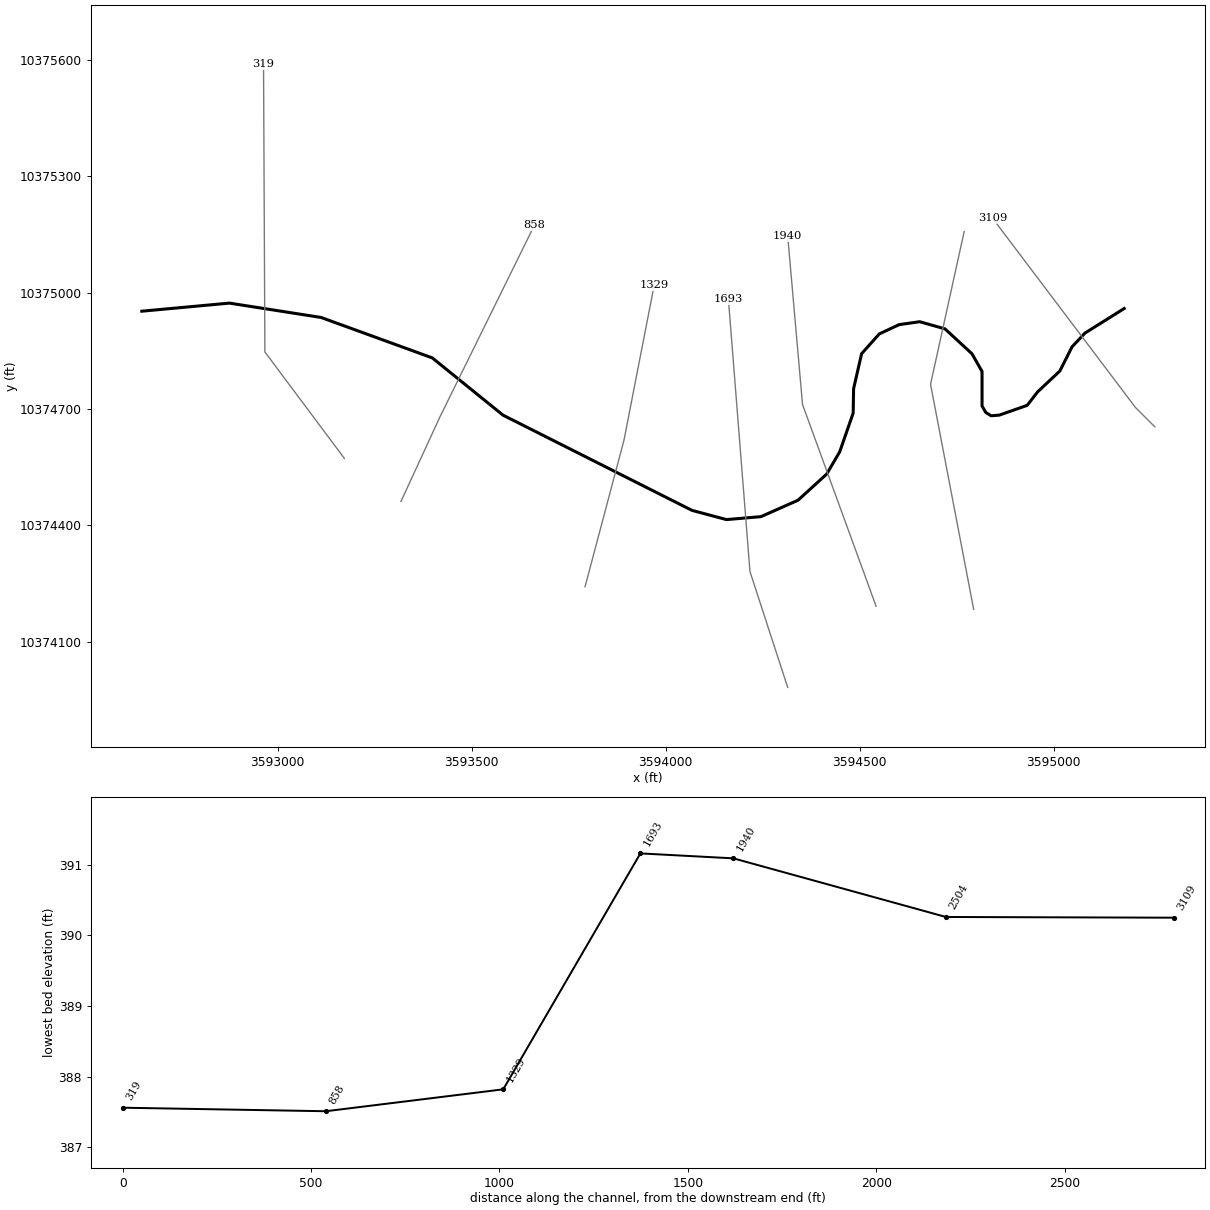
--- UNT04013 IN CEDR CR.prj (project) ---

Proj Title=UNT04013 IN CEDR CR Base Level Engineering
Current Plan=p01
Default Exp/Contr=0.3,0.1
English Units
Geom File=g01
Flow File=f01
Plan File=p01
BEGIN DESCRIPTION:
UNT04013 IN CEDR CR
END DESCRIPTION:

--- UNT04013 IN CEDR CR.p01 (plan) ---

Plan Title=Multiple Run
Short Identifier=Multiple
Geom File=g01
Flow File=f01
Subcritical Flow
K Sum by GR= 0
Std Step Tol= 0.01
Critical Tol= 0.01
Num of Std Step Trials= 20
Max Error Tol= 0.3
Flow Tol Ratio= 0.001
Split Flow NTrial= 30
Split Flow Tol= 0.02
Split Flow Ratio= 0.02
Log Output Level= 0
Friction Slope Method= 1
Unsteady Friction Slope Method= 2
Unsteady Bridges Friction Slope Method= 1
Parabolic Critical Depth
Global Vel Dist=  1 , 1 , 1
Global Log Level= 0
CheckData=True
Encroach Param= -1, 0, 0, 0
BEGIN DESCRIPTION:
Multiple Run
END DESCRIPTION:

--- UNT04013 IN CEDR CR.f01 (steady flow) ---

Flow Title=Multiple
Number of Profiles=7
Profile Names=10-year,25-year,50-year,1pct_min,100-year,1pct_plu,500-year
River Rch & RM= UNT04013 IN CEDR,Reach-1,3109
    1053    1448    1774    1587    2146    2902    3128
Boundary for River Rch & Prof#=UNT04013 IN CEDR,Reach-1,1
Up Type=0
Dn Type=3
Dn Slope=0.005
Boundary for River Rch & Prof#=UNT04013 IN CEDR,Reach-1,2
Up Type=0
Dn Type=3
Dn Slope=0.005
Boundary for River Rch & Prof#=UNT04013 IN CEDR,Reach-1,3
Up Type=0
Dn Type=3
Dn Slope=0.005
Boundary for River Rch & Prof#=UNT04013 IN CEDR,Reach-1,4
Up Type=0
Dn Type=3
Dn Slope=0.005
Boundary for River Rch & Prof#=UNT04013 IN CEDR,Reach-1,5
Up Type=0
Dn Type=3
Dn Slope=0.005
Boundary for River Rch & Prof#=UNT04013 IN CEDR,Reach-1,6
Up Type=0
Dn Type=3
Dn Slope=0.005
Boundary for River Rch & Prof#=UNT04013 IN CEDR,Reach-1,7
Up Type=0
Dn Type=3
Dn Slope=0.005

--- UNT04013 IN CEDR CR.g01 (geometry) ---

Geom Title=Existing Conditions

River Reach=UNT04013 IN CEDR,Reach-1
Reach XY= 30
      3595181.30     10374958.78      3595080.32     10374895.51
      3595046.90     10374859.92      3595015.65     10374797.85
      3594958.36     10374744.03      3594931.45     10374709.31
      3594859.83     10374684.14      3594838.56     10374682.40
      3594824.67     10374691.08      3594815.13     10374707.57
      3594815.08     10374796.78      3594789.04     10374842.35
      3594719.60     10374906.37      3594654.49     10374924.82
      3594601.32     10374917.22      3594550.33     10374893.35
      3594504.75     10374842.35      3594484.14     10374752.29
      3594483.05     10374689.36      3594448.33     10374589.53
      3594414.69     10374532.02      3594340.91     10374464.75
      3594245.42     10374422.43      3594156.45     10374414.84
      3594067.47     10374438.71      3593580.75     10374684.01
      3593398.46     10374831.57      3593112.00     10374935.74
      3592875.69     10374972.73      3592649.99     10374951.90

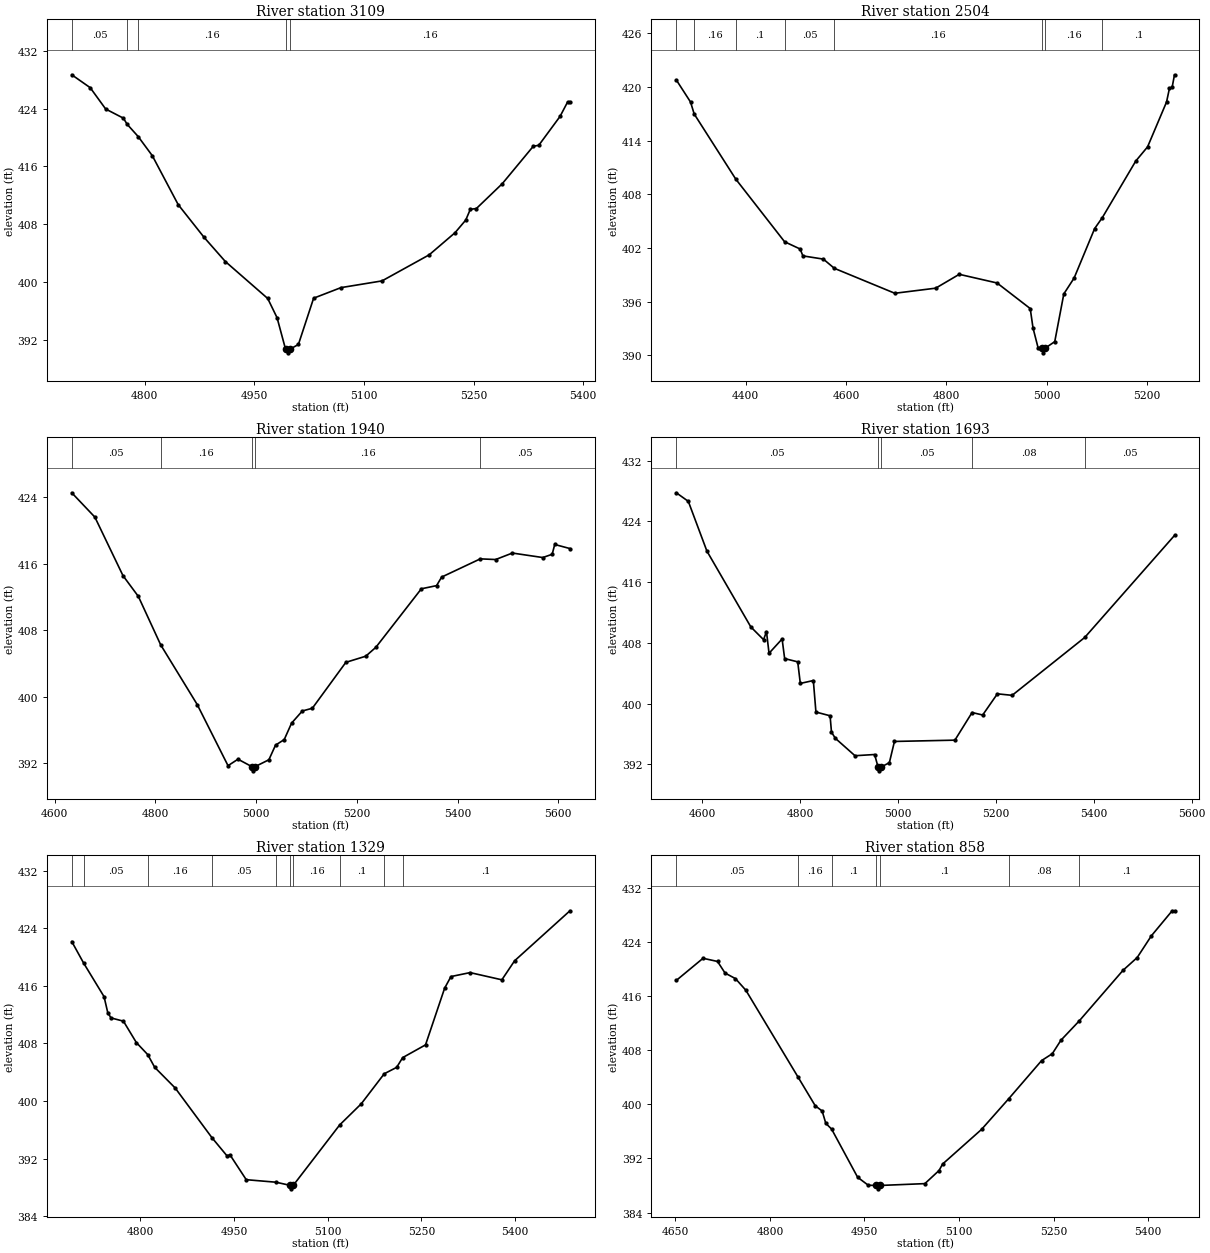
Type RM Length L Ch R = 1,3109,605,605,605
BEGIN DESCRIPTION:
UNT04013 IN CEDR CR 7.0
END DESCRIPTION:
XS GIS Cut Line= 3
      3595260.19     10374654.12      3595210.16     10374704.14
      3594842.09     10375191.66
#Sta/Elev= 30
  4700.3  428.67  4725.5  426.89  4746.7  423.94  4771.0  422.67  4776.0  421.84
  4791.2  420.13  4810.5  417.49  4845.9  410.73  4881.3  406.21  4910.4  402.87
  4968.4  397.76  4981.2  395.10  4992.8  390.75  4995.5  390.25  4998.8  390.75
  5010.4  391.41  5031.2  397.80  5068.6  399.26  5124.8  400.19  5189.3  403.79
  5224.7  406.85  5239.3  408.59  5245.6  410.08  5253.9  410.19  5289.3  413.62
  5331.8  418.80  5339.2  418.92  5368.3  422.91  5378.7  424.91  5381.9  424.91
#Mann=5,-1,0
  4700.3    0.05       0  4776.0     0.1       0  4791.2    0.16       0
  4992.8    0.07       0  4998.8    0.16       0
Bank Sta=4992.8,4998.8
Exp/Cntr=0.3,0.1

Type RM Length L Ch R = 1,2504,564,564,564
BEGIN DESCRIPTION:
UNT04013 IN CEDR CR 6.0
END DESCRIPTION:
XS GIS Cut Line= 3
      3594793.50     10374183.71      3594682.39     10374763.54
      3594769.08     10375157.13
#Sta/Elev= 30
  4261.8  420.77  4290.2  418.30  4297.4  416.97  4380.4  409.68  4477.7  402.68
  4508.7  401.87  4514.2  401.10  4555.0  400.74  4576.9  399.71  4697.5  396.92
  4779.0  397.49  4826.0  399.04  4901.4  398.07  4967.5  395.21  4973.1  393.03
  4983.3  390.80  4990.6  390.76  4993.3  390.26  4996.6  390.76  5016.4  391.51
  5034.5  396.85  5055.0  398.62  5096.0  404.16  5111.3  405.38  5177.9  411.70
  5201.5  413.29  5239.3  418.30  5245.2  419.85  5250.4  419.93  5255.2  421.35
#Mann=8,-1,0
  4261.8     0.1       0  4297.4    0.16       0  4380.4     0.1       0
  4477.7    0.05       0  4576.9    0.16       0  4990.6    0.07       0
  4996.6    0.16       0  5111.3     0.1       0
Bank Sta=4990.6,4996.6
Exp/Cntr=0.3,0.1

Type RM Length L Ch R = 1,1940,247,247,247
BEGIN DESCRIPTION:
UNT04013 IN CEDR CR 5.0
END DESCRIPTION:
XS GIS Cut Line= 3
      3594542.11     10374191.63      3594352.53     10374711.45
      3594314.34     10375145.46
#Sta/Elev= 30
  4634.0  424.54  4679.9  421.61  4735.7  414.57  4766.2  412.07  4810.5  406.25
  4883.1  399.06  4944.2  391.71  4964.0  392.49  4991.7  391.59  4994.5  391.09
  4997.7  391.59  5025.3  392.42  5038.5  394.18  5055.8  394.85  5070.4  396.83
  5091.7  398.29  5111.6  398.62  5178.1  404.14  5217.6  404.88  5237.7  405.95
  5328.0  412.99  5358.2  413.37  5368.3  414.40  5445.0  416.59  5475.5  416.51
  5508.7  417.29  5569.0  416.75  5587.7  417.14  5592.8  418.32  5623.0  417.83
#Mann=5,-1,0
  4634.0    0.05       0  4810.5    0.16       0  4991.7    0.07       0
  4997.7    0.16       0  5445.0    0.05       0
Bank Sta=4991.7,4997.7
Exp/Cntr=0.3,0.1

Type RM Length L Ch R = 1,1693,364,364,364
BEGIN DESCRIPTION:
UNT04013 IN CEDR CR 4.0
END DESCRIPTION:
XS GIS Cut Line= 3
      3594314.35     10373982.24      3594217.12     10374280.90
      3594161.56     10374982.32
#Sta/Elev= 30
  4547.3  427.77  4571.8  426.64  4609.8  420.09  4699.5  410.11  4725.5  408.43
  4731.5  409.49  4736.7  406.64  4763.4  408.52  4768.6  405.94  4795.3  405.51
  4800.6  402.67  4827.2  403.05  4832.5  398.90  4861.4  398.41  4864.3  396.25
  4872.2  395.44  4912.3  393.15  4952.4  393.31  4959.4  391.66  4962.2  391.16
  4965.4  391.66  4982.5  392.23  4992.9  395.03  5116.4  395.20  5151.5  398.84
  5173.1  398.51  5203.2  401.30  5233.3  401.10  5381.6  408.72  5565.0  422.15
#Mann=5,-1,0
  4547.3    0.05       0  4959.4    0.04       0  4965.4    0.05       0
  5151.5    0.08       0  5381.6    0.05       0
Bank Sta=4959.4,4965.4
Exp/Cntr=0.3,0.1

Type RM Length L Ch R = 1,1329,471,471,471
BEGIN DESCRIPTION:
UNT04013 IN CEDR CR 3.0
END DESCRIPTION:
XS GIS Cut Line= 3
      3593792.12     10374241.69      3593892.55     10374619.97
      3593970.22     10375018.58
#Sta/Elev= 30
  4690.2  422.14  4709.2  419.15  4741.9  414.49  4747.8  412.28  4753.0  411.54
  4772.9  411.09  4793.6  408.12  4811.8  406.45  4823.0  404.68  4855.7  401.82
  4914.5  394.93  4938.4  392.43  4943.6  392.52  4969.5  389.09  5017.1  388.74
  5038.9  388.32  5041.7  387.82  5044.9  388.32  5119.1  396.69  5153.6  399.62
  5190.4  403.79  5210.3  404.68  5219.9  406.03  5256.5  407.80  5287.1  415.67
  5297.2  417.28  5327.8  417.83  5378.7  416.83  5399.1  419.47  5487.7  426.41
#Mann=10,-1,0
  4690.2    0.16       0  4709.2    0.05       0  4811.8    0.16       0
  4914.5    0.05       0  5017.1    0.16       0  5038.9   0.035       0
  5044.9    0.16       0  5119.1     0.1       0  5190.4    0.08       0
  5219.9     0.1       0
Bank Sta=5038.9,5044.9
Exp/Cntr=0.3,0.1

Type RM Length L Ch R = 1,858,539,539,539
BEGIN DESCRIPTION:
UNT04013 IN CEDR CR 2.0
END DESCRIPTION:
XS GIS Cut Line= 3
      3593317.81     10374461.46      3593418.51     10374680.20
      3593661.55     10375173.25
#Sta/Elev= 30
  4651.5  418.31  4693.9  421.58  4716.9  421.11  4728.8  419.40  4745.4  418.57
  4761.8  416.86  4844.8  404.00  4871.9  399.79  4882.9  399.01  4888.7  397.19
  4897.9  396.34  4939.2  389.22  4956.1  388.04  4969.0  388.01  4971.7  387.51
  4975.0  388.01  5045.9  388.28  5068.4  390.22  5074.0  391.17  5135.8  396.29
  5179.0  400.83  5231.2  406.47  5248.1  407.48  5261.8  409.47  5290.6  412.30
  5360.3  419.80  5382.8  421.69  5405.3  424.90  5438.3  428.60  5442.0  428.60
#Mann=7,-1,0
  4651.5    0.05       0  4844.8    0.16       0  4897.9     0.1       0
  4969.0    0.07       0  4975.0     0.1       0  5179.0    0.08       0
  5290.6     0.1       0
Bank Sta=4969,4975
Exp/Cntr=0.3,0.1

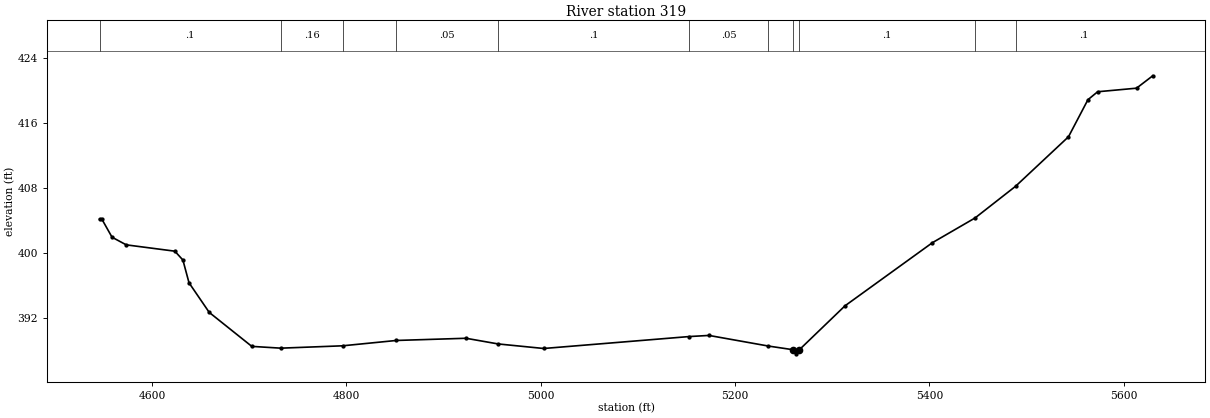
Type RM Length L Ch R = 1,319,0,0,0
BEGIN DESCRIPTION:
UNT04013 IN CEDR CR 1.0
END DESCRIPTION:
XS GIS Cut Line= 3
      3593171.98     10374572.56      3592967.12     10374846.87
      3592963.65     10375588.30
#Sta/Elev= 30
  4546.0  404.15  4548.5  404.15  4558.9  401.94  4573.5  401.00  4623.5  400.22
  4631.8  399.13  4638.1  396.32  4658.9  392.67  4702.7  388.48  4732.5  388.26
  4796.1  388.55  4851.5  389.21  4923.1  389.48  4956.2  388.78  5003.1  388.22
  5152.6  389.69  5173.1  389.83  5234.3  388.52  5260.1  388.06  5262.9  387.56
  5266.1  388.06  5313.1  393.48  5403.1  401.27  5447.0  404.32  5488.6  408.22
  5543.1  414.33  5563.1  418.90  5573.1  419.88  5613.1  420.32  5629.8  421.85
#Mann=11,-1,0
  4546.0     0.1       0  4732.5    0.16       0  4796.1     0.1       0
  4851.5    0.05       0  4956.2     0.1       0  5152.6    0.05       0
  5234.3     0.1       0  5260.1    0.07       0  5266.1     0.1       0
  5447.0    0.08       0  5488.6     0.1       0
Bank Sta=5260.1,5266.1
Exp/Cntr=0.3,0.1

Chan Stop Cuts=-1