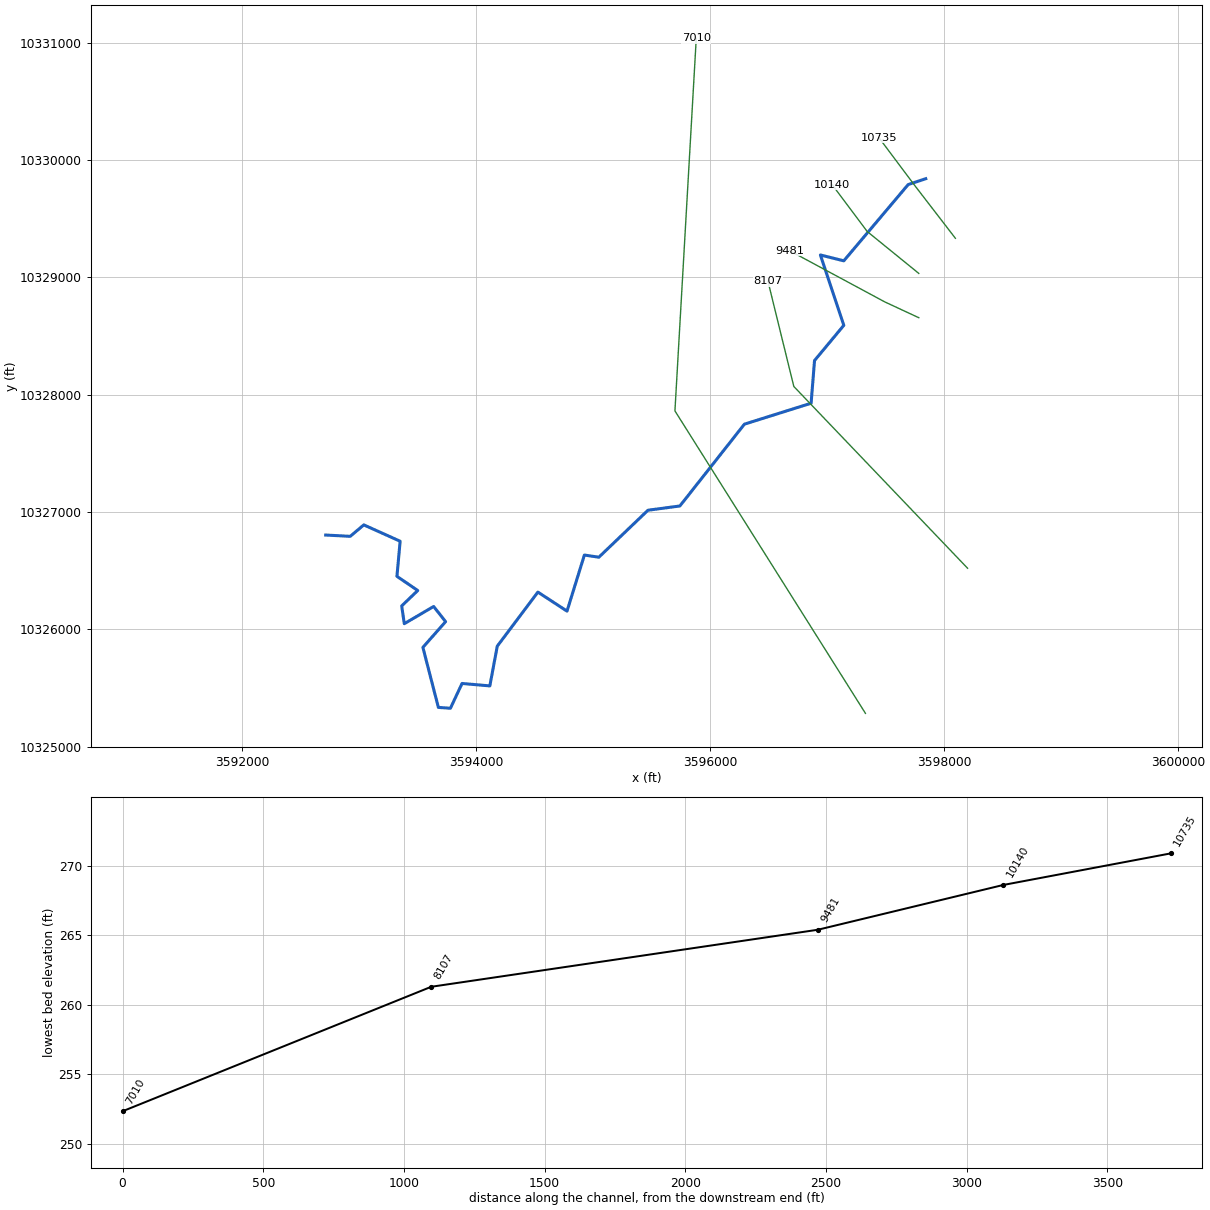
--- UNT0403 IN CEDR CR.prj (project) ---

Proj Title=UNT0403 IN CEDR CR Base Level Engineering
Current Plan=p01
Default Exp/Contr=0.3,0.1
English Units
Geom File=g01
Flow File=f01
Plan File=p01
BEGIN DESCRIPTION:
UNT0403 IN CEDR CR
END DESCRIPTION:

--- UNT0403 IN CEDR CR.p01 (plan) ---

Plan Title=Multiple Run
Short Identifier=Multiple
Geom File=g01
Flow File=f01
Subcritical Flow
K Sum by GR= 0
Std Step Tol= 0.01
Critical Tol= 0.01
Num of Std Step Trials= 20
Max Error Tol= 0.3
Flow Tol Ratio= 0.001
Split Flow NTrial= 30
Split Flow Tol= 0.02
Split Flow Ratio= 0.02
Log Output Level= 0
Friction Slope Method= 1
Unsteady Friction Slope Method= 2
Unsteady Bridges Friction Slope Method= 1
Parabolic Critical Depth
Global Vel Dist=  1 , 1 , 1
Global Log Level= 0
CheckData=True
Encroach Param= -1, 0, 0, 0
BEGIN DESCRIPTION:
Multiple Run
END DESCRIPTION:

--- UNT0403 IN CEDR CR.f01 (steady flow) ---

Flow Title=Multiple
Number of Profiles=7
Profile Names=10-year,25-year,50-year,1pct_min,100-year,1pct_plu,500-year
River Rch & RM= UNT0403 IN CEDR ,Reach-1,10735
    1199    1688    2104    1919    2596    3511    3962
Boundary for River Rch & Prof#=UNT0403 IN CEDR ,Reach-1,1
Up Type=0
Dn Type=3
Dn Slope=0.005
Boundary for River Rch & Prof#=UNT0403 IN CEDR ,Reach-1,2
Up Type=0
Dn Type=3
Dn Slope=0.005
Boundary for River Rch & Prof#=UNT0403 IN CEDR ,Reach-1,3
Up Type=0
Dn Type=3
Dn Slope=0.005
Boundary for River Rch & Prof#=UNT0403 IN CEDR ,Reach-1,4
Up Type=0
Dn Type=3
Dn Slope=0.005
Boundary for River Rch & Prof#=UNT0403 IN CEDR ,Reach-1,5
Up Type=0
Dn Type=3
Dn Slope=0.005
Boundary for River Rch & Prof#=UNT0403 IN CEDR ,Reach-1,6
Up Type=0
Dn Type=3
Dn Slope=0.005
Boundary for River Rch & Prof#=UNT0403 IN CEDR ,Reach-1,7
Up Type=0
Dn Type=3
Dn Slope=0.005

--- UNT0403 IN CEDR CR.g01 (geometry) ---

Geom Title=Existing Conditions

River Reach=UNT0403 IN CEDR ,Reach-1
Reach XY= 30
      3597842.11     10329841.64      3597692.11     10329791.64
      3597142.11     10329141.64      3596942.11     10329191.64
      3597142.11     10328591.64      3596892.11     10328291.64
      3596862.89     10327927.92      3596293.06     10327749.34
      3595741.98     10327052.15      3595469.32     10327015.81
      3595049.72     10326615.43      3594926.19     10326633.95
      3594777.71     10326155.87      3594528.90     10326318.02
      3594181.86     10325857.09      3594118.41     10325518.63
      3593881.09     10325539.28      3593781.70     10325327.91
      3593678.85     10325335.25      3593546.50     10325846.82
      3593740.54     10326066.10      3593638.32     10326195.48
      3593387.66     10326048.69      3593365.42     10326200.34
      3593502.63     10326331.50      3593324.83     10326452.47
      3593352.11     10326751.64      3593041.79     10326890.92
      3592926.05     10326793.31      3592716.10     10326804.45

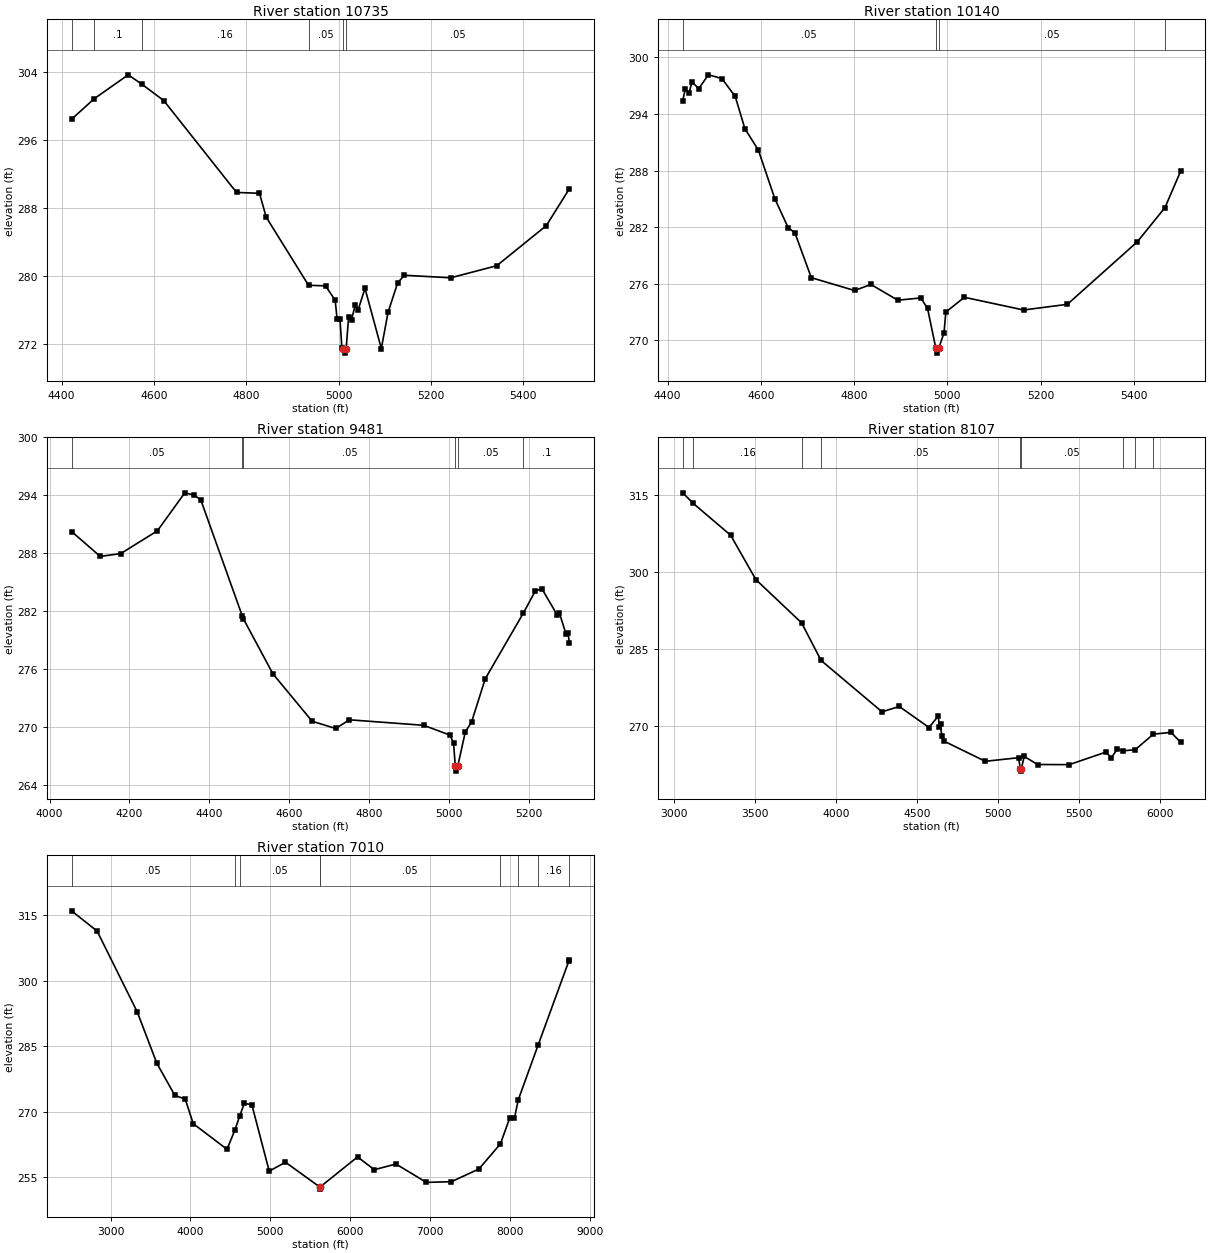
Type RM Length L Ch R = 1,10735,595,595,595
BEGIN DESCRIPTION:
UNT0403 IN CEDR CR 11.0
END DESCRIPTION:
XS GIS Cut Line= 3
      3598095.40     10329333.81      3597742.11     10329791.64
      3597442.11     10330191.64
#Sta/Elev= 30
  4421.7  298.42  4470.9  300.84  4544.4  303.65  4573.9  302.55  4621.4  300.62
  4779.0  289.80  4828.8  289.70  4843.3  286.89  4935.0  278.87  4971.9  278.80
  4992.8  277.10  4996.8  274.92  5003.1  274.92  5007.3  271.44  5010.5  271.38
  5013.3  270.88  5016.5  271.38  5021.9  275.17  5028.1  274.82  5036.5  276.60
  5042.7  276.01  5057.3  278.51  5092.7  271.42  5107.3  275.69  5128.1  279.16
  5142.7  280.05  5242.7  279.75  5342.7  281.17  5450.0  285.89  5500.0  290.23
#Mann=6,-1,0
  4421.7    0.05       0  4470.9     0.1       0  4573.9    0.16       0
  4935.0    0.05       0  5010.5   0.035       0  5016.5    0.05       0
Bank Sta=5010.5,5016.5
Exp/Cntr=0.3,0.1

Type RM Length L Ch R = 1,10140,659,659,659
BEGIN DESCRIPTION:
UNT0403 IN CEDR CR 10.0
END DESCRIPTION:
XS GIS Cut Line= 3
      3597782.88     10329034.35      3597342.11     10329391.64
      3597042.11     10329791.64
#Sta/Elev= 30
  4432.6  295.41  4438.1  296.67  4446.1  296.24  4452.5  297.40  4466.9  296.70
  4487.7  298.16  4516.5  297.77  4545.2  295.86  4566.0  292.43  4594.8  290.17
  4630.0  285.02  4658.7  281.93  4673.1  281.39  4708.3  276.62  4801.0  275.26
  4836.2  275.90  4893.7  274.23  4943.2  274.47  4957.6  273.35  4975.4  269.11
  4978.2  268.61  4981.4  269.11  4992.8  270.75  4996.8  272.97  5036.5  274.54
  5163.5  273.19  5257.3  273.79  5407.3  280.43  5466.6  284.06  5500.0  287.90
#Mann=4,-1,0
  4432.6    0.05       0  4975.4   0.035       0  4981.4    0.05       0
  5466.6    0.16       0
Bank Sta=4975.4,4981.4
Exp/Cntr=0.3,0.1

Type RM Length L Ch R = 1,9481,1374,1374,1374
BEGIN DESCRIPTION:
UNT0403 IN CEDR CR 8.0
END DESCRIPTION:
XS GIS Cut Line= 3
      3597782.90     10328656.72      3597492.11     10328791.64
      3596676.63     10329229.37
#Sta/Elev= 30
  4055.2  290.23  4127.0  287.65  4178.3  287.94  4270.0  290.30  4338.7  294.24
  4361.6  294.01  4378.6  293.52  4482.7  281.46  4485.6  281.16  4559.3  275.47
  4657.5  270.56  4716.3  269.81  4750.9  270.71  4936.8  270.14  5002.6  269.12
  5011.3  268.33  5015.8  265.89  5018.6  265.39  5021.8  265.89  5040.8  269.44
  5056.7  270.51  5090.8  274.97  5185.7  281.74  5216.1  284.07  5232.4  284.31
  5270.6  281.59  5276.2  281.82  5292.5  279.65  5298.1  279.73  5301.3  278.65
#Mann=6,-1,0
  4055.2    0.05       0  4482.7     0.1       0  4485.6    0.05       0
  5015.8   0.035       0  5021.8    0.05       0  5185.7     0.1       0
Bank Sta=5015.8,5021.8
Exp/Cntr=0.3,0.1

Type RM Length L Ch R = 1,8107,1097,1097,1097
BEGIN DESCRIPTION:
UNT0403 IN CEDR CR 7.0
END DESCRIPTION:
XS GIS Cut Line= 3
      3598199.57     10326521.31      3596715.20     10328070.78
      3596494.17     10328967.91
#Sta/Elev= 30
  3055.0  315.46  3120.4  313.39  3350.4  307.21  3506.1  298.57  3788.3  290.14
  3907.9  282.84  4284.2  272.83  4390.1  273.88  4574.1  269.78  4630.7  272.02
  4637.7  269.84  4644.9  270.41  4651.8  268.12  4666.0  267.13  4920.7  263.20
  5125.7  263.90  5136.9  261.79  5139.6  261.29  5142.9  261.79  5161.0  264.15
  5242.8  262.58  5438.5  262.55  5665.1  265.00  5697.8  263.87  5734.1  265.55
  5768.7  265.24  5845.1  265.46  5957.5  268.49  6066.1  268.83  6124.7  266.94
#Mann=9,-1,0
  3055.0     0.1       0  3120.4    0.16       0  3788.3     0.1       0
  3907.9    0.05       0  5136.9   0.035       0  5142.9    0.05       0
  5768.7     0.1       0  5845.1    0.05       0  5957.5     0.1       0
Bank Sta=5136.9,5142.9
Exp/Cntr=0.3,0.1

Type RM Length L Ch R = 1,7010,0,0,0
BEGIN DESCRIPTION:
UNT0403 IN CEDR CR 1.0
END DESCRIPTION:
XS GIS Cut Line= 3
      3597327.16     10325284.36      3595699.58     10327862.45
      3595881.78     10331038.06
#Sta/Elev= 30
  2512.6  315.95  2832.9  311.31  3334.1  292.86  3580.0  281.10  3804.8  273.77
  3935.4  272.90  4035.4  267.30  4457.8  261.44  4558.2  265.92  4617.3  269.08
  4673.6  271.92  4768.2  271.66  4986.2  256.45  5189.7  258.49  5617.8  252.84
  5620.5  252.34  5623.8  252.84  6091.5  259.70  6301.9  256.78  6572.3  258.08
  6952.9  253.88  7266.2  254.04  7611.1  256.95  7879.2  262.68  7994.7  268.52
  8054.8  268.56  8103.2  272.77  8350.4  285.22  8737.8  304.57  8742.3  304.71
#Mann=9,-1,0
  2512.6    0.05       0  4558.2    0.12       0  4617.3    0.05       0
  5617.8   0.035       0  5623.8    0.05       0  7879.2     0.1       0
  8103.2    0.05       0  8350.4    0.16       0  8737.8    0.12       0
Bank Sta=5617.8,5623.8
Exp/Cntr=0.3,0.1

Chan Stop Cuts=-1