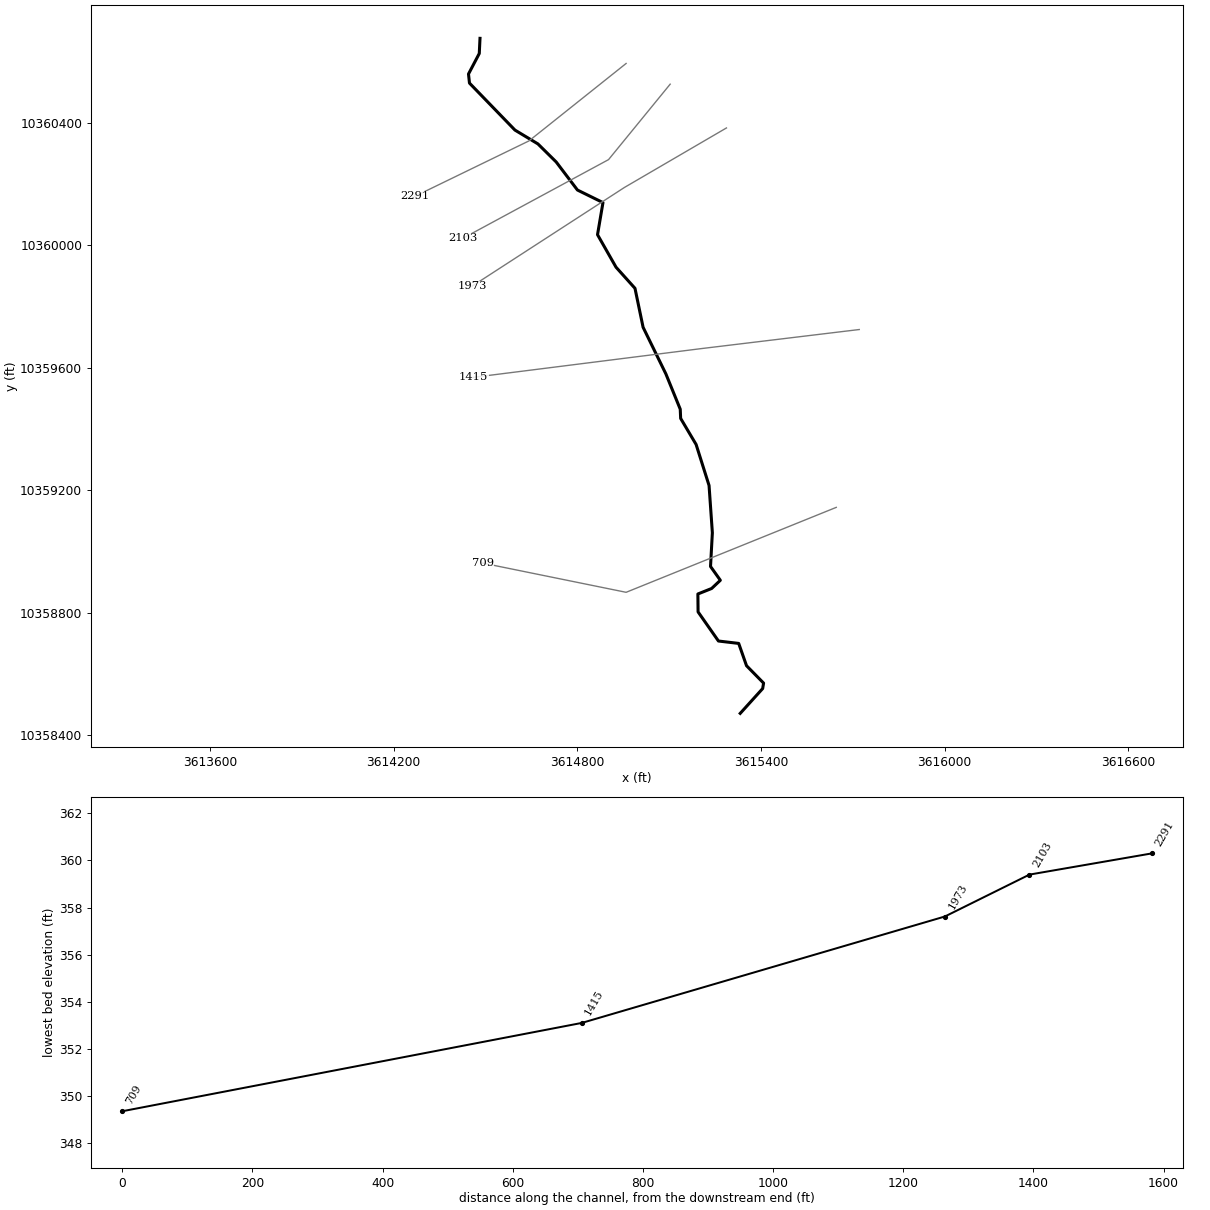
--- UNT04113 IN CEDR CR.prj (project) ---

Proj Title=UNT04113 IN CEDR CR Base Level Engineering
Current Plan=p01
Default Exp/Contr=0.3,0.1
English Units
Geom File=g01
Flow File=f01
Plan File=p01
Y Axis Title=Elevation
X Axis Title(PF)=Main Channel Distance
X Axis Title(XS)=Station
BEGIN DESCRIPTION:
UNT04113 IN CEDR CR
END DESCRIPTION:
DSS Export Rating Curves= 0
DSS Export Rating Curve Sorted= 0
DSS Export Volume Flow Curves= 0
DXF OffsetX= 0
DXF OffsetY= 0
DXF ScaleX= 1
DXF ScaleY= 10

--- UNT04113 IN CEDR CR.p01 (plan) ---

Plan Title=Multiple Run
Short Identifier=Multiple
Geom File=g01
Flow File=f01
Subcritical Flow
K Sum by GR= 0
Std Step Tol= 0.01
Critical Tol= 0.01
Num of Std Step Trials= 20
Max Error Tol= 0.3
Flow Tol Ratio= 0.001
Split Flow NTrial= 30
Split Flow Tol= 0.02
Split Flow Ratio= 0.02
Log Output Level= 0
Friction Slope Method= 1
Unsteady Friction Slope Method= 2
Unsteady Bridges Friction Slope Method= 1
Parabolic Critical Depth
Global Vel Dist=  1 , 1 , 1
Global Log Level= 0
CheckData=True
Encroach Param= -1, 0, 0, 0
BEGIN DESCRIPTION:
Multiple Run
END DESCRIPTION:

--- UNT04113 IN CEDR CR.f01 (steady flow) ---

Flow Title=Multiple
Number of Profiles=7
Profile Names=10-year,25-year,50-year,1pct_min,100-year,1pct_plu,500-year
River Rch & RM= UNT04113 IN CEDR,Reach-1,2291
     350     447     521     445     601     813     796
Boundary for River Rch & Prof#=UNT04113 IN CEDR,Reach-1,1
Up Type=0
Dn Type=3
Dn Slope=0.005
Boundary for River Rch & Prof#=UNT04113 IN CEDR,Reach-1,2
Up Type=0
Dn Type=3
Dn Slope=0.005
Boundary for River Rch & Prof#=UNT04113 IN CEDR,Reach-1,3
Up Type=0
Dn Type=3
Dn Slope=0.005
Boundary for River Rch & Prof#=UNT04113 IN CEDR,Reach-1,4
Up Type=0
Dn Type=3
Dn Slope=0.005
Boundary for River Rch & Prof#=UNT04113 IN CEDR,Reach-1,5
Up Type=0
Dn Type=3
Dn Slope=0.005
Boundary for River Rch & Prof#=UNT04113 IN CEDR,Reach-1,6
Up Type=0
Dn Type=3
Dn Slope=0.005
Boundary for River Rch & Prof#=UNT04113 IN CEDR,Reach-1,7
Up Type=0
Dn Type=3
Dn Slope=0.005

--- UNT04113 IN CEDR CR.g01 (geometry) ---

Geom Title=Existing Conditions
Program Version=4.10

River Reach=UNT04113 IN CEDR,Reach-1
Reach XY= 30
      3614482.11     10360676.64      3614479.75     10360627.12
      3614444.54     10360560.12      3614447.74     10360530.44
      3614596.29     10360376.94      3614671.29      10360331.8
      3614731.01     10360272.77      3614800.46      10360181.1
      3614883.79     10360140.13      3614865.97     10360035.24
       3614926.5     10359928.96      3614988.36      10359860.1
      3615014.86     10359732.78      3615089.29     10359580.47
       3615136.2     10359465.23      3615137.53     10359435.17
      3615188.02     10359349.99       3615230.3     10359216.08
      3615241.13     10359061.57      3615235.09     10358951.54
      3615267.21     10358906.38      3615238.76     10358879.59
      3615193.81     10358861.63      3615194.46     10358803.09
      3615260.99     10358707.98      3615327.14     10358700.17
      3615352.71     10358627.27      3615408.44     10358570.54
      3615405.43     10358552.66      3615332.11     10358471.64

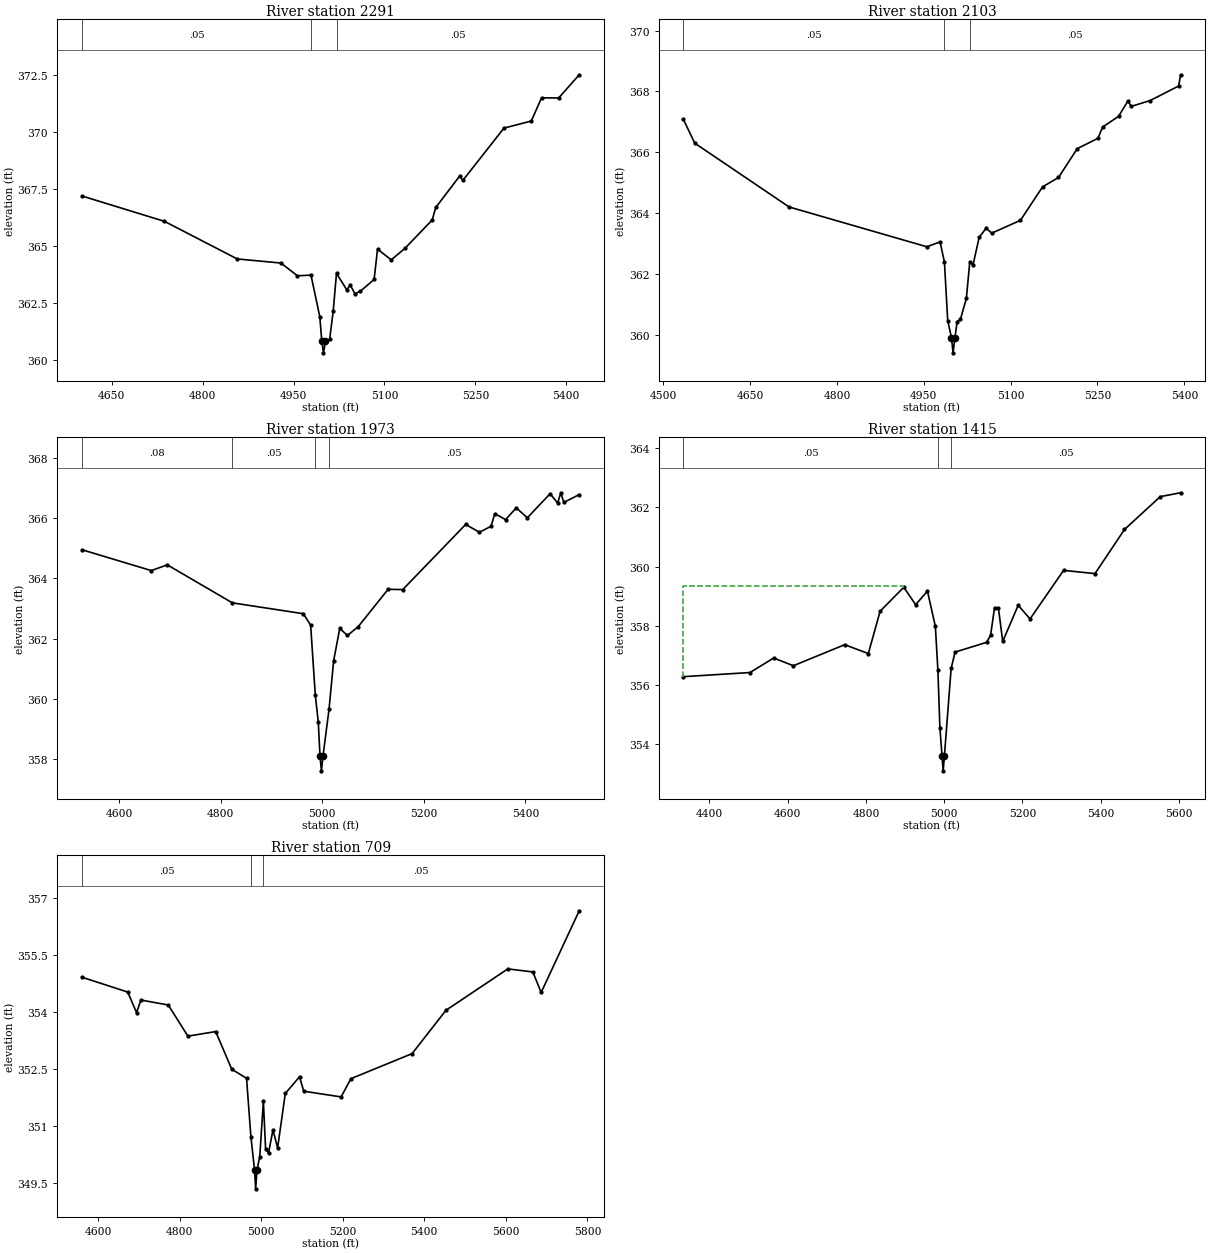
Type RM Length L Ch R = 1 ,2291    ,188,188,188
BEGIN DESCRIPTION:
UNT04113 IN CEDR CR 5.0
END DESCRIPTION:
XS GIS Cut Line= 3
       3614959.4     10360594.56      3614642.11     10360341.64
      3614269.24      10360160.5
#Sta/Elev= 30
    4601  367.18  4736.9  366.07    4857  364.42  4929.1  364.24  4956.3  363.68
  4978.7  363.71  4993.2  361.89  4996.6   360.8  4999.3   360.3  5002.6   360.8
  5009.5  360.89  5015.3  362.12  5020.8  363.79  5037.8  363.06  5043.4  363.28
  5051.2  362.89  5060.4  363.01  5082.9  363.52  5088.5  364.85  5111.1  364.38
  5133.6  364.88  5178.7  366.13  5184.6  366.68  5223.9  368.05  5229.4  367.87
  5297.1  370.16  5342.2  370.47  5359.2  371.49  5387.3  371.48  5421.3   372.5
#Mann= 3 ,-1 , 0
    4601     .05       0  4978.7     .03       0  5020.8     .05       0
Bank Sta=4996.6,5002.6
XS Rating Curve= 0 ,0
Exp/Cntr=0.3,0.1

Type RM Length L Ch R = 1 ,2103    ,130,130,130
BEGIN DESCRIPTION:
UNT04113 IN CEDR CR 5.01
END DESCRIPTION:
XS GIS Cut Line= 3
      3615103.34     10360526.95      3614901.98     10360280.46
      3614426.67     10360023.72
#Sta/Elev= 30
    4535  367.08  4554.5   366.3  4717.5   364.2  4955.4  362.89  4978.2  363.05
  4985.7  362.39  4991.4  360.46  4997.9   359.9  5000.6   359.4  5003.9   359.9
  5007.6  360.42  5013.3   360.5  5023.6  361.19  5029.5   362.4  5035.2   362.3
  5045.7   363.2  5057.7   363.5  5067.6  363.34    5117  363.76  5155.1  364.86
  5182.7  365.17  5215.1  366.12  5250.9  366.46  5258.9  366.83  5286.4  367.18
  5302.6  367.69  5308.3  367.51  5340.7   367.7  5390.2  368.18  5393.5  368.55
#Mann= 3 ,-1 , 0
    4535     .05       0  4985.7     .03       0  5029.5     .05       0
Bank Sta=4997.9,5003.9
XS Rating Curve= 0 ,0
Exp/Cntr=0.3,0.1

Type RM Length L Ch R = 1 ,1973    ,558,558,558
BEGIN DESCRIPTION:
UNT04113 IN CEDR CR 3.0
END DESCRIPTION:
XS GIS Cut Line= 3
      3615287.14     10360383.92      3614953.83      10360189.5
      3614456.42     10359867.13
#Sta/Elev= 30
  4527.4  364.95  4663.6  364.26  4695.1  364.45  4823.2  363.19    4963  362.83
  4977.3  362.45  4986.5  360.13  4992.4  359.23  4995.7  358.12  4998.5  357.62
  5001.7  358.12  5013.5  359.66  5022.6  361.27  5034.6  362.34  5049.8  362.11
  5070.9   362.4  5129.8  363.64  5158.6  363.63  5282.5  365.79  5309.6  365.53
  5332.4  365.73  5339.9  366.15    5361  365.95  5382.1  366.34  5403.9  366.01
  5448.7  366.81  5463.5   366.5  5469.8  366.84  5475.7  366.52    5506  366.78
#Mann= 4 ,-1 , 0
  4527.4     .08       0  4823.2     .05       0  4986.5     .03       0
  5013.5     .05       0
Bank Sta=4995.7,5001.7
XS Rating Curve= 0 ,0
Exp/Cntr=0.3,0.1

Type RM Length L Ch R = 1 ,1415    ,706,706,706
BEGIN DESCRIPTION:
UNT04113 IN CEDR CR 4.0
END DESCRIPTION:
XS GIS Cut Line= 3
      3615720.95     10359725.48      3615203.63     10359662.99
       3614460.6     10359569.24
#Sta/Elev= 30
  4333.9  356.28    4504  356.42  4564.4  356.91  4614.8  356.65  4745.9  357.36
  4806.2  357.06  4836.4  358.49  4896.8   359.3  4927.1  358.71  4957.3  359.17
  4977.5  357.98    4984  356.49  4989.1  354.55  4994.6   353.6  4997.4   353.1
  5000.6   353.6  5017.8  356.56  5027.9  357.11  5108.5  357.44  5118.6  357.68
  5128.7  358.61  5138.7  358.59  5149.6  357.47  5189.1  358.69  5219.4  358.23
  5305.1  359.87  5385.3  359.76  5460.6  361.25    5552  362.36  5603.9  362.49
#Mann= 3 ,-1 , 0
  4333.9     .05       0    4984     .03       0  5017.8     .05       0
#XS Ineff= 2 , 0
         4895.45  359.34
Permanent Ineff=
       F       F
Bank Sta=4994.6,5000.6
XS Rating Curve= 0 ,0
Exp/Cntr=0.3,0.1

Type RM Length L Ch R = 1 ,709     ,0,0,0
BEGIN DESCRIPTION:
UNT04113 IN CEDR CR 1.0
END DESCRIPTION:
XS GIS Cut Line= 3
      3615645.88     10359144.58      3614959.39     10358867.12
      3614490.66      10358962.6
#Sta/Elev= 30
  4561.1  354.92    4673  354.53  4694.6  353.99  4705.4  354.32  4772.3  354.19
  4820.5  353.37  4888.7  353.49  4927.9   352.5  4964.3  352.26    4975  350.72
  4983.9  349.85  4986.6  349.35  4989.9  349.85  4996.6  350.19  5005.6  351.65
    5011  350.41  5018.2  350.29    5029   350.9  5040.5  350.43  5059.3  351.86
  5094.2   352.3  5104.5  351.92  5196.1  351.77  5220.2  352.25  5370.2  352.91
  5453.2  354.05  5604.9  355.14  5666.2  355.06  5686.6  354.52  5779.9  356.67
#Mann= 3 ,-1 , 0
  4561.1     .05       0    4975     .03       0  5005.6     .05       0
Bank Sta=4983.9,4989.9
XS Rating Curve= 0 ,0
Exp/Cntr=0.3,0.1

Chan Stop Cuts=-1
Use User Specified Reach Order=0
Composite Channel Slope=5