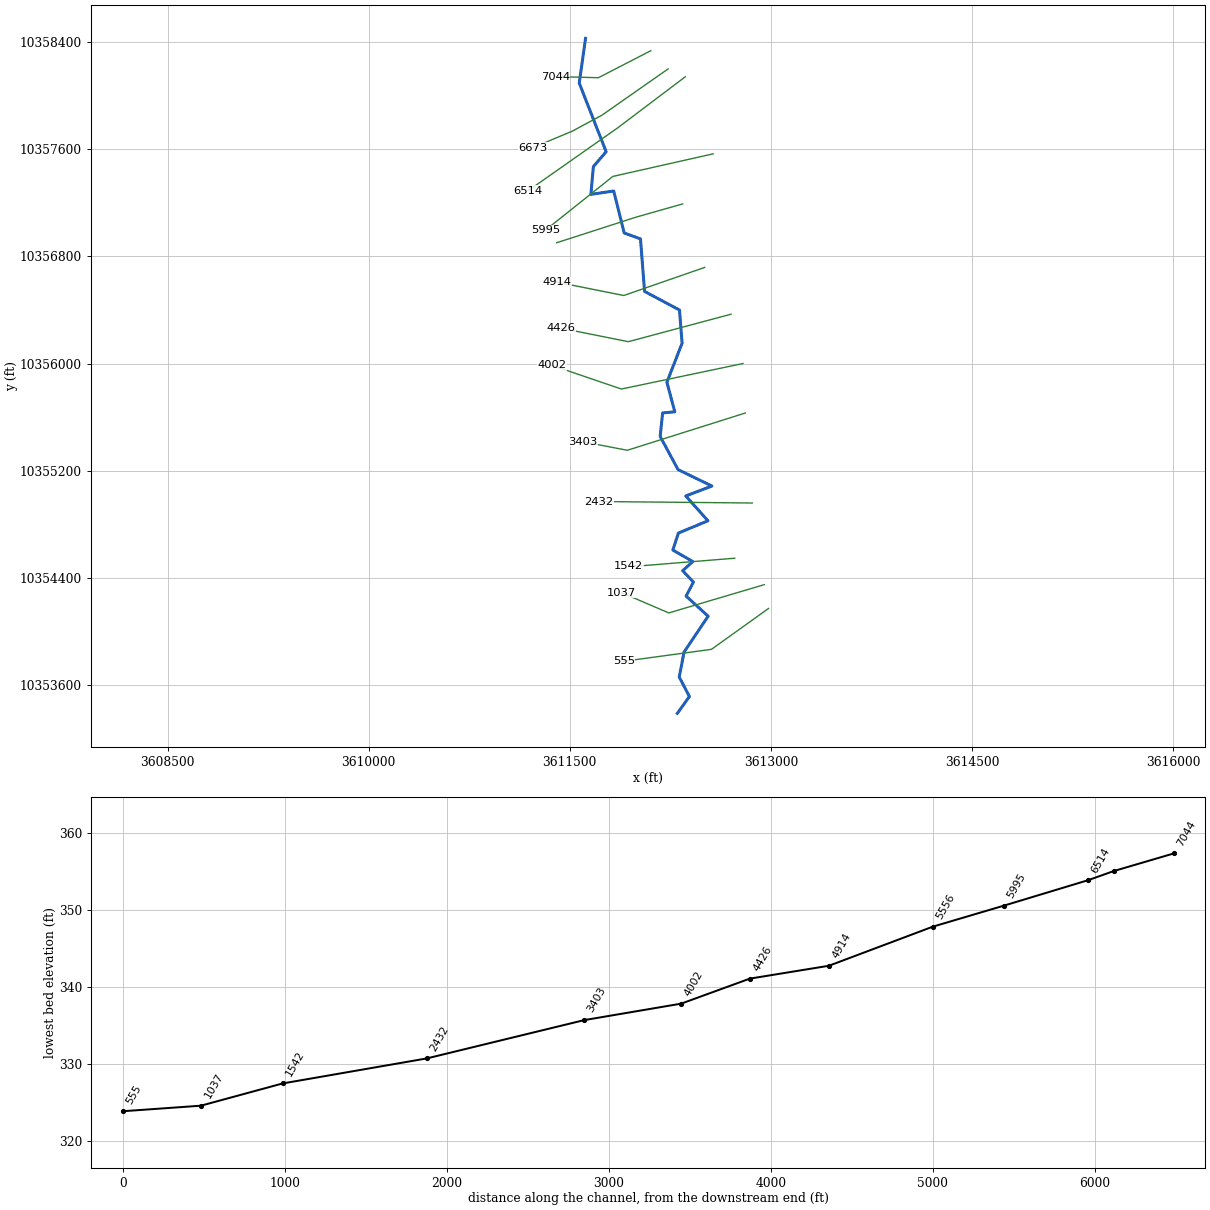
--- UNT04118 IN CEDR CR.prj (project) ---

Proj Title=UNT04118 IN CEDR CR Base Level Engineering
Current Plan=p01
Default Exp/Contr=0.3,0.1
English Units
Geom File=g01
Flow File=f01
Plan File=p01
BEGIN DESCRIPTION:
UNT04118 IN CEDR CR
END DESCRIPTION:

--- UNT04118 IN CEDR CR.p01 (plan) ---

Plan Title=Multiple Run
Short Identifier=Multiple
Geom File=g01
Flow File=f01
Subcritical Flow
K Sum by GR= 0
Std Step Tol= 0.01
Critical Tol= 0.01
Num of Std Step Trials= 20
Max Error Tol= 0.3
Flow Tol Ratio= 0.001
Split Flow NTrial= 30
Split Flow Tol= 0.02
Split Flow Ratio= 0.02
Log Output Level= 0
Friction Slope Method= 1
Unsteady Friction Slope Method= 2
Unsteady Bridges Friction Slope Method= 1
Parabolic Critical Depth
Global Vel Dist=  1 , 1 , 1
Global Log Level= 0
CheckData=True
Encroach Param= -1, 0, 0, 0
BEGIN DESCRIPTION:
Multiple Run
END DESCRIPTION:

--- UNT04118 IN CEDR CR.f01 (steady flow) ---

Flow Title=Multiple
Number of Profiles=7
Profile Names=10-year,25-year,50-year,1pct_min,100-year,1pct_plu,500-year
River Rch & RM= UNT04118 IN CEDR,Reach-1,7044
     550     723     859     747    1010    1366    1389
Boundary for River Rch & Prof#=UNT04118 IN CEDR,Reach-1,1
Up Type=0
Dn Type=3
Dn Slope=0.005
Boundary for River Rch & Prof#=UNT04118 IN CEDR,Reach-1,2
Up Type=0
Dn Type=3
Dn Slope=0.005
Boundary for River Rch & Prof#=UNT04118 IN CEDR,Reach-1,3
Up Type=0
Dn Type=3
Dn Slope=0.005
Boundary for River Rch & Prof#=UNT04118 IN CEDR,Reach-1,4
Up Type=0
Dn Type=3
Dn Slope=0.005
Boundary for River Rch & Prof#=UNT04118 IN CEDR,Reach-1,5
Up Type=0
Dn Type=3
Dn Slope=0.005
Boundary for River Rch & Prof#=UNT04118 IN CEDR,Reach-1,6
Up Type=0
Dn Type=3
Dn Slope=0.005
Boundary for River Rch & Prof#=UNT04118 IN CEDR,Reach-1,7
Up Type=0
Dn Type=3
Dn Slope=0.005

--- UNT04118 IN CEDR CR.g01 (geometry) ---

Geom Title=Existing Conditions

River Reach=UNT04118 IN CEDR,Reach-1
Reach XY= 30
      3611617.45     10358426.53      3611570.30     10358092.68
      3611771.09     10357580.90      3611675.86     10357469.90
      3611657.18     10357262.98      3611827.63     10357287.73
      3611905.77     10356974.67      3612027.22     10356930.81
      3612057.63     10356538.91      3612318.21     10356400.13
      3612337.48     10356152.65      3612224.28     10355861.69
      3612283.19     10355640.93      3612192.48     10355632.46
      3612174.00     10355457.18      3612307.39     10355209.83
      3612560.06     10355087.15      3612364.98     10355013.39
      3612530.47     10354828.01      3612309.91     10354736.70
      3612268.59     10354609.96      3612417.40     10354524.09
      3612341.86     10354455.80      3612421.78     10354371.33
      3612367.55     10354266.21      3612531.79     10354116.56
      3612352.07     10353848.85      3612316.23     10353662.57
      3612392.09     10353517.39      3612302.11     10353391.64

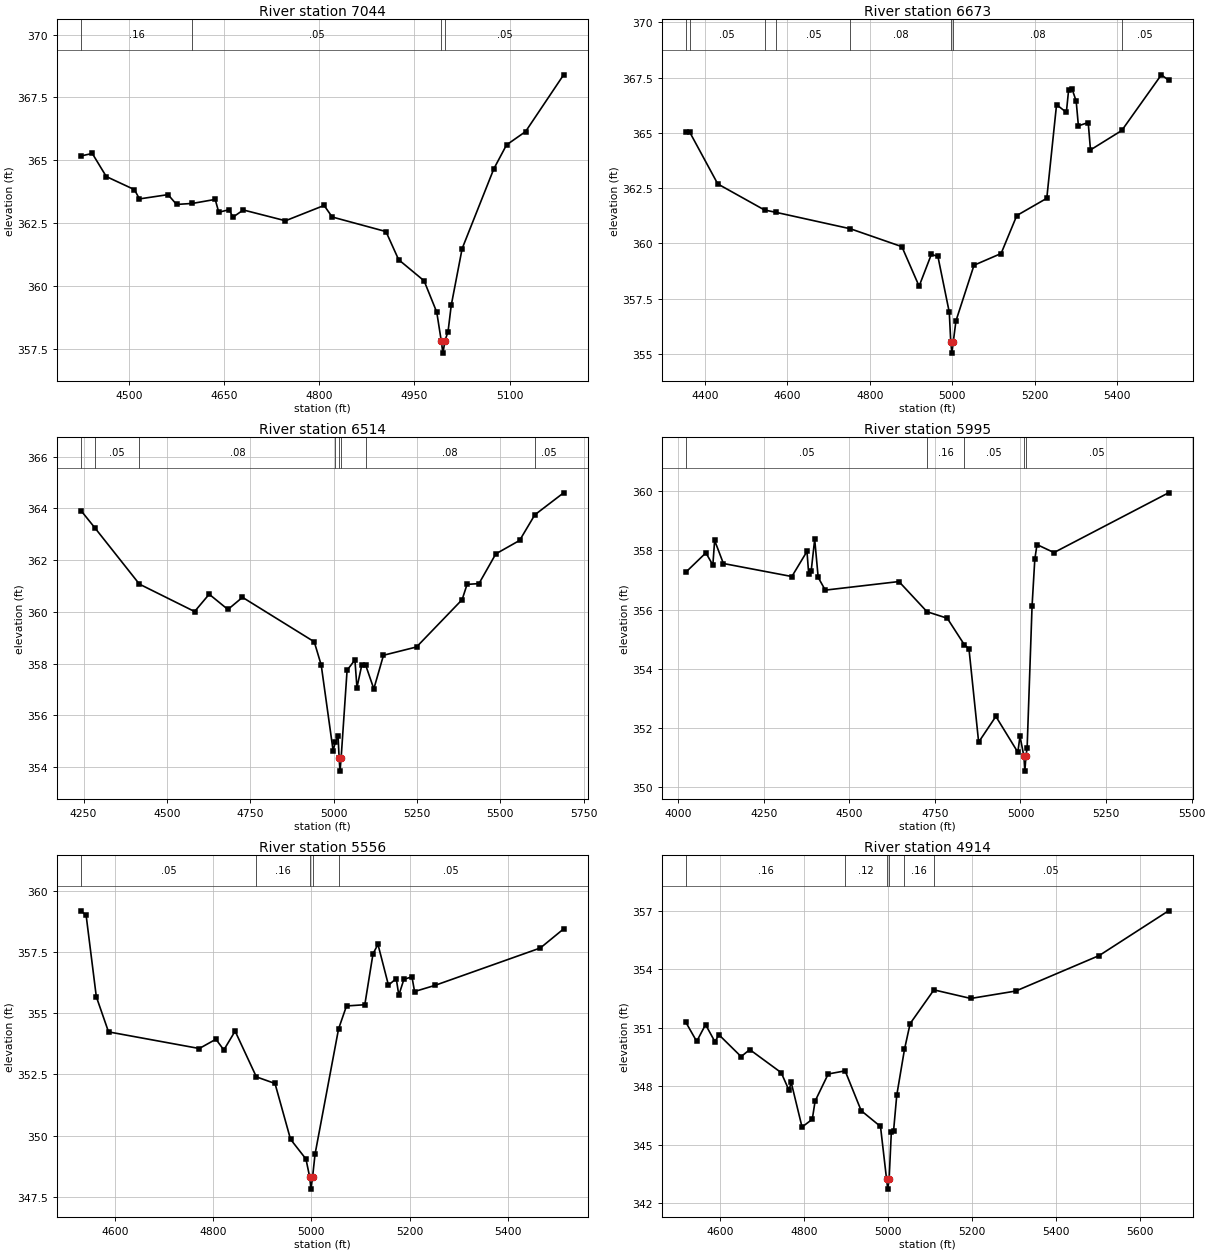
Type RM Length L Ch R = 1,7044,371,371,371
BEGIN DESCRIPTION:
UNT04118 IN CEDR CR 13.0
END DESCRIPTION:
XS GIS Cut Line= 3
      3612103.96     10358334.14      3611713.21     10358132.69
      3611392.15     10358141.64
#Sta/Elev= 30
  4424.5  365.17  4442.2  365.27  4464.3  364.35  4508.6  363.83  4516.6  363.46
  4561.6  363.63  4575.1  363.24  4600.1  363.28  4636.0  363.44  4641.6  362.93
  4658.2  363.03  4663.8  362.73  4680.3  363.02  4746.8  362.59  4807.7  363.20
  4820.4  362.74  4905.2  362.16  4925.2  361.04  4965.3  360.20  4985.3  358.95
  4992.3  357.82  4995.0  357.32  4998.3  357.82  5003.1  358.18  5008.1  359.22
  5025.3  361.48  5075.3  364.66  5095.3  365.61  5125.3  366.14  5185.3  368.40
#Mann=4,-1,0
  4424.5    0.16       0  4600.1    0.05       0  4992.3    0.03       0
  4998.3    0.05       0
Bank Sta=4992.3,4998.3
Exp/Cntr=0.3,0.1

Type RM Length L Ch R = 1,6673,159,159,159
BEGIN DESCRIPTION:
UNT04118 IN CEDR CR 12.0
END DESCRIPTION:
XS GIS Cut Line= 4
      3612233.68     10358198.61      3611739.94     10357853.53
      3611518.59     10357734.17      3611226.40     10357611.89
#Sta/Elev= 30
  4354.2  365.03  4363.2  365.04  4431.4  362.69  4544.8  361.51  4573.7  361.40
  4753.1  360.66  4878.0  359.85  4919.8  358.06  4949.5  359.50  4965.4  359.41
  4993.0  356.88  4996.6  355.53  4999.3  355.03  5002.6  355.53  5009.2  356.49
  5053.0  359.01  5118.7  359.54  5156.8  361.26  5229.5  362.04  5253.2  366.28
  5277.0  365.93  5282.5  366.95  5291.0  366.98  5300.8  366.44  5306.2  365.32
  5330.0  365.47  5335.5  364.23  5411.4  365.11  5507.4  367.63  5524.8  367.39
#Mann=8,-1,0
  4354.2    0.16       0  4363.2    0.05       0  4544.8    0.08       0
  4573.7    0.05       0  4753.1    0.08       0  4996.6    0.07       0
  5002.6    0.08       0  5411.4    0.05       0
Bank Sta=4996.6,5002.6
Exp/Cntr=0.3,0.1

Type RM Length L Ch R = 1,6514,519,519,519
BEGIN DESCRIPTION:
UNT04118 IN CEDR CR 11.01
END DESCRIPTION:
XS GIS Cut Line= 3
      3612361.67     10358139.98      3611856.05     10357758.05
      3611189.78     10357290.35
#Sta/Elev= 30
  4242.3  363.91  4283.5  363.25  4417.4  361.07  4583.0  360.01  4626.7  360.68
  4682.9  360.09  4726.6  360.56  4941.9  358.84  4962.8  357.94  4998.5  354.63
  5005.1  354.96  5013.4  355.19  5016.5  354.34  5019.2  353.84  5022.5  354.34
  5040.4  357.74  5063.9  358.14  5070.0  357.07  5084.8  357.96  5096.1  357.94
  5120.6  357.02  5149.6  358.32  5248.7  358.64  5385.5  360.47  5400.3  361.06
  5436.0  361.09  5486.6  362.24  5558.0  362.76  5603.6  363.75  5690.0  364.60
#Mann=8,-1,0
  4242.3    0.08       0  4283.5    0.05       0  4417.4    0.08       0
  5005.1    0.16       0  5016.5    0.07       0  5022.5    0.16       0
  5096.1    0.08       0  5603.6    0.05       0
Bank Sta=5016.5,5022.5
Exp/Cntr=0.3,0.1

Type RM Length L Ch R = 1,5995,439,439,439
BEGIN DESCRIPTION:
UNT04118 IN CEDR CR 11.0
END DESCRIPTION:
XS GIS Cut Line= 3
      3612568.88     10357565.04      3611821.17     10357396.51
      3611318.43     10356995.90
#Sta/Elev= 30
  4023.1  357.27  4081.3  357.92  4101.7  357.51  4106.9  358.34  4132.5  357.56
  4332.4  357.12  4376.6  357.97  4381.7  357.19  4388.8  357.30  4399.1  358.38
  4409.3  357.09  4430.0  356.66  4645.1  356.95  4727.1  355.93  4786.2  355.71
  4835.8  354.82  4849.7  354.67  4877.9  351.52  4928.2  352.39  4992.3  351.18
  4998.7  351.72  5010.1  351.04  5012.8  350.54  5016.1  351.04  5019.5  351.33
  5033.9  356.12  5041.9  357.70  5048.3  358.20  5097.9  357.93  5432.4  359.95
#Mann=5,-1,0
  4023.1    0.05       0  4727.1    0.16       0  4835.8    0.05       0
  5010.1    0.03       0  5016.1    0.05       0
Bank Sta=5010.1,5016.1
Exp/Cntr=0.3,0.1

Type RM Length L Ch R = 1,5556,642,642,642
BEGIN DESCRIPTION:
UNT04118 IN CEDR CR 10.0
END DESCRIPTION:
XS GIS Cut Line= 3
      3612342.07     10357191.63      3611992.35     10357092.26
      3611402.35     10356901.94
#Sta/Elev= 30
  4530.5  359.19  4540.9  359.00  4561.6  355.68  4586.5  354.24  4771.5  353.56
  4805.4  353.94  4821.5  353.50  4844.5  354.27  4887.8  352.40  4925.8  352.13
  4957.4  349.85  4988.9  349.04  4996.4  348.31  4999.1  347.81  5002.4  348.31
  5007.4  349.24  5055.3  354.36  5071.5  355.30  5108.8  355.35  5125.5  357.43
  5135.6  357.82  5157.0  356.15  5172.9  356.42  5178.1  355.74  5188.5  356.39
  5204.9  356.49  5210.2  355.89  5251.6  356.14  5466.5  357.67  5514.0  358.45
#Mann=5,-1,0
  4530.5    0.05       0  4887.8    0.16       0  4996.4    0.07       0
  5002.4    0.16       0  5055.3    0.05       0
Bank Sta=4996.4,5002.4
Exp/Cntr=0.3,0.1

Type RM Length L Ch R = 1,4914,488,488,488
BEGIN DESCRIPTION:
UNT04118 IN CEDR CR 9.0
END DESCRIPTION:
XS GIS Cut Line= 3
      3612506.25     10356717.97      3611902.54     10356508.42
      3611402.58     10356608.41
#Sta/Elev= 30
  4519.4  351.27  4545.0  350.30  4566.1  351.16  4588.5  350.28  4597.9  350.64
  4650.8  349.52  4671.3  349.88  4746.1  348.70  4764.7  347.80  4770.0  348.20
  4795.8  345.91  4820.2  346.31  4826.9  347.24  4858.1  348.63  4898.4  348.79
  4936.6  346.75  4982.6  345.94  4997.1  343.23  4999.9  342.73  5003.1  343.23
  5008.4  345.65  5013.7  345.71  5021.3  347.54  5039.7  349.89  5053.1  351.21
  5109.8  352.94  5197.5  352.50  5304.6  352.88  5503.4  354.70  5668.3  356.99
#Mann=6,-1,0
  4519.4    0.16       0  4898.4    0.12       0  4997.1    0.07       0
  5003.1    0.12       0  5039.7    0.16       0  5109.8    0.05       0
Bank Sta=4997.1,5003.1
Exp/Cntr=0.3,0.1

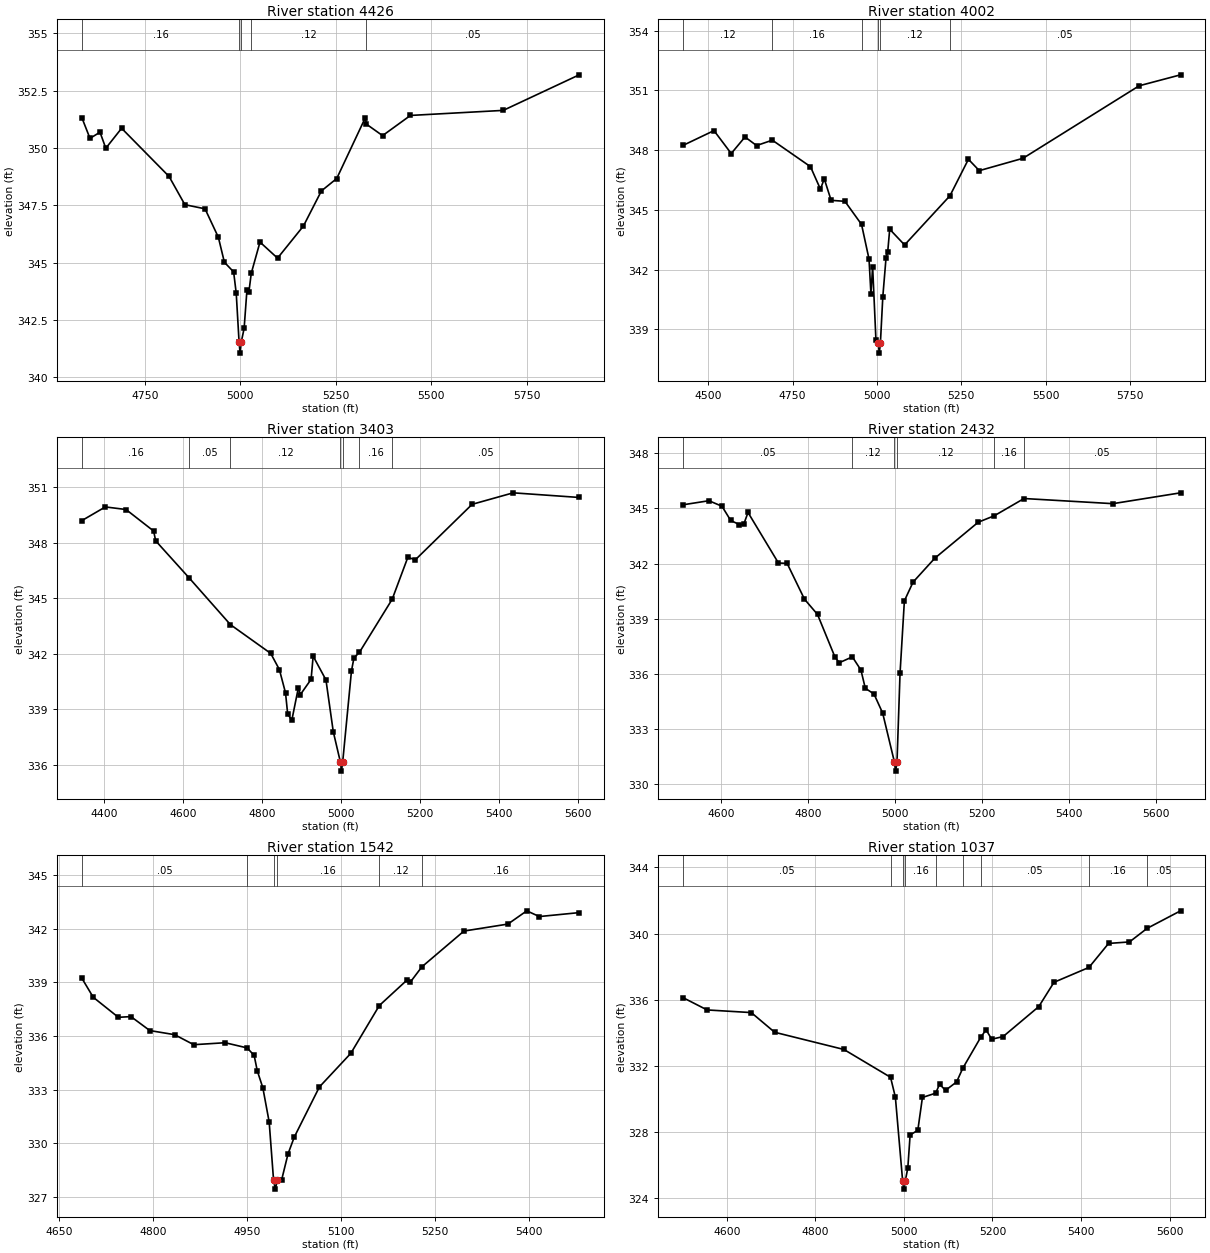
Type RM Length L Ch R = 1,4426,424,424,424
BEGIN DESCRIPTION:
UNT04118 IN CEDR CR 8.0
END DESCRIPTION:
XS GIS Cut Line= 3
      3612702.89     10356369.04      3611936.84     10356164.01
      3611436.95     10356263.99
#Sta/Elev= 30
  4584.5  351.33  4606.0  350.42  4632.2  350.69  4647.4  349.99  4688.8  350.86
  4813.1  348.76  4854.5  347.53  4907.3  347.35  4942.2  346.11  4958.0  345.02
  4982.2  344.60  4989.0  343.67  4996.4  341.56  4999.1  341.06  5002.4  341.56
  5009.7  342.14  5017.1  343.82  5022.2  343.73  5028.4  344.54  5051.2  345.90
  5097.2  345.20  5165.0  346.60  5212.1  348.13  5252.2  348.67  5327.1  351.32
  5330.0  351.04  5372.3  350.54  5445.3  351.42  5688.3  351.64  5887.3  353.19
#Mann=5,-1,0
  4584.5    0.16       0  4996.4    0.07       0  5002.4    0.16       0
  5028.4    0.12       0  5330.0    0.05       0
Bank Sta=4996.4,5002.4
Exp/Cntr=0.3,0.1

Type RM Length L Ch R = 1,4002,599,599,599
BEGIN DESCRIPTION:
UNT04118 IN CEDR CR 7.0
END DESCRIPTION:
XS GIS Cut Line= 3
      3612791.67     10356001.07      3611884.50     10355810.75
      3611365.73     10355987.89
#Sta/Elev= 30
  4425.3  348.24  4516.8  348.98  4567.9  347.83  4608.8  348.66  4643.1  348.23
  4689.8  348.50  4802.9  347.17  4832.5  346.04  4843.8  346.56  4864.2  345.48
  4905.1  345.43  4954.4  344.27  4976.6  342.53  4982.2  340.79  4987.3  342.14
  4997.1  338.46  5004.3  338.31  5007.0  337.81  5010.3  338.31  5017.5  340.65
  5027.0  342.59  5032.1  342.91  5037.9  344.03  5082.0  343.24  5216.6  345.71
  5271.3  347.54  5303.6  346.97  5433.2  347.59  5777.7  351.23  5900.4  351.78
#Mann=6,-1,0
  4425.3    0.12       0  4689.8    0.16       0  4954.4    0.12       0
  5004.3    0.07       0  5010.3    0.12       0  5216.6    0.05       0
Bank Sta=5004.3,5010.3
Exp/Cntr=0.3,0.1

Type RM Length L Ch R = 1,3403,971,971,971
BEGIN DESCRIPTION:
UNT04118 IN CEDR CR 6.0
END DESCRIPTION:
XS GIS Cut Line= 3
      3612808.92     10355631.87      3611928.91     10355353.98
      3611599.00     10355417.42
#Sta/Elev= 30
  4344.5  349.18  4404.1  349.92  4456.4  349.78  4526.3  348.62  4531.5  348.09
  4615.8  346.10  4720.7  343.57  4822.6  342.02  4844.5  341.15  4860.1  339.89
  4865.5  338.76  4876.0  338.41  4892.5  340.16  4897.7  339.80  4924.8  340.62
  4930.0  341.87  4962.4  340.59  4980.9  337.80  4998.8  336.17  5001.6  335.67
  5004.8  336.17  5027.0  341.08  5033.3  341.78  5046.9  342.07  5130.0  344.94
  5169.6  347.20  5188.7  347.07  5332.3  350.06  5436.2  350.68  5603.3  350.43
#Mann=7,-1,0
  4344.5    0.16       0  4615.8    0.05       0  4720.7    0.12       0
  4998.8    0.07       0  5004.8    0.12       0  5046.9    0.16       0
  5130.0    0.05       0
Bank Sta=4998.8,5004.8
Exp/Cntr=0.3,0.1

Type RM Length L Ch R = 1,2432,890,890,890
BEGIN DESCRIPTION:
UNT04118 IN CEDR CR 5.0
END DESCRIPTION:
XS GIS Cut Line= 3
      3612861.48     10354960.65      3611865.55     10354970.35
      3611716.32     10354970.35
#Sta/Elev= 30
  4512.4  345.20  4571.8  345.42  4601.8  345.12  4621.8  344.35  4641.8  344.12
  4651.8  344.13  4661.8  344.78  4731.8  342.03  4751.8  342.01  4791.8  340.06
  4821.8  339.23  4861.8  336.92  4871.8  336.60  4902.0  336.92  4921.8  336.20
  4931.8  335.21  4951.8  334.90  4971.8  333.86  4998.8  331.20  5001.5  330.70
  5004.8  331.20  5011.8  336.03  5021.8  339.97  5041.8  340.99  5091.8  342.29
  5191.8  344.25  5228.7  344.60  5297.3  345.54  5501.8  345.26  5657.6  345.85
#Mann=6,-1,0
  4512.4    0.05       0  4902.0    0.12       0  4998.8    0.07       0
  5004.8    0.12       0  5228.7    0.16       0  5297.3    0.05       0
Bank Sta=4998.8,5004.8
Exp/Cntr=0.3,0.1

Type RM Length L Ch R = 1,1542,505,505,505
BEGIN DESCRIPTION:
UNT04118 IN CEDR CR 3.0
END DESCRIPTION:
XS GIS Cut Line= 3
      3612730.30     10354549.00      3612038.38     10354492.83
      3611938.38     10354492.83
#Sta/Elev= 30
  4686.3  339.24  4704.6  338.17  4744.7  337.05  4764.8  337.09  4794.9  336.31
  4834.5  336.08  4865.1  335.52  4915.2  335.63  4950.4  335.34  4961.5  334.92
  4966.5  334.06  4975.4  333.11  4985.5  331.20  4992.5  327.95  4995.3  327.45
  4998.5  327.95  5005.5  327.98  5015.6  329.42  5025.6  330.36  5065.7  333.16
  5115.9  335.04  5161.4  337.71  5205.5  339.13  5210.5  339.00  5229.3  339.87
  5296.5  341.87  5366.7  342.26  5396.8  343.00  5416.8  342.68  5480.5  342.90
#Mann=6,-1,0
  4686.3    0.05       0  4950.4    0.16       0  4992.5    0.07       0
  4998.5    0.16       0  5161.4    0.12       0  5229.3    0.16       0
Bank Sta=4992.5,4998.5
Exp/Cntr=0.3,0.1

Type RM Length L Ch R = 1,1037,482,482,482
BEGIN DESCRIPTION:
UNT04118 IN CEDR CR 2.0
END DESCRIPTION:
XS GIS Cut Line= 3
      3612950.31     10354351.62      3612238.34     10354140.89
      3611888.34     10354290.89
#Sta/Elev= 30
  4501.6  336.13  4555.7  335.39  4655.5  335.23  4708.3  334.04  4864.7  333.00
  4970.0  331.32  4980.9  330.12  4997.3  325.06  5000.1  324.56  5003.3  325.06
  5009.0  325.84  5014.2  327.83  5031.6  328.12  5042.0  330.10  5071.9  330.36
  5080.7  330.90  5094.2  330.53  5119.2  331.04  5133.0  331.86  5173.7  333.74
  5185.7  334.19  5198.5  333.62  5224.2  333.78  5304.7  335.59  5339.1  337.06
  5418.1  337.96  5462.4  339.41  5509.6  339.50  5549.4  340.32  5624.9  341.38
#Mann=9,-1,0
  4501.6    0.05       0  4970.0    0.16       0  4997.3    0.07       0
  5003.3    0.16       0  5071.9    0.05       0  5133.0    0.16       0
  5173.7    0.05       0  5418.1    0.16       0  5549.4    0.05       0
Bank Sta=4997.3,5003.3
Exp/Cntr=0.3,0.1

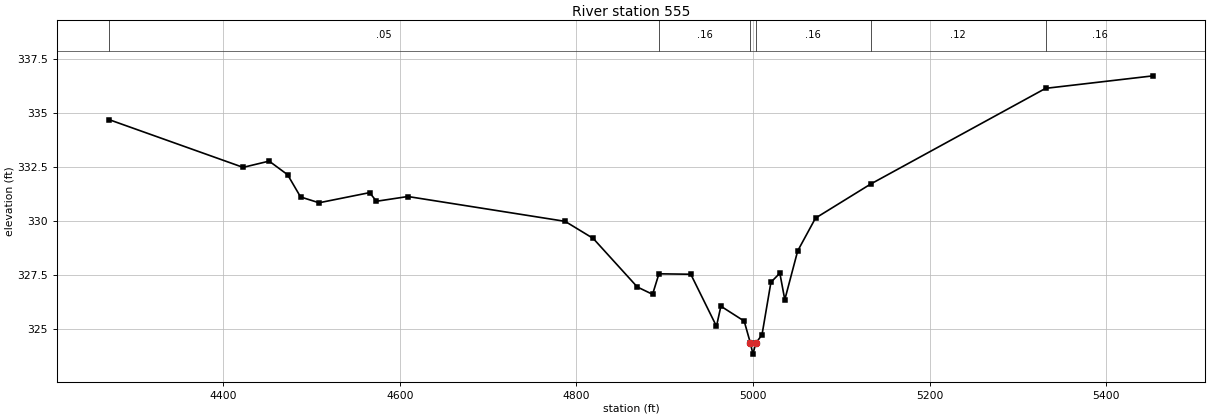
Type RM Length L Ch R = 1,555,0,0,0
BEGIN DESCRIPTION:
UNT04118 IN CEDR CR 1.0
END DESCRIPTION:
XS GIS Cut Line= 3
      3612982.02     10354173.98      3612556.97     10353869.47
      3611902.98     10353780.37
#Sta/Elev= 30
  4270.5  334.70  4422.3  332.49  4451.8  332.78  4472.7  332.15  4487.4  331.12
  4508.3  330.85  4565.6  331.32  4573.4  330.92  4609.0  331.14  4787.1  329.99
  4818.9  329.20  4868.9  326.95  4886.2  326.61  4893.4  327.56  4929.5  327.54
  4958.6  325.13  4963.6  326.06  4990.0  325.37  4997.1  324.34  4999.9  323.84
  5003.1  324.34  5010.2  324.74  5020.3  327.17  5030.4  327.59  5036.0  326.36
  5050.6  328.62  5070.8  330.14  5133.4  331.72  5331.5  336.15  5453.4  336.73
#Mann=6,-1,0
  4270.5    0.05       0  4893.4    0.16       0  4997.1    0.07       0
  5003.1    0.16       0  5133.4    0.12       0  5331.5    0.16       0
Bank Sta=4997.1,5003.1
Exp/Cntr=0.3,0.1

Chan Stop Cuts=-1