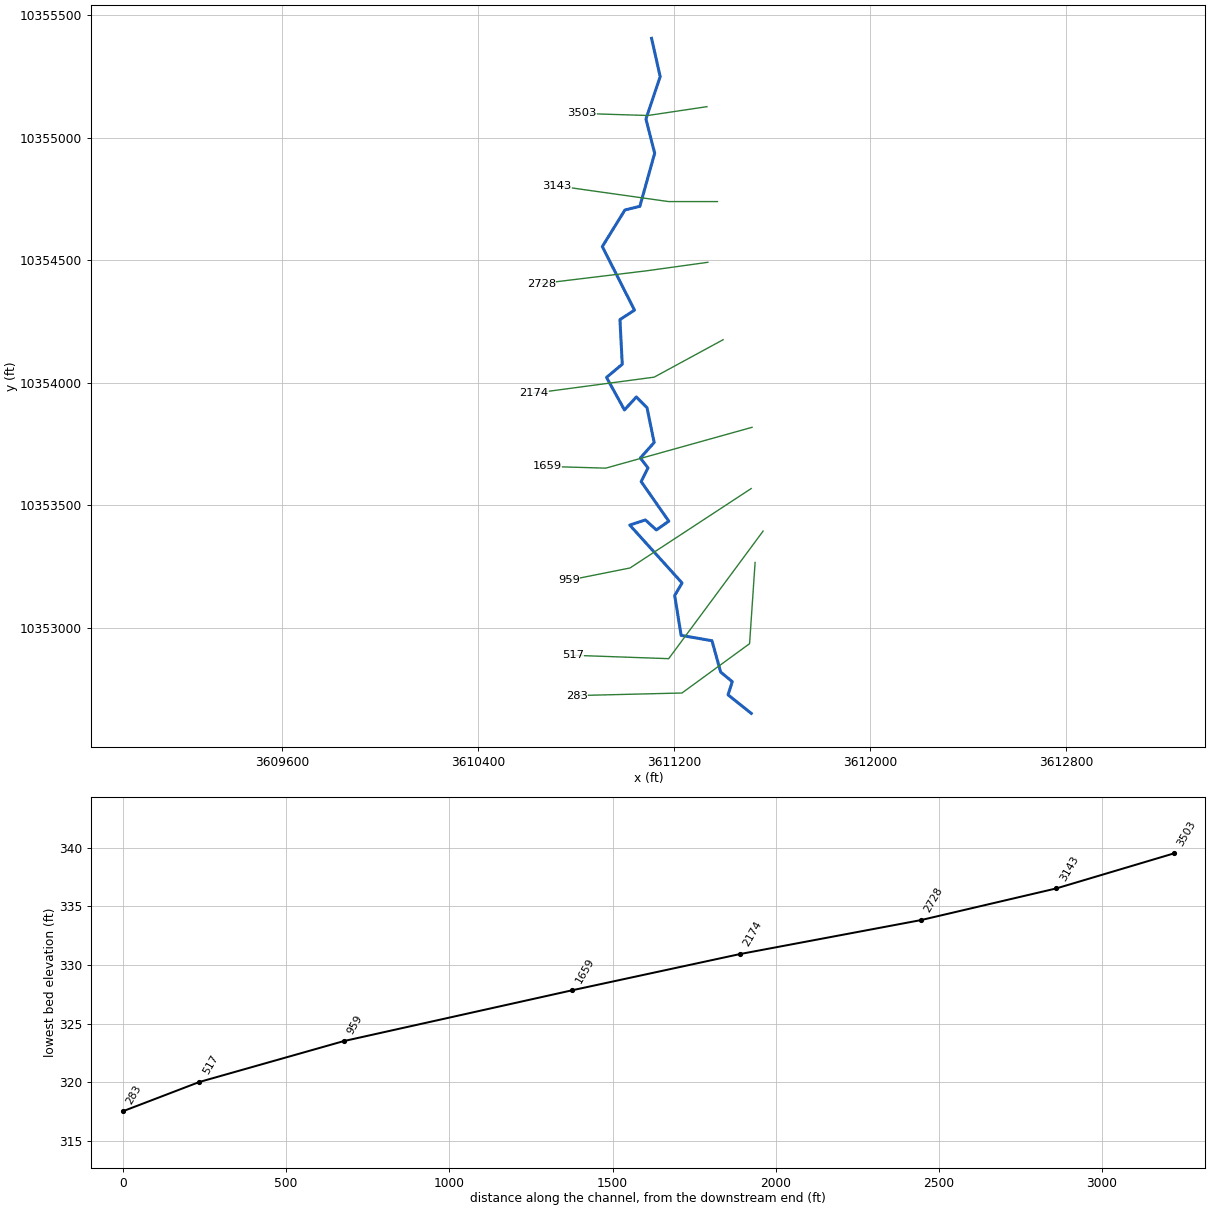
--- UNT04119 IN CEDR CR.prj (project) ---

Proj Title=UNT04119 IN CEDR CR Base Level Engineering
Current Plan=p01
Default Exp/Contr=0.3,0.1
English Units
Geom File=g01
Flow File=f01
Plan File=p01
BEGIN DESCRIPTION:
UNT04119 IN CEDR CR
END DESCRIPTION:

--- UNT04119 IN CEDR CR.p01 (plan) ---

Plan Title=Multiple Run
Short Identifier=Multiple
Geom File=g01
Flow File=f01
Subcritical Flow
K Sum by GR= 0
Std Step Tol= 0.01
Critical Tol= 0.01
Num of Std Step Trials= 20
Max Error Tol= 0.3
Flow Tol Ratio= 0.001
Split Flow NTrial= 30
Split Flow Tol= 0.02
Split Flow Ratio= 0.02
Log Output Level= 0
Friction Slope Method= 1
Unsteady Friction Slope Method= 2
Unsteady Bridges Friction Slope Method= 1
Parabolic Critical Depth
Global Vel Dist=  1 , 1 , 1
Global Log Level= 0
CheckData=True
Encroach Param= -1, 0, 0, 0
BEGIN DESCRIPTION:
Multiple Run
END DESCRIPTION:

--- UNT04119 IN CEDR CR.f01 (steady flow) ---

Flow Title=Multiple
Number of Profiles=7
Profile Names=10-year,25-year,50-year,1pct_min,100-year,1pct_plu,500-year
River Rch & RM= UNT04119 IN CEDR,Reach-1,3503
     383     492     577     496     671     907     900
Boundary for River Rch & Prof#=UNT04119 IN CEDR,Reach-1,1
Up Type=0
Dn Type=3
Dn Slope=0.005
Boundary for River Rch & Prof#=UNT04119 IN CEDR,Reach-1,2
Up Type=0
Dn Type=3
Dn Slope=0.005
Boundary for River Rch & Prof#=UNT04119 IN CEDR,Reach-1,3
Up Type=0
Dn Type=3
Dn Slope=0.005
Boundary for River Rch & Prof#=UNT04119 IN CEDR,Reach-1,4
Up Type=0
Dn Type=3
Dn Slope=0.005
Boundary for River Rch & Prof#=UNT04119 IN CEDR,Reach-1,5
Up Type=0
Dn Type=3
Dn Slope=0.005
Boundary for River Rch & Prof#=UNT04119 IN CEDR,Reach-1,6
Up Type=0
Dn Type=3
Dn Slope=0.005
Boundary for River Rch & Prof#=UNT04119 IN CEDR,Reach-1,7
Up Type=0
Dn Type=3
Dn Slope=0.005

--- UNT04119 IN CEDR CR.g01 (geometry) ---

Geom Title=Existing Conditions

River Reach=UNT04119 IN CEDR,Reach-1
Reach XY= 30
      3611107.11     10355406.64      3611142.29     10355250.20
      3611084.06     10355077.22      3611119.81     10354937.69
      3611059.32     10354720.81      3610998.38     10354705.97
      3610906.05     10354556.47      3611037.46     10354297.00
      3610977.99     10354258.37      3610987.45     10354076.24
      3610923.27     10354022.40      3610996.42     10353889.67
      3611045.09     10353942.56      3611088.57     10353898.59
      3611117.67     10353756.71      3611061.41     10353693.51
      3611092.40     10353652.89      3611064.65     10353597.01
      3611177.50     10353435.36      3611126.53     10353399.53
      3611081.94     10353440.49      3611018.09     10353419.60
      3611231.68     10353183.11      3611201.48     10353132.07
      3611227.81     10352969.23      3611353.62     10352947.36
      3611389.20     10352819.30      3611436.63     10352780.41
      3611419.23     10352726.59      3611514.04     10352650.79

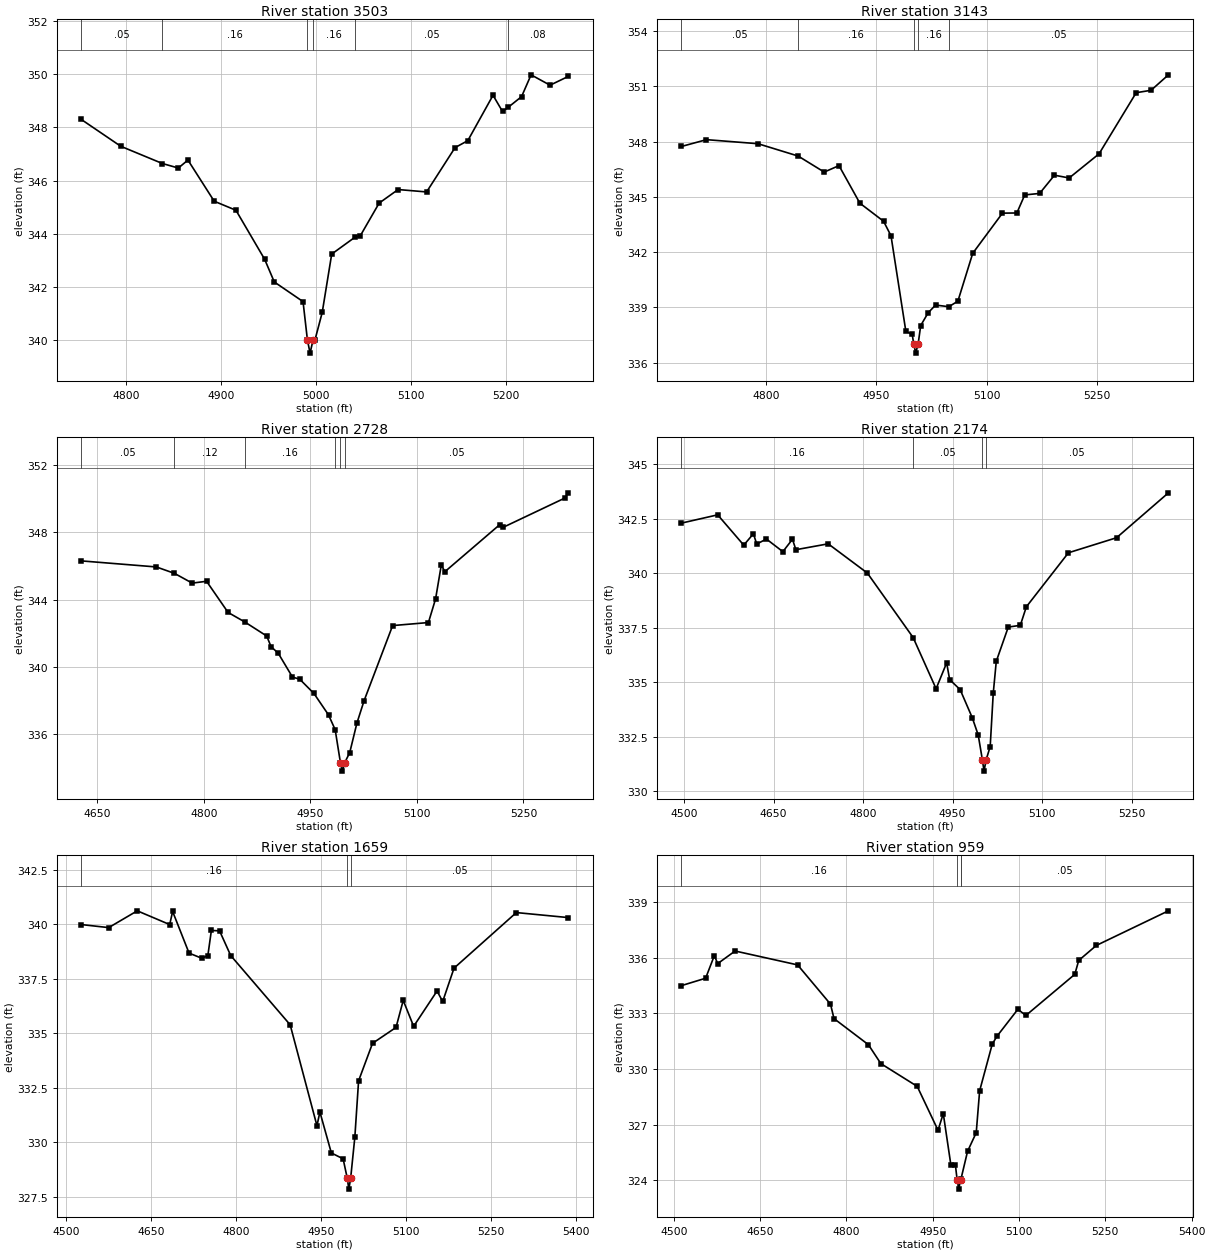
Type RM Length L Ch R = 1,3503,360,360,360
BEGIN DESCRIPTION:
UNT04119 IN CEDR CR 7.0
END DESCRIPTION:
XS GIS Cut Line= 3
      3611333.27     10355127.74      3611092.11     10355091.64
      3610822.88     10355099.96
#Sta/Elev= 30
  4752.8  348.30  4794.4  347.29  4838.3  346.64  4855.1  346.47  4865.2  346.77
  4892.9  345.22  4915.8  344.88  4946.1  343.03  4956.2  342.18  4986.5  341.44
  4991.1  340.00  4993.9  339.50  4997.1  340.00  4999.1  340.00  5006.7  341.03
  5016.7  343.23  5041.4  343.87  5046.7  343.91  5066.7  345.15  5086.7  345.66
  5116.7  345.57  5146.7  347.24  5160.1  347.50  5186.7  349.21  5196.7  348.60
  5202.8  348.76  5216.8  349.16  5226.8  349.98  5246.8  349.59  5266.0  349.92
#Mann=6,-1,0
  4752.8    0.05       0  4838.3    0.16       0  4991.1    0.07       0
  4997.1    0.16       0  5041.4    0.05       0  5202.8    0.08       0
Bank Sta=4991.1,4997.1
Exp/Cntr=0.3,0.1

Type RM Length L Ch R = 1,3143,415,415,415
BEGIN DESCRIPTION:
UNT04119 IN CEDR CR 6.0
END DESCRIPTION:
XS GIS Cut Line= 3
      3611376.18     10354740.26      3611176.14     10354740.26
      3610718.71     10354804.80
#Sta/Elev= 30
  4685.2  347.74  4719.3  348.11  4789.3  347.89  4843.9  347.22  4879.3  346.35
  4899.4  346.70  4927.8  344.66  4960.0  343.68  4970.1  342.89  4990.3  337.70
  4998.9  337.54  5001.0  337.02  5003.7  336.52  5007.0  337.02  5010.5  338.02
  5020.6  338.71  5030.7  339.13  5048.7  339.04  5061.0  339.34  5081.2  341.94
  5121.6  344.12  5141.2  344.13  5151.9  345.11  5172.1  345.19  5192.3  346.18
  5212.3  346.03  5252.9  347.34  5303.4  350.66  5323.6  350.79  5347.2  351.63
#Mann=5,-1,0
  4685.2    0.05       0  4843.9    0.16       0  5001.0    0.07       0
  5007.0    0.16       0  5048.7    0.05       0
Bank Sta=5001,5007
Exp/Cntr=0.3,0.1

Type RM Length L Ch R = 1,2728,554,554,554
BEGIN DESCRIPTION:
UNT04119 IN CEDR CR 5.0
END DESCRIPTION:
XS GIS Cut Line= 3
      3611336.81     10354492.29      3611086.75     10354457.56
      3610656.64     10354405.53
#Sta/Elev= 30
  4627.4  346.30  4733.1  345.94  4758.6  345.56  4783.6  344.98  4803.8  345.09
  4834.1  343.24  4857.8  342.67  4888.5  341.84  4894.6  341.21  4904.7  340.82
  4924.8  339.40  4934.9  339.28  4955.0  338.43  4975.5  337.16  4984.9  336.28
  4992.3  334.32  4995.1  333.82  4998.3  334.32  5005.4  334.92  5015.5  336.67
  5025.6  338.00  5065.8  342.46  5116.2  342.64  5126.3  344.05  5134.3  346.05
  5139.4  345.66  5216.3  348.44  5221.3  348.29  5308.3  350.03  5313.1  350.34
#Mann=6,-1,0
  4627.4    0.05       0  4758.6    0.12       0  4857.8    0.16       0
  4984.9    0.05       0  4992.3    0.03       0  4998.3    0.05       0
Bank Sta=4992.3,4998.3
Exp/Cntr=0.3,0.1

Type RM Length L Ch R = 1,2174,515,515,515
BEGIN DESCRIPTION:
UNT04119 IN CEDR CR 4.0
END DESCRIPTION:
XS GIS Cut Line= 3
      3611399.30     10354176.31      3611118.00     10354023.51
      3610626.01     10353957.68
#Sta/Elev= 30
  4495.3  342.31  4556.1  342.69  4599.8  341.30  4616.0  341.82  4621.6  341.35
  4637.8  341.58  4665.4  341.00  4681.5  341.57  4687.2  341.09  4741.4  341.36
  4807.0  340.02  4883.8  337.06  4922.3  334.71  4940.0  335.90  4945.0  335.13
  4962.6  334.67  4982.8  333.39  4992.9  332.59  5000.0  331.43  5002.7  330.93
  5006.0  331.43  5013.0  332.06  5018.1  334.50  5023.2  335.97  5043.3  337.54
  5063.5  337.62  5073.6  338.47  5144.2  340.95  5224.9  341.64  5311.8  343.70
#Mann=4,-1,0
  4495.3    0.16       0  4883.8    0.05       0  5000.0    0.03       0
  5006.0    0.05       0
Bank Sta=5000,5006
Exp/Cntr=0.3,0.1

Type RM Length L Ch R = 1,1659,700,700,700
BEGIN DESCRIPTION:
UNT04119 IN CEDR CR 3.0
END DESCRIPTION:
XS GIS Cut Line= 3
      3611517.35     10353818.64      3610920.07     10353651.96
      3610680.47     10353658.90
#Sta/Elev= 30
  4527.0  339.98  4575.4  339.84  4625.9  340.61  4683.1  339.98  4688.3  340.58
  4717.3  338.67  4740.1  338.43  4750.5  338.56  4756.7  339.71  4771.2  339.69
  4790.8  338.56  4895.8  335.38  4943.1  330.75  4948.3  331.38  4968.5  329.50
  4989.3  329.23  4996.6  328.34  4999.4  327.84  5002.6  328.34  5010.0  330.23
  5016.6  332.81  5041.2  334.53  5082.7  335.26  5095.4  336.50  5113.8  335.31
  5155.1  336.93  5165.1  336.45  5185.1  337.98  5295.1  340.53  5386.8  340.30
#Mann=3,-1,0
  4527.0    0.16       0  4996.6    0.07       0  5002.6    0.05       0
Bank Sta=4996.6,5002.6
Exp/Cntr=0.3,0.1

Type RM Length L Ch R = 1,959,442,442,442
BEGIN DESCRIPTION:
UNT04119 IN CEDR CR 2.0
END DESCRIPTION:
XS GIS Cut Line= 3
      3611513.89     10353568.64      3611019.18     10353244.41
      3610769.22     10353194.42
#Sta/Elev= 30
  4513.2  334.50  4555.3  334.90  4570.4  336.12  4576.3  335.69  4606.5  336.37
  4715.1  335.62  4772.3  333.50  4778.4  332.72  4838.2  331.31  4859.8  330.29
  4923.0  329.06  4959.2  326.69  4968.3  327.59  4981.6  324.80  4989.4  324.81
  4992.4  324.01  4995.1  323.51  4998.4  324.01  4999.1  324.06  5010.5  325.55
  5025.6  326.56  5031.5  328.82  5053.4  331.34  5061.7  331.77  5097.9  333.22
  5111.9  332.89  5196.9  335.11  5203.7  335.86  5234.3  336.67  5359.6  338.54
#Mann=4,-1,0
  4513.2    0.16       0  4992.4    0.03       0  4998.4    0.16       0
  4999.1    0.05       0
Bank Sta=4992.4,4998.4
Exp/Cntr=0.3,0.1

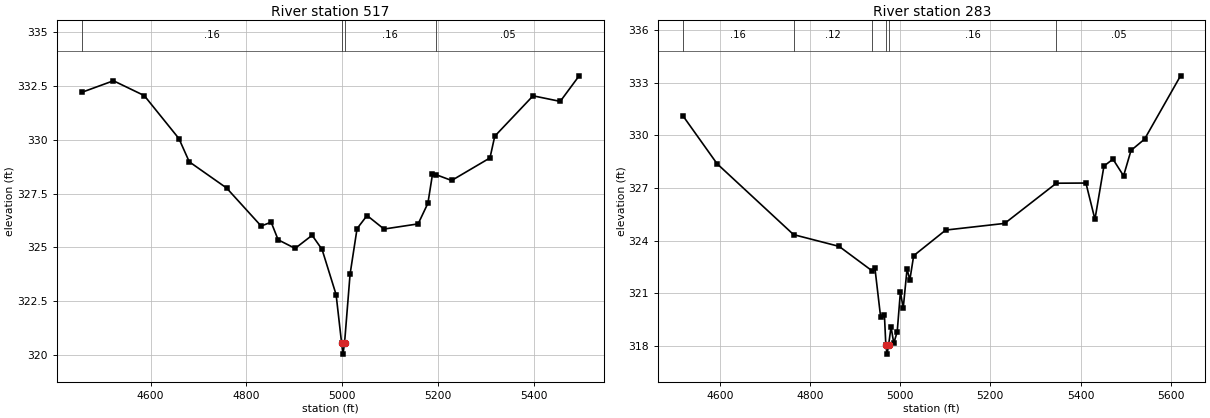
Type RM Length L Ch R = 1,517,234,234,234
BEGIN DESCRIPTION:
UNT04119 IN CEDR CR 1.0
END DESCRIPTION:
XS GIS Cut Line= 3
      3611562.49     10353395.02      3611177.03     10352874.13
      3610785.87     10352887.98
#Sta/Elev= 30
  4455.8  332.21  4522.2  332.75  4586.6  332.06  4659.0  330.06  4680.6  328.98
  4758.6  327.76  4830.8  325.99  4851.7  326.17  4866.3  325.35  4901.8  324.95
  4937.3  325.56  4958.1  324.90  4987.4  322.80  4999.0  320.53  5001.7  320.03
  5005.0  320.53  5016.6  323.75  5031.2  325.87  5052.1  326.48  5087.5  325.85
  5158.8  326.09  5179.2  327.05  5188.8  328.40  5196.3  328.38  5228.8  328.11
  5308.9  329.16  5318.9  330.17  5398.9  332.05  5455.7  331.79  5495.2  332.98
#Mann=4,-1,0
  4455.8    0.16       0  4999.0    0.07       0  5005.0    0.16       0
  5196.3    0.05       0
Bank Sta=4999,5005
Exp/Cntr=0.3,0.1

Type RM Length L Ch R = 1,283,0,0,0
BEGIN DESCRIPTION:
UNT04119 IN CEDR CR 1.01
END DESCRIPTION:
XS GIS Cut Line= 4
      3611529.80     10353266.90      3611507.23     10352935.35
      3611231.19     10352733.96      3610802.33     10352723.54
#Sta/Elev= 30
  4518.8  331.11  4594.2  328.39  4763.8  324.35  4864.8  323.68  4938.8  322.27
  4944.1  322.46  4956.7  319.68  4965.2  319.79  4968.4  318.04  4971.1  317.54
  4974.4  318.04  4979.9  319.09  4986.0  318.16  4993.6  318.82  5000.7  321.10
  5006.9  320.15  5015.4  322.39  5021.6  321.77  5030.1  323.15  5101.1  324.61
  5231.9  324.99  5346.4  327.28  5412.0  327.29  5432.0  325.22  5452.0  328.26
  5472.0  328.65  5495.5  327.70  5512.0  329.15  5542.0  329.79  5621.8  333.40
#Mann=6,-1,0
  4518.8    0.16       0  4763.8    0.12       0  4938.8    0.16       0
  4968.4    0.07       0  4974.4    0.16       0  5346.4    0.05       0
Bank Sta=4968.4,4974.4
Exp/Cntr=0.3,0.1

Chan Stop Cuts=-1