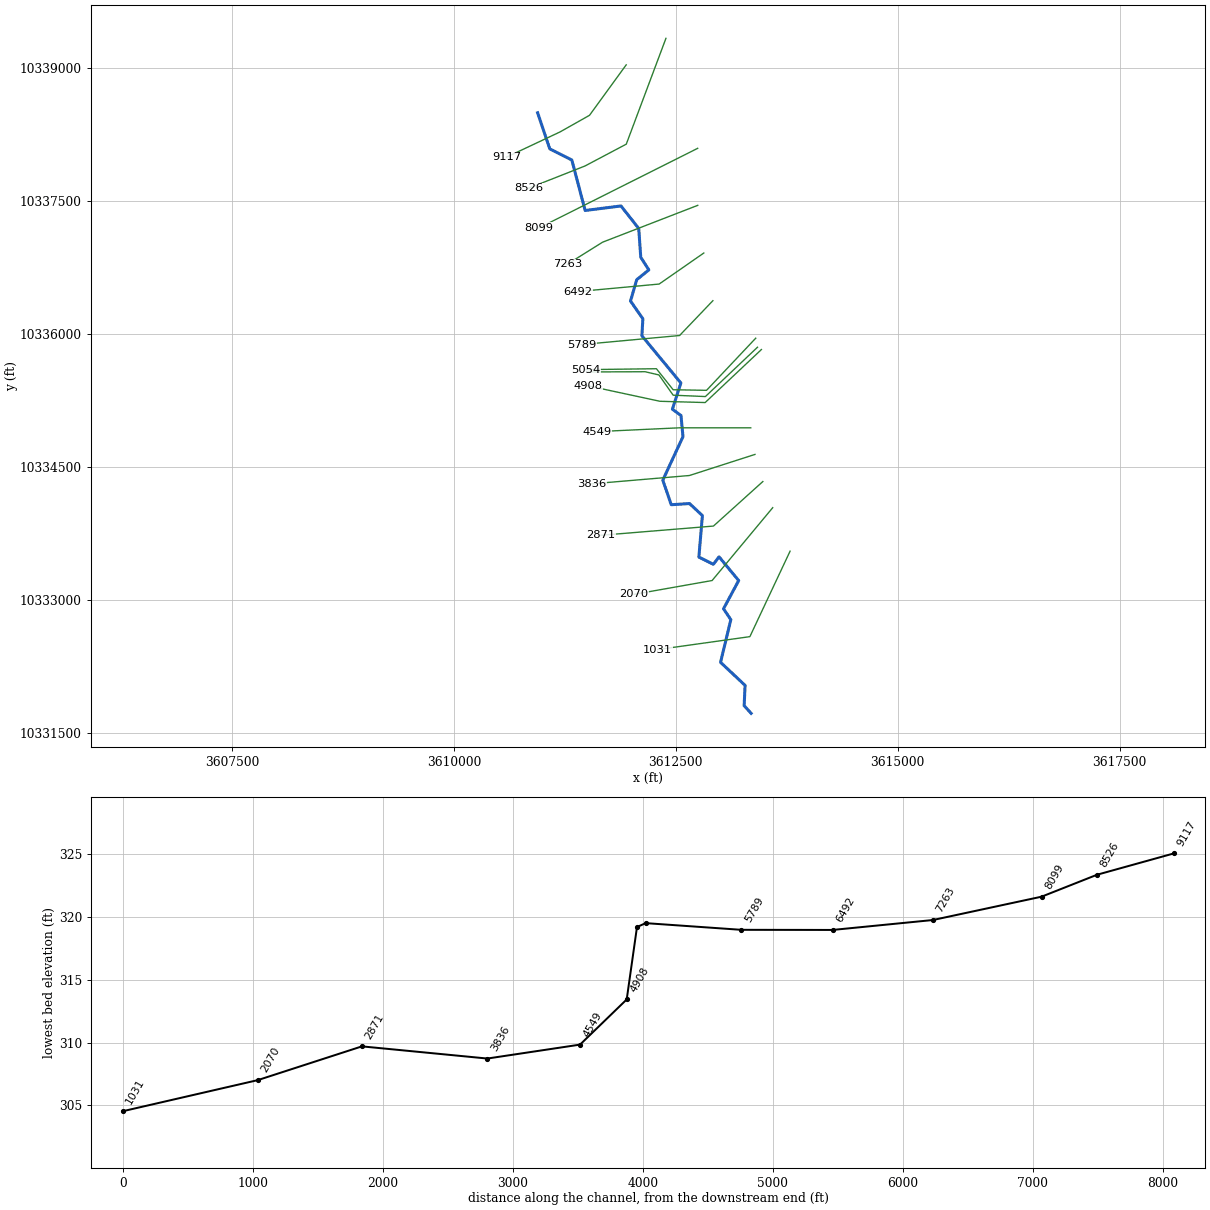
--- UNT0412 IN CEDR CR.prj (project) ---

Proj Title=UNT0412 IN CEDR CR Base Level Engineering
Current Plan=p01
Default Exp/Contr=0.3,0.1
English Units
Geom File=g01
Flow File=f01
Plan File=p01
Y Axis Title=Elevation
X Axis Title(PF)=Main Channel Distance
X Axis Title(XS)=Station
BEGIN DESCRIPTION:
UNT0412 IN CEDR CR
END DESCRIPTION:
DSS Export Rating Curves= 0
DSS Export Rating Curve Sorted= 0
DSS Export Volume Flow Curves= 0
DXF OffsetX= 0
DXF OffsetY= 0
DXF ScaleX= 1
DXF ScaleY= 10

--- UNT0412 IN CEDR CR.p01 (plan) ---

Plan Title=Multiple Run
Short Identifier=Multiple
Geom File=g01
Flow File=f01
Subcritical Flow
K Sum by GR= 0
Std Step Tol= 0.01
Critical Tol= 0.01
Num of Std Step Trials= 20
Max Error Tol= 0.3
Flow Tol Ratio= 0.001
Split Flow NTrial= 30
Split Flow Tol= 0.02
Split Flow Ratio= 0.02
Log Output Level= 0
Friction Slope Method= 1
Unsteady Friction Slope Method= 2
Unsteady Bridges Friction Slope Method= 1
Parabolic Critical Depth
Global Vel Dist=  1 , 1 , 1
Global Log Level= 0
CheckData=True
Encroach Param= -1, 0, 0, 0
BEGIN DESCRIPTION:
Multiple Run
END DESCRIPTION:

--- UNT0412 IN CEDR CR.f01 (steady flow) ---

Flow Title=Multiple
Number of Profiles=7
Profile Names=10-year,25-year,50-year,1pct_min,100-year,1pct_plu,500-year
River Rch & RM= UNT0412 IN CEDR ,Reach-1,9117
     777    1048    1268    1122    1517    2051    2177
River Rch & RM= UNT0412 IN CEDR ,Reach-1,4987
    1029    1408    1720    1535    2076    2808    3033
Boundary for River Rch & Prof#=UNT0412 IN CEDR ,Reach-1,1
Up Type=0
Dn Type=3
Dn Slope=0.005
Boundary for River Rch & Prof#=UNT0412 IN CEDR ,Reach-1,2
Up Type=0
Dn Type=3
Dn Slope=0.005
Boundary for River Rch & Prof#=UNT0412 IN CEDR ,Reach-1,3
Up Type=0
Dn Type=3
Dn Slope=0.005
Boundary for River Rch & Prof#=UNT0412 IN CEDR ,Reach-1,4
Up Type=0
Dn Type=3
Dn Slope=0.005
Boundary for River Rch & Prof#=UNT0412 IN CEDR ,Reach-1,5
Up Type=0
Dn Type=3
Dn Slope=0.005
Boundary for River Rch & Prof#=UNT0412 IN CEDR ,Reach-1,6
Up Type=0
Dn Type=3
Dn Slope=0.005
Boundary for River Rch & Prof#=UNT0412 IN CEDR ,Reach-1,7
Up Type=0
Dn Type=3
Dn Slope=0.005

--- UNT0412 IN CEDR CR.g01 (geometry) ---

Geom Title=Existing Conditions
Program Version=4.10

River Reach=UNT0412 IN CEDR ,Reach-1
Reach XY= 30
      3610942.49     10338491.65      3611079.93     10338084.67
      3611328.22     10337959.48       3611478.2     10337390.58
      3611882.11     10337441.64      3612082.19     10337187.73
      3612104.98      10336863.3      3612196.12     10336721.15
       3612059.4     10336610.48      3611989.31     10336370.15
      3612128.88      10336170.2      3612117.34     10335979.25
      3612557.09     10335446.78      3612461.52      10335151.3
      3612558.17     10335080.45      3612580.79     10334841.65
      3612353.31     10334351.79      3612448.48      10334074.9
      3612654.66     10334087.93      3612799.63     10333952.51
      3612759.83     10333484.93       3612922.5     10333403.71
      3612987.38      10333487.5      3613208.59     10333220.22
      3613037.53     10332902.29      3613120.25      10332779.9
      3613004.26     10332298.79      3613280.64     10332039.07
      3613270.23     10331809.91      3613349.13     10331723.53

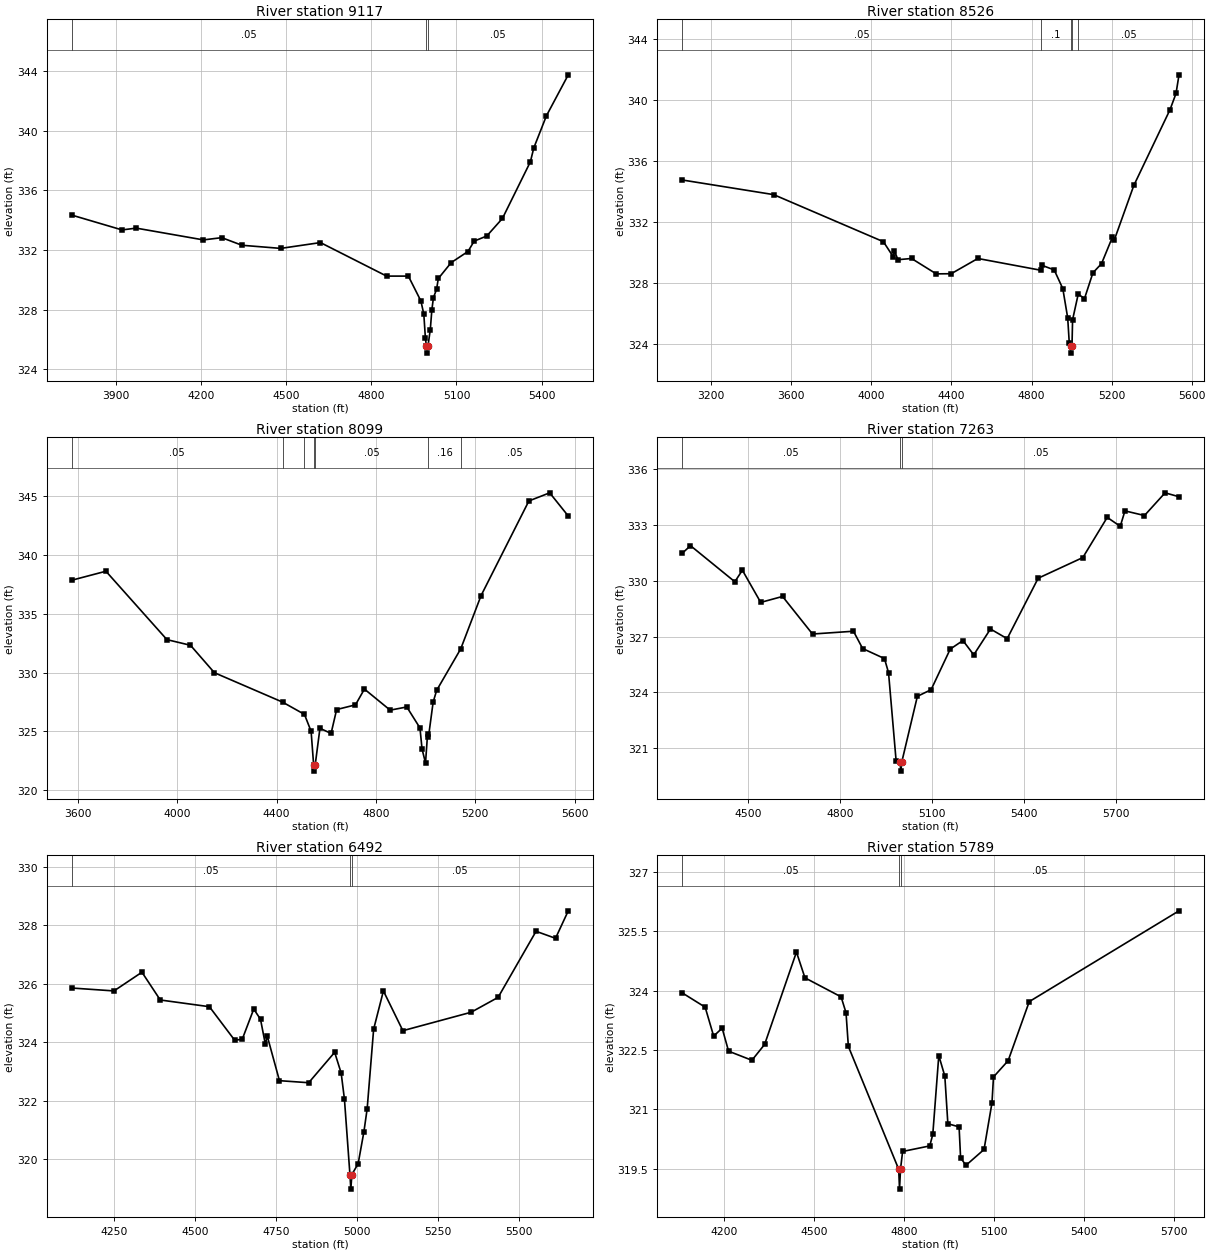
Type RM Length L Ch R = 1 ,9117    ,591,591,591
BEGIN DESCRIPTION:
UNT0412 IN CEDR CR 15.0
END DESCRIPTION:
XS GIS Cut Line= 4
      3611940.87     10339032.01      3611527.66     10338463.35
      3611195.07     10338275.74      3610592.14     10337991.66
#Sta/Elev= 30
  3742.9  334.35    3921  333.35  3971.2  333.47  4207.8  332.68  4272.7  332.83
  4343.8  332.32  4480.4  332.11  4620.5   332.5  4853.8  330.25  4930.5  330.25
  4974.7  328.58    4985  327.69  4990.5  326.09  4993.8  325.58  4996.5  325.08
  4999.8  325.58  5007.8  326.66  5013.3  327.98  5018.9  328.81  5029.9  329.36
  5036.1  330.09  5081.7  331.16  5140.5   331.9  5162.6   332.6  5206.8  332.94
  5262.1  334.12  5360.6  337.92  5372.6  338.85  5417.2  341.01  5494.2  343.76
#Mann= 3 ,-1 , 0
  3742.9     .05       0  4993.8     .03       0  4999.8     .05       0
Bank Sta=4993.8,4999.8
XS Rating Curve= 0 ,0
Exp/Cntr=0.3,0.1

Type RM Length L Ch R = 1 ,8526    ,427,427,427
BEGIN DESCRIPTION:
UNT0412 IN CEDR CR 14.0
END DESCRIPTION:
XS GIS Cut Line= 4
      3612388.77     10339330.59       3611941.7     10338138.05
      3611476.49     10337891.98      3610842.07     10337641.63
#Sta/Elev= 30
    3055  334.74  3511.7  333.78    4060  330.69  4109.8  329.69  4115.1   330.1
  4132.5  329.51  4200.6  329.59    4324  328.58  4398.7  328.59  4531.8  329.59
  4849.6  328.81  4854.5  329.13  4913.3  328.84  4956.4  327.61  4980.8  325.69
  4988.6  324.05  4996.3  323.88  4999.1  323.38  5002.3  323.88  5005.2  325.57
  5033.3  327.25  5064.7  326.96  5106.8  328.65  5149.8  329.25  5203.6  330.97
  5214.3  330.83  5311.1  334.38  5492.2  339.36    5522  340.42  5536.9  341.64
#Mann= 5 ,-1 , 0
    3055     .05       0  4849.6      .1       0  4996.3     .07       0
  5002.3      .1       0  5033.3     .05       0
Bank Sta=4996.3,5002.3
XS Rating Curve= 0 ,0
Exp/Cntr=0.3,0.1

Type RM Length L Ch R = 1 ,8099    ,836,836,836
BEGIN DESCRIPTION:
UNT0412 IN CEDR CR 13.0
END DESCRIPTION:
XS GIS Cut Line= 3
      3612746.46     10338091.06      3611357.99     10337394.33
      3610957.98     10337194.33
#Sta/Elev= 30
    3574  337.84  3712.6  338.61  3958.3   332.8  4053.2  332.32  4149.5  329.99
  4424.3  327.49  4512.2  326.45    4539  325.01  4549.3  322.13    4552  321.63
  4555.3  322.13  4574.6  325.27  4619.4  324.83  4641.8  326.86  4717.7  327.26
  4753.7   328.6  4857.4  326.81  4924.4  327.08  4977.4   325.3  4985.8  323.51
  4999.8  322.32  5008.1   324.8  5011.5   324.5  5030.5  327.49  5044.6  328.49
  5141.7  332.02  5223.5  336.54  5416.1  344.58  5499.9  345.27  5574.7   343.3
#Mann= 7 ,-1 , 0
    3574     .05       0  4424.3     .16       0  4512.2     .05       0
  4549.3     .03       0  4555.3     .05       0  5011.5     .16       0
  5141.7     .05       0
Bank Sta=4549.3,4555.3
XS Rating Curve= 0 ,0
Exp/Cntr=0.3,0.1

Type RM Length L Ch R = 1 ,7263    ,771,771,771
BEGIN DESCRIPTION:
UNT0412 IN CEDR CR 12.0
END DESCRIPTION:
XS GIS Cut Line= 3
      3612747.15     10337448.52      3611675.05     10337033.47
       3611276.1     10336784.12
#Sta/Elev= 30
  4285.8  331.48  4312.7  331.89  4457.3  329.95  4481.9  330.57  4541.7  328.84
  4612.9  329.16  4710.6  327.14  4844.2  327.29  4874.1  326.36  4945.3  325.82
  4958.6  325.06  4983.2  320.34  4995.9  320.27  4998.7  319.77  5001.9  320.27
  5052.6  323.79  5097.5  324.15  5159.8  326.33  5201.2  326.79  5236.5  326.02
    5291  327.41  5345.5  326.89  5446.6  330.14  5592.2  331.25  5671.8  333.41
  5714.3  332.93  5729.6  333.76  5793.3  333.51  5860.5  334.73  5905.9  334.52
#Mann= 3 ,-1 , 0
  4285.8     .05       0  4995.9     .03       0  5001.9     .05       0
Bank Sta=4995.9,5001.9
XS Rating Curve= 0 ,0
Exp/Cntr=0.3,0.1

Type RM Length L Ch R = 1 ,6492    ,703,703,703
BEGIN DESCRIPTION:
UNT0412 IN CEDR CR 11.0
END DESCRIPTION:
XS GIS Cut Line= 3
      3612815.41     10336911.28      3612312.24     10336561.61
      3611392.91     10336476.49
#Sta/Elev= 30
  4117.2  325.86  4248.5  325.76    4335   326.4  4391.7  325.45  4543.6  325.22
  4621.3  324.08  4644.9   324.1  4680.7  325.14  4701.6  324.79  4716.5  323.94
  4722.6  324.21  4760.2  322.69  4850.6  322.62  4930.9  323.66    4951  322.95
  4961.1  322.06  4978.1  319.48  4980.9  318.98  4984.1  319.48  5003.5  319.85
  5021.3  320.94  5031.4  321.73  5051.4  324.45  5081.6  325.76  5141.8   324.4
  5352.7  325.03  5436.3  325.54  5553.6   327.8  5613.8  327.56  5653.2   328.5
#Mann= 3 ,-1 , 0
  4117.2     .05       0  4978.1     .03       0  4984.1     .05       0
Bank Sta=4978.1,4984.1
XS Rating Curve= 0 ,0
Exp/Cntr=0.3,0.1

Type RM Length L Ch R = 1 ,5789    ,735,735,735
BEGIN DESCRIPTION:
UNT0412 IN CEDR CR 10.0
END DESCRIPTION:
XS GIS Cut Line= 3
      3612917.72     10336373.99      3612542.49     10335981.71
      3611435.44     10335879.52
#Sta/Elev= 30
  4061.4  323.94  4137.7  323.58    4166  322.85  4194.3  323.05  4215.7  322.47
  4293.4  322.24  4335.8  322.64  4441.8  324.97  4470.1  324.32  4590.5  323.84
  4606.9  323.44  4614.7  322.59  4782.4  319.49  4785.1  318.99  4788.4  319.49
  4795.4  319.94  4885.8  320.08  4895.9  320.37  4915.9  322.36    4936  321.84
  4946.1  320.64  4983.5  320.56  4988.5  319.78  5006.3  319.59  5066.6  319.99
  5093.1  321.17  5098.1  321.82  5146.9  322.23  5217.2  323.72    5716  326.01
#Mann= 3 ,-1 , 0
  4061.4     .05       0  4782.4     .03       0  4788.4     .05       0
Bank Sta=4782.4,4788.4
XS Rating Curve= 0 ,0
Exp/Cntr=0.3,0.1

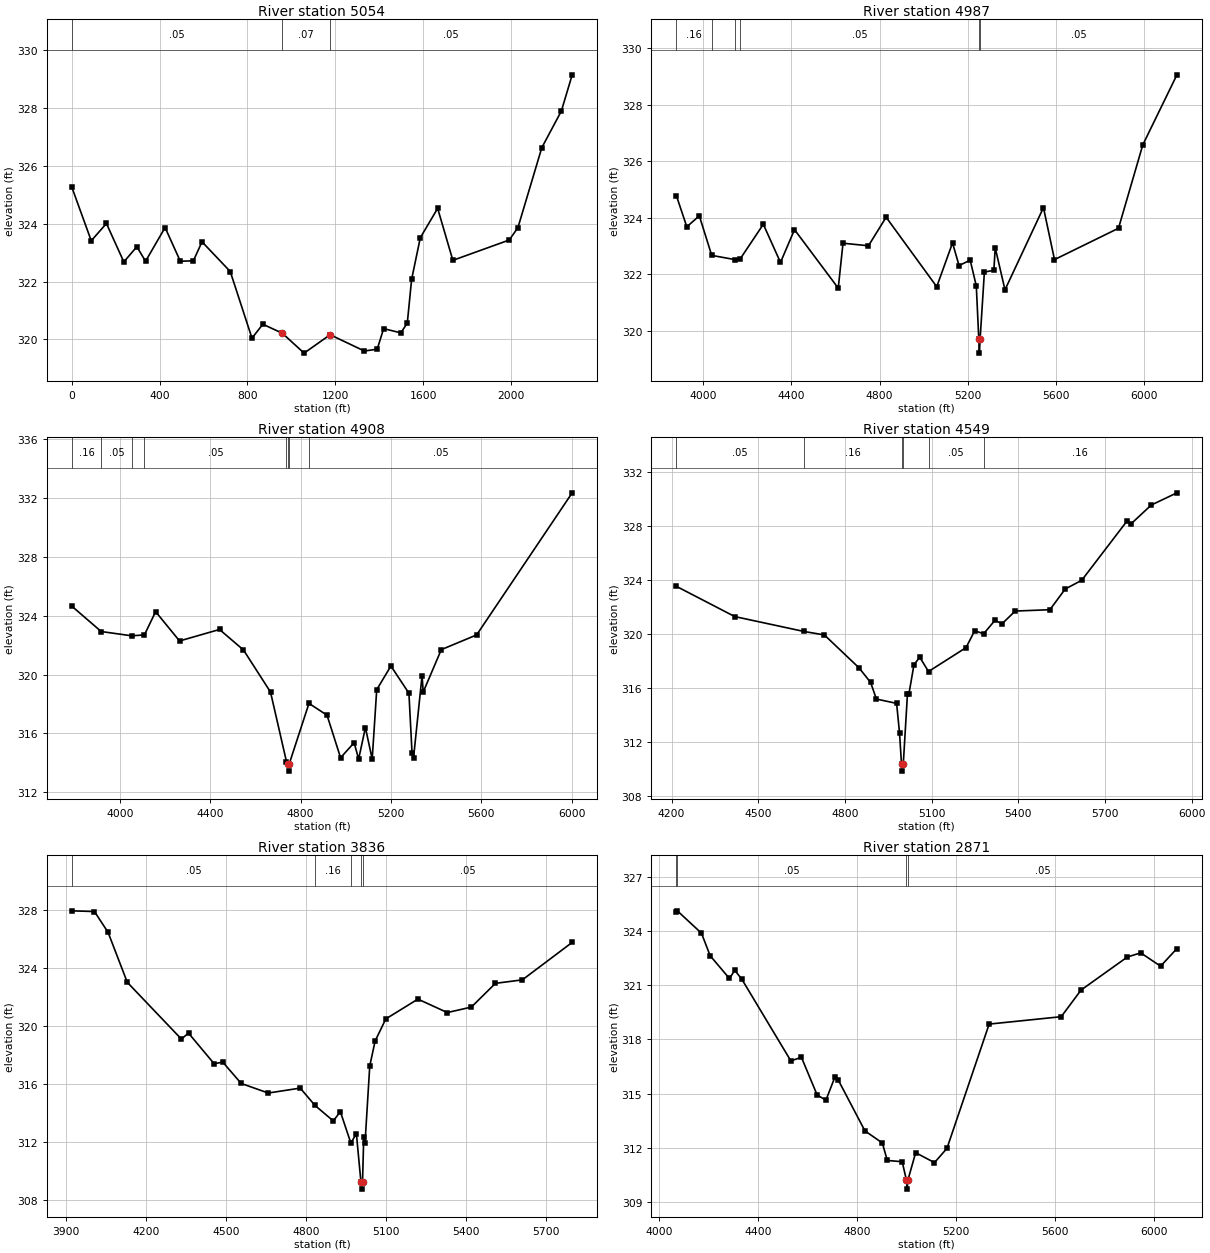
Type RM Length L Ch R = 1 ,5054    ,67,67,67
BEGIN DESCRIPTION:
UNT0412 IN CEDR CR 9.0
END DESCRIPTION:
XS GIS Cut Line= 5
     3613400.406    10335951.502      3612846.32     10335363.98
      3612470.02     10335370.49      3612281.22     10335607.47
      3611480.44     10335597.06
#Sta/Elev= 30
       0325.281188.96812323.4127158.1655324.0102237.2483322.6804296.5604323.2062
336.1018322.7035425.0699323.8697494.2673322.7046553.5794322.7167593.1208323.3767
721.6303322.3467820.4798320.0404869.8864320.5229958.8184320.20981057.632319.5223
1176.208320.15931332.063319.59481390.453319.65931419.648320.37081497.645320.2245
1527.271320.55861547.022322.07471586.524323.51711665.528324.53421734.656322.7347
1991.419 323.4392030.921323.86942139.551326.6359 2228.43327.90262277.807329.1571
#Mann= 3 , 0 , 0
       0     .05       0958.8184     .07       01176.208     .05       0
Bank Sta=958.8184,1176.208
XS Rating Curve= 0 ,0
Exp/Cntr=0.3,0.1

Type RM Length L Ch R = 1 ,4987    ,79,79,79
BEGIN DESCRIPTION:
Mapping XS 869dc23c
END DESCRIPTION:
XS GIS Cut Line= 6
      3613420.55     10335849.67       3612833.3     10335293.67
      3612470.02      10335309.3      3612309.87     10335537.16
      3612153.62     10335573.62       3611497.4     10335571.02
#Sta/Elev= 30
    3880  324.78    3927  323.68  3983.7  324.07  4039.8  322.67    4145  322.52
  4168.4  322.54  4273.7  323.77  4351.4  322.42  4414.9  323.58  4613.1  321.51
  4634.6   323.1    4750  323.01    4830  324.02  5059.3  321.56  5130.8  323.11
  5160.4  322.31  5210.9   322.5  5238.5  321.59  5249.8  319.71  5252.5  319.21
  5255.8  319.71  5275.2  322.08  5318.1  322.14  5324.2  322.94  5368.5  321.45
  5542.8  324.36  5592.8  322.52  5882.8  323.63  5992.8  326.58  6147.5  329.06
#Mann= 6 ,-1 , 0
    3880     .16       0  4039.8     .05       0    4145     .16       0
  4168.4     .05       0  5249.8    .033       0  5255.8     .05       0
Bank Sta=5249.8,5255.8
XS Rating Curve= 0 ,0
Exp/Cntr=0.3,0.1

Type RM Length L Ch R = 1 ,4908    ,359,359,359
BEGIN DESCRIPTION:
Mapping XS 2edb77a1
END DESCRIPTION:
XS GIS Cut Line= 4
      3613464.89     10335823.87      3612830.74     10335226.18
      3612321.62      10335240.5      3611505.51     10335415.94
#Sta/Elev= 30
  3787.1  324.65  3917.8  322.92  4052.7  322.63    4109  322.69  4158.6  324.27
  4264.6  322.28  4441.4  323.06  4547.4  321.67  4667.2  318.81  4737.9  314.08
  4744.2  313.94  4746.9  313.44  4750.2  313.94  4837.4  318.04  4917.3  317.24
  4977.3  314.35  5037.3  315.37  5057.3  314.26  5087.3   316.4  5117.3  314.25
  5137.3  318.97  5200.1  320.58  5279.9  318.73  5293.7  314.66  5300.3  314.34
    5338  319.93  5343.1  318.81  5423.1  321.69  5579.6  322.69  6002.6  332.34
#Mann= 8 ,-1 , 0
  3787.1     .16       0  3917.8     .05       0  4052.7     .16       0
    4109     .05       0  4737.9     .16       0  4744.2     .03       0
  4750.2     .16       0  4837.4     .05       0
Bank Sta=4744.2,4750.2
XS Rating Curve= 0 ,0
Exp/Cntr=0.3,0.1

Type RM Length L Ch R = 1 ,4549    ,713,713,713
BEGIN DESCRIPTION:
UNT0412 IN CEDR CR 8.0
END DESCRIPTION:
XS GIS Cut Line= 3
       3613344.1      10334941.3      3612542.11     10334941.64
      3611612.99     10334898.66
#Sta/Elev= 30
    4217  323.53    4419  321.29  4657.9  320.19    4729  319.93    4849  317.49
    4889  316.41    4909  315.18    4979  314.86    4989  312.68    4996  310.34
  4998.7  309.84    5002  310.34  5016.5  315.55  5021.5  315.55    5039  317.72
    5059  318.28  5089.4  317.22  5219.2  318.99  5249.2  320.24  5280.2  320.02
  5319.3  321.01    5344  320.76  5389.4   321.7  5509.5   321.8  5562.3  323.33
  5619.6  323.98  5775.6  328.35  5789.8  328.15  5859.9  329.55  5949.1  330.46
#Mann= 6 ,-1 , 0
    4217     .05       0  4657.9     .16       0    4996     .07       0
    5002     .16       0  5089.4     .05       0  5280.2     .16       0
Bank Sta=4996,5002
XS Rating Curve= 0 ,0
Exp/Cntr=0.3,0.1

Type RM Length L Ch R = 1 ,3836    ,965,965,965
BEGIN DESCRIPTION:
UNT0412 IN CEDR CR 6.0
END DESCRIPTION:
XS GIS Cut Line= 3
       3613392.1     10334641.64      3612653.36     10334404.03
      3611555.16     10334310.39
#Sta/Elev= 30
  3921.1  327.96  4006.6  327.91  4057.7  326.47  4129.7  323.02  4332.7   319.1
  4359.5  319.51  4455.8  317.39  4487.9  317.51  4557.3  316.03  4658.8  315.37
  4778.7  315.71  4834.3  314.51    4903  313.44  4929.2  314.09  4968.7  311.91
  4989.4  312.57  5006.5  309.23  5009.2  308.73  5012.5  309.23    5017  312.32
    5022  311.95  5039.6  317.24  5059.7  318.96  5099.8  320.49  5220.3  321.86
  5330.7  320.93    5421  321.31  5511.3  322.95  5612.3  323.19  5799.3  325.78
#Mann= 5 ,-1 , 0
  3921.1     .05       0  4834.3     .16       0  4968.7     .05       0
  5006.5     .03       0  5012.5     .05       0
Bank Sta=5006.5,5012.5
XS Rating Curve= 0 ,0
Exp/Cntr=0.3,0.1

Type RM Length L Ch R = 1 ,2871    ,801,801,801
BEGIN DESCRIPTION:
UNT0412 IN CEDR CR 5.0
END DESCRIPTION:
XS GIS Cut Line= 3
      3613480.57     10334335.81      3612924.09     10333834.28
      3611656.37     10333730.39
#Sta/Elev= 30
  4069.8  325.08  4073.4  325.13  4170.9  323.89    4206  322.64  4283.8  321.38
  4305.4  321.83  4333.8  321.34  4531.9  316.81  4574.5  317.01    4638  314.92
  4673.5  314.63    4709  315.89  4723.2  315.75    4831  312.93  4901.2  312.26
  4921.3  311.29  4981.5  311.22  4998.5   310.2  5001.3   309.7  5004.5   310.2
  5035.8  311.72  5111.9  311.17  5162.2  311.96  5332.6  318.85  5623.6  319.26
  5703.9  320.74  5890.7  322.57  5944.7   322.8  6024.9  322.06  6090.9  323.04
#Mann= 4 ,-1 , 0
  4069.8     .16       0  4073.4     .05       0  4998.5     .03       0
  5004.5     .05       0
Bank Sta=4998.5,5004.5
XS Rating Curve= 0 ,0
Exp/Cntr=0.3,0.1

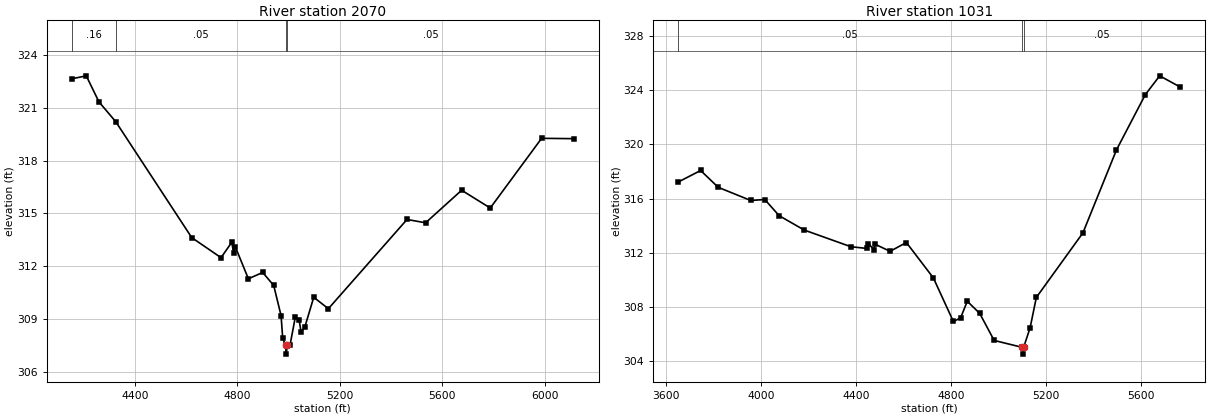
Type RM Length L Ch R = 1 ,2070    ,1039,1039,1039
BEGIN DESCRIPTION:
UNT0412 IN CEDR CR 3.0
END DESCRIPTION:
XS GIS Cut Line= 3
      3613592.11     10334041.64      3612909.09     10333220.62
      3612030.83     10333065.14
#Sta/Elev= 30
  4154.1  322.65  4210.7  322.82  4260.2  321.34    4326  320.21  4622.4  313.63
  4736.7  312.49  4778.5  313.36  4786.2  312.76  4792.7   313.1  4843.5  311.29
  4899.4  311.65  4942.4  310.91  4971.1   309.2  4977.6   307.9  4988.9  307.51
  4991.6  307.01  4994.9  307.51  5006.2  307.53    5027  309.14  5041.4  308.97
  5049.2  308.27  5063.5  308.53  5098.6  310.24  5155.7  309.59  5462.8  314.66
  5535.3  314.47    5676  316.32  5787.7  315.31  5988.2  319.27    6114  319.25
#Mann= 4 ,-1 , 0
  4154.1     .16       0    4326     .05       0  4988.9     .03       0
  4994.9     .05       0
Bank Sta=4988.9,4994.9
XS Rating Curve= 0 ,0
Exp/Cntr=0.3,0.1

Type RM Length L Ch R = 1 ,1031    ,0,0,0
BEGIN DESCRIPTION:
UNT0412 IN CEDR CR 1.0
END DESCRIPTION:
XS GIS Cut Line= 3
      3613787.58     10333551.24       3613334.7      10332588.2
      3612296.14     10332442.73
#Sta/Elev= 30
  3650.8  317.22  3745.1  318.07    3819  316.83  3955.8  315.86    4015  315.93
  4075.3  314.74  4180.8  313.68  4377.3  312.45  4445.7  312.32  4451.2  312.68
    4474  312.23  4479.5  312.63  4542.4  312.11  4610.8  312.76  4724.5  310.15
  4808.5  306.94  4838.8  307.19  4867.2  308.43  4919.6  307.53  4980.2  305.54
  5098.3  305.03  5101.1  304.53  5104.3  305.03  5131.6  306.47  5157.8  308.71
  5353.8  313.47  5495.1  319.59  5616.3  323.66  5676.9  325.05  5763.7  324.22
#Mann= 3 ,-1 , 0
  3650.8     .05       0  5098.3     .03       0  5104.3     .05       0
Bank Sta=5098.3,5104.3
XS Rating Curve= 0 ,0
Exp/Cntr=0.3,0.1

Chan Stop Cuts=-1
Use User Specified Reach Order=0
Composite Channel Slope=5