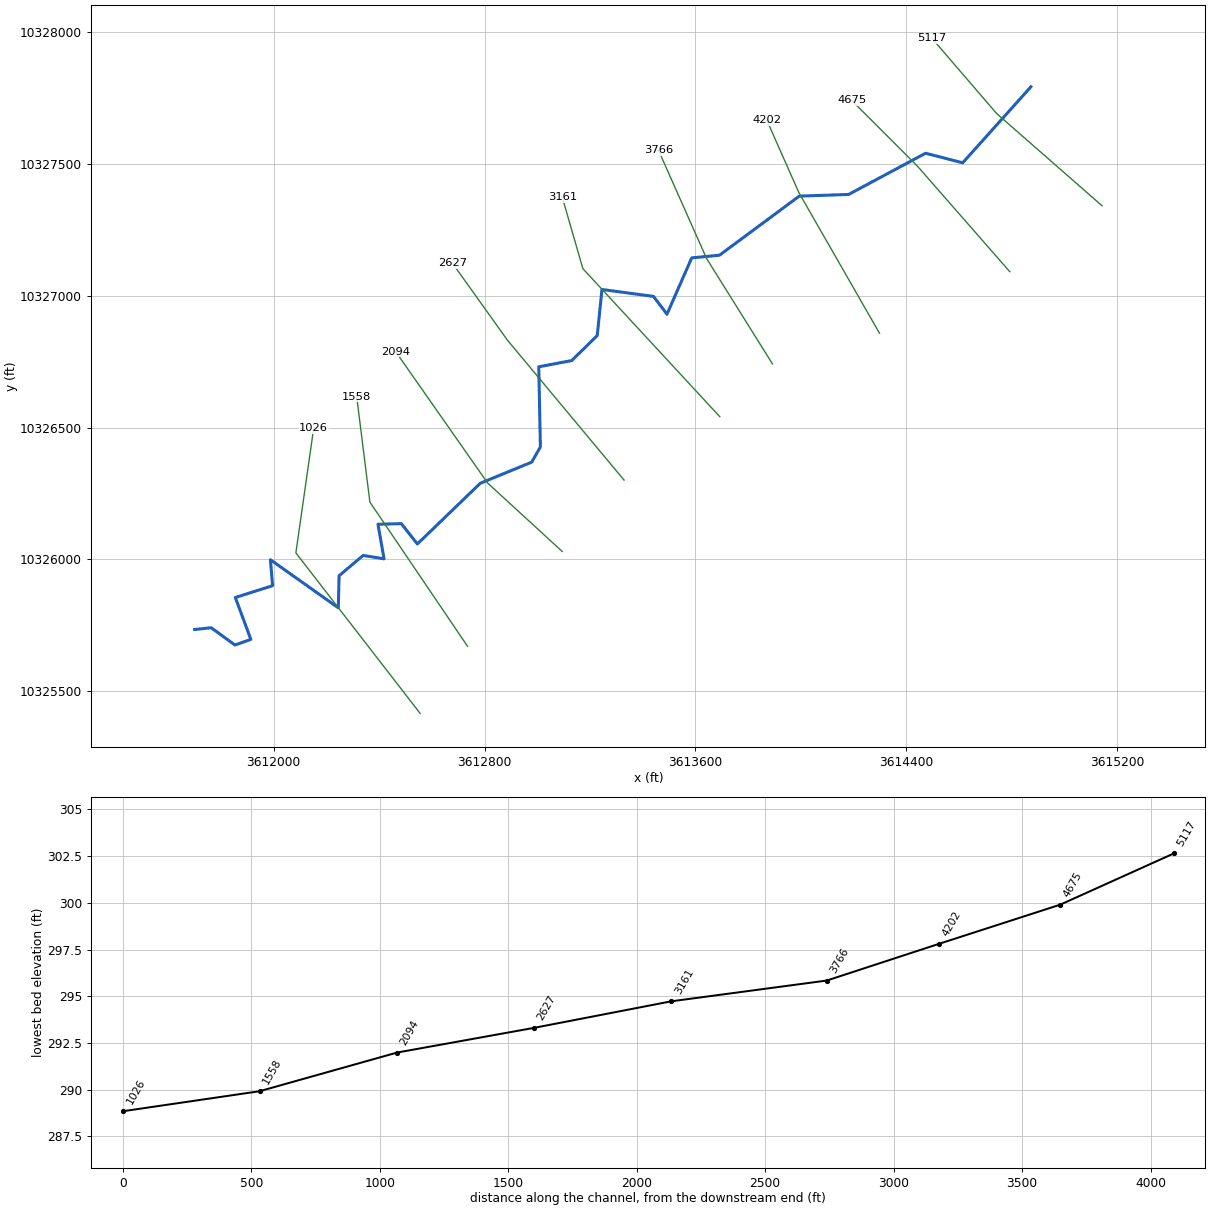
--- UNT0414 IN CEDR CR.prj (project) ---

Proj Title=UNT0414 IN CEDR CR Base Level Engineering
Current Plan=p01
Default Exp/Contr=0.3,0.1
English Units
Geom File=g01
Flow File=f01
Plan File=p01
BEGIN DESCRIPTION:
UNT0414 IN CEDR CR
END DESCRIPTION:

--- UNT0414 IN CEDR CR.p01 (plan) ---

Plan Title=Multiple Run
Short Identifier=Multiple
Geom File=g01
Flow File=f01
Subcritical Flow
K Sum by GR= 0
Std Step Tol= 0.01
Critical Tol= 0.01
Num of Std Step Trials= 20
Max Error Tol= 0.3
Flow Tol Ratio= 0.001
Split Flow NTrial= 30
Split Flow Tol= 0.02
Split Flow Ratio= 0.02
Log Output Level= 0
Friction Slope Method= 1
Unsteady Friction Slope Method= 2
Unsteady Bridges Friction Slope Method= 1
Parabolic Critical Depth
Global Vel Dist=  1 , 1 , 1
Global Log Level= 0
CheckData=True
Encroach Param= -1, 0, 0, 0
BEGIN DESCRIPTION:
Multiple Run
END DESCRIPTION:

--- UNT0414 IN CEDR CR.f01 (steady flow) ---

Flow Title=Multiple
Number of Profiles=7
Profile Names=10-year,25-year,50-year,1pct_min,100-year,1pct_plu,500-year
River Rch & RM= UNT0414 IN CEDR ,Reach-1,5117
     657     884    1069     946    1280    1731    1838
Boundary for River Rch & Prof#=UNT0414 IN CEDR ,Reach-1,1
Up Type=0
Dn Type=3
Dn Slope=0.005
Boundary for River Rch & Prof#=UNT0414 IN CEDR ,Reach-1,2
Up Type=0
Dn Type=3
Dn Slope=0.005
Boundary for River Rch & Prof#=UNT0414 IN CEDR ,Reach-1,3
Up Type=0
Dn Type=3
Dn Slope=0.005
Boundary for River Rch & Prof#=UNT0414 IN CEDR ,Reach-1,4
Up Type=0
Dn Type=3
Dn Slope=0.005
Boundary for River Rch & Prof#=UNT0414 IN CEDR ,Reach-1,5
Up Type=0
Dn Type=3
Dn Slope=0.005
Boundary for River Rch & Prof#=UNT0414 IN CEDR ,Reach-1,6
Up Type=0
Dn Type=3
Dn Slope=0.005
Boundary for River Rch & Prof#=UNT0414 IN CEDR ,Reach-1,7
Up Type=0
Dn Type=3
Dn Slope=0.005

--- UNT0414 IN CEDR CR.g01 (geometry) ---

Geom Title=Existing Conditions

River Reach=UNT0414 IN CEDR ,Reach-1
Reach XY= 30
      3614872.28     10327792.77      3614613.63     10327504.61
      3614472.69     10327540.80      3614180.95     10327384.51
      3613993.64     10327378.15      3613691.04     10327153.97
      3613585.73     10327143.95      3613491.88     10326930.26
      3613440.79     10326997.80      3613245.24     10327024.03
      3613227.42     10326849.17      3613130.73     10326754.45
      3613005.64     10326730.78      3613011.76     10326426.67
      3612978.73     10326369.08      3612783.78     10326289.00
      3612545.04     10326058.70      3612484.42     10326135.80
      3612395.67     10326133.57      3612418.73     10326002.47
      3612339.35     10326015.23      3612248.23     10325938.27
      3612245.24     10325816.65      3611987.70     10325999.04
      3611996.05     10325900.47      3611854.63     10325855.76
      3611913.62     10325696.73      3611853.13     10325675.46
      3611763.03     10325741.09      3611700.39     10325734.26

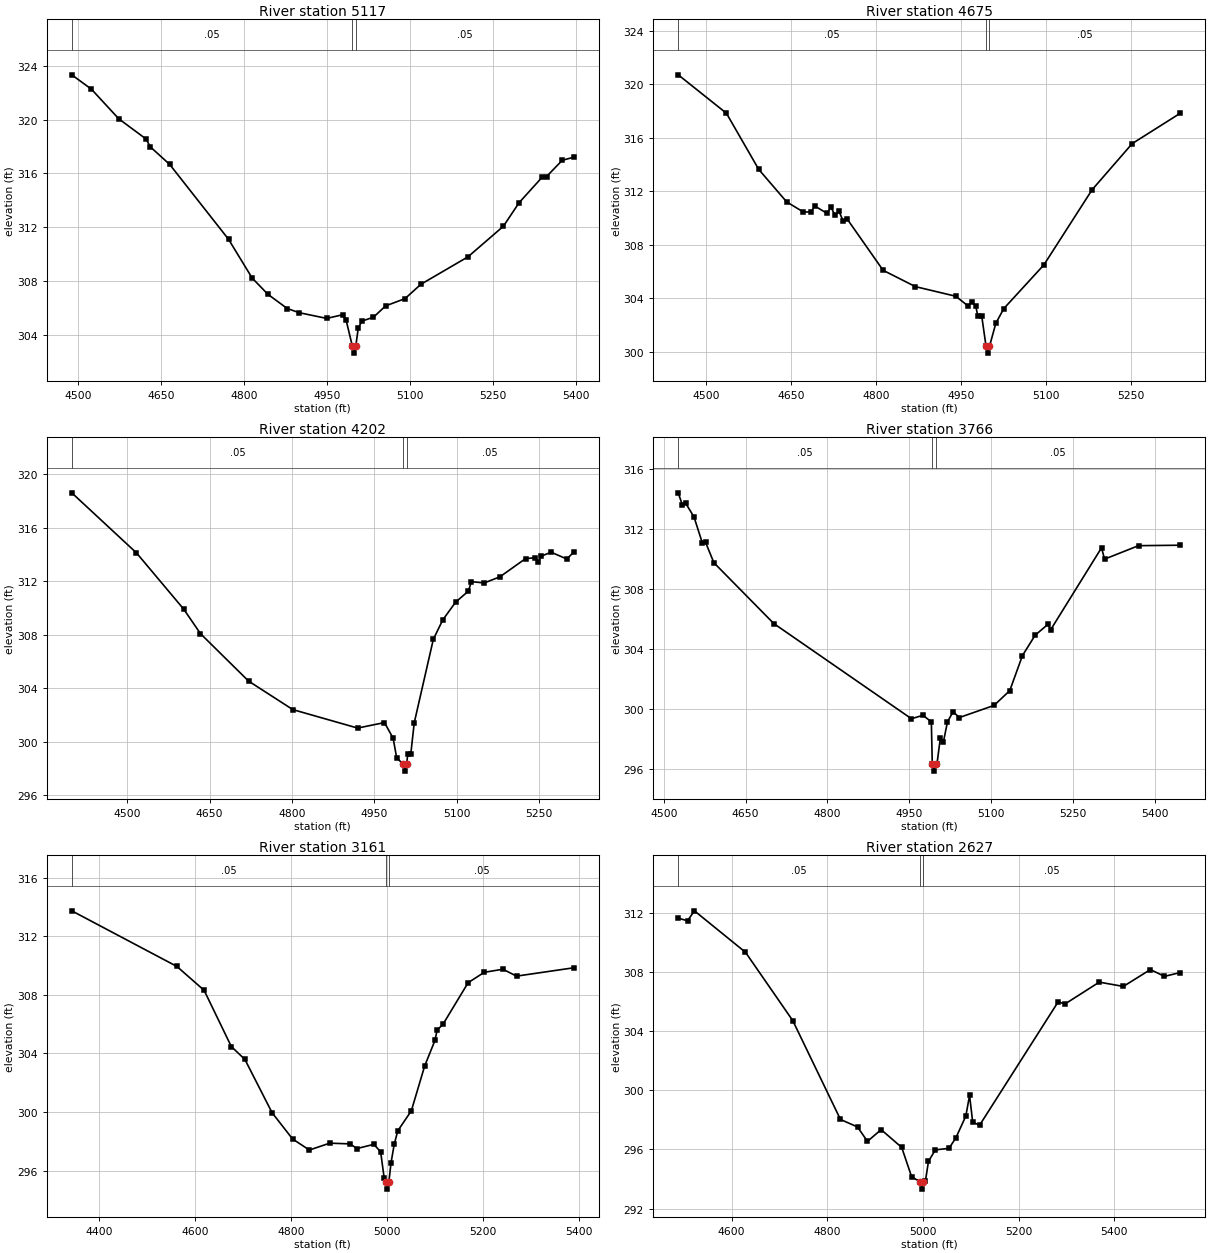
Type RM Length L Ch R = 1,5117,442,442,442
BEGIN DESCRIPTION:
UNT0414 IN CEDR CR 10.0
END DESCRIPTION:
XS GIS Cut Line= 3
      3615142.12     10327341.63      3614742.11     10327691.64
      3614497.04     10327976.64
#Sta/Elev= 30
  4488.7  323.32  4524.3  322.25  4573.7  320.05  4623.0  318.55  4630.6  317.97
  4665.7  316.66  4772.0  311.10  4814.7  308.22  4843.2  307.01  4878.3  305.95
  4900.2  305.64  4949.5  305.22  4978.0  305.49  4984.6  305.08  4995.9  303.14
  4998.6  302.64  5001.9  303.14  5006.5  304.51  5013.1  305.02  5034.0  305.31
  5055.9  306.15  5091.0  306.69  5119.5  307.75  5204.9  309.80  5268.8  312.07
  5297.2  313.82  5339.0  315.72  5346.7  315.76  5375.2  316.97  5396.1  317.20
#Mann=3,-1,0
  4488.7    0.05       0  4995.9    0.03       0  5001.9    0.05       0
Bank Sta=4995.9,5001.9
Exp/Cntr=0.3,0.1

Type RM Length L Ch R = 1,4675,473,473,473
BEGIN DESCRIPTION:
UNT0414 IN CEDR CR 9.0
END DESCRIPTION:
XS GIS Cut Line= 3
      3614792.09     10327091.66      3614442.11     10327491.64
      3614192.13     10327741.61
#Sta/Elev= 30
  4451.6  320.70  4536.5  317.83  4593.5  313.63  4642.8  311.20  4671.3  310.47
  4685.5  310.43  4692.2  310.90  4714.0  310.34  4720.7  310.81  4728.2  310.19
  4734.9  310.51  4742.5  309.75  4749.1  309.94  4812.7  306.09  4869.7  304.87
  4940.9  304.15  4961.7  303.45  4969.3  303.70  4976.0  303.41  4979.8  302.66
  4986.6  302.66  4994.2  300.40  4997.0  299.90  5000.2  300.40  5011.4  302.13
  5025.5  303.23  5096.2  306.50  5181.1  312.11  5251.8  315.56  5336.6  317.83
#Mann=3,-1,0
  4451.6    0.05       0  4994.2    0.03       0  5000.2    0.05       0
Bank Sta=4994.2,5000.2
Exp/Cntr=0.3,0.1

Type RM Length L Ch R = 1,4202,436,436,436
BEGIN DESCRIPTION:
UNT0414 IN CEDR CR 8.0
END DESCRIPTION:
XS GIS Cut Line= 3
      3614297.88     10326858.28      3613992.11     10327391.64
      3613870.78     10327665.58
#Sta/Elev= 30
  4398.9  318.61  4516.7  314.12  4603.0  309.90  4633.3  308.08  4721.0  304.53
  4801.5  302.40  4919.5  301.02  4968.4  301.43  4984.2  300.26  4990.6  298.80
  5002.8  298.30  5005.5  297.80  5008.8  298.30  5010.8  299.11  5016.4  299.11
  5022.6  301.41  5057.4  307.66  5074.6  309.11  5097.9  310.43  5121.2  311.26
  5126.7  311.97  5150.0  311.87  5178.7  312.33  5225.3  313.69  5243.1  313.76
  5248.6  313.45  5254.3  313.88  5271.9  314.17  5300.6  313.66  5313.3  314.19
#Mann=3,-1,0
  4398.9    0.05       0  5002.8    0.03       0  5008.8    0.05       0
Bank Sta=5002.8,5008.8
Exp/Cntr=0.3,0.1

Type RM Length L Ch R = 1,3766,605,605,605
BEGIN DESCRIPTION:
UNT0414 IN CEDR CR 7.0
END DESCRIPTION:
XS GIS Cut Line= 3
      3613892.09     10326741.67      3613642.11     10327141.64
      3613459.83     10327551.68
#Sta/Elev= 30
  4526.6  314.43  4534.2  313.61  4540.1  313.74  4555.5  312.82  4570.8  311.08
  4576.7  311.12  4592.0  309.76  4701.7  305.70  4954.1  299.34  4975.3  299.57
  4990.6  299.13  4992.3  296.34  4995.1  295.84  4998.3  296.34  5001.0  296.34
  5007.2  298.08  5012.6  297.77  5020.2  299.14  5030.4  299.80  5042.0  299.42
  5105.6  300.23  5134.4  301.22  5157.6  303.56  5180.9  304.92  5204.1  305.64
  5209.6  305.30  5302.6  310.76  5308.1  310.00  5370.4  310.90  5447.0  310.93
#Mann=3,-1,0
  4526.6    0.05       0  4992.3    0.03       0  4998.3    0.05       0
Bank Sta=4992.3,4998.3
Exp/Cntr=0.3,0.1

Type RM Length L Ch R = 1,3161,534,534,534
BEGIN DESCRIPTION:
UNT0414 IN CEDR CR 6.0
END DESCRIPTION:
XS GIS Cut Line= 3
      3613692.14     10326541.61      3613172.86     10327103.10
      3613094.73     10327373.95
#Sta/Elev= 30
  4342.5  313.74  4561.7  309.94  4618.4  308.31  4675.1  304.47  4703.4  303.59
  4760.1  299.95  4802.7  298.16  4837.8  297.40  4880.3  297.87  4922.9  297.82
  4937.0  297.50  4972.2  297.79  4986.4  297.28  4993.7  295.51  4997.6  295.23
  5000.3  294.73  5003.6  295.23  5007.9  296.49  5014.7  297.79  5022.1  298.71
  5050.4  300.08  5078.2  303.14  5099.8  304.90  5104.2  305.60  5116.2  305.98
  5168.8  308.83  5202.4  309.54  5241.3  309.75  5269.7  309.28  5389.2  309.85
#Mann=3,-1,0
  4342.5    0.05       0  4997.6    0.03       0  5003.6    0.05       0
Bank Sta=4997.6,5003.6
Exp/Cntr=0.3,0.1

Type RM Length L Ch R = 1,2627,533,533,533
BEGIN DESCRIPTION:
UNT0414 IN CEDR CR 5.0
END DESCRIPTION:
XS GIS Cut Line= 3
      3613329.08     10326301.05      3612886.40     10326832.27
      3612678.08     10327123.92
#Sta/Elev= 30
  4488.4  311.62  4507.9  311.45  4522.2  312.12  4629.0  309.32  4727.9  304.70
  4827.6  298.02  4863.3  297.51  4884.1  296.54  4912.7  297.33  4955.7  296.13
  4976.5  294.14  4994.3  293.81  4997.1  293.31  5000.3  293.81  5005.2  293.84
  5011.7  295.19  5026.0  295.96  5054.6  296.07  5068.9  296.77  5089.8  298.25
  5097.6  299.65  5104.1  297.85  5118.4  297.62  5282.7  305.96  5297.5  305.83
  5368.8  307.30  5419.2  307.01  5475.7  308.15  5505.2  307.69  5538.3  307.95
#Mann=3,-1,0
  4488.4    0.05       0  4994.3    0.03       0  5000.3    0.05       0
Bank Sta=4994.3,5000.3
Exp/Cntr=0.3,0.1

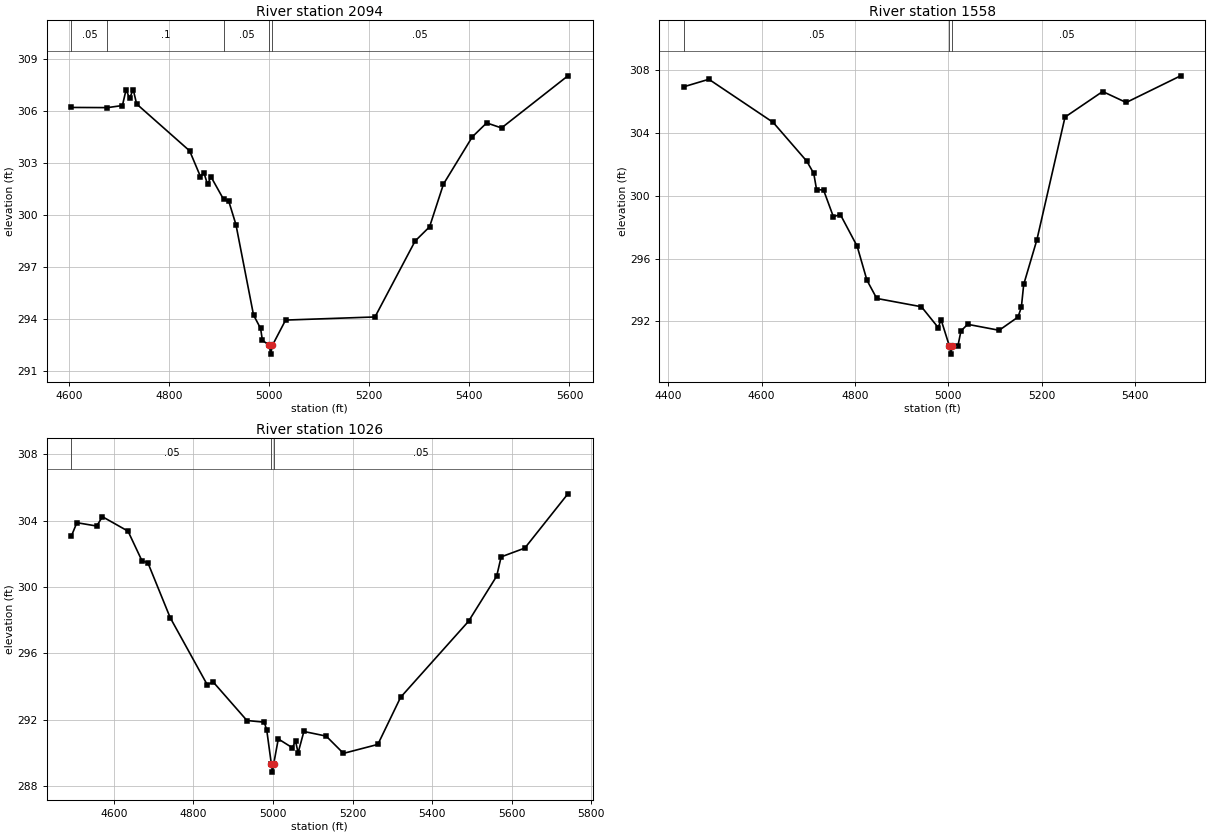
Type RM Length L Ch R = 1,2094,536,536,536
BEGIN DESCRIPTION:
UNT0414 IN CEDR CR 4.0
END DESCRIPTION:
XS GIS Cut Line= 3
      3613094.71     10326030.21      3612811.90     10326289.56
      3612462.90     10326788.12
#Sta/Elev= 30
  4604.6  306.19  4676.5  306.18  4706.4  306.30  4713.8  307.22  4720.6  306.71
  4728.0  307.22  4734.8  306.39  4840.8  303.69  4862.4  302.21  4869.2  302.44
  4876.6  301.76  4883.4  302.20  4908.6  300.90  4919.1  300.78  4933.3  299.45
  4968.5  294.24  4982.6  293.47  4986.2  292.79  5000.1  292.49  5002.8  291.99
  5006.1  292.49  5032.6  293.95  5211.3  294.13  5291.5  298.50  5320.4  299.32
  5348.2  301.78  5405.9  304.50  5434.5  305.30  5464.2  305.01  5596.9  308.01
#Mann=5,-1,0
  4604.6    0.05       0  4676.5     0.1       0  4908.6    0.05       0
  5000.1    0.03       0  5006.1    0.05       0
Bank Sta=5000.1,5006.1
Exp/Cntr=0.3,0.1

Type RM Length L Ch R = 1,1558,532,532,532
BEGIN DESCRIPTION:
UNT0414 IN CEDR CR 2.0
END DESCRIPTION:
XS GIS Cut Line= 3
      3612735.36     10325670.82      3612365.02     10326217.68
      3612315.08     10326617.21
#Sta/Elev= 30
  4434.3  306.97  4487.2  307.44  4624.9  304.69  4696.8  302.22  4711.8  301.44
  4717.8  300.41  4732.8  300.38  4753.8  298.68  4768.7  298.82  4804.7  296.80
  4825.7  294.63  4846.7  293.47  4942.4  292.94  4978.4  291.61  4984.4  292.12
  5002.4  290.42  5005.2  289.92  5008.4  290.42  5020.4  290.43  5027.1  291.40
  5041.4  291.82  5108.8  291.44  5149.1  292.28  5156.4  292.91  5161.4  294.36
  5189.5  297.19  5249.9  305.03  5330.5  306.66  5380.9  305.96  5497.4  307.66
#Mann=3,-1,0
  4434.3    0.05       0  5002.4    0.03       0  5008.4    0.05       0
Bank Sta=5002.4,5008.4
Exp/Cntr=0.3,0.1

Type RM Length L Ch R = 1,1026,0,0,0
BEGIN DESCRIPTION:
UNT0414 IN CEDR CR 1.0
END DESCRIPTION:
XS GIS Cut Line= 3
      3612555.60     10325416.21      3612084.32     10326024.98
      3612151.86     10326497.80
#Sta/Elev= 30
  4493.4  303.09  4506.9  303.88  4556.7  303.68  4571.2  304.24  4635.5  303.37
  4670.8  301.57  4685.3  301.47  4741.4  298.16  4834.7  294.11  4849.2  294.29
  4934.3  291.96  4977.8  291.86  4984.1  291.38  4995.6  289.35  4998.3  288.85
  5001.6  289.35  5013.1  290.85  5048.4  290.32  5056.5  290.72  5062.9  290.01
  5077.4  291.30  5133.5  291.02  5176.9  289.98  5263.3  290.52  5320.5  293.36
  5491.2  297.94  5561.9  300.66  5573.1  301.82  5632.6  302.35  5740.9  305.62
#Mann=3,-1,0
  4493.4    0.05       0  4995.6    0.03       0  5001.6    0.05       0
Bank Sta=4995.6,5001.6
Exp/Cntr=0.3,0.1

Chan Stop Cuts=-1