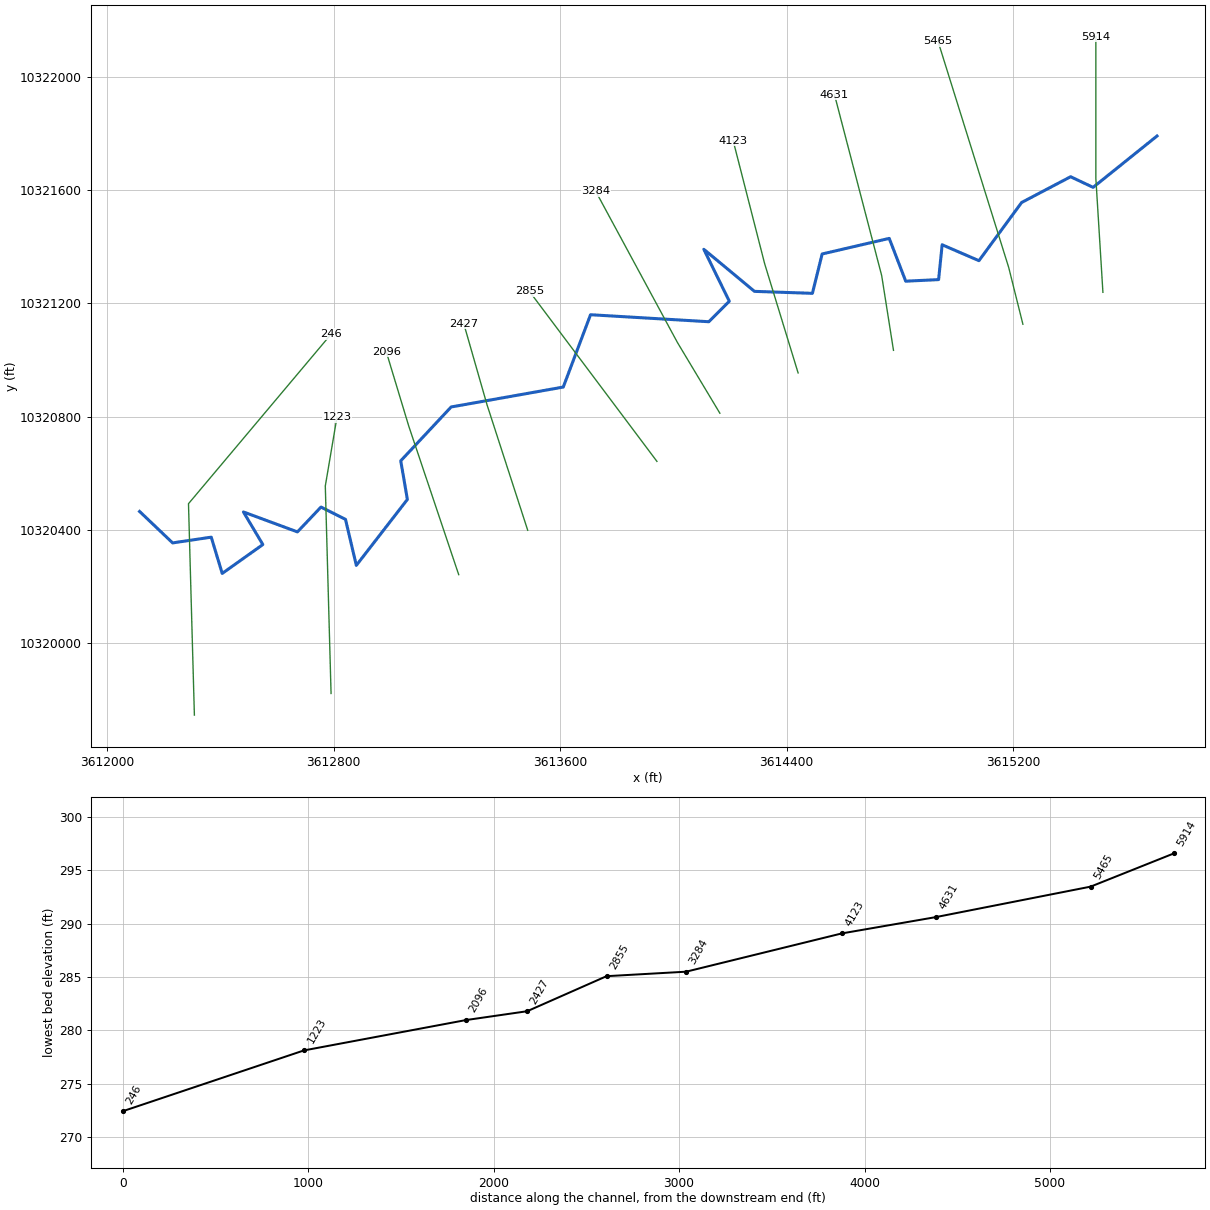
--- UNT0415 IN CEDR CR.prj (project) ---

Proj Title=UNT0415 IN CEDR CR Base Level Engineering
Current Plan=p01
Default Exp/Contr=0.3,0.1
English Units
Geom File=g01
Flow File=f01
Plan File=p01
BEGIN DESCRIPTION:
UNT0415 IN CEDR CR
END DESCRIPTION:

--- UNT0415 IN CEDR CR.p01 (plan) ---

Plan Title=Multiple Run
Short Identifier=Multiple
Geom File=g01
Flow File=f01
Subcritical Flow
K Sum by GR= 0
Std Step Tol= 0.01
Critical Tol= 0.01
Num of Std Step Trials= 20
Max Error Tol= 0.3
Flow Tol Ratio= 0.001
Split Flow NTrial= 30
Split Flow Tol= 0.02
Split Flow Ratio= 0.02
Log Output Level= 0
Friction Slope Method= 1
Unsteady Friction Slope Method= 2
Unsteady Bridges Friction Slope Method= 1
Parabolic Critical Depth
Global Vel Dist=  1 , 1 , 1
Global Log Level= 0
CheckData=True
Encroach Param= -1, 0, 0, 0
BEGIN DESCRIPTION:
Multiple Run
END DESCRIPTION:

--- UNT0415 IN CEDR CR.f01 (steady flow) ---

Flow Title=Multiple
Number of Profiles=7
Profile Names=10-year,25-year,50-year,1pct_min,100-year,1pct_plu,500-year
River Rch & RM= UNT0415 IN CEDR ,Reach-1,5914
     638     858    1037     919    1242    1680    1785
Boundary for River Rch & Prof#=UNT0415 IN CEDR ,Reach-1,1
Up Type=0
Dn Type=3
Dn Slope=0.005
Boundary for River Rch & Prof#=UNT0415 IN CEDR ,Reach-1,2
Up Type=0
Dn Type=3
Dn Slope=0.005
Boundary for River Rch & Prof#=UNT0415 IN CEDR ,Reach-1,3
Up Type=0
Dn Type=3
Dn Slope=0.005
Boundary for River Rch & Prof#=UNT0415 IN CEDR ,Reach-1,4
Up Type=0
Dn Type=3
Dn Slope=0.005
Boundary for River Rch & Prof#=UNT0415 IN CEDR ,Reach-1,5
Up Type=0
Dn Type=3
Dn Slope=0.005
Boundary for River Rch & Prof#=UNT0415 IN CEDR ,Reach-1,6
Up Type=0
Dn Type=3
Dn Slope=0.005
Boundary for River Rch & Prof#=UNT0415 IN CEDR ,Reach-1,7
Up Type=0
Dn Type=3
Dn Slope=0.005

--- UNT0415 IN CEDR CR.g01 (geometry) ---

Geom Title=Existing Conditions

River Reach=UNT0415 IN CEDR ,Reach-1
Reach XY= 30
      3615708.06     10321790.58      3615482.40     10321609.30
      3615402.99     10321646.82      3615229.99     10321555.87
      3615079.25     10321350.36      3614949.32     10321406.58
      3614936.85     10321283.55      3614820.68     10321277.94
      3614762.50     10321429.09      3614525.58     10321374.06
      3614491.19     10321235.05      3614286.57     10321242.05
      3614107.71     10321390.61      3614197.73     10321207.20
      3614125.35     10321134.80      3613707.70     10321159.54
      3613611.38     10320904.08      3613215.50     10320833.78
      3613037.49     10320643.65      3613060.87     10320507.21
      3612880.58     10320274.41      3612842.34     10320436.77
      3612755.85     10320480.38      3612672.71     10320392.65
      3612481.96     10320463.01      3612550.51     10320347.90
      3612407.04     10320245.93      3612368.25     10320374.00
      3612231.94     10320353.74      3612115.19     10320464.86

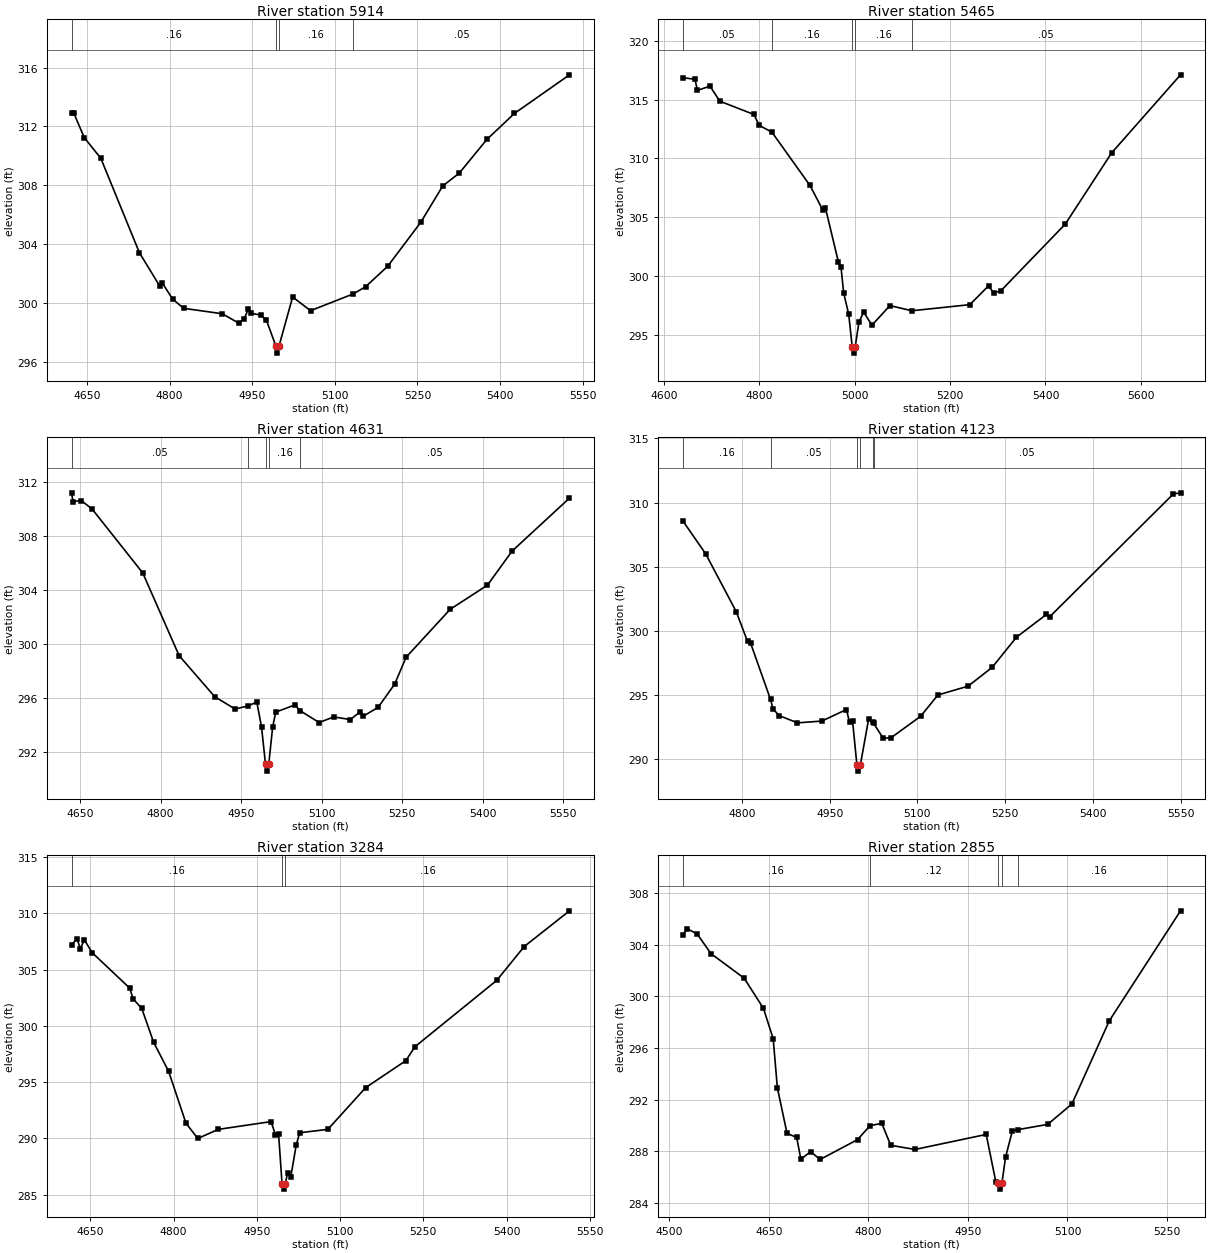
Type RM Length L Ch R = 1,5914,449,449,449
BEGIN DESCRIPTION:
UNT0415 IN CEDR CR 10.0
END DESCRIPTION:
XS GIS Cut Line= 3
      3615517.07     10321238.64      3615492.11     10321641.64
      3615492.11     10322141.66
#Sta/Elev= 30
  4622.2  312.91  4626.2  312.91  4645.2  311.24  4675.3  309.83  4745.4  303.40
  4782.0  301.15  4787.0  301.34  4805.6  300.25  4825.6  299.62  4895.7  299.25
  4925.8  298.61  4935.8  298.91  4943.0  299.58  4948.0  299.28  4965.9  299.16
  4975.9  298.81  4992.9  297.07  4995.7  296.57  4998.9  297.07  5023.5  300.39
  5056.0  299.46  5133.5  300.60  5156.0  301.09  5196.0  302.48  5256.0  305.47
  5296.0  307.95  5326.0  308.82  5376.0  311.11  5426.0  312.88  5526.0  315.51
#Mann=4,-1,0
  4622.2    0.16       0  4992.9    0.07       0  4998.9    0.16       0
  5133.5    0.05       0
Bank Sta=4992.9,4998.9
Exp/Cntr=0.3,0.1

Type RM Length L Ch R = 1,5465,834,834,834
BEGIN DESCRIPTION:
UNT0415 IN CEDR CR 9.0
END DESCRIPTION:
XS GIS Cut Line= 3
      3615234.51     10321125.95      3615184.50     10321325.98
      3614934.51     10322125.94
#Sta/Elev= 30
  4638.9  316.87  4664.8  316.73  4670.0  315.79  4696.3  316.15  4716.9  314.87
  4788.5  313.74  4799.4  312.82  4826.2  312.24  4906.0  307.71  4933.3  305.59
  4938.5  305.79  4965.7  301.20  4971.0  300.81  4976.7  298.57  4987.2  296.78
  4994.7  293.96  4997.4  293.46  5000.7  293.96  5008.7  296.09  5018.6  296.96
  5035.9  295.83  5073.7  297.50  5119.8  297.06  5241.3  297.58  5280.6  299.18
  5291.0  298.58  5306.2  298.75  5441.4  304.42  5538.8  310.48  5683.2  317.11
#Mann=5,-1,0
  4638.9    0.05       0  4826.2    0.16       0  4994.7    0.07       0
  5000.7    0.16       0  5119.8    0.05       0
Bank Sta=4994.7,5000.7
Exp/Cntr=0.3,0.1

Type RM Length L Ch R = 1,4631,508,508,508
BEGIN DESCRIPTION:
UNT0415 IN CEDR CR 8.0
END DESCRIPTION:
XS GIS Cut Line= 3
      3614777.49     10321033.77      3614735.82     10321297.70
      3614569.15     10321936.62
#Sta/Elev= 30
  4634.0  311.18  4636.7  310.53  4652.1  310.61  4672.3  309.98  4766.6  305.26
  4834.3  299.15  4900.7  296.11  4938.6  295.20  4963.4  295.44  4979.1  295.72
  4987.9  293.86  4995.3  291.11  4998.0  290.61  5001.3  291.11  5008.6  293.88
  5014.4  294.97  5049.7  295.50  5060.0  295.07  5095.3  294.20  5122.3  294.62
  5153.3  294.42  5171.1  294.98  5176.3  294.65  5205.0  295.32  5236.0  297.05
  5257.2  299.03  5339.3  302.57  5408.8  304.36  5454.5  306.87  5561.5  310.79
#Mann=5,-1,0
  4634.0    0.05       0  4963.4    0.16       0  4995.3    0.07       0
  5001.3    0.16       0  5060.0    0.05       0
Bank Sta=4995.3,5001.3
Exp/Cntr=0.3,0.1

Type RM Length L Ch R = 1,4123,839,839,839
BEGIN DESCRIPTION:
UNT0415 IN CEDR CR 7.0
END DESCRIPTION:
XS GIS Cut Line= 3
      3614440.68     10320953.95      3614322.63     10321339.37
      3614211.52     10321773.38
#Sta/Elev= 30
  4698.7  308.60  4738.1  306.01  4790.4  301.50  4809.7  299.18  4815.0  299.04
  4849.0  294.66  4853.2  293.93  4863.6  293.41  4895.0  292.84  4936.8  292.98
  4978.7  293.88  4984.0  292.90  4989.2  293.00  4996.6  289.58  4999.3  289.08
  5002.6  289.58  5016.7  293.14  5023.5  292.90  5025.1  292.81  5041.4  291.65
  5054.7  291.67  5105.5  293.35  5135.1  295.01  5186.7  295.70  5228.0  297.17
  5269.3  299.51  5320.7  301.29  5325.9  301.09  5537.7  310.68  5549.8  310.76
#Mann=6,-1,0
  4698.7    0.16       0  4849.0    0.05       0  4996.6    0.03       0
  5002.6    0.05       0  5023.5    0.16       0  5025.1    0.05       0
Bank Sta=4996.6,5002.6
Exp/Cntr=0.3,0.1

Type RM Length L Ch R = 1,3284,429,429,429
BEGIN DESCRIPTION:
UNT0415 IN CEDR CR 6.0
END DESCRIPTION:
XS GIS Cut Line= 3
      3614164.32     10320811.80      3614014.33     10321061.78
      3613726.24     10321594.77
#Sta/Elev= 30
  4616.0  307.20  4625.8  307.77  4631.7  306.86  4639.1  307.66  4653.0  306.52
  4720.8  303.36  4726.9  302.41  4742.5  301.56  4763.8  298.56  4791.0  295.96
  4822.1  291.37  4843.5  290.00  4880.5  290.81  4975.6  291.50  4983.5  290.32
  4989.2  290.36  4995.3  286.00  4998.1  285.50  5001.3  286.00  5005.4  286.93
  5011.1  286.58  5021.0  289.45  5027.3  290.51  5077.9  290.81  5146.1  294.52
  5218.6  296.92  5234.8  298.15  5382.3  304.05  5431.7  307.05  5513.4  310.23
#Mann=3,-1,0
  4616.0    0.16       0  4995.3    0.07       0  5001.3    0.16       0
Bank Sta=4995.3,5001.3
Exp/Cntr=0.3,0.1

Type RM Length L Ch R = 1,2855,428,428,428
BEGIN DESCRIPTION:
UNT0415 IN CEDR CR 5.0
END DESCRIPTION:
XS GIS Cut Line= 3
      3613942.09     10320641.67      3613642.11     10321041.64
      3613492.09     10321241.67
#Sta/Elev= 30
  4520.3  304.74  4527.6  305.21  4542.1  304.83  4563.0  303.30  4613.0  301.40
  4642.1  299.06  4656.7  296.72  4663.0  292.93  4677.6  289.39  4692.1  289.08
  4698.4  287.40  4713.0  287.97  4727.6  287.38  4783.8  288.91  4802.7  289.99
  4820.3  290.17  4833.8  288.47  4870.3  288.15  4977.6  289.31  4992.1  285.64
  4995.4  285.58  4998.1  285.08  5001.4  285.58  5006.7  287.54  5017.1  289.60
  5025.2  289.68  5070.3  290.09  5106.7  291.67  5163.0  298.10  5270.3  306.61
#Mann=5,-1,0
  4520.3    0.16       0  4802.7    0.12       0  4995.4    0.07       0
  5001.4    0.12       0  5025.2    0.16       0
Bank Sta=4995.4,5001.4
Exp/Cntr=0.3,0.1

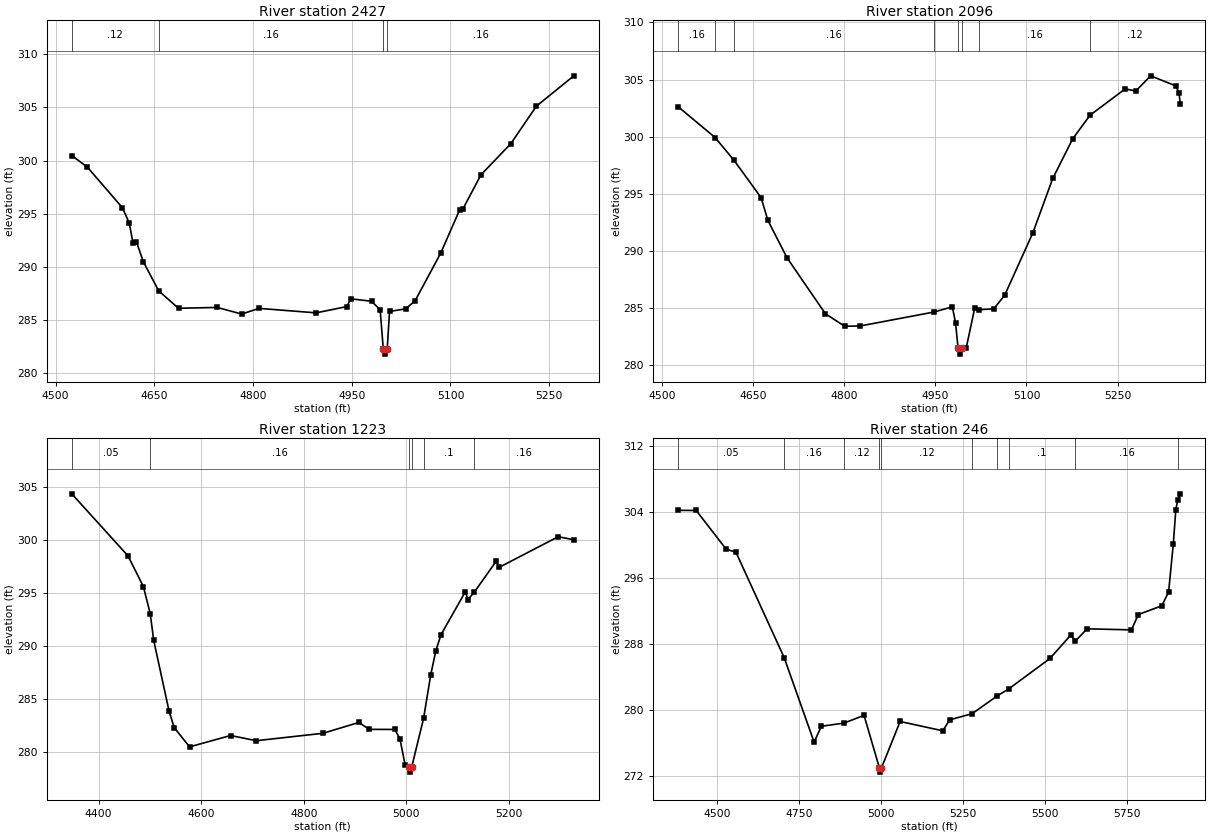
Type RM Length L Ch R = 1,2427,331,331,331
BEGIN DESCRIPTION:
UNT0415 IN CEDR CR 4.0
END DESCRIPTION:
XS GIS Cut Line= 3
      3613485.83     10320398.37      3613342.11     10320841.64
      3613260.25     10321127.14
#Sta/Elev= 30
  4524.5  300.47  4548.3  299.37  4601.5  295.56  4612.0  294.10  4617.5  292.23
  4622.7  292.38  4633.1  290.50  4656.7  287.74  4686.7  286.11  4745.4  286.19
  4782.6  285.57  4809.3  286.10  4895.9  285.68  4942.5  286.27  4948.4  287.00
  4980.0  286.77  4993.1  285.98  4997.9  282.30  5000.6  281.80  5003.9  282.30
  5007.4  285.81  5032.1  286.06  5046.3  286.82  5085.3  291.31  5113.8  295.34
  5119.0  295.46  5146.5  298.67  5191.7  301.58  5230.6  305.11  5287.5  307.96
#Mann=4,-1,0
  4524.5    0.12       0  4656.7    0.16       0  4997.9    0.07       0
  5003.9    0.16       0
Bank Sta=4997.9,5003.9
Exp/Cntr=0.3,0.1

Type RM Length L Ch R = 1,2096,873,873,873
BEGIN DESCRIPTION:
UNT0415 IN CEDR CR 3.0
END DESCRIPTION:
XS GIS Cut Line= 3
      3613242.10     10320241.65      3613065.68     10320766.45
      3612986.39     10321028.45
#Sta/Elev= 30
  4526.1  302.62  4586.8  299.93  4617.7  297.96  4662.6  294.67  4673.8  292.68
  4705.4  289.40  4768.7  284.50  4800.4  283.41  4825.5  283.43  4948.0  284.66
  4977.8  285.11  4983.1  283.71  4987.3  281.47  4990.0  280.97  4993.3  281.47
  5000.8  281.54  5014.6  284.98  5021.9  284.86  5046.1  284.93  5064.1  286.13
  5110.3  291.56  5143.3  296.35  5176.2  299.82  5204.9  301.89  5262.8  304.19
  5280.2  304.00  5304.6  305.33  5346.1  304.45  5351.3  303.83  5353.5  302.87
#Mann=8,-1,0
  4526.1    0.16       0  4586.8    0.12       0  4617.7    0.16       0
  4948.0    0.12       0  4987.3    0.07       0  4993.3    0.12       0
  5021.9    0.16       0  5204.9    0.12       0
Bank Sta=4987.3,4993.3
Exp/Cntr=0.3,0.1

Type RM Length L Ch R = 1,1223,977,977,977
BEGIN DESCRIPTION:
UNT0415 IN CEDR CR 2.0
END DESCRIPTION:
XS GIS Cut Line= 3
      3612791.38     10319822.02      3612771.05     10320554.81
      3612812.12     10320797.18
#Sta/Elev= 30
  4347.8  304.35  4457.5  298.50  4487.5  295.60  4500.8  293.06  4507.5  290.56
  4537.5  283.88  4547.5  282.32  4577.5  280.51  4657.5  281.58  4707.6  281.09
  4837.6  281.79  4907.6  282.81  4927.6  282.16  4977.7  282.15  4987.7  281.25
  4997.7  278.81  5004.7  278.63  5007.4  278.13  5010.7  278.63  5033.7  283.19
  5047.7  287.31  5057.7  289.58  5067.7  291.08  5115.1  295.12  5120.2  294.38
  5132.9  295.11  5175.5  298.01  5180.6  297.41  5296.2  300.31  5326.7  300.02
#Mann=6,-1,0
  4347.8    0.05       0  4500.8    0.16       0  5004.7    0.07       0
  5010.7    0.16       0  5033.7     0.1       0  5132.9    0.16       0
Bank Sta=5004.7,5010.7
Exp/Cntr=0.3,0.1

Type RM Length L Ch R = 1,246,0,0,0
BEGIN DESCRIPTION:
UNT0415 IN CEDR CR 1.0
END DESCRIPTION:
XS GIS Cut Line= 3
      3612308.74     10319745.66      3612287.91     10320492.14
      3612792.10     10321091.64
#Sta/Elev= 30
  4382.7  304.19  4437.5  304.17  4528.7  299.48  4558.7  299.10  4705.5  286.33
  4796.8  276.07  4818.8  278.00  4888.3  278.39  4948.9  279.33  4995.9  272.94
  4998.7  272.44  5001.9  272.94  5058.9  278.58  5189.0  277.45  5209.8  278.78
  5278.4  279.53  5355.1  281.69  5390.2  282.54  5515.5  286.22  5579.2  289.07
  5593.2  288.34  5628.6  289.82  5763.9  289.69  5784.7  291.55  5856.2  292.61
  5877.1  294.28  5891.4  300.09  5899.1  304.27  5905.1  305.48  5912.8  306.19
#Mann=10,-1,0
  4382.7    0.05       0  4705.5    0.16       0  4888.3    0.12       0
  4995.9    0.07       0  5001.9    0.12       0  5278.4     0.1       0
  5355.1    0.12       0  5390.2     0.1       0  5593.2    0.16       0
  5905.1    0.12       0
Bank Sta=4995.9,5001.9
Exp/Cntr=0.3,0.1

Chan Stop Cuts=-1