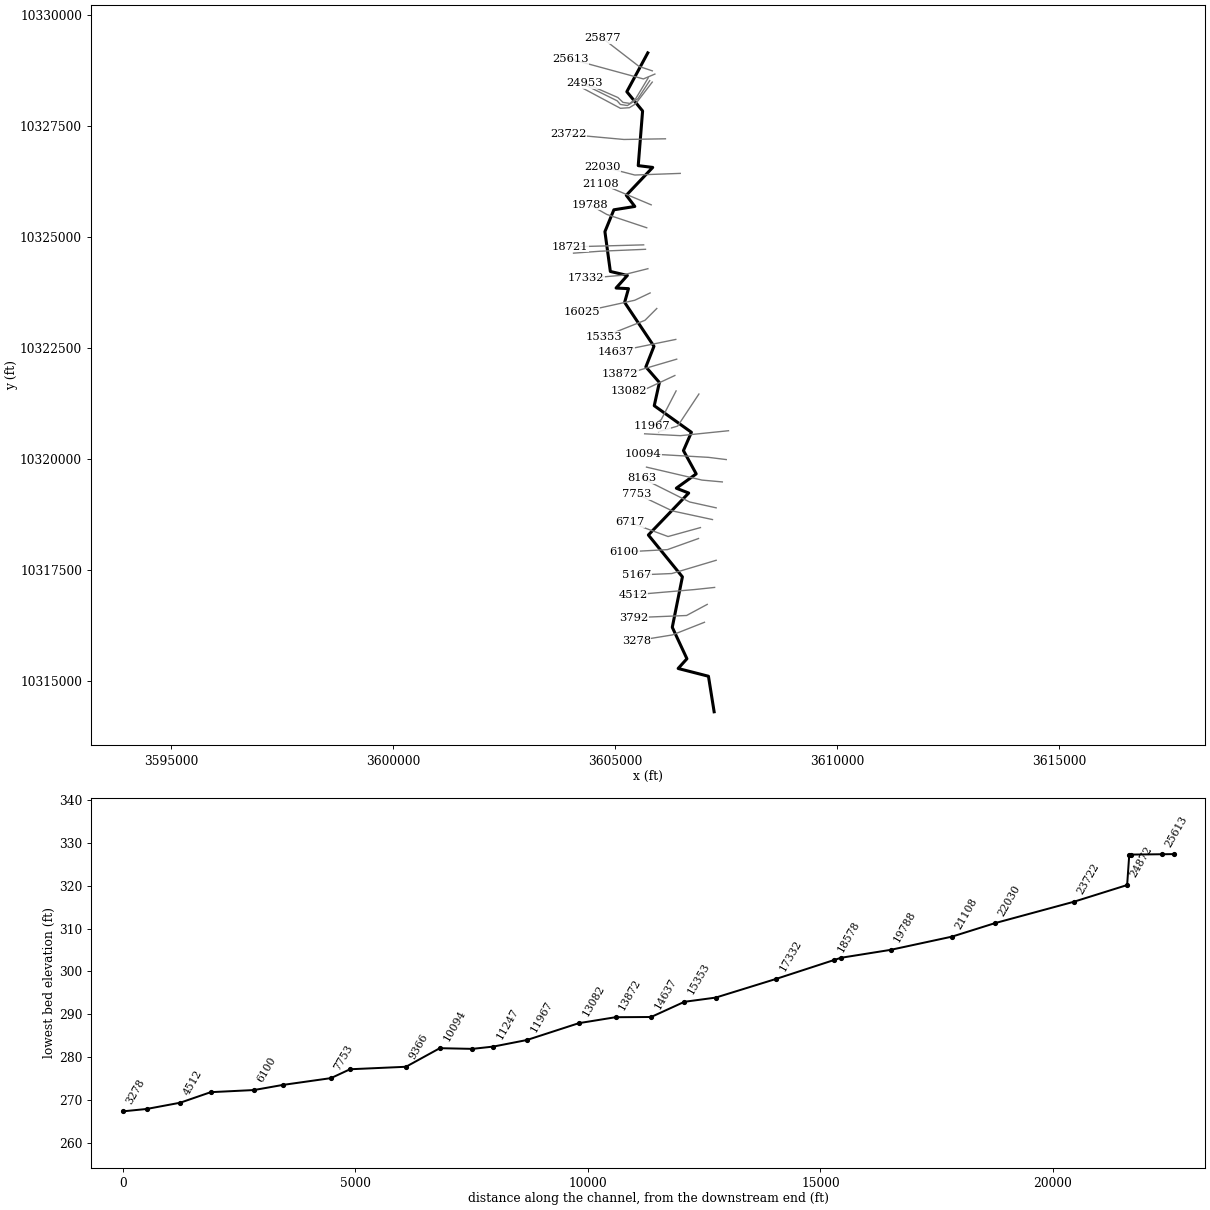
--- UNT0416 IN CEDR CR.prj (project) ---

Proj Title=UNT0416 IN CEDR CR Base Level Engineering
Current Plan=p01
Default Exp/Contr=0.3,0.1
English Units
Geom File=g01
Flow File=f01
Plan File=p01
Y Axis Title=Elevation
X Axis Title(PF)=Main Channel Distance
X Axis Title(XS)=Station
BEGIN DESCRIPTION:
UNT0416 IN CEDR CR
END DESCRIPTION:
DSS Export Rating Curves= 0
DSS Export Rating Curve Sorted= 0
DSS Export Volume Flow Curves= 0
DXF OffsetX= 0
DXF OffsetY= 0
DXF ScaleX= 1
DXF ScaleY= 10

--- UNT0416 IN CEDR CR.p01 (plan) ---

Plan Title=Multiple Run
Short Identifier=Multiple
Geom File=g01
Flow File=f01
Subcritical Flow
K Sum by GR= 0
Std Step Tol= 0.01
Critical Tol= 0.01
Num of Std Step Trials= 20
Max Error Tol= 0.3
Flow Tol Ratio= 0.001
Split Flow NTrial= 30
Split Flow Tol= 0.02
Split Flow Ratio= 0.02
Log Output Level= 0
Friction Slope Method= 1
Unsteady Friction Slope Method= 2
Unsteady Bridges Friction Slope Method= 1
Parabolic Critical Depth
Global Vel Dist=  1 , 1 , 1
Global Log Level= 0
CheckData=True
Encroach Param= -1, 0, 0, 0
BEGIN DESCRIPTION:
Multiple Run
END DESCRIPTION:

--- UNT0416 IN CEDR CR.f01 (steady flow) ---

Flow Title=Multiple
Number of Profiles=7
Profile Names=10-year,25-year,50-year,1pct_min,100-year,1pct_plu,500-year
River Rch & RM= UNT0416 IN CEDR ,Reach-1,25877
     539     718     863     760    1027    1389    1459
River Rch & RM= UNT0416 IN CEDR ,Reach-1,24953
     808    1096    1332    1184    1601    2166    2319
River Rch & RM= UNT0416 IN CEDR ,Reach-1,11247
     969    1323    1614    1439    1945    2631    2835
Boundary for River Rch & Prof#=UNT0416 IN CEDR ,Reach-1,1
Up Type=0
Dn Type=3
Dn Slope=0.005
Boundary for River Rch & Prof#=UNT0416 IN CEDR ,Reach-1,2
Up Type=0
Dn Type=3
Dn Slope=0.005
Boundary for River Rch & Prof#=UNT0416 IN CEDR ,Reach-1,3
Up Type=0
Dn Type=3
Dn Slope=0.005
Boundary for River Rch & Prof#=UNT0416 IN CEDR ,Reach-1,4
Up Type=0
Dn Type=3
Dn Slope=0.005
Boundary for River Rch & Prof#=UNT0416 IN CEDR ,Reach-1,5
Up Type=0
Dn Type=3
Dn Slope=0.005
Boundary for River Rch & Prof#=UNT0416 IN CEDR ,Reach-1,6
Up Type=0
Dn Type=3
Dn Slope=0.005
Boundary for River Rch & Prof#=UNT0416 IN CEDR ,Reach-1,7
Up Type=0
Dn Type=3
Dn Slope=0.005

--- UNT0416 IN CEDR CR.g01 (geometry) ---

Geom Title=Existing Conditions
Program Version=4.10

River Reach=UNT0416 IN CEDR ,Reach-1
Reach XY= 30
      3605739.73     10329146.36      3605267.56     10328272.14
      3605622.78      10327838.8      3605524.29     10326607.59
      3605850.72     10326567.57      3605255.34     10325940.18
       3605447.6     10325688.72      3604975.64     10325613.52
      3604774.01     10325121.54      3604896.24     10324225.16
      3605280.23     10324135.63      3605025.11     10323852.28
       3605304.7     10323838.21      3605218.05     10323528.79
      3605878.61      10322540.2      3605696.12     10322076.95
       3606000.7     10321726.03      3605885.21     10321203.07
      3606722.59     10320604.43       3606542.9     10320192.27
      3606830.42     10319668.25       3606382.4     10319345.59
      3606661.17     10319237.03       3605752.5     10318292.01
      3606519.36     10317349.81      3606291.37     10316214.26
      3606621.13     10315506.19      3606423.37     10315287.14
      3607106.05     10315112.28      3607234.05     10314312.26

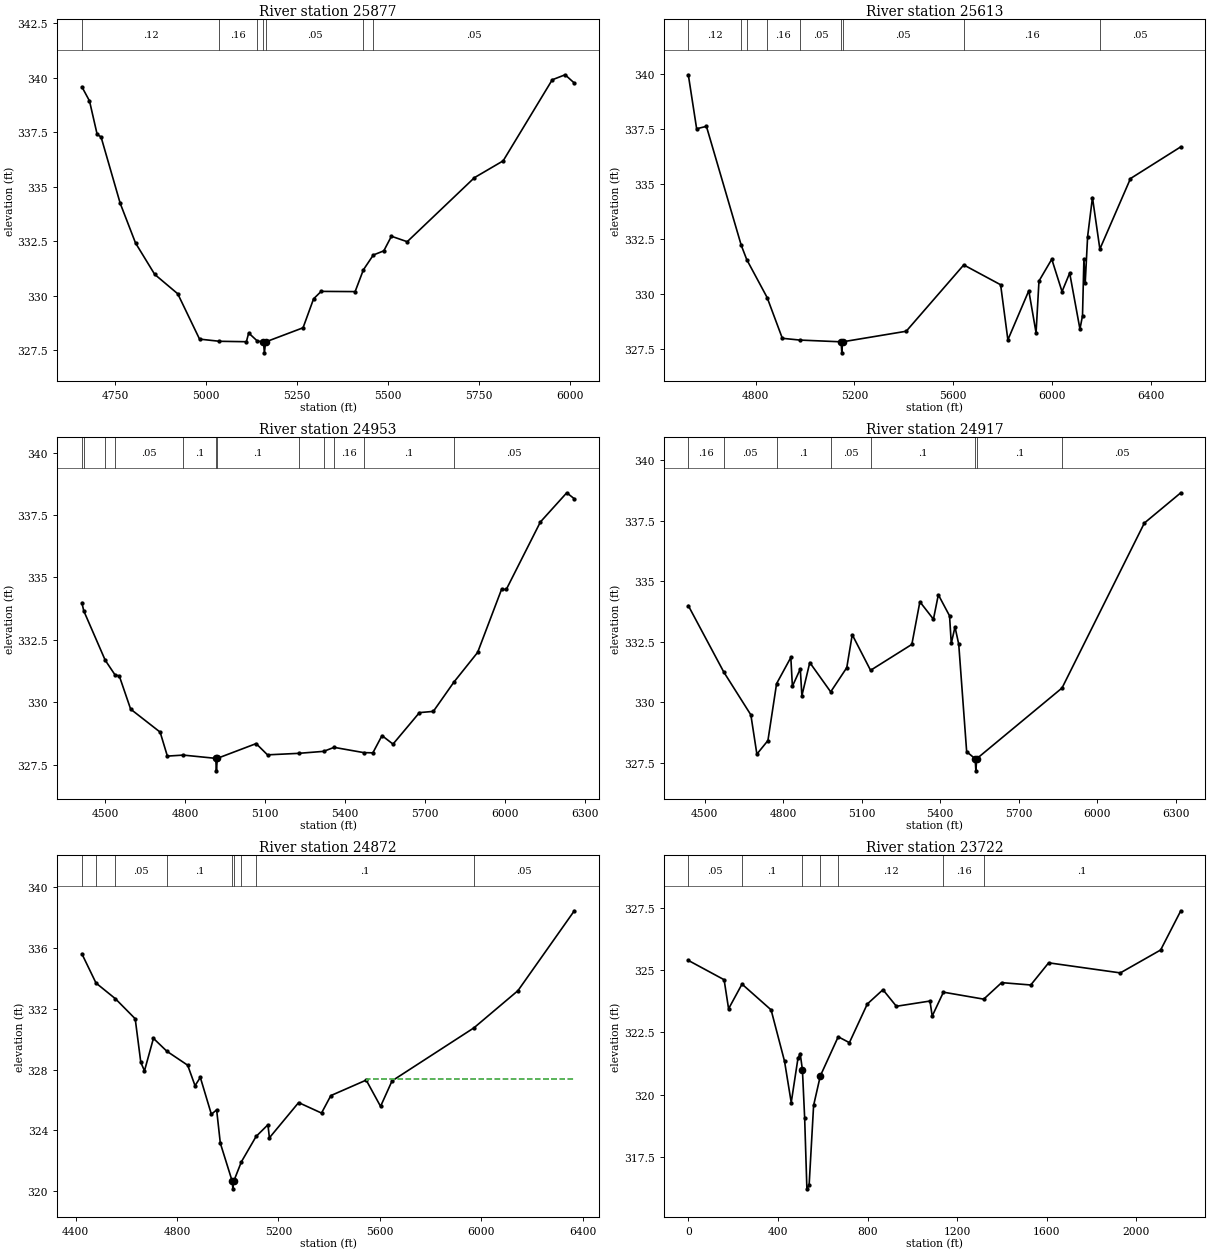
Type RM Length L Ch R = 1 ,25877   ,264,264,264
BEGIN DESCRIPTION:
UNT0416 IN CEDR CR 43.0
END DESCRIPTION:
XS GIS Cut Line= 3
      3605842.07     10328741.65      3605542.11     10328841.64
      3604721.31     10329475.42
#Sta/Elev= 30
  4658.8  339.58  4679.8  338.93  4700.9  337.39  4711.5  337.28  4764.2  334.23
  4806.3  332.41    4859  330.97  4922.3  330.08  4982.2     328  5036.9   327.9
  5110.9  327.88  5117.2  328.28  5141.1  327.91  5157.7  327.87  5160.4  327.37
  5163.7  327.87  5266.6  328.52  5295.6  329.85  5316.4  330.19  5409.7  330.18
  5432.4  331.18  5459.7  331.86  5488.5  332.05  5509.4  332.72  5552.8  332.47
  5737.6  335.41  5816.4  336.18  5951.3   339.9  5986.7  340.13    6012  339.75
#Mann= 7 ,-1 , 0
  4658.8     .12       0  5036.9     .16       0  5141.1     .05       0
  5157.7     .07       0  5163.7     .05       0  5432.4     .16       0
  5459.7     .05       0
Bank Sta=5157.7,5163.7
XS Rating Curve= 0 ,0
Exp/Cntr=0.3,0.1

Type RM Length L Ch R = 1 ,25613   ,660,660,660
BEGIN DESCRIPTION:
UNT0416 IN CEDR CR 42.0
END DESCRIPTION:
XS GIS Cut Line= 3
      3605899.57      10328669.2      3605640.86     10328559.81
      3603988.12     10329009.45
#Sta/Elev= 30
  4527.9  339.96  4561.6  337.51  4601.2  337.62  4742.2  332.22  4764.5  331.57
    4847  329.85  4908.5     328  4978.9  327.92  5146.5  327.84  5149.2  327.34
  5152.5  327.84    5410  328.32  5642.9  331.33  5792.2  330.43  5821.6  327.93
  5906.3  330.16  5935.7  328.25  5947.5   330.6  5999.3  331.59  6040.8  330.12
  6071.8  330.96  6113.3  328.42  6123.7  329.02  6129.4  331.61  6134.6   330.5
  6144.4  332.62    6164  334.39    6194  332.05  6317.9  335.25  6521.6  336.69
#Mann= 9 ,-1 , 0
  4527.9     .12       0  4742.2     .16       0  4764.5     .12       0
    4847     .16       0  4978.9     .05       0  5146.5     .03       0
  5152.5     .05       0  5642.9     .16       0    6194     .05       0
Bank Sta=5146.5,5152.5
XS Rating Curve= 0 ,0
Exp/Cntr=0.3,0.1

Type RM Length L Ch R = 1 ,24953   ,36,36,36
BEGIN DESCRIPTION:
Mapping XS 498ecd06
END DESCRIPTION:
XS GIS Cut Line= 6
      3605750.21     10328585.82      3605472.45     10328124.05
      3605338.77     10328007.73      3605180.79     10328032.03
       3605066.2     10328141.41       3604319.3      10328467.2
#Sta/Elev= 30
  4411.7  333.99    4419  333.66  4499.3  331.69  4536.3   331.1  4552.2  331.06
  4594.9  329.73  4705.6  328.81  4732.8  327.85  4792.6  327.89  4914.3  327.76
  4917.1  327.26  4920.3  327.76  5066.1  328.35  5108.8   327.9  5225.3  327.96
  5319.6  328.04  5358.8   328.2  5469.8  327.99  5504.4  327.98  5538.7  328.67
  5580.1  328.33  5679.2  329.59  5731.5  329.64  5808.6  330.81  5897.8     332
  5987.5  334.52  6005.4  334.52  6133.4  337.22  6232.5  338.39  6260.9  338.15
#Mann= 12 ,-1 , 0
  4411.7     .12       0    4419     .16       0  4499.3     .12       0
  4536.3     .05       0  4792.6      .1       0  4914.3    .033       0
  4920.3      .1       0  5225.3      .1       0  5319.6     .05       0
  5358.8     .16       0  5469.8      .1       0  5808.6     .05       0
Bank Sta=4914.3,4920.3
XS Rating Curve= 0 ,0
Exp/Cntr=0.3,0.1

Type RM Length L Ch R = 1 ,24917   ,45,45,45
BEGIN DESCRIPTION:
UNT0416 IN CEDR CR 41.0
END DESCRIPTION:
XS GIS Cut Line= 6
      3605783.23     10328521.63      3605517.59     10328115.37
      3605281.48     10327960.85      3605121.76     10327985.16
      3605050.58     10328066.75      3604300.54     10328437.44
#Sta/Elev= 30
    4438  333.99  4573.4  331.25  4676.9  329.48  4699.9  327.86  4742.1  328.42
  4775.2  330.77  4829.6  331.85  4835.6  330.66  4865.8  331.38  4871.8  330.27
    4902  331.64  4981.9  330.43  5043.3  331.43  5064.2  332.79  5134.2  331.32
  5291.9  332.39  5322.6  334.15  5374.4  333.43  5393.1  334.44  5435.9  333.57
  5442.5  332.43  5456.7  333.11    5471   332.4  5501.3  327.96  5533.7  327.67
  5536.5  327.17  5539.7  327.67  5865.6  330.59  6180.1   337.4  6319.3  338.65
#Mann= 8 ,-1 , 0
    4438     .16       0  4573.4     .05       0  4775.2      .1       0
  4981.9     .05       0  5134.2      .1       0  5533.7    .033       0
  5539.7      .1       0  5865.6     .05       0
Bank Sta=5533.7,5539.7
XS Rating Curve= 0 ,0
Exp/Cntr=0.3,0.1

Type RM Length L Ch R = 1 ,24872   ,1150,1150,1150
BEGIN DESCRIPTION:
Mapping XS 383583ab
END DESCRIPTION:
XS GIS Cut Line= 5
       3605840.5     10328488.62      3605463.77     10327997.31
      3605324.88     10327912.24       3605123.5     10327898.35
        3604278.     10328349.75
#Sta/Elev= 30
  4424.7  335.63  4480.6   333.7  4556.9  332.67  4635.1  331.35  4657.2  328.48
  4671.7  327.92    4707  330.06    4760  329.21  4842.1  328.29  4871.1  326.94
  4891.9  327.49  4935.5  325.06  4956.3  325.35  4970.8  323.16  5017.7  320.65
  5020.4  320.15  5023.7  320.65  5053.9  321.93  5111.9   323.6  5158.6  324.37
  5164.4  323.51  5279.6  325.83  5369.9  325.14  5406.7  326.29  5546.2  327.31
  5602.8  325.58  5648.2  327.26    5971  330.75  6144.7   333.2    6367  338.46
#Mann= 9 ,-1 , 0
  4424.7     .05       0  4480.6     .16       0  4556.9     .05       0
    4760      .1       0  5017.7     .07       0  5023.7      .1       0
  5053.9     .05       0  5111.9      .1       0    5971     .05       0
#XS Ineff= 2 , 0
                          5548.3          327.36
Permanent Ineff=
       F       F
Bank Sta=5017.7,5023.7
XS Rating Curve= 0 ,0
Exp/Cntr=0.3,0.1

Type RM Length L Ch R = 1 ,23722   ,1692,1692,1692
BEGIN DESCRIPTION:
UNT0416 IN CEDR CR 39.0
END DESCRIPTION:
XS GIS Cut Line= 3
      3606137.23     10327211.93      3605201.49     10327196.81
     3603947.075    10327311.235
#Sta/Elev= 30
       0325.3884 159.764324.6138179.7345323.4495239.6461324.4389369.4543323.4056
429.3658 321.349459.3216319.6936489.2774321.4597499.2626321.6564509.2479321.0061
519.2331319.0744529.2184 316.234539.2036316.3844559.1741319.5768589.1299 320.759
669.0119322.3274718.9382322.0927798.8202323.6407868.7169 324.214928.6285  323.55
1078.538323.76011088.533323.1564 1138.51324.11521318.426323.83571398.388324.4974
1528.327324.4033 1608.29325.2918 1928.14324.88772108.055325.80592198.013327.3771
#Mann= 7 ,-1 , 0
       0     .05       0239.6461      .1       0509.2479     .07       0
589.1299      .1       0669.0119     .12       0 1138.51     .16       0
1318.426      .1       0
Bank Sta=509.2479,589.1299
XS Rating Curve= 0 ,0
Exp/Cntr=0.3,0.1

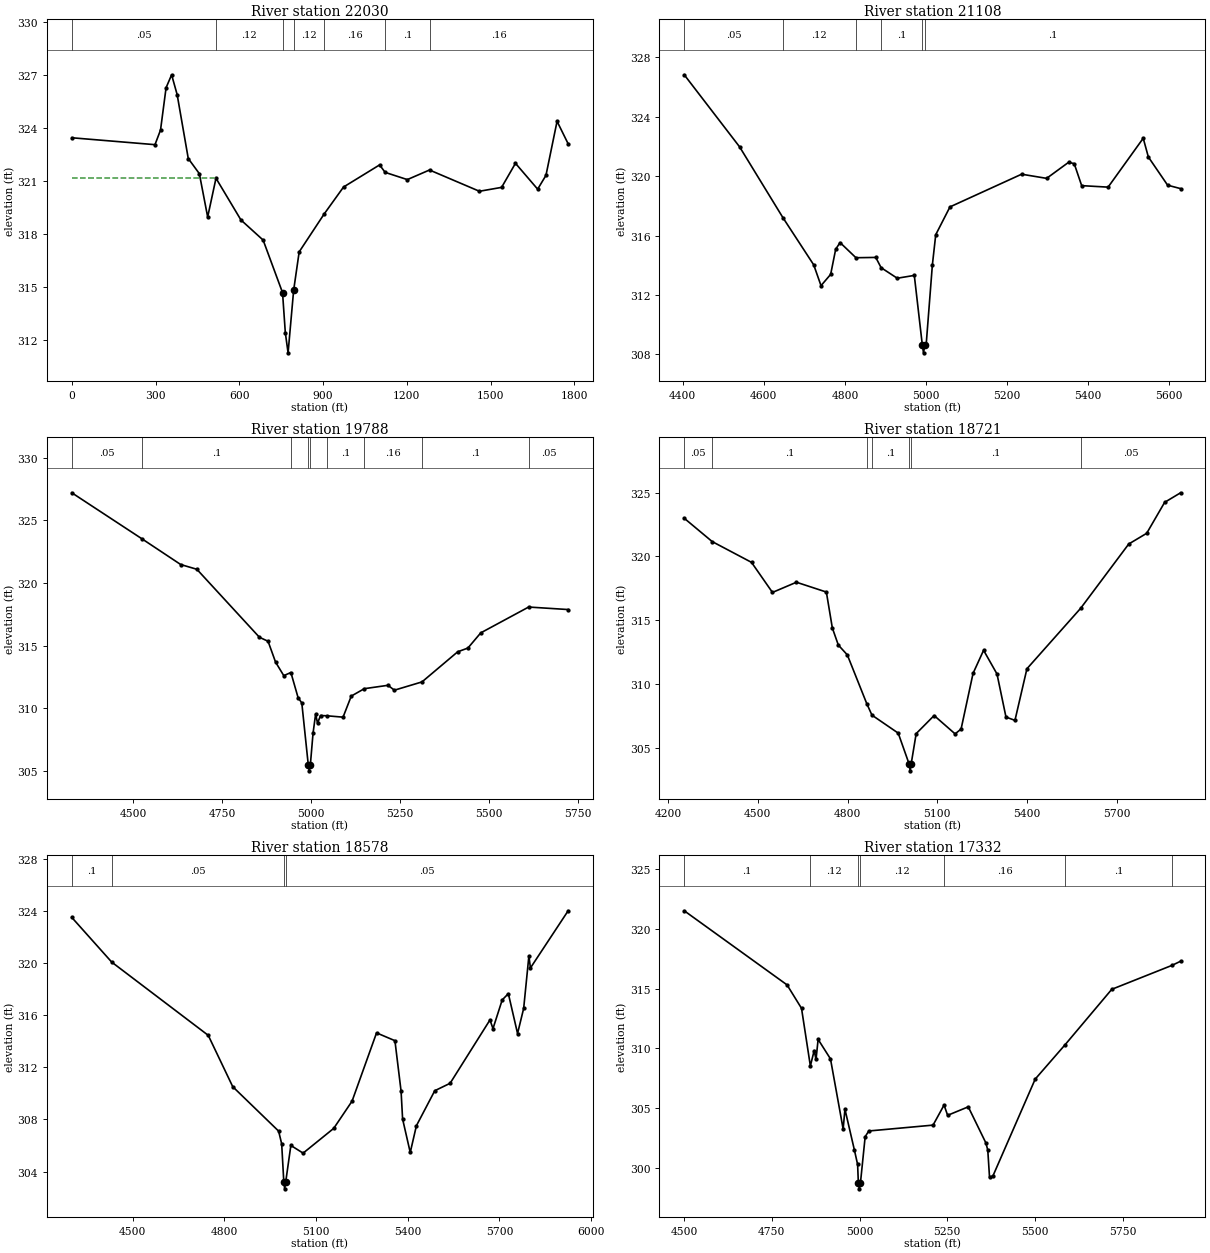
Type RM Length L Ch R = 1 ,22030   ,922,922,922
BEGIN DESCRIPTION:
UNT0416 IN CEDR CR 38.0
END DESCRIPTION:
XS GIS Cut Line= 3
      3606470.92     10326433.13      3605447.39     10326396.34
     3604711.499    10326586.083
#Sta/Elev= 30
       0323.4468297.9267323.0552317.7885 323.886337.6502326.2828 357.512327.0175
377.3738325.8893417.0973322.2708456.8209321.4113486.6136318.9556516.4063321.1523
605.7842318.7861685.2313317.6464754.7476314.6674764.6785312.4016774.6093311.2541
794.4711314.7937814.3329316.9781903.7109319.1235973.2271320.65431102.332321.9079
1122.194321.48471201.644321.07521281.094321.61921459.856320.41371539.306320.6346
1588.963321.99891668.413320.53291698.206321.31561737.931  324.381777.656323.1036
#Mann= 7 ,-1 , 0
       0     .05       0516.4063     .12       0754.7476     .07       0
794.4711     .12       0903.7109     .16       01122.194      .1       0
1281.094     .16       0
#XS Ineff= 2 , 0
          515.91  321.17
Permanent Ineff=
       F       F
Bank Sta=754.7476,794.4711
XS Rating Curve= 0 ,0
Exp/Cntr=0.3,0.1

Type RM Length L Ch R = 1 ,21108   ,1320,1320,1320
BEGIN DESCRIPTION:
UNT0416 IN CEDR CR 37.0
END DESCRIPTION:
XS GIS Cut Line= 3
      3605816.66     10325725.26      3605092.11     10326029.48
      3604687.08     10326198.74
#Sta/Elev= 30
  4403.6  326.82  4540.2  321.97    4647  317.21  4723.1  314.03  4741.1  312.63
  4764.9  313.39  4777.3  315.08  4788.1  315.53  4827.3  314.51  4876.2  314.53
  4889.4  313.84  4929.2  313.13  4971.3  313.32  4991.2  308.61    4994  308.11
  4997.2  308.61  5000.5  308.63  5015.9  314.03  5024.2  316.06  5059.3  317.93
  5236.1  320.13  5297.8  319.85    5352  320.93  5365.9  320.84  5384.3  319.36
  5449.5  319.26  5536.2  322.55  5548.8  321.29  5596.4  319.39  5628.4  319.16
#Mann= 6 ,-1 , 0
  4403.6     .05       0    4647     .12       0  4827.3     .16       0
  4889.4      .1       0  4991.2     .07       0  4997.2      .1       0
Bank Sta=4991.2,4997.2
XS Rating Curve= 0 ,0
Exp/Cntr=0.3,0.1

Type RM Length L Ch R = 1 ,19788   ,1067,1067,1067
BEGIN DESCRIPTION:
UNT0416 IN CEDR CR 35.0
END DESCRIPTION:
XS GIS Cut Line= 3
      3605715.72     10325209.16      3604817.27     10325508.65
      3604426.85     10325729.89
#Sta/Elev= 30
  4326.6  327.19  4524.4  323.51  4632.8  321.47  4678.3  321.09  4854.2  315.67
  4878.5  315.35  4899.6  313.69  4922.7  312.61  4942.7  312.86  4962.9  310.86
  4973.4  310.43  4991.5  305.52  4994.2  305.02  4997.5  305.52    5005  308.02
  5012.3  309.55  5017.6  308.82  5026.1  309.43  5043.6  309.41  5089.4   309.3
  5112.5  310.98  5149.1  311.57  5215.8  311.84  5233.7  311.45  5311.4  312.11
  5411.7  314.51  5440.5  314.81  5476.6  316.02  5611.3  318.08  5722.4  317.88
#Mann= 9 ,-1 , 0
  4326.6     .05       0  4524.4      .1       0  4942.7     .12       0
  4991.5     .07       0  4997.5     .12       0  5043.6      .1       0
  5149.1     .16       0  5311.4      .1       0  5611.3     .05       0
Bank Sta=4991.5,4997.5
XS Rating Curve= 0 ,0
Exp/Cntr=0.3,0.1

Type RM Length L Ch R = 1 ,18721   ,143,143,143
BEGIN DESCRIPTION:
UNT0416 IN CEDR CR 34.0
END DESCRIPTION:
XS GIS Cut Line= 2
      3605646.82     10324824.13      3603988.85     10324778.56
#Sta/Elev= 30
  4254.2  322.99  4347.6  321.16    4479  319.53    4549  317.17  4629.1  317.97
  4729.1   317.2  4749.1  314.38  4769.1  313.04  4799.1  312.27    4864  308.45
  4881.5  307.54  4969.2  306.13  5006.2  303.67  5008.9  303.17  5012.2  303.67
  5029.2  306.09  5089.2  307.51  5159.3  306.07  5179.3  306.45  5219.3  310.82
  5254.5  312.63  5299.3  310.77  5329.3  307.39  5359.3  307.13  5399.3  311.18
    5579  315.93  5739.5  320.97  5799.5  321.81  5859.5  324.24  5912.8  324.99
#Mann= 7 ,-1 , 0
  4254.2     .05       0  4347.6      .1       0    4864     .16       0
  4881.5      .1       0  5006.2     .07       0  5012.2      .1       0
    5579     .05       0
Bank Sta=5006.2,5012.2
XS Rating Curve= 0 ,0
Exp/Cntr=0.3,0.1

Type RM Length L Ch R = 1 ,18578   ,1246,1246,1246
BEGIN DESCRIPTION:
UNT0416 IN CEDR CR 33.0
END DESCRIPTION:
XS GIS Cut Line= 3
        3605688.     10324724.31      3604665.89      10324680.9
        3604067.     10324637.51
#Sta/Elev= 30
  4301.2   323.5  4431.8  320.07  4747.5  314.45  4827.6  310.51  4977.7   307.1
  4987.7  306.12  4994.7  303.17  4997.5  302.67  5000.7  303.17  5017.7     306
  5057.8  305.41  5157.9  307.31  5217.9   309.4    5298  314.64  5358.1  314.04
  5378.2  310.17  5383.2  308.03  5408.2  305.46  5428.3  307.51  5488.4   310.2
  5538.6  310.77  5668.9  315.63  5678.9  314.97    5709  317.17  5729.1  317.65
  5759.2  314.59  5779.2  316.52  5796.3  320.55  5801.3  319.62  5924.7  324.01
#Mann= 4 ,-1 , 0
  4301.2      .1       0  4431.8     .05       0  4994.7     .04       0
  5000.7     .05       0
Bank Sta=4994.7,5000.7
XS Rating Curve= 0 ,0
Exp/Cntr=0.3,0.1

Type RM Length L Ch R = 1 ,17332   ,1307,1307,1307
BEGIN DESCRIPTION:
UNT0416 IN CEDR CR 32.0
END DESCRIPTION:
XS GIS Cut Line= 3
      3605742.09     10324287.47      3605142.11     10324137.48
      3604349.39     10324070.28
#Sta/Elev= 30
  4500.7  321.52  4793.6  315.32  4834.8  313.36    4860  308.54  4870.9  309.83
  4876.1  309.08  4882.1  310.76  4917.3  309.13  4953.4  303.26  4958.5  304.92
  4985.1  301.55  4994.6   300.3  4996.7  298.76  4999.5  298.26  5002.7  298.76
  5016.1  302.62  5026.4   303.1  5209.5  303.59  5240.9  305.27    5251  304.41
  5309.8  305.12    5360   302.1  5365.4   301.5  5370.4  299.22  5380.1  299.34
  5500.5  307.44  5586.1  310.33  5718.6  314.95  5890.7  316.96  5914.7   317.3
#Mann= 7 ,-1 , 0
  4500.7      .1       0    4860     .12       0  4996.7     .07       0
  5002.7     .12       0  5240.9     .16       0  5586.1      .1       0
  5890.7     .16       0
Bank Sta=4996.7,5002.7
XS Rating Curve= 0 ,0
Exp/Cntr=0.3,0.1

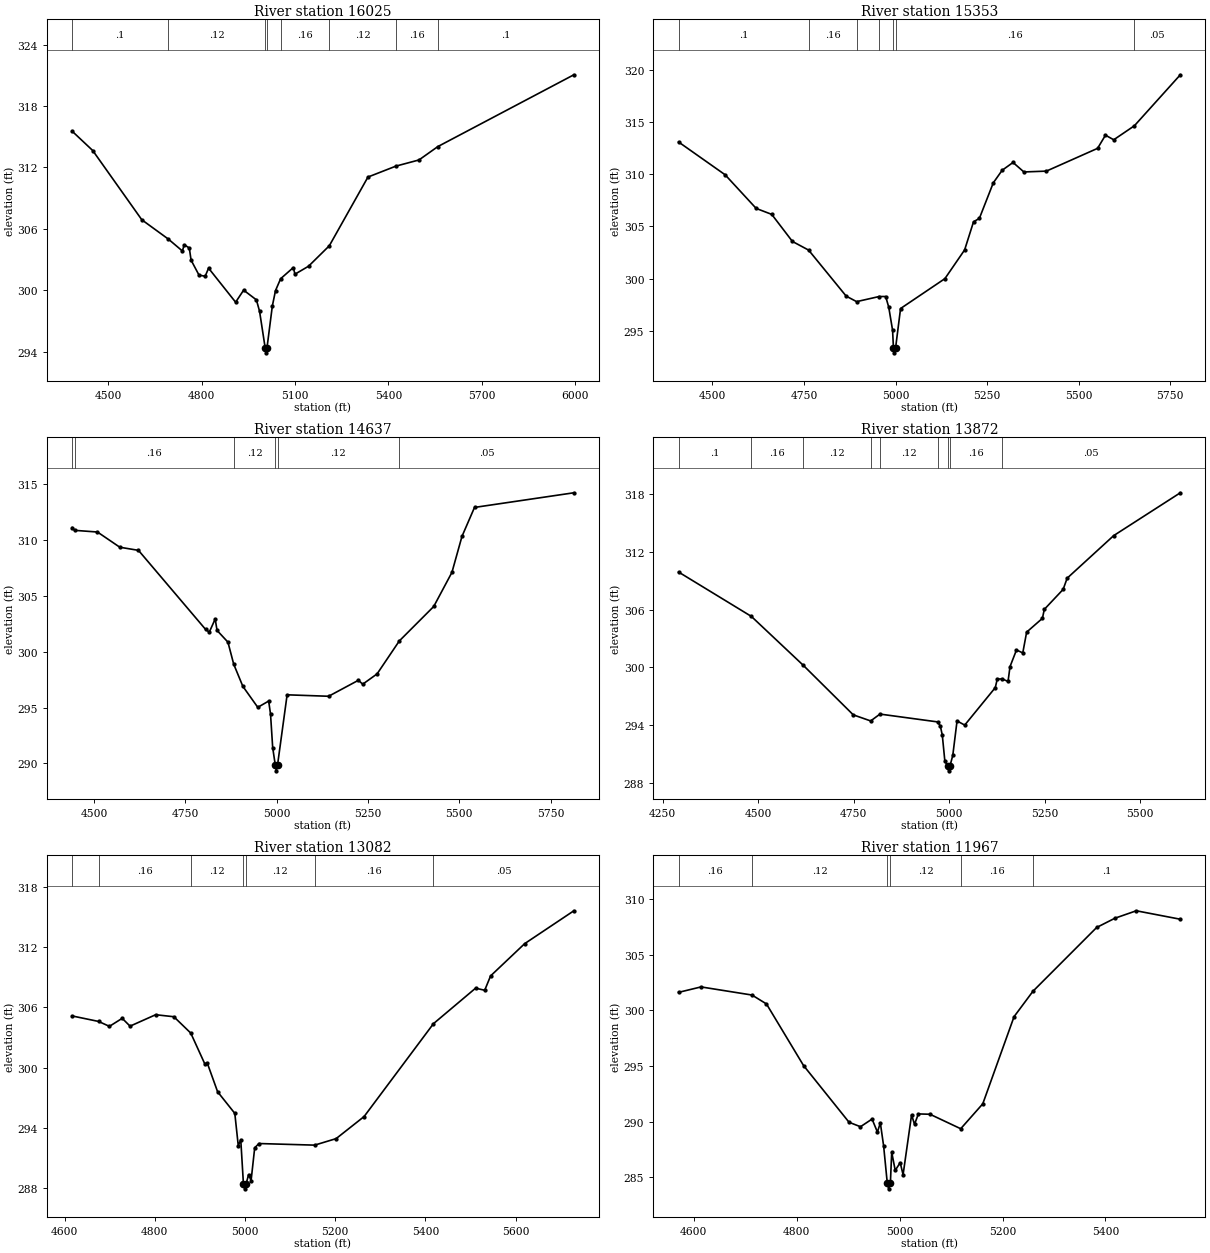
Type RM Length L Ch R = 1 ,16025   ,672,672,672
BEGIN DESCRIPTION:
UNT0416 IN CEDR CR 30.0
END DESCRIPTION:
XS GIS Cut Line= 3
      3605792.07     10323741.62      3605446.61     10323577.23
      3604246.21     10323313.55
#Sta/Elev= 30
  4384.3  315.55  4450.7  313.65  4608.3  306.88  4693.2     305  4738.6  303.83
  4744.6  304.44  4760.8  304.12  4766.6  302.93    4792  301.47  4811.8  301.36
  4822.7  302.15  4909.6  298.82  4935.3     300  4976.3  299.05  4986.5  297.93
  5004.4  294.37  5007.1  293.87  5010.4  294.37  5027.5  298.45  5037.7  299.96
  5054.2  301.12  5094.9  302.21  5100.1  301.56  5143.8  302.34  5210.5  304.34
  5334.6  311.06  5424.6  312.13  5498.4  312.73  5559.1  314.04  5995.9  321.06
#Mann= 8 ,-1 , 0
  4384.3      .1       0  4693.2     .12       0  5004.4     .07       0
  5010.4     .12       0  5054.2     .16       0  5210.5     .12       0
  5424.6     .16       0  5559.1      .1       0
Bank Sta=5004.4,5010.4
XS Rating Curve= 0 ,0
Exp/Cntr=0.3,0.1

Type RM Length L Ch R = 1 ,15353   ,716,716,716
BEGIN DESCRIPTION:
UNT0416 IN CEDR CR 28.0
END DESCRIPTION:
XS GIS Cut Line= 3
       3605942.1     10323391.64      3605676.04     10323125.57
      3604752.13     10322757.77
#Sta/Elev= 30
  4407.3  313.07  4534.6  309.93  4619.4  306.71  4661.9  306.14  4718.4  303.55
  4762.7  302.72  4865.2  298.32  4893.7  297.79  4955.4  298.28  4973.1  298.28
  4981.5  297.26    4992  295.05  4994.3  293.39  4997.1  292.89  5000.3  293.39
  5013.8  297.13  5134.9  299.99  5188.8  302.74  5213.1  305.43  5229.1  305.76
  5267.1  309.16  5291.3  310.36    5321  311.11  5350.7   310.2  5412.1  310.28
    5552  312.46  5573.5  313.72  5596.1  313.28  5652.5  314.62    5778   319.5
#Mann= 7 ,-1 , 0
  4407.3      .1       0  4762.7     .16       0  4893.7     .12       0
  4955.4     .16       0  4994.3     .07       0  5000.3     .16       0
  5652.5     .05       0
Bank Sta=4994.3,5000.3
XS Rating Curve= 0 ,0
Exp/Cntr=0.3,0.1

Type RM Length L Ch R = 1 ,14637   ,765,765,765
BEGIN DESCRIPTION:
UNT0416 IN CEDR CR 27.0
END DESCRIPTION:
XS GIS Cut Line= 3
      3606370.18     10322695.27      3605428.22     10322502.75
      3605028.26     10322402.76
#Sta/Elev= 30
  4440.2   311.1  4447.2  310.85  4509.7   310.7  4570.9  309.34    4622  309.06
  4805.7  301.99  4815.9  301.75    4832  302.92  4837.1   301.9  4866.9  300.85
  4882.7  298.88  4907.7   296.9  4948.6  295.02  4978.4  295.58  4983.5  294.42
  4989.4  291.42  4996.6  289.84  4999.4  289.34  5002.6  289.84  5028.9  296.14
  5142.5  296.01  5224.1  297.44  5235.9  297.09  5275.2  298.01  5336.1  300.96
  5430.3  304.04  5480.1  307.09  5507.6  310.31  5541.9   312.9  5813.9  314.21
#Mann= 6 ,-1 , 0
  4440.2      .1       0  4447.2     .16       0  4882.7     .12       0
  4996.6     .07       0  5002.6     .12       0  5336.1     .05       0
Bank Sta=4996.6,5002.6
XS Rating Curve= 0 ,0
Exp/Cntr=0.3,0.1

Type RM Length L Ch R = 1 ,13872   ,790,790,790
BEGIN DESCRIPTION:
UNT0416 IN CEDR CR 26.0
END DESCRIPTION:
XS GIS Cut Line= 3
      3606391.02     10322250.83      3605516.05     10321993.89
      3605120.21     10321924.45
#Sta/Elev= 30
  4291.5  309.89  4482.2  305.29  4618.2  300.22    4749  295.09  4794.6  294.46
  4818.9  295.17  4969.8  294.36  4976.9  293.94  4982.1  292.99  4988.7  290.33
  4996.1  289.79  4998.8  289.29  5002.1  289.79  5009.5  290.88  5020.7  294.46
  5040.8  294.03  5120.8  297.91    5126   298.8  5139.4  298.81  5154.2  298.55
  5159.4  300.09  5176.3  301.81  5192.8  301.51  5202.9  303.66  5244.2  305.09
  5249.2  306.02  5298.5  308.09    5309  309.25  5430.8  313.66  5605.3   318.1
#Mann= 9 ,-1 , 0
  4291.5      .1       0  4482.2     .16       0  4618.2     .12       0
  4794.6     .16       0  4818.9     .12       0  4969.8     .16       0
  4996.1     .07       0  5002.1     .16       0  5139.4     .05       0
Bank Sta=4996.1,5002.1
XS Rating Curve= 0 ,0
Exp/Cntr=0.3,0.1

Type RM Length L Ch R = 1 ,13082   ,1115,1115,1115
BEGIN DESCRIPTION:
UNT0416 IN CEDR CR 24.0
END DESCRIPTION:
XS GIS Cut Line= 3
      3606349.42      10321882.8      3605704.61     10321583.31
      3605305.88     10321533.47
#Sta/Elev= 30
  4616.4  305.15  4675.2   304.6  4699.2  304.11  4727.6  304.91    4745  304.13
  4801.8  305.27  4842.1  305.07  4879.6  303.44  4910.8  300.36  4916.3  300.44
  4939.2  297.58  4977.3  295.43    4985  292.19  4990.5  292.81  4996.4   288.4
  4999.1   287.9  5002.4   288.4  5007.9  289.32  5013.4  288.72  5021.4  291.99
  5030.8  292.42  5154.3  292.26    5202  292.91    5264  295.11  5417.9  304.38
  5511.3  307.92  5531.5  307.71  5544.5  309.14  5620.1  312.36  5729.2  315.64
#Mann= 7 ,-1 , 0
  4616.4      .1       0  4675.2     .16       0  4879.6     .12       0
  4996.4     .07       0  5002.4     .12       0  5154.3     .16       0
  5417.9     .05       0
Bank Sta=4996.4,5002.4
XS Rating Curve= 0 ,0
Exp/Cntr=0.3,0.1

Type RM Length L Ch R = 1 ,11967   ,720,720,720
BEGIN DESCRIPTION:
UNT0416 IN CEDR CR 22.0
END DESCRIPTION:
XS GIS Cut Line= 3
      3606377.17     10321535.56      3606043.49     10320891.64
      3605843.52     10320741.66
#Sta/Elev= 30
  4570.3  301.62    4614  302.11  4713.1  301.38  4741.2  300.58  4813.2  295.05
  4901.7  289.95  4923.9  289.55  4946.4  290.24  4956.8  289.07  4962.5  289.89
  4968.9  287.82    4976  284.47  4978.7  283.97    4982  284.47  4984.6  287.26
  4991.4  285.63  5001.1  286.32  5006.7  285.24  5023.2  290.62  5028.9  289.77
  5036.5   290.7    5059  290.67  5118.7  289.37  5161.6  291.61  5222.4  299.44
  5259.1  301.72  5382.9  307.45  5418.3  308.28  5459.9  308.95  5545.5  308.19
#Mann= 6 ,-1 , 0
  4570.3     .16       0  4713.1     .12       0    4976     .07       0
    4982     .12       0  5118.7     .16       0  5259.1      .1       0
Bank Sta=4976,4982
XS Rating Curve= 0 ,0
Exp/Cntr=0.3,0.1

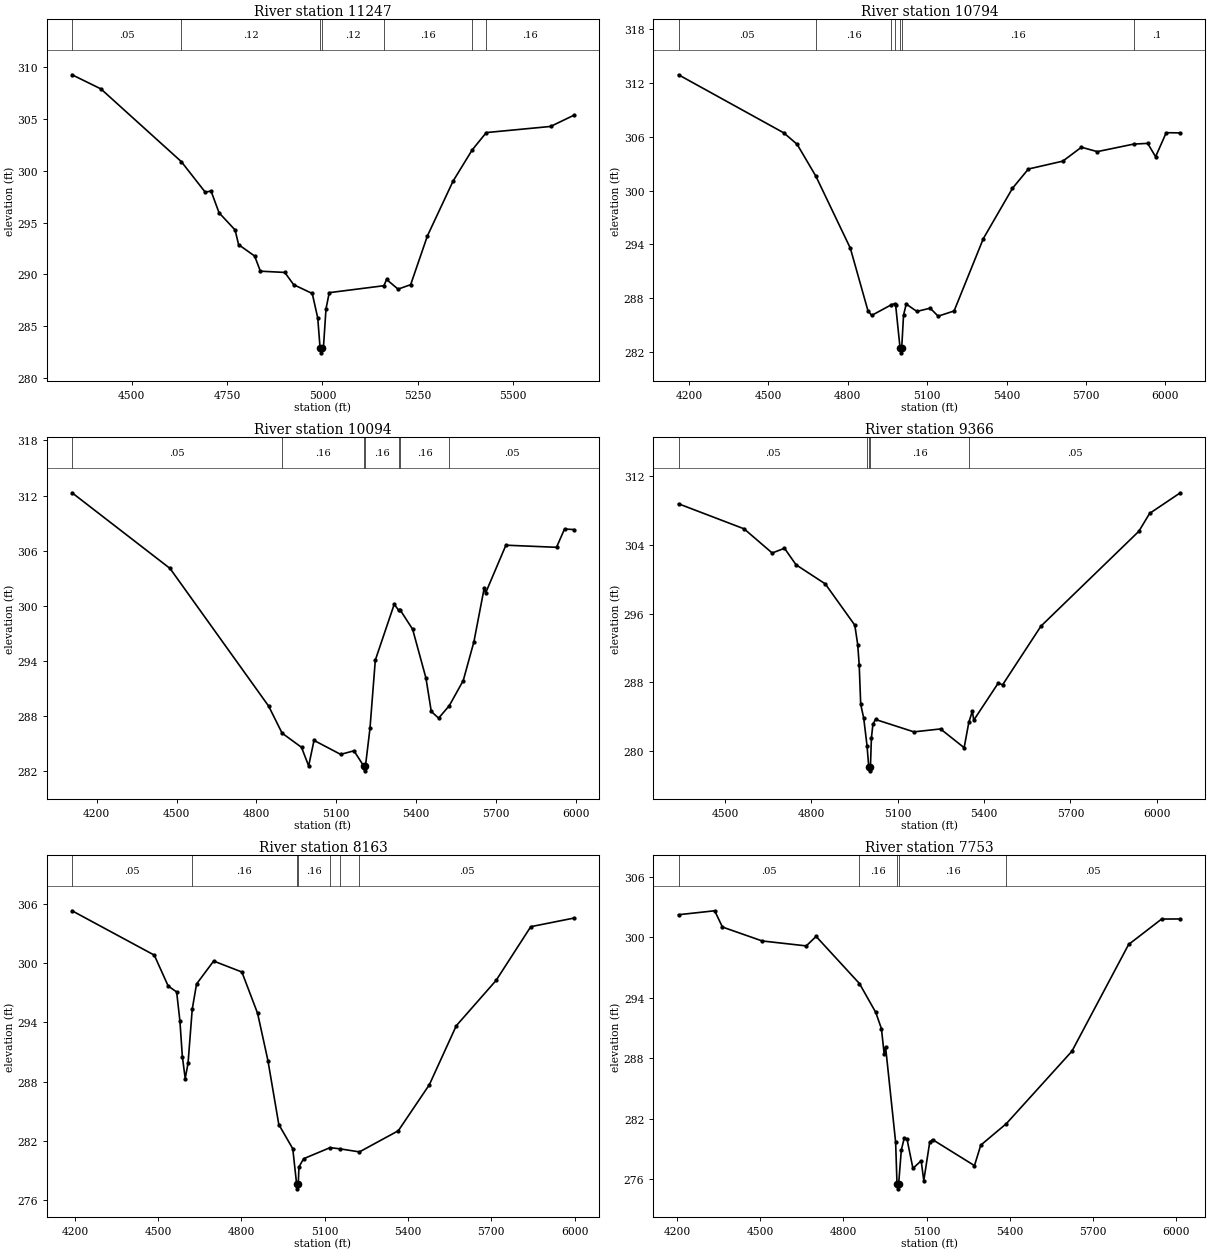
Type RM Length L Ch R = 1 ,11247   ,453,453,453
BEGIN DESCRIPTION:
UNT0416 IN CEDR CR 21.0
END DESCRIPTION:
XS GIS Cut Line= 3
      3606891.08     10321466.16      3606411.89     10320743.89
      3605981.33     10320618.89
#Sta/Elev= 30
  4343.8  309.24  4419.3  307.88  4630.1  300.87  4692.9  297.92    4708  298.04
    4729  295.94  4771.1  294.28  4780.2  292.87  4822.3  291.77  4837.3  290.31
  4901.3  290.19  4924.5  289.01  4973.3  288.16  4987.7  285.79  4993.7  282.94
  4996.5  282.44  4999.7  282.94  5002.7  283.01  5009.3  286.68  5017.8  288.24
  5161.1  288.91  5168.1  289.51  5198.2  288.58  5231.2  289.01  5275.2  293.72
  5342.3  298.99  5392.5     302  5429.4  303.67    5598  304.26  5658.9  305.34
#Mann= 7 ,-1 , 0
  4343.8     .05       0  4630.1     .12       0  4993.7     .07       0
  4999.7     .12       0  5161.1     .16       0  5392.5      .1       0
  5429.4     .16       0
Bank Sta=4993.7,4999.7
XS Rating Curve= 0 ,0
Exp/Cntr=0.3,0.1

Type RM Length L Ch R = 1 ,10794   ,700,700,700
BEGIN DESCRIPTION:
UNT0416 IN CEDR CR 20.0
END DESCRIPTION:
XS GIS Cut Line= 3
      3607557.71     10320639.72      3606474.39     10320528.61
      3605668.87     10320570.28
#Sta/Elev= 30
  4160.5  312.91  4558.2  306.43  4608.4  305.16  4679.5  301.59  4809.5  293.57
  4875.8  286.62  4889.9  286.07    4965  287.27  4977.4  287.38  4980.4  287.29
  4997.5   282.4  5000.2   281.9  5003.5   282.4  5010.5  286.11  5020.6  287.34
  5060.8  286.52  5111.1  286.88  5141.2  285.99  5201.5  286.57  5311.9  294.64
    5422  300.25  5482.1   302.4  5612.3  303.28  5682.4  304.83  5742.4  304.34
    5880  305.18  5932.7  305.26  5962.7  303.77  6002.8  306.45  6056.1  306.43
#Mann= 7 ,-1 , 0
  4160.5     .05       0  4679.5     .16       0    4965     .12       0
  4977.4     .16       0  4997.5     .07       0  5003.5     .16       0
    5880      .1       0
Bank Sta=4997.5,5003.5
XS Rating Curve= 0 ,0
Exp/Cntr=0.3,0.1

Type RM Length L Ch R = 1 ,10094   ,728,728,728
BEGIN DESCRIPTION:
UNT0416 IN CEDR CR 18.0
END DESCRIPTION:
XS GIS Cut Line= 3
      3607507.43     10319990.25      3607107.38     10320040.25
      3605627.11     10320125.84
#Sta/Elev= 30
  4107.4   312.3  4475.6  304.07  4846.4  289.09  4896.7  286.16  4969.7  284.62
  4996.6  282.59  5016.7  285.37  5116.8  283.85  5166.9  284.24    5204  282.56
  5206.7  282.06    5210  282.56    5227  286.67  5247.1   294.1  5318.2  300.18
  5334.3  299.54  5339.9  299.58  5387.3  297.46  5437.4  292.15  5457.4  288.52
    5485  287.79    5525  289.14  5577.6  291.88  5617.7   296.1  5656.7  301.99
  5661.7  301.41  5737.9   306.6  5928.2  306.37  5958.2  308.36  5993.3   308.3
#Mann= 7 ,-1 , 0
  4107.4     .05       0  4896.7     .16       0    5204     .07       0
    5210     .16       0  5334.3     .05       0  5339.9     .16       0
    5525     .05       0
Bank Sta=5204,5210
XS Rating Curve= 0 ,0
Exp/Cntr=0.3,0.1

Type RM Length L Ch R = 1 ,9366    ,1203,1203,1203
BEGIN DESCRIPTION:
UNT0416 IN CEDR CR 17.0
END DESCRIPTION:
XS GIS Cut Line= 3
      3607418.83     10319486.95       3606960.5     10319528.61
       3605710.5     10319820.28
#Sta/Elev= 30
  4338.2  308.76  4565.9  305.85  4663.7  303.04  4706.4  303.59  4746.6  301.67
  4848.1  299.45  4950.8  294.65  4960.9  292.38    4966  290.05  4971.3  285.44
  4981.6  283.87  4993.2  280.66  4999.1  278.22  5001.9  277.72  5005.1  278.22
  5008.5  281.55  5013.7  283.14  5022.7  283.69  5156.2  282.25  5248.6  282.59
  5330.7  280.41  5347.1  283.37  5359.1  284.64  5364.3  283.62  5449.4  287.93
  5464.2  287.71  5597.7  294.54  5937.8  305.56  5975.3  307.64    6082  310.04
#Mann= 5 ,-1 , 0
  4338.2     .05       0  4993.2     .16       0  4999.1     .07       0
  5005.1     .16       0  5347.1     .05       0
Bank Sta=4999.1,5005.1
XS Rating Curve= 0 ,0
Exp/Cntr=0.3,0.1

Type RM Length L Ch R = 1 ,8163    ,410,410,410
BEGIN DESCRIPTION:
UNT0416 IN CEDR CR 15.0
END DESCRIPTION:
XS GIS Cut Line= 3
      3607279.96     10318903.61      3606682.72     10319035.56
      3605613.29     10319570.27
#Sta/Elev= 30
  4189.9  305.29    4486   300.8  4535.9  297.68  4566.6  297.07  4578.4  294.11
  4587.1  290.53  4597.4  288.31  4607.6  289.85  4622.7  295.33  4638.3  297.88
  4699.8   300.2  4801.5  299.09  4858.1  294.91  4895.3  290.13  4934.5  283.65
  4984.8   281.2  4998.6  277.64  5001.3  277.14  5004.6  277.64  5007.1  279.36
  5023.9  280.19  5119.2  281.31  5154.7  281.19  5224.9  280.88  5364.9  283.02
  5476.7  287.68  5573.7  293.65  5717.1  298.24    5842  303.68  5997.2  304.55
#Mann= 7 ,-1 , 0
  4189.9     .05       0  4622.7     .16       0  4998.6     .07       0
  5004.6     .16       0  5119.2     .12       0  5154.7     .16       0
  5224.9     .05       0
Bank Sta=4998.6,5004.6
XS Rating Curve= 0 ,0
Exp/Cntr=0.3,0.1

Type RM Length L Ch R = 1 ,7753    ,1036,1036,1036
BEGIN DESCRIPTION:
UNT0416 IN CEDR CR 13.0
END DESCRIPTION:
XS GIS Cut Line= 3
      3607196.64     10318639.72      3606293.83     10318834.17
      3605496.17     10319215.66
#Sta/Elev= 30
  4206.2  302.23  4336.4  302.62  4364.3  301.01  4507.5  299.63  4666.3  299.14
  4701.8  300.08  4857.9  295.41  4916.7  292.55  4937.1  290.94  4946.9  288.45
    4952  289.15  4988.3  279.69  4993.2  275.57  4995.9  275.07  4999.2  275.57
  5008.7   278.9    5019  280.06  5029.2  280.01  5050.6   277.1  5080.3  277.85
  5089.7  275.88    5111  279.68  5121.2  279.95  5272.3  277.37    5295   279.4
  5387.2  281.53  5623.5  288.71  5827.6  299.28  5946.5   301.8  6013.9  301.81
#Mann= 5 ,-1 , 0
  4206.2     .05       0  4857.9     .16       0  4993.2     .07       0
  4999.2     .16       0  5387.2     .05       0
Bank Sta=4993.2,4999.2
XS Rating Curve= 0 ,0
Exp/Cntr=0.3,0.1

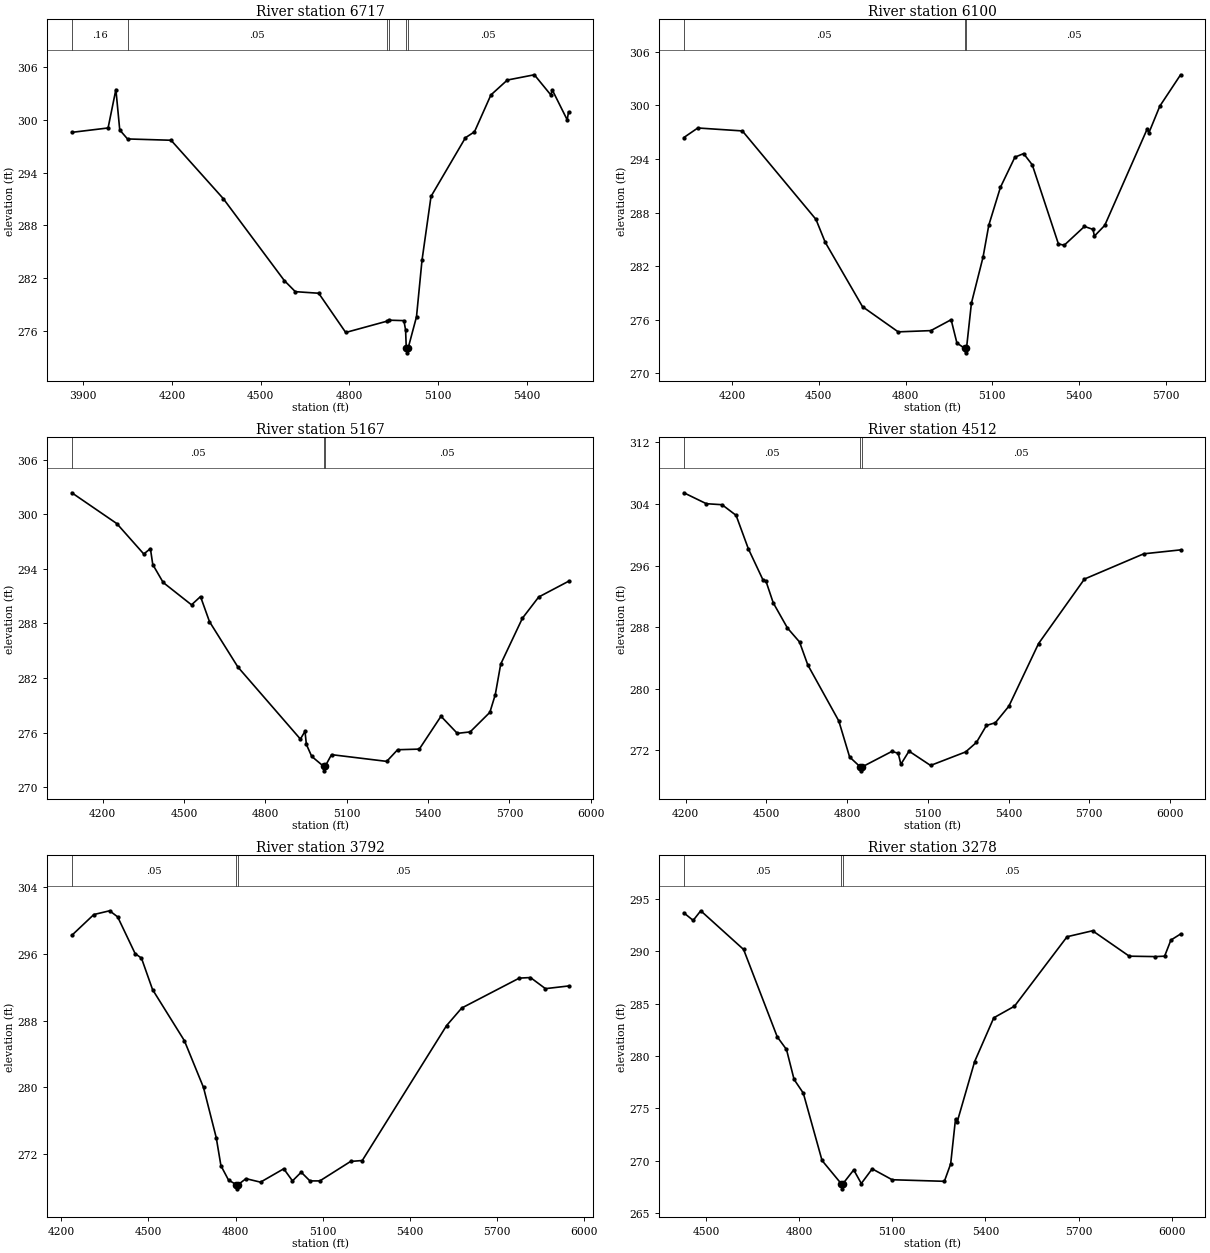
Type RM Length L Ch R = 1 ,6717    ,617,617,617
BEGIN DESCRIPTION:
UNT0416 IN CEDR CR 12.0
END DESCRIPTION:
XS GIS Cut Line= 3
      3606925.79     10318459.17      3606196.61     10318257.78
      3605329.35     10318576.93
#Sta/Elev= 30
  3861.3   298.6    3984   299.1  4010.4  303.48  4023.5  298.87  4049.8  297.85
  4197.1   297.7  4373.5  291.06  4580.1  281.72  4617.5  280.45  4696.6  280.27
    4788   275.8    4928  277.09  4935.4   277.2  4984.9  277.15  4990.6  276.08
  4992.9  273.98  4995.6  273.48  4998.9  273.98  5027.5  277.59  5046.1  284.02
  5076.6   291.3  5193.1  297.99  5223.6  298.66  5279.2  302.86  5334.8  304.56
  5426.2  305.16  5481.8  302.87  5487.1  303.42  5537.3  300.03  5541.9  300.93
#Mann= 6 ,-1 , 0
  3861.3     .16       0  4049.8     .05       0    4928     .16       0
  4935.4     .05       0  4992.9     .03       0  4998.9     .05       0
Bank Sta=4992.9,4998.9
XS Rating Curve= 0 ,0
Exp/Cntr=0.3,0.1

Type RM Length L Ch R = 1 ,6100    ,933,933,933
BEGIN DESCRIPTION:
UNT0416 IN CEDR CR 11.0
END DESCRIPTION:
XS GIS Cut Line= 3
      3606882.05     10318213.01      3606182.05       10317963.
      3605210.47     10317910.56
#Sta/Elev= 30
    4034  296.41  4082.2  297.48  4236.2  297.15  4490.5  287.24  4522.4  284.68
  4651.3  277.46  4774.6  274.64  4887.4  274.78  4957.5     276  4977.5  273.39
  5004.6  272.79  5007.3  272.29  5010.6  272.79  5027.6  277.86  5067.7     283
  5087.7   286.6  5127.8  290.83  5177.8  294.21  5207.9  294.61  5237.9  293.35
  5328.1   284.5  5348.1  284.34  5418.2  286.45  5447.6  286.12  5452.6  285.37
  5488.3  286.57  5635.4   297.4  5640.5  296.91  5678.6  299.93  5750.3  303.44
#Mann= 3 ,-1 , 0
    4034     .05       0  5004.6     .03       0  5010.6     .05       0
Bank Sta=5004.6,5010.6
XS Rating Curve= 0 ,0
Exp/Cntr=0.3,0.1

Type RM Length L Ch R = 1 ,5167    ,655,655,655
BEGIN DESCRIPTION:
UNT0416 IN CEDR CR 10.0
END DESCRIPTION:
XS GIS Cut Line= 3
      3607279.92     10317723.05      3606279.94     10317424.45
      3605492.13     10317391.64
#Sta/Elev= 30
  4085.9  302.36    4252  298.97  4351.3  295.63  4375.8  296.22  4384.5  294.47
  4422.8   292.5  4527.4  290.04  4560.6  290.95  4593.7  288.19  4698.3  283.21
    4929  275.28  4945.9  276.14  4951.1  274.69  4970.7  273.38  5014.3  272.29
  5017.1  271.79  5020.3  272.29  5043.8  273.57  5247.4  272.83  5287.5  274.11
  5367.6  274.18  5447.6  277.79  5507.7  275.91  5555.1  276.07  5627.8  278.22
  5647.8  280.17  5667.8  283.52  5747.9  288.57  5807.9   290.9    5918  292.63
#Mann= 3 ,-1 , 0
  4085.9     .05       0  5014.3     .03       0  5020.3     .05       0
Bank Sta=5014.3,5020.3
XS Rating Curve= 0 ,0
Exp/Cntr=0.3,0.1

Type RM Length L Ch R = 1 ,4512    ,720,720,720
BEGIN DESCRIPTION:
UNT0416 IN CEDR CR 8.0
END DESCRIPTION:
XS GIS Cut Line= 3
      3607245.22     10317111.95      3606786.89     10317063.34
      3605406.02     10316945.37
#Sta/Elev= 30
  4192.9  305.46  4276.5  304.04  4334.9  303.91  4387.1  302.53  4432.6  298.19
  4487.7  294.09  4497.7  294.03  4525.2  291.16  4578.2  287.88  4622.9  286.08
  4653.7  283.09    4769  275.81  4809.2  271.13  4849.1  269.83  4851.9  269.33
  4855.1  269.83  4966.1  271.85  4989.8  271.62  4999.8  270.18    5030  271.89
  5110.2  270.03  5240.7  271.79  5280.9  273.03  5317.9  275.23  5351.1  275.58
  5401.3  277.73  5511.7  285.87  5682.3  294.25  5902.7  297.53  6039.7  298.04
#Mann= 3 ,-1 , 0
  4192.9     .05       0  4849.1     .03       0  4855.1     .05       0
Bank Sta=4849.1,4855.1
XS Rating Curve= 0 ,0
Exp/Cntr=0.3,0.1

Type RM Length L Ch R = 1 ,3792    ,514,514,514
BEGIN DESCRIPTION:
UNT0416 IN CEDR CR 7.0
END DESCRIPTION:
XS GIS Cut Line= 3
      3607078.56     10316730.01      3606613.27       10316480.
      3605432.67     10316431.39
#Sta/Elev= 30
  4236.2  298.21    4312   300.7  4366.4  301.15    4394  300.42  4454.1  296.03
    4476  295.48  4514.1  291.72  4623.7   285.6  4689.5     280  4733.3     274
  4749.5  270.64  4775.6  268.92  4802.6  268.37  4805.4  267.87  4808.6  268.37
  4835.6  269.09  4885.7  268.67  4965.7  270.27  4995.8  268.82  5025.8  269.86
  5055.8  268.82    5090  268.82  5195.9  271.15    5236  271.26  5526.2  287.41
  5578.3  289.51  5776.4  293.09  5814.9  293.16  5866.5  291.83    5946  292.15
#Mann= 3 ,-1 , 0
  4236.2     .05       0  4802.6     .03       0  4808.6     .05       0
Bank Sta=4802.6,4808.6
XS Rating Curve= 0 ,0
Exp/Cntr=0.3,0.1

Type RM Length L Ch R = 1 ,3278    ,395,395,395
BEGIN DESCRIPTION:
UNT0416 IN CEDR CR 6.0
END DESCRIPTION:
XS GIS Cut Line= 3
      3607016.09     10316327.24      3606293.83      10316042.5
      3605481.33     10315910.56
#Sta/Elev= 30
  4428.8  293.69  4458.8  292.97  4483.2  293.89  4621.2  290.19  4729.5  281.84
  4759.3  280.63  4783.7  277.77  4813.4  276.46  4873.8  270.02  4935.3  267.81
    4938  267.31  4941.3  267.81  4975.8  269.12  5000.2  267.82  5035.3  269.22
  5099.5  268.18  5267.7  268.03    5288   269.7  5303.6     274  5308.7  273.68
  5365.2  279.48  5426.8  283.66  5493.5  284.77  5662.8  291.41  5744.9  291.98
    5863  289.55  5946.5  289.51  5976.9  289.55  5997.1  291.09  6028.3  291.67
#Mann= 3 ,-1 , 0
  4428.8     .05       0  4935.3     .03       0  4941.3     .05       0
Bank Sta=4935.3,4941.3
XS Rating Curve= 0 ,0
Exp/Cntr=0.3,0.1