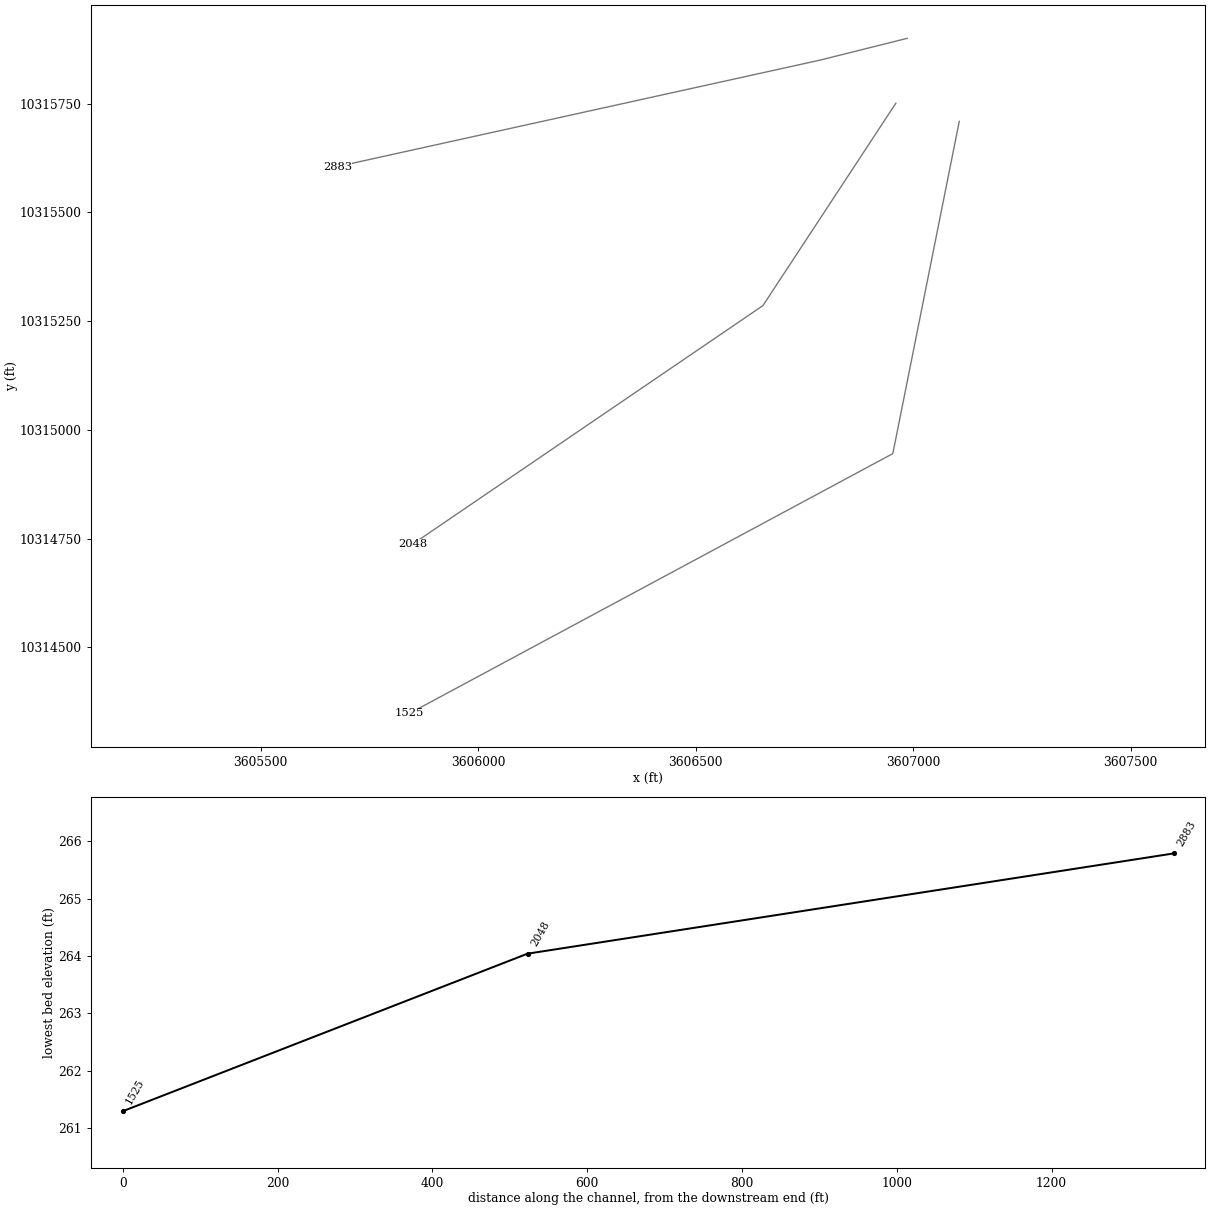
HEC-RAS study UNT0416 IN CEDR CR.prj: UNT0416 IN CEDR CR Base Level Engineering

--- UNT0416 IN CEDR CR.g01 (geometry) --- (continued)

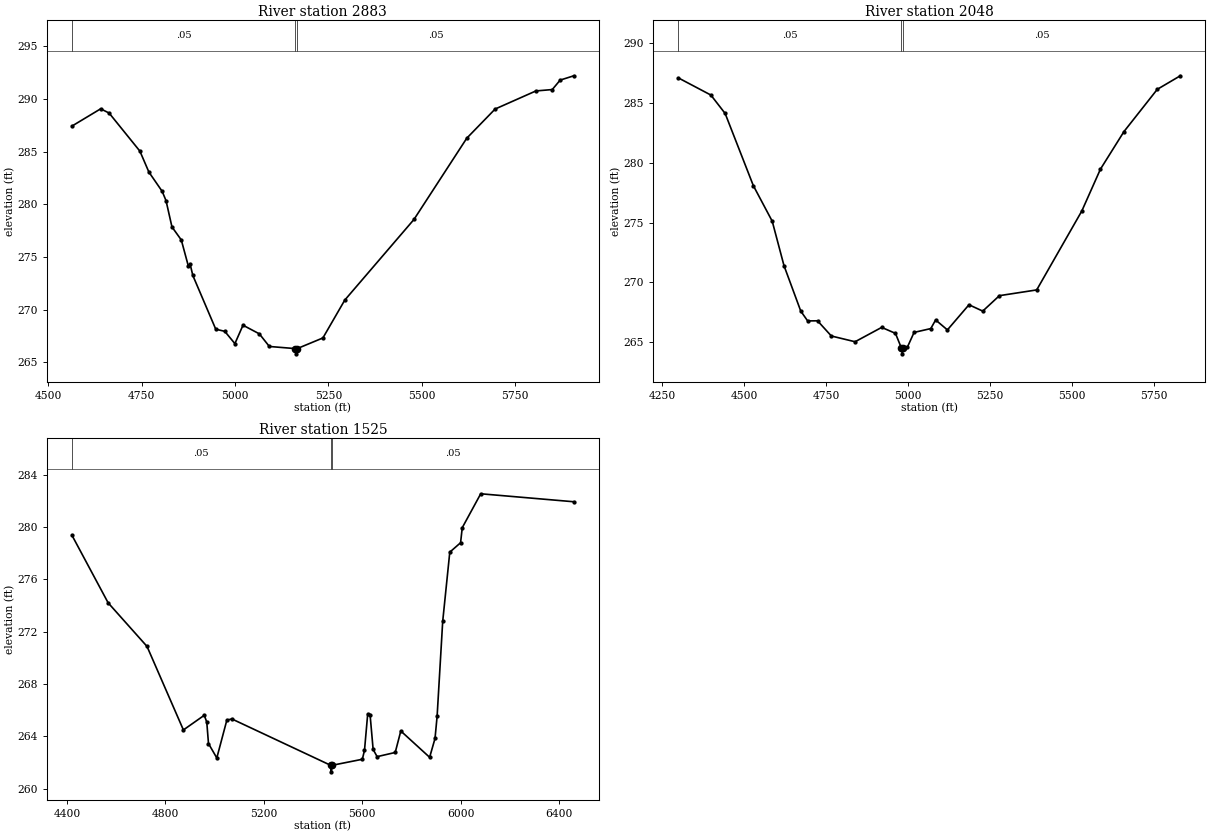
Type RM Length L Ch R = 1 ,2883    ,835,835,835
BEGIN DESCRIPTION:
UNT0416 IN CEDR CR 5.0
END DESCRIPTION:
XS GIS Cut Line= 3
      3606986.57     10315899.98      3606786.55     10315849.98
       3605676.4     10315605.14
#Sta/Elev= 30
  4563.7  287.43  4640.5  289.07  4663.1  288.67  4745.5  285.05  4769.6  283.06
  4805.1  281.23  4815.4  280.35  4831.3  277.85  4856.3  276.61    4875  274.15
  4880.1  274.29  4887.1  273.24  4948.5  268.13  4972.6  267.93  4999.7  266.76
  5021.4  268.51  5065.1  267.69  5091.9  266.49  5160.6  266.29  5163.3  265.79
  5166.6  266.29  5235.2   267.3  5293.8   270.9  5478.9  278.56  5620.2  286.28
    5696  289.05  5805.2  290.77  5848.9   290.9  5870.1   291.8  5906.7  292.21
#Mann= 3 ,-1 , 0
  4563.7     .05       0  5160.6     .03       0  5166.6     .05       0
Bank Sta=5160.6,5166.6
XS Rating Curve= 0 ,0
Exp/Cntr=0.3,0.1

Type RM Length L Ch R = 1 ,2048    ,523,523,523
BEGIN DESCRIPTION:
UNT0416 IN CEDR CR 3.0
END DESCRIPTION:
XS GIS Cut Line= 3
      3606960.52     10315750.87      3606654.94     10315285.56
      3605849.39     10314736.95
#Sta/Elev= 30
  4299.5  287.09  4398.5  285.66  4442.1  284.12  4528.1  278.09  4585.7  275.12
  4621.6  271.41  4672.8  267.61  4693.8  266.79    4724   266.8  4766.1  265.53
  4838.5  265.05  4919.7  266.25  4961.7  265.75  4979.6  264.54  4982.4  264.04
  4985.6  264.54  4997.6  264.57  5018.5  265.83  5069.4  266.15  5084.3  266.87
  5120.2  266.04    5186  268.14    5228  267.61  5278.8   268.9  5392.6  269.38
  5530.2  275.97  5587.1  279.47  5658.9  282.61  5760.6  286.14  5830.8  287.27
#Mann= 3 ,-1 , 0
  4299.5     .05       0  4979.6     .03       0  4985.6     .05       0
Bank Sta=4979.6,4985.6
XS Rating Curve= 0 ,0
Exp/Cntr=0.3,0.1

Type RM Length L Ch R = 1 ,1525    ,0,0,0
BEGIN DESCRIPTION:
UNT0416 IN CEDR CR 1.0
END DESCRIPTION:
XS GIS Cut Line= 3
      3607106.32     10315709.12      3606953.55     10314945.28
      3605842.45     10314348.07
#Sta/Elev= 30
  4419.8  279.36  4566.9   274.2    4725  270.87  4872.9  264.49  4957.7  265.61
  4967.9  265.09  4974.9  263.45  5008.7  262.35  5049.5  265.24  5069.9  265.33
  5471.5  261.79  5474.3  261.29  5477.5  261.79  5600.3  262.25  5609.1  262.93
  5622.2  265.73  5631.8  265.65  5644.2     263  5660.4  262.45    5734  262.77
  5756.7  264.41  5873.9   262.4  5895.8  263.84  5904.3  265.53    5927  272.78
  5955.8  278.07  5999.7  278.79  6006.5  279.94  6081.6  282.53  6460.2  281.92
#Mann= 3 ,-1 , 0
  4419.8     .05       0  5471.5     .03       0  5477.5     .05       0
Bank Sta=5471.5,5477.5
XS Rating Curve= 0 ,0
Exp/Cntr=0.3,0.1

Chan Stop Cuts=-1
Use User Specified Reach Order=0
Composite Channel Slope=5