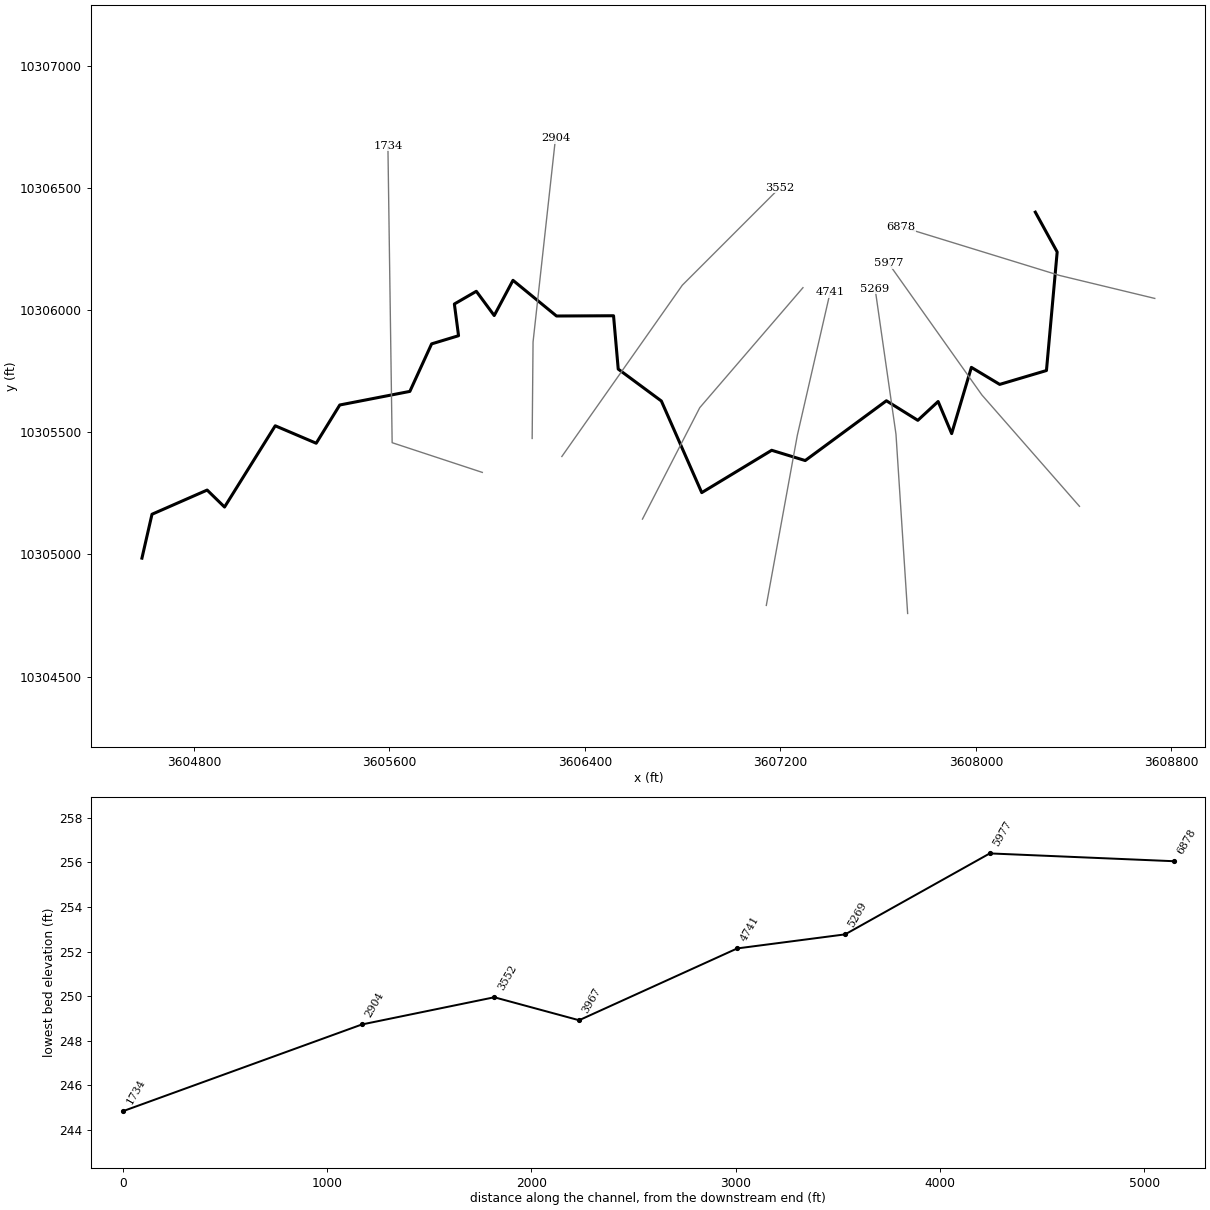
--- UNT0419 IN CEDR CR.prj (project) ---

Proj Title=UNT0419 IN CEDR CR Base Level Engineering
Current Plan=p01
Default Exp/Contr=0.3,0.1
English Units
Geom File=g01
Flow File=f01
Plan File=p01
BEGIN DESCRIPTION:
UNT0419 IN CEDR CR
END DESCRIPTION:

--- UNT0419 IN CEDR CR.p01 (plan) ---

Plan Title=Multiple Run
Short Identifier=Multiple
Geom File=g01
Flow File=f01
Subcritical Flow
K Sum by GR= 0
Std Step Tol= 0.01
Critical Tol= 0.01
Num of Std Step Trials= 20
Max Error Tol= 0.3
Flow Tol Ratio= 0.001
Split Flow NTrial= 30
Split Flow Tol= 0.02
Split Flow Ratio= 0.02
Log Output Level= 0
Friction Slope Method= 1
Unsteady Friction Slope Method= 2
Unsteady Bridges Friction Slope Method= 1
Parabolic Critical Depth
Global Vel Dist=  1 , 1 , 1
Global Log Level= 0
CheckData=True
Encroach Param= -1, 0, 0, 0
BEGIN DESCRIPTION:
Multiple Run
END DESCRIPTION:

--- UNT0419 IN CEDR CR.f01 (steady flow) ---

Flow Title=Multiple
Number of Profiles=7
Profile Names=10-year,25-year,50-year,1pct_min,100-year,1pct_plu,500-year
River Rch & RM= UNT0419 IN CEDR ,Reach-1,6878
     833    1138    1389    1242    1679    2271    2459
Boundary for River Rch & Prof#=UNT0419 IN CEDR ,Reach-1,1
Up Type=0
Dn Type=3
Dn Slope=0.005
Boundary for River Rch & Prof#=UNT0419 IN CEDR ,Reach-1,2
Up Type=0
Dn Type=3
Dn Slope=0.005
Boundary for River Rch & Prof#=UNT0419 IN CEDR ,Reach-1,3
Up Type=0
Dn Type=3
Dn Slope=0.005
Boundary for River Rch & Prof#=UNT0419 IN CEDR ,Reach-1,4
Up Type=0
Dn Type=3
Dn Slope=0.005
Boundary for River Rch & Prof#=UNT0419 IN CEDR ,Reach-1,5
Up Type=0
Dn Type=3
Dn Slope=0.005
Boundary for River Rch & Prof#=UNT0419 IN CEDR ,Reach-1,6
Up Type=0
Dn Type=3
Dn Slope=0.005
Boundary for River Rch & Prof#=UNT0419 IN CEDR ,Reach-1,7
Up Type=0
Dn Type=3
Dn Slope=0.005

--- UNT0419 IN CEDR CR.g01 (geometry) ---

Geom Title=Existing Conditions

River Reach=UNT0419 IN CEDR ,Reach-1
Reach XY= 30
      3608242.91     10306400.62      3608332.30     10306237.82
      3608288.44     10305752.68      3608097.14     10305695.93
      3607981.22     10305765.57      3607900.58     10305494.63
      3607845.18     10305625.90      3607762.10     10305548.88
      3607633.51     10305628.94      3607301.36     10305384.35
      3607164.09     10305426.36      3606877.92     10305253.12
      3606712.62     10305628.02      3606536.16     10305758.57
      3606517.00     10305976.79      3606283.55     10305975.75
      3606105.53     10306121.72      3606028.72     10305977.64
      3605955.53     10306076.87      3605865.69     10306024.86
      3605882.77     10305895.12      3605772.59     10305861.74
      3605683.53     10305667.29      3605396.72     10305611.65
      3605300.31     10305455.17      3605132.70     10305526.60
      3604925.24     10305194.14      3604854.06     10305263.58
      3604628.36     10305164.62      3604587.20     10304985.03

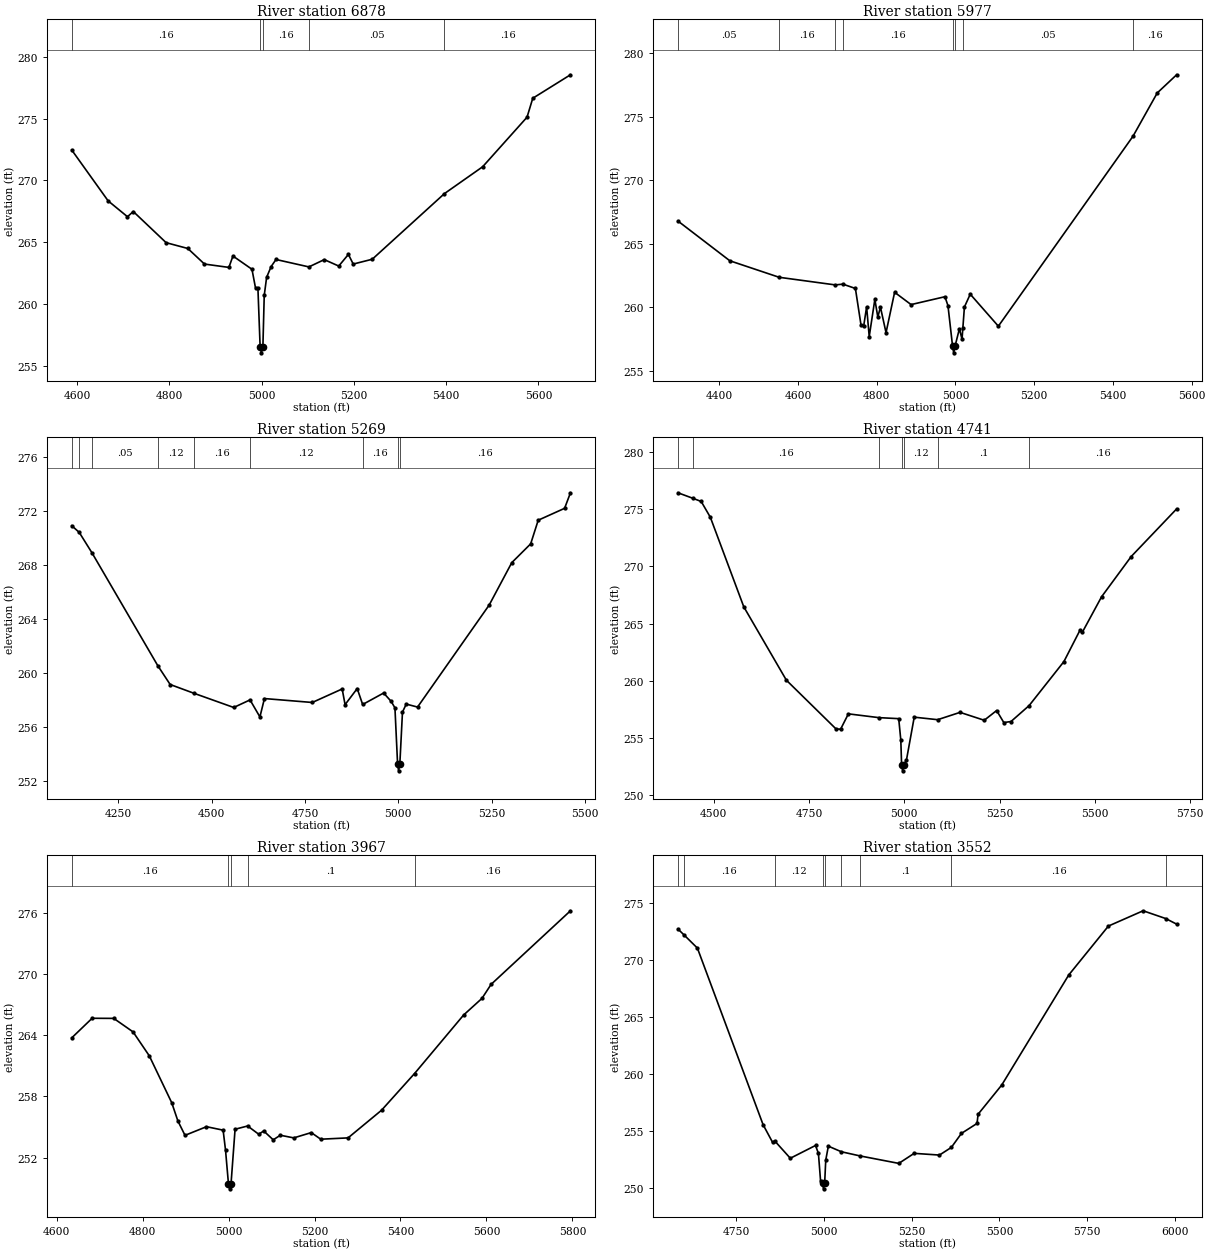
Type RM Length L Ch R = 1,6878,901,901,901
BEGIN DESCRIPTION:
UNT0419 IN CEDR CR 8.0
END DESCRIPTION:
XS GIS Cut Line= 3
      3608731.69     10306047.68      3608342.11     10306141.64
      3607692.13     10306341.63
#Sta/Elev= 30
  4588.6  272.45  4667.4  268.34  4709.3  267.06  4721.9  267.48  4793.1  264.96
  4840.1  264.49  4876.2  263.23  4929.1  262.96  4937.9  263.88  4979.1  262.81
  4986.8  261.30  4992.0  261.30  4996.8  256.55  4999.6  256.05  5002.8  256.55
  5005.7  260.69  5010.9  262.16  5020.7  263.03  5031.2  263.60  5102.5  263.00
  5135.8  263.59  5167.2  263.07  5188.1  264.01  5198.6  263.23  5239.8  263.62
  5396.3  268.93  5479.1  271.10  5575.3  275.11  5587.7  276.64  5669.4  278.54
#Mann=5,-1,0
  4588.6    0.16       0  4996.8    0.07       0  5002.8    0.16       0
  5102.5    0.05       0  5396.3    0.16       0
Bank Sta=4996.8,5002.8
Exp/Cntr=0.3,0.1

Type RM Length L Ch R = 1,5977,708,708,708
BEGIN DESCRIPTION:
UNT0419 IN CEDR CR 7.0
END DESCRIPTION:
XS GIS Cut Line= 3
      3608423.55     10305197.00      3608024.26     10305652.70
      3607642.08     10306191.67
#Sta/Elev= 30
  4295.3  266.78  4427.1  263.65  4552.4  262.35  4694.9  261.75  4714.3  261.81
  4746.0  261.47  4760.2  258.60  4766.9  258.48  4774.5  260.02  4781.1  257.68
  4795.4  260.61  4802.9  259.22  4809.6  260.00  4823.8  257.99  4845.6  261.17
  4887.4  260.20  4973.4  260.82  4981.1  260.12  4992.9  256.90  4995.7  256.40
  4998.9  256.90  5010.2  258.30  5016.8  257.47  5018.9  258.34  5022.9  260.01
  5037.7  261.02  5109.1  258.50  5451.1  273.46  5512.7  276.87  5561.9  278.30
#Mann=8,-1,0
  4295.3    0.05       0  4552.4    0.16       0  4694.9    0.05       0
  4714.3    0.16       0  4992.9    0.07       0  4998.9    0.16       0
  5018.9    0.05       0  5451.1    0.16       0
Bank Sta=4992.9,4998.9
Exp/Cntr=0.3,0.1

Type RM Length L Ch R = 1,5269,528,528,528
BEGIN DESCRIPTION:
UNT0419 IN CEDR CR 6.0
END DESCRIPTION:
XS GIS Cut Line= 3
      3607720.44     10304758.65      3607672.70     10305492.11
      3607587.30     10306087.20
#Sta/Elev= 30
  4125.2  270.91  4145.1  270.42  4179.2  268.91  4355.5  260.56  4388.8  259.16
  4453.6  258.50  4559.1  257.46  4602.8  258.02  4629.3  256.76  4641.4  258.12
  4769.6  257.83  4849.7  258.83  4857.5  257.67  4890.0  258.86  4904.6  257.68
  4960.8  258.53  4981.0  257.91  4991.1  257.43  4998.2  253.27  5000.9  252.77
  5004.2  253.27  5011.3  257.12  5021.4  257.71  5051.7  257.49  5243.6  265.04
  5304.2  268.18  5354.8  269.57  5375.0  271.32  5445.7  272.20  5461.4  273.35
#Mann=9,-1,0
  4125.2    0.05       0  4145.1    0.16       0  4179.2    0.05       0
  4355.5    0.12       0  4453.6    0.16       0  4602.8    0.12       0
  4904.6    0.16       0  4998.2    0.07       0  5004.2    0.16       0
Bank Sta=4998.2,5004.2
Exp/Cntr=0.3,0.1

Type RM Length L Ch R = 1,4741,774,774,774
BEGIN DESCRIPTION:
UNT0419 IN CEDR CR 5.0
END DESCRIPTION:
XS GIS Cut Line= 3
      3607142.10     10304791.62      3607269.06     10305487.77
      3607403.60     10306073.69
#Sta/Elev= 30
  4405.8  276.44  4445.6  275.95  4466.8  275.68  4490.8  274.30  4578.6  266.47
  4690.4  260.06  4820.7  255.80  4832.7  255.78  4853.1  257.12  4933.0  256.79
  4985.2  256.70  4990.7  254.83  4992.8  252.64  4995.5  252.14  4998.8  252.64
  5005.6  253.10  5025.9  256.83  5087.4  256.61  5146.2  257.25  5209.7  256.56
  5242.2  257.41  5261.0  256.36  5279.9  256.45  5327.4  257.84  5418.8  261.69
  5461.6  264.47  5466.8  264.23  5517.6  267.35  5595.4  270.87  5714.6  275.03
#Mann=7,-1,0
  4405.8    0.05       0  4445.6    0.16       0  4933.0    0.12       0
  4992.8    0.07       0  4998.8    0.12       0  5087.4     0.1       0
  5327.4    0.16       0
Bank Sta=4992.8,4998.8
Exp/Cntr=0.3,0.1

Type RM Length L Ch R = 1,3967,415,415,415
BEGIN DESCRIPTION:
UNT0419 IN CEDR CR 3.0
END DESCRIPTION:
XS GIS Cut Line= 3
      3606635.36     10305144.86      3606869.75     10305600.62
      3607292.12     10306091.66
#Sta/Elev= 30
  4635.3  263.77  4682.6  265.69  4732.9  265.68  4777.9  264.35  4815.6  262.00
  4867.8  257.39  4882.2  255.59  4898.7  254.18  4948.7  255.03  4987.4  254.69
  4993.0  252.72  4999.8  249.42  5002.5  248.92  5005.8  249.42  5015.2  254.78
  5044.4  255.10  5070.2  254.29  5081.8  254.61  5104.0  253.74  5120.5  254.19
  5151.8  253.93  5192.5  254.45  5214.5  253.80  5278.1  253.93  5356.0  256.65
  5432.8  260.26  5546.9  266.01  5589.7  267.65  5610.8  269.02  5795.5  276.26
#Mann=5,-1,0
  4635.3    0.16       0  4999.8    0.07       0  5005.8    0.16       0
  5044.4     0.1       0  5432.8    0.16       0
Bank Sta=4999.8,5005.8
Exp/Cntr=0.3,0.1

Type RM Length L Ch R = 1,3552,648,648,648
BEGIN DESCRIPTION:
UNT0419 IN CEDR CR 2.0
END DESCRIPTION:
XS GIS Cut Line= 3
      3606305.50     10305400.94      3606798.36     10306101.71
      3607197.71     10306501.07
#Sta/Elev= 30
  4583.5  272.72  4599.6  272.24  4638.9  271.05  4826.2  255.57  4853.3  254.02
  4860.2  254.12  4903.8  252.63  4975.6  253.75  4983.9  253.06  4990.0  250.65
  4995.7  250.45  4998.4  249.95  5001.7  250.45  5004.8  252.47  5012.2  253.69
  5049.3  253.20  5101.7  252.84  5213.0  252.18  5256.8  253.06  5328.9  252.91
  5362.8  253.58  5391.6  254.81  5436.0  255.68  5439.1  256.49  5506.5  259.05
  5697.4  268.69  5810.5  272.98  5909.5  274.32  5973.8  273.64  6005.0  273.15
#Mann=9,-1,0
  4583.5     0.1       0  4599.6    0.16       0  4860.2    0.12       0
  4995.7    0.07       0  5001.7    0.12       0  5049.3    0.16       0
  5101.7     0.1       0  5362.8    0.16       0  5973.8    0.05       0
Bank Sta=4995.7,5001.7
Exp/Cntr=0.3,0.1

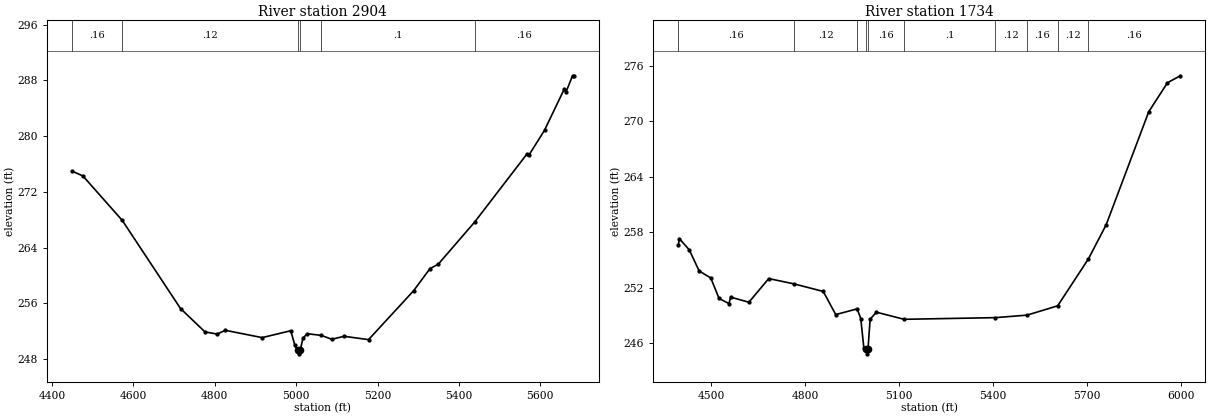
Type RM Length L Ch R = 1,2904,1170,1170,1170
BEGIN DESCRIPTION:
UNT0419 IN CEDR CR 1.1
END DESCRIPTION:
XS GIS Cut Line= 3
      3606183.99     10305474.74      3606187.65     10305869.46
      3606279.48     10306703.08
#Sta/Elev= 30
  4448.9  274.97  4475.8  274.28  4572.7  267.88  4715.8  255.23  4775.8  251.88
  4805.8  251.57  4825.8  252.11  4916.3  251.06  4986.7  252.05  4996.7  249.94
  5003.8  249.23  5006.5  248.73  5009.8  249.23  5016.6  250.99  5026.9  251.62
  5061.9  251.38  5087.3  250.82  5117.6  251.25  5177.8  250.77  5288.5  257.79
  5328.7  260.97  5348.9  261.59  5438.6  267.66  5567.2  277.44  5572.3  277.30
  5610.4  280.86  5658.2  286.69  5663.2  286.35  5679.0  288.66  5682.3  288.66
#Mann=6,-1,0
  4448.9    0.16       0  4572.7    0.12       0  5003.8    0.07       0
  5009.8    0.12       0  5061.9     0.1       0  5438.6    0.16       0
Bank Sta=5003.8,5009.8
Exp/Cntr=0.3,0.1

Type RM Length L Ch R = 1,1734,0,0,0
BEGIN DESCRIPTION:
UNT0419 IN CEDR CR 1.0
END DESCRIPTION:
XS GIS Cut Line= 3
      3605979.98     10305335.87      3605611.07     10305457.39
      3605593.71     10306672.66
#Sta/Elev= 30
  4394.9  256.60  4397.6  257.32  4429.4  256.11  4461.2  253.81  4498.2  253.06
  4524.7  250.84  4556.5  250.28  4561.8  250.98  4620.1  250.43  4683.6  252.99
  4763.5  252.42  4857.6  251.60  4897.6  249.09  4966.0  249.71  4977.6  248.66
  4987.6  245.43  4994.6  245.34  4997.3  244.84  5000.6  245.34  5007.6  248.60
  5027.6  249.35  5116.0  248.58  5408.0  248.76  5508.7  249.03  5606.8  250.04
  5705.0  255.12  5761.8  258.82  5897.7  271.05  5957.7  274.20  5998.7  274.95
#Mann=10,-1,0
  4394.9    0.16       0  4763.5    0.12       0  4966.0    0.16       0
  4994.6    0.07       0  5000.6    0.16       0  5116.0     0.1       0
  5408.0    0.12       0  5508.7    0.16       0  5606.8    0.12       0
  5705.0    0.16       0
Bank Sta=4994.6,5000.6
Exp/Cntr=0.3,0.1

Chan Stop Cuts=-1