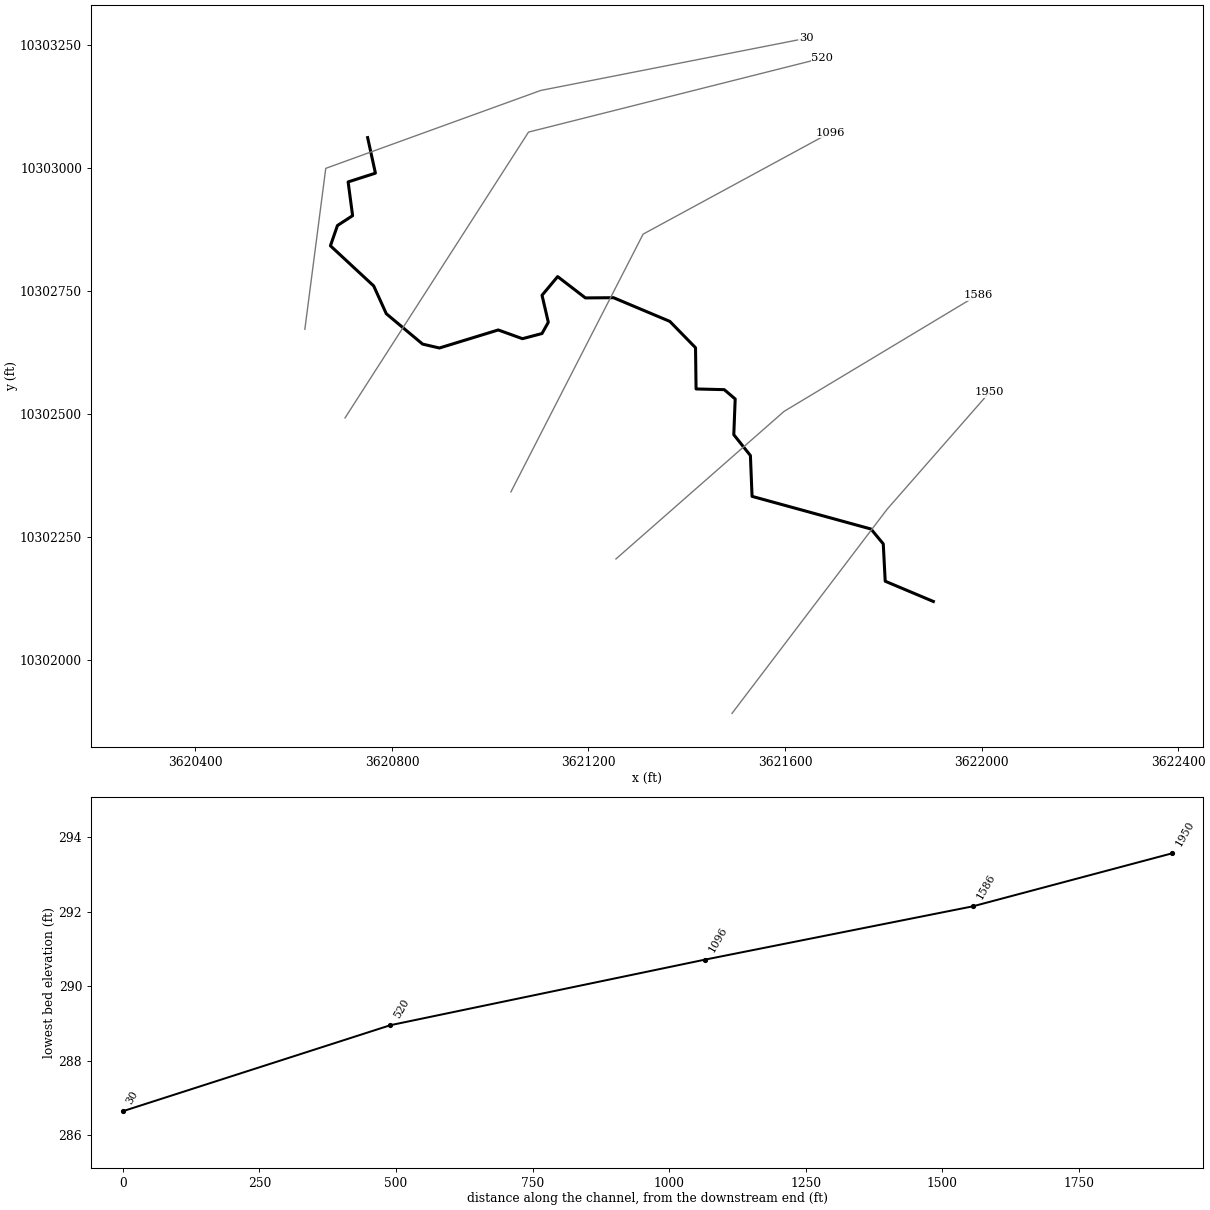
--- UNT0421 IN CEDR CR.prj (project) ---

Proj Title=UNT0421 IN CEDR CR Base Level Engineering
Current Plan=p01
Default Exp/Contr=0.3,0.1
English Units
Geom File=g01
Flow File=f01
Plan File=p01
Y Axis Title=Elevation
X Axis Title(PF)=Main Channel Distance
X Axis Title(XS)=Station
BEGIN DESCRIPTION:
UNT0421 IN CEDR CR
END DESCRIPTION:
DSS Export Rating Curves= 0
DSS Export Rating Curve Sorted= 0
DSS Export Volume Flow Curves= 0
DXF OffsetX= 0
DXF OffsetY= 0
DXF ScaleX= 1
DXF ScaleY= 10

--- UNT0421 IN CEDR CR.p01 (plan) ---

Plan Title=Multiple Run
Short Identifier=Multiple
Geom File=g01
Flow File=f01
Subcritical Flow
K Sum by GR= 0
Std Step Tol= 0.01
Critical Tol= 0.01
Num of Std Step Trials= 20
Max Error Tol= 0.3
Flow Tol Ratio= 0.001
Split Flow NTrial= 30
Split Flow Tol= 0.02
Split Flow Ratio= 0.02
Log Output Level= 0
Friction Slope Method= 1
Unsteady Friction Slope Method= 2
Unsteady Bridges Friction Slope Method= 1
Parabolic Critical Depth
Global Vel Dist=  1 , 1 , 1
Global Log Level= 0
CheckData=True
Encroach Param= -1, 0, 0, 0
BEGIN DESCRIPTION:
Multiple Run
END DESCRIPTION:

--- UNT0421 IN CEDR CR.f01 (steady flow) ---

Flow Title=Multiple
Program Version=4.10
Number of Profiles= 7
Profile Names=10-year,25-year,50-year,1pct_min,100-year,1pct_plu,500-year
River Rch & RM=UNT0421 IN CEDR,Reach-1         ,1950
     548     726     869     762    1030    1393    1451
River Rch & RM=UNT0421 IN CEDR,Reach-1         ,30
    1233    1703    2093    1881    2543    3440    3762
Boundary for River Rch & Prof#=UNT0421 IN CEDR,Reach-1         , 1
Up Type= 0
Dn Type= 3
Dn Slope=0.006
Boundary for River Rch & Prof#=UNT0421 IN CEDR,Reach-1         , 2
Up Type= 0
Dn Type= 3
Dn Slope=0.006
Boundary for River Rch & Prof#=UNT0421 IN CEDR,Reach-1         , 3
Up Type= 0
Dn Type= 3
Dn Slope=0.006
Boundary for River Rch & Prof#=UNT0421 IN CEDR,Reach-1         , 4
Up Type= 0
Dn Type= 3
Dn Slope=0.006
Boundary for River Rch & Prof#=UNT0421 IN CEDR,Reach-1         , 5
Up Type= 0
Dn Type= 3
Dn Slope=0.006
Boundary for River Rch & Prof#=UNT0421 IN CEDR,Reach-1         , 6
Up Type= 0
Dn Type= 3
Dn Slope=0.006
Boundary for River Rch & Prof#=UNT0421 IN CEDR,Reach-1         , 7
Up Type= 0
Dn Type= 3
Dn Slope=0.006
DSS Import GetInterval= 0
DSS Import GetPeak= 0
DSS Import FillOption= 0

--- UNT0421 IN CEDR CR.g01 (geometry) ---

Geom Title=Existing Conditions
Program Version=4.10

River Reach=UNT0421 IN CEDR ,Reach-1
Reach XY= 30
      3621901.94     10302118.97       3621803.9     10302160.14
      3621799.95     10302235.97      3621774.95     10302266.21
       3621532.9     10302332.55      3621529.53     10302415.49
      3621495.72     10302457.86      3621498.56     10302530.41
      3621476.31     10302549.36      3621418.93     10302550.77
      3621417.84     10302634.57      3621365.52     10302688.05
      3621250.91      10302736.2      3621193.67     10302735.74
       3621137.2     10302779.08      3621105.43     10302741.09
       3621118.2     10302686.26      3621105.36      10302663.4
      3621065.56     10302652.89      3621016.32     10302670.64
      3620896.54     10302633.98      3620862.36      10302641.9
      3620788.45     10302703.63      3620762.84     10302760.05
      3620674.74     10302841.65      3620689.06     10302882.88
      3620719.87     10302902.84      3620710.76     10302971.42
      3620766.32     10302989.22      3620750.45     10303061.44

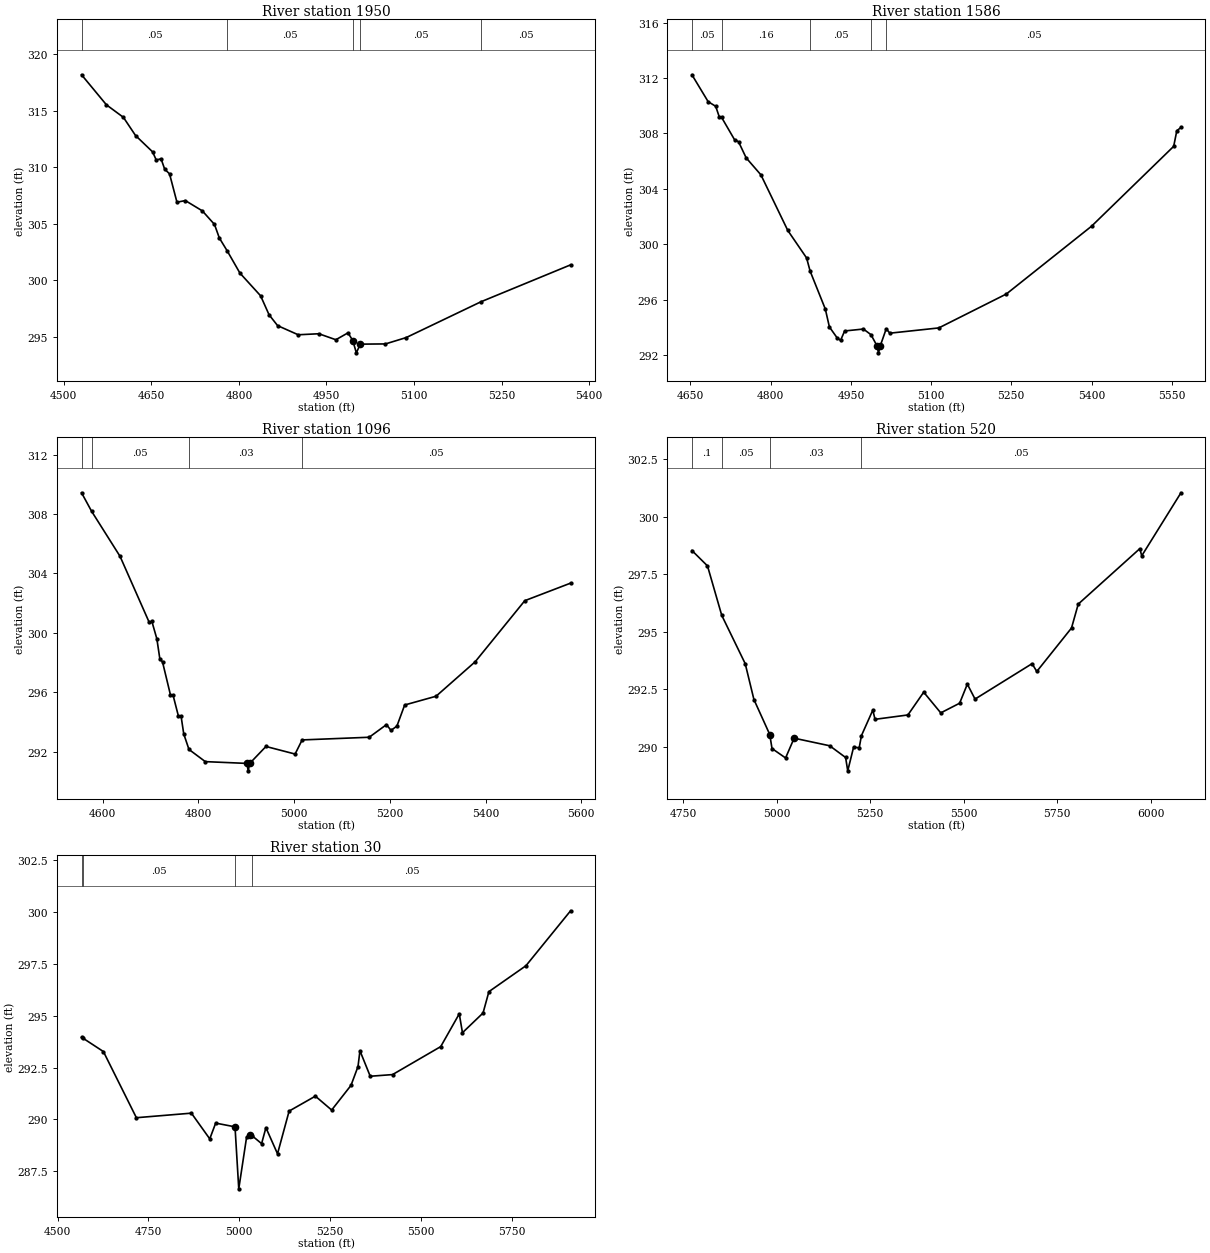
Type RM Length L Ch R = 1 ,1950    ,364,364,364
BEGIN DESCRIPTION:
UNT0421 IN CEDR CR 4.0
END DESCRIPTION:
XS GIS Cut Line= 3
       3621492.1     10301891.63      3621807.69      10302306.3
       3622016.5     10302544.28
#Sta/Elev= 30
  4530.5  318.19  4573.1  315.53  4602.2  314.42    4623  312.81  4652.1  311.37
  4658.4  310.65  4666.7  310.75  4672.9  309.83  4681.2  309.42  4693.9  306.91
  4708.3  307.05  4737.4  306.14  4758.2  304.94  4766.5  303.74  4780.3  302.57
  4801.8  300.63  4837.2  298.62  4851.7  296.94  4866.3  295.98  4901.6  295.17
    4937  295.26  4966.1  294.73  4986.9  295.34  4995.1  294.66  5001.2  293.57
    5008  294.34  5051.1  294.36  5086.5  294.92  5214.6  298.09  5368.2  301.36
#Mann= 5 ,-1 , 0
  4530.5     .05       0  4780.3     .05       0  4995.1    .035       0
    5008     .05       0  5214.6     .05       0
Bank Sta=4995.1,5008
XS Rating Curve= 0 ,0
Exp/Cntr=0.3,0.1

Type RM Length L Ch R = 1 ,1586    ,490,490,490
BEGIN DESCRIPTION:
UNT0421 IN CEDR CR 3.0
END DESCRIPTION:
XS GIS Cut Line= 3
      3621255.81     10302205.35      3621598.07     10302505.22
      3621992.14     10302741.66
#Sta/Elev= 30
  4652.7  312.24    4683   310.3  4697.2  309.96  4703.9  309.19  4708.2  309.16
  4732.4  307.55  4739.9   307.4  4754.1  306.24  4781.7  305.01    4832  300.99
  4867.1  299.01  4873.8  298.05  4902.2  295.31  4909.8  294.02  4924.1  293.24
  4930.7  293.05  4938.3  293.73  4973.4  293.87  4987.6  293.46  4998.9  292.65
  5001.6  292.15  5004.9  292.65  5016.1  293.89  5022.8  293.57  5114.4  293.95
  5240.7   296.4  5400.1   301.3  5553.7  307.07  5559.5  308.19  5567.3  308.44
#Mann= 5 ,-1 , 0
  4652.7     .05       0  4708.2     .16       0  4873.8     .05       0
  4987.6     .03       0  5016.1     .05       0
Bank Sta=4998.9,5004.9
XS Rating Curve= 0 ,0
Exp/Cntr=0.3,0.1

Type RM Length L Ch R = 1 ,1096    ,576,576,576
BEGIN DESCRIPTION:
UNT0421 IN CEDR CR 2.0
END DESCRIPTION:
XS GIS Cut Line= 3
       3621042.1     10302341.63      3621311.16     10302865.33
      3621692.19     10303071.71
#Sta/Elev= 30
  4555.6  309.43  4576.5  308.19  4636.1  305.15    4697  300.71  4702.6  300.77
    4713   299.6  4719.2  298.26  4724.8  298.05  4741.4  295.83    4747  295.79
  4757.9  294.42  4763.5  294.42  4769.2   293.2  4780.1  292.16  4814.2  291.34
  4901.1  291.22  4903.9  290.72  4907.1  291.22    4941  292.36  5001.9  291.85
  5016.6   292.8  5156.8  292.98  5192.9  293.83  5202.3  293.44  5214.7  293.73
  5230.9  295.15  5296.5  295.74  5378.3  298.06    5482  302.17  5577.7  303.35
#Mann= 4 ,-1 , 0
  4555.6      .1       0  4576.5     .05       0  4780.1     .03       0
  5016.6     .05       0
Bank Sta=4901.1,4907.1
XS Rating Curve= 0 ,0
Exp/Cntr=0.3,0.1

Type RM Length L Ch R = 1 ,520     ,490,490,490
BEGIN DESCRIPTION:
UNT0421 IN CEDR CR 1.0
END DESCRIPTION:
XS GIS Cut Line= 3
      3620704.45     10302491.91      3621077.91     10303072.63
      3621675.76     10303222.97
#Sta/Elev= 30
  4773.7  298.54  4815.3  297.87  4853.4  295.72  4916.1  293.62  4939.4  292.06
  4981.7  290.54  4987.7  289.93    5024  289.52  5046.8  290.38  5141.9  290.05
  5184.4  289.54  5190.1  288.96  5205.6  289.98  5220.8  289.97  5226.7  290.49
  5257.1   291.6    5263   291.2  5350.9  291.39  5393.1  292.38  5438.7  291.48
  5489.1   291.9  5509.7  292.73  5530.3  292.08  5682.7  293.62  5695.3  293.28
  5788.1  295.17  5806.1  296.21  5970.6  298.62  5975.8  298.31  6080.6  301.05
#Mann= 4 ,-1 , 0
  4773.7      .1       0  4853.4     .05       0  4981.7     .03       0
  5226.7     .05       0
Bank Sta=4981.7,5046.8
XS Rating Curve= 0 ,0
Exp/Cntr=0.3,0.1

Type RM Length L Ch R = 1 ,30      ,0,0,0
BEGIN DESCRIPTION:
UNT0421 IN CEDR CR 1.0111
END DESCRIPTION:
XS GIS Cut Line= 4
      3620622.68     10302672.06      3620665.24     10302998.98
      3621102.71     10303157.25      3621642.62     10303263.15
#Sta/Elev= 30
    4566  293.96  4570.4  293.91  4626.1  293.27  4716.8  290.08  4868.1   290.3
  4918.6  289.06  4934.9  289.82  4988.1  289.64  4998.4  286.65    5020  289.15
  5030.5  289.26  5035.8   289.2  5061.2  288.83  5073.1   289.6    5105  288.34
  5136.9   290.4  5209.1  291.12  5253.9  290.45  5307.1  291.64  5326.4  292.55
  5331.7  293.31    5360  292.08  5421.4  292.16  5553.9  293.51  5604.9  295.09
  5613.7  294.18  5670.3  295.13  5686.4  296.16  5788.3  297.41  5911.1  300.06
#Mann= 4 ,-1 , 0
    4566     .16       0  4570.4     .05       0  4988.1     .03       0
  5035.8     .05       0
Bank Sta=4988.1,5030.5
XS Rating Curve= 0 ,0
Exp/Cntr=0.3,0.1

Chan Stop Cuts=-1
Use User Specified Reach Order=0
Composite Channel Slope=5