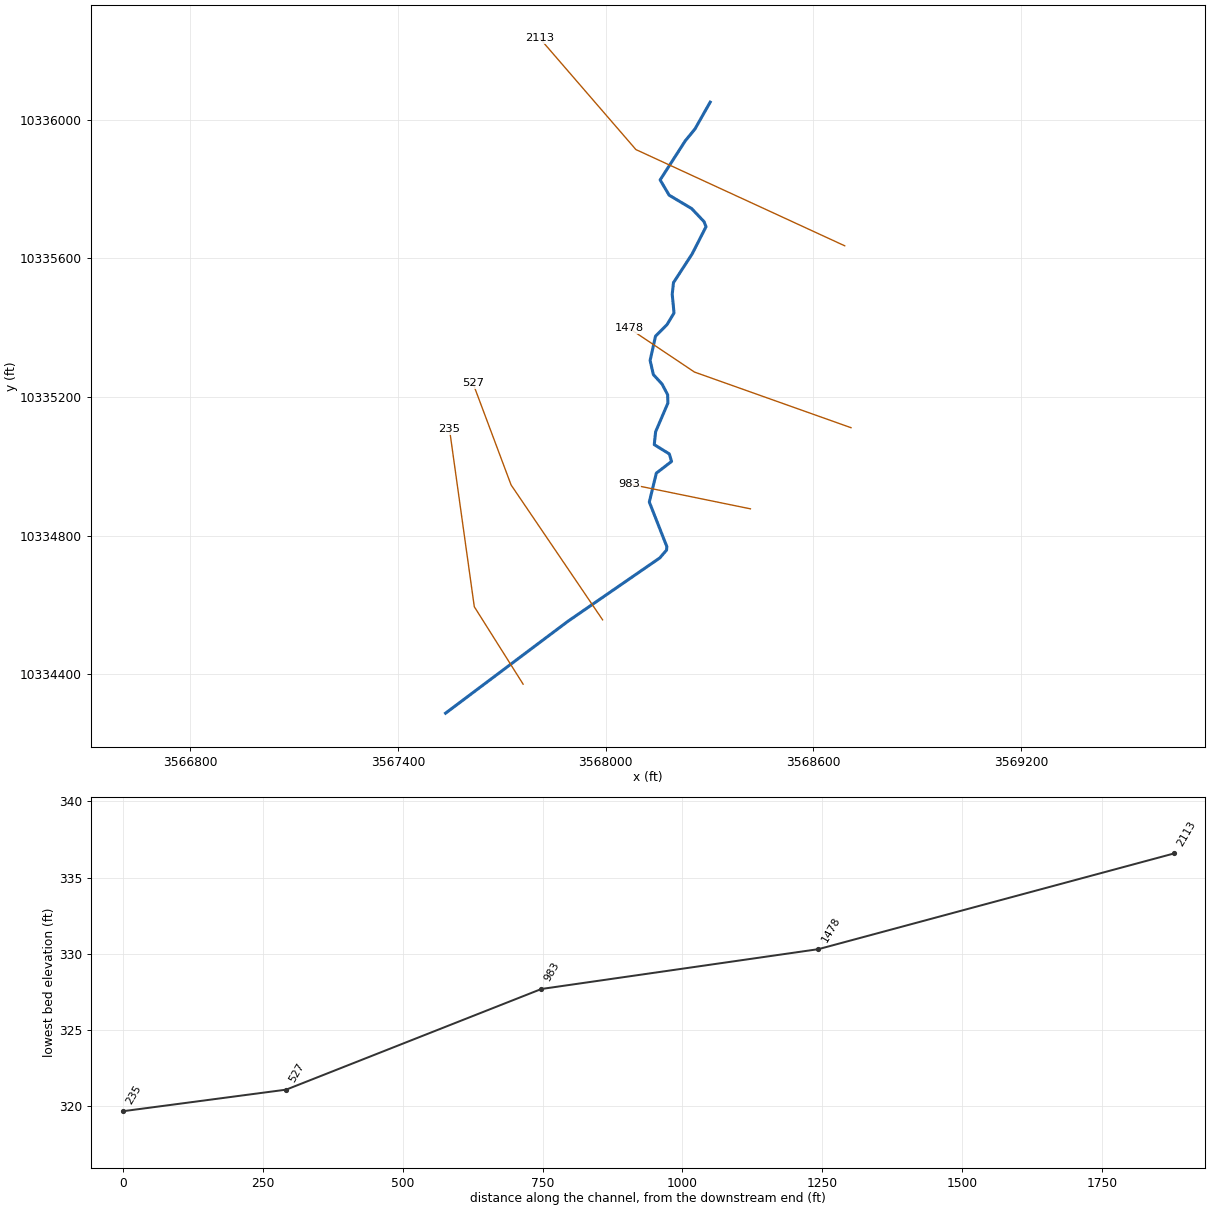
--- UNT04222 IN CEDR CR.prj (project) ---

Proj Title=UNT04222 IN CEDR CR Base Level Engineering
Current Plan=p01
Default Exp/Contr=0.3,0.1
English Units
Geom File=g01
Flow File=f01
Plan File=p01
Y Axis Title=Elevation
X Axis Title(PF)=Main Channel Distance
X Axis Title(XS)=Station
BEGIN DESCRIPTION:
UNT04222 IN CEDR CR
END DESCRIPTION:
DSS Export Rating Curves= 0
DSS Export Rating Curve Sorted= 0
DSS Export Volume Flow Curves= 0
DXF OffsetX= 0
DXF OffsetY= 0
DXF ScaleX= 1
DXF ScaleY= 10

--- UNT04222 IN CEDR CR.p01 (plan) ---

Plan Title=Multiple Run
Short Identifier=Multiple
Geom File=g01
Flow File=f01
Subcritical Flow
K Sum by GR= 0
Std Step Tol= 0.01
Critical Tol= 0.01
Num of Std Step Trials= 20
Max Error Tol= 0.3
Flow Tol Ratio= 0.001
Split Flow NTrial= 30
Split Flow Tol= 0.02
Split Flow Ratio= 0.02
Log Output Level= 0
Friction Slope Method= 1
Unsteady Friction Slope Method= 2
Unsteady Bridges Friction Slope Method= 1
Parabolic Critical Depth
Global Vel Dist=  1 , 1 , 1
Global Log Level= 0
CheckData=True
Encroach Param= -1, 0, 0, 0
BEGIN DESCRIPTION:
Multiple Run
END DESCRIPTION:

--- UNT04222 IN CEDR CR.f01 (steady flow) ---

Flow Title=Multiple
Program Version=4.10
Number of Profiles= 7
Profile Names=10-year,25-year,50-year,1pct_min,100-year,1pct_plu,500-year
River Rch & RM=UNT04222 IN CEDR,Reach-1         ,2113
     141     174     198     167     226     306     292
Boundary for River Rch & Prof#=UNT04222 IN CEDR,Reach-1         , 1
Up Type= 0
Dn Type= 3
Dn Slope=0.0108
Boundary for River Rch & Prof#=UNT04222 IN CEDR,Reach-1         , 2
Up Type= 0
Dn Type= 3
Dn Slope=0.0108
Boundary for River Rch & Prof#=UNT04222 IN CEDR,Reach-1         , 3
Up Type= 0
Dn Type= 3
Dn Slope=0.0108
Boundary for River Rch & Prof#=UNT04222 IN CEDR,Reach-1         , 4
Up Type= 0
Dn Type= 3
Dn Slope=0.0108
Boundary for River Rch & Prof#=UNT04222 IN CEDR,Reach-1         , 5
Up Type= 0
Dn Type= 3
Dn Slope=0.0108
Boundary for River Rch & Prof#=UNT04222 IN CEDR,Reach-1         , 6
Up Type= 0
Dn Type= 3
Dn Slope=0.0108
Boundary for River Rch & Prof#=UNT04222 IN CEDR,Reach-1         , 7
Up Type= 0
Dn Type= 3
Dn Slope=0.0108
DSS Import GetInterval= 0
DSS Import GetPeak= 0
DSS Import FillOption= 0

--- UNT04222 IN CEDR CR.g01 (geometry) ---

Geom Title=Existing Conditions
Program Version=4.10

River Reach=UNT04222 IN CEDR,Reach-1
Reach XY= 30
       3568301.7     10336051.22      3568257.75     10335973.71
      3568229.97     10335939.86      3568157.11     10335826.64
      3568183.09     10335782.66      3568248.28     10335743.84
      3568283.98     10335706.17      3568289.66     10335691.52
      3568249.46      10335612.8      3568195.66     10335530.09
      3568192.01     10335496.64      3568197.22     10335442.51
      3568177.22     10335409.26      3568143.78     10335375.54
      3568128.13     10335305.54      3568137.54     10335264.61
       3568162.8     10335237.09      3568178.77     10335206.53
      3568179.46     10335182.23      3568144.05     10335099.59
      3568140.12     10335062.41      3568183.62     10335035.64
      3568190.14      10335013.9       3568146.1     10334980.12
      3568125.83     10334896.71      3568176.48     10334768.01
      3568175.67     10334758.06      3568156.11     10334735.34
      3567890.66      10334552.4      3567537.19     10334287.12

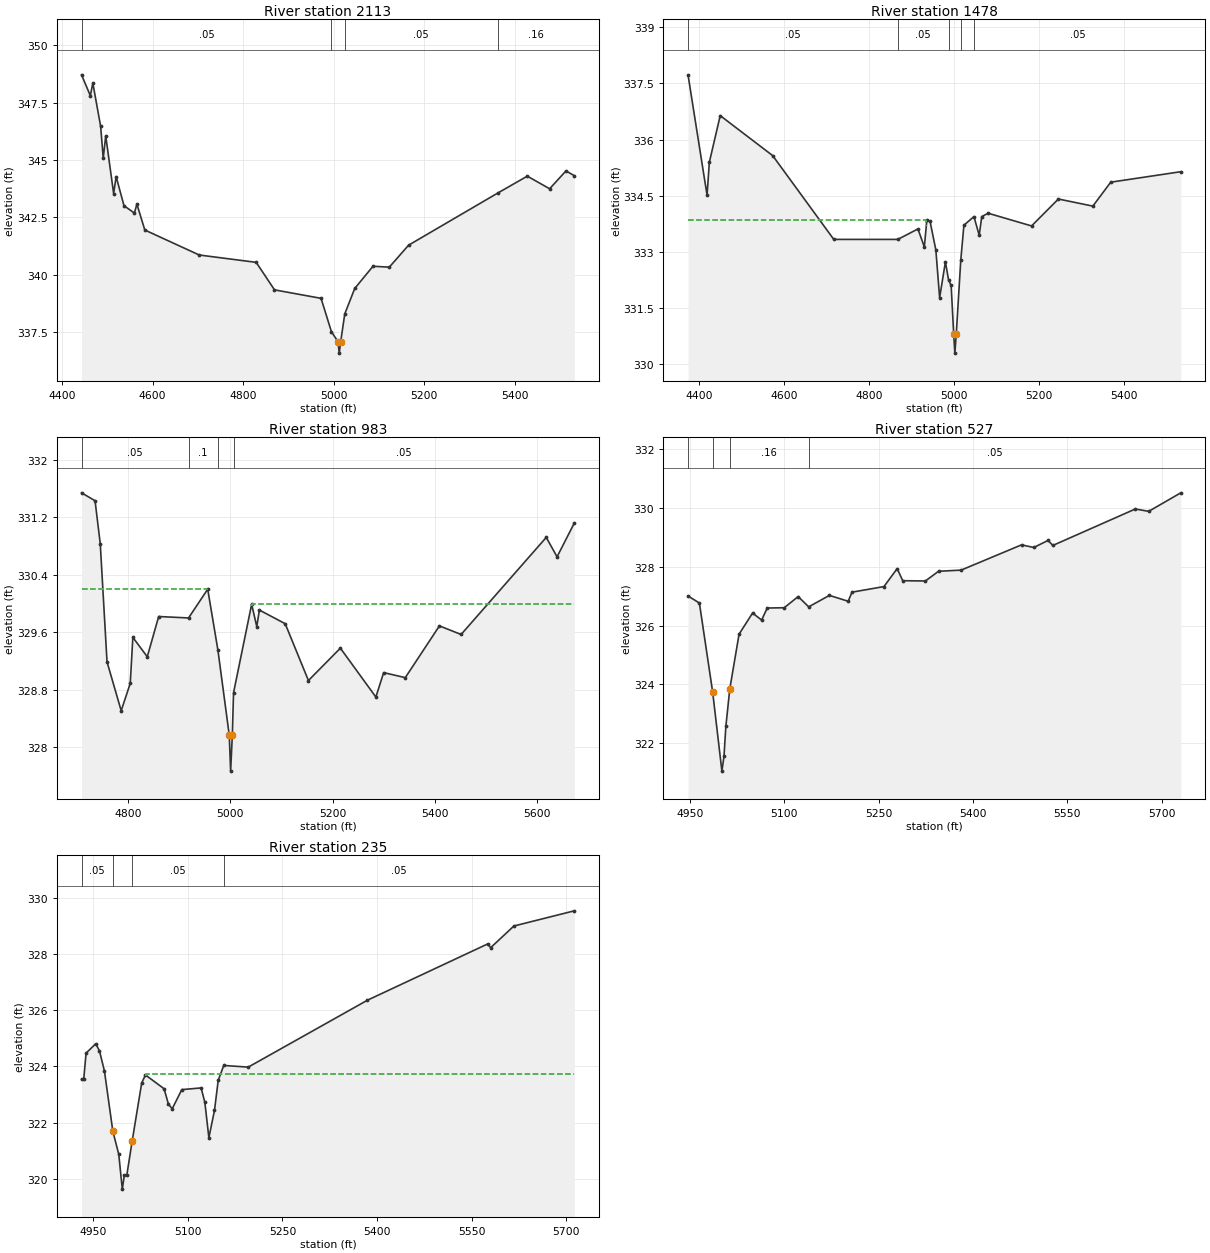
Type RM Length L Ch R = 1 ,2113    ,635,635,635
BEGIN DESCRIPTION:
UNT04222 IN CEDR CR 3.0
END DESCRIPTION:
XS GIS Cut Line= 3
       3568690.4     10335636.51      3568087.11     10335914.28
      3567809.33     10336235.46
#Sta/Elev= 30
  4443.1  348.72  4462.5  347.81    4468  348.36  4485.3  346.47    4491  345.08
  4496.5  346.06    4514  343.54  4519.5  344.28  4536.9  343.01  4559.9  342.69
  4565.4  343.08  4582.9  341.95  4703.2  340.86    4829  340.54  4869.4  339.34
  4972.3  338.97  4995.3  337.51  5009.7  337.08  5012.5  336.58  5015.7  337.08
  5024.7  338.29  5046.7   339.4  5087.1  340.37  5123.1  340.33  5165.8  341.29
  5362.5  343.56    5428   344.3  5477.4  343.75  5513.5  344.53  5531.9  344.32
#Mann= 4 ,-1 , 0
  4443.1     .05       0  4995.3    .035       0  5024.7     .05       0
  5362.5     .16       0
Bank Sta=5009.7,5015.7
XS Rating Curve= 0 ,0
Exp/Cntr=0.3,0.1

Type RM Length L Ch R = 1 ,1478    ,495,495,495
BEGIN DESCRIPTION:
UNT04222 IN CEDR CR 2.0
END DESCRIPTION:
XS GIS Cut Line= 3
      3568708.57     10335111.36      3568256.38     10335271.92
      3568067.26    10335398.485
#Sta/Elev= 30
  4374.6  337.73  4419.4  334.51  4424.7  335.39  4450.3  336.64  4573.7  335.57
  4717.4  333.33  4867.9  333.33  4915.3  333.61  4930.3  333.13  4936.3  333.85
  4943.8  333.81  4957.4  333.05  4966.3  331.77  4979.9  332.73  4987.4  332.24
  4993.4   332.1  4999.4  330.79  5002.1  330.29  5005.4  330.79    5016  332.77
  5023.4  333.71    5047  333.94  5059.4  333.44  5065.4  333.94  5080.4  334.03
  5182.5  333.69  5245.6  334.41  5326.6  334.22  5368.7  334.86  5533.4  335.14
#Mann= 5 ,-1 , 0
  4374.6     .05       0  4867.9     .05       0  4987.4     .03       0
    5016      .1       0    5047     .05       0
#XS Ineff= 2 , 0
            4935  333.86
Permanent Ineff=
       F       F
Bank Sta=4999.4,5005.4
XS Rating Curve= 0 ,0
Exp/Cntr=0.3,0.1

Type RM Length L Ch R = 1 ,983     ,456,456,456
BEGIN DESCRIPTION:
Mapping XS 10a9557f
END DESCRIPTION:
XS GIS Cut Line= 2
      3568417.99     10334877.08     3568069.067    10334948.363
#Sta/Elev= 30
  4709.2  331.54  4735.6  331.43  4745.8  330.83    4759  329.19  4786.7  328.51
  4804.4  328.89  4809.5  329.53  4837.7  329.26    4860  329.82  4918.4   329.8
  4955.9   330.2  4975.9  329.35    4998  328.17  5000.7  327.67    5004  328.17
  5006.4  328.76  5041.8  329.99  5051.8  329.68  5056.9  329.91  5107.4  329.72
  5152.8  328.93  5215.3  329.38  5284.7   328.7  5299.9  329.04  5342.2  328.97
    5409  329.69  5451.3  329.57  5617.8  330.92    5639  330.65  5672.7  331.12
#Mann= 4 ,-1 , 0
  4709.2     .05       0  4918.4      .1       0  4975.9     .03       0
  5006.4     .05       0
#XS Ineff= 2 , 0
         4955.23   330.2  5042.5          329.99
Permanent Ineff=
       F       F
Bank Sta=4998,5004
XS Rating Curve= 0 ,0
Exp/Cntr=0.3,0.1

Type RM Length L Ch R = 1 ,527     ,292,292,292
BEGIN DESCRIPTION:
Mapping XS e7fe7ee5
END DESCRIPTION:
XS GIS Cut Line= 3
      3567990.82     10334556.68      3567726.49       10334946.
      3567616.48     10335239.38
#Sta/Elev= 30
  4946.7  327.01  4964.8  326.77  4985.9  323.74  5000.6  321.05  5003.9  321.55
  5006.9  322.57  5013.1  323.84  5027.9  325.71  5049.4  326.43  5063.8  326.19
  5072.7   326.6  5099.8  326.61  5121.9  326.99  5138.7  326.64  5171.6  327.03
  5201.5  326.83  5207.6  327.14  5258.4  327.33  5279.4  327.94  5288.3  327.53
  5324.3  327.52  5345.2  327.85  5381.2  327.89  5477.3  328.75  5496.8  328.66
  5519.4   328.9  5527.1  328.73  5658.3  329.97  5679.6  329.89  5730.6  330.52
#Mann= 4 ,-1 , 0
  4946.7     .05       0  4985.9     .03       0  5013.1     .16       0
  5138.7     .05       0
Bank Sta=4985.9,5013.1
XS Rating Curve= 0 ,0
Exp/Cntr=0.3,0.1

Type RM Length L Ch R = 1 ,235     ,0,0,0
BEGIN DESCRIPTION:
UNT04222 IN CEDR CR 1.0
END DESCRIPTION:
XS GIS Cut Line= 3
      3567761.21     10334370.93      3567620.16     10334594.44
      3567548.55     10335106.56
#Sta/Elev= 30
  4931.4  323.53  4934.8  323.53  4938.6  324.47  4953.9   324.8  4959.8  324.55
  4967.7  323.83    4981  321.69  4990.4  320.87    4996  319.63  4999.3  320.13
  5003.2  320.13  5011.6  321.33  5026.8  323.41  5032.8  323.69  5062.3   323.2
  5069.2  322.65  5075.2  322.49  5090.4  323.17    5121  323.23  5126.9  322.72
  5133.3  321.46  5142.2  322.43  5148.1   323.5  5156.9  324.03  5195.7  323.97
  5384.7  326.35  5575.2  328.35  5580.2  328.22    5617  328.99  5712.8  329.53
#Mann= 4 ,-1 , 0
  4931.4     .05       0    4981     .03       0  5011.6     .05       0
  5156.9     .05       0
#XS Ineff= 2 , 0
                         5034.09          323.74
Permanent Ineff=
       F       F
Bank Sta=4981,5011.6
XS Rating Curve= 0 ,0
Exp/Cntr=0.3,0.1

Chan Stop Cuts=-1
Use User Specified Reach Order=0
Composite Channel Slope=5