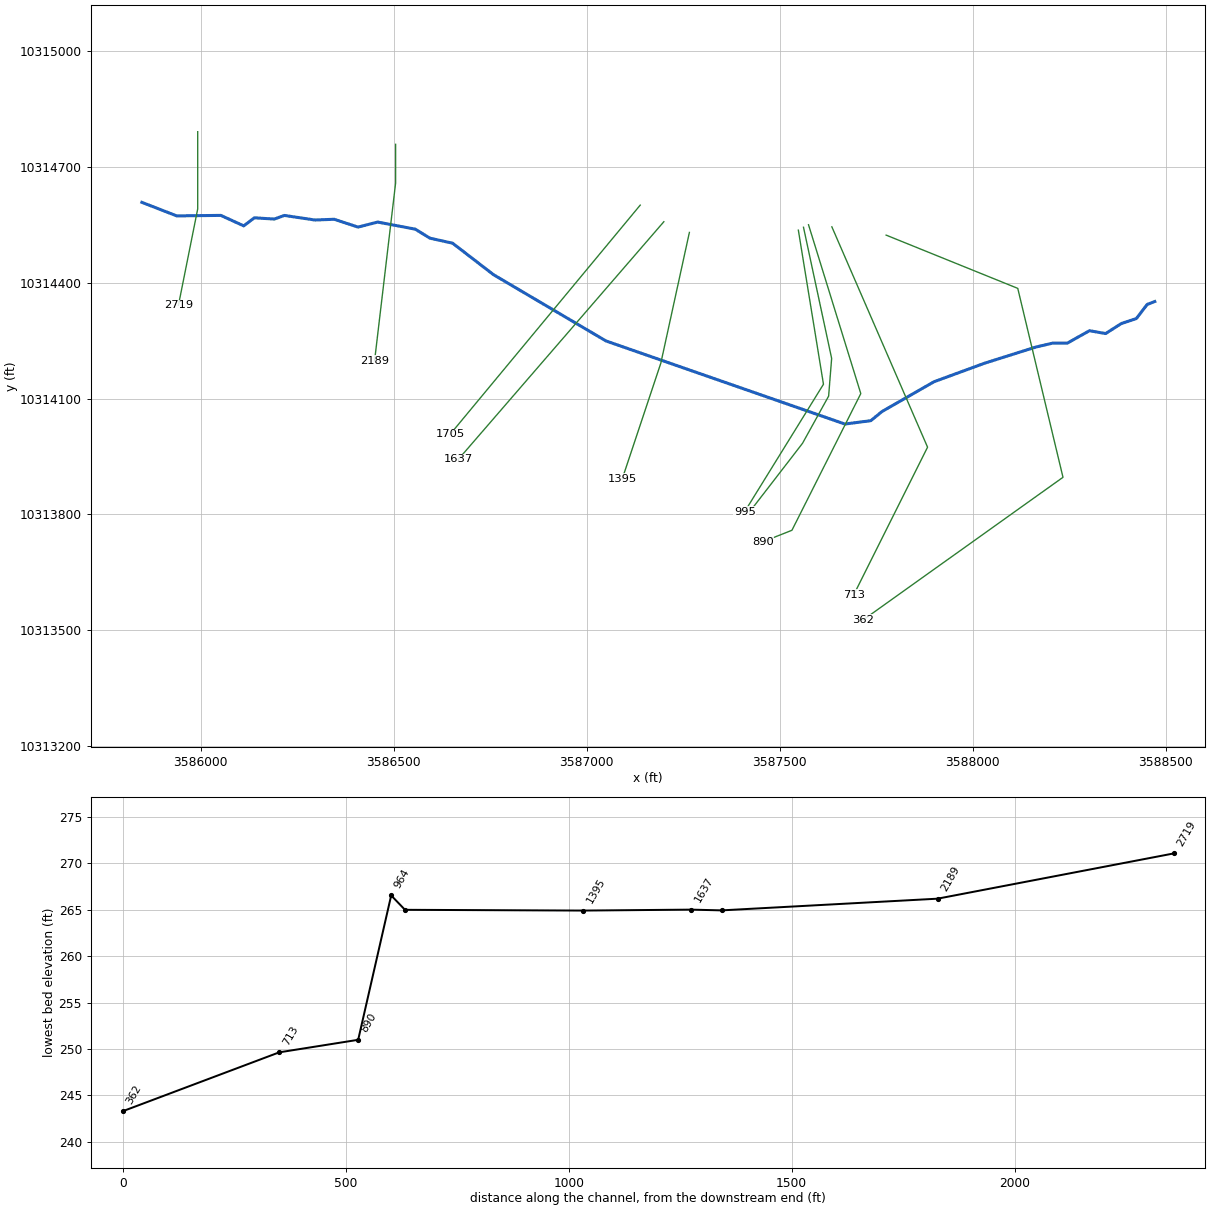
--- UNT04285 IN CEDR CR.prj (project) ---

Proj Title=UNT04285 IN CEDR CR Base Level Engineering
Current Plan=p01
Default Exp/Contr=0.3,0.1
English Units
Geom File=g01
Flow File=f01
Plan File=p01
Y Axis Title=Elevation
X Axis Title(PF)=Main Channel Distance
X Axis Title(XS)=Station
BEGIN DESCRIPTION:
UNT04285 IN CEDR CR
END DESCRIPTION:
DSS Export Rating Curves= 0
DSS Export Rating Curve Sorted= 0
DSS Export Volume Flow Curves= 0
DXF OffsetX= 0
DXF OffsetY= 0
DXF ScaleX= 1
DXF ScaleY= 10

--- UNT04285 IN CEDR CR.p01 (plan) ---

Plan Title=Multiple Run
Short Identifier=Multiple
Geom File=g01
Flow File=f01
Subcritical Flow
K Sum by GR= 0
Std Step Tol= 0.01
Critical Tol= 0.01
Num of Std Step Trials= 20
Max Error Tol= 0.3
Flow Tol Ratio= 0.001
Split Flow NTrial= 30
Split Flow Tol= 0.02
Split Flow Ratio= 0.02
Log Output Level= 0
Friction Slope Method= 1
Unsteady Friction Slope Method= 2
Unsteady Bridges Friction Slope Method= 1
Parabolic Critical Depth
Global Vel Dist=  1 , 1 , 1
Global Log Level= 0
CheckData=True
Encroach Param= -1, 0, 0, 0
BEGIN DESCRIPTION:
Multiple Run
END DESCRIPTION:

--- UNT04285 IN CEDR CR.f01 (steady flow) ---

Flow Title=Multiple
Number of Profiles=7
Profile Names=10-year,25-year,50-year,1pct_min,100-year,1pct_plu,500-year
River Rch & RM= UNT04285 IN CEDR,Reach-1,2719
     296     385     455     396     536     725     743
Boundary for River Rch & Prof#=UNT04285 IN CEDR,Reach-1,1
Up Type=0
Dn Type=3
Dn Slope=0.005
Boundary for River Rch & Prof#=UNT04285 IN CEDR,Reach-1,2
Up Type=0
Dn Type=3
Dn Slope=0.005
Boundary for River Rch & Prof#=UNT04285 IN CEDR,Reach-1,3
Up Type=0
Dn Type=3
Dn Slope=0.005
Boundary for River Rch & Prof#=UNT04285 IN CEDR,Reach-1,4
Up Type=0
Dn Type=3
Dn Slope=0.005
Boundary for River Rch & Prof#=UNT04285 IN CEDR,Reach-1,5
Up Type=0
Dn Type=3
Dn Slope=0.005
Boundary for River Rch & Prof#=UNT04285 IN CEDR,Reach-1,6
Up Type=0
Dn Type=3
Dn Slope=0.005
Boundary for River Rch & Prof#=UNT04285 IN CEDR,Reach-1,7
Up Type=0
Dn Type=3
Dn Slope=0.005

--- UNT04285 IN CEDR CR.g01 (geometry) ---

Geom Title=Existing Conditions
Program Version=4.10

River Reach=UNT04285 IN CEDR,Reach-1
Reach XY= 30
      3585847.28     10314608.61      3585937.67     10314573.47
      3586051.97     10314574.75      3586111.53     10314547.59
      3586138.73     10314568.47      3586190.74     10314565.22
      3586216.49     10314574.65      3586296.17     10314562.73
      3586345.74     10314564.72       3586407.6     10314544.41
      3586458.52     10314557.46        3586556.     10314539.02
       3586593.8     10314515.73      3586652.56     10314502.73
       3586758.4     10314421.26      3587050.07     10314249.39
      3587668.99     10314034.11      3587736.27     10314042.79
      3587765.56     10314066.66      3587900.11      10314143.7
      3588030.32     10314191.45      3588163.91     10314233.55
      3588208.36     10314243.96      3588245.67     10314243.81
      3588303.04     10314275.97      3588344.69     10314268.54
      3588385.55     10314294.57      3588424.33     10314307.39
       3588452.5     10314344.01      3588472.11     10314351.64

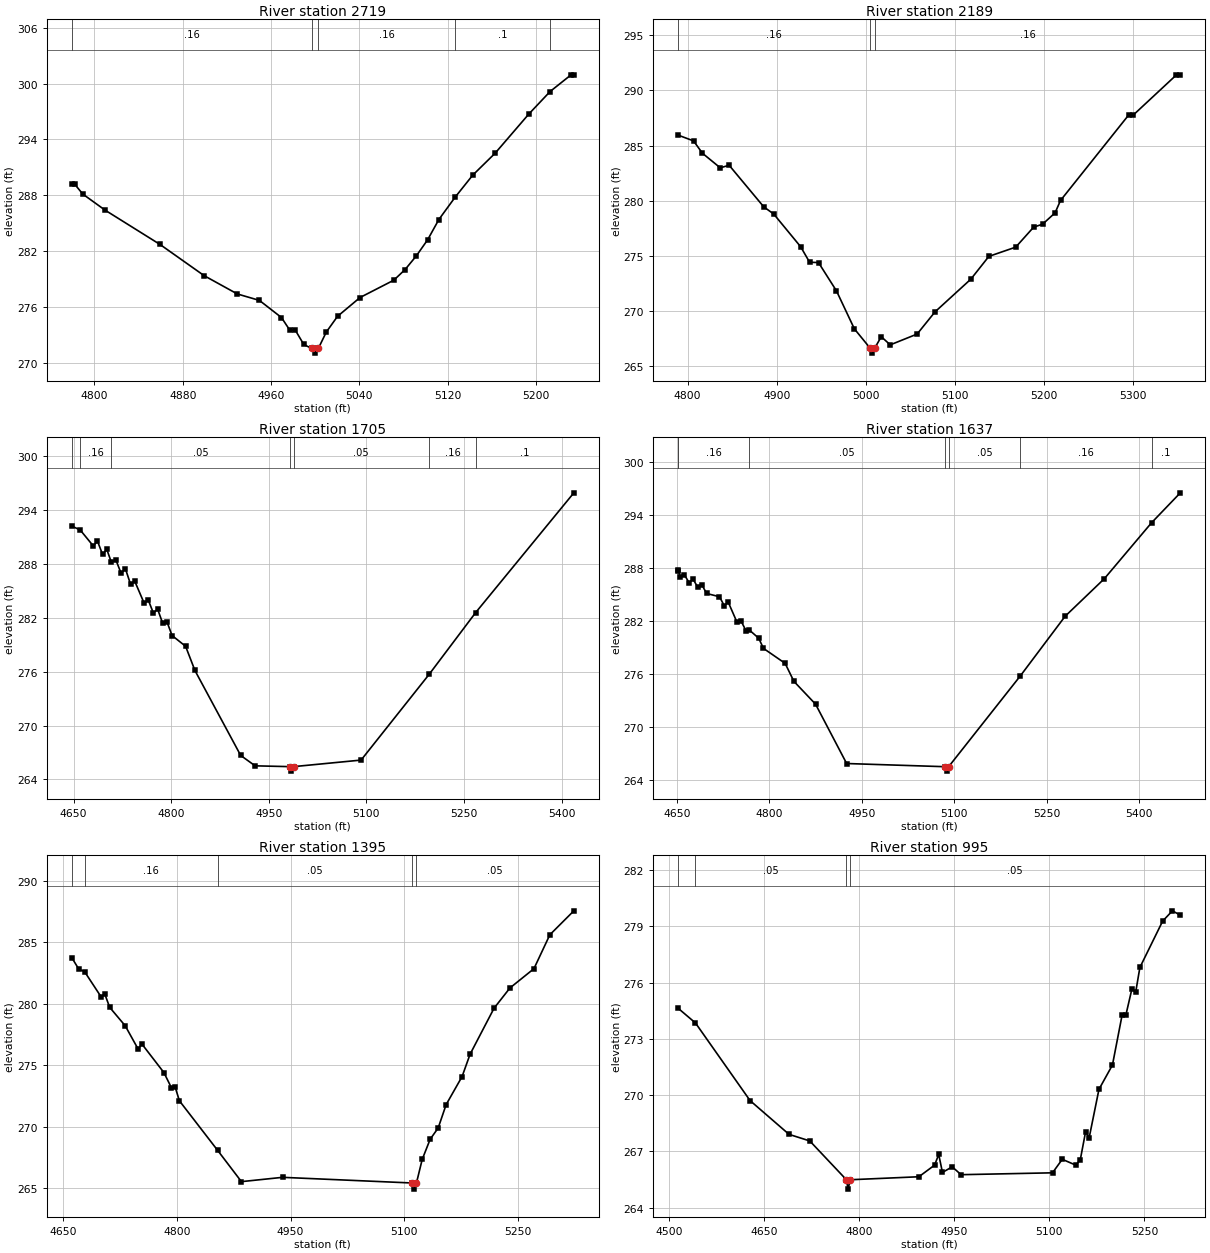
Type RM Length L Ch R = 1 ,2719    ,530,530,530
BEGIN DESCRIPTION:
UNT04285 IN CEDR CR 6.0
END DESCRIPTION:
XS GIS Cut Line= 3
      3585992.11     10314791.63      3585992.11     10314591.64
      3585942.11     10314341.68
#Sta/Elev= 30
  4779.5  289.22    4782  289.22  4789.5  288.14  4809.5  286.43  4859.5  282.73
  4899.5  279.38  4929.5  277.42  4949.5  276.73  4969.5  274.89    4977  273.54
    4982  273.54  4989.7     272  4996.9  271.57  4999.6  271.07  5002.9  271.57
  5010.1  273.33  5020.3  275.02  5040.7  277.04  5071.3   278.9  5081.5  280.04
  5091.7  281.51  5101.9  283.23  5112.1  285.41  5126.8   287.8  5142.7  290.16
  5163.1  292.53  5193.6  296.73  5212.9  299.15  5231.9  300.94  5234.4  300.94
#Mann= 5 ,-1 , 0
  4779.5     .16       0  4996.9     .07       0  5002.9     .16       0
  5126.8      .1       0  5212.9     .05       0
Bank Sta=4996.9,5002.9
XS Rating Curve= 0 ,0
Exp/Cntr=0.3,0.1

Type RM Length L Ch R = 1 ,2189    ,484,484,484
BEGIN DESCRIPTION:
UNT04285 IN CEDR CR 5.0
END DESCRIPTION:
XS GIS Cut Line= 3
      3586504.95     10314758.88      3586504.95     10314658.83
      3586450.44     10314197.99
#Sta/Elev= 30
  4789.4  285.95  4806.6  285.43  4816.6  284.31  4836.6  282.99  4846.6  283.22
  4885.5  279.45  4896.7   278.8  4926.9  275.84    4937  274.43    4947   274.4
  4967.2  271.83  4987.3  268.39  5004.5  266.69  5007.2  266.19  5010.5  266.69
  5017.5  267.68  5027.6  266.94  5057.8  267.92  5077.9  269.93  5118.2   272.9
  5138.4  274.96  5168.6   275.8  5188.7  277.61  5198.8  277.88  5212.8  278.91
  5218.9  280.03  5295.6  287.79  5300.6  287.77  5349.2  291.42  5353.5  291.42
#Mann= 3 ,-1 , 0
  4789.4     .16       0  5004.5     .07       0  5010.5     .16       0
Bank Sta=5004.5,5010.5
XS Rating Curve= 0 ,0
Exp/Cntr=0.3,0.1

Type RM Length L Ch R = 1 ,1705    ,68,68,68
BEGIN DESCRIPTION:
UNT04285 IN CEDR CR 4.0
END DESCRIPTION:
XS GIS Cut Line= 2
      3587138.74      10314601.3      3586646.31     10314007.52
#Sta/Elev= 30
  4647.3  292.22  4660.3  291.78  4680.3  290.01  4686.8  290.54  4694.6  289.06
  4701.1  289.63  4707.9  288.23  4715.4  288.39  4723.2  286.94  4729.7  287.47
  4737.6  285.74  4744.1  286.07  4758.4  283.65  4764.9  283.97  4772.7  282.53
  4779.2  282.97  4787.1  281.37  4793.6  281.55  4801.4  280.03  4822.2  278.83
  4836.5  276.14  4906.8  266.68    4929  265.52    4982  265.43  4984.7  264.93
    4988  265.43  5091.8  266.16  5196.3   275.7  5267.9  282.59  5418.7  295.92
#Mann= 7 ,-1 , 0
  4647.3     .05       0  4660.3     .16       0  4707.9     .05       0
    4982     .03       0    4988     .05       0  5196.3     .16       0
  5267.9      .1       0
Bank Sta=4982,4988
XS Rating Curve= 0 ,0
Exp/Cntr=0.3,0.1

Type RM Length L Ch R = 1 ,1637    ,242,242,242
BEGIN DESCRIPTION:
Mapping XS fe28ed39
END DESCRIPTION:
XS GIS Cut Line= 2
      3587199.94     10314558.33      3586667.39     10313942.44
#Sta/Elev= 30
  4652.1  287.72  4652.5  287.63  4655.4  286.94    4662  287.22  4669.6  286.33
  4676.2  286.71  4683.9  285.79  4690.5  286.07  4698.1   285.1    4719  284.73
  4726.7  283.72  4733.3   284.1  4747.5  281.83  4754.1  281.97  4761.8  280.91
  4766.7  281.01  4782.6  280.04  4790.3  278.89  4825.4   277.2  4839.7  275.16
  4874.8  272.58  4925.2  265.87  5084.6  265.51  5087.3  265.01  5090.6  265.51
    5207  275.79  5279.5  282.52  5343.1  286.77  5419.6  293.09  5466.3  296.48
#Mann= 7 ,-1 , 0
  4652.1     .05       0  4652.5     .16       0  4766.7     .05       0
  5084.6     .03       0  5090.6     .05       0    5207     .16       0
  5419.6      .1       0
Bank Sta=5084.6,5090.6
XS Rating Curve= 0 ,0
Exp/Cntr=0.3,0.1

Type RM Length L Ch R = 1 ,1395    ,400,400,400
BEGIN DESCRIPTION:
UNT04285 IN CEDR CR 3.0
END DESCRIPTION:
XS GIS Cut Line= 3
      3587266.17     10314530.58      3587192.11     10314191.64
      3587092.09     10313891.61
#Sta/Elev= 30
    4661  283.76  4670.2  282.83    4678  282.61  4699.6  280.58  4704.7  280.78
  4711.1  279.71  4731.6  278.21  4748.6  276.32  4753.7  276.72  4782.7   274.4
  4792.5  273.18  4797.6  273.21  4803.2   272.1  4853.5  268.08  4885.1  265.52
  4939.5  265.87  5110.3  265.41  5113.1  264.91  5116.3  265.41  5123.9  267.33
  5134.4  268.97    5145  269.89  5155.5  271.79  5176.6  274.08  5187.1  275.89
  5218.8  279.64  5239.8  281.29  5271.5  282.86  5292.5  285.62  5324.2  287.57
#Mann= 5 ,-1 , 0
    4661     .05       0    4678     .16       0  4853.5     .05       0
  5110.3     .03       0  5116.3     .05       0
Bank Sta=5110.3,5116.3
XS Rating Curve= 0 ,0
Exp/Cntr=0.3,0.1

Type RM Length L Ch R = 1 ,995     ,31,31,31
BEGIN DESCRIPTION:
UNT04285 IN CEDR CR 2.0
END DESCRIPTION:
XS GIS Cut Line= 3
      3587548.53     10314536.51      3587613.63     10314137.21
      3587409.65     10313807.36
#Sta/Elev= 30
  4514.3  274.63  4541.5  273.85  4627.7  269.71  4689.2  267.91  4721.9  267.56
  4779.7  265.49  4782.4  264.99  4785.7  265.49  4894.1  265.65  4918.9  266.27
  4925.4  266.84  4931.3  265.88  4946.7  266.18  4960.7  265.76    5105  265.86
  5120.4  266.58  5141.7  266.27  5148.8  266.55  5157.1  268.03  5162.9  267.74
  5178.3  270.31  5199.6  271.61    5215   274.3  5220.9  274.29  5230.4  275.68
  5236.2  275.48  5242.9  276.81  5278.8  279.28  5294.2  279.83  5306.7   279.6
#Mann= 4 ,-1 , 0
  4514.3      .1       0  4541.5     .05       0  4779.7     .03       0
  4785.7     .05       0
Bank Sta=4779.7,4785.7
XS Rating Curve= 0 ,0
Exp/Cntr=0.3,0.1

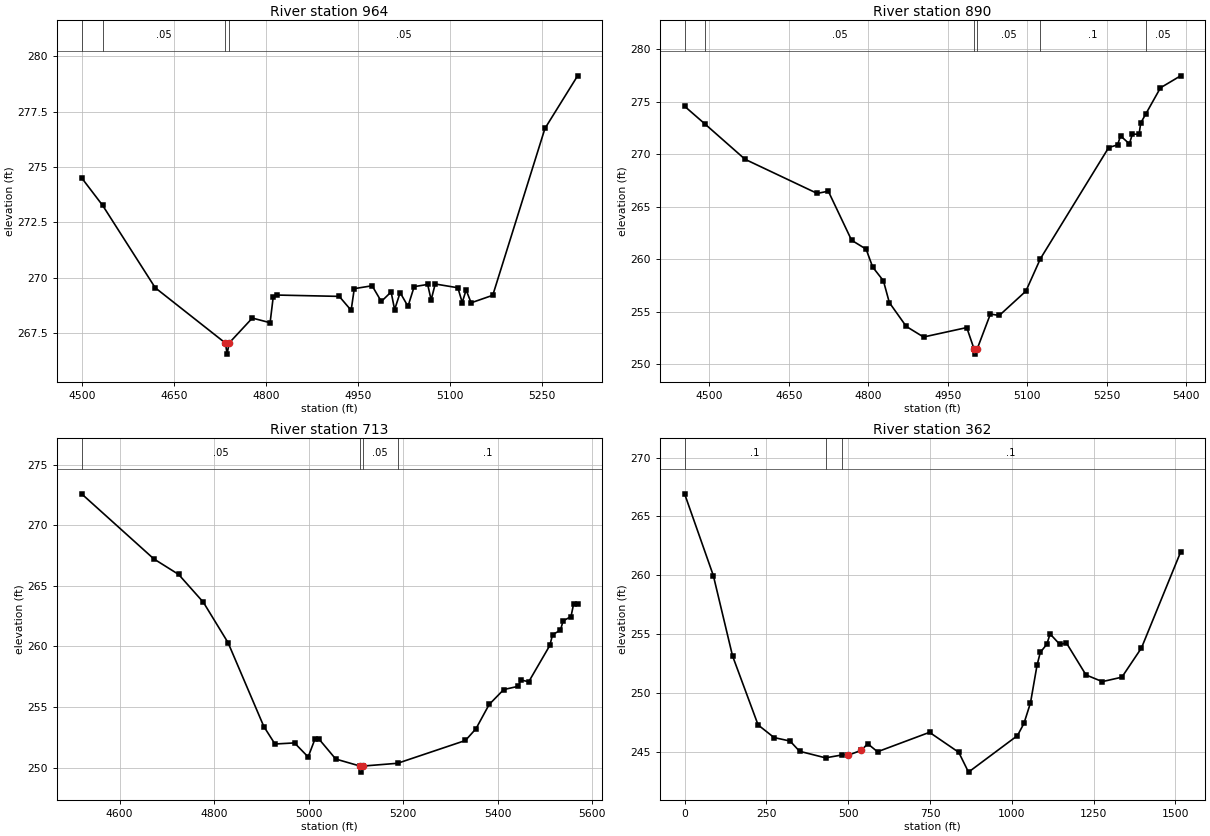
Type RM Length L Ch R = 1 ,964     ,74,74,74
BEGIN DESCRIPTION:
Mapping XS 9cb65bc9
END DESCRIPTION:
XS GIS Cut Line= 5
      3587561.89     10314543.98      3587634.81     10314204.13
      3587626.99     10314106.47      3587559.29     10313984.08
      3587422.59     10313807.03
#Sta/Elev= 30
  4499.1  274.51  4533.5  273.26  4619.2  269.54  4733.7  267.04  4736.5  266.54
  4739.7  267.04  4777.6  268.17  4806.6  267.96  4811.7  269.13  4818.5  269.21
  4919.4  269.15  4938.8  268.52  4943.9   269.5    4973  269.63    4988  268.92
    5004  269.35  5009.7  268.55  5018.7  269.32  5031.5   268.7  5041.6  269.59
  5063.6  269.69  5069.3  268.99  5075.9  269.71  5112.9  269.54    5120  268.87
  5126.3  269.44  5134.5  268.86  5169.8   269.2  5254.9  276.74  5308.2  279.12
#Mann= 4 ,-1 , 0
  4499.1      .1       0  4533.5     .05       0  4733.7     .03       0
  4739.7     .05       0
Bank Sta=4733.7,4739.7
XS Rating Curve= 0 ,0
Exp/Cntr=0.3,0.1

Type RM Length L Ch R = 1 ,890     ,177,177,177
BEGIN DESCRIPTION:
Mapping XS e03ce96b
END DESCRIPTION:
XS GIS Cut Line= 4
      3587574.91     10314550.49      3587710.33     10314112.98
      3587531.94     10313758.82      3587456.78     10313729.01
#Sta/Elev= 30
  4453.7  274.59  4492.6  272.88  4567.7  269.54  4703.7  266.29  4724.7   266.5
  4768.6  261.83    4796  260.98  4808.4  259.27  4828.6  257.97  4839.8  255.89
  4871.7  253.62  4904.3  252.61  4985.8  253.51  4999.5  251.48  5002.2  250.98
  5005.5  251.48  5030.4   254.8  5047.1  254.66  5097.3  256.98  5124.6  260.06
  5253.5  270.66  5270.2  270.91  5275.8  271.77  5292.5  271.01  5298.1  271.94
  5310.8  271.92  5313.8  272.99  5323.8  273.89  5351.1  276.35  5389.1  277.49
#Mann= 6 ,-1 , 0
  4453.7      .1       0  4492.6     .05       0  4999.5     .03       0
  5005.5     .05       0  5124.6      .1       0  5323.8     .05       0
Bank Sta=4999.5,5005.5
XS Rating Curve= 0 ,0
Exp/Cntr=0.3,0.1

Type RM Length L Ch R = 1 ,713     ,351,351,351
BEGIN DESCRIPTION:
UNT04285 IN CEDR CR 1.0
END DESCRIPTION:
XS GIS Cut Line= 3
      3587635.34     10314545.17      3587883.35     10313974.13
      3587692.11     10313591.64
#Sta/Elev= 30
  4519.4  272.59  4672.4  267.22  4724.8  265.94  4777.1  263.65  4829.5  260.31
  4905.3  253.39  4928.8  251.95  4970.2  252.04  4999.1  250.88  5013.9   252.4
  5022.6  252.33  5057.5  250.71    5109  250.13  5111.7  249.63    5115  250.13
  5188.4  250.36    5332  252.24  5354.4  253.21  5382.3  255.21  5413.1  256.44
  5443.8  256.71  5449.4  257.23  5466.2  257.09  5510.9  260.09  5516.5  260.97
  5533.3  261.34  5538.9  262.11  5555.6  262.46  5561.2  263.52  5569.6   263.5
#Mann= 4 ,-1 , 0
  4519.4     .05       0    5109    .035       0    5115     .05       0
  5188.4      .1       0
Bank Sta=5109,5115
XS Rating Curve= 0 ,0
Exp/Cntr=0.3,0.1

Type RM Length L Ch R = 1 ,362     ,0,0,0
XS GIS Cut Line= 4
     3587775.948    10314523.663     3588117.094    10314385.642
     3588234.281    10313896.059     3587716.052    10313526.267
#Sta/Elev= 30
       0266.923787.88672259.9746146.4779 253.159224.5994247.2929273.4254246.2179
322.2513245.9221351.5469245.0518430.6761244.4958480.3419244.7351500.2082244.7219
539.9408245.1329559.8071245.6916589.6065245.0118748.5369246.6626837.9352244.9636
867.7347243.28151017.308246.38321037.256247.42391057.205249.17161077.153252.3568
1087.127253.45511107.076254.1442 1117.05255.02321146.973 254.1281166.922254.2572
1226.767251.53941276.639250.97041336.484251.3473 1396.33253.82911516.021261.9764
#Mann= 3 ,-1 , 0
       0      .1       0430.6761     .05       0480.3419      .1       0
Bank Sta=500.2082,539.9408
XS Rating Curve= 0 ,0
Exp/Cntr=0.3,0.1

Chan Stop Cuts=-1
Use User Specified Reach Order=0
Composite Channel Slope=5