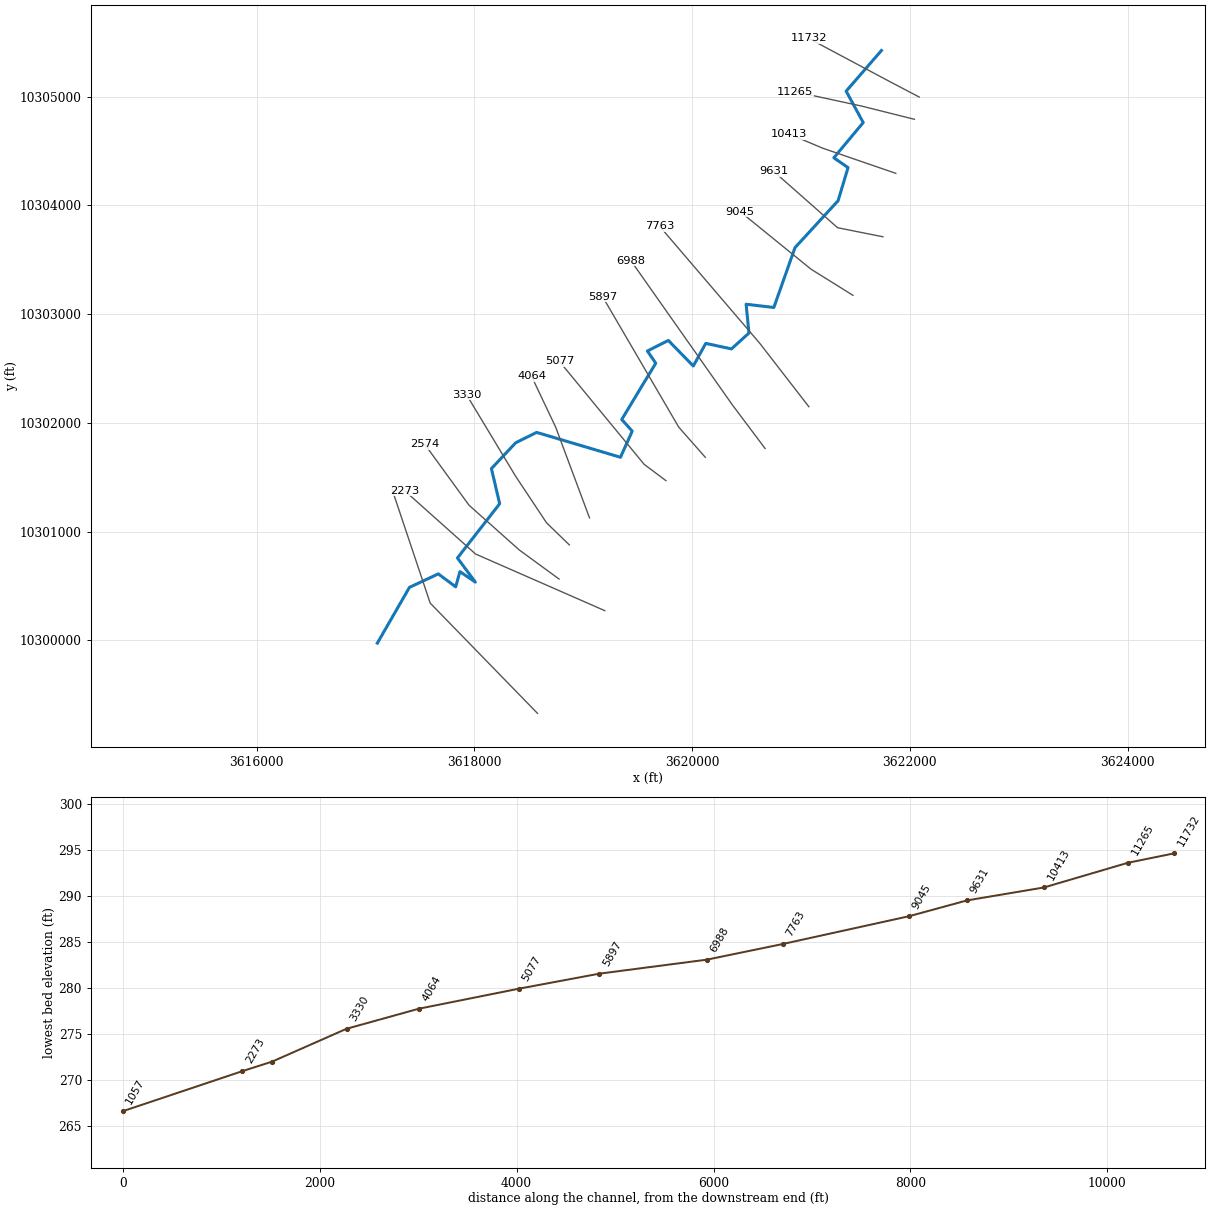
--- UNT04382 IN CEDR CR.prj (project) ---

Proj Title=UNT04382 IN CEDR CR Base Level Engineering
Current Plan=p01
Default Exp/Contr=0.3,0.1
English Units
Geom File=g01
Flow File=f01
Plan File=p01
Y Axis Title=Elevation
X Axis Title(PF)=Main Channel Distance
X Axis Title(XS)=Station
BEGIN DESCRIPTION:
UNT04382 IN CEDR CR
END DESCRIPTION:
DSS Export Rating Curves= 0
DSS Export Rating Curve Sorted= 0
DSS Export Volume Flow Curves= 0
DXF OffsetX= 0
DXF OffsetY= 0
DXF ScaleX= 1
DXF ScaleY= 10

--- UNT04382 IN CEDR CR.p01 (plan) ---

Plan Title=Multiple Run
Short Identifier=Multiple
Geom File=g01
Flow File=f01
Subcritical Flow
K Sum by GR= 0
Std Step Tol= 0.01
Critical Tol= 0.01
Num of Std Step Trials= 20
Max Error Tol= 0.3
Flow Tol Ratio= 0.001
Split Flow NTrial= 30
Split Flow Tol= 0.02
Split Flow Ratio= 0.02
Log Output Level= 0
Friction Slope Method= 1
Unsteady Friction Slope Method= 2
Unsteady Bridges Friction Slope Method= 1
Parabolic Critical Depth
Global Vel Dist=  1 , 1 , 1
Global Log Level= 0
CheckData=True
Encroach Param= -1, 0, 0, 0
BEGIN DESCRIPTION:
Multiple Run
END DESCRIPTION:

--- UNT04382 IN CEDR CR.f01 (steady flow) ---

Flow Title=Multiple
Program Version=4.10
Number of Profiles= 7
Profile Names=10-year,25-year,50-year,1pct_min,100-year,1pct_plu,500-year
River Rch & RM=UNT04382 IN CEDR,Reach-1         ,11732
     736     999    1214    1081    1462    1978    2125
River Rch & RM=UNT04382 IN CEDR,Reach-1         ,7763
    1233    1703    2093    1881    2543    3440    3762
Boundary for River Rch & Prof#=UNT04382 IN CEDR,Reach-1         , 1
Up Type= 0
Dn Type= 3
Dn Slope=0.005
Boundary for River Rch & Prof#=UNT04382 IN CEDR,Reach-1         , 2
Up Type= 0
Dn Type= 3
Dn Slope=0.005
Boundary for River Rch & Prof#=UNT04382 IN CEDR,Reach-1         , 3
Up Type= 0
Dn Type= 3
Dn Slope=0.005
Boundary for River Rch & Prof#=UNT04382 IN CEDR,Reach-1         , 4
Up Type= 0
Dn Type= 3
Dn Slope=0.005
Boundary for River Rch & Prof#=UNT04382 IN CEDR,Reach-1         , 5
Up Type= 0
Dn Type= 3
Dn Slope=0.005
Boundary for River Rch & Prof#=UNT04382 IN CEDR,Reach-1         , 6
Up Type= 0
Dn Type= 3
Dn Slope=0.005
Boundary for River Rch & Prof#=UNT04382 IN CEDR,Reach-1         , 7
Up Type= 0
Dn Type= 3
Dn Slope=0.005
DSS Import GetInterval= 0
DSS Import GetPeak= 0
DSS Import FillOption= 0

--- UNT04382 IN CEDR CR.g01 (geometry) ---

Geom Title=Existing Conditions
Program Version=4.10

River Reach=UNT04382 IN CEDR,Reach-1
Reach XY= 30
      3621738.57     10305423.59      3621414.86     10305050.47
      3621571.64     10304761.47       3621301.5     10304437.86
      3621432.05     10304347.58      3621340.83     10304043.16
      3620944.65     10303611.56      3620750.45     10303061.44
      3620495.67     10303091.39      3620521.87      10302826.8
      3620361.19     10302680.45      3620124.73     10302731.49
      3620010.41     10302523.42      3619780.72     10302758.57
      3619588.53     10302661.18      3619665.36      10302549.2
      3619352.94     10302031.93      3619449.29     10301924.64
       3619341.4     10301684.36      3618570.89     10301913.05
      3618378.18     10301817.21      3618155.63     10301580.25
       3618231.3       10301257.      3617843.28      10300758.3
       3618007.6     10300536.82      3617866.54     10300632.74
      3617826.91     10300493.32      3617667.57     10300612.02
      3617402.57     10300488.21      3617107.65     10299975.73

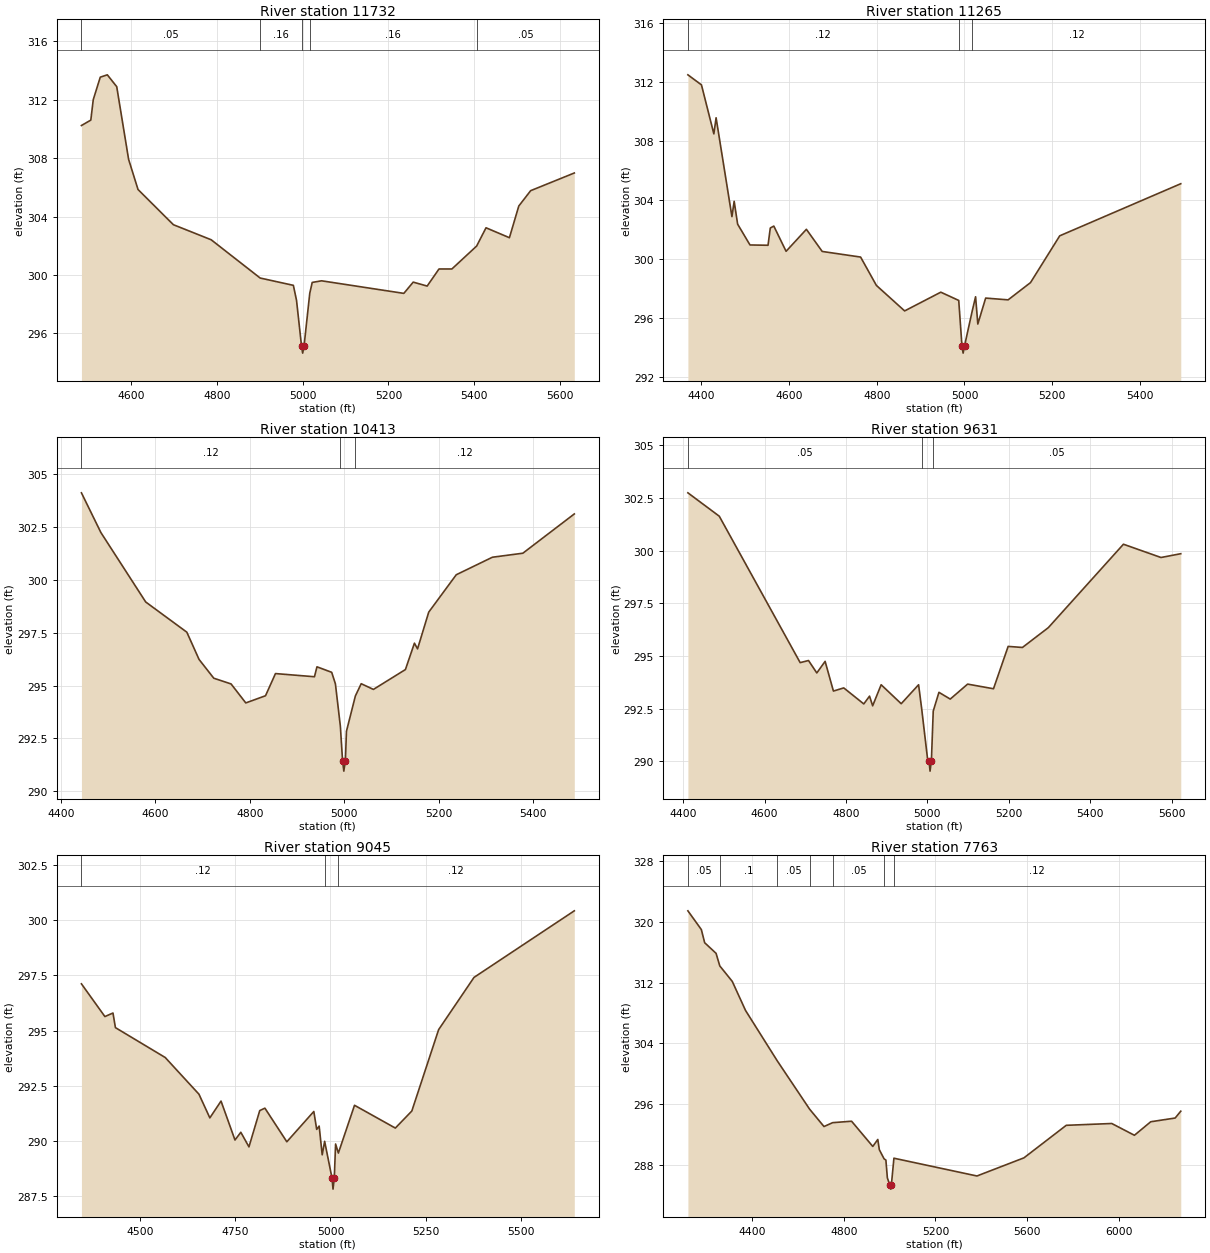
Type RM Length L Ch R = 1 ,11732   ,467,467,467
BEGIN DESCRIPTION:
UNT04382 IN CEDR CR 17.0
END DESCRIPTION:
XS GIS Cut Line= 3
      3622086.11     10304996.25      3621819.88     10305136.09
       3621069.9     10305536.08
#Sta/Elev= 30
  4483.2  310.23  4505.1   310.6  4510.8     312  4527.2  313.54  4543.6   313.7
  4565.6  312.89  4593.3  307.92  4615.3  305.85  4697.9  303.44  4786.1  302.41
  4900.5  299.79    4978  299.29  4985.4  298.26    4997  295.15  4999.7  294.65
    5003  295.15  5016.3  298.75    5022  299.49  5043.9   299.6  5235.9  298.74
  5257.8  299.51  5290.4  299.24    5318  300.41  5348.1  300.41  5405.9  301.98
  5427.8  303.23  5482.4  302.55  5504.3  304.72    5532  305.77  5633.9  306.98
#Mann= 5 ,-1 , 0
  4483.2     .05       0  4900.5     .16       0    4997     .07       0
  5016.3     .16       0  5405.9     .05       0
Bank Sta=4997,5003
XS Rating Curve= 0 ,0
Exp/Cntr=0.3,0.1

Type RM Length L Ch R = 1 ,11265   ,852,852,852
BEGIN DESCRIPTION:
UNT04382 IN CEDR CR 16.0
END DESCRIPTION:
XS GIS Cut Line= 3
       3622042.1     10304791.64      3621558.31     10304912.92
      3620947.25     10305044.86
#Sta/Elev= 30
  4369.4  312.49  4400.3  311.81  4428.6  308.49  4433.7  309.58  4469.8  302.88
  4474.9  303.92  4482.8  302.37    4511  300.96  4552.1  300.94  4557.3  302.11
  4565.3  302.24  4593.3  300.53  4639.6  302.02  4675.7  300.52  4763.2  300.14
  4799.2  298.22  4863.6  296.49  4946.1  297.76    4987   297.2  4994.3  294.13
    4997  293.63  5000.3  294.13  5017.7  296.48  5025.4  297.45  5030.5   295.6
  5048.4  297.36  5099.6  297.24  5150.7  298.41  5217.3  301.58  5493.3  305.11
#Mann= 3 ,-1 , 0
  4369.4     .12       0    4987     .07       0  5017.7     .12       0
Bank Sta=4994.3,5000.3
XS Rating Curve= 0 ,0
Exp/Cntr=0.3,0.1

Type RM Length L Ch R = 1 ,10413   ,782,782,782
BEGIN DESCRIPTION:
UNT04382 IN CEDR CR 15.0
END DESCRIPTION:
XS GIS Cut Line= 3
      3621870.85     10304294.85      3621200.44     10304525.67
      3620891.64     10304655.98
#Sta/Elev= 30
  4443.3  304.13  4484.5  302.25  4579.5  298.96  4666.6  297.53  4692.5  296.24
  4723.7  295.35  4760.3  295.08  4791.5  294.18  4833.3  294.52  4854.4  295.57
    4937  295.42  4942.3  295.89  4973.5  295.63  4981.4  295.08  4991.9  293.07
  4996.5  291.45  4999.2  290.95  5002.5  291.45  5004.8  292.84  5023.7  294.51
    5036  295.09  5061.9  294.82  5129.7  295.76  5148.8  297.01  5155.4  296.74
  5179.1  298.48  5237.4  300.25    5314  301.08  5378.5  301.27  5487.5  303.13
#Mann= 3 ,-1 , 0
  4443.3     .12       0  4991.9     .07       0  5023.7     .12       0
Bank Sta=4996.5,5002.5
XS Rating Curve= 0 ,0
Exp/Cntr=0.3,0.1

Type RM Length L Ch R = 1 ,9631    ,586,586,586
BEGIN DESCRIPTION:
UNT04382 IN CEDR CR 14.0
END DESCRIPTION:
XS GIS Cut Line= 3
      3621752.73     10303711.54      3621336.09     10303794.87
      3620746.49      10304315.1
#Sta/Elev= 30
  4411.4  302.75  4488.5  301.64  4687.3  294.69  4707.8  294.79  4728.2   294.2
  4748.6  294.75    4769  293.34  4794.4  293.49  4843.6  292.73  4857.8   293.1
  4865.4  292.64  4886.3  293.64  4935.6  292.74  4978.3  293.64  4985.9   292.5
  5000.1  290.16  5003.8  290.04  5006.5  289.54  5009.8  290.04  5014.3  292.39
  5028.3  293.28  5056.1  292.96  5098.8  293.67  5162.4  293.45  5198.4  295.46
  5233.5  295.41  5297.1  296.35  5481.7  300.31    5574  299.68  5622.6  299.86
#Mann= 3 ,-1 , 0
  4411.4     .05       0  4985.9     .07       0  5014.3     .05       0
Bank Sta=5003.8,5009.8
XS Rating Curve= 0 ,0
Exp/Cntr=0.3,0.1

Type RM Length L Ch R = 1 ,9045    ,1282,1282,1282
BEGIN DESCRIPTION:
UNT04382 IN CEDR CR 13.0
END DESCRIPTION:
XS GIS Cut Line= 3
      3621477.74     10303173.16      3621093.03     10303412.92
      3620442.11     10303941.64
#Sta/Elev= 30
  4347.2  297.11  4408.7  295.63  4429.9  295.79  4436.3  295.13  4566.8  293.78
  4655.3  292.12  4683.8  291.05  4713.1  291.81  4749.7  290.05    4765   290.4
  4786.3  289.74  4814.6  291.38  4828.1  291.49  4885.6  289.97  4956.3  291.34
  4963.9  290.53  4970.3  290.68  4978.3  289.38  4984.7  289.99    5004  288.33
  5006.7  287.83    5010  288.33  5013.4  289.87  5020.7  289.46    5063  291.62
    5170  290.59  5213.2  291.36  5283.5  295.04  5376.2   297.4  5639.1  300.41
#Mann= 3 ,-1 , 0
  4347.2     .12       0  4984.7     .07       0  5020.7     .12       0
Bank Sta=5004,5010
XS Rating Curve= 0 ,0
Exp/Cntr=0.3,0.1

Type RM Length L Ch R = 1 ,7763    ,775,775,775
BEGIN DESCRIPTION:
UNT04382 IN CEDR CR 12.0
END DESCRIPTION:
XS GIS Cut Line= 3
      3621072.18     10302149.07      3620620.81     10302732.37
      3619702.33      10303806.6
#Sta/Elev= 30
  4119.5  321.45  4178.2  318.98  4192.7  317.25  4242.5  315.85  4258.6   314.2
  4313.1  312.16  4371.1  308.33  4510.1  301.67  4650.6  295.34  4713.4  293.05
  4751.2  293.56  4833.8  293.75  4926.4  290.43  4948.2  291.35  4954.9     290
  4975.8  288.79  4983.5  288.64    4990  286.28  5001.3  285.31  5004.1  284.81
  5007.3  285.31  5018.6  288.88  5380.9  286.54  5586.1  288.93  5770.6  293.21
  5969.3  293.45  6068.1   291.9  6139.4  293.68  6245.9  294.17  6270.4  295.07
#Mann= 7 ,-1 , 0
  4119.5     .05       0  4258.6      .1       0  4510.1     .05       0
  4650.6      .1       0  4751.2     .05       0  4975.8     .05       0
  5018.6     .12       0
Bank Sta=5001.3,5007.3
XS Rating Curve= 0 ,0
Exp/Cntr=0.3,0.1

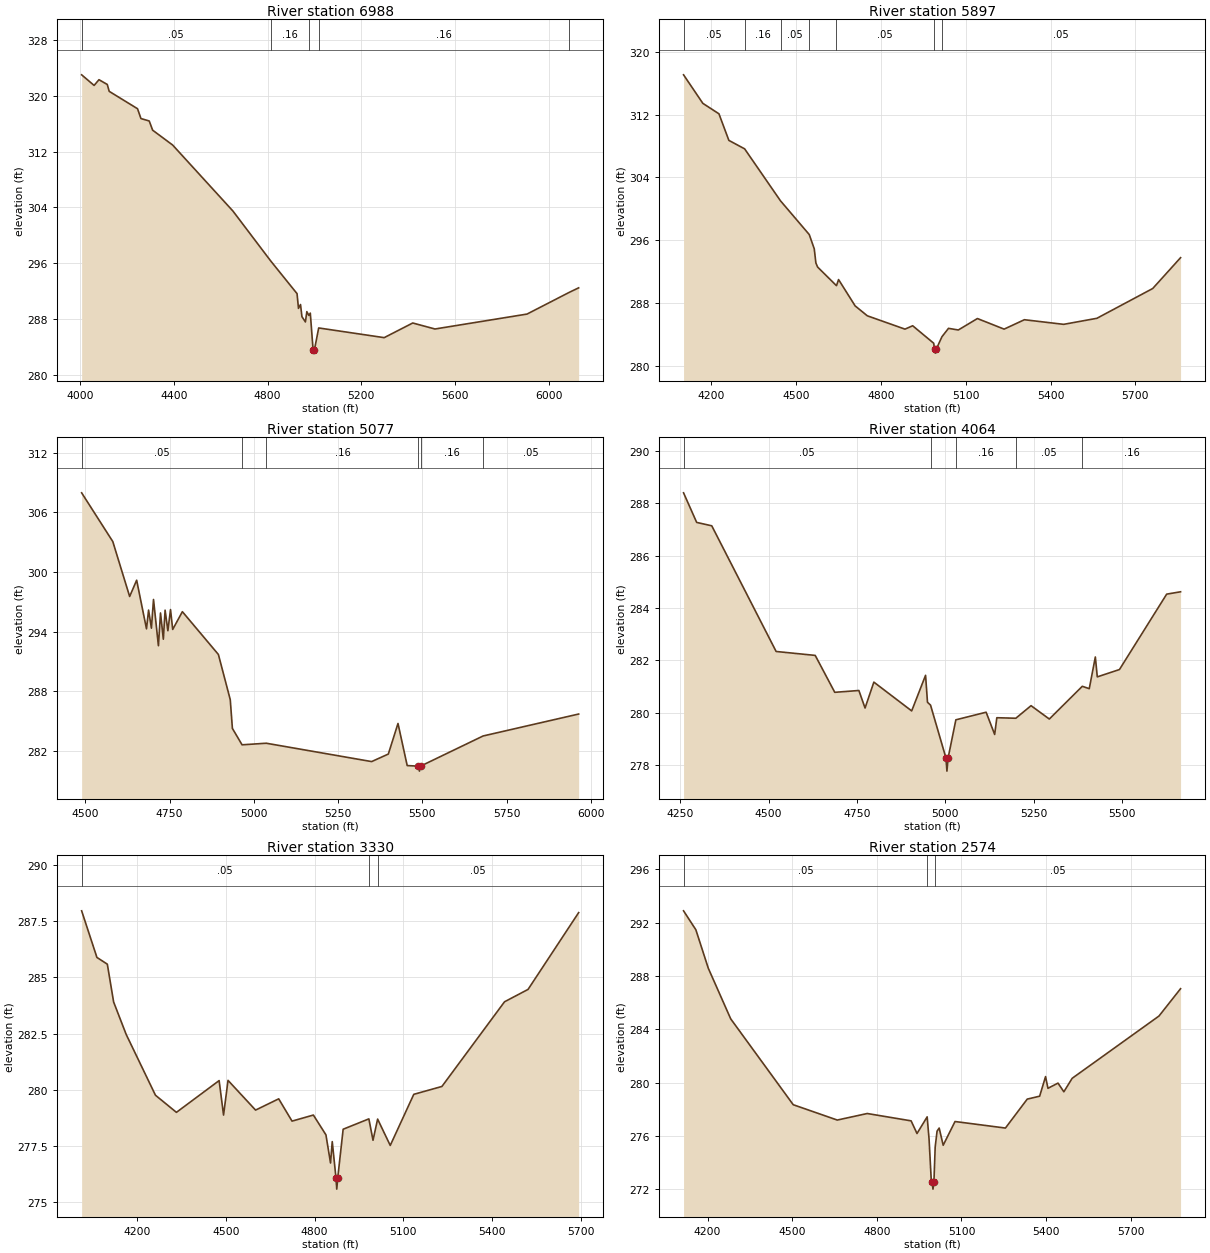
Type RM Length L Ch R = 1 ,6988    ,1091,1091,1091
BEGIN DESCRIPTION:
UNT04382 IN CEDR CR 11.0
END DESCRIPTION:
XS GIS Cut Line= 3
      3620669.87     10301765.27      3620369.88     10302165.25
       3619436.9     10303492.09
#Sta/Elev= 30
  4006.4  323.01  4059.6  321.49  4080.4  322.31  4115.8  321.63  4124.1  320.64
    4245  318.15  4259.6  316.74    4295  316.39  4309.6  315.07    4395  312.94
  4652.5  303.47  4814.3  296.29  4926.1  291.63  4932.2  289.52  4940.9  290.07
    4947  288.33  4961.8  287.57  4967.9  289.05  4976.6  288.51  4982.7  288.84
  4994.5   283.6  4997.3   283.1  5000.5   283.6  5018.5  286.71  5298.1  285.32
  5420.1  287.42    5515  286.56    5908   288.7  6089.2  291.83  6128.4  292.46
#Mann= 5 ,-1 , 0
  4006.4     .05       0  4814.3     .16       0  4976.6     .05       0
  5018.5     .16       0  6089.2     .05       0
Bank Sta=4994.5,5000.5
XS Rating Curve= 0 ,0
Exp/Cntr=0.3,0.1

Type RM Length L Ch R = 1 ,5897    ,820,820,820
BEGIN DESCRIPTION:
UNT04382 IN CEDR CR 10.0
END DESCRIPTION:
XS GIS Cut Line= 3
      3620120.79     10301683.78      3619876.83     10301961.09
      3619176.97     10303160.84
#Sta/Elev= 30
  4101.4  317.07  4169.7  313.43  4226.6   312.1  4261.7  308.71  4317.5  307.63
  4444.4     301  4546.1   296.7  4563.8  294.88  4569.6  293.07  4575.6  292.56
  4642.4  290.18  4649.8  290.96  4708.5   287.6  4751.5  286.34  4884.7  284.64
    4912  285.07  4986.4  282.84  4989.4  282.08  4992.1  281.58  4995.4  282.08
  5015.5  283.67  5038.7  284.74  5073.4  284.53    5141  285.99  5235.5  284.64
  5307.2  285.84  5446.2  285.25  5563.6  286.02  5761.2  289.82  5859.7  293.75
#Mann= 7 ,-1 , 0
  4101.4     .05       0  4317.5     .16       0  4444.4     .05       0
  4546.1     .16       0  4642.4     .05       0  4986.4     .05       0
  5015.5     .05       0
Bank Sta=4989.4,4995.4
XS Rating Curve= 0 ,0
Exp/Cntr=0.3,0.1

Type RM Length L Ch R = 1 ,5077    ,1013,1013,1013
BEGIN DESCRIPTION:
UNT04382 IN CEDR CR 8.0
END DESCRIPTION:
XS GIS Cut Line= 3
      3619758.76     10301469.43      3619558.77     10301619.42
      3618780.52     10302565.71
#Sta/Elev= 30
  4488.9  307.97  4581.4  303.06  4631.4  297.53  4652.2  299.17  4681.4  294.27
  4687.6  296.16    4696  294.34  4702.2  297.23  4716.8  292.57    4723  295.87
  4731.4  293.23  4736.6  296.15  4744.9  294.08  4752.7  296.21  4759.2  294.21
  4787.9     296  4894.8  291.69    4930  287.14  4936.4  284.24  4965.1  282.59
  5036.9  282.75  5349.7   280.9  5399.2  281.66  5427.9  284.74  5455.2   280.5
  5488.7  280.44  5491.5  279.94  5494.7  280.44  5680.5  283.48  5964.1  285.69
#Mann= 6 ,-1 , 0
  4488.9     .05       0  4965.1     .05       0  5036.9     .16       0
  5488.7     .03       0  5494.7     .16       0  5680.5     .05       0
Bank Sta=5488.7,5494.7
XS Rating Curve= 0 ,0
Exp/Cntr=0.3,0.1

Type RM Length L Ch R = 1 ,4064    ,734,734,734
BEGIN DESCRIPTION:
UNT04382 IN CEDR CR 7.0
END DESCRIPTION:
XS GIS Cut Line= 3
      3619056.92     10301126.84      3618745.81     10301961.53
      3618525.05     10302427.16
#Sta/Elev= 30
  4259.3   288.4  4296.4  287.27  4339.1  287.14  4521.2  282.34  4631.8  282.19
  4687.1  280.78  4755.3  280.85  4772.8  280.18  4797.7  281.17  4904.7  280.07
    4944  281.43  4949.4   280.4  4958.1  280.29  5001.7  278.27  5004.4  277.77
  5007.7  278.27  5029.7  279.73  5115.3  280.02  5139.5  279.17  5145.6  279.81
  5199.4  279.79  5242.4  280.27  5294.1  279.76  5387.4  281.01  5407.1  280.92
  5424.3  282.13  5429.8  281.37  5492.5  281.65  5626.1  284.53  5665.4  284.62
#Mann= 5 ,-1 , 0
  4259.3     .05       0  4958.1     .05       0  5029.7     .16       0
  5199.4     .05       0  5387.4     .16       0
Bank Sta=5001.7,5007.7
XS Rating Curve= 0 ,0
Exp/Cntr=0.3,0.1

Type RM Length L Ch R = 1 ,3330    ,756,756,756
BEGIN DESCRIPTION:
UNT04382 IN CEDR CR 4.0
END DESCRIPTION:
XS GIS Cut Line= 4
      3618871.79     10300878.34      3618662.19     10301081.57
      3618377.76     10301510.14      3617926.71     10302259.57
#Sta/Elev= 30
    4012  287.95  4063.7  285.88  4098.9  285.58  4120.2   283.9  4162.7  282.46
  4261.7  279.76  4332.6     279    4477  280.41    4492  278.88  4507.1  280.42
  4600.3   279.1  4678.5   279.6  4723.6  278.61  4795.8  278.88  4838.3     278
  4853.8  276.75  4859.6   277.7  4872.2  276.09  4874.9  275.59  4878.2  276.09
  4896.5  278.25  4983.5  278.71  4997.5  277.76  5013.1   278.7  5055.8  277.53
  5135.4   279.8  5230.6  280.15  5442.3  283.91  5521.9  284.46    5693  287.87
#Mann= 3 ,-1 , 0
    4012     .05       0  4983.5     .05       0  5013.1     .05       0
Bank Sta=4872.2,4878.2
XS Rating Curve= 0 ,0
Exp/Cntr=0.3,0.1

Type RM Length L Ch R = 1 ,2574    ,301,301,301
BEGIN DESCRIPTION:
UNT04382 IN CEDR CR 3.0
END DESCRIPTION:
XS GIS Cut Line= 4
      3618777.27     10300564.54      3618410.98     10300832.55
      3617950.21       10301243.      3617544.45     10301801.78
#Sta/Elev= 30
  4115.1  292.89  4158.7  291.47  4202.7  288.59  4282.2  284.79  4503.8  278.35
  4659.9   277.2  4766.1  277.69  4921.6  277.14  4942.5  276.19  4978.5  277.44
  4985.2  275.78  4992.7   272.8  4996.4  272.52  4999.1  272.02  5002.4  272.52
  5006.9  275.17  5013.6  276.37  5021.1   276.6  5035.3  275.31  5077.2  277.09
  5255.9   276.6  5333.2  278.77  5377.2  278.99  5398.1  280.46  5406.6  279.58
  5442.2  279.97    5463  279.32  5492.4  280.33  5800.1     285  5876.6  287.05
#Mann= 3 ,-1 , 0
  4115.1     .05       0  4978.5    .035       0  5006.9     .05       0
Bank Sta=4996.4,5002.4
XS Rating Curve= 0 ,0
Exp/Cntr=0.3,0.1

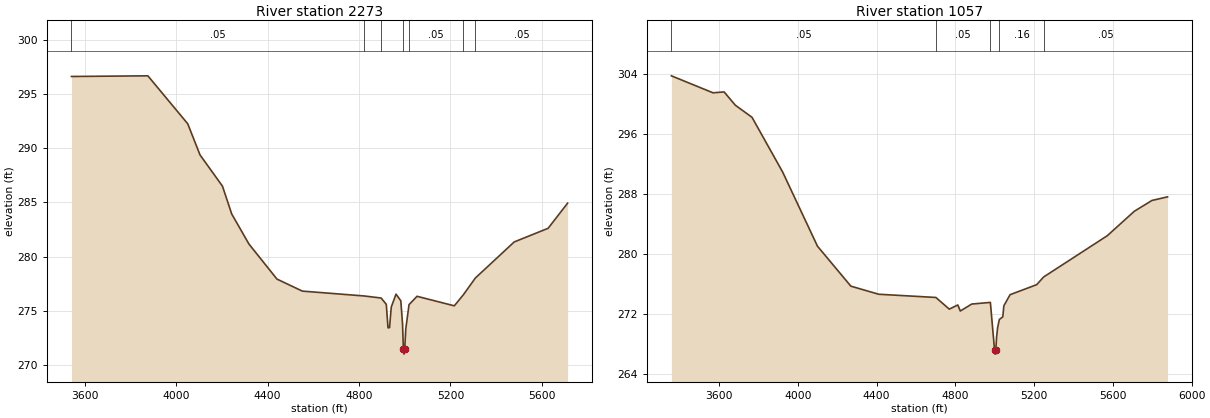
Type RM Length L Ch R = 1 ,2273    ,1216,1216,1216
BEGIN DESCRIPTION:
UNT04382 IN CEDR CR 2.0
END DESCRIPTION:
XS GIS Cut Line= 3
      3619197.17     10300274.05       3618009.7     10300794.87
      3617357.89     10301377.33
#Sta/Elev= 30
  3541.9  296.63  3876.2  296.69  4050.7  292.26  4104.3  289.39  4202.6   286.5
  4243.1  283.93  4318.7  281.15    4441  277.92    4552  276.81  4822.9  276.36
  4896.8  276.17  4919.4  275.59  4926.9  273.42  4933.6  273.44  4941.1  275.33
    4962  276.53  4982.9  275.92  4990.4  273.81  4994.1  271.49  4996.9  270.99
  5000.1  271.49  5004.6  273.31  5018.9  275.56    5054  276.33    5217  275.45
  5256.6  276.47  5309.2  278.02  5479.1  281.35  5627.5  282.61  5712.7  284.93
#Mann= 7 ,-1 , 0
  3541.9     .05       0  4822.9     .16       0  4896.8     .05       0
  4990.4    .035       0  5018.9     .05       0  5256.6     .16       0
  5309.2     .05       0
Bank Sta=4994.1,5000.1
XS Rating Curve= 0 ,0
Exp/Cntr=0.3,0.1

Type RM Length L Ch R = 1 ,1057    ,0,0,0
BEGIN DESCRIPTION:
UNT04382 IN CEDR CR 1.0
END DESCRIPTION:
XS GIS Cut Line= 3
      3618579.12     10299329.62      3617593.03     10300343.48
      3617242.09     10301391.68
#Sta/Elev= 30
  3357.7  303.81  3569.3  301.54  3625.6  301.66  3682.2  299.89  3767.1  298.27
  3922.7  290.96  4099.6  281.05  4269.2  275.71  4410.7  274.63  4700.9   274.2
  4769.1  272.64  4812.3   273.2  4825.1  272.39    4883  273.32  4977.7  273.54
  4999.1  267.13  5001.8  266.63  5005.1  267.13  5009.3   268.9  5014.5  270.15
  5023.2  271.26  5040.8  271.61  5046.1  273.08  5077.7  274.57    5213  275.91
  5247.9  276.93  5571.5  282.45    5709  285.72  5798.4  287.16  5877.4  287.64
#Mann= 5 ,-1 , 0
  3357.7     .05       0  4700.9     .05       0  4977.7    .035       0
  5023.2     .16       0  5247.9     .05       0
Bank Sta=4999.1,5005.1
XS Rating Curve= 0 ,0
Exp/Cntr=0.3,0.1

Chan Stop Cuts=-1
Use User Specified Reach Order=0
Composite Channel Slope=5