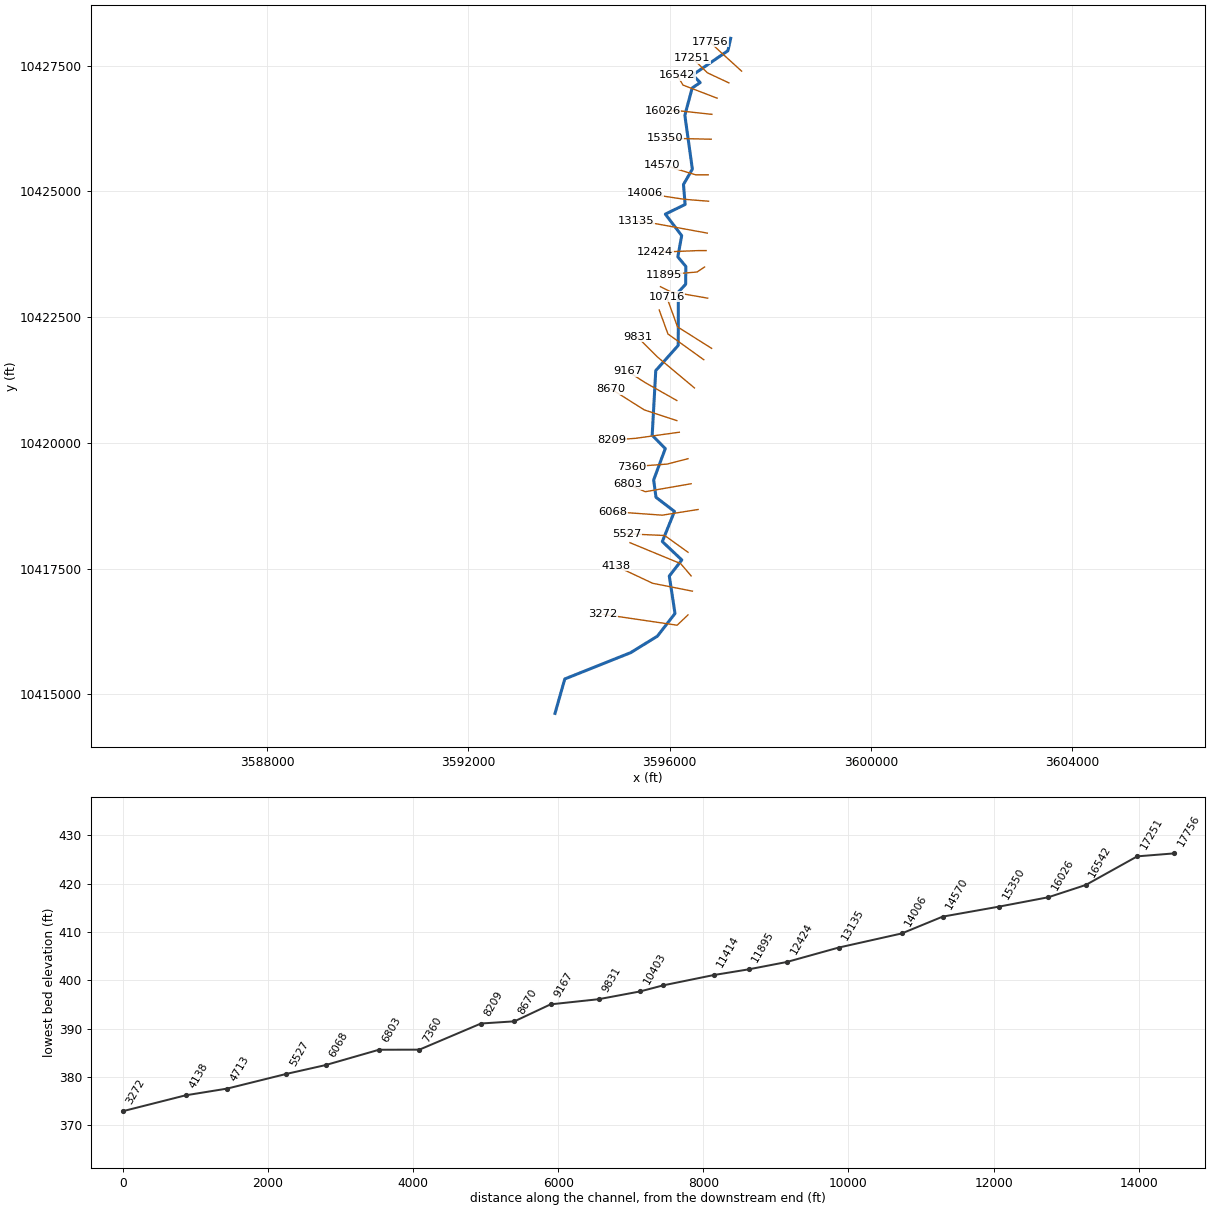
--- VESTAL BRANCH.prj (project) ---

Proj Title=VESTAL BRANCH Base Level Engineering
Current Plan=p01
Default Exp/Contr=0.3,0.1
English Units
Geom File=g01
Flow File=f01
Plan File=p01
BEGIN DESCRIPTION:
VESTAL BRANCH
END DESCRIPTION:

--- VESTAL BRANCH.p01 (plan) ---

Plan Title=Multiple Run
Short Identifier=Multiple
Geom File=g01
Flow File=f01
Subcritical Flow
K Sum by GR= 0
Std Step Tol= 0.01
Critical Tol= 0.01
Num of Std Step Trials= 20
Max Error Tol= 0.3
Flow Tol Ratio= 0.001
Split Flow NTrial= 30
Split Flow Tol= 0.02
Split Flow Ratio= 0.02
Log Output Level= 0
Friction Slope Method= 1
Unsteady Friction Slope Method= 2
Unsteady Bridges Friction Slope Method= 1
Parabolic Critical Depth
Global Vel Dist=  1 , 1 , 1
Global Log Level= 0
CheckData=True
Encroach Param= -1, 0, 0, 0
BEGIN DESCRIPTION:
Multiple Run
END DESCRIPTION:

--- VESTAL BRANCH.f01 (steady flow) ---

Flow Title=Multiple
Number of Profiles=7
Profile Names=10-year,25-year,50-year,1pct_min,100-year,1pct_plu,500-year
River Rch & RM= VESTAL BRANCH,Reach-1,17756
    2004    2888    3653    3369    4557    6162    7070
River Rch & RM= VESTAL BRANCH,Reach-1,13135
    2624    3829    4883    4536    6134    8296    9659
River Rch & RM= VESTAL BRANCH,Reach-1,10716
    3018    4418    5645    5250    7100    9602   11208
River Rch & RM= VESTAL BRANCH,Reach-1,4713
    3060    4468    5699    5289    7152    9672   11241
Boundary for River Rch & Prof#=VESTAL BRANCH,Reach-1,1
Up Type=0
Dn Type=3
Dn Slope=0.005
Boundary for River Rch & Prof#=VESTAL BRANCH,Reach-1,2
Up Type=0
Dn Type=3
Dn Slope=0.005
Boundary for River Rch & Prof#=VESTAL BRANCH,Reach-1,3
Up Type=0
Dn Type=3
Dn Slope=0.005
Boundary for River Rch & Prof#=VESTAL BRANCH,Reach-1,4
Up Type=0
Dn Type=3
Dn Slope=0.005
Boundary for River Rch & Prof#=VESTAL BRANCH,Reach-1,5
Up Type=0
Dn Type=3
Dn Slope=0.005
Boundary for River Rch & Prof#=VESTAL BRANCH,Reach-1,6
Up Type=0
Dn Type=3
Dn Slope=0.005
Boundary for River Rch & Prof#=VESTAL BRANCH,Reach-1,7
Up Type=0
Dn Type=3
Dn Slope=0.005

--- VESTAL BRANCH.g01 (geometry) ---

Geom Title=Existing Conditions

River Reach=VESTAL BRANCH,Reach-1
Reach XY= 30
      3597212.11     10428041.64      3597157.00     10427795.56
      3596458.01     10427314.36      3596606.07     10427162.02
      3596447.25     10427054.37      3596301.66     10426511.65
      3596450.84     10425441.07      3596274.47     10425136.44
      3596306.99     10424739.19      3595914.49     10424546.27
      3596238.60     10424120.14      3596162.21     10423696.94
      3596321.19     10423506.79      3596317.38     10423152.46
      3596172.62     10422997.05      3596170.24     10421937.60
      3595723.59     10421435.79      3595652.69     10420150.81
      3595912.98     10419885.23      3595681.86     10419262.27
      3595728.52     10418917.22      3596095.27     10418636.19
      3595854.10     10418037.47      3596241.33     10417671.52
      3595992.58     10417351.60      3596105.85     10416607.80
      3595755.41     10416155.80      3595223.32     10415827.88
      3593916.64     10415305.89      3593722.11     10414621.64

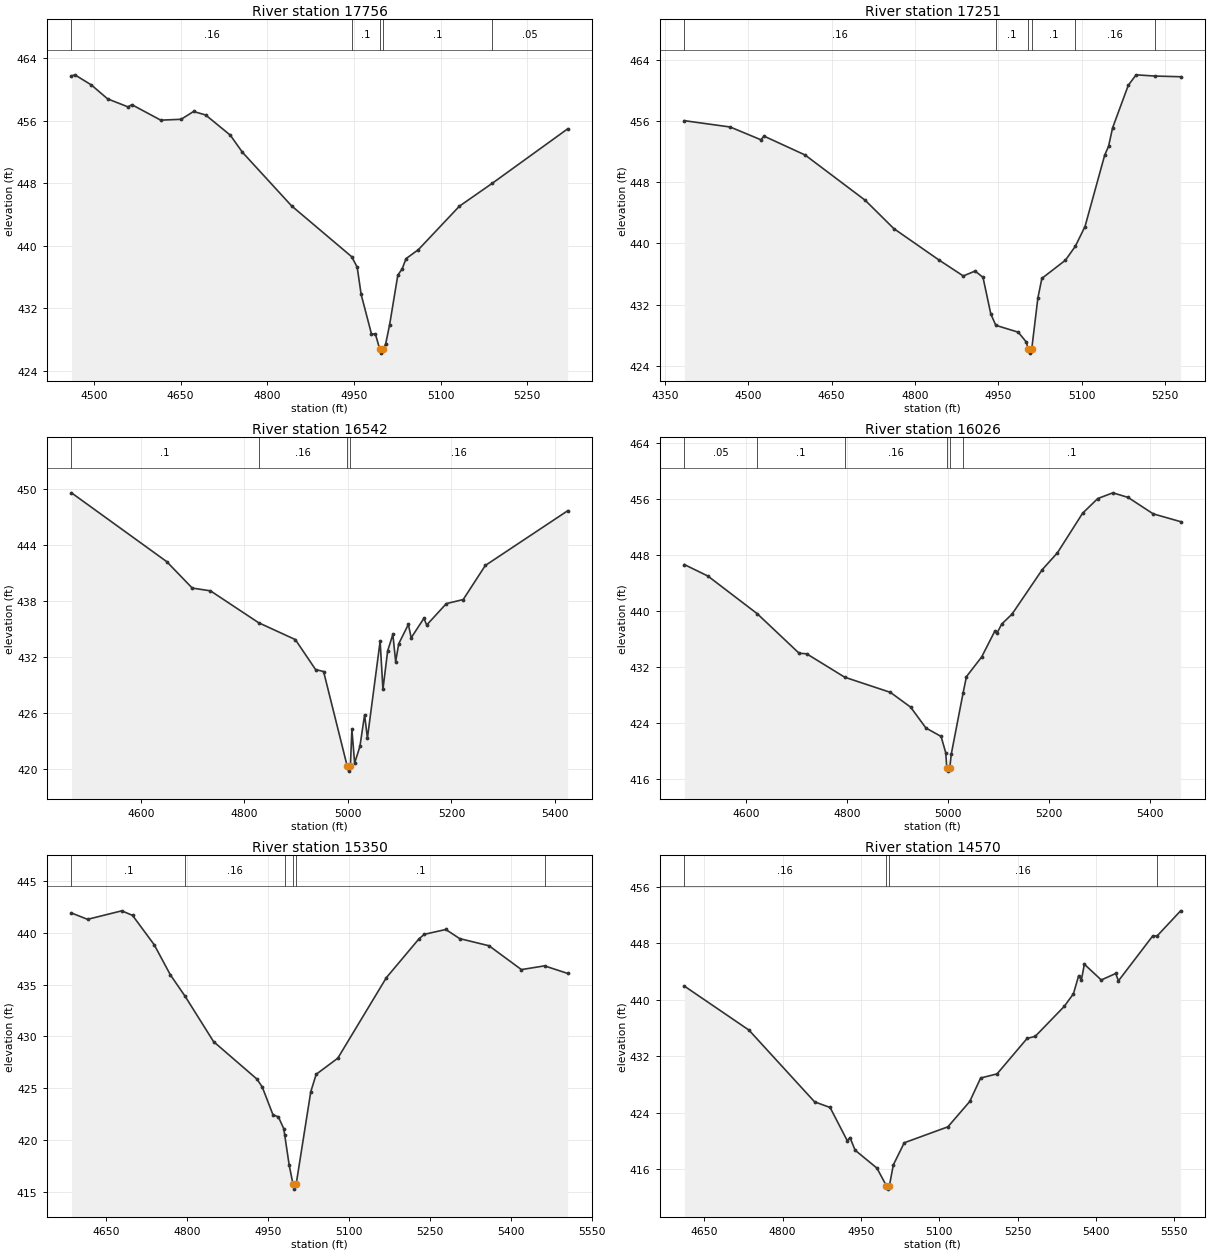
Type RM Length L Ch R = 1,17756,505,505,505
BEGIN DESCRIPTION:
VESTAL BRANCH 31.0
END DESCRIPTION:
XS GIS Cut Line= 3
      3597428.58     10427390.07      3597042.11     10427741.64
      3596796.02     10427970.63
#Sta/Elev= 30
  4461.3  461.72  4467.2  461.87  4495.6  460.58  4523.9  458.79  4559.1  457.77
  4565.8  458.05  4615.8  456.07  4651.0  456.18  4672.6  457.18  4693.5  456.73
  4736.1  454.15  4757.1  451.96  4842.2  445.10  4946.1  438.60  4955.7  437.26
  4962.5  433.78  4980.4  428.71  4987.2  428.71  4994.7  426.76  4997.4  426.26
  5000.7  426.76  5005.0  427.45  5011.8  429.89  5026.0  436.25  5033.4  437.02
  5040.2  438.35  5061.7  439.51  5132.5  445.06  5189.2  447.98  5319.9  454.96
#Mann=5,-1,0
  4461.3    0.16       0  4946.1     0.1       0  4994.7    0.07       0
  5000.7     0.1       0  5189.2    0.05       0
Bank Sta=4994.7,5000.7
Exp/Cntr=0.3,0.1

Type RM Length L Ch R = 1,17251,709,709,709
BEGIN DESCRIPTION:
VESTAL BRANCH 30.0
END DESCRIPTION:
XS GIS Cut Line= 3
      3597176.82     10427155.72      3596751.48     10427355.37
      3596447.69     10427650.48
#Sta/Elev= 30
  4385.0  456.07  4467.5  455.24  4522.8  453.57  4528.3  454.05  4602.3  451.58
  4710.6  445.65  4762.0  441.95  4843.1  437.85  4887.1  435.75  4908.4  436.39
  4922.6  435.57  4936.7  430.77  4945.7  429.29  4986.1  428.39  5000.3  427.13
  5004.3  426.15  5007.1  425.65  5010.3  426.15  5021.4  432.85  5028.6  435.43
  5071.0  437.81  5088.9  439.64  5106.3  442.22  5141.8  451.58  5148.7  452.72
  5155.9  455.12  5184.2  460.70  5198.3  462.07  5232.2  461.91  5278.4  461.82
#Mann=6,-1,0
  4385.0    0.16       0  4945.7     0.1       0  5004.3    0.07       0
  5010.3     0.1       0  5088.9    0.16       0  5232.2    0.05       0
Bank Sta=5004.3,5010.3
Exp/Cntr=0.3,0.1

Type RM Length L Ch R = 1,16542,516,516,516
BEGIN DESCRIPTION:
VESTAL BRANCH 29.0
END DESCRIPTION:
XS GIS Cut Line= 3
      3596942.44     10426851.90      3596265.37     10427112.31
      3596143.87     10427311.92
#Sta/Elev= 30
  4465.6  449.54  4649.7  442.17  4699.0  439.34  4734.3  439.04  4827.5  435.62
  4898.3  433.82  4937.4  430.61  4952.9  430.40  4998.7  420.23  5001.4  419.73
  5004.7  420.23  5007.6  424.19  5012.9  420.60  5023.1  422.37  5032.2  425.77
  5037.6  423.27  5062.2  433.65  5067.6  428.48  5076.7  432.60  5086.8  434.38
  5092.2  431.45  5098.1  433.37  5116.8  435.45  5122.2  434.01  5146.8  436.10
  5152.2  435.38  5190.1  437.67  5222.8  438.11  5265.5  441.76  5424.7  447.62
#Mann=4,-1,0
  4465.6     0.1       0  4827.5    0.16       0  4998.7    0.07       0
  5004.7    0.16       0
Bank Sta=4998.7,5004.7
Exp/Cntr=0.3,0.1

Type RM Length L Ch R = 1,16026,676,676,676
BEGIN DESCRIPTION:
VESTAL BRANCH 28.0
END DESCRIPTION:
XS GIS Cut Line= 3
      3596838.32     10426530.71      3596207.73     10426598.59
      3595857.76     10426598.59
#Sta/Elev= 30
  4477.4  446.64  4523.9  445.01  4621.8  439.64  4704.9  434.00  4719.9  433.92
  4795.4  430.58  4886.0  428.42  4926.2  426.31  4956.4  423.34  4986.5  422.14
  4995.8  419.80  4997.8  417.69  5000.6  417.19  5003.8  417.69  5006.7  419.60
  5030.0  428.27  5036.8  430.66  5067.0  433.47  5092.8  437.11  5097.8  436.92
  5106.9  438.17  5127.3  439.58  5187.3  445.93  5217.3  448.32  5267.3  453.97
  5297.3  456.06  5327.3  456.87  5357.3  456.22  5407.3  453.87  5461.6  452.76
#Mann=6,-1,0
  4477.4    0.05       0  4621.8     0.1       0  4795.4    0.16       0
  4997.8    0.07       0  5003.8    0.16       0  5030.0     0.1       0
Bank Sta=4997.8,5003.8
Exp/Cntr=0.3,0.1

Type RM Length L Ch R = 1,15350,780,780,780
BEGIN DESCRIPTION:
VESTAL BRANCH 26.0
END DESCRIPTION:
XS GIS Cut Line= 3
      3596825.22     10426035.92      3596105.65     10426052.41
      3595906.41     10426052.41
#Sta/Elev= 30
  4586.6  441.90  4616.4  441.29  4679.7  442.11  4699.7  441.67  4739.8  438.84
  4769.8  435.93  4797.0  433.87  4849.8  429.49  4929.8  425.89  4939.8  425.13
  4959.8  422.43  4969.8  422.23  4979.8  421.09  4981.5  420.49  4989.8  417.58
  4996.8  415.76  4999.6  415.26  5002.8  415.76  5029.8  424.66  5039.8  426.34
  5079.8  427.89  5169.9  435.67  5229.9  439.39  5239.9  439.84  5279.9  440.31
  5305.6  439.43  5359.9  438.74  5419.9  436.44  5462.7  436.80  5505.6  436.07
#Mann=6,-1,0
  4586.6     0.1       0  4797.0    0.16       0  4981.5     0.1       0
  4996.8    0.07       0  5002.8     0.1       0  5462.7    0.16       0
Bank Sta=4996.8,5002.8
Exp/Cntr=0.3,0.1

Type RM Length L Ch R = 1,14570,564,564,564
BEGIN DESCRIPTION:
VESTAL BRANCH 24.0
END DESCRIPTION:
XS GIS Cut Line= 3
      3596765.70     10425328.45      3596515.72     10425328.45
      3595845.75     10425532.03
#Sta/Elev= 30
  4611.8  441.95  4735.4  435.72  4861.1  425.55  4890.8  424.75  4923.7  420.04
  4928.9  420.49  4938.7  418.70  4980.5  416.16  4998.4  413.68  5001.2  413.18
  5004.4  413.68  5011.9  416.62  5032.8  419.75  5116.4  422.01  5158.2  425.60
  5179.1  428.93  5210.5  429.51  5268.1  434.54  5283.6  434.83  5339.1  439.07
  5356.8  440.87  5366.8  443.43  5372.0  442.81  5377.7  445.05  5410.1  442.82
  5437.7  443.74  5443.0  442.70  5508.7  449.07  5517.0  449.06  5562.0  452.62
#Mann=4,-1,0
  4611.8    0.16       0  4998.4    0.07       0  5004.4    0.16       0
  5517.0     0.1       0
Bank Sta=4998.4,5004.4
Exp/Cntr=0.3,0.1

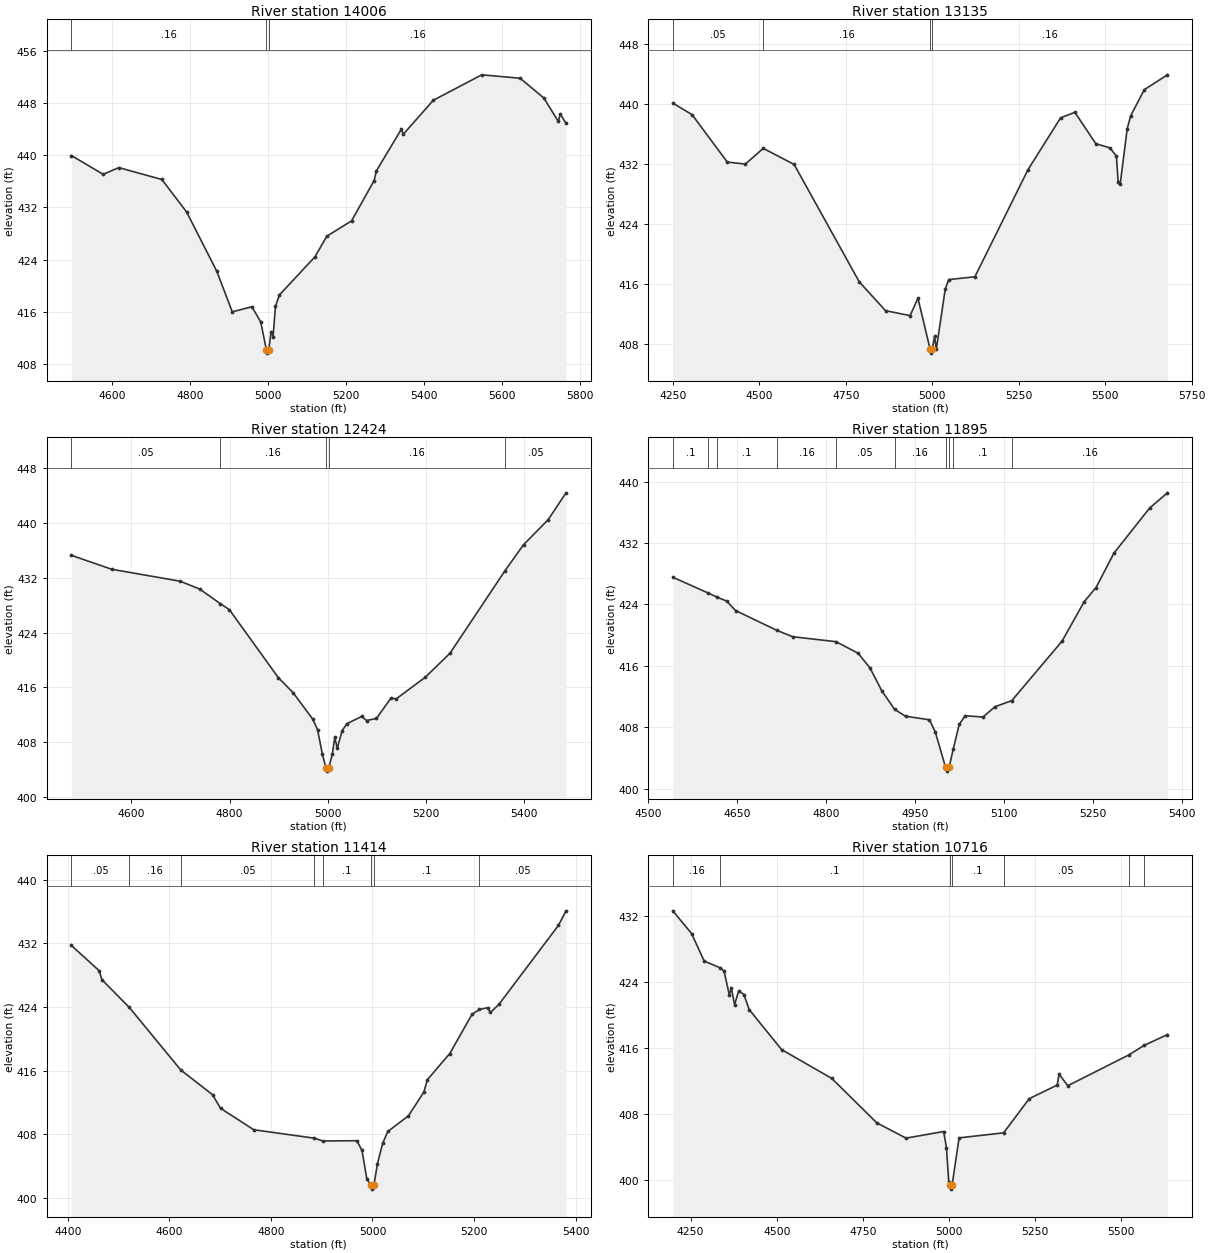
Type RM Length L Ch R = 1,14006,871,871,871
BEGIN DESCRIPTION:
VESTAL BRANCH 23.0
END DESCRIPTION:
XS GIS Cut Line= 3
      3596773.23     10424803.28      3596292.11     10424841.64
      3595515.83     10424959.33
#Sta/Elev= 30
  4496.0  439.95  4577.4  437.07  4617.5  438.10  4727.9  436.28  4791.5  431.29
  4868.3  422.28  4908.4  416.02  4958.6  416.80  4981.2  414.49  4995.9  410.20
  4998.6  409.70  5001.9  410.20  5008.0  413.00  5013.0  412.24  5019.1  416.86
  5029.2  418.61  5120.3  424.44  5150.6  427.59  5214.2  429.95  5272.0  436.12
  5277.9  437.61  5341.6  443.96  5346.7  443.20  5423.7  448.41  5547.9  452.30
  5646.2  451.78  5706.9  448.76  5744.1  445.17  5749.1  446.31  5763.8  444.88
#Mann=3,-1,0
  4496.0    0.16       0  4995.9    0.07       0  5001.9    0.16       0
Bank Sta=4995.9,5001.9
Exp/Cntr=0.3,0.1

Type RM Length L Ch R = 1,13135,711,711,711
BEGIN DESCRIPTION:
VESTAL BRANCH 21.0
END DESCRIPTION:
XS GIS Cut Line= 3
      3596747.14     10424169.60      3595736.20     10424354.49
      3595336.62     10424404.44
#Sta/Elev= 30
  4249.5  440.10  4305.4  438.54  4407.1  432.23  4459.2  431.97  4511.1  434.06
  4600.3  431.92  4788.6  416.28  4864.6  412.43  4935.7  411.77  4958.4  414.09
  4993.7  407.27  4996.5  406.77  4999.7  407.27  5006.5  409.01  5011.6  407.30
  5037.4  415.32  5047.6  416.57  5123.1  416.95  5276.7  431.22  5371.1  438.14
  5412.3  438.86  5472.8  434.68  5513.1  434.13  5532.3  433.05  5537.4  429.63
  5543.4  429.33  5563.5  436.65  5573.6  438.40  5613.0  441.88  5679.9  443.86
#Mann=4,-1,0
  4249.5    0.05       0  4511.1    0.16       0  4993.7    0.07       0
  4999.7    0.16       0
Bank Sta=4993.7,4999.7
Exp/Cntr=0.3,0.1

Type RM Length L Ch R = 1,12424,529,529,529
BEGIN DESCRIPTION:
VESTAL BRANCH 20.0
END DESCRIPTION:
XS GIS Cut Line= 3
      3596724.05     10423822.20      3596574.05     10423822.20
      3595715.65     10423787.72
#Sta/Elev= 30
  4477.4  435.27  4559.3  433.24  4699.4  431.49  4739.4  430.34  4781.5  428.20
  4799.5  427.36  4899.6  417.43  4929.6  415.25  4969.6  411.40  4979.6  409.84
  4989.6  406.23  4996.6  404.30  4999.4  403.80  5002.6  404.30  5009.7  406.26
  5014.8  408.74  5019.8  407.12  5029.7  409.70  5039.7  410.73  5069.7  411.77
  5079.7  411.18  5099.7  411.48  5129.8  414.49  5139.8  414.32  5199.8  417.51
  5249.8  420.99  5361.7  432.99  5400.0  436.83  5450.0  440.45  5486.5  444.38
#Mann=5,-1,0
  4477.4    0.05       0  4781.5    0.16       0  4996.6    0.07       0
  5002.6    0.16       0  5361.7    0.05       0
Bank Sta=4996.6,5002.6
Exp/Cntr=0.3,0.1

Type RM Length L Ch R = 1,11895,481,481,481
BEGIN DESCRIPTION:
VESTAL BRANCH 19.0
END DESCRIPTION:
XS GIS Cut Line= 3
      3596693.84     10423496.15      3596543.84     10423396.16
      3595892.09     10423341.64
#Sta/Elev= 30
  4541.7  427.54  4601.7  425.47  4616.9  424.92  4632.4  424.44  4647.5  423.20
  4717.4  420.61  4743.8  419.79  4816.9  419.14  4854.2  417.64  4874.2  415.73
  4894.3  412.73  4915.8  410.32  4934.4  409.42  4974.6  408.96  4984.6  407.35
  5001.7  402.77  5004.4  402.27  5007.7  402.77  5014.6  405.09  5024.8  408.35
  5034.8  409.49  5064.9  409.32  5085.0  410.66  5113.5  411.46  5198.2  419.20
  5235.5  424.34  5255.6  426.20  5285.7  430.67  5345.9  436.55  5376.0  438.54
#Mann=10,-1,0
  4541.7     0.1       0  4601.7    0.05       0  4616.9     0.1       0
  4717.4    0.16       0  4816.9    0.05       0  4915.8    0.16       0
  5001.7    0.07       0  5007.7    0.16       0  5014.6     0.1       0
  5113.5    0.16       0
Bank Sta=5001.7,5007.7
Exp/Cntr=0.3,0.1

Type RM Length L Ch R = 1,11414,698,698,698
BEGIN DESCRIPTION:
VESTAL BRANCH 18.0
END DESCRIPTION:
XS GIS Cut Line= 3
      3596755.78     10422876.21      3596016.41     10423004.84
      3595816.75     10423104.67
#Sta/Elev= 30
  4407.3  431.74  4461.8  428.58  4467.5  427.43  4521.4  423.94  4622.6  416.08
  4685.1  412.97  4700.9  411.26  4766.3  408.56  4885.4  407.50  4902.1  407.15
  4969.3  407.18  4979.4  405.96  4988.9  402.38  4996.7  401.59  4999.5  401.09
  5002.7  401.59  5009.9  404.30  5020.0  406.84  5030.2  408.34  5070.8  410.31
  5101.2  413.31  5108.1  414.86  5152.0  418.13  5196.1  423.09  5210.5  423.69
  5226.5  423.91  5232.1  423.31  5248.8  424.32  5366.2  434.28  5381.0  436.10
#Mann=8,-1,0
  4407.3    0.05       0  4521.4    0.16       0  4622.6    0.05       0
  4885.4    0.16       0  4902.1     0.1       0  4996.7    0.07       0
  5002.7     0.1       0  5210.5    0.05       0
Bank Sta=4996.7,5002.7
Exp/Cntr=0.3,0.1

Type RM Length L Ch R = 1,10716,313,313,313
BEGIN DESCRIPTION:
VESTAL BRANCH 17.0
END DESCRIPTION:
XS GIS Cut Line= 3
      3596833.97     10421877.92      3596156.03     10422305.83
      3595939.84     10422902.26
#Sta/Elev= 30
  4198.3  432.67  4252.9  429.91  4289.4  426.58  4336.0  425.76  4347.1  425.38
  4362.3  422.48  4368.3  423.32  4377.6  421.30  4389.7  423.00  4404.7  422.53
  4420.0  420.71  4514.1  415.86  4660.0  412.36  4790.6  406.98  4875.4  405.13
  4984.8  405.93  4992.8  403.98  4999.4  399.85  5003.2  399.45  5005.9  398.95
  5009.2  399.45  5029.5  405.16  5158.7  405.77  5233.2  409.91  5314.5  411.56
  5319.8  412.88  5345.1  411.48  5521.4  415.19  5567.4  416.38  5634.4  417.67
#Mann=7,-1,0
  4198.3    0.16       0  4336.0     0.1       0  5003.2    0.07       0
  5009.2     0.1       0  5158.7    0.05       0  5521.4     0.1       0
  5567.4    0.05       0
Bank Sta=5003.2,5009.2
Exp/Cntr=0.3,0.1

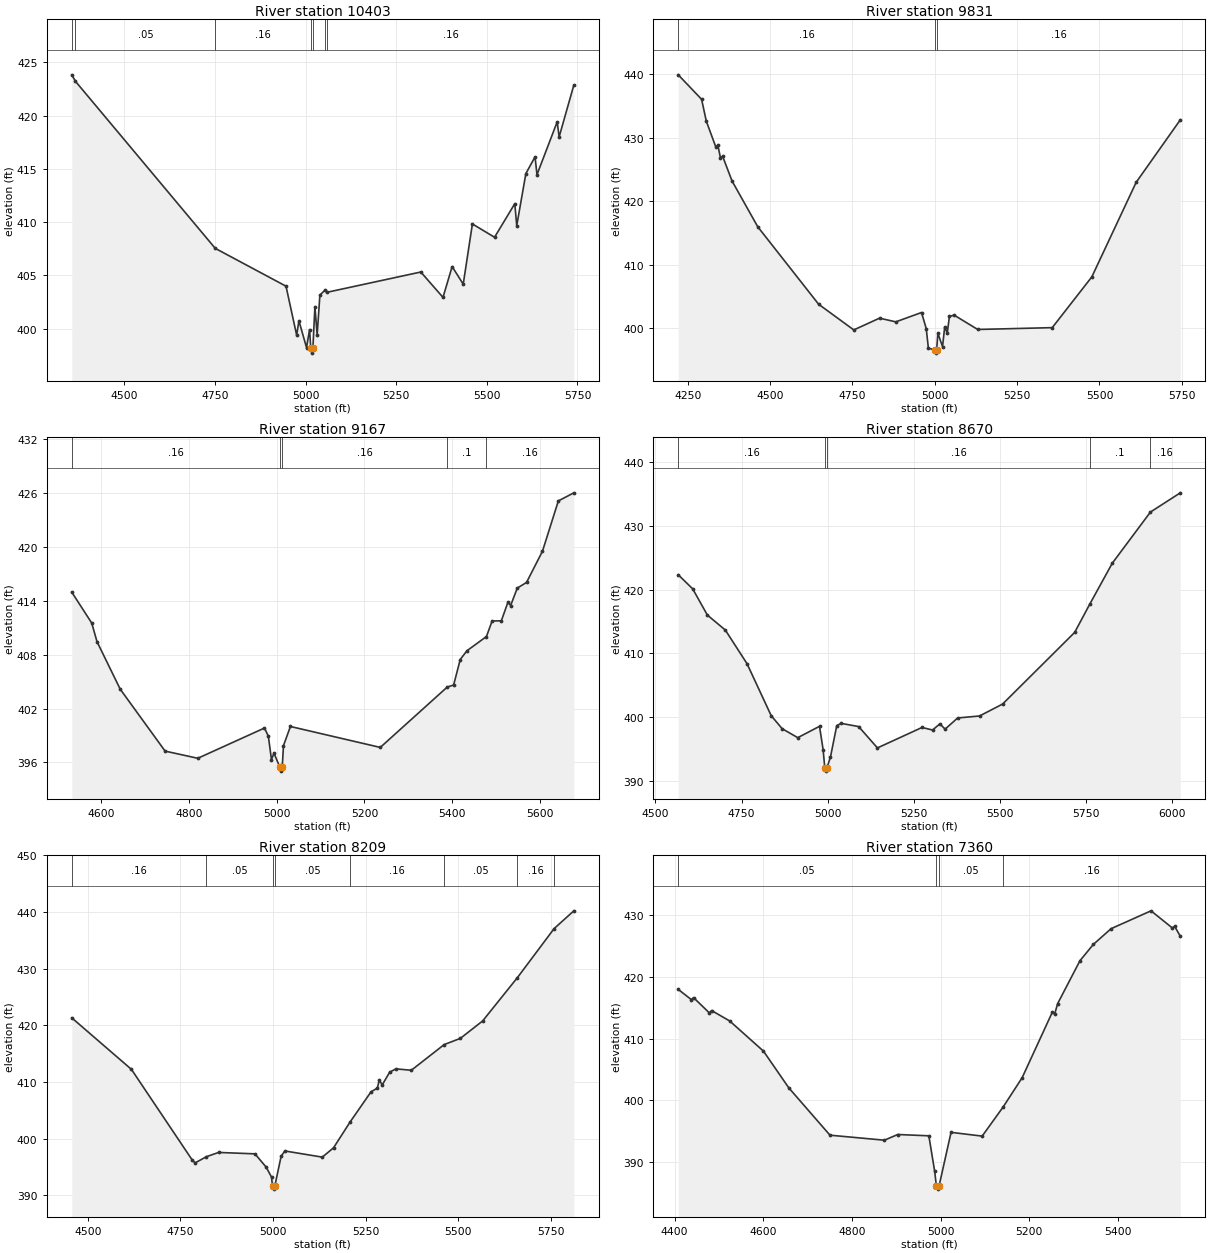
Type RM Length L Ch R = 1,10403,572,572,572
BEGIN DESCRIPTION:
VESTAL BRANCH 16.0
END DESCRIPTION:
XS GIS Cut Line= 3
      3596677.68     10421652.25      3595965.89     10422164.39
      3595792.10     10422641.65
#Sta/Elev= 30
  4355.2  423.82  4365.4  423.21  4750.9  407.54  4946.1  403.99  4975.5  399.39
  4981.7  400.75  5002.7  398.23  5011.1  399.92  5014.3  398.21  5017.0  397.71
  5020.3  398.21  5025.8  402.07  5032.0  399.43  5039.6  403.16  5053.1  403.60
  5059.6  403.42  5317.9  405.32  5379.1  402.94  5404.3  405.83  5434.9  404.18
  5460.2  409.83  5521.3  408.58  5577.1  411.73  5582.5  409.67  5607.7  414.56
  5633.0  416.13  5638.3  414.45  5694.1  419.41  5699.4  417.99  5740.0  422.86
#Mann=7,-1,0
  4355.2    0.16       0  4365.4    0.05       0  4750.9    0.16       0
  5014.3    0.07       0  5020.3    0.16       0  5053.1    0.08       0
  5059.6    0.16       0
Bank Sta=5014.3,5020.3
Exp/Cntr=0.3,0.1

Type RM Length L Ch R = 1,9831,664,664,664
BEGIN DESCRIPTION:
VESTAL BRANCH 14.0
END DESCRIPTION:
XS GIS Cut Line= 3
      3596492.08     10421091.66      3595757.38     10421706.57
      3595357.35     10422106.60
#Sta/Elev= 30
  4221.5  439.88  4292.4  436.03  4306.7  432.59  4335.3  428.56  4341.8  428.81
  4349.6  426.82  4356.2  427.07  4384.8  423.18  4462.8  415.98  4647.6  403.79
  4754.3  399.75  4832.4  401.60  4881.8  401.02  4959.9  402.49  4974.2  399.95
  4980.7  396.89  4999.8  396.60  5002.6  396.10  5005.8  396.60  5009.4  399.23
  5023.7  397.13  5030.2  400.22  5038.0  399.27  5044.5  401.87  5058.8  402.08
  5130.4  399.82  5356.6  400.11  5476.8  408.10  5611.2  422.96  5745.3  432.80
#Mann=3,-1,0
  4221.5    0.16       0  4999.8    0.07       0  5005.8    0.16       0
Bank Sta=4999.8,5005.8
Exp/Cntr=0.3,0.1

Type RM Length L Ch R = 1,9167,497,497,497
BEGIN DESCRIPTION:
VESTAL BRANCH 13.0
END DESCRIPTION:
XS GIS Cut Line= 3
      3596142.10     10420841.64      3595509.88     10421199.70
      3595158.63     10421426.53
#Sta/Elev= 30
  4532.8  414.96  4578.3  411.52  4590.3  409.45  4643.2  404.16  4745.6  397.26
  4820.1  396.46  4972.2  399.83  4981.0  398.92  4988.1  396.31  4993.8  397.03
  5006.7  395.53  5009.5  395.03  5012.7  395.53  5015.5  397.87  5031.3  400.00
  5236.2  397.67  5388.8  404.39  5403.4  404.62  5418.5  407.46  5433.7  408.43
  5478.3  410.02  5491.1  411.75  5512.2  411.77  5527.4  413.86  5533.4  413.47
  5548.5  415.41  5569.6  416.04  5605.9  419.51  5642.2  425.12  5677.5  426.02
#Mann=5,-1,0
  4532.8    0.16       0  5006.7    0.07       0  5012.7    0.16       0
  5388.8     0.1       0  5478.3    0.16       0
Bank Sta=5006.7,5012.7
Exp/Cntr=0.3,0.1

Type RM Length L Ch R = 1,8670,461,461,461
BEGIN DESCRIPTION:
VESTAL BRANCH 12.0
END DESCRIPTION:
XS GIS Cut Line= 3
      3596142.10     10420441.64      3595497.14     10420653.98
      3594837.42     10421070.64
#Sta/Elev= 30
  4566.1  422.33  4608.2  420.11  4650.8  416.00  4703.0  413.65  4766.1  408.37
  4836.2  400.23  4868.0  398.18  4913.5  396.77  4976.7  398.55  4987.2  394.90
  4992.1  392.02  4994.9  391.52  4998.1  392.02  5008.3  393.66  5026.9  398.67
  5039.9  399.01  5090.5  398.51  5145.1  395.16  5274.7  398.37  5305.3  397.97
  5326.5  398.93  5341.8  398.11  5378.2  399.86  5441.8  400.17  5508.8  402.04
  5718.3  413.28  5763.0  417.79  5827.7  424.14  5938.5  432.16  6025.4  435.18
#Mann=5,-1,0
  4566.1    0.16       0  4992.1    0.07       0  4998.1    0.16       0
  5763.0     0.1       0  5938.5    0.16       0
Bank Sta=4992.1,4998.1
Exp/Cntr=0.3,0.1

Type RM Length L Ch R = 1,8209,849,849,849
BEGIN DESCRIPTION:
VESTAL BRANCH 11.0
END DESCRIPTION:
XS GIS Cut Line= 3
      3596191.59     10420211.27      3595323.53     10420089.74
      3594846.61     10420055.06
#Sta/Elev= 30
  4456.9  421.32  4617.9  412.22  4781.7  396.23  4789.6  395.70  4820.3  396.80
  4853.1  397.55  4951.2  397.30  4981.5  394.95  4995.9  393.19  4998.6  391.57
  5001.4  391.07  5004.6  391.57  5021.8  396.88  5031.9  397.81  5132.9  396.72
  5163.2  398.37  5208.1  402.95  5264.2  408.24  5281.5  408.92  5286.5  410.35
  5294.5  409.47  5314.7  411.73  5331.6  412.31  5373.0  412.06  5461.8  416.60
  5505.3  417.69  5565.5  420.77  5659.4  428.43  5758.2  437.07  5811.6  440.22
#Mann=8,-1,0
  4456.9    0.16       0  4820.3    0.05       0  4998.6    0.03       0
  5004.6    0.05       0  5208.1    0.16       0  5461.8    0.05       0
  5659.4    0.16       0  5758.2    0.05       0
Bank Sta=4998.6,5004.6
Exp/Cntr=0.3,0.1

Type RM Length L Ch R = 1,7360,557,557,557
BEGIN DESCRIPTION:
VESTAL BRANCH 10.0
END DESCRIPTION:
XS GIS Cut Line= 3
      3596363.63     10419684.52      3595948.53     10419577.59
      3595246.21     10419525.56
#Sta/Elev= 30
  4408.1  417.95  4437.6  416.30  4442.7  416.62  4478.3  414.15  4483.4  414.53
  4524.1  412.85  4600.4  407.97  4657.5  402.04  4750.5  394.38  4873.3  393.57
  4903.4  394.49  4973.6  394.28  4986.8  388.51  4990.6  386.16  4993.4  385.66
  4996.6  386.16  5023.7  394.84  5093.9  394.23  5141.3  398.95  5184.1  403.67
  5252.5  414.31  5257.5  413.97  5264.3  415.66  5314.5  422.58  5344.6  425.21
  5384.7  427.76  5474.9  430.65  5523.2  427.87  5528.2  428.15  5541.0  426.54
#Mann=4,-1,0
  4408.1    0.05       0  4990.6    0.03       0  4996.6    0.05       0
  5141.3    0.16       0
Bank Sta=4990.6,4996.6
Exp/Cntr=0.3,0.1

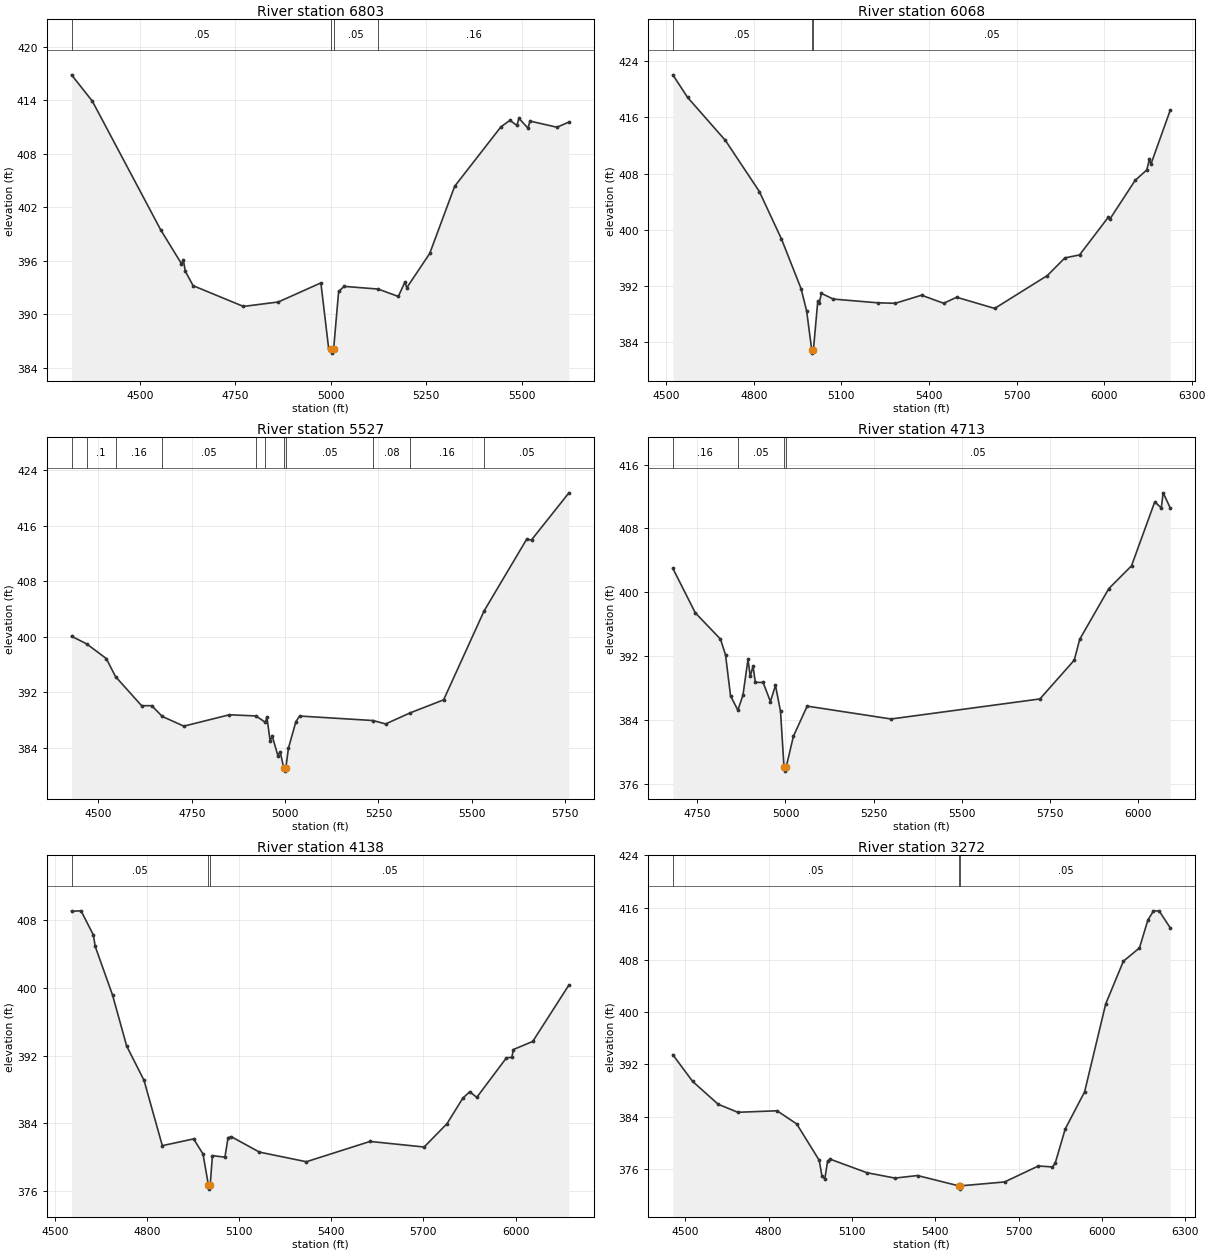
Type RM Length L Ch R = 1,6803,735,735,735
BEGIN DESCRIPTION:
VESTAL BRANCH 8.0
END DESCRIPTION:
XS GIS Cut Line= 3
      3596425.93     10419186.96      3595516.41     10419028.45
      3595166.79     10419178.28
#Sta/Elev= 30
  4320.4  416.87  4375.0  413.91  4553.9  399.49  4608.4  395.68  4613.5  396.07
  4618.7  394.82  4639.0  393.21  4770.9  390.88  4862.3  391.38  4973.9  393.52
  4994.2  386.20  5001.4  386.14  5004.1  385.64  5007.4  386.14  5020.4  392.56
  5034.8  393.13  5123.9  392.83  5176.9  392.00  5194.0  393.60  5199.1  392.98
  5259.1  396.82  5324.5  404.36  5445.9  411.04  5469.4  411.76  5487.6  411.20
  5493.0  411.99  5516.6  410.89  5522.0  411.68  5592.7  410.99  5624.0  411.57
#Mann=4,-1,0
  4320.4    0.05       0  5001.4    0.03       0  5007.4    0.05       0
  5123.9    0.16       0
Bank Sta=5001.4,5007.4
Exp/Cntr=0.3,0.1

Type RM Length L Ch R = 1,6068,541,541,541
BEGIN DESCRIPTION:
VESTAL BRANCH 7.0
END DESCRIPTION:
XS GIS Cut Line= 3
      3596564.90     10418674.82      3595853.05     10418561.96
      3594872.14     10418631.41
#Sta/Elev= 30
  4522.5  422.06  4572.8  418.86  4702.5  412.73  4818.9  405.46  4894.5  398.72
  4961.8  391.65  4980.9  388.47  4998.2  382.97  5000.9  382.47  5004.2  382.97
  5019.1  389.91  5024.1  389.62  5031.6  390.97  5072.1  390.16  5223.9  389.63
  5284.3  389.56  5374.5  390.71  5450.4  389.56  5494.8  390.42  5625.1  388.83
  5805.6  393.51  5865.7  396.02  5915.9  396.44  6014.3  401.80  6019.3  401.51
  6106.3  407.04  6146.4  408.54  6155.3  410.08  6160.3  409.33  6226.6  417.03
#Mann=3,-1,0
  4522.5    0.05       0  4998.2    0.03       0  5004.2    0.05       0
Bank Sta=4998.2,5004.2
Exp/Cntr=0.3,0.1

Type RM Length L Ch R = 1,5527,814,814,814
BEGIN DESCRIPTION:
VESTAL BRANCH 6.0
END DESCRIPTION:
XS GIS Cut Line= 3
      3596365.22     10417824.10      3595901.05     10418157.67
      3595142.11     10418191.64
#Sta/Elev= 30
  4428.4  400.08  4469.0  398.97  4521.5  396.86  4546.1  394.26  4616.0  390.07
  4643.1  390.07  4671.3  388.52  4729.0  387.12  4850.9  388.76  4921.8  388.59
  4947.5  387.67  4951.2  388.48  4959.8  385.04  4965.9  385.63  4980.7  382.87
  4986.8  383.45  4996.1  381.14  4998.9  380.64  5002.1  381.14  5008.9  383.94
  5029.0  387.78  5039.0  388.58  5235.4  387.93  5269.2  387.44  5334.5  389.03
  5424.3  390.91  5532.7  403.73  5646.2  414.02  5659.6  413.96  5759.7  420.74
#Mann=11,-1,0
  4428.4    0.16       0  4469.0     0.1       0  4546.1    0.16       0
  4671.3    0.05       0  4921.8    0.08       0  4947.5    0.05       0
  4996.1    0.03       0  5002.1    0.05       0  5235.4    0.08       0
  5334.5    0.16       0  5532.7    0.05       0
Bank Sta=4996.1,5002.1
Exp/Cntr=0.3,0.1

Type RM Length L Ch R = 1,4713,575,575,575
BEGIN DESCRIPTION:
VESTAL BRANCH 5.0
END DESCRIPTION:
XS GIS Cut Line= 3
      3596425.99     10417355.33      3596218.92     10417598.38
      3595210.64     10418015.11
#Sta/Elev= 30
  4680.7  403.00  4744.4  397.43  4815.8  394.14  4830.1  392.16  4844.3  387.03
  4865.1  385.24  4879.5  387.13  4893.7  391.59  4900.3  389.49  4908.0  390.76
  4914.6  388.73  4936.6  388.71  4957.4  386.32  4971.7  388.35  4986.0  385.09
  4995.9  378.11  4998.6  377.61  5001.9  378.11  5022.6  381.98  5061.5  385.75
  5299.5  384.14  5721.5  386.65  5818.9  391.51  5834.2  394.11  5916.7  400.46
  5981.2  403.32  6047.1  411.33  6065.6  410.57  6071.0  412.46  6091.0  410.57
#Mann=4,-1,0
  4680.7    0.16       0  4865.1    0.05       0  4995.9    0.03       0
  5001.9    0.05       0
Bank Sta=4995.9,5001.9
Exp/Cntr=0.3,0.1

Type RM Length L Ch R = 1,4138,866,866,866
BEGIN DESCRIPTION:
VESTAL BRANCH 3.0
END DESCRIPTION:
XS GIS Cut Line= 3
      3596451.96     10417051.56      3595662.07     10417207.80
      3594925.63     10417554.36
#Sta/Elev= 30
  4554.5  409.07  4585.4  409.12  4625.7  406.26  4631.5  404.92  4687.9  399.17
  4734.0  393.13  4790.4  389.08  4850.0  381.35  4951.9  382.15  4982.5  380.36
  4999.9  376.71  5002.6  376.21  5005.9  376.71  5013.1  380.17  5053.8  379.99
  5064.0  382.29  5074.2  382.42  5166.0  380.59  5318.9  379.45  5526.2  381.85
  5702.3  381.19  5776.9  383.96  5828.0  386.96  5850.8  387.73  5873.6  387.06
  5970.3  391.74  5987.6  391.79  5993.1  392.72  6055.9  393.68  6173.6  400.35
#Mann=3,-1,0
  4554.5    0.05       0  4999.9    0.03       0  5005.9    0.05       0
Bank Sta=4999.9,5005.9
Exp/Cntr=0.3,0.1

Type RM Length L Ch R = 1,3272,0,0,0
BEGIN DESCRIPTION:
VESTAL BRANCH 1.0
END DESCRIPTION:
XS GIS Cut Line= 3
      3596364.64     10416579.43      3596148.18     10416374.46
      3594672.46     10416591.48
#Sta/Elev= 30
  4455.6  393.48  4526.7  389.41  4618.6  385.91  4689.3  384.68  4830.6  384.91
  4901.2  382.90  4982.2  377.34  4992.3  374.88  5002.4  374.51  5012.5  377.23
  5022.6  377.49  5154.0  375.43  5255.1  374.61  5336.0  375.00  5484.6  373.42
  5487.3  372.92  5490.6  373.42  5649.3  374.02  5770.6  376.46  5821.1  376.32
  5831.2  376.87  5867.5  382.13  5937.2  387.81  6013.2  401.28  6076.7  407.80
  6134.5  409.83  6164.8  414.09  6185.0  415.49  6205.2  415.51  6245.3  412.91
#Mann=3,-1,0
  4455.6    0.05       0  5484.6    0.03       0  5490.6    0.05       0
Bank Sta=5484.6,5490.6
Exp/Cntr=0.3,0.1

Chan Stop Cuts=-1