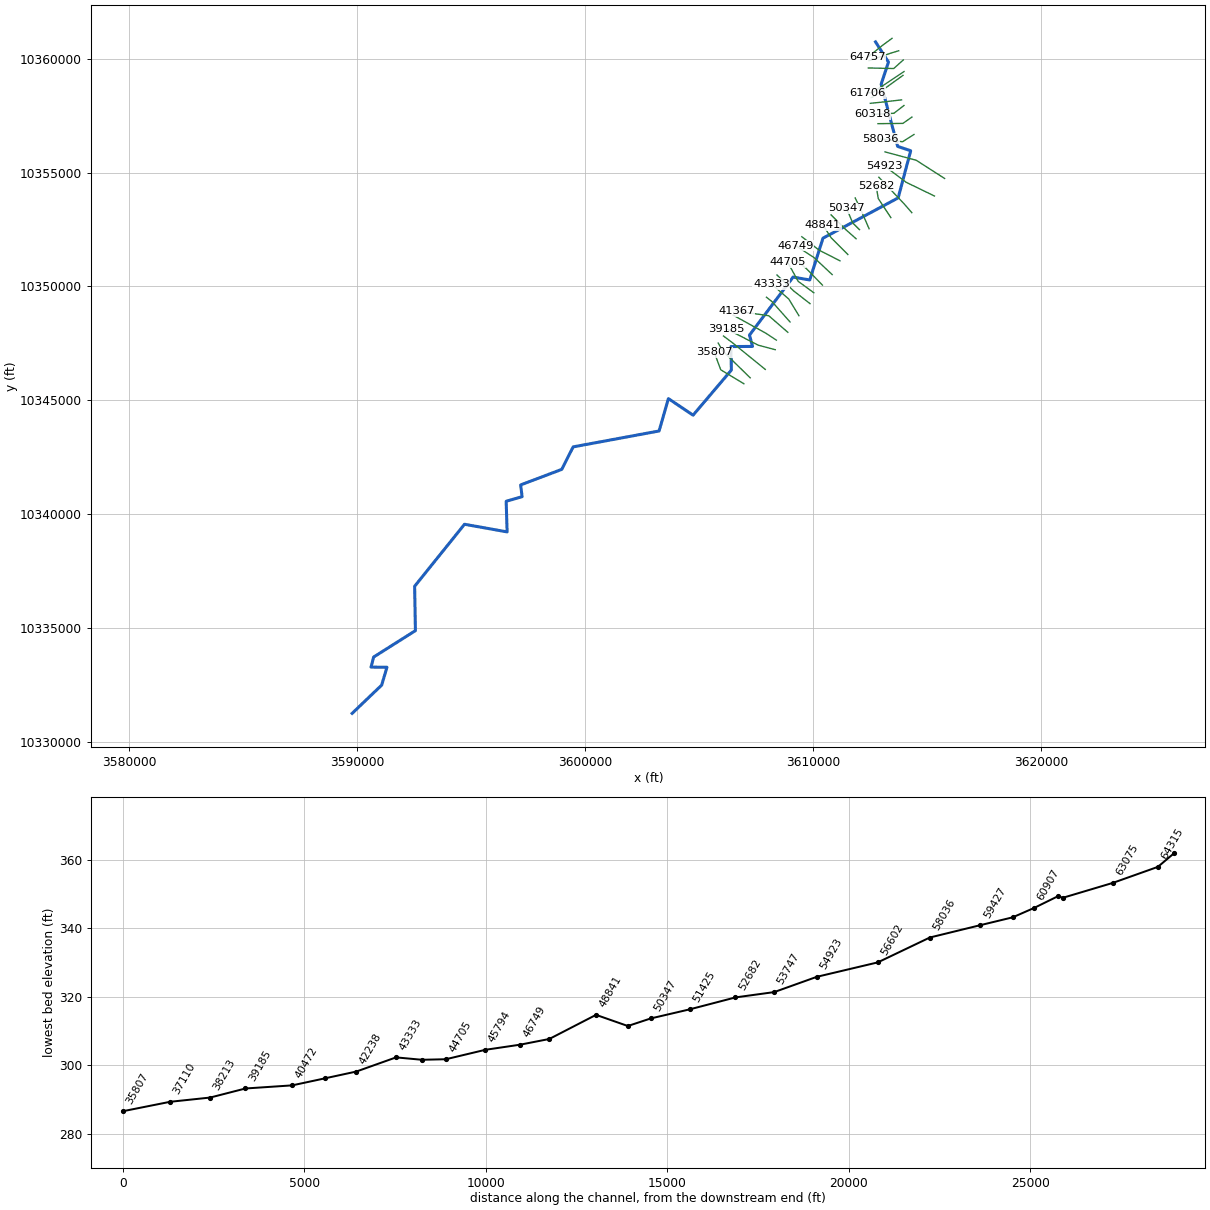
--- WEST CANEY CREEK.prj (project) ---

Proj Title=WEST CANEY CREEK Base Level Engineering
Current Plan=p01
Default Exp/Contr=0.3,0.1
English Units
Geom File=g01
Flow File=f01
Plan File=p01
Y Axis Title=Elevation
X Axis Title(PF)=Main Channel Distance
X Axis Title(XS)=Station
BEGIN DESCRIPTION:
WEST CANEY CREEK
END DESCRIPTION:
DSS Export Rating Curves= 0
DSS Export Rating Curve Sorted= 0
DSS Export Volume Flow Curves= 0
DXF OffsetX= 0
DXF OffsetY= 0
DXF ScaleX= 1
DXF ScaleY= 10

--- WEST CANEY CREEK.p01 (plan) ---

Plan Title=Multiple Run
Short Identifier=Multiple
Geom File=g01
Flow File=f01
Subcritical Flow
K Sum by GR= 0
Std Step Tol= 0.01
Critical Tol= 0.01
Num of Std Step Trials= 20
Max Error Tol= 0.3
Flow Tol Ratio= 0.001
Split Flow NTrial= 30
Split Flow Tol= 0.02
Split Flow Ratio= 0.02
Log Output Level= 0
Friction Slope Method= 1
Unsteady Friction Slope Method= 2
Unsteady Bridges Friction Slope Method= 1
Parabolic Critical Depth
Global Vel Dist=  1 , 1 , 1
Global Log Level= 0
CheckData=True
Encroach Param= -1, 0, 0, 0
BEGIN DESCRIPTION:
Multiple Run
END DESCRIPTION:

--- WEST CANEY CREEK.f01 (steady flow) ---

Flow Title=Multiple
Program Version=4.10
Number of Profiles= 7
Profile Names=10-year,25-year,50-year,1pct_min,100-year,1pct_plu,500-year
River Rch & RM=WEST CANEY CREEK,Reach-1         ,64757
    1124    1538    1878    1672    2261    3058    3267
River Rch & RM=WEST CANEY CREEK,Reach-1         ,56602
    2176    3082    3852    3502    4736    6405    7142
River Rch & RM=WEST CANEY CREEK,Reach-1         ,53747
    2176    3082    3852    3502    4736    6405    7142
River Rch & RM=WEST CANEY CREEK,Reach-1         ,51425
    2428    3457    4334    3952    5344    7228    8108
River Rch & RM=WEST CANEY CREEK,Reach-1         ,49717
    2735    3918    4935    4521    6114    8268    9369
River Rch & RM=WEST CANEY CREEK,Reach-1         ,46749
    2791    3999    5035    4613    6238    8436    9567
River Rch & RM=WEST CANEY CREEK,Reach-1         ,41367
    5707    8441   10865   10155   13734   18573   21914
River Rch & RM=WEST CANEY CREEK,Reach-1         ,40472
    5707    8441   10865   10155   13734   18573   21914
River Rch & RM=WEST CANEY CREEK,Reach-1         ,35033
    6793   10093   13031   12213   16516   22337   26494
River Rch & RM=WEST CANEY CREEK,Reach-1         ,33794
    6793   10093   13031   12213   16516   22337   26494
River Rch & RM=WEST CANEY CREEK,Reach-1         ,28791
    6907   10258   13240   12406   16777   22689   26903
River Rch & RM=WEST CANEY CREEK,Reach-1         ,24691
    6867   10166   13093   12242   16556   22391   26448
River Rch & RM=WEST CANEY CREEK,Reach-1         ,18937
    7716   11453   14780   13847   18726   25325   30041
River Rch & RM=WEST CANEY CREEK,Reach-1         ,13985
    7716   11453   14780   13847   18726   25325   30041
River Rch & RM=WEST CANEY CREEK,Reach-1         ,7021
    7661   11342   14611   13664   18479   24991   29546
River Rch & RM=WEST CANEY CREEK,Reach-1         ,4841
    7661   11342   14611   13664   18479   24991   29546
Boundary for River Rch & Prof#=WEST CANEY CREEK,Reach-1         , 1
Up Type= 0
Dn Type= 3
Dn Slope=0.00116
Boundary for River Rch & Prof#=WEST CANEY CREEK,Reach-1         , 2
Up Type= 0
Dn Type= 3
Dn Slope=0.00116
Boundary for River Rch & Prof#=WEST CANEY CREEK,Reach-1         , 3
Up Type= 0
Dn Type= 3
Dn Slope=0.00116
Boundary for River Rch & Prof#=WEST CANEY CREEK,Reach-1         , 4
Up Type= 0
Dn Type= 3
Dn Slope=0.00116
Boundary for River Rch & Prof#=WEST CANEY CREEK,Reach-1         , 5
Up Type= 0
Dn Type= 3
Dn Slope=0.00116
Boundary for River Rch & Prof#=WEST CANEY CREEK,Reach-1         , 6
Up Type= 0
Dn Type= 3
Dn Slope=0.00116
Boundary for River Rch & Prof#=WEST CANEY CREEK,Reach-1         , 7
Up Type= 0
Dn Type= 3
Dn Slope=0.00116
DSS Import GetInterval= 0
DSS Import GetPeak= 0
DSS Import FillOption= 0

--- WEST CANEY CREEK.g01 (geometry) ---

Geom Title=Existing Conditions
Program Version=4.10

River Reach=WEST CANEY CREEK,Reach-1
Reach XY= 30
      3612746.01     10360733.52      3613312.97      10359845.7
      3612992.22     10358876.95        3613714.     10356147.33
       3614288.5     10355956.92      3613738.71     10353887.22
      3610439.13     10352119.42      3609857.47     10350284.53
      3609126.61       10350411.      3607212.17      10347864.9
      3607346.72      10347367.5      3606402.56     10347361.86
      3606417.06     10346329.09      3604736.59     10344349.48
      3603653.65     10345078.27      3603244.74     10343656.53
      3599473.51     10342958.58      3598972.17     10341970.33
      3597168.63     10341288.49      3597231.85     10340772.87
      3596533.09      10340570.4      3596574.99     10339226.73
      3594704.44     10339561.95      3592515.56     10336840.28
      3592549.63     10334892.67      3590717.02     10333734.55
      3590601.84     10333292.05      3591300.16     10333286.11
      3591069.76     10332502.56      3589772.11     10331261.64

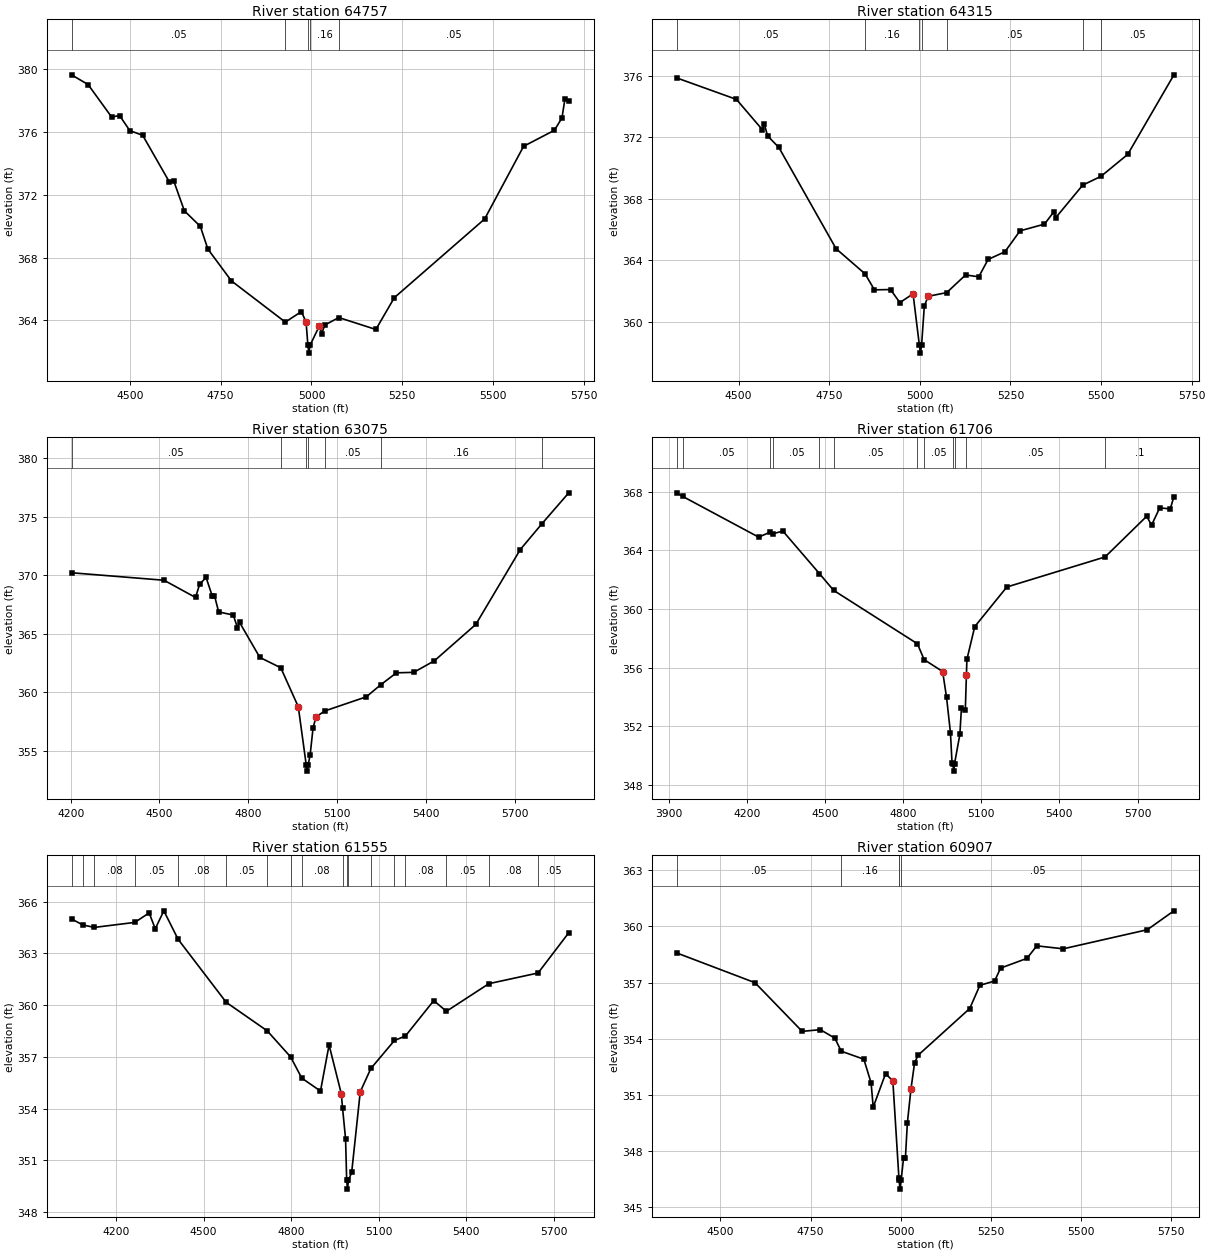
Type RM Length L Ch R = 1 ,64757   ,442,442,442
BEGIN DESCRIPTION:
WEST CANEY CREEK 75.0
END DESCRIPTION:
XS GIS Cut Line= 3
      3613468.51     10360890.27      3613049.02     10360579.84
       3612386.7     10360051.66
#Sta/Elev= 30
  4339.4  379.66    4385  379.04  4449.7  376.97  4471.8  377.06  4499.8   376.1
  4535.3   375.8  4608.4  372.84  4621.1  372.87  4650.1  370.98    4694  369.99
  4714.8  368.54  4779.6  366.51    4928  363.88  4972.3  364.55  4985.2  363.88
  4990.2   362.4  4992.9   361.9  4996.2   362.4    5022  363.65  5028.4  363.14
  5036.4  363.69  5075.3  364.17  5177.3  363.41  5228.2  365.44  5476.8  370.46
  5584.1   375.1  5668.9  376.12  5689.7  376.91  5697.7  378.09  5708.4  378.02
#Mann= 5 ,-1 , 0
  4339.4     .05       0    4928     .16       0  4990.2     .07       0
  4996.2     .16       0  5075.3     .05       0
Bank Sta=4985.2,5022
XS Rating Curve= 0 ,0
Exp/Cntr=0.3,0.1

Type RM Length L Ch R = 1 ,64315   ,1240,1240,1240
BEGIN DESCRIPTION:
WEST CANEY CREEK 74.0
END DESCRIPTION:
XS GIS Cut Line= 3
       3613762.1     10360344.91      3613426.55     10360244.25
      3612461.77     10359908.67
#Sta/Elev= 30
  4329.3  375.88  4494.2  374.48  4565.5  372.51  4570.8   372.9  4579.9  372.11
  4611.2  371.35    4769  364.76  4849.1  363.12  4874.9  362.08  4919.2   362.1
    4945  361.25  4981.4  361.82  4998.9  358.46  5001.7  357.96  5004.9  358.46
  5012.5  361.03  5023.1  361.66  5074.2   361.9  5126.3  363.05  5162.7  362.93
  5188.5  364.06  5234.9  364.56  5276.5  365.92    5344  366.36  5369.8  367.16
  5375.1  366.78  5449.5   368.9  5499.9  369.47  5573.7   370.9  5701.1  376.08
#Mann= 7 ,-1 , 0
  4329.3     .05       0  4849.1     .16       0  4998.9     .07       0
  5004.9     .16       0  5074.2     .05       0  5449.5     .16       0
  5499.9     .05       0
Bank Sta=4981.4,5023.1
XS Rating Curve= 0 ,0
Exp/Cntr=0.3,0.1

Type RM Length L Ch R = 1 ,63075   ,1369,1369,1369
BEGIN DESCRIPTION:
WEST CANEY CREEK 73.0
END DESCRIPTION:
XS GIS Cut Line= 3
      3613963.53     10359942.25      3613544.01     10359564.68
       3612428.2     10359589.85
#Sta/Elev= 30
  4202.7  370.23  4515.4  369.59  4621.7  368.12  4635.8  369.25  4657.4  369.83
  4678.4  368.24  4685.8  368.28    4700  366.88  4749.4  366.62  4763.6  365.53
  4770.6  365.99    4839     363  4909.9  362.11  4969.1  358.78  4996.1  353.78
  4998.8  353.28  5002.1  353.78  5009.1  354.65  5019.1  356.99  5029.1  357.91
  5058.4  358.42  5199.1  359.63  5247.3  360.65  5300.7  361.68  5359.2  361.72
  5429.2  362.71  5569.2  365.82  5719.3  372.21  5792.6  374.42  5883.2  377.06
#Mann= 7 ,-1 , 0
  4202.7     .05       0  4909.9     .16       0  4996.1     .07       0
  5002.1     .16       0  5058.4     .05       0  5247.3     .16       0
  5792.6     .05       0
Bank Sta=4969.1,5029.1
XS Rating Curve= 0 ,0
Exp/Cntr=0.3,0.1

Type RM Length L Ch R = 1 ,61706   ,151,151,151
BEGIN DESCRIPTION:
WEST CANEY CREEK 72.0
END DESCRIPTION:
XS GIS Cut Line= 3
      3613996.47     10359432.66      3612619.72     10358514.25
      3612368.03     10358488.22
#Sta/Elev= 30
  3931.4  367.92    3955  367.67  4245.9   364.9  4291.3  365.25  4302.2  365.14
    4339  365.31  4479.3  362.41  4533.7  361.27  4855.2  357.63  4880.9  356.55
  4951.9  355.74  4966.9  353.98  4981.9  351.57  4987.9  349.53  4991.5  349.45
  4994.2  348.95  4997.5  349.45    5018  351.45    5024  353.24    5039  353.13
  5043.2  355.53    5045  356.56  5075.1   358.8  5198.2   361.5  5575.3  363.55
  5734.8  366.32  5753.7  365.72    5785   366.9  5825.2  366.82  5839.4  367.66
#Mann= 12 ,-1 , 0
  3931.4     .08       0    3955     .05       0  4291.3     .08       0
  4302.2     .05       0  4479.3     .08       0  4533.7     .05       0
  4855.2     .08       0  4880.9     .05       0  4991.5     .07       0
  4997.5     .05       0  5043.2     .05       0  5575.3      .1       0
Bank Sta=4951.9,5043.2
XS Rating Curve= 0 ,0
Exp/Cntr=0.3,0.1

Type RM Length L Ch R = 1 ,61555   ,648,648,648
BEGIN DESCRIPTION:
WEST CANEY CREEK 71.0
END DESCRIPTION:
XS GIS Cut Line= 3
      3613949.55     10359264.23      3612626.66     10358312.86
      3612556.27     10358292.26
#Sta/Elev= 30
  4047.8  364.99  4086.6  364.64  4126.2   364.5  4264.5  364.79  4313.6  365.34
  4334.5  364.42  4363.9  365.46  4412.8  363.81  4577.6  360.16  4717.9  358.51
    4798     357  4836.3  355.77  4900.4  355.02  4929.8  357.69  4971.6  354.87
  4975.9  354.04  4986.3  352.25  4990.1  349.84  4992.8  349.34  4996.1  349.84
  5007.2  350.31  5036.6  354.98    5073  356.33  5153.7  357.95  5191.3  358.21
  5288.3  360.26  5331.6  359.64    5477  361.24  5645.6  361.86  5750.6  364.19
#Mann= 18 ,-1 , 0
  4047.8     .08       0  4086.6     .05       0  4126.2     .08       0
  4264.5     .05       0  4412.8     .08       0  4577.6     .05       0
  4717.9     .08       0    4798     .12       0  4836.3     .08       0
  4975.9     .05       0  4990.1     .03       0  4996.1     .05       0
    5073     .08       0  5153.7     .05       0  5191.3     .08       0
  5331.6     .05       0    5477     .08       0  5645.6     .05       0
Bank Sta=4971.6,5036.6
XS Rating Curve= 0 ,0
Exp/Cntr=0.3,0.1

Type RM Length L Ch R = 1 ,60907   ,589,589,589
BEGIN DESCRIPTION:
WEST CANEY CREEK 70.0
END DESCRIPTION:
XS GIS Cut Line= 3
      3613887.99     10358188.77      3613015.92     10358088.94
      3612516.47     10358038.99
#Sta/Elev= 30
  4378.6  358.58  4595.9  356.99  4726.7  354.39  4777.1  354.48  4817.3  354.03
  4835.2  353.33  4897.9   352.9    4918  351.64  4923.9  350.34  4958.2  352.13
  4978.4  351.74  4995.3  346.53  4995.5  346.46  4998.3  345.96  5001.5  346.46
  5008.2  347.64  5013.2   347.6  5018.6  349.48  5028.7  351.32  5038.8  352.72
  5048.8  353.12  5191.7  355.61  5219.9  356.85  5260.8  357.08  5277.3  357.77
  5350.6  358.29  5377.8  358.96  5451.1   358.8  5684.4  359.82  5758.3  360.83
#Mann= 5 ,-1 , 0
  4378.6     .05       0  4835.2     .16       0  4995.3     .05       0
  4995.5     .03       0  5001.5     .05       0
Bank Sta=4978.4,5028.7
XS Rating Curve= 0 ,0
Exp/Cntr=0.3,0.1

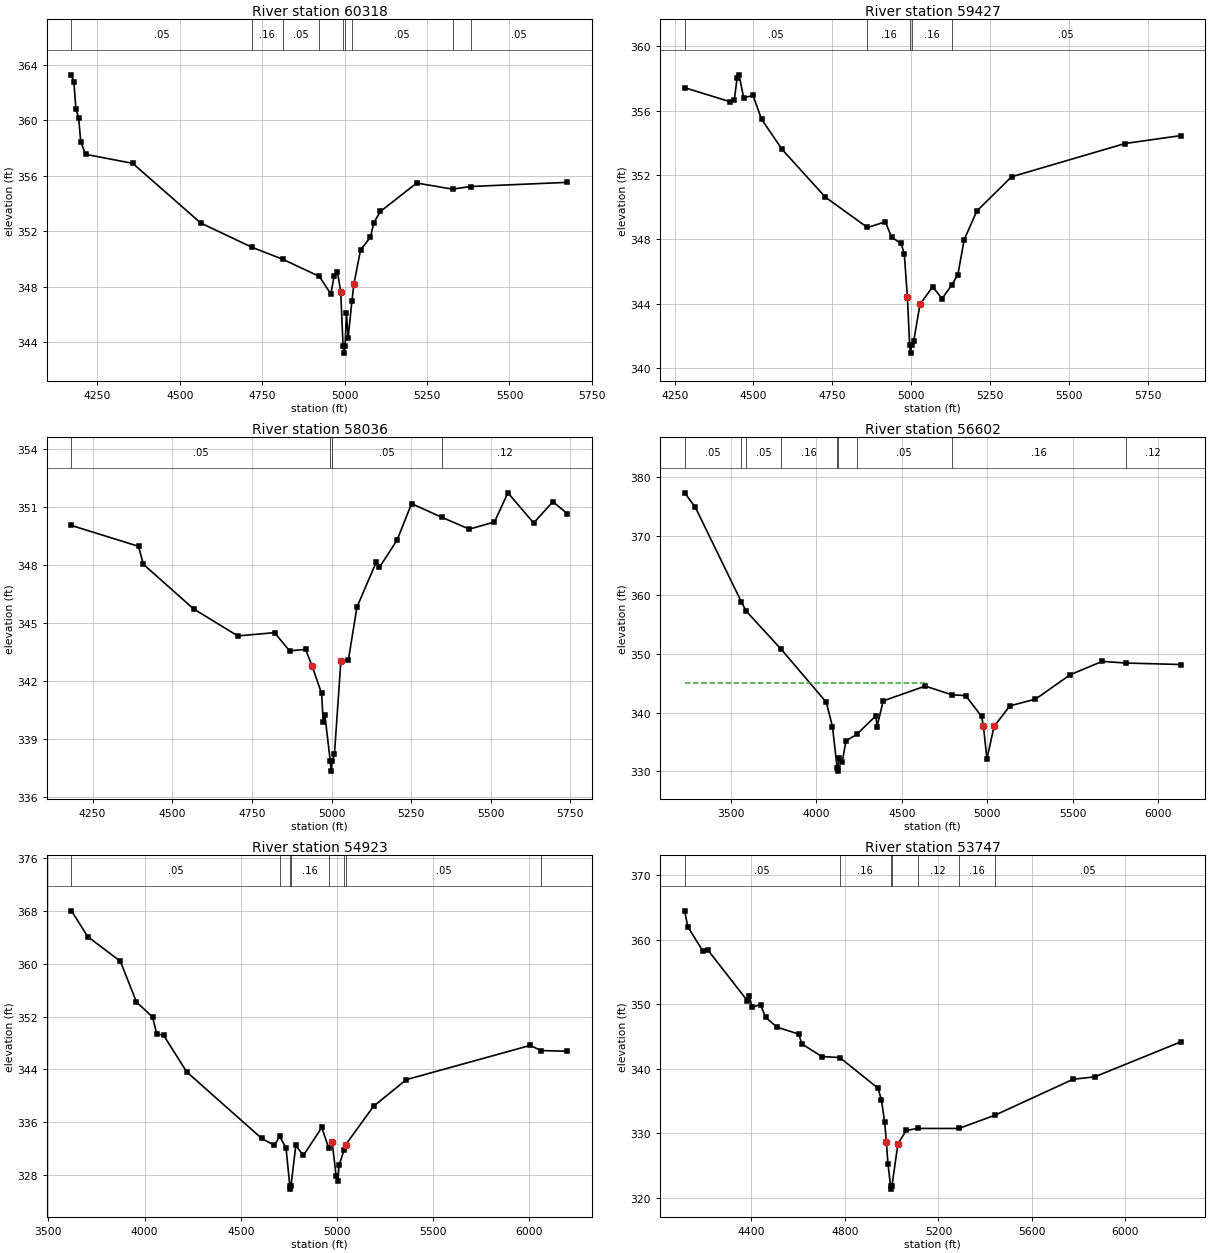
Type RM Length L Ch R = 1 ,60318   ,891,891,891
BEGIN DESCRIPTION:
WEST CANEY CREEK 69.0
END DESCRIPTION:
XS GIS Cut Line= 3
      3613992.14     10357941.67       3613552.4     10357601.49
      3612605.69     10357551.23
#Sta/Elev= 30
  4171.7  363.28    4179  362.77  4185.3  360.81  4193.5  360.17  4199.8  358.47
  4214.3  357.55  4357.4   356.9  4563.7   352.6    4718  350.86  4812.8  349.98
  4923.4  348.75  4958.3  347.48  4968.3   348.8  4978.3   349.1  4988.3  347.62
  4995.3  343.72  4998.1  343.22  5001.3  343.72  5005.6  346.09  5010.6  344.29
  5022.1  346.96  5028.4  348.23  5048.4  350.66  5078.4  351.58  5088.5  352.62
  5108.5  353.43  5218.6  355.48  5327.4  355.04  5381.8  355.23  5675.7  355.53
#Mann= 9 ,-1 , 0
  4171.7     .05       0    4718     .16       0  4812.8     .05       0
  4923.4     .16       0  4995.3     .07       0  5001.3     .16       0
  5022.1     .05       0  5327.4      .1       0  5381.8     .05       0
Bank Sta=4988.3,5028.4
XS Rating Curve= 0 ,0
Exp/Cntr=0.3,0.1

Type RM Length L Ch R = 1 ,59427   ,1391,1391,1391
BEGIN DESCRIPTION:
WEST CANEY CREEK 68.0
END DESCRIPTION:
XS GIS Cut Line= 3
      3614341.04      10357433.7      3613946.71     10357156.84
      3612855.79      10357145.1
#Sta/Elev= 30
  4281.8  357.43  4427.1  356.55  4439.4  356.69  4448.1  358.03  4454.2  358.23
    4469   356.8  4498.6  356.95  4525.6  355.47    4591  353.59  4727.8  350.63
  4861.5  348.74  4918.2  349.09  4938.2  348.13  4968.2  347.75  4978.2  347.11
  4988.2   344.4  4995.2  341.43    4998  340.93  5001.2  341.43  5008.2  341.69
  5028.2  343.97  5068.2  345.05  5098.2  344.32  5129.3  345.18  5148.2  345.81
  5168.2  347.98  5208.2  349.76  5318.3  351.89  5678.3  353.96  5854.6  354.45
#Mann= 5 ,-1 , 0
  4281.8     .05       0  4861.5     .16       0  4995.2     .07       0
  5001.2     .16       0  5129.3     .05       0
Bank Sta=4988.2,5028.2
XS Rating Curve= 0 ,0
Exp/Cntr=0.3,0.1

Type RM Length L Ch R = 1 ,58036   ,1434,1434,1434
BEGIN DESCRIPTION:
WEST CANEY CREEK 67.0
END DESCRIPTION:
XS GIS Cut Line= 3
      3614433.35     10356670.26      3613929.94     10356351.43
      3612976.92     10356475.92
#Sta/Elev= 30
  4183.6  350.04  4394.1  348.96  4409.3  348.03    4567  345.72  4705.9  344.32
  4821.2  344.49  4868.1  343.55  4918.5  343.62  4938.7  342.78  4968.9  341.34
    4974  339.85  4979.1  340.23  4996.2  337.82  4998.9  337.32  5002.2  337.82
  5009.3  338.22  5029.4  343.03    5053  343.08  5079.8  345.81  5140.4  348.14
  5150.4  347.87  5205.8  349.28  5251.3  351.17  5346.7  350.46  5432.6  349.85
  5511.5  350.22  5553.8  351.73  5634.5  350.17    5695  351.27  5740.6  350.65
#Mann= 4 ,-1 , 0
  4183.6     .05       0  4996.2     .03       0  5002.2     .05       0
  5346.7     .12       0
Bank Sta=4938.7,5029.4
XS Rating Curve= 0 ,0
Exp/Cntr=0.3,0.1

Type RM Length L Ch R = 1 ,56602   ,1679,1679,1679
BEGIN DESCRIPTION:
WEST CANEY CREEK 66.0
END DESCRIPTION:
XS GIS Cut Line= 3
      3615775.63     10354740.63      3614533.99     10355537.63
      3613158.36      10355906.7
#Sta/Elev= 30
  3230.4  377.37  3292.6  374.92    3561  358.89  3589.9  357.27  3794.1  350.79
  4058.3  341.77  4094.6  337.63    4122  330.55  4124.7  330.05    4128  330.55
  4130.9  332.34  4152.1  331.67  4173.3  335.19  4236.6   336.3    4349  339.48
  4354.9  337.56  4391.2  341.99  4636.8  344.51  4792.2  343.03  4873.4  342.89
  4966.6  339.34  4977.2  337.69  4997.7  332.11  5039.1  337.65  5132.3  341.15
  5281.6  342.29  5484.3  346.44  5671.3  348.71  5807.9  348.43  6130.1  348.18
#Mann= 9 ,-1 , 0
  3230.4     .05       0    3561     .16       0  3589.9     .05       0
  3794.1     .16       0    4122     .07       0    4128     .16       0
  4236.6     .05       0  4792.2     .16       0  5807.9     .12       0
#XS Ineff= 2 , 0
         4638.64  344.96
Permanent Ineff=
       F       F
Bank Sta=4977.2,5039.1
XS Rating Curve= 0 ,0
Exp/Cntr=0.3,0.1

Type RM Length L Ch R = 1 ,54923   ,1176,1176,1176
BEGIN DESCRIPTION:
WEST CANEY CREEK 65.0
END DESCRIPTION:
XS GIS Cut Line= 3
      3615330.99     10353968.77        3614090.      10354572.6
      3613132.92     10355294.32
#Sta/Elev= 30
  3619.9  368.02  3704.3  364.11  3874.4  360.36  3957.9  354.19  4041.3  351.93
  4063.5  349.36  4098.7  349.17  4219.2   343.6  4608.4  333.53  4675.2  332.46
  4702.4  333.81  4735.6  332.07  4755.2  326.33  4757.9  325.83  4761.2  326.33
  4786.4  332.45  4825.8  330.94  4921.6  335.18  4956.5  332.14  4975.4  332.98
    4996  327.83  5005.2  327.04  5011.4  329.48    5037  331.72  5045.7  332.56
  5190.5  338.39  5361.2  342.43  6004.4  347.61  6062.1  346.84  6198.7  346.73
#Mann= 8 ,-1 , 0
  3619.9     .05       0  4702.4     .16       0  4755.2     .03       0
  4761.2     .16       0  4956.5     .05       0    5037     .16       0
  5045.7     .05       0  6062.1     .12       0
Bank Sta=4975.4,5045.7
XS Rating Curve= 0 ,0
Exp/Cntr=0.3,0.1

Type RM Length L Ch R = 1 ,53747   ,1065,1065,1065
BEGIN DESCRIPTION:
WEST CANEY CREEK 64.0
END DESCRIPTION:
XS GIS Cut Line= 3
      3614338.13     10353239.25      3613988.11     10353639.27
      3612892.09     10354791.66
#Sta/Elev= 30
  4114.5  364.47  4127.8  362.01  4191.4   358.3  4212.3  358.47  4383.1  350.53
  4389.7   351.2    4404  349.54  4439.1  349.94  4460.9  347.96  4510.3  346.44
  4602.3  345.38  4616.6  343.83  4701.6   341.9  4778.3  341.74  4941.9  336.99
    4956  335.22  4970.2  331.78  4977.4  328.68  4984.3  325.28  4995.5  321.86
  4998.2  321.36  5001.5  321.86  5026.8  328.35  5062.4  330.45  5111.6  330.76
  5287.6  330.76  5441.4   332.8  5776.7  338.38  5868.5  338.75  6236.4  344.16
#Mann= 7 ,-1 , 0
  4114.5     .05       0  4778.3     .16       0  4995.5     .07       0
  5001.5     .16       0  5111.6     .12       0  5287.6     .16       0
  5441.4     .05       0
Bank Sta=4977.4,5026.8
XS Rating Curve= 0 ,0
Exp/Cntr=0.3,0.1

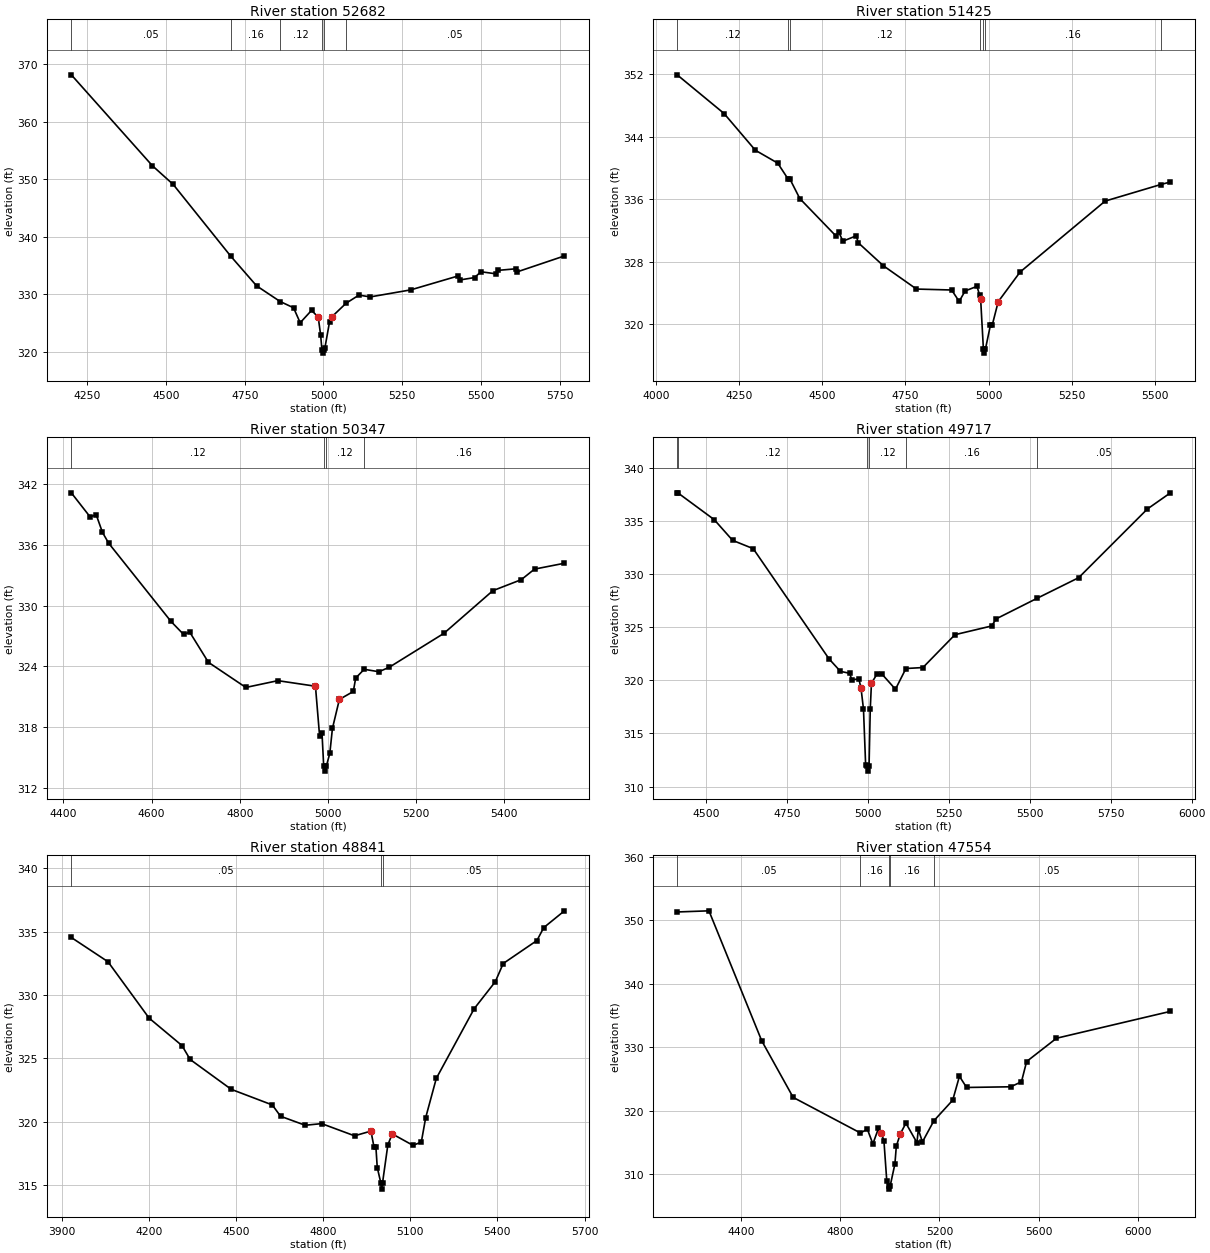
Type RM Length L Ch R = 1 ,52682   ,1257,1257,1257
BEGIN DESCRIPTION:
WEST CANEY CREEK 63.0
END DESCRIPTION:
XS GIS Cut Line= 3
      3613418.19     10353020.68      3612864.44     10353859.69
      3612772.16     10354413.38
#Sta/Elev= 30
    4199  368.17  4456.4  352.38  4522.7  349.12  4705.4  336.66  4787.6   331.5
  4862.4  328.78    4905  327.69  4926.1  325.09  4962.2  327.24  4983.3  326.07
  4990.9  323.04  4995.3  320.31  4998.1  319.81  5001.3  320.31  5004.3  320.62
  5019.4  325.26  5026.9  326.13  5071.9  328.48  5112.7  329.89  5148.8  329.58
  5277.2   330.8  5427.8  333.22  5432.9  332.52    5480  332.94  5500.3  333.95
  5549.5  333.58  5554.5  334.19  5610.3  334.46  5615.4  333.93  5765.6   336.7
#Mann= 6 ,-1 , 0
    4199     .05       0  4705.4     .16       0  4862.4     .12       0
  4995.3     .07       0  5001.3     .12       0  5071.9     .05       0
Bank Sta=4983.3,5026.9
XS Rating Curve= 0 ,0
Exp/Cntr=0.3,0.1

Type RM Length L Ch R = 1 ,51425   ,1078,1078,1078
BEGIN DESCRIPTION:
WEST CANEY CREEK 61.0
END DESCRIPTION:
XS GIS Cut Line= 3
      3612461.73     10352534.14      3612050.83     10353484.61
      3611850.83     10353884.61
#Sta/Elev= 30
  4063.8  351.95  4204.8     347  4298.8   342.3  4366.1  340.65  4396.5  338.67
  4402.1  338.67  4432.6  336.11  4540.4  331.36  4550.1  331.78  4562.2  330.66
  4602.5  331.35    4608  330.47  4683.9  327.51  4783.3  324.53  4889.1  324.41
  4911.7  322.95  4929.7  324.29  4965.3  324.88  4973.2  323.75  4976.2  323.32
  4984.6  316.83  4987.4  316.33  4990.6  316.83  5005.7  319.91  5011.1  319.91
  5029.2  322.92  5094.9  326.71  5350.6  335.79  5517.9  337.91  5546.5  338.23
#Mann= 7 ,-1 , 0
  4063.8     .12       0  4396.5     .16       0  4402.1     .12       0
  4973.2     .16       0  4984.6     .07       0  4990.6     .16       0
  5517.9     .12       0
Bank Sta=4976.2,5029.2
XS Rating Curve= 0 ,0
Exp/Cntr=0.3,0.1

Type RM Length L Ch R = 1 ,50347   ,630,630,630
BEGIN DESCRIPTION:
WEST CANEY CREEK 60.0
END DESCRIPTION:
XS GIS Cut Line= 3
      3612042.12     10352491.63      3611744.08     10352789.67
      3611471.75     10353431.82
#Sta/Elev= 30
  4417.8  341.13  4460.2  338.77  4474.4  338.95  4488.5  337.22  4502.7  336.15
  4644.1  328.43  4672.4  327.16  4686.5  327.38  4728.9   324.4  4813.8  321.92
  4886.5  322.59  4971.8  322.04  4981.2  317.12  4986.6  317.45  4990.5  314.16
  4993.3  313.66  4996.5  314.16  5004.4  315.42  5010.3  317.87  5026.1  320.74
  5057.7  321.52  5063.1  322.85  5082.4  323.71  5115.9  323.47  5139.5  323.92
  5263.3  327.26  5374.3  331.47  5438.9  332.56  5468.9   333.6  5536.8  334.18
#Mann= 4 ,-1 , 0
  4417.8     .12       0  4990.5     .07       0  4996.5     .12       0
  5082.4     .16       0
Bank Sta=4971.8,5026.1
XS Rating Curve= 0 ,0
Exp/Cntr=0.3,0.1

Type RM Length L Ch R = 1 ,49717   ,876,876,876
BEGIN DESCRIPTION:
WEST CANEY CREEK 59.0
END DESCRIPTION:
XS GIS Cut Line= 3
      3611893.34     10352091.37      3611442.11     10352491.64
      3610792.12     10353141.63
#Sta/Elev= 30
  4411.6  337.62  4413.6  337.62  4525.9   335.1  4582.8  333.15  4646.4  332.37
  4880.6     322  4915.7  320.83  4944.1  320.65  4950.8  320.03  4972.5  320.13
  4979.2  319.25  4986.8  317.29  4993.5  312.01    4998  311.95  5000.7  311.45
    5004  311.95  5007.7  317.27  5011.4  319.72  5028.9  320.59  5043.1   320.6
  5085.5  319.15  5117.9   321.1  5170.3  321.19  5269.3  324.28  5382.5   325.1
  5396.6  325.77  5522.6   327.7  5651.2  329.64  5863.3   336.1    5934  337.61
#Mann= 6 ,-1 , 0
  4411.6     .16       0  4413.6     .12       0    4998     .07       0
    5004     .12       0  5117.9     .16       0  5522.6     .05       0
Bank Sta=4979.2,5011.4
XS Rating Curve= 0 ,0
Exp/Cntr=0.3,0.1

Type RM Length L Ch R = 1 ,48841   ,1287,1287,1287
BEGIN DESCRIPTION:
WEST CANEY CREEK 57.0
END DESCRIPTION:
XS GIS Cut Line= 3
      3611531.37     10351402.37      3610792.11     10352141.64
      3610442.11     10352691.64
#Sta/Elev= 30
  3933.3  334.53  4059.5  332.62    4201  328.18  4314.1  326.02  4342.4  324.92
  4483.8  322.57  4625.2  321.34  4653.5  320.45  4738.4  319.74  4794.9  319.87
  4908.1  318.91  4964.6  319.28  4975.2  318.03  4981.7  318.03  4986.4  316.41
  4998.6  315.21  5001.4  314.71  5004.6  315.21  5022.8  318.19    5038  319.06
  5109.2  318.16    5138  318.41  5153.2  320.35  5189.6  323.43    5320  328.92
  5392.8  331.05  5419.9  332.48  5535.9  334.29  5559.6  335.31  5630.7  336.63
#Mann= 3 ,-1 , 0
  3933.3     .05       0  4998.6     .03       0  5004.6     .05       0
Bank Sta=4964.6,5038
XS Rating Curve= 0 ,0
Exp/Cntr=0.3,0.1

Type RM Length L Ch R = 1 ,47554   ,805,805,805
BEGIN DESCRIPTION:
WEST CANEY CREEK 55.0
END DESCRIPTION:
XS GIS Cut Line= 3
      3611186.48     10351124.66      3610267.32      10351593.6
      3609509.21     10352183.09
#Sta/Elev= 30
  4140.2  351.34  4268.6  351.52  4481.9  331.03  4608.8  322.12  4880.6  316.51
  4908.5  317.11  4930.9  314.79  4953.3  317.22  4964.6  316.51  4975.5  315.28
  4987.1  308.91  4994.7  308.16  4997.5  307.66  5000.7  308.16  5019.9  311.63
  5025.6  314.44  5042.2  316.42  5064.4  318.05  5108.9  314.98  5114.5  317.06
  5131.1   315.1  5177.3  318.43  5253.4  321.68  5280.6  325.44  5309.5  323.68
  5487.8  323.79  5531.2  324.58    5552  327.77  5672.7  331.44  6132.4  335.67
#Mann= 5 ,-1 , 0
  4140.2     .05       0  4880.6     .16       0  4994.7     .07       0
  5000.7     .16       0  5177.3     .05       0
Bank Sta=4964.6,5042.2
XS Rating Curve= 0 ,0
Exp/Cntr=0.3,0.1

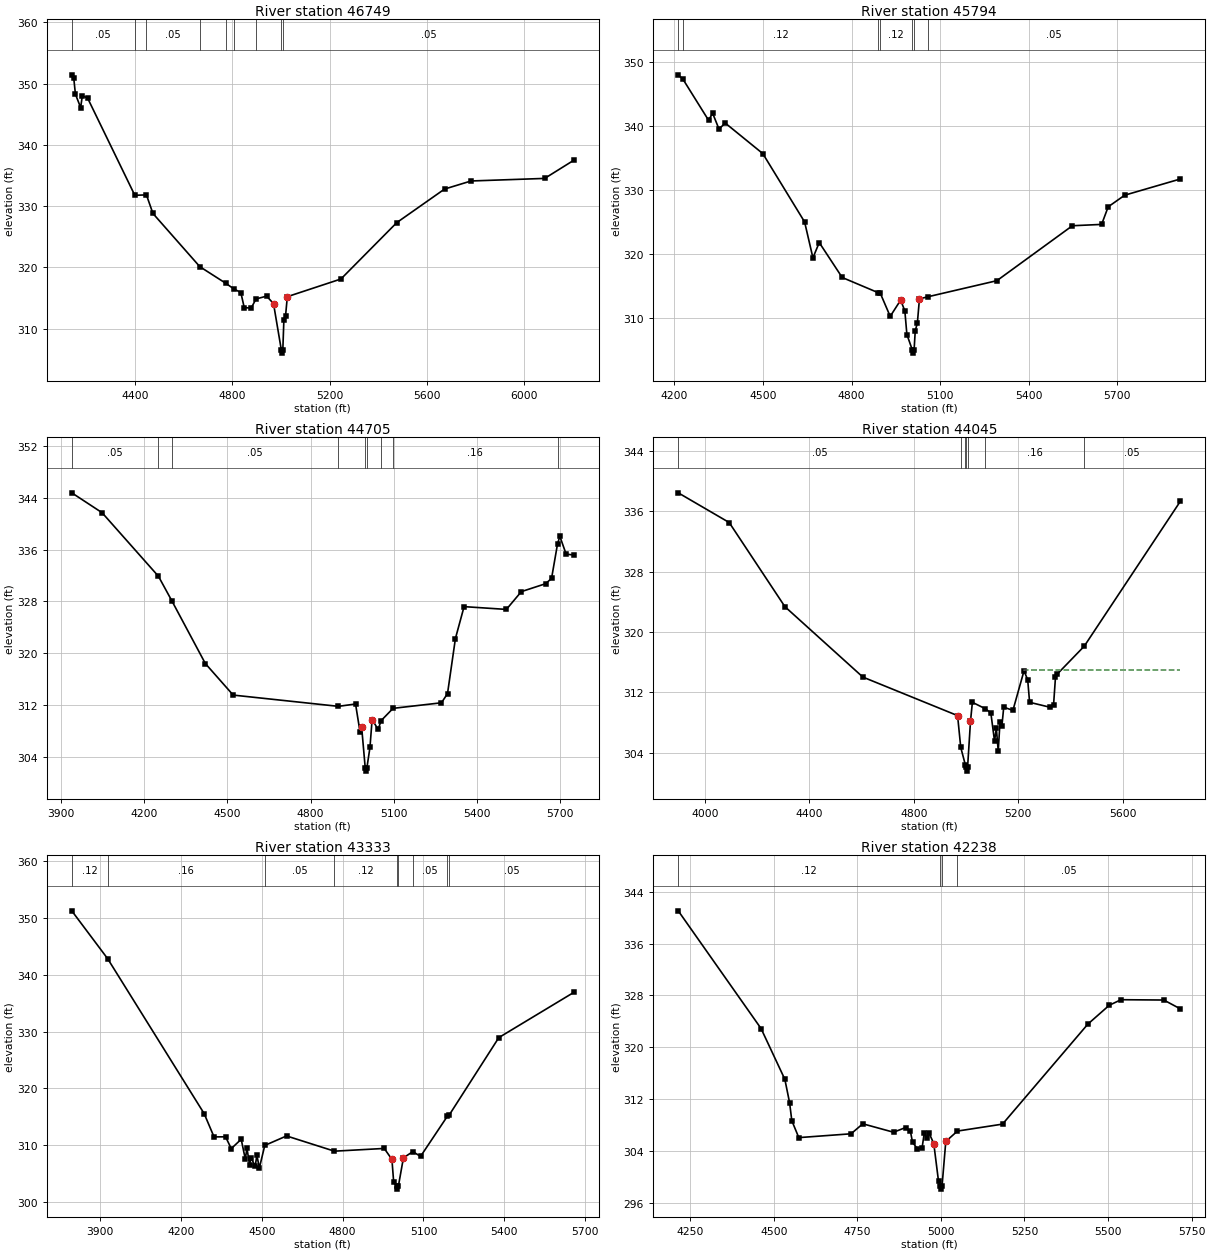
Type RM Length L Ch R = 1 ,46749   ,955,955,955
BEGIN DESCRIPTION:
WEST CANEY CREEK 54.0
END DESCRIPTION:
XS GIS Cut Line= 3
      3610842.54     10350520.57       3610045.5     10351267.27
      3609231.66     10351795.85
#Sta/Elev= 30
  4140.3  351.45  4148.5  350.89  4155.3  348.29  4176.8   346.1  4183.6  348.02
  4205.1  347.67  4399.3  331.77    4447  331.84  4473.8   328.8  4666.4  320.11
  4773.4  317.39  4806.9  316.46  4834.8  315.89  4848.9  313.42  4877.3  313.35
  4897.3  314.84  4940.8   315.3  4969.1  314.08  5001.3  306.49    5004  305.99
  5007.3  306.49  5011.6  311.33  5018.4     312  5025.8  315.21  5246.1   318.1
  5475.5  327.31  5671.8  332.79  5780.6  334.11  6083.1  334.53  6202.9   337.5
#Mann= 9 ,-1 , 0
  4140.3     .05       0  4399.3     .16       0    4447     .05       0
  4666.4     .16       0  4773.4     .05       0  4806.9     .12       0
  4897.3     .05       0  5001.3     .03       0  5007.3     .05       0
Bank Sta=4969.1,5025.8
XS Rating Curve= 0 ,0
Exp/Cntr=0.3,0.1

Type RM Length L Ch R = 1 ,45794   ,1089,1089,1089
BEGIN DESCRIPTION:
WEST CANEY CREEK 52.0
END DESCRIPTION:
XS GIS Cut Line= 3
      3610414.65     10350059.15      3609724.65      10350768.5
      3609174.67     10351218.49
#Sta/Elev= 30
  4212.8  348.02  4228.8  347.33  4315.3  340.93  4329.4     342  4350.8  339.54
  4371.9  340.48  4499.2   335.7  4640.7  325.02  4668.9   319.4  4690.3  321.79
    4768  316.33    4890  313.95  4897.1  313.86  4930.6  310.25    4966  312.79
  4980.2  311.09  4987.1  307.41  5005.5     305  5008.2   304.5  5011.5     305
  5015.4     308  5022.6  309.22  5029.6  312.98  5057.9  313.31  5291.9  315.83
  5547.5  324.42  5646.5  324.63  5668.8  327.38  5724.8   329.2    5913  331.73
#Mann= 7 ,-1 , 0
  4212.8     .16       0  4228.8     .12       0    4890     .05       0
  4897.1     .12       0  5005.5     .07       0  5011.5     .12       0
  5057.9     .05       0
Bank Sta=4966,5029.6
XS Rating Curve= 0 ,0
Exp/Cntr=0.3,0.1

Type RM Length L Ch R = 1 ,44705   ,660,660,660
BEGIN DESCRIPTION:
WEST CANEY CREEK 50.0
END DESCRIPTION:
XS GIS Cut Line= 3
      3610037.07     10349723.59       3609350.5     10350223.85
      3608887.75     10351065.87
#Sta/Elev= 30
  3938.8  344.78    4048  341.71  4251.2  331.88  4299.1  328.12  4420.4  318.38
  4520.8   313.5  4900.1  311.76    4962  312.12  4978.1  307.82  4983.8  308.63
  4996.9  302.24  4999.7  301.74  5002.9  302.24    5014  305.42  5021.7  309.72
  5043.5  308.18    5054  309.54  5097.3  311.45  5271.8  312.31  5293.6  313.73
  5322.1  322.25  5353.3  327.18  5505.8  326.75  5559.8   329.5  5646.9  330.72
  5668.7  331.54  5690.4  336.91  5698.6  338.05  5721.4  335.29  5749.1  335.17
#Mann= 9 ,-1 , 0
  3938.8     .05       0  4251.2     .16       0  4299.1     .05       0
  4900.1     .16       0  4996.9     .07       0  5002.9     .16       0
    5054     .12       0  5097.3     .16       0  5690.4     .05       0
Bank Sta=4983.8,5021.7
XS Rating Curve= 0 ,0
Exp/Cntr=0.3,0.1

Type RM Length L Ch R = 1 ,44045   ,712,712,712
BEGIN DESCRIPTION:
WEST CANEY CREEK 48.0
END DESCRIPTION:
XS GIS Cut Line= 3
      3609869.34     10349245.33      3609147.81     10349807.46
      3608417.87     10350503.84
#Sta/Elev= 30
  3897.3  338.42  4092.5  334.49    4306  323.35  4604.6  314.03  4967.5  308.93
  4979.6  304.72  4997.1  302.43  4999.8  302.08  5002.5  301.58  5005.8  302.08
  5016.9  308.15  5024.2  310.69  5073.2  309.85  5094.9  309.29  5109.1  305.55
    5116  307.28  5123.2  304.23  5130.1  308.13  5137.4   307.6  5144.3  310.05
  5179.5  309.62    5222  314.86  5236.1  313.67  5243.4  310.69  5321.1  310.04
  5335.2  310.34  5342.5  313.99  5349.4  314.43  5452.8  318.12  5820.8  337.29
#Mann= 7 ,-1 , 0
  3897.3     .05       0  4979.6     .16       0  4997.1     .12       0
  4999.8     .07       0  5005.8     .12       0  5073.2     .16       0
  5452.8     .05       0
#XS Ineff= 2 , 0
                         5223.01          314.92
Permanent Ineff=
       F       F
Bank Sta=4967.5,5016.9
XS Rating Curve= 0 ,0
Exp/Cntr=0.3,0.1

Type RM Length L Ch R = 1 ,43333   ,1095,1095,1095
BEGIN DESCRIPTION:
WEST CANEY CREEK 47.0
END DESCRIPTION:
XS GIS Cut Line= 3
      3609382.71     10348716.81      3608938.06     10349446.71
      3608175.88     10350108.38
#Sta/Elev= 30
  3794.4  351.26  3927.4  342.85  4285.9  315.57  4322.6  311.47  4365.3  311.49
  4386.6  309.41  4423.4  311.06  4438.8  307.53  4444.7  309.52  4454.3  306.58
  4460.2  307.78  4475.6  306.31  4481.5  308.27  4490.9  306.01  4510.9  309.97
  4591.8  311.64  4769.5  308.96  4954.5  309.44    4983  307.51  4989.6  303.46
  5000.9  302.78  5003.6  302.28  5006.9  302.78  5025.7  307.79  5060.7  308.88
  5089.3  308.04  5189.2  315.13  5196.1  315.35  5379.9  328.95  5658.4  336.91
#Mann= 9 ,-1 , 0
  3794.4     .12       0  3927.4     .16       0  4510.9     .05       0
  4769.5     .12       0  5000.9     .07       0  5006.9     .12       0
  5060.7     .05       0  5189.2     .16       0  5196.1     .05       0
Bank Sta=4983,5025.7
XS Rating Curve= 0 ,0
Exp/Cntr=0.3,0.1

Type RM Length L Ch R = 1 ,42238   ,871,871,871
BEGIN DESCRIPTION:
WEST CANEY CREEK 45.0
END DESCRIPTION:
XS GIS Cut Line= 3
      3608992.12     10348441.62      3608207.53     10349327.23
      3607957.86     10349526.97
#Sta/Elev= 30
  4213.6  341.04  4461.6  322.89  4532.7  315.07  4546.9  311.47  4553.6  308.69
  4574.5  306.08  4730.9  306.67  4766.1  308.21  4858.1  306.91    4894  307.63
  4908.3  307.12  4914.9  305.38  4929.2  304.37  4943.4  304.46  4950.1  306.79
  4957.6  305.99  4964.3  306.79  4978.5  305.17  4992.7  299.36  4997.3  298.64
    5000  298.14  5003.3  298.64  5014.5  305.49  5049.4  307.09  5184.3  308.16
  5439.8  323.58  5503.8  326.48    5539  327.34  5667.1  327.29  5716.5  325.93
#Mann= 4 ,-1 , 0
  4213.6     .12       0  4997.3     .07       0  5003.3     .12       0
  5049.4     .05       0
Bank Sta=4978.5,5014.5
XS Rating Curve= 0 ,0
Exp/Cntr=0.3,0.1

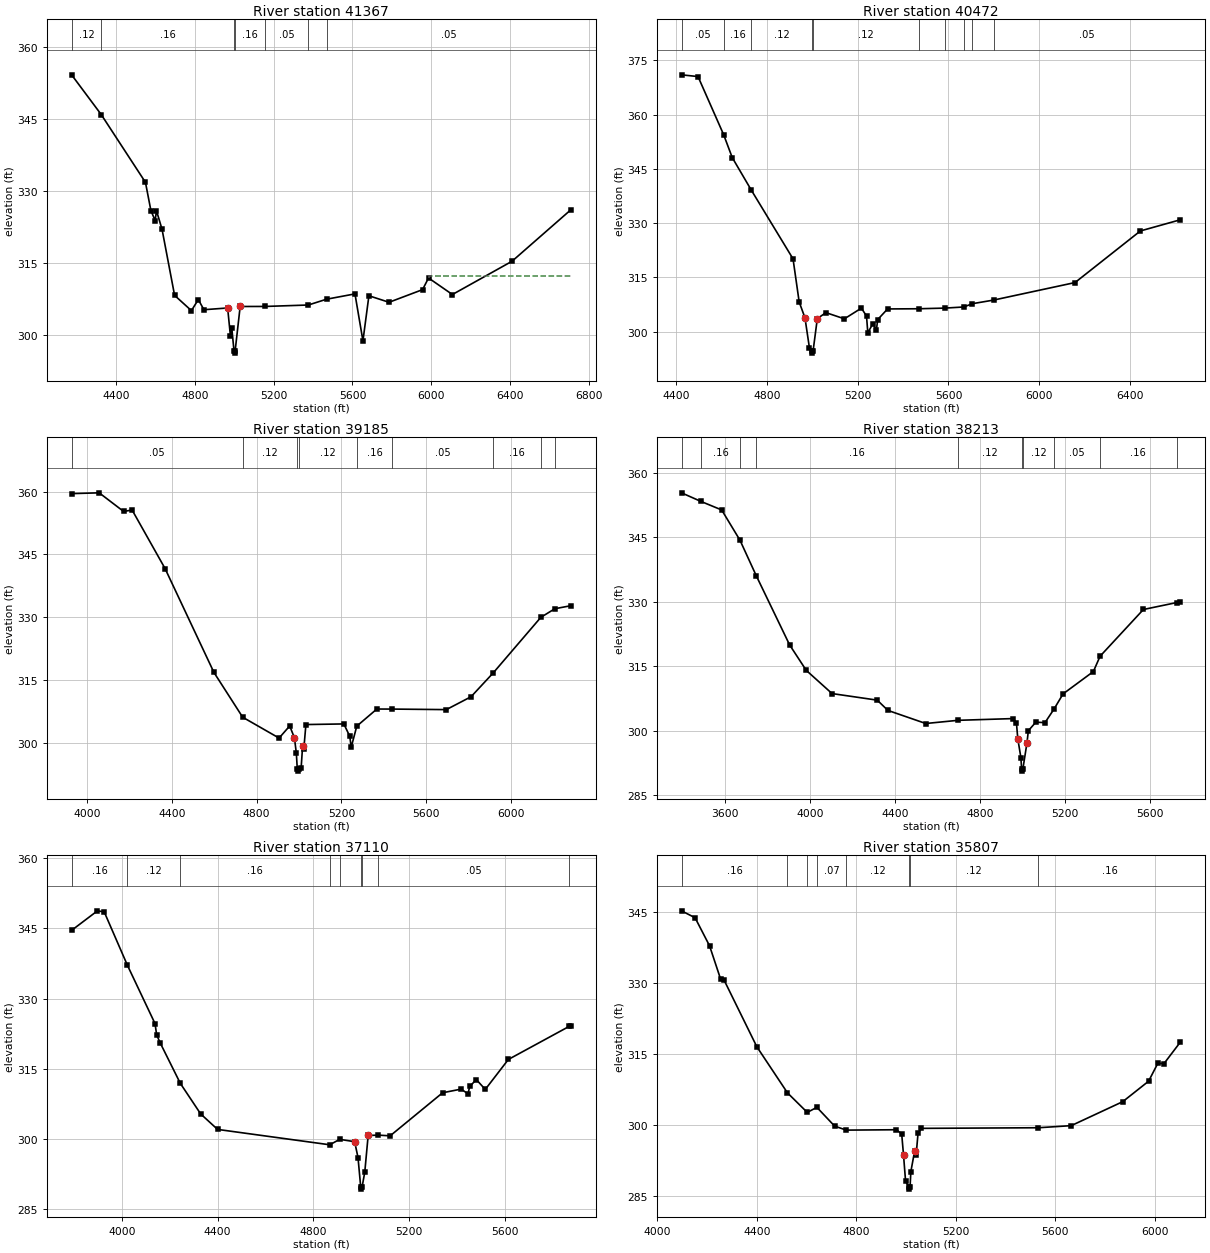
Type RM Length L Ch R = 1 ,41367   ,895,895,895
BEGIN DESCRIPTION:
WEST CANEY CREEK 44.0
END DESCRIPTION:
XS GIS Cut Line= 3
      3608896.11      10347986.9      3608057.83     10348715.84
      3606647.65     10348918.16
#Sta/Elev= 30
  4172.8  354.21  4323.1  345.93    4548  331.78  4575.7  325.89  4597.3   323.8
    4604  325.86  4632.4  321.96  4696.1  308.19  4781.5  305.01  4816.7  307.31
  4845.1   305.2  4965.7  305.56    4980  299.65  4986.6  301.42  4997.9  296.64
  5000.6  296.14  5003.9  296.64  5029.3  305.87  5155.8  305.88  5375.6  306.18
  5468.2  307.39  5612.7   308.5  5653.2   298.7  5683.5  308.11  5785.9  306.75
  5956.2  309.39  5986.5  311.82  6107.8  308.37  6410.8  315.31  6708.3     326
#Mann= 7 ,-1 , 0
  4172.8     .12       0  4323.1     .16       0  4997.9     .07       0
  5003.9     .16       0  5155.8     .05       0  5375.6     .16       0
  5468.2     .05       0
#XS Ineff= 2 , 0
                          5987.5          312.17
Permanent Ineff=
       F       F
Bank Sta=4965.7,5029.3
XS Rating Curve= 0 ,0
Exp/Cntr=0.3,0.1

Type RM Length L Ch R = 1 ,40472   ,1287,1287,1287
BEGIN DESCRIPTION:
WEST CANEY CREEK 43.0
END DESCRIPTION:
XS GIS Cut Line= 3
       3608392.7     10347642.94      3607942.11     10347941.64
      3606492.06     10348741.66
#Sta/Elev= 30
  4424.8     371  4497.5  370.52  4610.1  354.49  4648.1  348.14  4731.5   339.2
  4915.8  320.15  4942.8  308.25  4968.3  303.86  4988.2  295.46  4997.9   294.6
  5000.7   294.1  5003.9   294.6  5022.7  303.64  5060.5  305.29  5141.9  303.58
  5216.7  306.53  5239.3  304.35    5245  299.71  5266.8  302.17  5282.9  300.58
  5288.6  303.38  5332.1  306.31  5468.2  306.36  5583.5  306.54  5667.5  306.85
  5705.3  307.76    5799  308.76  6157.3   313.6    6445  327.86  6621.5  330.96
#Mann= 10 ,-1 , 0
  4424.8     .05       0  4610.1     .16       0  4731.5     .12       0
  4997.9     .07       0  5003.9     .12       0  5468.2     .05       0
  5583.5     .16       0  5667.5     .05       0  5705.3     .16       0
    5799     .05       0
Bank Sta=4968.3,5022.7
XS Rating Curve= 0 ,0
Exp/Cntr=0.3,0.1

Type RM Length L Ch R = 1 ,39185   ,972,972,972
BEGIN DESCRIPTION:
WEST CANEY CREEK 41.0
END DESCRIPTION:
XS GIS Cut Line= 3
      3608343.83      10347223.5       3607593.8     10347423.51
       3606192.1     10348141.65
#Sta/Elev= 30
  3928.4  359.51  4058.3   359.7  4173.4  355.25  4213.5  355.59  4368.8   341.6
    4599  316.78  4734.6  306.07    4906  301.09  4956.1  303.99  4978.3  301.15
  4987.4  297.46  4991.8  293.69  4994.6  293.19  4997.8  293.69  5009.9  293.91
    5017  299.24  5022.7  298.54  5032.4  304.32  5211.2  304.47  5239.1  301.52
  5245.9   298.9  5272.2  303.94  5366.7  308.03  5438.4  308.02  5694.1  307.89
  5810.7  310.97  5915.6  316.69  6139.4  329.94  6205.4     332  6279.6  332.71
#Mann= 9 ,-1 , 0
  3928.4     .05       0  4734.6     .12       0  4991.8     .07       0
  4997.8     .12       0  5272.2     .16       0  5438.4     .05       0
  5915.6     .16       0  6139.4     .12       0  6205.4     .16       0
Bank Sta=4978.3,5017
XS Rating Curve= 0 ,0
Exp/Cntr=0.3,0.1

Type RM Length L Ch R = 1 ,38213   ,1103,1103,1103
BEGIN DESCRIPTION:
WEST CANEY CREEK 39.0
END DESCRIPTION:
XS GIS Cut Line= 3
      3607906.13      10346359.3      3606471.45     10347524.26
      3606071.44     10347824.27
#Sta/Elev= 30
  3394.6  355.35  3485.5  353.36  3583.7  351.36  3669.9   344.3  3746.5  336.03
  3903.3  319.94  3981.6  314.01    4103   308.6  4315.7  307.07  4365.9  304.68
  4544.1  301.63  4695.4  302.37  4956.5  302.78  4970.8  301.74  4977.3  298.02
  4991.7  293.71  4995.1  291.04  4997.8  290.54  5001.1  291.04  5020.4  297.14
  5026.8  299.95    5062  301.94  5105.1  301.83  5148.1  305.03  5190.3  308.53
  5332.8  313.73  5364.4   317.3  5568.2  328.18  5724.7  329.79  5742.7  329.91
#Mann= 10 ,-1 , 0
  3394.6     .05       0  3485.5     .16       0  3669.9     .12       0
  3746.5     .16       0  4695.4     .12       0  4995.1     .07       0
  5001.1     .12       0  5148.1     .05       0  5364.4     .16       0
  5724.7     .12       0
Bank Sta=4977.3,5020.4
XS Rating Curve= 0 ,0
Exp/Cntr=0.3,0.1

Type RM Length L Ch R = 1 ,37110   ,1303,1303,1303
BEGIN DESCRIPTION:
WEST CANEY CREEK 38.0
END DESCRIPTION:
XS GIS Cut Line= 3
      3607243.34     10345990.16      3606040.08      10347165.8
      3605840.06     10347515.83
#Sta/Elev= 30
  3789.5  344.56  3897.5  348.73  3925.8   348.5  4022.9  337.08    4138  324.66
    4145  322.24  4159.1  320.59  4243.9  311.88  4328.9  305.36  4399.6  302.05
  4868.3  298.77    4910  299.93  4972.4  299.43  4986.5  296.05  4997.7   289.8
  5000.4   289.3  5003.7   289.8  5014.8  292.95  5028.9  300.76  5071.8  300.83
  5120.8  300.68  5340.1  309.88  5417.9  310.66  5446.1  309.64  5453.3  311.23
    5481  312.69  5518.4  310.59  5614.9  316.99  5868.2  324.03  5874.9  324.11
#Mann= 9 ,-1 , 0
  3789.5     .16       0  4022.9     .12       0  4243.9     .16       0
  4868.3     .12       0    4910     .16       0  4997.7     .07       0
  5003.7     .16       0  5071.8     .05       0  5868.2     .16       0
Bank Sta=4972.4,5028.9
XS Rating Curve= 0 ,0
Exp/Cntr=0.3,0.1

Type RM Length L Ch R = 1 ,35807   ,774,774,774
BEGIN DESCRIPTION:
WEST CANEY CREEK 37.0
END DESCRIPTION:
XS GIS Cut Line= 3
      3606966.52     10345730.05      3605951.33     10346342.52
      3605665.29     10347111.83
#Sta/Elev= 30
  4096.8  345.16  4151.4   343.7  4209.6  337.79  4253.8  330.81  4267.9  330.58
  4399.9  316.51    4523  306.81  4602.5   302.7  4641.1  303.77  4712.4  299.82
  4759.3  298.97  4960.8  299.05  4982.2  298.17  4989.6   293.7  4997.7  288.28
  5009.9  287.04  5012.7  286.54  5015.9  287.04  5019.1  290.25  5034.6  294.67
  5040.4  293.82  5047.9   298.3  5061.8  299.34  5531.7  299.47  5663.9  299.91
    5871  304.96    5975  309.27  6012.1  313.04  6037.1  312.99  6103.2  317.54
#Mann= 8 ,-1 , 0
  4096.8     .16       0    4523     .07       0  4602.5      .1       0
  4641.1     .07       0  4759.3     .12       0  5009.9     .07       0
  5015.9     .12       0  5531.7     .16       0
Bank Sta=4989.6,5034.6
XS Rating Curve= 0 ,0
Exp/Cntr=0.3,0.1