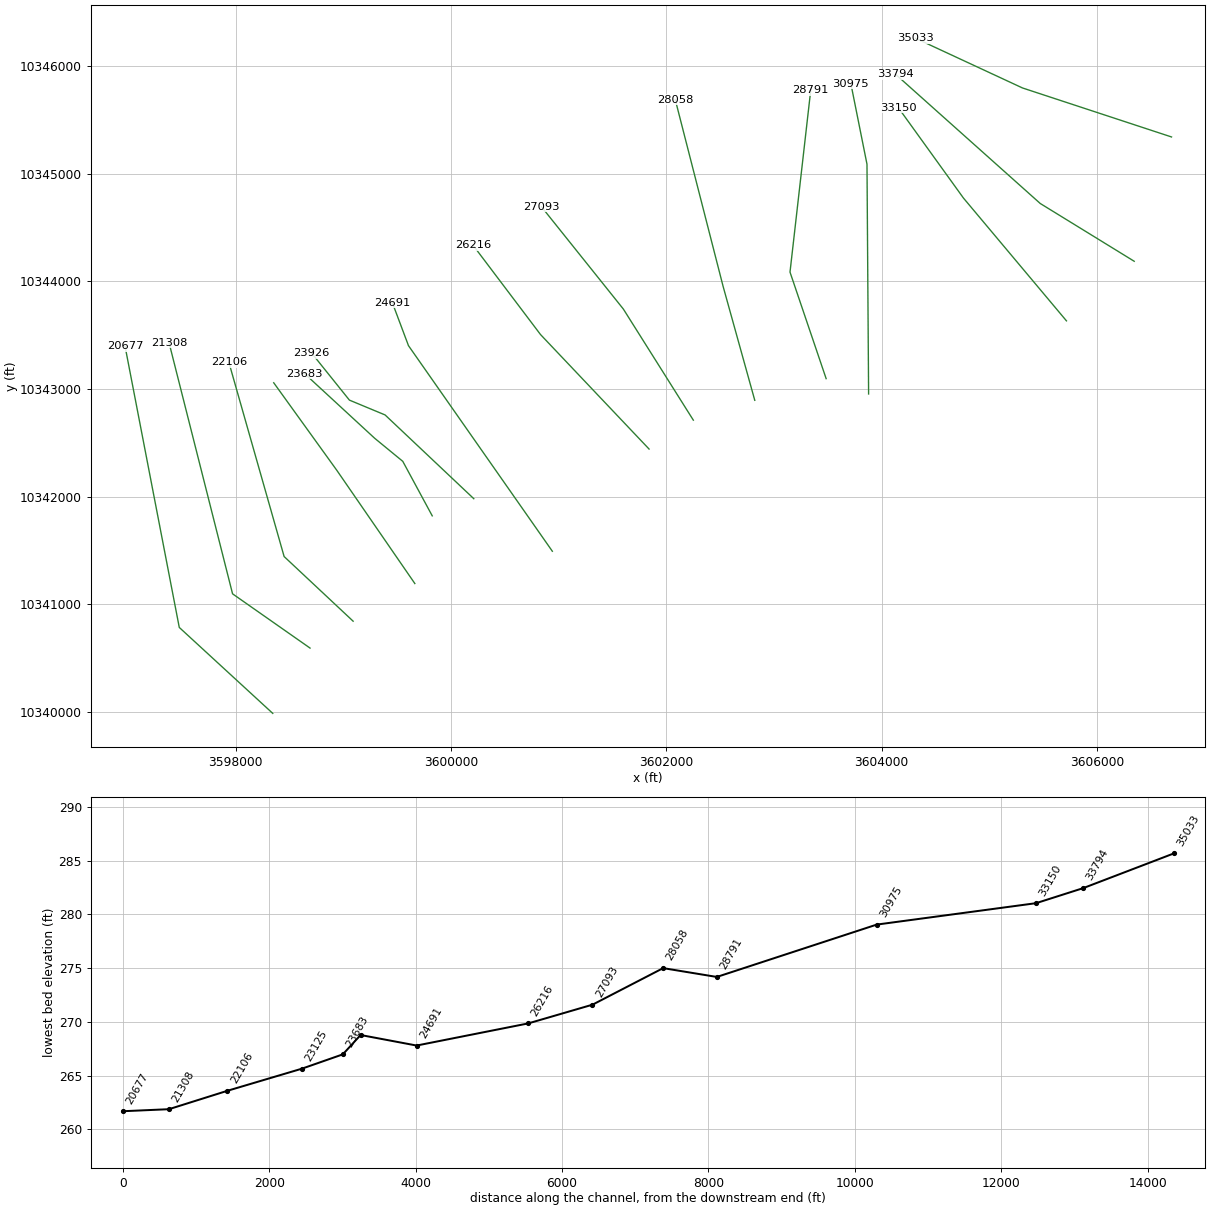
HEC-RAS study WEST CANEY CREEK.prj: WEST CANEY CREEK Base Level Engineering

--- WEST CANEY CREEK.g01 (geometry) --- (continued)

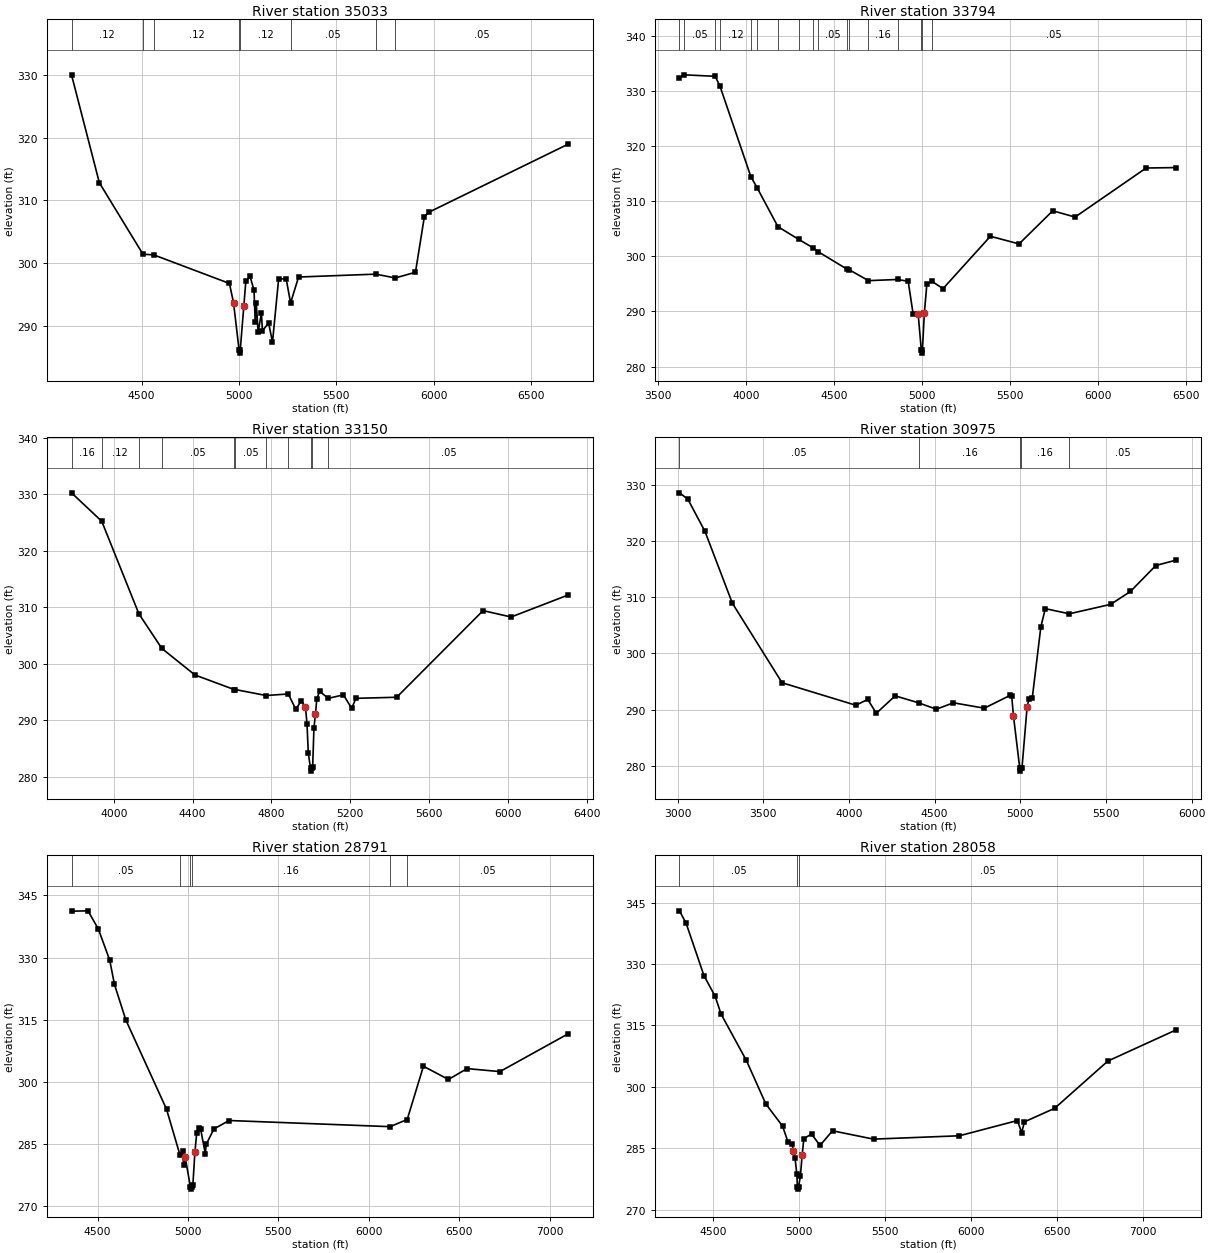
Type RM Length L Ch R = 1 ,35033   ,1239,1239,1239
BEGIN DESCRIPTION:
WEST CANEY CREEK 36.0
END DESCRIPTION:
XS GIS Cut Line= 3
      3606692.08     10345341.65      3605308.18       10345797.
      3604316.25      10346258.2
#Sta/Elev= 30
  4140.5  330.02  4283.5  312.81  4507.2  301.43  4562.8  301.32  4951.1  296.77
  4972.1  293.72  5000.7  286.16  5003.5  285.66  5006.7  286.16  5025.2  293.21
  5035.3   297.1    5057  297.89  5077.4  295.68  5083.5   290.6  5088.8  293.68
  5098.5     289  5115.3  292.04  5120.6  289.22  5152.3  290.46  5172.2  287.41
  5203.7  297.48  5242.4   297.5  5265.1  293.66    5306  297.79  5702.5  298.25
  5802.2  297.64  5906.1  298.55  5951.9  307.43  5974.8  308.12  6691.3  318.99
#Mann= 8 ,-1 , 0
  4140.5     .12       0  4507.2     .05       0  4562.8     .12       0
  5000.7     .07       0  5006.7     .12       0  5265.1     .05       0
  5702.5     .16       0  5802.2     .05       0
Bank Sta=4972.1,5025.2
XS Rating Curve= 0 ,0
Exp/Cntr=0.3,0.1

Type RM Length L Ch R = 1 ,33794   ,644,644,644
BEGIN DESCRIPTION:
WEST CANEY CREEK 35.0
END DESCRIPTION:
XS GIS Cut Line= 3
      3606345.67     10344186.35      3605473.12      10344723.3
      3604130.75     10345923.04
#Sta/Elev= 30
    3622  332.45  3648.5  332.99  3825.1  332.72  3852.1  330.94  4028.3  314.45
  4062.8  312.51  4181.7   305.4  4300.6  303.08  4380.6  301.57  4411.3  300.84
  4575.1  297.67  4585.5   297.6  4696.6   295.6  4861.7  295.81  4922.2  295.48
  4950.7  289.47  4979.1  289.46    4997  282.93  4999.7  282.43    5003  282.93
  5014.2  289.73  5028.4  294.96  5056.5  295.48  5120.4  294.15  5389.6  303.66
  5552.6  302.27    5744  308.29  5871.1  307.15  6274.8  316.06  6446.9  316.14
#Mann= 17 ,-1 , 0
    3622     .16       0  3648.5     .05       0  3825.1     .16       0
  3852.1     .12       0  4028.3     .16       0  4062.8     .05       0
  4181.7     .16       0  4300.6     .05       0  4380.6     .16       0
  4411.3     .05       0  4575.1     .16       0  4585.5     .05       0
  4696.6     .16       0  4861.7     .12       0    4997     .07       0
    5003     .12       0  5056.5     .05       0
Bank Sta=4979.1,5014.2
XS Rating Curve= 0 ,0
Exp/Cntr=0.3,0.1

Type RM Length L Ch R = 1 ,33150   ,2175,2175,2175
BEGIN DESCRIPTION:
WEST CANEY CREEK 33.0
END DESCRIPTION:
XS GIS Cut Line= 3
       3605716.4     10343632.66      3604759.99     10344773.64
      3604156.53     10345611.79
#Sta/Elev= 30
  3785.8  330.27  3939.2  325.24  4127.6  308.87  4244.1  302.74  4412.3  298.04
  4611.6  295.46  4616.2  295.47  4772.9  294.41  4885.7  294.68  4923.6  291.99
  4952.3  293.46  4973.1  292.36  4980.9  289.34  4987.4  284.18  4998.7  281.53
  5001.5  281.03  5004.7  281.53  5009.5  281.71    5016  288.65  5023.8  291.13
  5030.3  293.74  5044.6  295.18  5088.4   293.9  5165.6  294.53  5207.3  292.15
  5229.4  293.91    5436   294.1  5874.2  309.43  6016.6   308.3  6307.4  312.21
#Mann= 11 ,-1 , 0
  3785.8     .16       0  3939.2     .12       0  4127.6     .16       0
  4244.1     .05       0  4611.6     .16       0  4616.2     .05       0
  4772.9     .16       0  4885.7     .12       0  4998.7     .07       0
  5004.7     .12       0  5088.4     .05       0
Bank Sta=4973.1,5023.8
XS Rating Curve= 0 ,0
Exp/Cntr=0.3,0.1

Type RM Length L Ch R = 1 ,30975   ,2184,2184,2184
BEGIN DESCRIPTION:
WEST CANEY CREEK 32.0
END DESCRIPTION:
XS GIS Cut Line= 3
      3603879.07     10342953.03      3603864.02     10345088.72
      3603714.23     10345837.65
#Sta/Elev= 30
  3011.5  328.57  3060.1  327.45  3160.1  321.72  3320.1  308.92  3610.1  294.77
  4040.1  290.77  4110.1  291.79  4160.1  289.34  4270.1  292.44  4409.3  291.17
  4510.1  290.06  4610.1   291.2  4790.2  290.24  4940.2  292.51  4950.2  292.37
  4960.2  288.89  4997.2  279.54  4999.9  279.04  5003.2  279.54  5010.2  279.65
  5040.2  290.54  5050.2  291.79  5070.2  292.08  5120.2  304.73  5146.2  307.96
  5286.2  307.04  5527.5  308.72  5643.1  311.02    5791  315.63    5911  316.61
#Mann= 5 ,-1 , 0
  3011.5     .05       0  4409.3     .16       0  4997.2     .07       0
  5003.2     .16       0  5286.2     .05       0
Bank Sta=4960.2,5040.2
XS Rating Curve= 0 ,0
Exp/Cntr=0.3,0.1

Type RM Length L Ch R = 1 ,28791   ,733,733,733
BEGIN DESCRIPTION:
WEST CANEY CREEK 31.0
END DESCRIPTION:
XS GIS Cut Line= 3
      3603484.75     10343095.72      3603149.17     10344085.69
      3603341.92     10345778.56
#Sta/Elev= 30
  4355.5  341.17  4446.6  341.26  4504.1  336.86  4566.9  329.36  4593.1  323.53
  4655.9  314.96  4881.1  293.45  4955.8  282.36    4970  283.36  4975.3  279.99
  4984.7  281.82  5013.4  274.67  5016.2  274.17  5019.4  274.67    5027  275.24
  5038.1  283.07  5048.1  287.67  5058.6  288.89  5069.5  288.72  5095.7  282.72
  5100.9  284.98  5143.1  288.68  5227.6  290.71  6117.5  289.23  6212.6  290.95
  6302.5  303.79  6440.8  300.61  6544.1  303.23  6725.3   302.5  7104.6  311.65
#Mann= 6 ,-1 , 0
  4355.5     .05       0  4955.8     .16       0  5013.4     .07       0
  5019.4     .16       0  6117.5     .16       0  6212.6     .05       0
Bank Sta=4984.7,5038.1
XS Rating Curve= 0 ,0
Exp/Cntr=0.3,0.1

Type RM Length L Ch R = 1 ,28058   ,965,965,965
BEGIN DESCRIPTION:
WEST CANEY CREEK 30.0
END DESCRIPTION:
XS GIS Cut Line= 3
      3602821.98     10342894.31      3602528.33     10343951.45
      3602083.87     10345687.38
#Sta/Elev= 30
  4304.9  343.01  4343.7  339.95  4447.4  327.17  4512.4   322.1  4546.7  317.78
    4694  306.43  4807.2  295.79  4904.1  290.41  4935.2  286.62  4959.7  286.13
  4966.4  284.34  4976.7  282.61  4987.1  278.73    4991  275.49  4993.7  274.99
    4997  275.49  5007.9  278.15  5018.3  283.43  5028.2  287.35  5072.9  288.46
    5122  285.66  5194.7  289.25  5433.2  287.21  5932.5  288.03  6269.4  291.75
  6294.6  288.83  6310.7  291.44  6486.1  294.74  6795.8   306.3    7194  313.94
#Mann= 3 ,-1 , 0
  4304.9     .05       0    4991     .03       0    4997     .05       0
Bank Sta=4966.4,5018.3
XS Rating Curve= 0 ,0
Exp/Cntr=0.3,0.1

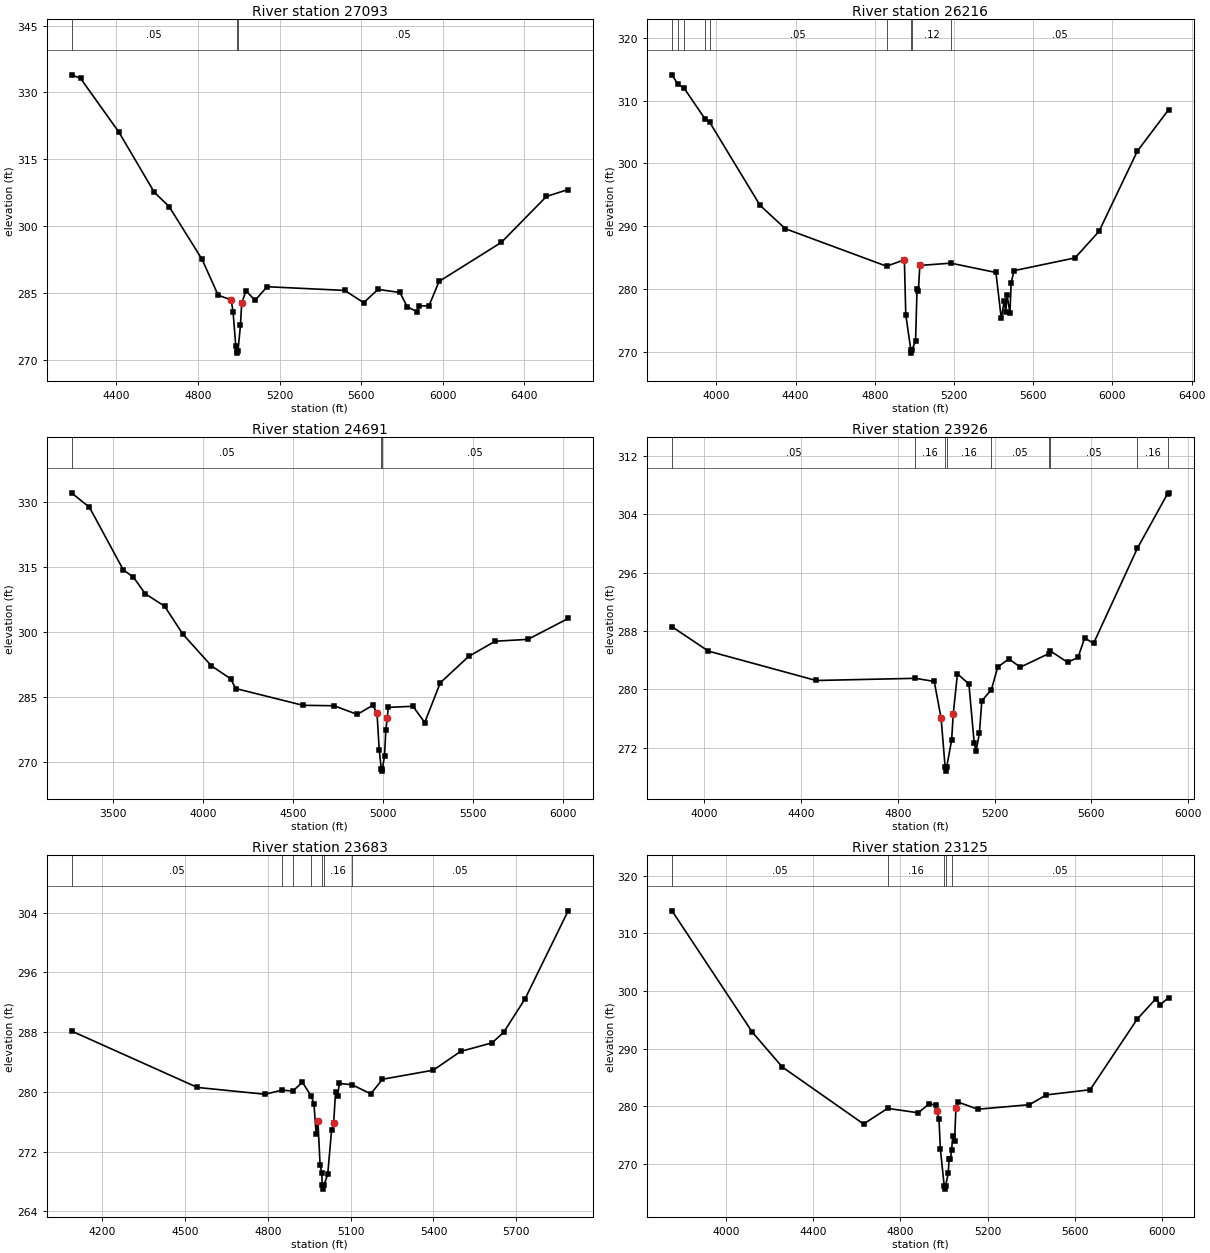
Type RM Length L Ch R = 1 ,27093   ,877,877,877
BEGIN DESCRIPTION:
WEST CANEY CREEK 29.0
END DESCRIPTION:
XS GIS Cut Line= 3
      3602251.47     10342709.78      3601601.75     10343742.09
      3600842.09     10344691.66
#Sta/Elev= 30
  4179.9  333.95  4224.5  333.15  4412.9  321.07    4586  307.63    4659  304.41
  4820.2   292.6  4899.2  284.57  4962.8  283.52  4972.2  280.89  4985.6  273.18
  4990.4  272.09  4993.2  271.59  4996.4  272.09  5008.7  277.94  5014.6  282.83
  5035.8  285.56  5080.1  283.41  5139.2  286.47  5519.9  285.64  5612.8   282.9
  5683.2  285.87  5790.5  285.18  5825.7  282.03  5875.3  280.82  5883.3  282.18
  5932.9  282.18  5982.6  287.66  6288.3  296.41  6509.2   306.7  6615.7  308.25
#Mann= 3 ,-1 , 0
  4179.9     .05       0  4990.4     .03       0  4996.4     .05       0
Bank Sta=4962.8,5014.6
XS Rating Curve= 0 ,0
Exp/Cntr=0.3,0.1

Type RM Length L Ch R = 1 ,26216   ,1525,1525,1525
BEGIN DESCRIPTION:
WEST CANEY CREEK 28.0
END DESCRIPTION:
XS GIS Cut Line= 3
      3601840.35     10342441.33      3600832.72     10343504.95
      3600204.67     10344336.99
#Sta/Elev= 30
  3776.4  314.09  3804.7  312.64  3837.6  311.96  3943.2  307.07  3966.7  306.54
  4220.9  293.34  4348.3  289.63  4859.3  283.67  4949.5  284.68  4956.7  275.94
  4982.1  270.35  4984.8  269.85  4988.1  270.35  5006.1  271.85  5013.4  280.01
  5020.3  279.76  5027.5  283.79  5184.3  284.15  5411.7  282.67  5438.8  275.36
  5453.3  278.07  5461.6  276.43  5467.9  279.07  5482.5  276.23  5488.7  281.04
  5503.3  282.96  5811.3  284.99  5932.1   289.2  6125.6  301.95    6284  308.57
#Mann= 9 ,-1 , 0
  3776.4     .16       0  3804.7     .12       0  3837.6     .16       0
  3943.2     .12       0  3966.7     .05       0  4859.3     .12       0
  4982.1     .07       0  4988.1     .12       0  5184.3     .05       0
Bank Sta=4949.5,5027.5
XS Rating Curve= 0 ,0
Exp/Cntr=0.3,0.1

Type RM Length L Ch R = 1 ,24691   ,765,765,765
BEGIN DESCRIPTION:
WEST CANEY CREEK 26.0
END DESCRIPTION:
XS GIS Cut Line= 3
      3600942.08     10341491.67      3599606.18     10343402.06
      3599456.65      10343800.8
#Sta/Elev= 30
    3269  332.02  3368.8  328.67  3556.3  314.25    3613  312.55  3678.4  308.72
  3785.7  305.86  3886.8  299.42  4044.7  292.12  4151.9  289.11  4181.6  286.84
  4553.9  282.98  4726.6  282.88  4855.3  280.88  4941.1  282.98  4964.7  281.29
  4977.3  272.61  4988.7  268.29  4991.4  267.79  4994.7  268.29  5006.5  271.29
  5013.9  277.34  5021.3  279.95  5027.4   282.5  5164.4  282.76  5229.8  279.01
  5316.1  288.18  5473.9  294.27  5620.8  297.77  5802.6   298.2    6026  303.02
#Mann= 3 ,-1 , 0
    3269     .05       0  4988.7     .03       0  4994.7     .05       0
Bank Sta=4964.7,5021.3
XS Rating Curve= 0 ,0
Exp/Cntr=0.3,0.1

Type RM Length L Ch R = 1 ,23926   ,243,243,243
BEGIN DESCRIPTION:
WEST CANEY CREEK 25.0
END DESCRIPTION:
XS GIS Cut Line= 4
      3600212.76     10341979.88      3599389.01     10342758.21
      3599057.59     10342896.05      3598706.57     10343333.74
#Sta/Elev= 30
  3866.7  288.57  4017.1  285.23  4462.5   281.2  4872.7   281.5  4950.8  281.07
  4979.1  276.03  4995.9  269.27  4998.6  268.77  5001.9  269.27  5022.8  273.06
  5029.1  276.56  5046.7  282.12  5094.1  280.71  5115.8  272.67  5123.7  271.55
  5137.4  273.95  5147.5  278.41    5187  279.94  5213.3  283.05  5259.2  284.15
  5306.9  283.03  5424.4  284.89  5428.6   285.3  5502.1  283.69  5545.3  284.37
  5572.6  287.04  5609.4  286.29  5790.5  299.33  5915.7  306.84    5920  306.94
#Mann= 9 ,-1 , 0
  3866.7     .05       0  4872.7     .16       0  4995.9     .07       0
  5001.9     .16       0    5187     .05       0  5424.4     .16       0
  5428.6     .05       0  5790.5     .16       0  5915.7     .05       0
Bank Sta=4979.1,5029.1
XS Rating Curve= 0 ,0
Exp/Cntr=0.3,0.1

Type RM Length L Ch R = 1 ,23683   ,558,558,558
BEGIN DESCRIPTION:
WEST CANEY CREEK 24.0
END DESCRIPTION:
XS GIS Cut Line= 4
      3599826.85     10341820.47      3599553.27     10342327.11
      3599292.11     10342541.64      3598642.07     10343141.67
#Sta/Elev= 30
  4089.4  288.15  4545.3  280.59  4790.1  279.68    4852  280.23  4890.8  280.11
  4925.5  281.29  4957.3  279.43  4967.3  278.43  4975.2  274.33  4981.6  276.16
  4989.5   270.2    4996  269.12  4996.9  267.47  4999.7  266.97  5002.9  267.47
  5017.1  268.93  5031.2   274.9  5038.6  275.79  5045.4  279.93  5052.8   279.5
  5059.6  281.13  5105.7  280.95    5173  279.73  5215.5  281.69  5399.2   282.9
  5498.5  285.42  5611.9  286.56  5654.4  287.98  5732.1  292.49  5887.8  304.25
#Mann= 7 ,-1 , 0
  4089.4     .05       0    4852     .16       0  4890.8     .05       0
  4957.3     .16       0  4996.9     .07       0  5002.9     .16       0
  5105.7     .05       0
Bank Sta=4981.6,5038.6
XS Rating Curve= 0 ,0
Exp/Cntr=0.3,0.1

Type RM Length L Ch R = 1 ,23125   ,1019,1019,1019
BEGIN DESCRIPTION:
WEST CANEY CREEK 23.0
END DESCRIPTION:
XS GIS Cut Line= 3
      3599665.22     10341191.42      3598942.11     10342241.64
      3598354.84     10343057.21
#Sta/Elev= 30
  3751.5  313.92  4120.3  292.86  4257.6  286.83  4630.9  276.94  4741.4  279.65
  4881.8  278.88  4932.6  280.45  4962.4   280.2  4968.4  279.13  4977.2  277.74
  4983.3  272.61  5001.3  266.14    5004  265.64  5007.3  266.14  5019.2  268.37
  5023.6  270.86  5029.7  270.86  5035.1  272.42  5040.1  274.81  5048.7  274.06
  5054.8  279.68  5063.4  280.76  5155.5   279.5  5392.3  280.29  5470.2  281.99
  5670.9  282.88  5886.9  295.12  5972.8  298.68  5993.7  297.66  6031.6  298.87
#Mann= 5 ,-1 , 0
  3751.5     .05       0  4741.4     .16       0  5001.3     .07       0
  5007.3     .16       0  5035.1     .05       0
Bank Sta=4968.4,5054.8
XS Rating Curve= 0 ,0
Exp/Cntr=0.3,0.1

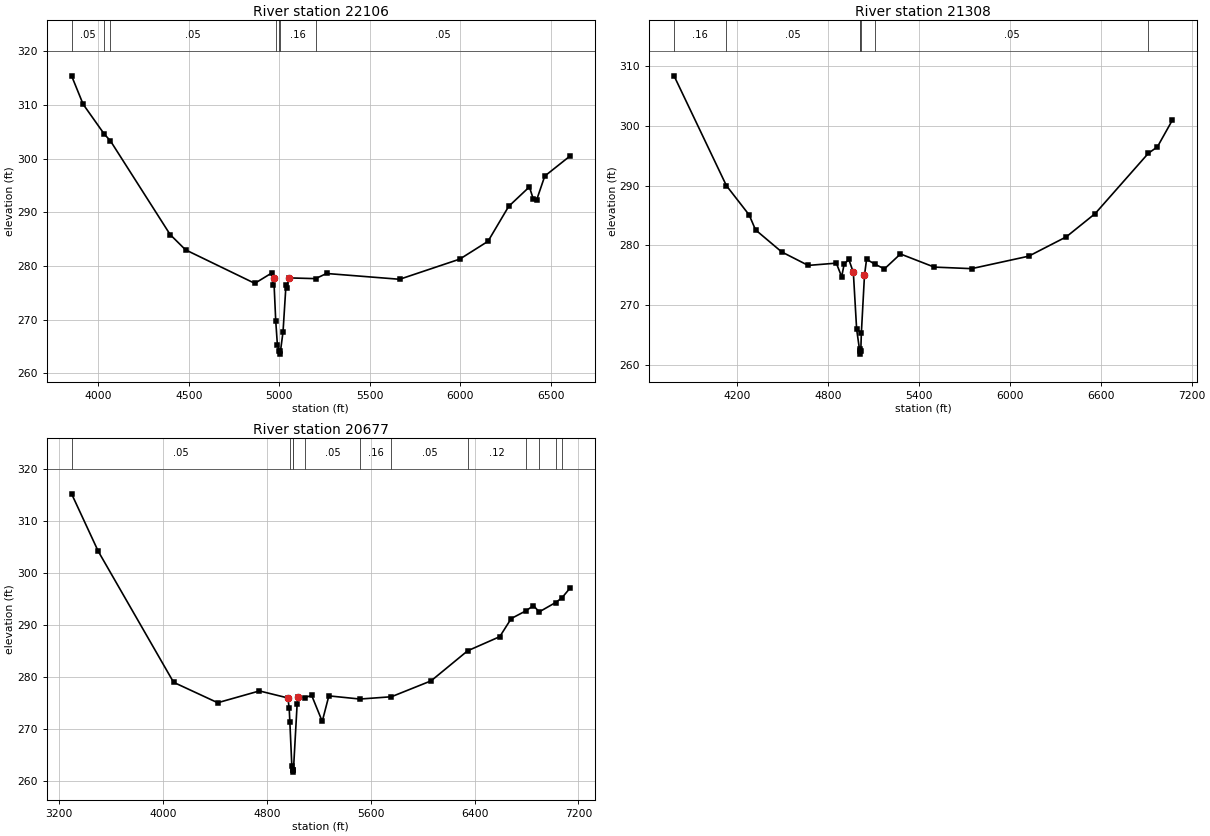
Type RM Length L Ch R = 1 ,22106   ,798,798,798
BEGIN DESCRIPTION:
WEST CANEY CREEK 21.0
END DESCRIPTION:
XS GIS Cut Line= 3
      3599092.11     10340841.64      3598451.36     10341442.34
      3597938.08      10343247.7
#Sta/Elev= 30
  3851.8  315.45  3915.5  310.16  4031.3  304.64  4066.6  303.32  4396.7  285.86
  4481.7  283.02  4864.5  276.77  4958.1   278.7  4964.2  276.46  4969.4  277.81
  4980.3  269.76  4989.3  265.36  5000.2  264.08    5003  263.58  5006.2  264.08
  5020.5  267.69  5037.1  276.54  5042.3   275.9  5051.6  277.79  5200.5  277.65
  5261.2  278.61    5665  277.53  5997.7  281.29  6153.7  284.61    6268  291.12
  6382.4  294.75  6403.2  292.57  6423.2  292.39  6467.5  296.77    6607   300.5
#Mann= 7 ,-1 , 0
  3851.8     .05       0  4031.3     .16       0  4066.6     .05       0
  4980.3     .16       0  5000.2     .07       0  5006.2     .16       0
  5200.5     .05       0
Bank Sta=4969.4,5051.6
XS Rating Curve= 0 ,0
Exp/Cntr=0.3,0.1

Type RM Length L Ch R = 1 ,21308   ,631,631,631
BEGIN DESCRIPTION:
WEST CANEY CREEK 20.0
END DESCRIPTION:
XS GIS Cut Line= 3
      3598692.08     10340591.66      3597972.52     10341095.92
      3597382.24     10343431.01
#Sta/Elev= 30
  3785.9   308.3  4131.2  289.98  4281.4  285.09  4323.3   282.6  4495.9  278.92
  4670.5  276.67  4856.1  277.05  4891.4  274.78  4907.7  276.88  4938.6  277.66
  4968.4   275.5  4990.2     266    5009  262.65  5011.5  262.37  5014.3  261.87
  5017.5  262.37  5021.2  265.36  5041.8  274.99  5055.6   277.7  5109.3  276.89
  5173.5  276.09    5279  278.58  5501.8  276.39  5747.9  276.13  6124.8  278.21
  6372.4  281.43  6563.4  285.32  6914.5  295.39  6973.7  296.45  7073.1  300.94
#Mann= 7 ,-1 , 0
  3785.9     .16       0  4131.2     .05       0    5009     .12       0
  5011.5     .03       0  5017.5     .12       0  5109.3     .05       0
  6914.5     .12       0
Bank Sta=4968.4,5041.8
XS Rating Curve= 0 ,0
Exp/Cntr=0.3,0.1

Type RM Length L Ch R = 1 ,20677   ,1740,1740,1740
BEGIN DESCRIPTION:
WEST CANEY CREEK 19.0
END DESCRIPTION:
XS GIS Cut Line= 3
      3598345.77     10339984.83      3597477.73     10340783.42
      3596974.26     10343396.25
#Sta/Elev= 30
  3294.6  315.22  3500.3  304.15  4080.5  278.96  4420.2  275.03  4741.9   277.3
  4961.1  275.95  4971.3  273.97  4976.3  271.36  4991.7  262.83  4998.3  262.18
  5001.1  261.68  5004.3  262.18  5032.4  274.79  5042.6  276.11  5091.9  276.02
  5144.4  276.44  5225.9  271.44  5276.8  276.35  5516.6  275.74  5758.7  276.18
  6064.5  279.24  6346.1  285.02  6593.6  287.74  6682.2  291.23  6795.2  292.71
    6853  293.71  6897.8  292.51  7024.1  294.31  7072.1  295.19    7135  297.08
#Mann= 12 ,-1 , 0
  3294.6     .05       0  4976.3     .16       0  4998.3     .07       0
  5004.3     .16       0  5091.9     .05       0  5516.6     .16       0
  5758.7     .05       0  6346.1     .12       0  6795.2     .05       0
  6897.8     .16       0  7024.1     .05       0  7072.1     .16       0
Bank Sta=4961.1,5042.6
XS Rating Curve= 0 ,0
Exp/Cntr=0.3,0.1