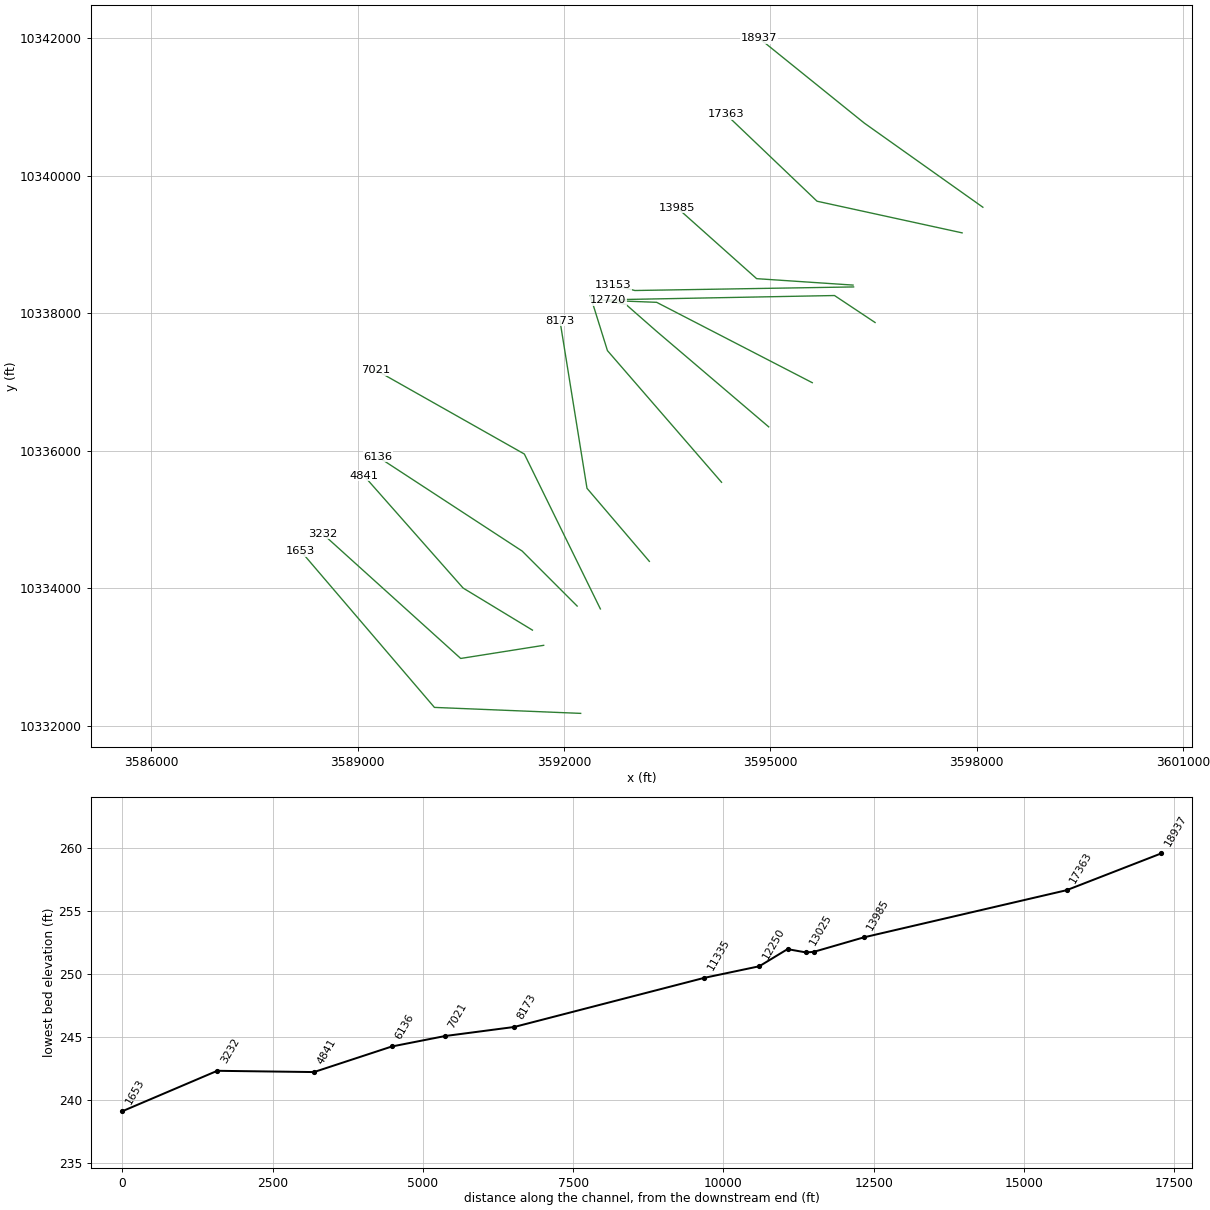
HEC-RAS study WEST CANEY CREEK.prj: WEST CANEY CREEK Base Level Engineering

--- WEST CANEY CREEK.g01 (geometry) --- (continued)

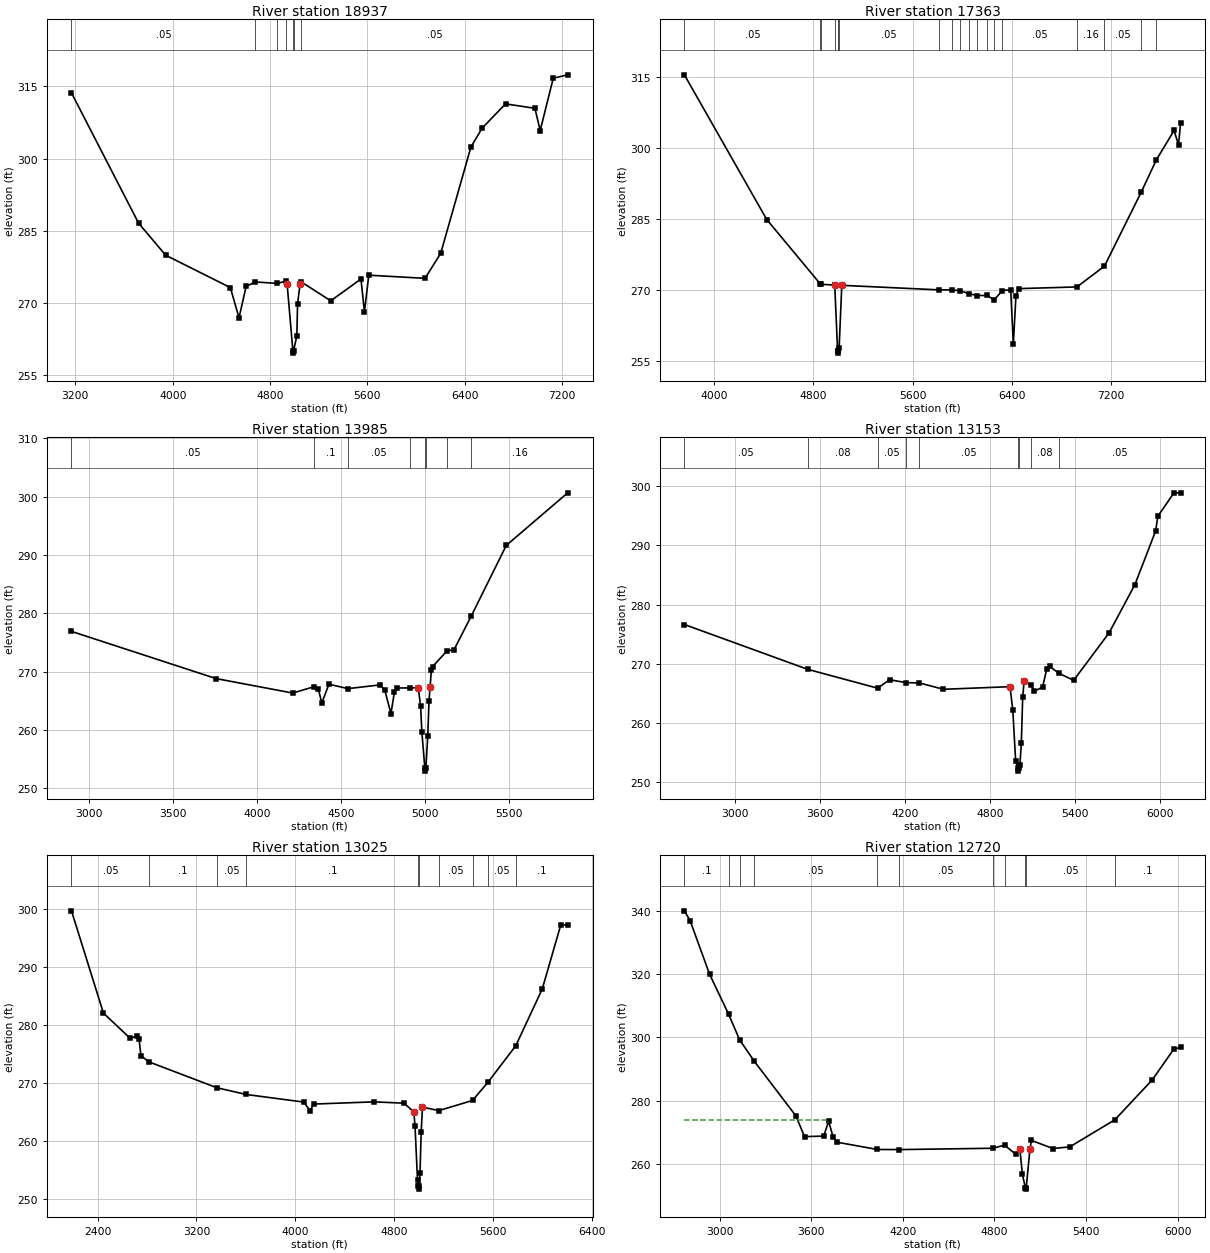
Type RM Length L Ch R = 1 ,18937   ,1574,1574,1574
BEGIN DESCRIPTION:
WEST CANEY CREEK 18.0
END DESCRIPTION:
XS GIS Cut Line= 3
      3598092.14     10339541.61      3596366.62     10340766.06
      3594840.13     10341997.66
#Sta/Elev= 30
  3168.3  313.64  3720.1  286.58  3942.1  279.94  4473.6  273.22    4545  266.94
    4603  273.45    4679  274.39  4859.6  274.08  4929.3  274.56  4939.9  274.04
  4987.3  260.11  4990.1  259.61  4993.3  260.11  5019.8  263.16    5026  269.86
  5046.9  274.02  5054.4  274.43  5298.7  270.47  5546.9     275  5575.4  268.19
  5611.1  275.79  6073.7  275.14  6202.2  280.34  6450.2  302.39  6542.9  306.34
  6734.8  311.36  6976.4  310.44  7019.5  305.82  7126.7  316.69  7245.5  317.39
#Mann= 7 ,-1 , 0
  3168.3     .05       0    4679     .16       0  4859.6     .05       0
  4929.3     .16       0  4987.3     .07       0  4993.3     .16       0
  5054.4     .05       0
Bank Sta=4939.9,5046.9
XS Rating Curve= 0 ,0
Exp/Cntr=0.3,0.1

Type RM Length L Ch R = 1 ,17363   ,3378,3378,3378
BEGIN DESCRIPTION:
WEST CANEY CREEK 17.0
END DESCRIPTION:
XS GIS Cut Line= 3
      3597790.18     10339168.85      3595680.85     10339628.91
      3594352.73     10340896.27
#Sta/Elev= 30
  3763.4  315.38  4426.7  284.86  4857.8  271.27  4862.6  271.21  4972.5  271.04
  4973.7  271.06  4996.9  257.19  4999.6  256.69  5002.9  257.19  5008.9  257.67
  5030.6  270.99    5814  270.03    5916  270.03    5985  269.82  6055.4  269.22
  6121.6  268.83  6197.2  268.86  6258.2  267.95  6323.6  269.89  6390.3  270.05
  6411.4  258.64  6432.5  268.71  6453.9  270.29  6924.1  270.65  7145.3  275.05
  7441.3  290.65  7562.5  297.43  7705.6  303.65  7741.2  300.58  7758.1  305.31
#Mann= 19 ,-1 , 0
  3763.4     .05       0  4857.8     .16       0  4862.6     .05       0
  4972.5     .16       0  4996.9     .07       0  5002.9     .16       0
  5008.9     .05       0    5814     .16       0    5916      .1       0
    5985     .16       0  6055.4      .1       0  6121.6     .05       0
  6197.2     .12       0  6258.2     .16       0  6323.6     .05       0
  6924.1     .16       0  7145.3     .05       0  7441.3      .1       0
  7562.5     .05       0
Bank Sta=4973.7,5030.6
XS Rating Curve= 0 ,0
Exp/Cntr=0.3,0.1

Type RM Length L Ch R = 1 ,13985   ,832,832,832
BEGIN DESCRIPTION:
WEST CANEY CREEK 16.01
END DESCRIPTION:
XS GIS Cut Line= 3
      3596204.14      10338409.4      3594802.26     10338502.72
      3593647.78     10339532.63
#Sta/Elev= 30
  2896.3  276.89  3756.7   268.8    4213  266.32  4341.7  267.43  4364.5  267.05
  4385.4  264.62  4428.1  267.84  4540.5  267.08  4732.4  267.72  4760.8  266.76
  4796.8   262.8  4817.7  266.51  4831.9  267.19  4911.3   267.2    4959  267.24
  4973.2  264.17  4980.7  259.68  4998.6  253.44  5001.4  252.94  5004.6  253.44
  5015.8   258.9  5023.3  264.91    5030  267.43  5037.5  270.31  5044.2  270.84
  5129.3  273.52  5172.1  273.75    5275  279.54  5483.2  291.63  5848.4  300.64
#Mann= 8 ,-1 , 0
  2896.3     .05       0  4341.7      .1       0  4540.5     .05       0
  4911.3     .12       0  4998.6     .07       0  5004.6     .12       0
  5129.3     .05       0    5275     .16       0
Bank Sta=4959,5030
XS Rating Curve= 0 ,0
Exp/Cntr=0.3,0.1

Type RM Length L Ch R = 1 ,13153   ,128,128,128
BEGIN DESCRIPTION:
WEST CANEY CREEK 16.0
END DESCRIPTION:
XS GIS Cut Line= 3
      3596212.48     10338382.49       3593031.9     10338330.41
      3592716.52     10338410.12
#Sta/Elev= 30
  2639.7  276.62  3510.9  269.03  4004.6  265.84  4090.3  267.27  4204.4  266.78
  4300.8  266.72  4470.3  265.65  4940.4  266.09  4960.4  262.13  4980.4   253.5
  4997.4  252.29  5000.1  251.79  5003.4  252.29  5010.4  252.86  5020.4  256.47
  5030.4  264.42  5040.4  267.04  5090.7  266.33  5110.4  265.31  5170.4  266.01
  5200.4   269.1  5220.4  269.52  5288.1  268.33  5390.4  267.17  5640.5   275.2
  5823.2  283.38  5969.3  292.45  5985.5  294.97    6099  298.91    6146  298.92
#Mann= 9 ,-1 , 0
  2639.7     .05       0  3510.9     .08       0  4004.6     .05       0
  4204.4      .1       0  4300.8     .05       0  4997.4     .04       0
  5003.4     .05       0  5090.7     .08       0  5288.1     .05       0
Bank Sta=4940.4,5040.4
XS Rating Curve= 0 ,0
Exp/Cntr=0.3,0.1

Type RM Length L Ch R = 1 ,13025   ,305,305,305
BEGIN DESCRIPTION:
WEST CANEY CREEK 13.0
END DESCRIPTION:
XS GIS Cut Line= 3
      3596524.95     10337865.14      3595934.68     10338257.49
      3592626.34     10338195.01
#Sta/Elev= 30
  2188.4  299.71    2447  282.09  2663.5  277.74  2720.6  278.16  2735.6  277.68
  2750.6  274.73  2817.8  273.66  3365.6  269.22  3603.5  268.06    4070  266.75
    4120  265.25    4150  266.41  4640.1  266.79  4880.1  266.56  4960.1  265.08
  4970.1  262.58  4990.1  253.32  4997.1  252.25  4999.9  251.75  5003.1  252.25
  5010.1  254.46  5020.1  261.68  5030.1  265.89  5162.7  265.28  5435.5  267.03
  5559.1  270.13  5785.7  276.46  6000.3  286.25  6150.3   297.3  6206.1  297.26
#Mann= 10 ,-1 , 0
  2188.4     .05       0  2817.8      .1       0  3365.6     .05       0
  3603.5      .1       0  4997.1     .07       0  5003.1      .1       0
  5162.7     .05       0  5435.5     .08       0  5559.1     .05       0
  5785.7      .1       0
Bank Sta=4960.1,5030.1
XS Rating Curve= 0 ,0
Exp/Cntr=0.3,0.1

Type RM Length L Ch R = 1 ,12720   ,470,470,470
BEGIN DESCRIPTION:
WEST CANEY CREEK 14.0
END DESCRIPTION:
XS GIS Cut Line= 3
      3595611.41     10336990.02      3593348.26     10338158.64
      3592646.55     10338185.86
#Sta/Elev= 30
    2770  339.98  2807.4  336.87  2934.7  319.98  3060.2  307.23  3131.5  299.21
  3228.4  292.38  3499.4  275.21    3557   268.6  3682.2  268.78  3714.6  273.42
  3743.1  268.62  3770.9  266.83  4033.7  264.54  4178.4  264.51  4788.2  264.93
  4866.6  265.89  4938.9  263.08  4966.7   264.7  4983.2  256.73  5002.4  252.51
  5005.1  252.01  5008.4  252.51  5033.2  264.85  5042.6  267.42  5182.6  264.85
  5293.4  265.36  5588.3  273.91  5833.6  286.54  5973.7  296.19  6019.3  296.85
#Mann= 11 ,-1 , 0
    2770      .1       0  3060.2     .05       0  3131.5      .1       0
  3228.4     .05       0  4033.7      .1       0  4178.4     .05       0
  4788.2      .1       0  4866.6     .05       0  5002.4     .03       0
  5008.4     .05       0  5588.3      .1       0
#XS Ineff= 2 , 0
         3711.36  273.79
Permanent Ineff=
       F       F
Bank Sta=4966.7,5033.2
XS Rating Curve= 0 ,0
Exp/Cntr=0.3,0.1

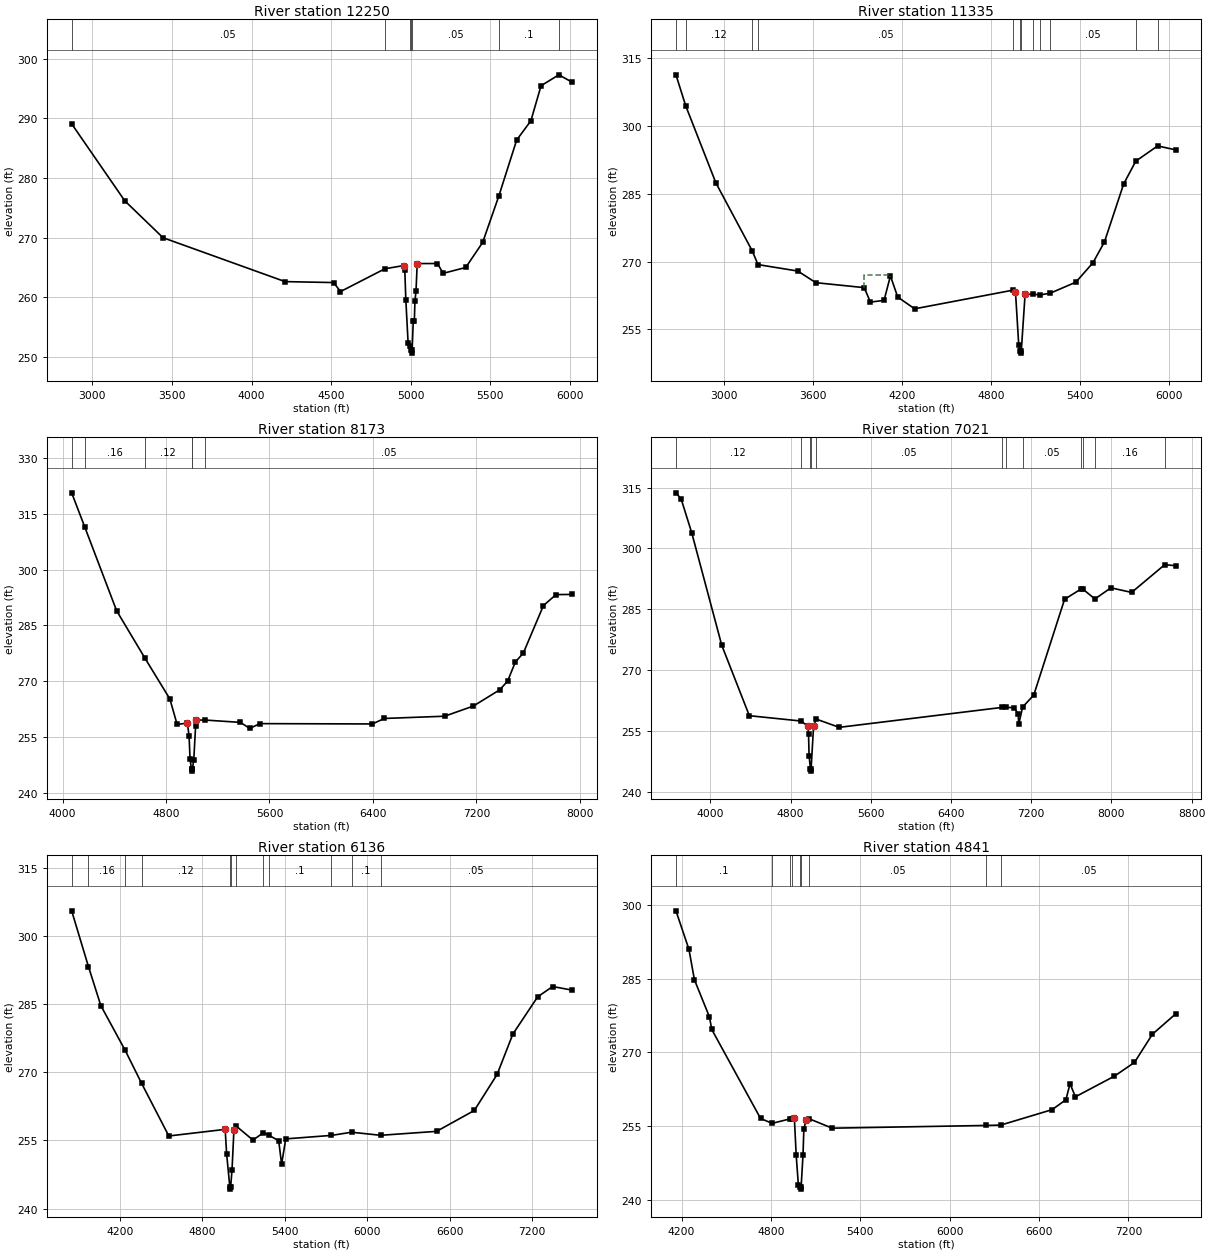
Type RM Length L Ch R = 1 ,12250   ,915,915,915
BEGIN DESCRIPTION:
WEST CANEY CREEK 12.0
END DESCRIPTION:
XS GIS Cut Line= 4
      3594977.75     10336347.64      3593342.11     10337741.64
      3592902.48     10338127.25      3592502.73      10338205.5
#Sta/Elev= 30
  2870.4  289.09  3203.9  276.19  3444.3     270  4210.8  262.64    4516  262.48
  4558.9  260.97  4837.6  264.79  4955.2  265.33  4962.9  264.53  4969.5   259.5
  4983.8  252.27  4992.4  251.86  5002.8  251.15  5005.5  250.65  5008.8  251.15
  5016.2  256.11  5022.8  256.11  5026.6  259.39  5033.3  261.08  5040.8  265.67
    5168  265.67  5204.1  264.03  5345.5  265.01  5451.7   269.2    5553  276.95
  5665.8  286.39  5754.8   289.6  5818.6  295.48  5930.4  297.31  6011.6  296.11
#Mann= 7 ,-1 , 0
  2870.4     .05       0  4837.6     .12       0  4992.4     .05       0
  5002.8    .035       0  5008.8     .05       0    5553      .1       0
  5930.4     .05       0
Bank Sta=4955.2,5040.8
XS Rating Curve= 0 ,0
Exp/Cntr=0.3,0.1

Type RM Length L Ch R = 1 ,11335   ,3162,3162,3162
BEGIN DESCRIPTION:
WEST CANEY CREEK 10.0
END DESCRIPTION:
XS GIS Cut Line= 3
       3594292.1     10335541.65      3592632.72     10337456.31
      3592382.73      10338256.3
#Sta/Elev= 30
  2674.2  311.35  2740.4  304.45  2943.4  287.42  3188.3  272.38  3227.5  269.33
  3496.2   267.9  3616.8  265.33  3943.5  264.23  3985.3  261.03  4077.4  261.41
  4120.1  266.83  4169.5  262.14  4283.5  259.54    4949  263.69  4963.5  263.23
  4985.4  251.51  4996.6  250.23  4999.4  249.73  5002.6  250.23  5028.1  262.73
  5084.2  262.78  5128.1  262.62  5197.8     263  5370.6  265.44  5485.8  269.74
  5563.2  274.35  5693.1  287.22  5774.9  292.25  5922.1  295.61    6046  294.72
#Mann= 12 ,-1 , 0
  2674.2     .05       0  2740.4     .12       0  3188.3     .16       0
  3227.5     .05       0    4949      .1       0  4996.6     .07       0
  5002.6      .1       0  5084.2     .05       0  5128.1      .1       0
  5197.8     .05       0  5774.9      .1       0  5922.1     .05       0
#XS Ineff= 1 ,-1
 3940.91 4118.18  266.93
Permanent Ineff=
       F
Bank Sta=4963.5,5028.1
XS Rating Curve= 0 ,0
Exp/Cntr=0.3,0.1

Type RM Length L Ch R = 1 ,8173    ,1152,1152,1152
BEGIN DESCRIPTION:
WEST CANEY CREEK 9.0
END DESCRIPTION:
XS GIS Cut Line= 3
      3593242.13     10334391.61      3592335.26      10335454.1
      3591942.11     10337891.61
#Sta/Elev= 30
  4070.8  320.64    4173  311.36  4418.3  288.94  4636.4  276.24  4830.1  265.22
    4886  258.37  4964.9  258.76  4978.3  255.36    4986  249.01  4997.2  246.33
    5000  245.83  5003.2  246.33  5014.5  248.74  5028.8  257.92  5035.4  259.55
  5101.7  259.56  5375.7  258.93  5447.1  257.31    5526   258.6  6395.1  258.51
  6488.3  259.99  6954.2  260.59    7177  263.34  7379.6  267.68  7440.4  270.01
  7501.2  275.19    7562  277.55  7717.9  290.35  7815.2  293.28  7936.7  293.33
#Mann= 6 ,-1 , 0
  4070.8     .12       0    4173     .16       0  4636.4     .12       0
  4997.2     .07       0  5003.2     .12       0  5101.7     .05       0
Bank Sta=4964.9,5035.4
XS Rating Curve= 0 ,0
Exp/Cntr=0.3,0.1

Type RM Length L Ch R = 1 ,7021    ,885,885,885
BEGIN DESCRIPTION:
WEST CANEY CREEK 8.0
END DESCRIPTION:
XS GIS Cut Line= 3
      3592529.83     10333700.05      3591424.27     10335952.45
      3589266.54     10337171.96
#Sta/Elev= 30
  3656.9   313.7  3708.6  312.18  3814.6  303.82  4113.4  276.15  4388.8  258.77
  4899.3  257.47  4973.1  256.25  4979.1  254.29  4984.6  248.89  4998.5  245.61
  5001.3  245.11  5004.5  245.61  5029.6  256.27  5056.3  257.93  5285.1   255.9
  6910.8  260.82  6949.1  260.87  7031.9   260.7  7069.5  259.21  7075.9  256.68
  7113.9  260.89  7225.2  263.84  7532.9  287.47  7695.6  289.97  7719.3  289.88
  7835.4  287.54  7994.9  290.29  8201.4  289.15  8531.6  295.99  8644.5  295.73
#Mann= 12 ,-1 , 0
  3656.9     .12       0  4899.3     .16       0  4998.5     .07       0
  5004.5     .16       0  5056.3     .05       0  6910.8     .16       0
  6949.1      .1       0  7113.9     .05       0  7695.6     .16       0
  7719.3     .05       0  7835.4     .16       0  8531.6     .05       0
Bank Sta=4973.1,5029.6
XS Rating Curve= 0 ,0
Exp/Cntr=0.3,0.1

Type RM Length L Ch R = 1 ,6136    ,1295,1295,1295
BEGIN DESCRIPTION:
WEST CANEY CREEK 7.0
END DESCRIPTION:
XS GIS Cut Line= 3
      3592192.12     10333741.62      3591392.11     10334541.64
      3589291.94     10335913.65
#Sta/Elev= 30
  3848.2   305.6  3970.1  293.33  4060.4  284.72  4237.8  274.85  4356.5  267.63
  4555.3  255.99  4965.5  257.45  4976.1  252.04  4999.3  244.78    5002  244.28
  5005.3  244.78  5015.4  248.53  5029.3  257.39  5042.7  258.25  5168.2  255.08
  5242.3  256.69  5282.2  256.17  5355.1  254.95  5376.2  249.79  5406.5  255.35
  5739.2  256.12  5885.6  256.82  6096.5  256.14  6504.4  257.01  6778.9  261.61
  6944.8  269.55  7059.4  278.44  7240.4  286.66    7349  288.92  7488.2  288.14
#Mann= 12 ,-1 , 0
  3848.2     .12       0  3970.1     .16       0  4237.8     .05       0
  4356.5     .12       0  4999.3     .07       0  5005.3     .12       0
  5042.7     .16       0  5242.3     .05       0  5282.2      .1       0
  5739.2     .16       0  5885.6      .1       0  6096.5     .05       0
Bank Sta=4965.5,5029.3
XS Rating Curve= 0 ,0
Exp/Cntr=0.3,0.1

Type RM Length L Ch R = 1 ,4841    ,1609,1609,1609
BEGIN DESCRIPTION:
WEST CANEY CREEK 6.0
END DESCRIPTION:
XS GIS Cut Line= 3
      3591542.12     10333391.63      3590533.28     10334003.91
      3589092.29     10335635.88
#Sta/Elev= 30
  4162.5  298.77  4249.7  290.94  4286.6  284.76  4387.4  277.22  4402.9  274.67
  4730.5   256.6  4807.7  255.61  4930.8  256.53    4939  256.58  4957.2  256.79
  4969.7  249.12  4984.4  243.05  4996.9  242.75  4999.7  242.25  5002.9  242.75
  5015.4   249.2  5021.2  254.55  5036.7  256.25  5057.4  256.53  5211.2  254.63
  6241.7  255.18  6342.2  255.25  6687.5  258.39  6780.3   260.4    6808  263.66
    6844     261  7105.8  265.19  7240.5  267.98    7361  273.71  7519.7  277.91
#Mann= 9 ,-1 , 0
  4162.5      .1       0  4807.7     .12       0  4930.8     .05       0
    4939     .12       0  4996.9     .07       0  5002.9     .12       0
  5057.4     .05       0  6241.7      .1       0  6342.2     .05       0
Bank Sta=4957.2,5036.7
XS Rating Curve= 0 ,0
Exp/Cntr=0.3,0.1

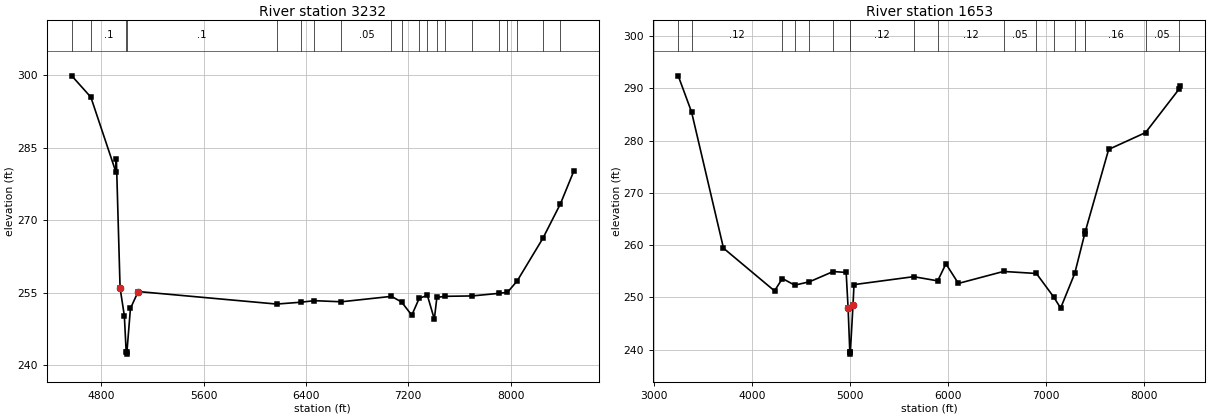
Type RM Length L Ch R = 1 ,3232    ,1579,1579,1579
BEGIN DESCRIPTION:
WEST CANEY CREEK 3.0
END DESCRIPTION:
XS GIS Cut Line= 3
      3591705.15     10333170.57      3590498.56      10332979.6
       3588492.1     10334791.65
#Sta/Elev= 30
  4568.7  299.88  4717.9  295.47  4912.3   280.1  4917.4  282.69  4946.4  256.01
  4979.7  250.29    4994  242.85  4996.8  242.35    5000  242.85  5027.4   251.8
  5088.1  255.29  6170.2   252.7  6359.6  253.08  6464.8   253.4  6675.9  253.17
  7068.1  254.29  7147.1  253.12  7226.9   250.4  7285.1   253.9  7348.9  254.49
  7403.2  249.57  7423.1  254.08  7489.3   254.3  7699.1  254.38  7910.5  254.92
  7975.1  255.13  8050.9  257.48  8251.1  266.26  8389.1  273.43  8493.9  280.21
#Mann= 20 ,-1 , 0
  4568.7      .1       0  4717.9      .1       0    4994     .07       0
    5000      .1       0  6170.2      .1       0  6359.6     .05       0
  6464.8      .1       0  6675.9     .05       0  7068.1     .05       0
  7147.1     .12       0  7285.1      .1       0  7348.9     .12       0
  7423.1      .1       0  7489.3     .05       0  7699.1      .1       0
  7910.5      .1       0  7975.1     .05       0  8050.9      .1       0
  8251.1     .16       0  8389.1      .1       0
Bank Sta=4946.4,5088.1
XS Rating Curve= 0 ,0
Exp/Cntr=0.3,0.1

Type RM Length L Ch R = 1 ,1653    ,0,0,0
BEGIN DESCRIPTION:
WEST CANEY CREEK 1.0
END DESCRIPTION:
XS GIS Cut Line= 3
      3592243.31     10332180.99      3590116.62      10332267.8
      3588172.16     10334542.12
#Sta/Elev= 30
  3250.8  292.39  3386.7  285.47  3712.4  259.41  4232.8  251.24    4313  253.61
  4438.5  252.34  4588.7  252.98  4830.4  254.94  4963.4  254.77  4983.4   247.9
  5000.5  239.64  5003.2  239.14  5006.5  239.64  5033.5  248.63  5043.5  252.44
  5651.9  253.96  5897.1  253.16  5980.8  256.42  6108.1  252.67  6568.4  254.96
  6903.8  254.57  7081.2  250.04    7151  247.95  7294.8  254.59    7396  262.12
  7402.7  262.62  7640.7  278.31  8016.9  281.53  8355.9  289.78  8371.5  290.43
#Mann= 18 ,-1 , 0
  3250.8     .05       0  3386.7     .12       0    4313      .1       0
  4438.5     .12       0  4588.7      .1       0  4830.4     .12       0
  5000.5     .07       0  5006.5     .12       0  5651.9      .1       0
  5897.1     .12       0  6568.4     .05       0  6903.8      .1       0
  7081.2     .12       0  7294.8      .1       0    7396     .12       0
  7402.7     .16       0  8016.9     .05       0  8355.9      .1       0
Bank Sta=4983.4,5033.5
XS Rating Curve= 0 ,0
Exp/Cntr=0.3,0.1

Chan Stop Cuts=-1
Use User Specified Reach Order=0
Composite Channel Slope=5