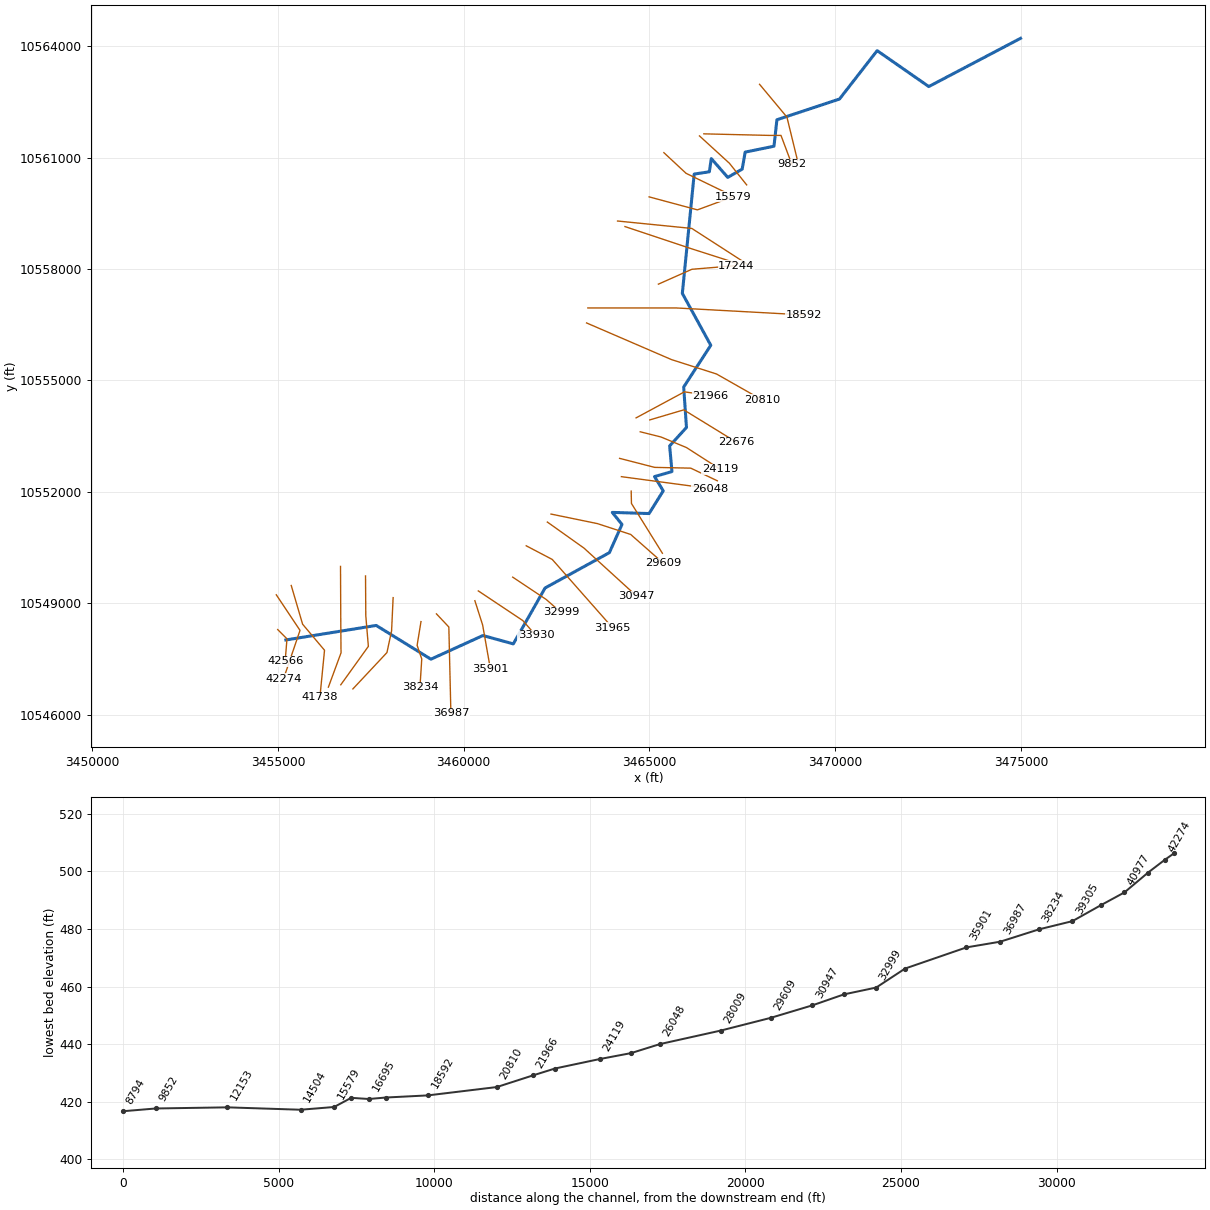
--- BARGER BRANCH.prj (project) ---

Proj Title=BARGER BRANCH Base Level Engineering
Current Plan=p01
Default Exp/Contr=0.3,0.1
English Units
Geom File=g01
Flow File=f01
Plan File=p01
Y Axis Title=Elevation
X Axis Title(PF)=Main Channel Distance
X Axis Title(XS)=Station
BEGIN DESCRIPTION:
BARGER BRANCH
END DESCRIPTION:
DSS Export Rating Curves= 0
DSS Export Rating Curve Sorted= 0
DSS Export Volume Flow Curves= 0
DXF OffsetX= 0
DXF OffsetY= 0
DXF ScaleX= 1
DXF ScaleY= 10

--- BARGER BRANCH.p01 (plan) ---

Plan Title=Multiple Run
Short Identifier=Multiple
Geom File=g01
Flow File=f01
Subcritical Flow
K Sum by GR= 0
Std Step Tol= 0.01
Critical Tol= 0.01
Num of Std Step Trials= 20
Max Error Tol= 0.3
Flow Tol Ratio= 0.001
Split Flow NTrial= 30
Split Flow Tol= 0.02
Split Flow Ratio= 0.02
Log Output Level= 0
Friction Slope Method= 1
Unsteady Friction Slope Method= 2
Unsteady Bridges Friction Slope Method= 1
Parabolic Critical Depth
Global Vel Dist=  1 , 1 , 1
Global Log Level= 0
CheckData=True
Encroach Param= -1, 0, 0, 0
BEGIN DESCRIPTION:
Multiple Run
END DESCRIPTION:

--- BARGER BRANCH.f01 (steady flow) ---

Flow Title=Multiple
Program Version=4.10
Number of Profiles= 7
Profile Names=10-year,25-year,50-year,1pct_min,100-year,1pct_plu,500-year
River Rch & RM=BARGER BRANCH,Reach-1         ,42566
     435     547     630     528     714     966     915
River Rch & RM=BARGER BRANCH,Reach-1         ,35901
     642     820     954     806    1091    1475    1422
River Rch & RM=BARGER BRANCH,Reach-1         ,26048
     721     924    1076     911    1232    1666    1611
River Rch & RM=BARGER BRANCH,Reach-1         ,20810
    1836    2466    2965    2584    3494    4726    4844
River Rch & RM=BARGER BRANCH,Reach-1         ,16695
    2070    2788    3358    2930    3962    5358    5507
River Rch & RM=BARGER BRANCH,Reach-1         ,9852
    2121    2855    3438    2999    4056    5485    5634
River Rch & RM=BARGER BRANCH,Reach-1         ,8794
    2378    3208    3868    3377    4567    6176    6354
River Rch & RM=BARGER BRANCH,Reach-1         ,1317
    2385    3213    3872    3377    4567    6177    6344
Boundary for River Rch & Prof#=BARGER BRANCH,Reach-1         , 1
Up Type= 0
Dn Type= 3
Dn Slope=0.001
Boundary for River Rch & Prof#=BARGER BRANCH,Reach-1         , 2
Up Type= 0
Dn Type= 3
Dn Slope=0.001
Boundary for River Rch & Prof#=BARGER BRANCH,Reach-1         , 3
Up Type= 0
Dn Type= 3
Dn Slope=0.001
Boundary for River Rch & Prof#=BARGER BRANCH,Reach-1         , 4
Up Type= 0
Dn Type= 3
Dn Slope=0.001
Boundary for River Rch & Prof#=BARGER BRANCH,Reach-1         , 5
Up Type= 0
Dn Type= 3
Dn Slope=0.001
Boundary for River Rch & Prof#=BARGER BRANCH,Reach-1         , 6
Up Type= 0
Dn Type= 3
Dn Slope=0.001
Boundary for River Rch & Prof#=BARGER BRANCH,Reach-1         , 7
Up Type= 0
Dn Type= 3
Dn Slope=0.001
DSS Import GetInterval= 0
DSS Import GetPeak= 0
DSS Import FillOption= 0

--- BARGER BRANCH.g01 (geometry) ---

Geom Title=Existing Conditions
Program Version=4.10

River Reach=BARGER BRANCH   ,Reach-1
Reach XY= 30
      3455212.04     10548011.58      3457644.18     10548402.59
      3459117.74     10547493.89      3460517.31     10548131.23
       3461335.4     10547905.96      3462192.11     10549411.64
      3463921.73      10550361.6      3464261.39     10551122.06
      3464000.22     10551446.13      3464990.46     10551415.18
      3465372.21     10552026.62      3465137.27     10552410.25
      3465607.31     10552545.51      3465544.83      10553236.3
      3465997.66     10553732.91      3465922.94     10554821.45
      3466652.42     10555946.16      3465886.47     10557343.21
      3466205.74     10560555.22      3466613.35     10560617.35
      3466667.06     10560971.76      3467109.05     10560465.52
      3467498.37     10560688.93      3467577.74     10561146.27
      3468354.09     10561305.49      3468432.79     10562017.66
      3470118.32     10562576.16      3471131.86     10563878.62
      3472522.11     10562911.64      3474992.56     10564210.09

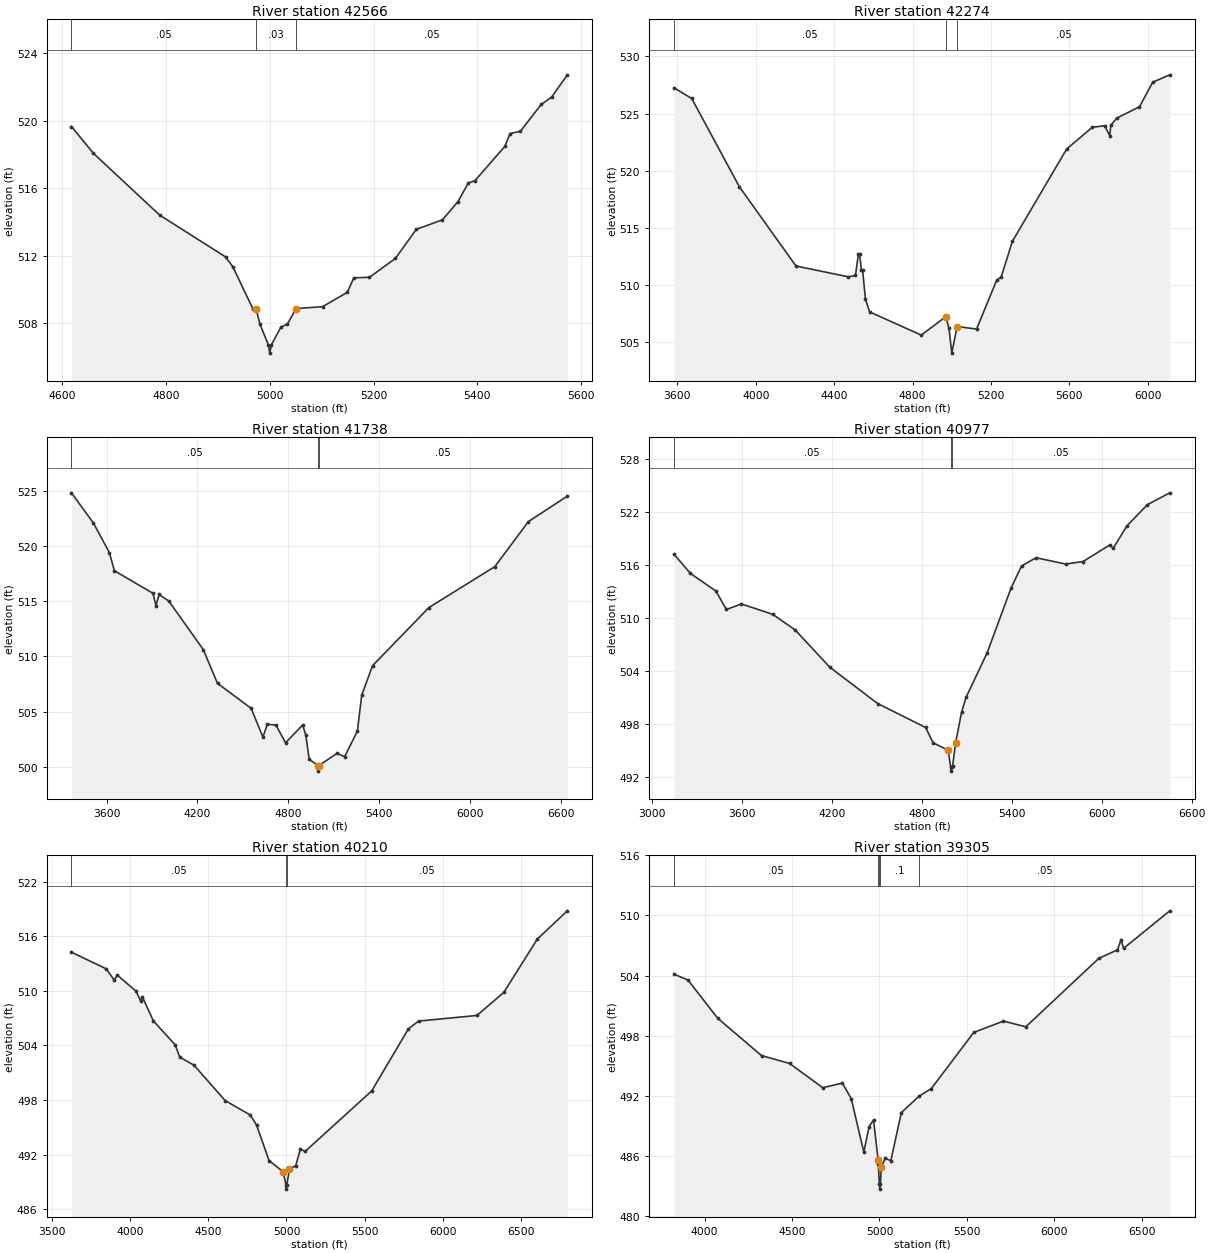
Type RM Length L Ch R = 1 ,42566   ,292,292,292
BEGIN DESCRIPTION:
BARGER BRANCH 59.0
END DESCRIPTION:
XS GIS Cut Line= 3
      3454992.14     10548291.61      3455242.11     10548041.64
       3455192.1     10547441.63
#Sta/Elev= 30
  4617.6  519.66    4660  518.07  4787.3  514.42  4914.5  511.94  4928.7  511.35
  4967.6  508.84  4973.6  508.84  4981.1  507.94    4997  506.74  4999.8  506.24
    5003  506.74  5021.3  507.78  5033.8  507.96 5050.57  508.88  5101.6  508.99
  5149.2  509.84  5161.8   510.7  5191.9  510.73    5242  511.85  5282.2  513.57
  5332.4  514.13  5362.5  515.21  5382.5  516.32  5395.1  516.45  5452.8  518.48
  5462.8  519.24  5482.9  519.38    5523  520.97  5543.1   521.4  5573.2  522.72
#Mann= 3 , 0 , 0
  4617.6     .05       0  4973.6     .03       0 5050.57     .05       0
Bank Sta=4973.6,5050.57
XS Rating Curve= 0 ,0
Exp/Cntr=0.3,0.1

Type RM Length L Ch R = 1 ,42274   ,536,536,536
BEGIN DESCRIPTION:
BARGER BRANCH 58.0
END DESCRIPTION:
XS GIS Cut Line= 3
      3454953.97     10549227.79      3455592.84     10548269.49
      3455148.87     10546965.32
#Sta/Elev= 30
  3582.6  527.25  3673.2  526.32  3916.6  518.58  4205.1  511.65  4472.5   510.7
  4508.5  510.82  4523.6  512.72  4529.6  512.73  4538.6  511.33  4544.6  511.32
  4559.6  508.74  4580.6  507.63  4844.1   505.6  4969.5  507.21  4985.6  506.18
  4999.8  504.02    5027  506.35  5126.3  506.13  5228.5  510.39  5251.8  510.69
  5309.2  513.82  5586.2   521.9  5716.9   523.8  5779.6  523.93  5805.7  523.06
    5811  523.97  5842.4  524.61  5957.2  525.59  6025.2  527.75    6112  528.39
#Mann= 3 , 0 , 0
  3582.6     .05       0  4969.5     .03       0    5027     .05       0
Bank Sta=4969.5,5027
XS Rating Curve= 0 ,0
Exp/Cntr=0.3,0.1

Type RM Length L Ch R = 1 ,41738   ,761,761,761
BEGIN DESCRIPTION:
BARGER BRANCH 57.0
END DESCRIPTION:
XS GIS Cut Line= 4
      3455356.74     10549477.78      3455662.28     10548436.16
      3456252.56     10547734.77       3456127.7     10546465.33
#Sta/Elev= 30
  3366.8  524.81    3512  522.07  3617.4   519.4  3650.8  517.75  3905.5  515.71
  3925.5   514.6  3946.4   515.6  4010.8     515  4238.2  510.61  4332.3  507.55
  4554.6  505.29  4632.6  502.68  4661.2  503.85  4718.4  503.77  4782.2  502.17
  4895.4  503.78  4916.2  502.85  4938.3  500.67    4997   500.1  4999.8   499.6
    5003   500.1  5122.9  501.22  5172.4   500.9  5256.9  503.23  5285.5  506.47
    5357  509.15  5730.1  514.42    6166  518.13    6387   522.2  6644.6  524.51
#Mann= 3 ,-1 , 0
  3366.8     .05       0    4997     .03       0    5003     .05       0
Bank Sta=4997,5003
XS Rating Curve= 0 ,0
Exp/Cntr=0.3,0.1

Type RM Length L Ch R = 1 ,40977   ,767,767,767
BEGIN DESCRIPTION:
BARGER BRANCH 55.0
END DESCRIPTION:
XS GIS Cut Line= 4
      3456683.12     10549991.76      3456690.06     10548540.33
      3456697.01     10547665.33      3456356.93     10546742.26
#Sta/Elev= 30
  3143.9  517.26    3254  515.08    3424  513.09    3494     511    3594  511.63
    3804  510.45    3954  508.67    4184  504.47    4504  500.35    4824  497.64
    4874  495.91  4974.1  495.07  4991.1   493.2  4993.8   492.7  4997.1   493.2
  5004.1   493.3  5024.1  495.91  5064.1  499.38  5094.1  501.06  5234.1  506.07
  5394.1  513.42  5464.1  515.92  5560.9  516.86    5758  516.15  5874.5  516.43
  6051.9  518.29    6077  517.95  6168.3  520.48  6304.6  522.87  6454.1  524.21
#Mann= 3 ,-1 , 0
  3143.9     .05       0  4991.1     .03       0  4997.1     .05       0
Bank Sta=4974.1,5024.1
XS Rating Curve= 0 ,0
Exp/Cntr=0.3,0.1

Type RM Length L Ch R = 1 ,40210   ,905,905,905
BEGIN DESCRIPTION:
BARGER BRANCH 53.0
END DESCRIPTION:
XS GIS Cut Line= 4
      3457356.73     10549734.81      3457363.67     10548665.33
      3457433.12     10547838.94      3456690.93     10546805.43
#Sta/Elev= 30
  3624.7  514.24  3847.9  512.41  3897.9  511.17  3917.9  511.73  4037.9  509.95
  4067.9  508.86  4077.9  509.37  4147.9  506.71  4287.9  504.06  4317.9   502.7
  4407.9  501.83  4607.9  497.93  4768.2  496.35  4808.3  495.25  4888.6  491.34
    4979   490.1    4996   488.7  4998.7   488.2    5002   488.7    5019  490.38
  5059.2  490.79  5088.9  492.59  5119.4  492.35  5544.8  498.99  5779.4  505.81
  5844.4  506.67  6217.7  507.29  6389.6  509.82  6603.6  515.67  6795.9  518.79
#Mann= 3 ,-1 , 0
  3624.7     .05       0    4996     .03       0    5002     .05       0
Bank Sta=4979,5019
XS Rating Curve= 0 ,0
Exp/Cntr=0.3,0.1

Type RM Length L Ch R = 1 ,39305   ,1071,1071,1071
BEGIN DESCRIPTION:
BARGER BRANCH 51.0
END DESCRIPTION:
XS GIS Cut Line= 4
      3458099.78     10549151.46      3458058.12     10548255.61
      3457933.12     10547672.27      3457016.78     10546693.46
#Sta/Elev= 30
  3825.4  504.14  3905.3  503.57  4075.5  499.75  4325.8  496.03  4485.9  495.25
  4676.1  492.83  4787.6  493.29  4838.8  491.74  4910.4  486.42    4941  488.96
  4966.1  489.62  4992.2  485.67  4993.4  485.26  4999.4  483.22  5002.2  482.72
  5005.4  483.22  5010.5  484.92  5033.1   485.8    5065  485.55  5125.1  490.35
  5225.7  491.97  5296.8  492.75  5539.1  498.34    5709  499.47  5836.5   498.9
  6253.7  505.72  6360.2  506.57  6381.2  507.59  6395.4  506.72  6659.6  510.46
#Mann= 5 ,-1 , 0
  3825.4     .05       0  4993.4      .1       0  4999.4     .07       0
  5005.4      .1       0  5225.7     .05       0
Bank Sta=4992.2,5010.5
XS Rating Curve= 0 ,0
Exp/Cntr=0.3,0.1

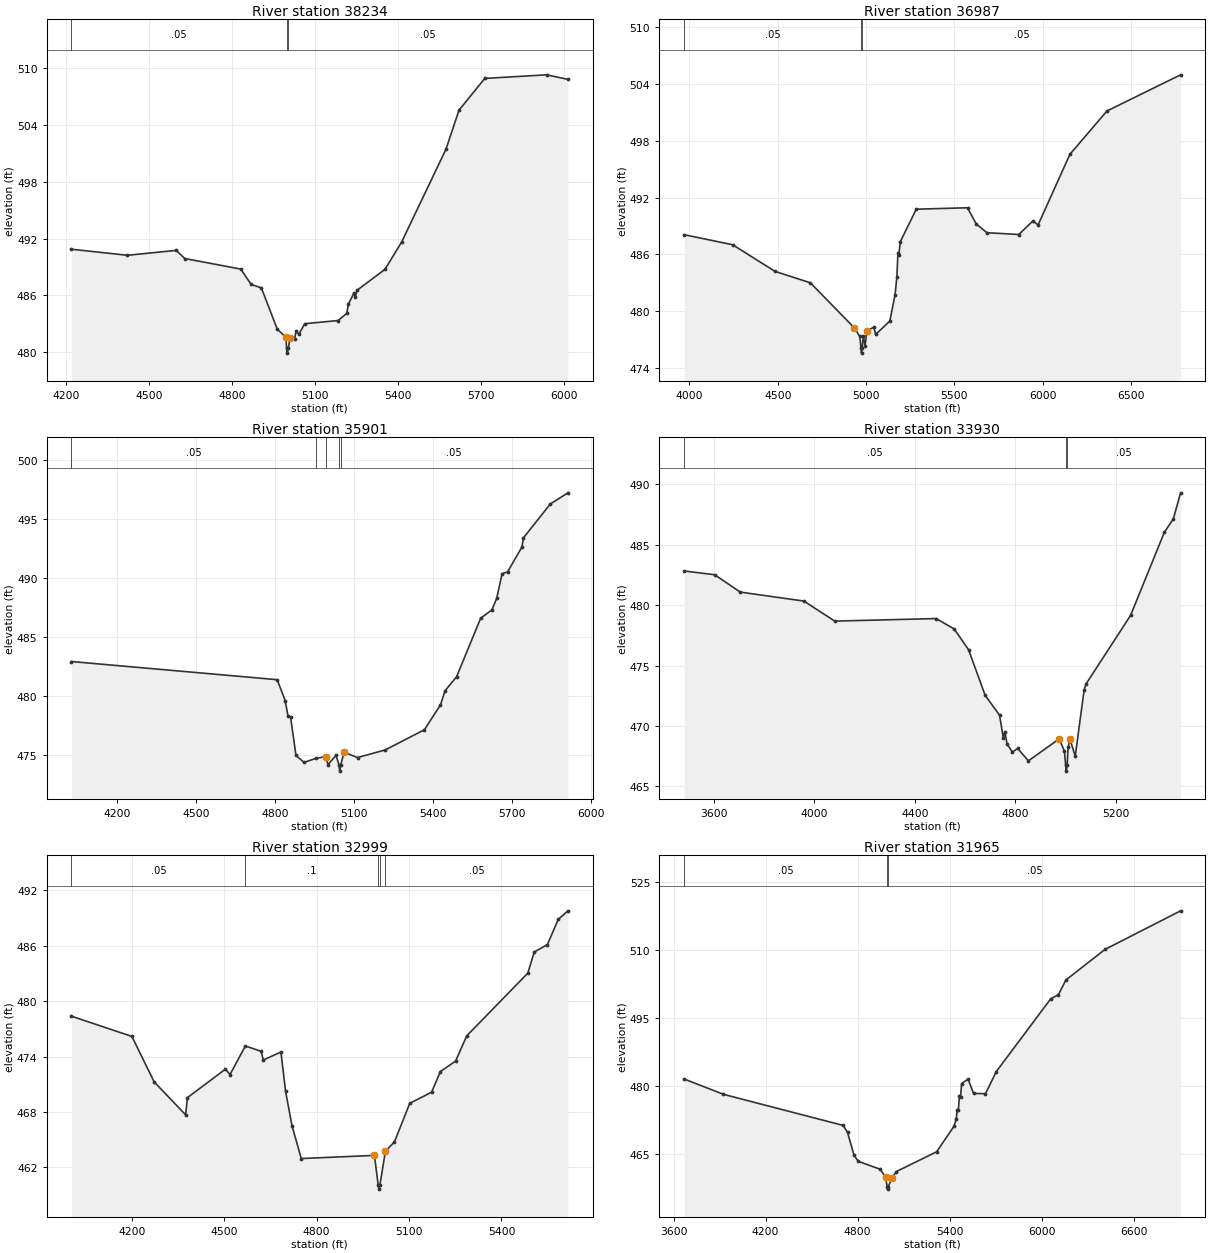
Type RM Length L Ch R = 1 ,38234   ,1247,1247,1247
BEGIN DESCRIPTION:
BARGER BRANCH 49.0
END DESCRIPTION:
XS GIS Cut Line= 4
      3458849.78     10548505.61      3458745.62     10547866.72
      3458870.62     10547498.66      3458822.01     10546741.75
#Sta/Elev= 30
  4219.2  490.87  4421.5  490.23  4598.1  490.75  4628.5  489.89  4831.1  488.77
  4868.9  487.14  4905.5  486.79    4963  482.42  4994.4  481.55  4996.7  480.38
  4999.5  479.88  5002.7  480.38  5009.2   481.5  5025.8  481.37  5031.1  482.26
  5040.9  481.87  5062.5  482.99  5182.8  483.33  5214.2  484.08  5220.4  485.08
  5240.3  486.23  5245.6  485.81    5251  486.52  5352.4  488.74  5412.6  491.63
  5572.9  501.45    5620  505.58  5713.2  508.94  5936.4  509.32  6013.7  508.84
#Mann= 3 ,-1 , 0
  4219.2     .05       0  4996.7     .03       0  5002.7     .05       0
Bank Sta=4994.4,5009.2
XS Rating Curve= 0 ,0
Exp/Cntr=0.3,0.1

Type RM Length L Ch R = 1 ,36987   ,1086,1086,1086
BEGIN DESCRIPTION:
BARGER BRANCH 47.0
END DESCRIPTION:
XS GIS Cut Line= 3
      3459266.47     10548713.92      3459599.78     10548359.77
       3459655.3     10546034.97
#Sta/Elev= 30
  3970.2  488.08  4244.7  487.02  4484.7  484.21  4684.7  483.01  4934.8  478.24
  4964.8  477.35  4971.8  476.09  4974.6  475.59  4977.8  476.09  4984.8  477.41
  4994.8  476.34  5004.8  477.95  5044.8  478.32  5054.8  477.56  5134.9  478.97
  5164.9  481.77  5174.9  483.64    5181  486.15    5186  485.97  5194.9  487.36
  5284.9  490.77    5575  490.92    5625   489.2    5685  488.29  5865.1   488.1
  5945.1  489.52  5975.1  489.12  6155.1  496.56  6365.2  501.13    6782  504.94
#Mann= 3 ,-1 , 0
  3970.2     .05       0  4971.8    .035       0  4977.8     .05       0
Bank Sta=4934.8,5004.8
XS Rating Curve= 0 ,0
Exp/Cntr=0.3,0.1

Type RM Length L Ch R = 1 ,35901   ,1971,1971,1971
BEGIN DESCRIPTION:
BARGER BRANCH 45.0
END DESCRIPTION:
XS GIS Cut Line= 3
      3460301.18     10549068.08      3460509.51     10548415.33
      3460717.67     10547235.75
#Sta/Elev= 30
  4027.8   482.9  4808.1  481.36  4838.6  479.58  4848.7  478.32  4858.9  478.19
  4879.2  474.95  4909.7  474.35    4955  474.69  4991.4  474.84  5001.1  474.17
  5031.5  474.95  5042.6  474.11  5045.3  473.61  5048.6  474.11    5062  475.21
  5112.8  474.76  5218.2  475.41  5366.6  477.12  5427.5  479.23    5445  480.43
  5488.5  481.61  5579.9  486.57  5622.7  487.28  5640.8  488.26  5661.1  490.34
  5681.9   490.5  5736.1  492.59  5742.3  493.39  5843.9  496.25  5910.8   497.2
#Mann= 5 ,-1 , 0
  4027.8     .05       0    4955     .12       0  4991.4     .05       0
  5042.6     .07       0  5048.6     .05       0
Bank Sta=4991.4,5062
XS Rating Curve= 0 ,0
Exp/Cntr=0.3,0.1

Type RM Length L Ch R = 1 ,33930   ,931,931,931
BEGIN DESCRIPTION:
BARGER BRANCH 43.0
END DESCRIPTION:
XS GIS Cut Line= 3
      3460393.49     10549331.92      3461593.49     10548531.92
      3461943.47     10548131.94
#Sta/Elev= 30
  3483.2  482.84  3604.3  482.53  3706.5  481.09  3958.9  480.35    4082  478.69
  4484.7   478.9  4556.8  478.04  4613.9  476.32    4680  472.54  4737.1   470.9
  4752.1  469.02  4758.1  469.52  4767.1  468.51  4788.1  467.85  4809.2  468.15
  4851.6  467.12  4974.4  468.94  4995.3   467.9  4999.9  466.77  5002.6  466.27
  5005.9  466.77  5009.5  468.24  5017.1   468.9    5038  467.51  5073.1  472.95
  5080.7  473.48    5258  479.16    5392  486.03  5428.1  487.16  5456.9  489.31
#Mann= 3 ,-1 , 0
  3483.2     .05       0  4999.9     .03       0  5005.9     .05       0
Bank Sta=4974.4,5017.1
XS Rating Curve= 0 ,0
Exp/Cntr=0.3,0.1

Type RM Length L Ch R = 1 ,32999   ,1034,1034,1034
BEGIN DESCRIPTION:
BARGER BRANCH 42.0
END DESCRIPTION:
XS GIS Cut Line= 3
      3461319.91     10549702.73      3462219.88     10549102.75
       3462618.5     10548753.96
#Sta/Elev= 30
  4004.4  478.37  4200.5  476.18  4272.6  471.27  4374.8   467.7  4380.8  469.56
    4504  472.64    4519  472.06  4568.8  475.15    4620  474.57  4627.2  473.63
  4684.2   474.5  4699.3  470.25  4720.3  466.49  4750.3  462.97  4987.7  463.31
  4999.7  460.16  5002.5  459.66  5005.7  460.16  5023.5  463.78  5052.6  464.76
  5102.3  468.94  5173.3  470.15  5201.8  472.38  5251.1  473.51  5287.2  476.24
  5485.6  483.03  5506.4  485.31  5549.1  486.12  5584.3  488.84  5615.7  489.77
#Mann= 5 ,-1 , 0
  4004.4     .05       0  4568.8      .1       0  4999.7     .07       0
  5005.7      .1       0  5023.5     .05       0
Bank Sta=4987.7,5023.5
XS Rating Curve= 0 ,0
Exp/Cntr=0.3,0.1

Type RM Length L Ch R = 1 ,31965   ,1018,1018,1018
BEGIN DESCRIPTION:
BARGER BRANCH 39.0
END DESCRIPTION:
XS GIS Cut Line= 3
      3461683.15     10550547.25      3462384.51     10550179.22
      3464002.23     10548346.26
#Sta/Elev= 30
  3669.1  481.56  3925.3  478.19  4705.8  471.34  4734.2   469.8  4776.9  464.75
  4804.7  463.41  4946.7  461.69  4981.8  459.98  4993.1   457.8  4995.8   457.3
  4999.1   457.8  5024.5  459.76    5053  461.18  5314.8  465.52  5428.6  471.16
  5442.8  472.73  5449.5  474.78    5457  474.84  5463.7  477.73  5471.3  477.69
  5477.9  480.56  5520.6  481.54  5555.7   478.4  5633.5  478.32  5704.6  483.22
  6058.5  499.22  6108.7  500.13  6158.1  503.39  6413.2  510.13  6905.9  518.63
#Mann= 3 ,-1 , 0
  3669.1     .05       0  4993.1     .03       0  4999.1     .05       0
Bank Sta=4981.8,5024.5
XS Rating Curve= 0 ,0
Exp/Cntr=0.3,0.1

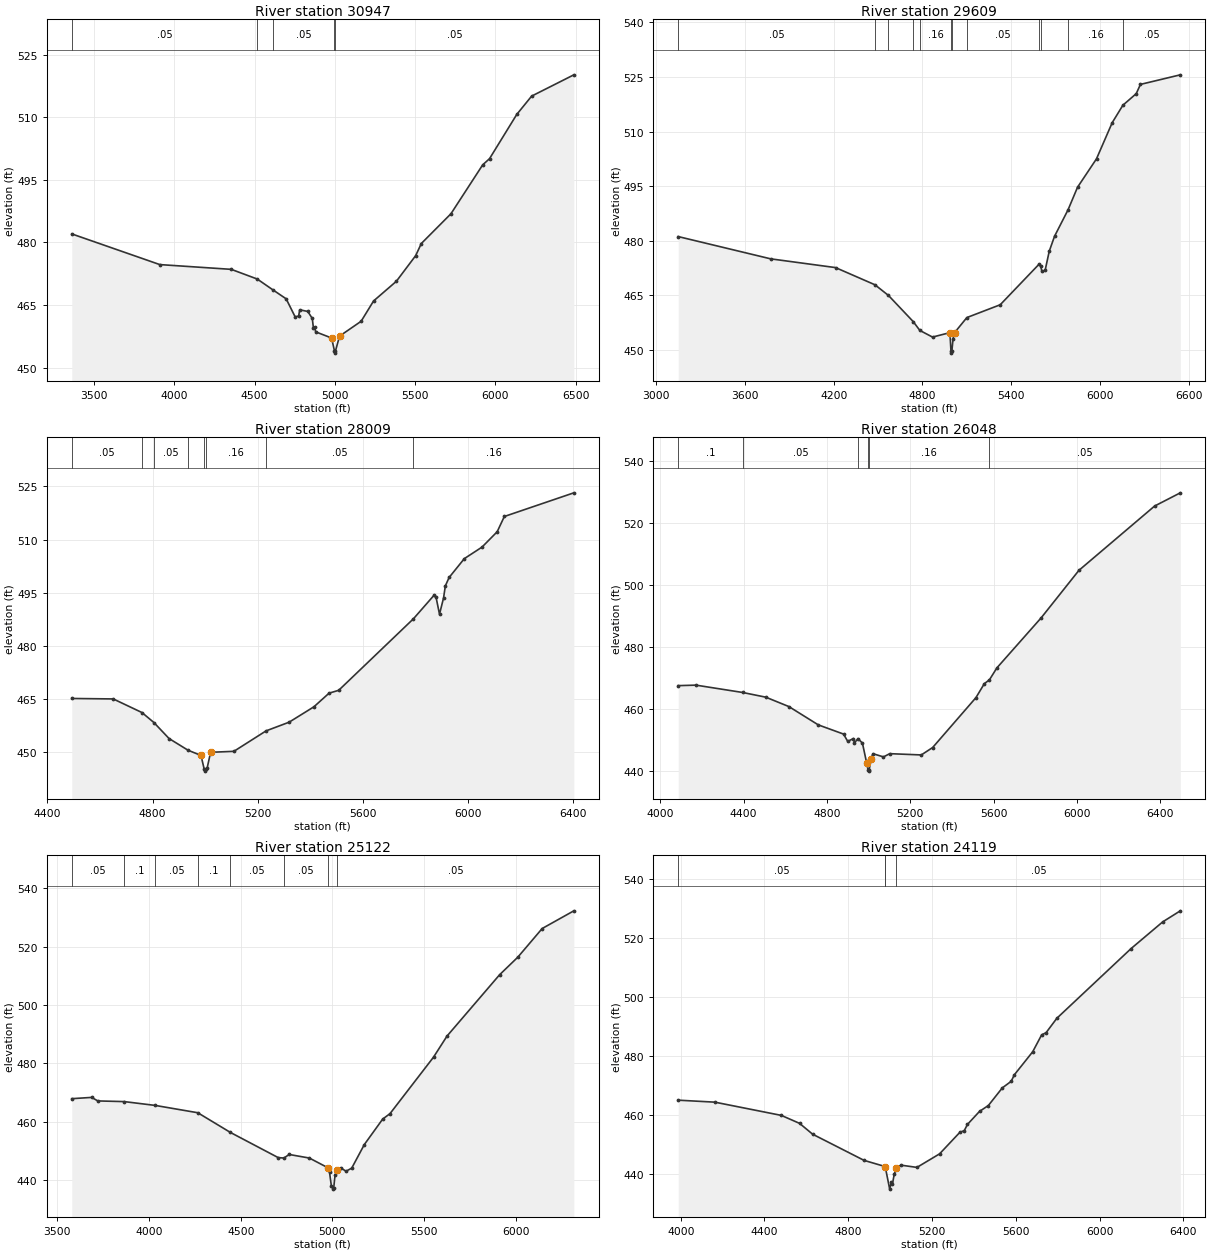
Type RM Length L Ch R = 1 ,30947   ,1338,1338,1338
BEGIN DESCRIPTION:
BARGER BRANCH 37.0
END DESCRIPTION:
XS GIS Cut Line= 3
      3462252.56     10551186.16      3463238.67     10550484.77
      3464655.32     10549193.12
#Sta/Elev= 30
  3360.8  482.04  3909.2  474.69  4354.2  473.55    4516  471.23  4612.7  468.66
  4696.1  466.49  4752.2  462.16  4773.8  462.37  4780.6  463.85  4830.6  463.47
    4859  461.78  4865.7  459.55  4873.2   459.8  4879.9  458.58  4979.2   457.1
  4997.2  453.98  4999.9  453.48  5003.2  453.98  5028.6  457.55    5163  461.11
  5240.7  465.98  5382.6  470.69  5502.9  476.84    5538  479.74  5722.4  486.86
  5920.4  498.59    5963  500.07  6132.6  510.67  6225.1  515.05    6488  520.15
#Mann= 5 ,-1 , 0
  3360.8     .05       0    4516     .12       0  4612.7     .05       0
  4997.2     .03       0  5003.2     .05       0
Bank Sta=4979.2,5028.6
XS Rating Curve= 0 ,0
Exp/Cntr=0.3,0.1

Type RM Length L Ch R = 1 ,29609   ,1600,1600,1600
BEGIN DESCRIPTION:
BARGER BRANCH 34.0
END DESCRIPTION:
XS GIS Cut Line= 4
      3462349.81     10551401.43      3463599.78     10551144.49
      3464495.62     10550852.83      3465376.41     10550076.07
#Sta/Elev= 30
  3149.9  481.16    3775  475.04  4212.8  472.64  4479.1  467.92  4570.6  464.98
  4737.5  457.81  4782.7  455.37  4868.1  453.55  4985.8  454.77  4992.8  449.64
  4995.5  449.14  4998.8  449.64  5006.9  453.07  5017.4  454.78  5100.2  458.91
  5325.6  462.43  5586.8  473.52  5598.1  473.15  5607.2  471.64    5629  471.87
  5656.8  477.13  5692.5  481.23  5784.1  488.53  5848.1  494.72  5976.2  502.53
  6082.4  512.46  6154.5  517.25  6244.7  520.43  6273.1  522.97  6542.5   525.6
#Mann= 12 ,-1 , 0
  3149.9     .05       0  4479.1      .1       0  4570.6     .16       0
  4737.5      .1       0  4782.7     .16       0  4992.8     .07       0
  4998.8     .16       0  5100.2     .05       0  5586.8     .16       0
  5598.1     .12       0  5784.1     .16       0  6154.5     .05       0
Bank Sta=4985.8,5017.4
XS Rating Curve= 0 ,0
Exp/Cntr=0.3,0.1

Type RM Length L Ch R = 1 ,28009   ,1961,1961,1961
BEGIN DESCRIPTION:
BARGER BRANCH 30.0
END DESCRIPTION:
XS GIS Cut Line= 3
      3464509.51      10552019.5      3464516.45     10551686.16
      3465349.55     10550346.25
#Sta/Elev= 30
  4492.4  465.22  4650.3  465.09  4759.5  461.26  4805.2  458.43  4862.7  453.93
  4934.8  450.64  4984.3  449.16  4996.7  445.24  4999.4  444.74  5002.7  445.24
  5007.8  445.64  5020.9  450.05  5109.5  450.32  5232.1  456.09  5319.6  458.53
  5414.1  462.87  5471.9  466.72  5508.5  467.52  5793.2   487.7    5871  494.28
  5879.1  493.77  5892.2  488.97  5907.6  493.55  5914.5  496.97  5928.8  499.33
  5986.7  504.64    6054  507.89  6111.8  512.22    6139  516.52  6403.6  523.19
#Mann= 8 ,-1 , 0
  4492.4     .05       0  4759.5     .16       0  4805.2     .05       0
  4934.8     .16       0  4996.7     .07       0  5002.7     .16       0
  5232.1     .05       0  5793.2     .16       0
Bank Sta=4984.3,5020.9
XS Rating Curve= 0 ,0
Exp/Cntr=0.3,0.1

Type RM Length L Ch R = 1 ,26048   ,926,926,926
BEGIN DESCRIPTION:
BARGER BRANCH 29.0
END DESCRIPTION:
XS GIS Cut Line= 2
       3464245.6     10552408.39      3466634.53     10552088.94
#Sta/Elev= 30
    4086   467.6  4171.4  467.76  4395.6  465.39  4506.2  463.88  4617.2  460.85
  4758.4  454.94  4879.5  451.98  4899.7  449.62    4927  450.55    4932  449.12
  4948.8  450.53  4970.3  449.05  4990.5  442.67    4997  440.53  4999.8  440.03
    5003  440.53  5010.7  443.78  5020.8  445.65  5071.2  444.62  5101.5  445.66
  5252.8  445.25  5307.3  447.64  5515.1  463.73  5555.5  468.25  5579.6  469.45
    5616  473.35  5827.9  489.44  6009.5  504.78  6372.7  525.51  6496.2  529.78
#Mann= 6 ,-1 , 0
    4086      .1       0  4395.6     .05       0  4948.8     .16       0
    4997     .07       0    5003     .16       0  5579.6     .05       0
Bank Sta=4990.5,5010.7
XS Rating Curve= 0 ,0
Exp/Cntr=0.3,0.1

Type RM Length L Ch R = 1 ,25122   ,1003,1003,1003
BEGIN DESCRIPTION:
BARGER BRANCH 27.0
END DESCRIPTION:
XS GIS Cut Line= 4
      3464197.02     10552901.44      3465141.45     10552658.38
      3466113.67     10552637.55      3466828.01     10552297.72
#Sta/Elev= 30
  3578.3  467.91  3686.8  468.35  3720.4  467.14  3864.6  466.91  4033.6   465.6
  4265.6  463.09  4444.1  456.32  4704.2  447.71  4735.5  447.56  4764.2  448.78
  4874.2  447.56  4974.3  444.27  4984.3  442.64  4994.3  438.04    5004   436.9
  5007.3   437.4  5014.3   441.7  5024.3  443.52  5044.3  444.23  5074.3  443.04
  5105.4   444.1  5174.3   452.2  5274.3  460.92  5314.3  462.79  5551.6  482.15
  5625.3  489.39  5911.8  510.39  6011.4  516.43  6144.4  526.26    6317  532.32
#Mann= 8 ,-1 , 0
  3578.3     .05       0  3864.6      .1       0  4033.6     .05       0
  4265.6      .1       0  4444.1     .05       0  4735.5     .05       0
  4974.3     .07       0  5024.3     .05       0
Bank Sta=4974.3,5024.3
XS Rating Curve= 0 ,0
Exp/Cntr=0.3,0.1

Type RM Length L Ch R = 1 ,24119   ,1443,1443,1443
BEGIN DESCRIPTION:
BARGER BRANCH 25.0
END DESCRIPTION:
XS GIS Cut Line= 4
      3464752.57     10553616.72      3465308.12     10553477.83
      3465995.62     10553193.11      3466905.38     10552609.75
#Sta/Elev= 30
  3988.2  464.98    4163  464.31  4480.3  459.83  4567.3  457.14  4630.1  453.45
  4875.6  444.59  4976.5  442.49  4997.9  434.85  5005.9  437.23  5011.3  436.64
  5019.8  439.97  5029.8  442.03  5052.2  442.97    5128  442.21  5236.2   446.8
    5333  454.09  5354.1  454.67  5369.3  456.77  5426.8  461.18  5469.1  463.17
  5535.9  469.16  5578.1  471.37  5593.3  473.59  5680.9  481.39  5723.5   487.1
  5744.7  487.84  5796.2  492.73  6150.4  516.32  6301.7  525.38  6385.7  529.12
#Mann= 4 ,-1 , 0
  3988.2     .05       0  4976.5     .16       0  4976.5     .07       0
  5029.8     .05       0
Bank Sta=4976.5,5029.8
XS Rating Curve= 0 ,0
Exp/Cntr=0.3,0.1

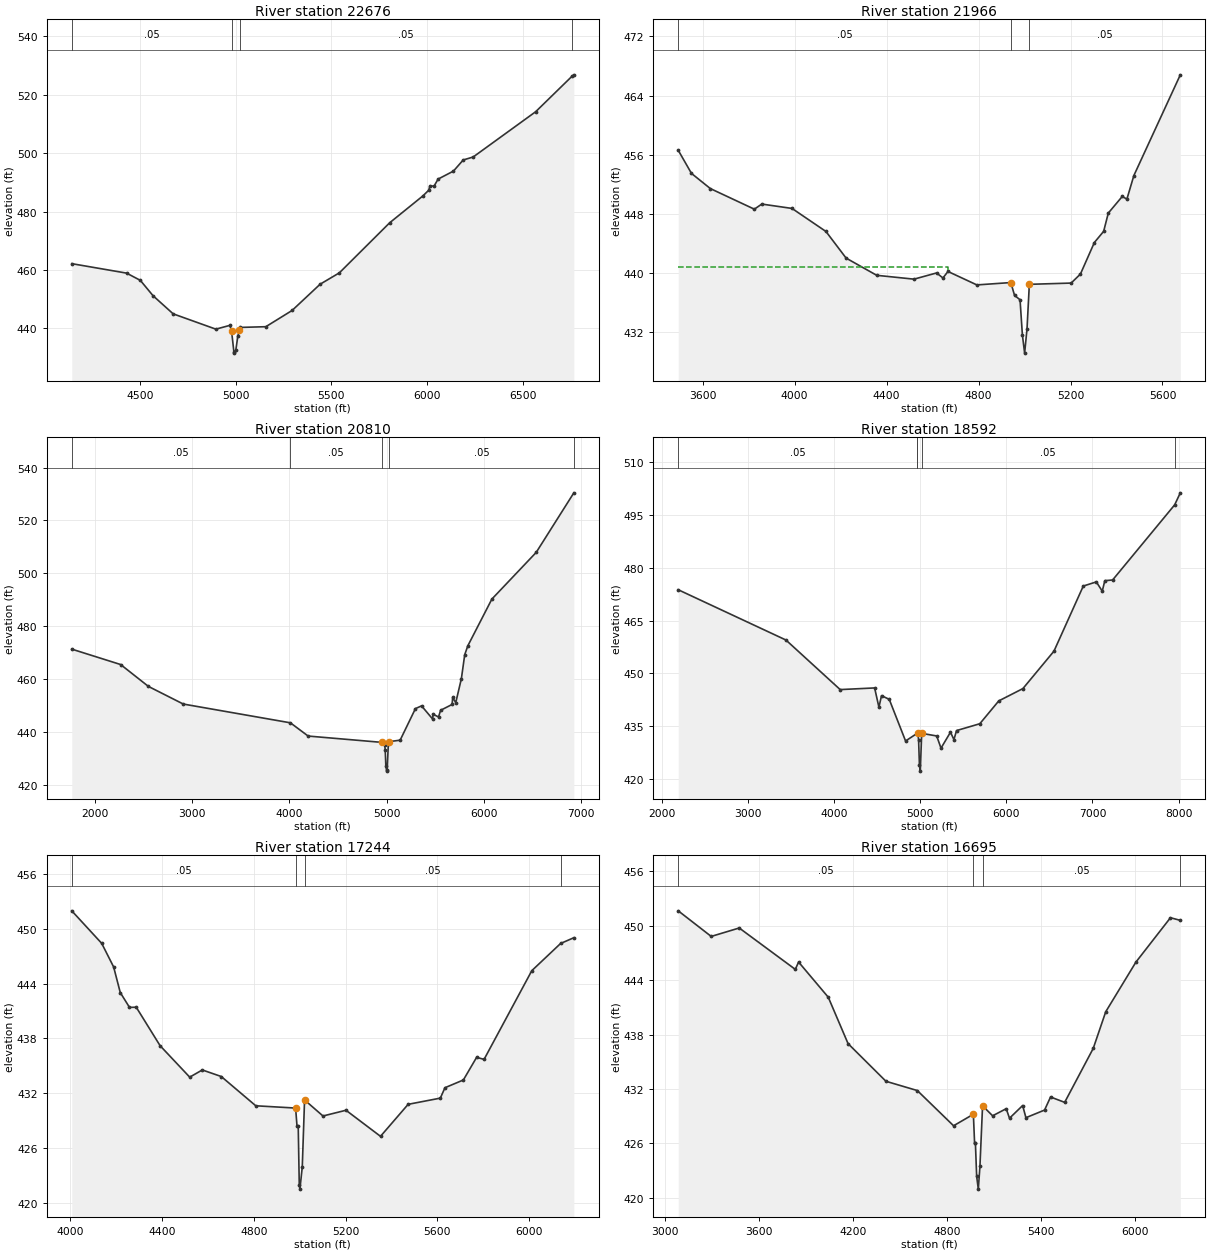
Type RM Length L Ch R = 1 ,22676   ,710,710,710
BEGIN DESCRIPTION:
BARGER BRANCH 23.0
END DESCRIPTION:
XS GIS Cut Line= 3
      3465009.53     10553936.17      3465926.17     10554206.99
      3467348.48     10553332.79
#Sta/Elev= 30
  4142.3  462.19    4429  458.95  4500.8  456.47  4567.4   451.2  4672.5     445
  4895.7  439.76  4968.7  441.05  4977.7  439.23  4989.9  432.05  4992.6  431.55
    5000  432.52  5010.4  437.27    5019  439.52  5020.9  440.35    5157   440.6
  5294.3  446.16  5441.1  455.16  5541.6  459.05  5804.4  476.18  5978.4   485.4
  6008.9  487.35  6015.1  488.86  6036.4  488.71  6057.7  491.15    6138  493.89
  6189.1   497.7  6241.2  498.72  6567.9  514.22  6757.2  526.32  6767.6  526.86
#Mann= 4 ,-1 , 0
  4142.3     .05       0  4977.7     .07       0  5020.9     .05       0
  6757.2     .16       0
Bank Sta=4977.7,5019
XS Rating Curve= 0 ,0
Exp/Cntr=0.3,0.1

Type RM Length L Ch R = 1 ,21966   ,1156,1156,1156
BEGIN DESCRIPTION:
BARGER BRANCH 22.0
END DESCRIPTION:
XS GIS Cut Line= 3
       3464642.1     10553991.64      3465942.11     10554691.64
      3466642.12     10554591.64
#Sta/Elev= 30
  3493.9   456.6  3551.5  453.47  3633.4  451.42  3824.9  448.63  3857.3  449.32
  3988.8  448.73  4136.4  445.61    4224  442.01  4357.1  439.68  4519.3  439.16
  4617.5     440  4645.1  439.32    4667   440.2  4792.7  438.38  4940.4   438.7
  4956.6  436.96  4980.5  436.37  4990.6  431.64  5000.4  429.15  5010.8  432.43
  5020.9  438.46  5202.7  438.63  5243.1  439.85  5303.7  444.12  5344.1  445.63
  5364.3   448.1    5425  450.35  5445.2  449.99  5475.5  453.18  5677.5  466.81
#Mann= 3 ,-1 , 0
  3493.9     .05       0  4940.4     .07       0  5020.9     .05       0
#XS Ineff= 2 , 0
       0    4665  440.76               0
Permanent Ineff=
       T       F
Bank Sta=4940.4,5020.9
XS Rating Curve= 0 ,0
Exp/Cntr=0.3,0.1

Type RM Length L Ch R = 1 ,20810   ,2218,2218,2218
BEGIN DESCRIPTION:
BARGER BRANCH 21.0
END DESCRIPTION:
XS GIS Cut Line= 4
      3463308.09     10556547.28      3465592.84     10555561.16
      3466808.12     10555172.27       3468028.7     10554478.76
#Sta/Elev= 30
  1759.7  471.28  2262.8  465.45  2548.7  457.17  2907.7   450.5  4010.2   443.4
  4192.9  438.39  4948.8  436.01    4981  434.94  4986.2  433.22  4992.9  426.92
  5003.1  425.12  5006.4  425.62  5018.4  435.44  5024.4  436.27  5139.9  436.83
  5297.4  448.78  5360.4  449.81  5473.8  444.86  5479.1  446.65    5535  445.62
  5556.6  448.14  5674.9  450.35  5680.6  452.99  5712.4  451.03  5770.3  460.11
  5804.8  469.18  5836.4  472.52  6084.3  490.22  6540.9   507.9    6928  530.42
#Mann= 5 ,-1 , 0
  1759.7     .05       0  4010.2     .05       0  4948.8     .07       0
  5024.4     .05       0    6928     .05       0
Bank Sta=4948.8,5024.4
XS Rating Curve= 0 ,0
Exp/Cntr=0.3,0.1

Type RM Length L Ch R = 1 ,18592   ,1348,1348,1348
BEGIN DESCRIPTION:
BARGER BRANCH 18.0
END DESCRIPTION:
XS GIS Cut Line= 3
      3463341.18     10556950.92      3465723.12     10556950.92
      3469167.38     10556763.43
#Sta/Elev= 30
  2188.7  473.74  3439.6  459.46  4069.6  445.38  4469.6  445.85  4519.6  440.37
  4549.6  443.66  4639.7   442.6  4829.1  430.78  4960.2   432.9  4970.2  433.17
  4980.2  431.15  4990.2  423.83    5000  422.22  5016.3  432.95  5190.5  432.21
  5240.6  428.75  5350.8  433.28  5390.8  431.17  5420.9  433.74  5691.3  435.68
  5911.6  442.17    6192  445.67  6552.6   456.3  6893.1  474.79  7044.6  475.97
  7113.4  473.34  7143.4  476.32  7233.6  476.51  7954.6  497.86    8020  501.27
#Mann= 5 ,-1 , 0
  2188.7     .05       0  4960.2     .16       0  4960.2     .07       0
  5016.3     .05       0  7954.6     .05       0
Bank Sta=4970.2,5016.3
XS Rating Curve= 0 ,0
Exp/Cntr=0.3,0.1

Type RM Length L Ch R = 1 ,17244   ,549,549,549
BEGIN DESCRIPTION:
BARGER BRANCH 17.0
END DESCRIPTION:
XS GIS Cut Line= 3
      3465242.09     10557591.64      3466142.11     10557991.64
      3467342.15     10558091.65
#Sta/Elev= 30
  4005.7     452  4136.3  448.43  4188.3  445.84  4217.1  443.04  4257.4  441.41
  4286.8  441.43  4390.8  437.21    4520  433.76  4574.8  434.55  4657.5  433.83
    4808  430.62  4981.7  430.37  4987.9  428.35  4993.1  428.35  4997.6  421.98
  5000.4  421.48  5010.7  423.91  5020.7  431.26    5101   429.5  5201.3  430.13
  5351.8  427.27  5472.3  430.78  5612.7  431.46  5632.8   432.6  5713.1  433.45
  5770.8  435.93  5803.4  435.71  6011.6  445.44  6137.1  448.42  6194.8  449.05
#Mann= 4 ,-1 , 0
  4005.7     .05       0  4981.7     .07       0  5020.7     .05       0
  6137.1     .16       0
Bank Sta=4981.7,5020.7
XS Rating Curve= 0 ,0
Exp/Cntr=0.3,0.1

Type RM Length L Ch R = 1 ,16695   ,566,566,566
BEGIN DESCRIPTION:
BARGER BRANCH 16.0
END DESCRIPTION:
XS GIS Cut Line= 3
      3464342.15     10559141.63      3466142.11     10558541.64
      3467392.14     10558141.63
#Sta/Elev= 30
  3082.2  451.63    3293  448.81  3472.2  449.74  3830.6  445.18  3851.6  445.99
  4041.4  442.11  4167.9     437  4410.3  432.85  4610.6  431.83  4842.5  427.95
    4969  429.22  4976.9  426.02  4982.1  426.02    4990  422.39  5000.6  420.97
    5011  423.48  5027.8  430.15  5092.1  429.05    5179  429.83    5200  428.78
    5284  430.18    5305  428.84  5424.1  429.68  5462.5  431.12  5552.7  430.53
  5735.5  436.48  5815.2  440.51  6008.1  445.98    6229  450.87    6292  450.58
#Mann= 4 ,-1 , 0
  3082.2     .05       0    4969     .07       0  5027.8     .05       0
    6292     .16       0
Bank Sta=4969,5027.8
XS Rating Curve= 0 ,0
Exp/Cntr=0.3,0.1

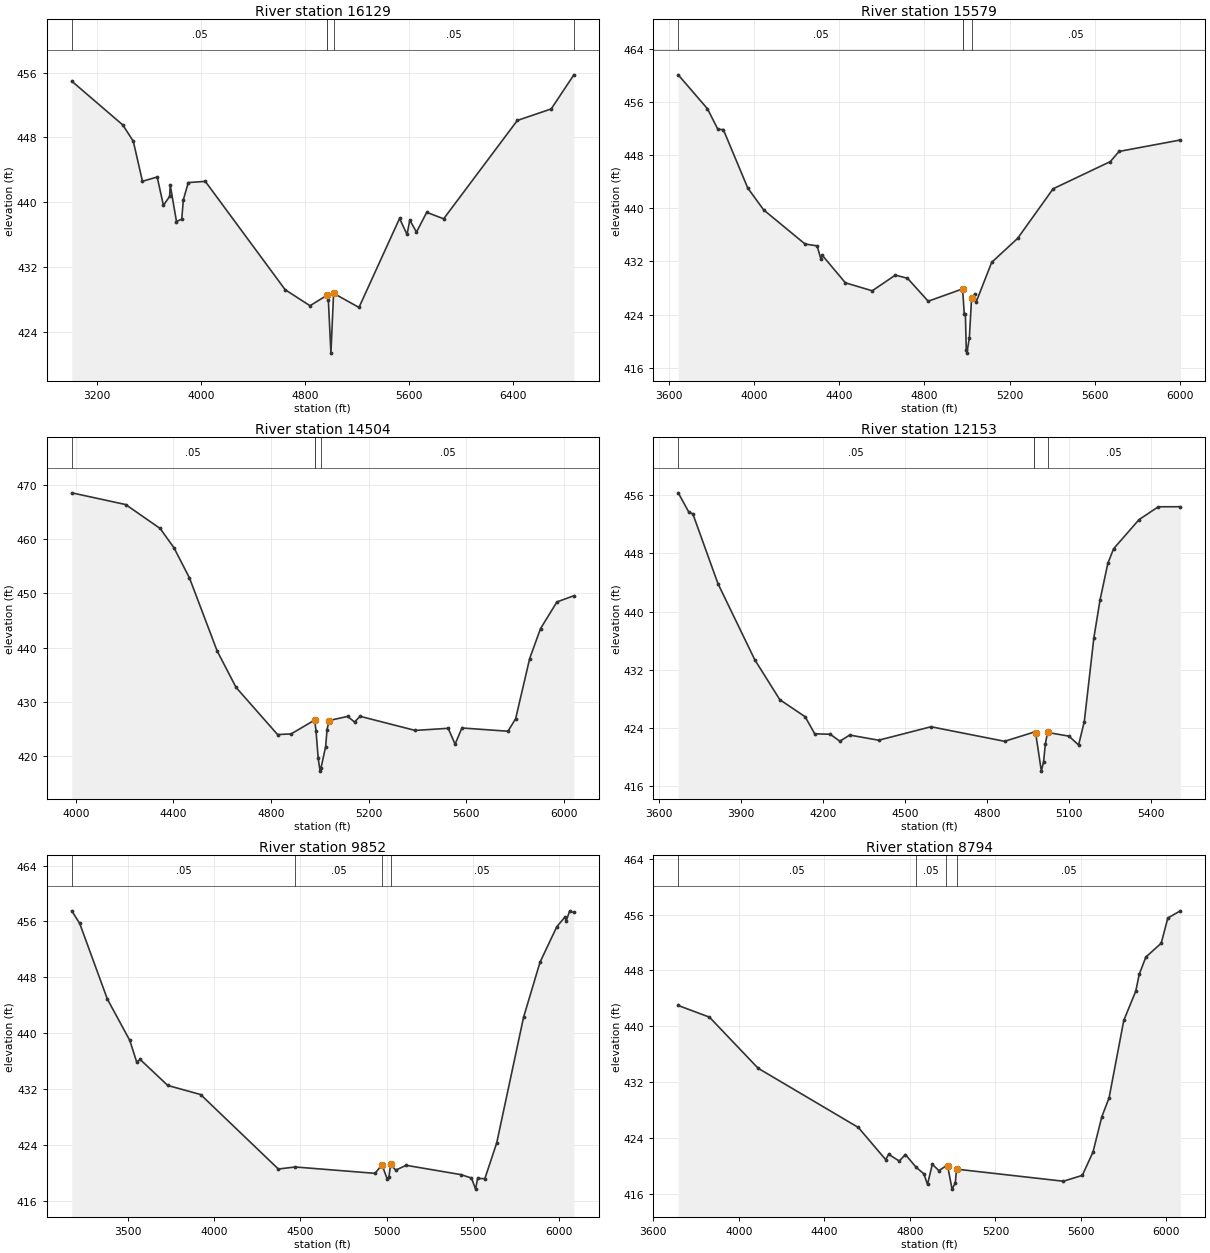
Type RM Length L Ch R = 1 ,16129   ,550,550,550
BEGIN DESCRIPTION:
BARGER BRANCH 15.0
END DESCRIPTION:
XS GIS Cut Line= 3
      3464142.09     10559291.64      3466142.11     10559091.64
      3467692.12     10558091.63
#Sta/Elev= 30
  3009.4  454.94  3401.4  449.53  3481.8  447.52  3552.1  442.58  3665.2  443.11
  3712.9  439.61  3760.6  440.71  3765.7   442.1  3813.4   437.6  3853.6  437.92
  3866.2  440.31  3903.9  442.42  4034.5  442.57  4647.5   429.2  4838.5  427.22
  4971.7  428.54  4979.2  427.95    4999  421.37  5019.4  428.73  5022.4  428.73
  5214.4  427.01  5525.9  437.99  5583.3  436.02  5604.5  437.79  5655.9  436.31
  5734.5  438.75  5864.5  437.95  6430.1  450.09  6690.1  451.51    6864  455.72
#Mann= 5 ,-1 , 0
  3009.4     .05       0  4971.7     .16       0  4971.7     .07       0
  5019.4     .05       0    6864     .16       0
Bank Sta=4971.7,5022.4
XS Rating Curve= 0 ,0
Exp/Cntr=0.3,0.1

Type RM Length L Ch R = 1 ,15579   ,1075,1075,1075
BEGIN DESCRIPTION:
BARGER BRANCH 14.0
END DESCRIPTION:
XS GIS Cut Line= 3
      3464992.12     10559941.64      3466292.11     10559591.64
       3467242.1     10559941.64
#Sta/Elev= 30
  3643.4  460.12  3780.6  455.01  3829.8   451.9  3855.3  451.87    3970  443.07
  4044.7  439.77  4239.2  434.63  4295.8  434.35  4313.9  432.33  4319.1  432.97
  4428.6  428.79  4554.7  427.58  4663.1  429.94  4720.4  429.47  4817.7  426.01
  4979.3  427.87  4987.1  424.13  4992.3  424.13  4996.6  418.69  4999.3  418.19
    5011  420.48  5021.6   426.5  5035.4  427.03    5043  425.89    5116  431.87
  5237.8  435.48  5404.5  442.95  5673.3  447.05  5714.4  448.58  6002.1   450.3
#Mann= 4 ,-1 , 0
  3643.4     .05       0  4979.3     .16       0  4979.3     .07       0
  5021.6     .05       0
Bank Sta=4979.3,5021.6
XS Rating Curve= 0 ,0
Exp/Cntr=0.3,0.1

Type RM Length L Ch R = 1 ,14504   ,2351,2351,2351
BEGIN DESCRIPTION:
BARGER BRANCH 12.0
END DESCRIPTION:
XS GIS Cut Line= 3
      3465389.79     10561131.47      3465987.01     10560575.92
      3467105.05     10560034.26
#Sta/Elev= 30
  3983.3  468.51  4204.4  466.35  4345.6  461.94  4402.3  458.38  4465.8  452.83
  4579.1  439.39  4656.8  432.66  4826.8  423.98  4882.4  424.09  4978.8  426.65
  4984.4   424.7  4993.5  419.57  5001.2  417.24  5004.4  417.74    5024  421.76
  5029.5  424.84    5038  426.56  5114.3  427.32  5142.4  426.29    5165  427.34
  5390.8  424.74  5526.3  425.13  5554.4  422.21  5582.6  425.19  5771.3  424.59
  5802.8  426.91  5860.2  437.97  5904.7   443.5    5972  448.41  6041.3  449.55
#Mann= 4 ,-1 , 0
  3983.3     .05       0  4978.8     .16       0  4978.8     .07       0
  5004.4     .05       0
Bank Sta=4978.8,5038
XS Rating Curve= 0 ,0
Exp/Cntr=0.3,0.1

Type RM Length L Ch R = 1 ,12153   ,2301,2301,2301
BEGIN DESCRIPTION:
BARGER BRANCH 10.0
END DESCRIPTION:
XS GIS Cut Line= 3
      3466348.11     10561582.87      3467153.68     10560846.75
      3467618.01      10560264.6
#Sta/Elev= 30
  3670.7  456.33  3709.8  453.65    3724  453.45  3815.9  443.85  3950.3   433.4
  4042.2  427.89  4134.7  425.55  4169.8   423.2  4226.6  423.14  4261.7  422.18
  4297.5  423.03  4403.6  422.32  4594.8  424.17    4864  422.17  4971.3  423.43
  4977.7  423.29  4998.5  418.07  5006.6  419.36    5013  421.78    5021  423.39
  5099.4  422.88  5134.7  421.66  5155.5  424.89  5190.7  436.44  5213.1  441.61
  5241.8  446.67  5262.8  448.65  5355.7  452.65  5426.1  454.41  5506.6  454.42
#Mann= 4 ,-1 , 0
  3670.7     .05       0  4971.3     .16       0  4971.3     .07       0
    5021     .05       0
Bank Sta=4977.7,5021
XS Rating Curve= 0 ,0
Exp/Cntr=0.3,0.1

Type RM Length L Ch R = 1 ,9852    ,1058,1058,1058
BEGIN DESCRIPTION:
BARGER BRANCH 9.0
END DESCRIPTION:
XS GIS Cut Line= 4
      3466466.16     10561638.42      3468216.18     10561596.75
      3468542.56     10561596.75      3468834.24     10560818.94
#Sta/Elev= 30
    3176  457.52    3222  455.71    3382  444.89    3512  438.97  3552.1  435.87
  3572.1  436.24  3732.1  432.52  3922.2  431.22  4372.3  420.56    4470  420.85
  4932.4  419.94  4972.4  421.17  5002.4  419.15  5012.4  419.37  5022.4  421.21
  5052.4   420.4  5112.4  421.09  5429.2  419.76  5490.8  419.27  5514.4  417.68
  5526.4  419.22  5568.1  419.17  5636.8  424.29  5792.4  442.28  5887.8  450.17
  5984.6  455.23  6033.7  456.68  6039.1  456.06  6058.6  457.44  6083.6   457.3
#Mann= 4 ,-1 , 0
    3176     .05       0    4470     .05       0  4972.4     .07       0
  5022.4     .05       0
Bank Sta=4972.4,5022.4
XS Rating Curve= 0 ,0
Exp/Cntr=0.3,0.1

Type RM Length L Ch R = 1 ,8794    ,369,369,369
BEGIN DESCRIPTION:
BARGER BRANCH 8.0
END DESCRIPTION:
XS GIS Cut Line= 3
      3467966.16     10562971.77      3468702.29     10562089.81
      3468986.58     10560924.89
#Sta/Elev= 30
  3716.8  442.99  3862.7  441.32  4090.5  434.01  4559.1  425.54  4686.6  420.95
  4700.9   421.7  4750.4  420.74    4779  421.67  4829.1  419.85  4865.6  418.91
  4882.5  417.39  4904.9  420.28  4935.8  419.37    4971  420.07  4976.9  419.99
  4997.3  416.72  5012.7  417.63  5018.1  419.58    5518  417.85  5606.5  418.69
  5656.3  422.02  5697.5  427.06  5731.5  429.77  5800.4  440.86  5856.5  445.05
  5872.5  447.44  5903.4  449.91  5975.4   451.9  6006.3   455.5  6064.7  456.53
#Mann= 4 ,-1 , 0
  3716.8     .05       0  4829.1     .05       0    4971     .07       0
  5018.1     .05       0
Bank Sta=4976.9,5018.1
XS Rating Curve= 0 ,0
Exp/Cntr=0.3,0.1