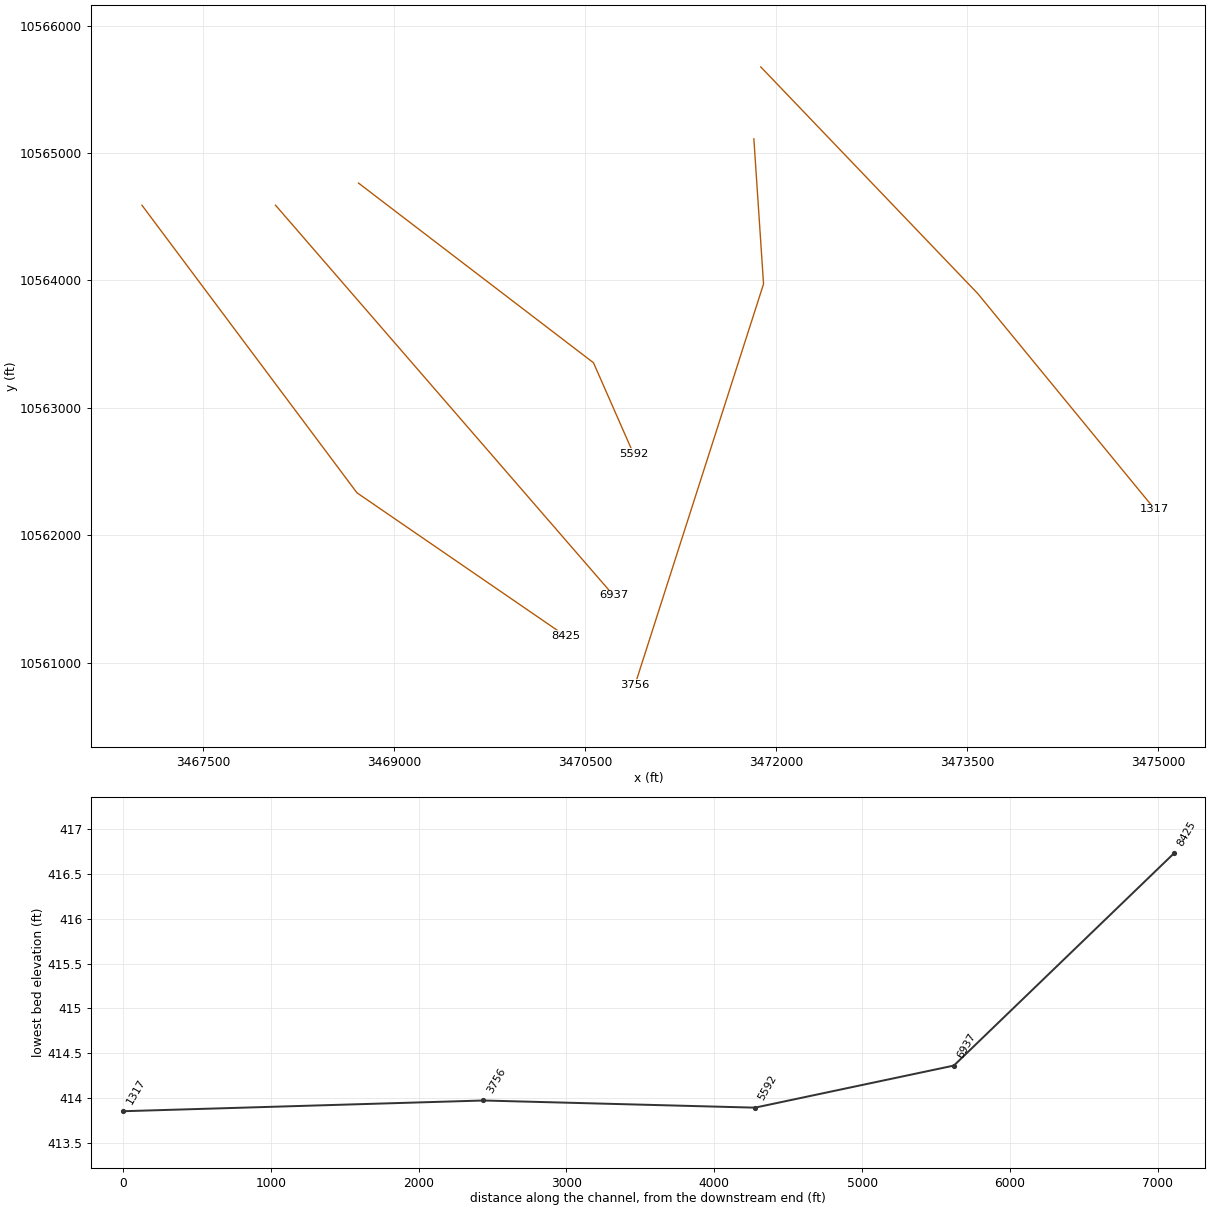
HEC-RAS study BARGER BRANCH.prj: BARGER BRANCH Base Level Engineering

--- BARGER BRANCH.g01 (geometry) --- (continued)

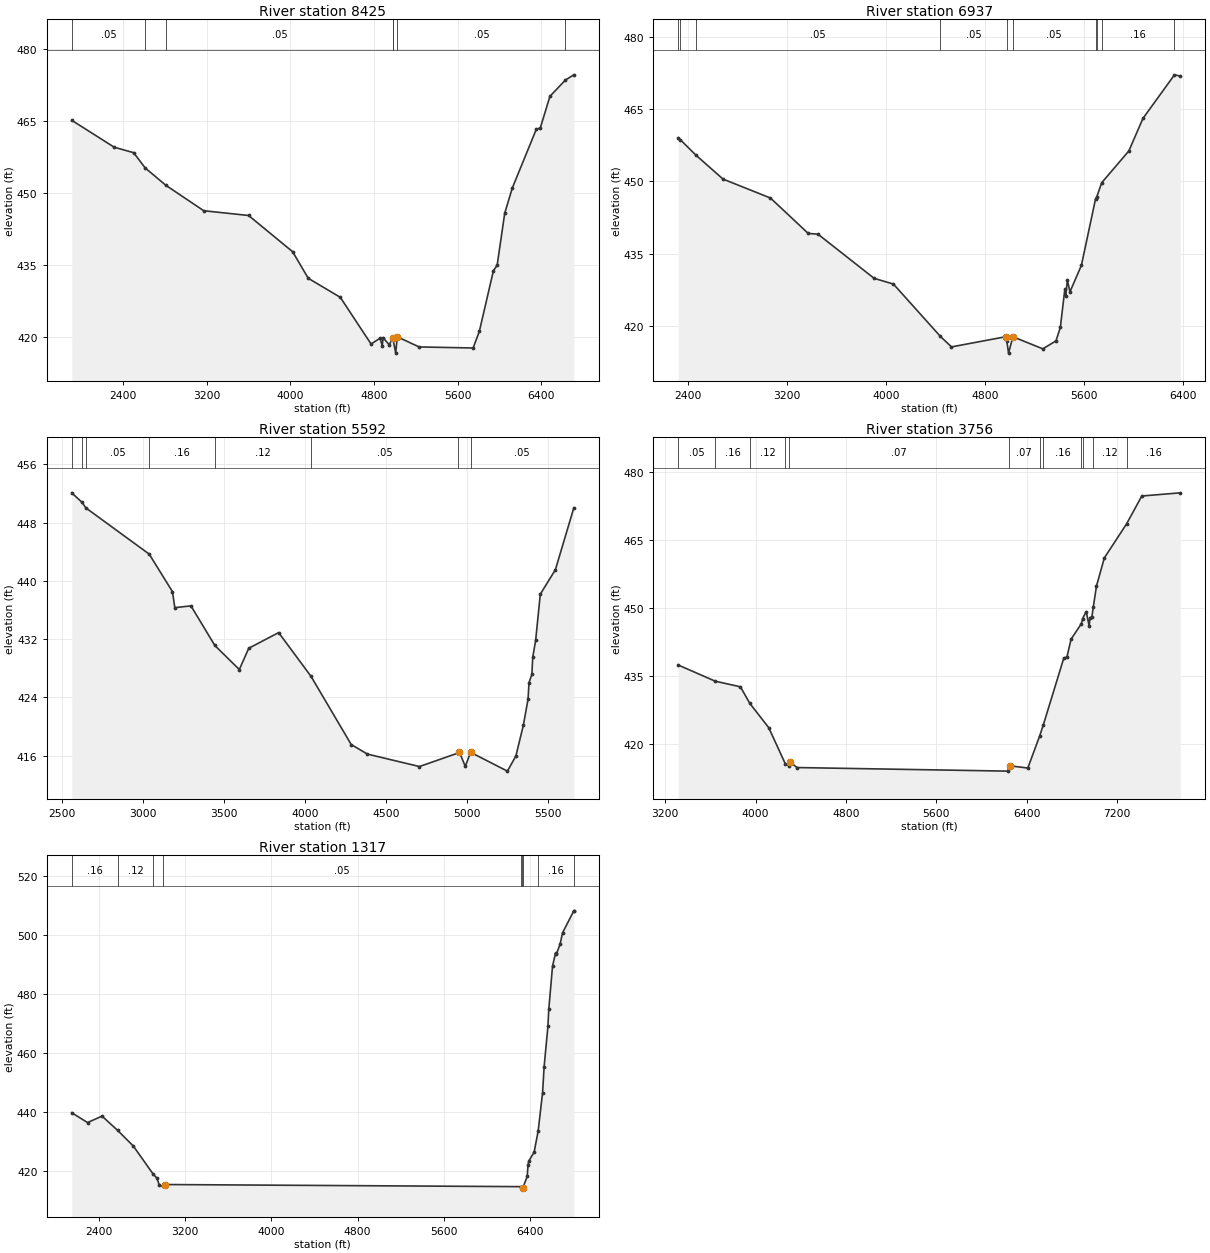
Type RM Length L Ch R = 1 ,8425    ,1488,1488,1488
BEGIN DESCRIPTION:
BARGER BRANCH 7.0
END DESCRIPTION:
XS GIS Cut Line= 3
      3467021.72     10564589.82      3468709.23     10562332.86
       3470347.6     10561208.22
#Sta/Elev= 30
  1908.1  465.21  2314.7   459.6  2500.2  458.47    2611  455.29  2809.1  451.67
  3171.4  446.38  3600.7  445.39  4021.7  437.85  4171.8  432.31  4478.2  428.35
  4772.3  418.64  4858.9  419.83  4879.9  418.23  4887.3  419.97  4945.6  418.47
  4981.4  419.86  5008.4  416.73  5023.4  420.13  5232.5  418.02  5749.5   417.8
  5809.1  421.27  5943.7   433.9  5979.5  435.04  6051.8  445.86  6124.5  451.12
    6355  463.39  6391.4  463.56  6484.4   470.2  6633.5  473.61  6713.4  474.68
#Mann= 7 ,-1 , 0
  1908.1     .05       0    2611     .16       0  2809.1     .05       0
  4981.4     .16       0  4981.4     .07       0  5023.4     .05       0
  6633.5     .16       0
Bank Sta=4981.4,5023.4
XS Rating Curve= 0 ,0
Exp/Cntr=0.3,0.1

Type RM Length L Ch R = 1 ,6937    ,1345,1345,1345
BEGIN DESCRIPTION:
BARGER BRANCH 4.0
END DESCRIPTION:
XS GIS Cut Line= 2
      3468070.33     10564589.82      3470723.12     10561527.31
#Sta/Elev= 30
  2322.9  459.04  2338.9  458.68  2464.4  455.48  2684.4  450.48  3067.2  446.55
  3372.1   439.2  3449.9  439.06  3903.9  429.88  4059.7  428.69  4438.2  417.84
  4527.9  415.65  4966.7  417.77  4974.3  416.95  4988.3  414.36  5023.7  417.76
    5265  415.25  5371.3   416.9  5406.4  419.69  5442.6  427.59  5449.2  426.31
  5463.5  429.47  5484.3  427.09  5576.4  432.58  5690.5  446.36  5698.8  446.67
  5740.1  449.72  5959.2  456.32  6073.2  463.08  6327.5  472.12  6374.6  471.86
#Mann= 10 ,-1 , 0
  2322.9     .05       0  2338.9     .16       0  2464.4     .05       0
  4438.2     .05       0  4974.3     .07       0  5023.7     .05       0
  5690.5     .16       0  5698.8     .12       0  5740.1     .16       0
  6327.5     .05       0
Bank Sta=4966.7,5023.7
XS Rating Curve= 0 ,0
Exp/Cntr=0.3,0.1

Type RM Length L Ch R = 1 ,5592    ,1836,1836,1836
BEGIN DESCRIPTION:
BARGER BRANCH 3.0
END DESCRIPTION:
XS GIS Cut Line= 3
      3468721.37     10564763.86        3470566.     10563353.26
      3470880.67     10562637.12
#Sta/Elev= 30
  2558.2  452.08  2619.8  450.81  2646.1     450    3037  443.67  3180.7  438.52
  3195.3  436.32    3295  436.57  3442.9  431.13  3594.2  427.83  3652.3  430.75
  3837.3   432.9  4036.8  426.92  4286.1  417.54  4385.9  416.23  4707.8  414.52
  4947.7  416.38  4955.4  416.48  4991.4  414.54  5024.1  416.47  5251.8  413.89
  5304.2  415.97  5350.9  420.23  5379.7  423.81  5385.2  426.02  5403.1  427.17
  5408.5  429.52  5426.4  431.82  5455.2  438.17  5548.4  441.52  5662.6  450.03
#Mann= 8 ,-1 , 0
  2558.2     .05       0  2619.8     .12       0  2646.1     .05       0
    3037     .16       0  3442.9     .12       0  4036.8     .05       0
  4947.7     .07       0  5024.1     .05       0
Bank Sta=4955.4,5024.1
XS Rating Curve= 0 ,0
Exp/Cntr=0.3,0.1

Type RM Length L Ch R = 1 ,3756    ,2439,2439,2439
BEGIN DESCRIPTION:
BARGER BRANCH 2.0
END DESCRIPTION:
XS GIS Cut Line= 3
      3471824.68     10565111.12      3471900.64     10563971.75
      3470891.78     10560825.86
#Sta/Elev= 30
  3315.4  437.39  3643.2  433.82  3866.1  432.58  3948.7  428.94  4116.7  423.56
  4263.8  415.57  4297.1   415.2  4307.1  415.94  4367.2  414.76  6231.8  413.97
  6242.7  414.56  6253.2  415.14  6410.7  414.65  6515.7  421.73  6548.4   424.2
  6729.7  438.95  6756.6  439.12    6794  443.11  6885.7  446.54  6895.6  447.63
  6927.7  449.19  6954.6  445.94  6959.8  447.85  6977.8  447.94  6990.1  450.11
  7018.8  454.84  7088.4  461.04  7284.6  468.52  7420.1   474.7    7761   475.4
#Mann= 12 ,-1 , 0
  3315.4     .05       0  3643.2     .16       0  3948.7     .12       0
  4263.8     .07       0  4297.1     .07       0  6242.7     .07       0
  6515.7     .12       0  6548.4     .16       0  6885.7     .12       0
  6895.6     .05       0  6990.1     .12       0  7284.6     .16       0
Bank Sta=4307.1,6253.2
XS Rating Curve= 0 ,0
Exp/Cntr=0.3,0.1

Type RM Length L Ch R = 1 ,1317    ,0,0,0
BEGIN DESCRIPTION:
BARGER BRANCH 1.0
END DESCRIPTION:
XS GIS Cut Line= 3
      3471878.97     10565675.28      3473582.49      10563895.8
      3474971.37     10562203.11
#Sta/Elev= 30
  2150.8  439.74    2297  436.42  2431.6   438.6  2576.2  433.75  2721.5  428.45
  2907.1  418.84  2940.7  417.55  2961.8  415.18  2997.3  414.86  3011.5  415.41
  6314.5  414.69  6325.8  414.35  6328.6  413.85  6331.8  414.35  6371.9  418.16
  6378.8  421.88  6386.2  423.38  6435.8  426.38  6473.4  433.62    6514  446.55
  6528.3  455.33  6563.5  468.98  6571.4  474.76  6606.5  489.52  6635.3     494
  6641.7  493.45  6676.9  496.97  6699.1  500.74  6803.5  508.19  6803.8  508.19
#Mann= 9 ,-1 , 0
  2150.8     .16       0  2576.2     .12       0  2907.1     .16       0
  2997.3     .05       0  6314.5     .07       0  6325.8    .033       0
  6331.8     .07       0  6473.4     .16       0  6803.5     .12       0
Bank Sta=3011.5,6331.8
XS Rating Curve= 0 ,0
Exp/Cntr=0.3,0.1

Chan Stop Cuts=-1
Use User Specified Reach Order=0
Composite Channel Slope=5