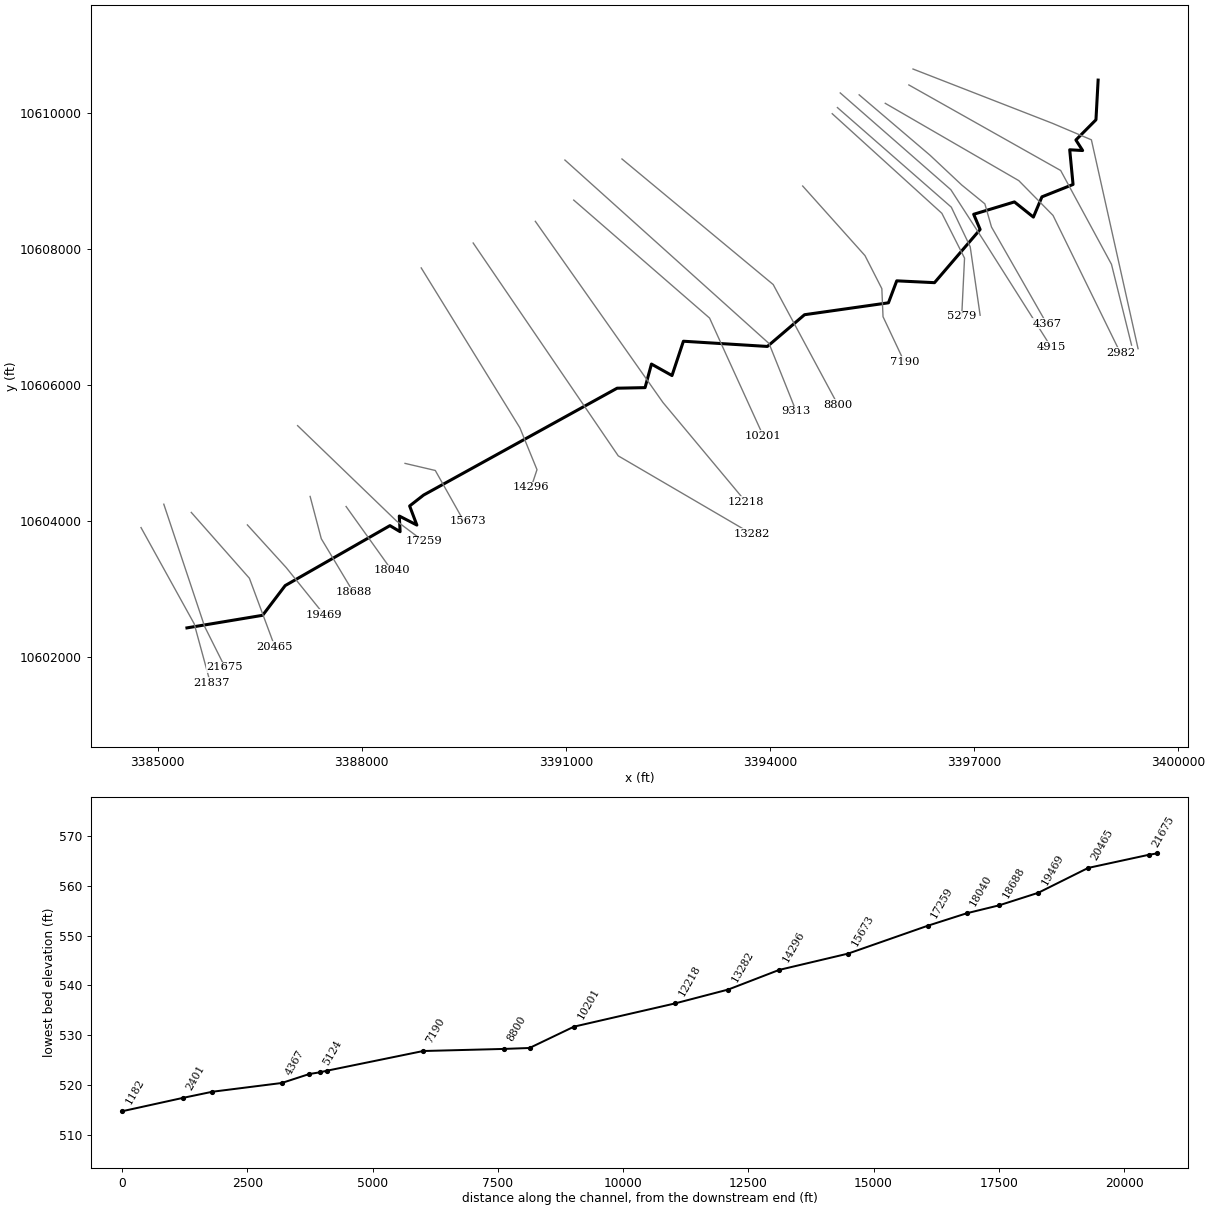
--- BOARD CREEK.prj (project) ---

Proj Title=BOARD CREEK Base Level Engineering
Current Plan=p01
Default Exp/Contr=0.3,0.1
English Units
Geom File=g01
Flow File=f01
Plan File=p01
Y Axis Title=Elevation
X Axis Title(PF)=Main Channel Distance
X Axis Title(XS)=Station
BEGIN DESCRIPTION:
BOARD CREEK
END DESCRIPTION:
DSS Export Rating Curves= 0
DSS Export Rating Curve Sorted= 0
DSS Export Volume Flow Curves= 0
DXF OffsetX= 0
DXF OffsetY= 0
DXF ScaleX= 1
DXF ScaleY= 10

--- BOARD CREEK.p01 (plan) ---

Plan Title=Multiple Run
Short Identifier=Multiple
Geom File=g01
Flow File=f01
Subcritical Flow
K Sum by GR= 0
Std Step Tol= 0.01
Critical Tol= 0.01
Num of Std Step Trials= 20
Max Error Tol= 0.3
Flow Tol Ratio= 0.001
Split Flow NTrial= 30
Split Flow Tol= 0.02
Split Flow Ratio= 0.02
Log Output Level= 0
Friction Slope Method= 1
Unsteady Friction Slope Method= 2
Unsteady Bridges Friction Slope Method= 1
Parabolic Critical Depth
Global Vel Dist=  1 , 1 , 1
Global Log Level= 0
CheckData=True
Encroach Param= -1, 0, 0, 0
BEGIN DESCRIPTION:
Multiple Run
END DESCRIPTION:

--- BOARD CREEK.f01 (steady flow) ---

Flow Title=Multiple
Program Version=4.10
Number of Profiles= 7
Profile Names=10-year,25-year,50-year,1pct_min,100-year,1pct_plu,500-year
River Rch & RM=BOARD CREEK,Reach-1         ,21837
     509     653     761     646     873    1181    1147
River Rch & RM=BOARD CREEK,Reach-1         ,20465
     524     671     781     662     895    1210    1172
River Rch & RM=BOARD CREEK,Reach-1         ,17259
     678     879    1032     880    1190    1610    1583
River Rch & RM=BOARD CREEK,Reach-1         ,14296
     721     936    1100     938    1269    1716    1687
River Rch & RM=BOARD CREEK,Reach-1         ,12218
    1300    1726    2057    1777    2403    3250    3278
River Rch & RM=BOARD CREEK,Reach-1         ,4915
    1420    1888    2254    1949    2636    3565    3603
Boundary for River Rch & Prof#=BOARD CREEK,Reach-1         , 1
Up Type= 0
Dn Type= 3
Dn Slope=0.003
Boundary for River Rch & Prof#=BOARD CREEK,Reach-1         , 2
Up Type= 0
Dn Type= 3
Dn Slope=0.003
Boundary for River Rch & Prof#=BOARD CREEK,Reach-1         , 3
Up Type= 0
Dn Type= 3
Dn Slope=0.003
Boundary for River Rch & Prof#=BOARD CREEK,Reach-1         , 4
Up Type= 0
Dn Type= 3
Dn Slope=0.003
Boundary for River Rch & Prof#=BOARD CREEK,Reach-1         , 5
Up Type= 0
Dn Type= 3
Dn Slope=0.003
Boundary for River Rch & Prof#=BOARD CREEK,Reach-1         , 6
Up Type= 0
Dn Type= 3
Dn Slope=0.003
Boundary for River Rch & Prof#=BOARD CREEK,Reach-1         , 7
Up Type= 0
Dn Type= 3
Dn Slope=0.003
DSS Import GetInterval= 0
DSS Import GetPeak= 0
DSS Import FillOption= 0

--- BOARD CREEK.g01 (geometry) ---

Geom Title=Existing Conditions
Program Version=4.10

River Reach=BOARD CREEK     ,Reach-1
Reach XY= 30
      3385432.24     10602421.66      3386544.65     10602606.92
       3386875.7     10603043.96      3388415.31     10603926.26
      3388564.79     10603836.99      3388552.65     10604067.51
       3388810.8     10603934.63      3388704.64     10604215.51
      3388909.78      10604376.1      3391753.48     10605948.33
      3392164.55     10605956.85      3392258.23     10606303.58
      3392560.17     10606134.47      3392727.79     10606639.52
      3393961.82     10606562.62      3394507.76     10607029.64
      3395740.97     10607204.86      3395862.81     10607528.07
      3396417.59     10607501.18      3397088.08     10608283.71
      3396993.53     10608507.41      3397592.01     10608689.29
      3397870.73     10608465.97      3397996.43     10608763.89
      3398453.66     10608946.06      3398404.68      10609456.4
      3398594.63     10609445.45      3398495.42     10609600.37
      3398790.22     10609897.66      3398822.11     10610481.64

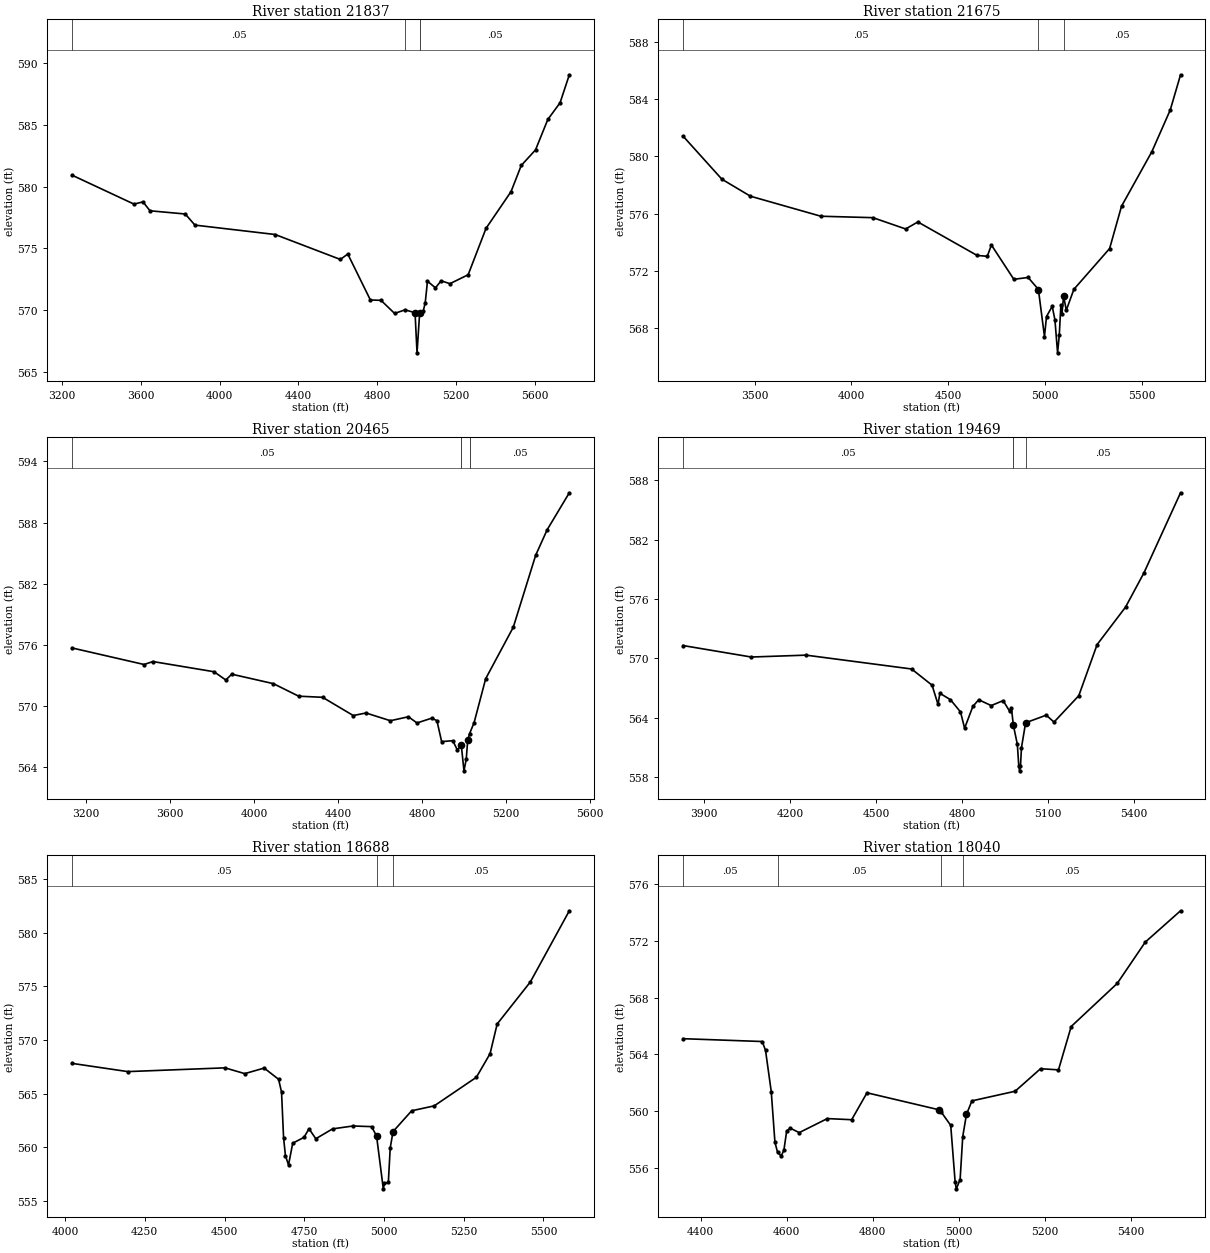
Type RM Length L Ch R = 1 ,21837   ,162,162,162
BEGIN DESCRIPTION:
BOARD CREEK 26.1
END DESCRIPTION:
XS GIS Cut Line= 4
      3384757.35     10603897.56      3385538.61     10602482.62
      3385772.98     10601623.25      3385788.76     10601615.36
#Sta/Elev= 30
  3250.1  580.93  3565.5  578.58    3611  578.76  3646.8  578.04  3825.6  577.78
  3874.8  576.88  4281.6  576.12  4612.8   574.1  4650.5  574.54  4765.1  570.82
    4819  570.79  4888.1  569.73  4940.9  570.02  4991.8  569.79  5001.9  566.54
  5015.2  569.78  5033.3  569.91  5043.6  570.61  5054.9  572.34  5095.4   571.8
    5124  572.37    5169  572.14  5261.3  572.86  5352.1  576.62    5479  579.59
  5530.8  581.71  5603.3  582.97  5665.5  585.43  5727.7  586.78  5774.8  589.05
#Mann= 4 ,-1 , 0
  3250.1     .05       0  4940.9     .07       0  5015.2     .03       0
  5015.2     .05       0
Bank Sta=4991.8,5015.2
XS Rating Curve= 0 ,0
Exp/Cntr=0.3,0.1

Type RM Length L Ch R = 1 ,21675   ,1210,1210,1210
BEGIN DESCRIPTION:
BOARD CREEK 26.0
END DESCRIPTION:
XS GIS Cut Line= 3
      3385092.11     10604241.63      3385692.11     10602441.64
      3385992.12     10601841.62
#Sta/Elev= 30
  3131.2  581.41  3331.5   578.4    3479  577.21  3842.7  575.81  4111.5  575.71
  4280.1  574.92  4343.4  575.41  4649.1  573.07  4701.8  573.01  4722.9   573.8
  4838.8   571.4  4912.6  571.53  4965.3   570.7  4965.9  570.66  4996.9   567.4
  5007.5   568.8  5036.9  569.51  5050.9  568.57  5064.6  566.26  5073.3  567.48
  5081.7  569.62  5087.3     569  5095.6  570.23  5109.6  569.24  5148.7   570.7
  5333.2  573.55  5394.7  576.51  5551.2  580.32  5646.3  583.24  5699.4   585.7
#Mann= 3 ,-1 , 0
  3131.2     .05       0  4965.3     .07       0  5095.6     .05       0
Bank Sta=4965.9,5095.6
XS Rating Curve= 0 ,0
Exp/Cntr=0.3,0.1

Type RM Length L Ch R = 1 ,20465   ,996,996,996
BEGIN DESCRIPTION:
BOARD CREEK 24.0
END DESCRIPTION:
XS GIS Cut Line= 3
      3385495.87     10604120.62      3386350.01      10603151.9
      3386725.03     10602141.44
#Sta/Elev= 30
  3132.5  575.69  3476.6  574.06  3518.4  574.35  3809.6  573.35  3865.6  572.54
  3894.1  573.11  4092.3  572.18  4212.8  570.95  4326.6  570.84  4472.7  569.05
  4533.4   569.3  4649.6  568.54  4735.4  568.93  4776.3  568.32  4846.2  568.79
  4871.2  568.55  4893.6  566.49  4946.9  566.58  4968.3  565.67  4987.4  566.13
    5000  563.62  5010.9  564.77  5017.7   566.6  5026.7  567.27  5048.1  568.34
  5103.5  572.67  5234.9  577.72  5341.6  584.79  5396.5   587.3  5501.8  590.92
#Mann= 5 ,-1 , 0
  3132.5     .05       0  4987.4     .16       0  4987.4     .07       0
  5026.7     .16       0  5026.7     .05       0
Bank Sta=4987.4,5017.7
XS Rating Curve= 0 ,0
Exp/Cntr=0.3,0.1

Type RM Length L Ch R = 1 ,19469   ,781,781,781
BEGIN DESCRIPTION:
BOARD CREEK 22.0
END DESCRIPTION:
XS GIS Cut Line= 3
      3386320.52      10603936.6      3386890.81     10603309.02
      3387447.44     10602617.13
#Sta/Elev= 30
  3826.4  571.29  4064.4  570.13  4255.6  570.32  4623.9  568.92  4695.3  567.28
  4716.1  565.34  4722.6  566.46  4759.3  565.82  4794.5  564.58  4808.9  562.93
  4837.7  565.14  4858.1  565.81  4901.7  565.22  4943.3  565.72  4965.7  564.66
  4972.1  564.98  4979.1  563.22  4992.9   561.3  4997.9  559.12  5000.7  558.62
  5003.9  559.12  5007.3  560.96  5021.7  563.48  5093.7  564.25  5120.9  563.55
  5207.3  566.22  5271.3  571.39  5370.5  575.18  5434.5  578.63  5562.4  586.74
#Mann= 4 ,-1 , 0
  3826.4     .05       0  4979.1     .16       0  4979.1     .07       0
  5021.7     .05       0
Bank Sta=4979.1,5021.7
XS Rating Curve= 0 ,0
Exp/Cntr=0.3,0.1

Type RM Length L Ch R = 1 ,18688   ,648,648,648
BEGIN DESCRIPTION:
BOARD CREEK 20.0
END DESCRIPTION:
XS GIS Cut Line= 3
      3387242.37     10604355.89      3387406.43      10603733.5
      3387877.46      10602947.6
#Sta/Elev= 30
  4021.3  567.82  4196.6  567.05  4501.4   567.4  4563.5  566.86  4624.3  567.38
  4669.6  566.33  4678.8  565.13  4685.2  560.87    4691   559.2  4700.7  558.33
  4713.8  560.36  4749.3  560.91  4764.9  561.71  4786.3  560.78  4838.8   561.7
  4902.9  561.97  4961.2  561.91  4976.8  561.03  4997.9   556.1  5001.2   556.6
  5013.7   556.7  5019.6  559.93  5028.5  561.45  5086.8  563.39  5157.6  563.85
  5289.8  566.52  5332.6  568.72    5355   571.5  5458.9  575.42  5581.2  582.07
#Mann= 3 , 0 , 0
  4021.3     .05       0  4976.8     .07       0  5028.5     .05       0
Bank Sta=4976.8,5028.5
XS Rating Curve= 0 ,0
Exp/Cntr=0.3,0.1

Type RM Length L Ch R = 1 ,18040   ,781,781,781
BEGIN DESCRIPTION:
BOARD CREEK 19.0
END DESCRIPTION:
XS GIS Cut Line= 2
      3387771.02     10604207.46      3388442.88     10603267.37
#Sta/Elev= 30
  4359.4   565.1  4543.3   564.9  4550.9  564.28  4564.2  561.37  4572.8  557.78
    4579  557.07  4587.6  556.82  4593.7  557.25  4600.1  558.59  4608.4  558.78
  4629.3  558.47  4694.5  559.46    4751  559.38  4786.6  561.28 4952.71  560.09
  4958.6  559.94  4981.1  558.98  4991.3     555    4994   554.5  5002.9  555.15
    5009  558.19  5017.6  559.75  5030.3  560.71  5130.7  561.39  5189.7  562.98
  5231.4   562.9  5260.9  565.96  5367.8     569    5433  571.92  5514.9  574.13
#Mann= 4 ,-1 , 0
  4359.4     .05       0    4579     .05       0  4958.6     .07       0
    5009     .05       0
Bank Sta=4952.71,5017.6
XS Rating Curve= 0 ,0
Exp/Cntr=0.3,0.1

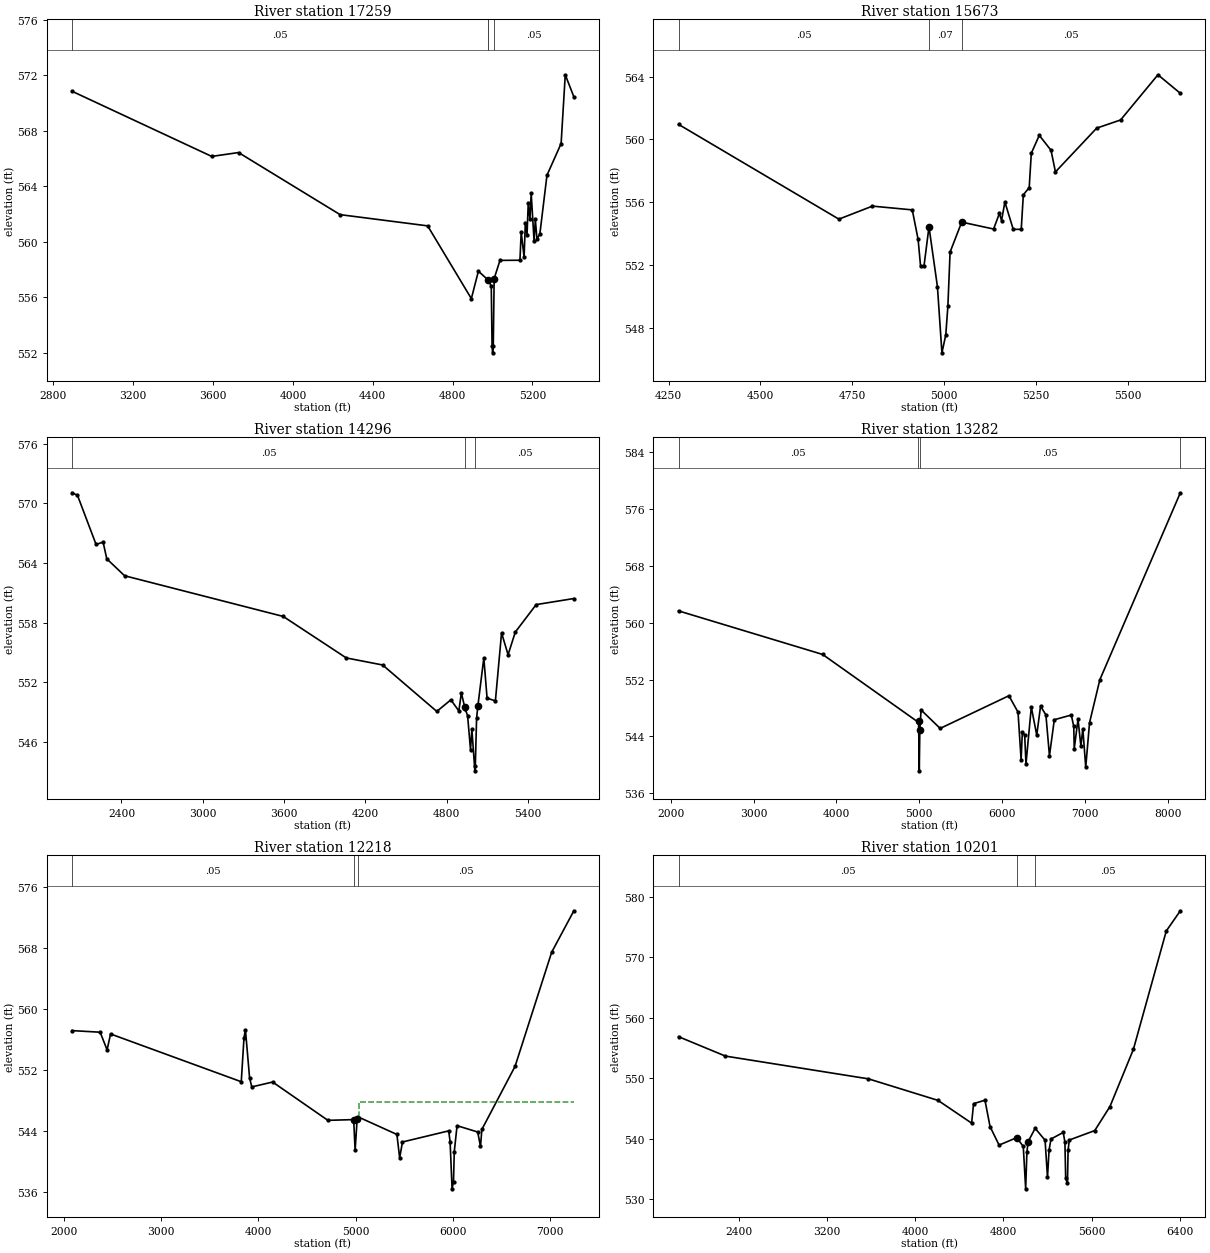
Type RM Length L Ch R = 1 ,17259   ,1586,1586,1586
BEGIN DESCRIPTION:
BOARD CREEK 18.0
END DESCRIPTION:
XS GIS Cut Line= 3
      3387058.26     10605397.37      3388508.25     10603997.37
      3388907.65     10603697.82
#Sta/Elev= 30
  2893.1  570.85  3593.1  566.15  3727.3  566.43  4236.4  561.95  4675.1  561.14
  4894.2  555.89  4929.4  557.87  4979.4  557.22    4994  556.79    4998  552.48
  5000.7  551.98    5004  552.48  5008.5  557.34  5037.7  558.65  5137.7  558.66
    5144  560.69  5158.5  558.88  5164.8  561.38  5173.1  560.48  5179.4   562.8
  5187.7  561.61    5194  563.48  5208.5  560.06  5214.8   561.6  5223.1  560.17
  5237.7  560.58  5273.1  564.79    5344  567.08  5364.8  572.04  5407.9  570.45
#Mann= 4 ,-1 , 0
  2893.1     .05       0  4979.4     .16       0  4979.4     .07       0
  5008.5     .05       0
Bank Sta=4979.4,5008.5
XS Rating Curve= 0 ,0
Exp/Cntr=0.3,0.1

Type RM Length L Ch R = 1 ,15673   ,1377,1377,1377
BEGIN DESCRIPTION:
BOARD CREEK 16.0
END DESCRIPTION:
XS GIS Cut Line= 4
      3388637.36       10604842.      3389081.78     10604737.84
       3389491.5     10604008.67      3389560.98     10603987.83
#Sta/Elev= 30
  4277.2  560.95  4713.5  554.91  4804.8  555.74  4913.2   555.5  4929.1  553.62
  4935.8  551.91  4945.1  551.92  4958.7  554.42  4981.7   550.6  4993.9  546.39
  5004.4  547.54  5010.1  549.36  5016.1  552.81  5047.7  554.72  5134.5  554.28
  5150.4  555.28  5156.1  554.82  5165.2     556    5188  554.26  5209.7  554.26
  5215.4  556.46  5231.4  556.92  5237.1  559.11  5258.8  560.25  5290.7   559.3
  5302.8  557.92    5415  560.71    5480  561.23  5581.7  564.11  5642.6  562.93
#Mann= 3 , 0 , 0
  4277.2     .05       0  4958.7     .07       0  5047.7     .05       0
Bank Sta=4958.7,5047.7
XS Rating Curve= 0 ,0
Exp/Cntr=0.3,0.1

Type RM Length L Ch R = 1 ,14296   ,1014,1014,1014
BEGIN DESCRIPTION:
BOARD CREEK 15.0
END DESCRIPTION:
XS GIS Cut Line= 4
      3388874.88     10607718.36      3390324.52     10605365.96
      3390576.25     10604749.64      3390489.46     10604489.27
#Sta/Elev= 30
  2035.3  571.06  2075.1  570.81  2212.3  565.87  2264.4   566.1  2291.5  564.42
  2422.9  562.72  3593.7  558.63  4058.9  554.46  4327.4  553.75  4727.2  549.08
    4831  550.25  4889.8  549.13  4908.5  550.94  4932.5  549.54  4937.9  549.28
  4954.4  548.66    4976  545.23  4985.9  547.29  5008.1  543.11  5011.4  543.61
  5020.8  548.41    5030   549.6  5074.2  554.46  5098.2  550.42  5159.6  550.14
  5205.1  556.98  5253.2  554.78  5306.6  557.06  5460.5  559.82  5738.7  560.43
#Mann= 3 ,-1 , 0
  2035.3     .05       0  4937.9     .07       0  5011.4     .05       0
#XS Ineff= 2 , 0
       0                 5088.29       0  550.79
Permanent Ineff=
       F       T
Bank Sta=4932.5,5030
XS Rating Curve= 0 ,0
Exp/Cntr=0.3,0.1

Type RM Length L Ch R = 1 ,13282   ,1064,1064,1064
BEGIN DESCRIPTION:
BOARD CREEK 13.9
END DESCRIPTION:
XS GIS Cut Line= 3
      3389638.46     10608084.71      3391770.43     10604952.74
      3393727.94     10603807.39
#Sta/Elev= 30
  2094.1  561.64  3833.5  555.52  4985.7  546.02  4991.7  546.14  4999.8  539.17
  5006.6  544.97  5021.6  547.72    5252  545.13  6081.7  549.72  6191.9  547.41
    6229  540.72  6243.9   544.6    6272  544.22  6287.7  540.14  6352.2  548.12
  6417.7  544.19  6463.7  548.25  6528.2  547.03  6571.2  541.29  6629.8  546.35
  6834.8  547.01  6864.5  545.41  6870.3  542.28  6915.9  546.43  6950.7  542.63
  6973.9  545.09  7009.1  539.67    7055  545.93  7179.3  551.97  8150.8  578.23
#Mann= 4 ,-1 , 0
  2094.1     .05       0  4985.7     .07       0  5006.6     .05       0
  8150.8     .05       0
#XS Ineff= 2 , 0
       0                 6096.59       0  549.34
Permanent Ineff=
       F       T
Bank Sta=4991.7,5006.6
XS Rating Curve= 0 ,0
Exp/Cntr=0.3,0.1

Type RM Length L Ch R = 1 ,12218   ,2017,2017,2017
BEGIN DESCRIPTION:
BOARD CREEK 13.0
END DESCRIPTION:
XS GIS Cut Line= 3
      3390551.88     10608403.66      3392426.87     10605738.74
      3393642.18     10604280.37
#Sta/Elev= 30
  2085.9  557.14  2374.4  556.93  2445.8  554.61  2481.5   556.7  3824.6  550.43
  3852.7  556.19  3867.5  557.26  3910.2  550.93  3932.8  549.75  4147.1  550.39
  4715.1  545.36  4979.9  545.46  4994.7  541.41  5015.7  545.54  5022.9  545.83
    5424  543.51  5452.6  540.43  5481.3  542.52  5956.4  543.98  5970.7  542.58
  5991.3  536.37  6005.8  537.33  6013.7  541.23  6042.3  544.66  6254.5  543.83
  6283.1  541.93  6297.4  544.17  6638.5  552.45  7014.7  567.43  7242.7  572.87
#Mann= 3 ,-1 , 0
  2085.9     .05       0  4979.9     .07       0  5022.9     .05       0
#XS Ineff= 2 , 0
       0                 5037.08       0  547.71
Permanent Ineff=
       F       T
Bank Sta=4979.9,5015.7
XS Rating Curve= 0 ,0
Exp/Cntr=0.3,0.1

Type RM Length L Ch R = 1 ,10201   ,888,888,888
BEGIN DESCRIPTION:
BOARD CREEK 12.0
END DESCRIPTION:
XS GIS Cut Line= 4
      3391116.09     10608716.19      3393112.64     10606980.06
      3393364.37      10606424.5      3393901.95      10605245.3
#Sta/Elev= 30
  1853.6  556.85  2279.3  553.64  3576.4  549.88  4207.2  546.32  4512.2  542.56
  4529.8  545.78  4633.2  546.35  4679.3  541.99  4761.2  538.93  4921.2  540.16
  4980.7  538.71  5002.4   531.7  5013.6  537.78  5024.7   539.5  5088.4   541.7
  5178.4  539.74  5200.4  533.61  5214.6   538.1  5232.2  539.94  5343.3  541.02
  5358.4  539.41  5365.3  533.43  5381.4   532.6  5387.2  538.07  5398.2  539.77
    5629  541.33  5766.6  545.29  5979.5  554.75    6278  574.32  6405.3  577.66
#Mann= 3 ,-1 , 0
  1853.6     .05       0  4921.2     .07       0  5088.4     .05       0
#XS Ineff= 2 , 0
       0                 5087.44       0  541.42
Permanent Ineff=
       T       T
Bank Sta=4921.2,5024.7
XS Rating Curve= 0 ,0
Exp/Cntr=0.3,0.1

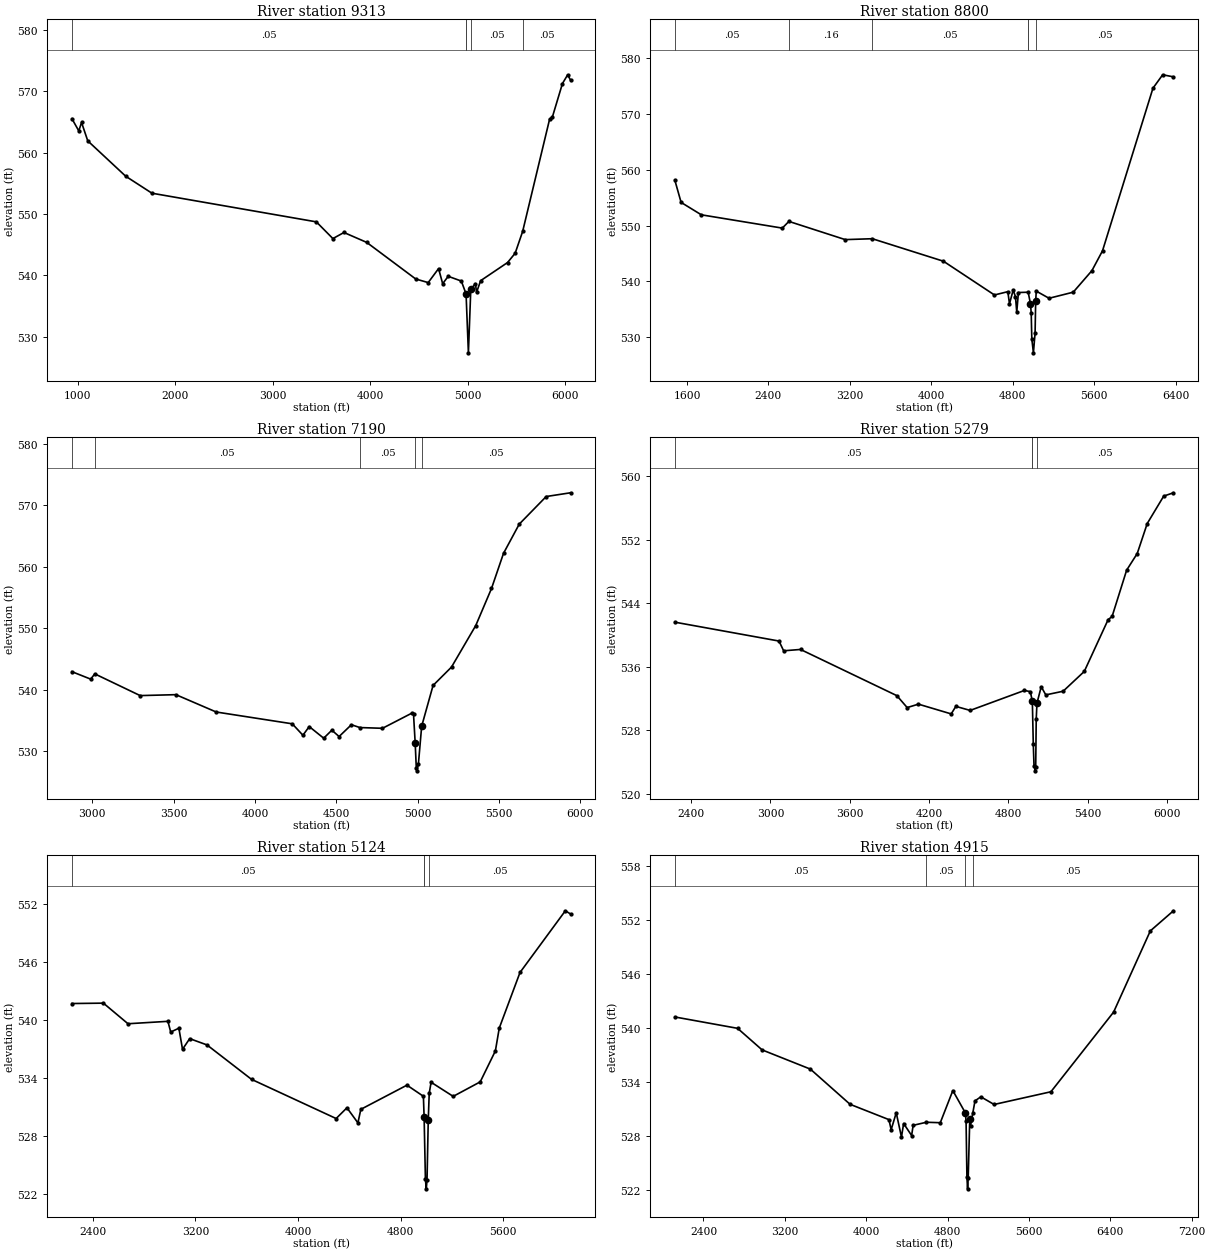
Type RM Length L Ch R = 1 ,9313    ,513,513,513
BEGIN DESCRIPTION:
BOARD CREEK 11.0
END DESCRIPTION:
XS GIS Cut Line= 3
      3390986.57     10609305.51      3393986.55     10606605.53
      3394386.33     10605606.08
#Sta/Elev= 30
   940.8  565.51  1011.3  563.52  1039.7  564.89  1103.3   561.9  1492.7  556.14
  1761.7  553.38  3447.2  548.72  3616.8     546  3730.4  546.99  3963.6  545.38
  4466.7  539.42  4594.2  538.84  4700.6  541.12  4742.5  538.66  4799.3  539.86
  4933.8  539.09  4982.4     537  5006.4  527.41  5030.9  537.73    5078  538.67
  5090.1  537.26  5131.8  539.15  5407.8   542.1  5485.9  543.62  5562.6  547.16
  5838.6   565.4  5868.3  565.82  5970.6  571.22  6024.4  572.65  6053.3  571.78
#Mann= 5 ,-1 , 0
   940.8     .05       0  4982.4     .16       0  4982.4     .07       0
  5030.9     .05       0  5562.6     .05       0
Bank Sta=4982.4,5030.9
XS Rating Curve= 0 ,0
Exp/Cntr=0.3,0.1

Type RM Length L Ch R = 1 ,8800    ,1610,1610,1610
BEGIN DESCRIPTION:
BOARD CREEK 10.0
END DESCRIPTION:
XS GIS Cut Line= 3
      3391824.87     10609321.14      3394047.06     10607473.95
      3394997.79     10605704.35
#Sta/Elev= 30
  1480.7  558.12  1542.1  554.15  1740.9  551.93  2536.4  549.55  2601.1  550.75
  3154.6  547.49  3420.5  547.65  4119.6  543.62  4620.5  537.58    4752  538.17
  4768.3     536  4804.4  538.45  4827.1  537.28  4839.7   534.5    4856  538.02
  4951.9  538.07  4974.6     536  4981.8  534.34  4987.5  529.76  5003.4  527.22
  5019.9   530.8  5025.6   536.5  5031.4  538.27  5157.1  536.99  5394.7  538.08
  5578.4  541.94  5682.3  545.49  6177.9   574.6  6273.3     577  6379.2  576.63
#Mann= 6 ,-1 , 0
  1480.7     .05       0  2601.1     .16       0  3420.5     .05       0
  4951.9     .16       0  4951.9     .07       0  5031.4     .05       0
Bank Sta=4974.6,5025.6
XS Rating Curve= 0 ,0
Exp/Cntr=0.3,0.1

Type RM Length L Ch R = 1 ,7190    ,1911,1911,1911
BEGIN DESCRIPTION:
BOARD CREEK 8.0
END DESCRIPTION:
XS GIS Cut Line= 5
      3394480.68     10608923.14      3395396.45     10607898.86
      3395643.85     10607412.75      3395661.21     10607000.43
      3395973.66     10606336.47
#Sta/Elev= 30
  2874.3  542.93  2989.6  541.72  3015.1  542.57  3293.9  539.04  3513.8  539.19
  3761.6  536.37  4229.3  534.45  4294.7  532.59  4333.6     534  4422.6  532.11
  4472.7  533.41  4517.2  532.38    4593   534.3    4645  533.84  4784.1  533.72
    4965  536.19    4975  535.98    4985  531.38    4992   527.3  4994.7   526.8
    5005  527.93    5025  534.05  5095.1  540.69  5208.5  543.68  5357.7  550.44
  5454.4  556.46  5528.3  562.18    5625  566.93  5790.8  571.42  5940.2  572.03
#Mann= 5 ,-1 , 0
  2874.3     .16       0  3015.1     .05       0    4645     .05       0
    4985     .07       0    5025     .05       0
Bank Sta=4985,5025
XS Rating Curve= 0 ,0
Exp/Cntr=0.3,0.1

Type RM Length L Ch R = 1 ,5279    ,155,155,155
BEGIN DESCRIPTION:
BOARD CREEK 7.0
END DESCRIPTION:
XS GIS Cut Line= 4
      3394914.66     10609987.14      3396525.79     10608521.84
      3396859.13     10607862.12      3396817.46     10607007.99
#Sta/Elev= 30
  2276.8  541.61  3064.7  539.23  3099.8     538  3227.5  538.17  3956.6  532.34
  4034.3  530.84  4119.5  531.27  4367.5  530.04  4402.6  530.99  4510.8  530.48
  4921.5     533  4966.1  532.85  4981.4  531.63  4988.4  526.29    4994  523.49
  5003.6  522.86  5006.8  523.36  5010.7  529.36  5016.3  531.39  5048.6  533.47
  5083.1  532.44  5214.3   532.9  5374.4   535.4  5554.7  541.93  5584.7  542.33
  5694.8  548.17  5774.9  550.27  5850.5  554.05  5975.2  557.51  6048.9  557.93
#Mann= 4 ,-1 , 0
  2276.8     .05       0  4981.4     .16       0  4981.4     .07       0
  5016.3     .05       0
Bank Sta=4981.4,5016.3
XS Rating Curve= 0 ,0
Exp/Cntr=0.3,0.1

Type RM Length L Ch R = 1 ,5124    ,209,209,209
BEGIN DESCRIPTION:
BOARD CREEK 6.0
END DESCRIPTION:
XS GIS Cut Line= 4
      3394991.09     10610077.38      3396664.68     10608612.12
      3396942.46     10608028.78      3397088.29     10607021.87
#Sta/Elev= 30
  2237.4  541.67    2483  541.71  2674.7  539.58    2986  539.83  3007.9  538.72
  3071.5  539.12  3099.9  536.94  3155.9  538.04  3290.7  537.39  3638.1  533.83
  4297.7  529.78  4382.1  530.89  4467.6  529.33  4490.3  530.73    4850  533.23
  4978.2  532.08  4983.8  529.95    4994  523.49  5000.7  522.51  5006.5  523.43
  5016.1   529.6  5023.6  532.38  5038.3  533.53  5210.6  532.07  5421.3  533.57
  5539.5  536.77  5569.8  539.13  5731.5  544.88  6085.1  551.26  6125.3  550.93
#Mann= 4 ,-1 , 0
  2237.4     .05       0  4983.8     .16       0  4983.8     .07       0
  5023.6     .05       0
Bank Sta=4983.8,5016.1
XS Rating Curve= 0 ,0
Exp/Cntr=0.3,0.1

Type RM Length L Ch R = 1 ,4915    ,548,548,548
BEGIN DESCRIPTION:
BOARD CREEK 5.0
END DESCRIPTION:
XS GIS Cut Line= 4
      3395032.72     10610292.68      3396657.74     10608869.06
       3397136.9       10608126.      3398129.91     10606556.64
#Sta/Elev= 30
  2118.8  541.22  2735.6  539.96  2976.6  537.57  3451.2  535.44  3841.2  531.54
  4223.7  529.84  4245.1  528.72  4295.2   530.6  4346.7  527.91  4367.8  529.41
  4446.4  528.08  4461.6  529.21  4591.6  529.55  4728.3   529.5  4851.6  533.06
  4975.7  530.57  4981.7  529.67  4990.1  523.49  4996.6  522.17  5002.8  523.42
    5018  529.89  5025.8  529.19  5048.3   530.6  5069.4  531.92  5126.9  532.37
  5257.3  531.52  5815.9  532.93  6432.2  541.76  6793.2  550.76  7020.5  552.99
#Mann= 4 ,-1 , 0
  2118.8     .05       0  4591.6     .05       0  4975.7     .07       0
  5048.3     .05       0
Bank Sta=4975.7,5018
XS Rating Curve= 0 ,0
Exp/Cntr=0.3,0.1

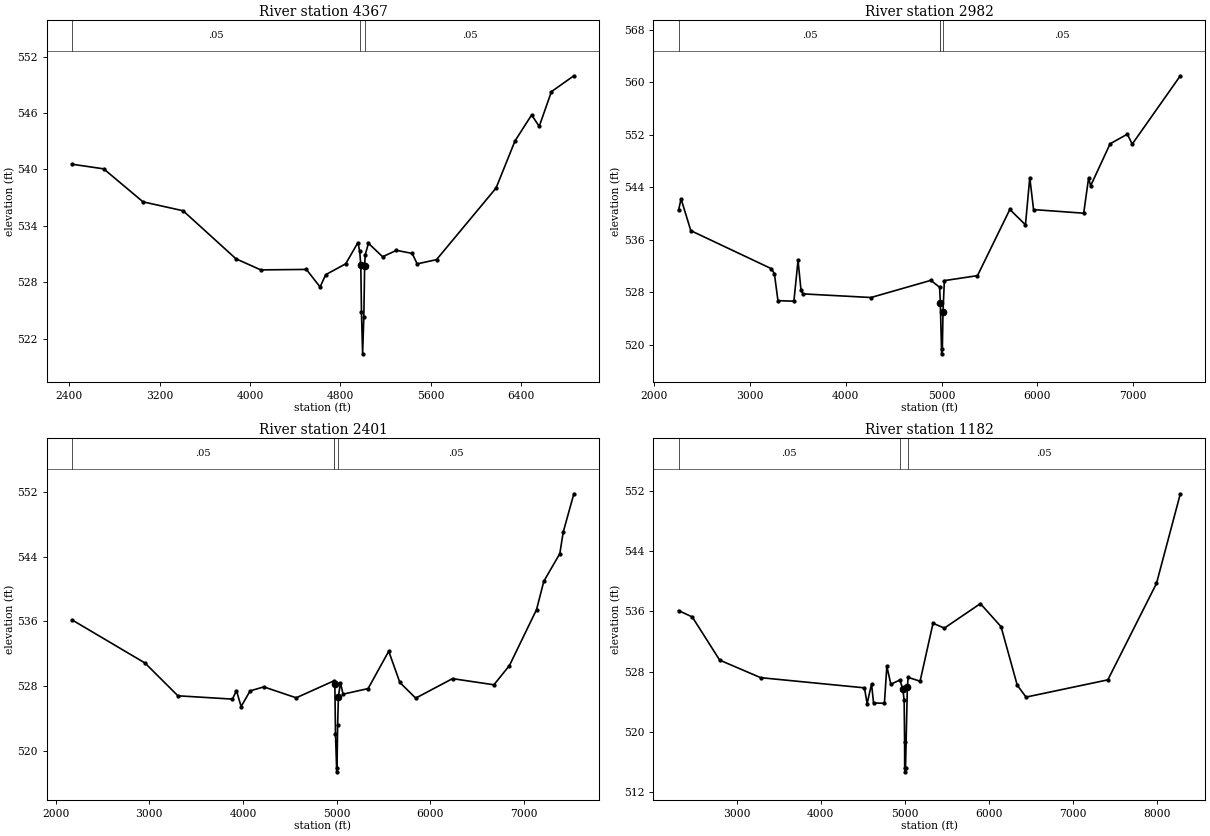
Type RM Length L Ch R = 1 ,4367    ,1385,1385,1385
BEGIN DESCRIPTION:
BOARD CREEK 4.0
END DESCRIPTION:
XS GIS Cut Line= 6
      3395310.48     10610264.92      3396352.18       10609376.
      3396817.46      10608938.5      3397157.74     10608660.73
      3397254.96     10608320.45      3398067.26     10606897.18
#Sta/Elev= 30
  2426.1  540.54  2705.8  540.05  3053.9  536.54  3408.5  535.59  3876.5  530.48
  4095.8   529.3  4499.3  529.35  4620.7  527.48  4670.2  528.79  4847.5  529.95
  4955.7  532.21  4971.3  531.26    4981   529.8  4986.9  524.77    4997  520.37
  5007.7   524.3  5014.8  529.72    5020  530.91  5048.6  532.13  5174.1   530.7
  5296.5  531.38  5436.2  531.05  5479.4  529.94  5650.8  530.39  6177.9  538.01
  6344.9  543.01  6492.5  545.79  6559.5  544.56  6667.5  548.26  6866.1  549.95
#Mann= 3 ,-1 , 0
  2426.1     .05       0  4971.3     .07       0    5020     .05       0
Bank Sta=4981,5014.8
XS Rating Curve= 0 ,0
Exp/Cntr=0.3,0.1

Type RM Length L Ch R = 1 ,2982    ,581,581,581
BEGIN DESCRIPTION:
BOARD CREEK 1.0
END DESCRIPTION:
XS GIS Cut Line= 4
      3395694.23     10610139.87        3397656.     10609002.74
      3398159.47     10608490.59      3399149.07       10606468.
#Sta/Elev= 30
  2254.3  540.47  2280.7  542.21  2382.6  537.37  3223.2  531.58  3254.7  530.82
    3292  526.71  3458.4  526.63  3501.5  532.84    3533  528.28  3554.5  527.74
    4263  527.19  4887.6   529.8  4979.5  528.75  4986.5   526.4  5000.4  518.61
  5007.8   519.4  5014.8  525.03  5028.9  529.76  5374.6  530.52  5712.2   540.6
  5875.3  538.26  5920.4  545.45  5959.8  540.58  6483.1  540.03  6533.7  545.33
  6556.2  544.22  6758.8   550.6  6938.9  552.07  6989.4  550.55  7491.7  560.96
#Mann= 4 ,-1 , 0
  2254.3     .05       0  4986.5     .16       0  4986.5     .07       0
  5014.8     .05       0
Bank Sta=4986.5,5014.8
XS Rating Curve= 0 ,0
Exp/Cntr=0.3,0.1

Type RM Length L Ch R = 1 ,2401    ,1219,1219,1219
BEGIN DESCRIPTION:
BOARD CREEK 1.9
END DESCRIPTION:
XS GIS Cut Line= 4
      3396040.89     10610410.34      3398271.83     10609151.64
      3399018.36     10607771.43       3399313.5      10606582.2
#Sta/Elev= 30
  2174.9  536.17  2953.5  530.84  3304.5  526.79  3886.6  526.38  3929.9  527.43
    3979  525.46  4075.8   527.4  4221.6  527.89  4566.9  526.54  4974.1  528.66
  4979.8  528.23  4986.5   522.1  4999.8  517.39    5003  517.89  5009.3  523.12
  5017.9   526.7  5039.7  528.42  5067.3  526.99  5334.7  527.68    5555   532.3
  5673.4  528.44  5842.7   526.5  6235.7  528.91  6677.7  528.15  6843.2  530.53
  7132.8  537.45  7210.3  540.95    7381  544.36  7417.2  547.02  7530.9  551.76
#Mann= 4 ,-1 , 0
  2174.9     .05       0  4974.1     .16       0  4974.1     .07       0
  5017.9     .05       0
Bank Sta=4979.8,5017.9
XS Rating Curve= 0 ,0
Exp/Cntr=0.3,0.1

Type RM Length L Ch R = 1 ,1182    ,340,740,100
BEGIN DESCRIPTION:
BOARD CREEK 1.8
END DESCRIPTION:
XS GIS Cut Line= 4
      3396101.73     10610644.68       3398150.3     10609846.09
      3398723.22     10609603.03      3399408.99     10606530.09
#Sta/Elev= 30
  2306.7   536.1    2470  535.25  2796.2  529.52  3283.8  527.19  4518.2  525.84
  4550.3  523.76  4603.1  526.35  4626.7  523.83  4755.9  523.79    4785   528.7
  4832.3  526.31  4939.5  526.88  4974.5   525.7  4990.6  524.22  4996.2   518.6
    4997  515.19  4999.8  514.69  5007.1  515.19  5028.8   525.9    5038  527.23
  5180.4  526.72  5334.2  534.41  5469.7  533.77  5897.6  537.02  6143.5  533.96
  6336.2  526.19  6440.7  524.61    7414   526.9  7992.6   539.7  8276.3   551.6
#Mann= 3 ,-1 , 0
  2306.7     .05       0  4939.5     .07       0    5038     .05       0
Bank Sta=4974.5,5028.8
XS Rating Curve= 0 ,0
Exp/Cntr=0.3,0.1

Chan Stop Cuts=-1
Use User Specified Reach Order=0
Composite Channel Slope=5