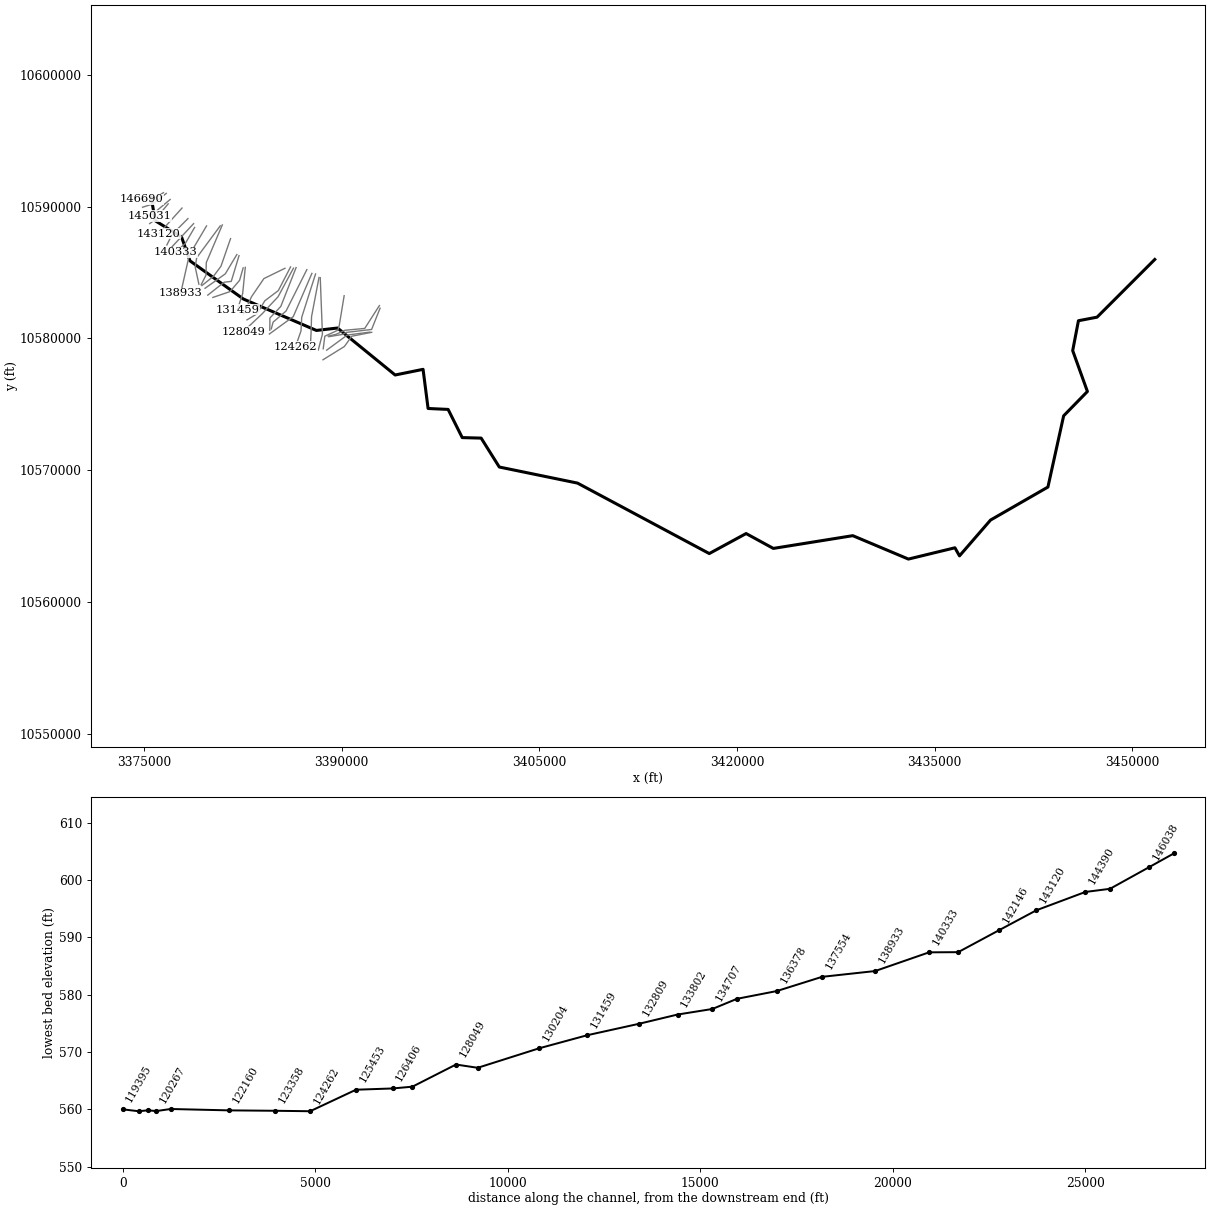
--- CHRISTMAS CREEK.prj (project) ---

Proj Title=CHRISTMAS CREEK Base Level Engineering
Current Plan=p01
Default Exp/Contr=0.3,0.1
English Units
Geom File=g01
Flow File=f01
Plan File=p01
Y Axis Title=Elevation
X Axis Title(PF)=Main Channel Distance
X Axis Title(XS)=Station
BEGIN DESCRIPTION:
CHRISTMAS CREEK
END DESCRIPTION:
DSS Export Rating Curves= 0
DSS Export Rating Curve Sorted= 0
DSS Export Volume Flow Curves= 0
DXF OffsetX= 0
DXF OffsetY= 0
DXF ScaleX= 1
DXF ScaleY= 10

--- CHRISTMAS CREEK.p01 (plan) ---

Plan Title=Multiple Run
Short Identifier=Multiple
Geom File=g01
Flow File=f01
Subcritical Flow
K Sum by GR= 0
Std Step Tol= 0.01
Critical Tol= 0.01
Num of Std Step Trials= 20
Max Error Tol= 0.3
Flow Tol Ratio= 0.001
Split Flow NTrial= 30
Split Flow Tol= 0.02
Split Flow Ratio= 0.02
Log Output Level= 0
Friction Slope Method= 1
Unsteady Friction Slope Method= 2
Unsteady Bridges Friction Slope Method= 1
Parabolic Critical Depth
Global Vel Dist=  1 , 1 , 1
Global Log Level= 0
CheckData=True
Encroach Param= -1, 0, 0, 0
BEGIN DESCRIPTION:
Multiple Run
END DESCRIPTION:

--- CHRISTMAS CREEK.f01 (steady flow) ---

Flow Title=Multiple
Program Version=4.10
Number of Profiles= 7
Profile Names=10-year,25-year,50-year,1pct_min,100-year,1pct_plu,500-year
River Rch & RM=CHRISTMAS CREEK,Reach-1         ,146690
     383     480     550     459     620     839     788
River Rch & RM=CHRISTMAS CREEK,Reach-1         ,144390
     483     611     705     591     799    1081    1026
River Rch & RM=CHRISTMAS CREEK,Reach-1         ,136378
     627     801     931     786    1063    1437    1383
River Rch & RM=CHRISTMAS CREEK,Reach-1         ,134707
     764     986    1152     977    1321    1787    1737
River Rch & RM=CHRISTMAS CREEK,Reach-1         ,128613
    1267    1659    1958    1674    2264    3061    3024
River Rch & RM=CHRISTMAS CREEK,Reach-1         ,120641
    1313    1720    2032    1738    2350    3178    3142
River Rch & RM=CHRISTMAS CREEK,Reach-1         ,120267
    1430    1881    2226    1907    2579    3488    3461
River Rch & RM=CHRISTMAS CREEK,Reach-1         ,119811
    1493    1966    2330    1998    2702    3654    3633
River Rch & RM=CHRISTMAS CREEK,Reach-1         ,118057
    1548    2038    2414    2070    2799    3786    3761
River Rch & RM=CHRISTMAS CREEK,Reach-1         ,116636
    1632    2153    2554    2192    2965    4010    3993
River Rch & RM=CHRISTMAS CREEK,Reach-1         ,110471
    1658    2181    2584    2214    2994    4049    4017
River Rch & RM=CHRISTMAS CREEK,Reach-1         ,104051
    1724    2269    2688    2303    3114    4211    4178
River Rch & RM=CHRISTMAS CREEK,Reach-1         ,101183
    1779    2346    2784    2388    3230    4368    4346
River Rch & RM=CHRISTMAS CREEK,Reach-1         ,94035
    1820    2397    2841    2435    3293    4454    4422
River Rch & RM=CHRISTMAS CREEK,Reach-1         ,87775
    2153    2848    3385    2909    3933    5320    5306
River Rch & RM=CHRISTMAS CREEK,Reach-1         ,81034
    2194    2902    3450    2964    4008    5421    5406
River Rch & RM=CHRISTMAS CREEK,Reach-1         ,70737
    2501    3320    3958    3409    4610    6234    6248
River Rch & RM=CHRISTMAS CREEK,Reach-1         ,67587
    2618    3472    4135    3558    4812    6507    6507
River Rch & RM=CHRISTMAS CREEK,Reach-1         ,62686
    2813    3744    4471    3856    5215    7053    7087
River Rch & RM=CHRISTMAS CREEK,Reach-1         ,60672
    2810    3736    4458    3843    5197    7028    7053
River Rch & RM=CHRISTMAS CREEK,Reach-1         ,56304
    3032    4035    4819    4156    5620    7601    7635
River Rch & RM=CHRISTMAS CREEK,Reach-1         ,48053
    3117    4150    4958    4277    5784    7822    7860
River Rch & RM=CHRISTMAS CREEK,Reach-1         ,42328
    3195    4246    5065    4363    5900    7979    7995
River Rch & RM=CHRISTMAS CREEK,Reach-1         ,38933
    3244    4315    5150    4439    6003    8119    8144
River Rch & RM=CHRISTMAS CREEK,Reach-1         ,36046
    3340    4442    5302    4569    6179    8357    8379
River Rch & RM=CHRISTMAS CREEK,Reach-1         ,26836
    3331    4424    5275    4541    6141    8306    8311
River Rch & RM=CHRISTMAS CREEK,Reach-1         ,22670
    3421    4552    5435    4685    6336    8569    8598
River Rch & RM=CHRISTMAS CREEK,Reach-1         ,20415
    3683    4903    5856    5049    6828    9234    9268
River Rch & RM=CHRISTMAS CREEK,Reach-1         ,12070
    3653    4851    5785    4980    6735    9108    9110
Boundary for River Rch & Prof#=CHRISTMAS CREEK,Reach-1         , 1
Up Type= 0
Dn Type= 3
Dn Slope=0.001
Boundary for River Rch & Prof#=CHRISTMAS CREEK,Reach-1         , 2
Up Type= 0
Dn Type= 3
Dn Slope=0.001
Boundary for River Rch & Prof#=CHRISTMAS CREEK,Reach-1         , 3
Up Type= 0
Dn Type= 3
Dn Slope=0.001
Boundary for River Rch & Prof#=CHRISTMAS CREEK,Reach-1         , 4
Up Type= 0
Dn Type= 3
Dn Slope=0.001
Boundary for River Rch & Prof#=CHRISTMAS CREEK,Reach-1         , 5
Up Type= 0
Dn Type= 3
Dn Slope=0.001
Boundary for River Rch & Prof#=CHRISTMAS CREEK,Reach-1         , 6
Up Type= 0
Dn Type= 3
Dn Slope=0.001
Boundary for River Rch & Prof#=CHRISTMAS CREEK,Reach-1         , 7
Up Type= 0
Dn Type= 3
Dn Slope=0.001
DSS Import GetInterval= 0
DSS Import GetPeak= 0
DSS Import FillOption= 0

--- CHRISTMAS CREEK.g01 (geometry) ---

Geom Title=Existing Conditions
Program Version=4.10

River Reach=CHRISTMAS CREEK ,Reach-1
Reach XY= 30
      3375552.11     10590711.64      3375857.85     10588929.27
      3377854.45     10587697.73      3378495.53     10585886.16
      3382545.71     10582989.02      3388087.78     10580603.87
      3389690.49     10580787.66      3394062.75     10577222.97
      3396181.18     10577652.14      3396562.35     10574681.66
      3398082.34     10574610.95      3399153.03     10572472.16
      3400588.74     10572433.76      3401965.98     10570239.39
      3407900.93      10569019.1      3417897.51     10563672.48
      3420692.01     10565191.56      3422757.82     10564062.81
      3428786.83     10565030.14      3433007.79     10563253.46
      3436537.34     10564111.21      3436883.39      10563497.5
      3439239.49     10566215.39      3443593.38     10568719.27
      3444786.29     10574124.38      3446590.11     10575971.97
      3445472.95      10579072.1      3445908.51     10581341.36
      3447322.15     10581611.55      3451700.55     10585990.68

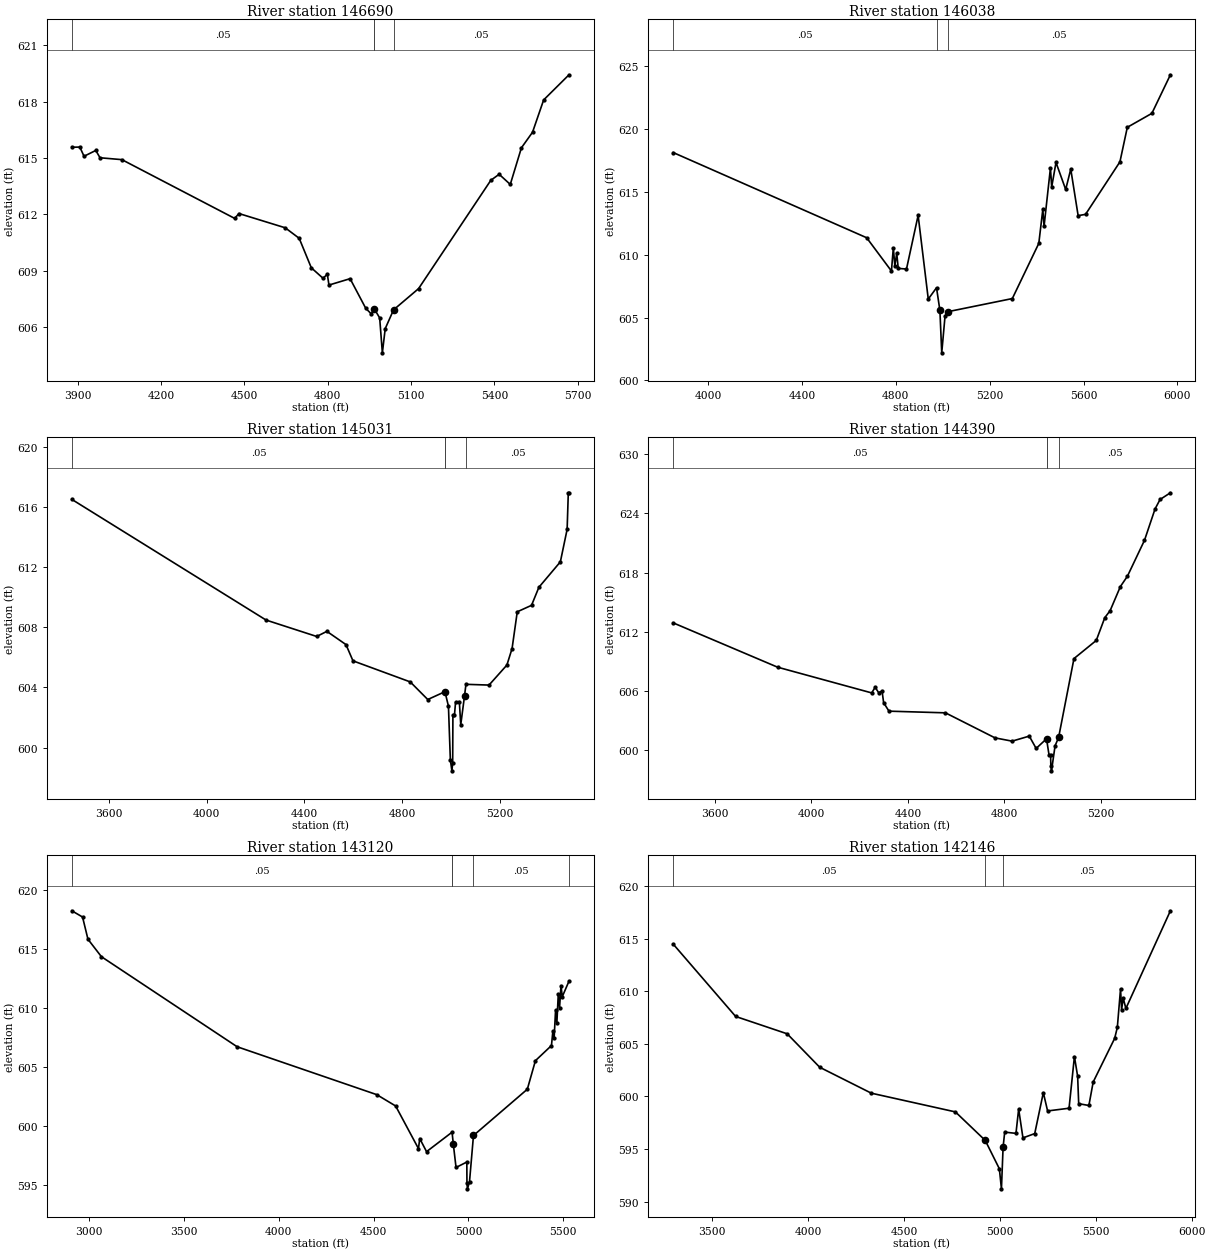
Type RM Length L Ch R = 1 ,146690  ,652,652,652
BEGIN DESCRIPTION:
CHRISTMAS CREEK 146.3
END DESCRIPTION:
XS GIS Cut Line= 3
      3376481.42     10591062.03      3375687.16     10590554.22
      3374840.78      10590541.2
#Sta/Elev= 30
  3879.1  615.57  3907.8  615.58    3923  615.09  3965.3   615.4  3980.5  615.01
  4059.2  614.91  4465.2  611.78  4480.4  612.04    4647  611.28  4697.3  610.72
  4740.9  609.15  4783.2  608.59  4798.5  608.81  4804.4  608.23 4880.45  608.57
  4936.9  606.99  4956.9  606.69  4966.9  606.98  4986.9  606.48  4996.6  604.62
  5006.9  605.91  5036.9  606.91  5126.9  608.04  5386.9  613.81  5416.9  614.13
  5456.9  613.59    5497  615.54    5537  616.37    5577  618.09  5668.3  619.43
#Mann= 4 ,-1 , 0
  3879.1     .05       0  4966.9     .12       0  4966.9     .07       0
  5036.9     .05       0
Bank Sta=4966.9,5036.9
XS Rating Curve= 0 ,0
Exp/Cntr=0.3,0.1

Type RM Length L Ch R = 1 ,146038  ,1007,1007,1007
BEGIN DESCRIPTION:
CHRISTMAS CREEK 146.0
END DESCRIPTION:
XS GIS Cut Line= 3
      3376696.66     10591004.87      3375696.62     10590204.84
      3374896.83      10589954.9
#Sta/Elev= 30
  3851.5  618.13  4675.8  611.35  4781.4   608.7  4789.4  610.55  4795.9  609.11
  4803.9  610.12  4810.3  608.91  4845.5  608.86  4895.1  613.13  4938.3  606.47
  4973.5  607.37  4987.9  605.56  4995.7  602.19  5009.9  605.14  5023.2  605.47
  5296.5  606.51  5409.3   610.9  5426.4   613.6  5431.7  612.26  5458.9   616.9
  5464.2  615.39  5482.6  617.34  5523.9  615.19  5545.5  616.81  5576.9  613.11
  5608.4  613.21    5755  617.39  5786.5  620.14  5891.2  621.25  5970.1  624.32
#Mann= 3 ,-1 , 0
  3851.5     .05       0  4973.5     .07       0  5023.2     .05       0
Bank Sta=4987.9,5023.2
XS Rating Curve= 0 ,0
Exp/Cntr=0.3,0.1

Type RM Length L Ch R = 1 ,145031  ,641,641,641
BEGIN DESCRIPTION:
CHRISTMAS CREEK 144.0
END DESCRIPTION:
XS GIS Cut Line= 3
      3376992.07     10590541.61      3375792.11     10589541.64
      3375392.11     10589291.64
#Sta/Elev= 30
  3448.7  616.49  4243.3  608.47  4450.3  607.38    4492  607.72  4570.1  606.84
  4598.7  605.76    4833  604.36  4904.6  603.19  4974.9  603.71  4989.2  602.75
    4997  599.19  5003.3  598.45  5006.5  598.95  5007.5  602.14  5013.7  602.14
  5018.4  603.02  5033.7  603.05  5039.6  601.52  5054.9  603.42  5060.8   604.2
  5155.2  604.15  5228.3  605.48  5249.5  606.58  5270.7  609.02  5329.1  609.45
  5359.2  610.65    5447  612.34  5474.7   614.5  5479.5  616.93  5482.4  616.93
#Mann= 4 ,-1 , 0
  3448.7     .05       0  4974.9     .12       0  4974.9     .07       0
  5060.8     .05       0
Bank Sta=4974.9,5054.9
XS Rating Curve= 0 ,0
Exp/Cntr=0.3,0.1

Type RM Length L Ch R = 1 ,144390  ,1270,1270,1270
BEGIN DESCRIPTION:
CHRISTMAS CREEK 143.0
END DESCRIPTION:
XS GIS Cut Line= 3
      3376842.12     10590211.46      3375842.11     10589011.43
      3375442.09     10588711.42
#Sta/Elev= 30
  3426.7   612.9  3859.4  608.41  4249.9   605.8  4264.2  606.37  4278.6  605.83
  4292.9  605.98  4299.4  604.81  4321.5  603.95  4555.8  603.78  4761.5  601.24
  4832.3  600.91  4903.4  601.42    4932  600.17    4975  601.15  4985.4  599.51
  4991.9  599.51  4992.9   598.4  4995.6   597.9  5010.5  600.44  5025.1  601.28
  5088.8  609.28  5181.3  611.12  5216.7  613.43  5238.8  614.14  5281.3  616.58
  5310.5  617.63  5381.3  621.27  5425.1  624.45  5445.9  625.41  5488.8  626.09
#Mann= 4 ,-1 , 0
  3426.7     .05       0    4975     .12       0    4975     .07       0
  5025.1     .05       0
Bank Sta=4975,5025.1
XS Rating Curve= 0 ,0
Exp/Cntr=0.3,0.1

Type RM Length L Ch R = 1 ,143120  ,974,974,974
BEGIN DESCRIPTION:
CHRISTMAS CREEK 141.0
END DESCRIPTION:
XS GIS Cut Line= 3
      3377892.14     10589891.68      3376492.11     10588341.64
      3376142.12     10587941.65
#Sta/Elev= 30
    2910  618.27  2966.5  617.74  2994.9  615.86  3065.9  614.38    3781  606.75
  4517.1  602.69  4616.5  601.73  4736.8  598.12  4743.5  598.97  4779.4  597.86
  4913.9  599.51  4920.6  598.48  4934.8  596.52  4991.6  596.98  4992.3  595.21
  4995.1  594.71  5005.8  595.32  5026.7  599.23  5310.5  603.15  5353.2  605.57
  5437.7  606.85  5445.3   608.1  5451.9  607.53  5459.5  609.88  5466.1  608.75
  5473.7  611.22  5480.4  610.07    5488  611.93  5494.6  610.99  5530.2  612.31
#Mann= 5 ,-1 , 0
    2910     .05       0  4913.9     .12       0  4913.9     .07       0
  5026.7     .05       0  5530.2     .05       0
Bank Sta=4920.6,5026.7
XS Rating Curve= 0 ,0
Exp/Cntr=0.3,0.1

Type RM Length L Ch R = 1 ,142146  ,1057,1057,1057
BEGIN DESCRIPTION:
CHRISTMAS CREEK 139.0
END DESCRIPTION:
XS GIS Cut Line= 3
      3378342.12     10589091.65      3377142.11     10587891.64
      3376742.11     10587091.64
#Sta/Elev= 30
  3297.7  614.47    3623   607.6  3891.7  605.95  4061.4  602.77  4330.1  600.31
  4768.5  598.53  4924.1  595.82  4997.6  593.13  5008.5  591.22  5017.1  595.18
  5025.5  596.61  5084.2  596.49  5098.2   598.8  5120.6  596.06    5182  596.47
  5226.8  600.36  5249.1  598.62  5360.9  598.88  5388.9  603.79  5405.7  601.91
  5411.2  599.31  5464.3  599.14  5486.7  601.37  5598.5  605.51  5612.5  606.55
  5629.3  610.22  5634.8  608.25  5643.2  609.33  5657.2  608.36  5889.2  617.64
#Mann= 3 , 0 , 0
  3297.7     .05       0  4924.1     .07       0  5017.1     .05       0
#XS Ineff= 2 , 0
                          5098.3          597.96
Permanent Ineff=
       F       F
Bank Sta=4924.1,5017.1
XS Rating Curve= 0 ,0
Exp/Cntr=0.3,0.1

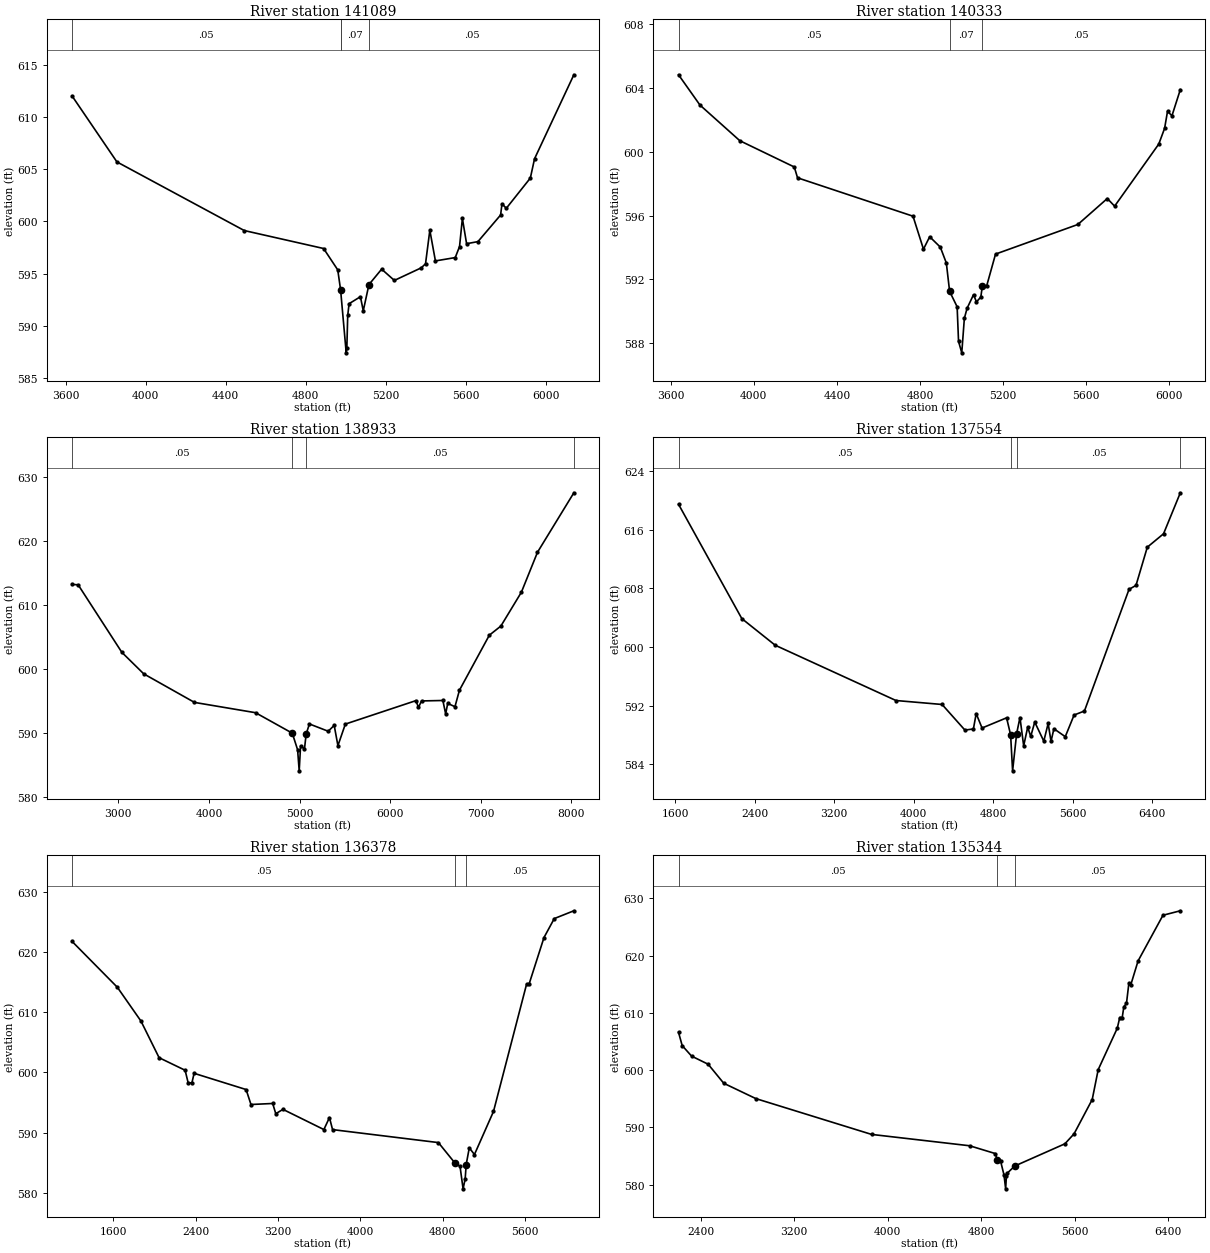
Type RM Length L Ch R = 1 ,141089  ,756,756,756
BEGIN DESCRIPTION:
CHRISTMAS CREEK 137.0
END DESCRIPTION:
XS GIS Cut Line= 2
      3378770.54     10588709.96      3377060.81     10586875.32
#Sta/Elev= 30
  3631.7  612.03  3855.8  605.71  4492.4  599.13  4888.7  597.41  4959.5  595.36
  4973.7  593.45  5001.8  587.41    5005  587.91  5009.3  590.99  5016.2  592.12
  5072.8  592.79    5087  591.44  5115.3  593.95  5178.9  595.43  5242.4  594.35
  5377.2  595.56  5398.2  595.95  5419.7  599.16  5447.6  596.22  5546.7  596.54
  5568.2   597.6  5582.4  600.29  5603.4  597.87  5660.1  598.07  5773.4  600.62
  5780.3   601.7  5801.8  601.26    5922  604.16    5943  606.01  6139.5  614.06
#Mann= 4 ,-1 , 0
  3631.7     .05       0  4973.7     .12       0  4973.7     .07       0
  5115.3     .05       0
#XS Ineff= 2 , 0
                         5182.39          595.14
Permanent Ineff=
       F       F
Bank Sta=4973.7,5115.3
XS Rating Curve= 0 ,0
Exp/Cntr=0.3,0.1

Type RM Length L Ch R = 1 ,140333  ,1400,1400,1400
BEGIN DESCRIPTION:
CHRISTMAS CREEK 135.0
END DESCRIPTION:
XS GIS Cut Line= 3
       3378846.6     10588419.74      3378146.62     10587219.77
      3377396.86     10586519.99
#Sta/Elev= 30
    3638  604.84    3741  602.94  3932.9   600.7    4195  599.05  4210.7  598.37
  4766.4  595.96  4816.7  593.89  4846.6  594.67  4897.7  594.02  4926.8  593.02
  4942.5  591.24  4978.7  590.27  4985.5   588.1    5001  587.38  5013.5  589.55
  5026.7  590.18  5057.5  591.03  5071.7  590.58  5092.7  590.88    5100  591.57
    5121  591.59  5163.5  593.58  5559.7  595.44  5701.4  597.07  5736.6  596.59
  5949.1  600.49  5977.2  601.48  5991.1  602.54  6012.6  602.27  6052.8  603.91
#Mann= 3 , 0 , 0
    3638     .05       0  4942.5     .07       0    5100     .05       0
Bank Sta=4942.5,5100
XS Rating Curve= 0 ,0
Exp/Cntr=0.3,0.1

Type RM Length L Ch R = 1 ,138933  ,1379,1379,1379
BEGIN DESCRIPTION:
CHRISTMAS CREEK 133.0
END DESCRIPTION:
XS GIS Cut Line= 4
      3379751.17     10588534.59      3378570.61     10586538.05
      3378405.68     10586147.43      3377789.35     10583421.71
#Sta/Elev= 30
  2489.2  613.27  2556.3  613.21  3038.6  602.65  3279.9  599.29  3840.2  594.82
  4514.1  593.21  4919.6  590.01  4978.4  587.41  4995.9  584.12    5011  587.99
  5054.4  587.57  5072.7  589.87  5108.7  591.45  5316.2  590.31  5382.1  591.23
  5423.2  588.06  5505.2  591.43  6284.4   595.1  6312.2  594.03  6345.9  595.05
  6581.5  595.12  6612.4  593.02  6634.9  594.66    6715  594.15  6764.5  596.73
  7094.3  605.33  7221.8  606.76    7448  612.05  7625.8   618.3  8027.2   627.6
#Mann= 4 ,-1 , 0
  2489.2     .05       0  4919.6     .07       0  5072.7     .05       0
  8027.2     .05       0
Bank Sta=4919.6,5072.7
XS Rating Curve= 0 ,0
Exp/Cntr=0.3,0.1

Type RM Length L Ch R = 1 ,137554  ,1176,1176,1176
BEGIN DESCRIPTION:
CHRISTMAS CREEK 131.0
END DESCRIPTION:
XS GIS Cut Line= 4
      3380792.84     10588543.27      3379004.63     10586121.38
      3378891.79     10585418.26      3379169.52     10584116.39
#Sta/Elev= 30
  1631.2  619.46  2268.6  603.87  2604.7  600.24    3821   592.7  4285.6  592.16
  4515.3  588.67  4600.9  588.82    4629  590.91  4688.1  588.95  4935.2  590.34
  4975.7  588.02  4995.7  583.11  5036.4  588.19  5069.9  590.38  5107.3  586.52
  5147.8  589.07  5178.2   587.8  5218.7  589.76  5309.9  587.16  5353.8  589.57
  5382.7  587.13  5411.7  588.85  5526.2  587.77    5615  590.72  5719.2  591.27
  6168.4  607.86  6238.5   608.4  6352.4  613.61    6516  615.44    6685  621.03
#Mann= 4 ,-1 , 0
  1631.2     .05       0  4975.7     .07       0  5036.4     .05       0
    6685     .05       0
Bank Sta=4975.7,5036.4
XS Rating Curve= 0 ,0
Exp/Cntr=0.3,0.1

Type RM Length L Ch R = 1 ,136378  ,1034,1034,1034
BEGIN DESCRIPTION:
CHRISTMAS CREEK 129.0
END DESCRIPTION:
XS GIS Cut Line= 4
      3380949.08      10588612.7       3379733.8      10585756.8
      3379707.76     10584793.26      3379343.17     10584072.76
#Sta/Elev= 30
  1199.6  621.82  1639.8  614.18  1868.9  608.56  2045.2  602.46  2297.9  600.37
    2327  598.31  2363.6  598.25  2385.3  599.86  2890.4  597.16  2937.7  594.67
  3148.6  594.84  3178.7  593.14  3248.5  593.86    3646   590.5  3700.3   592.5
  3730.3  590.49  4758.6  588.33  4922.5  584.86  4968.7  584.39  4998.5  580.63
  5018.7  582.27  5028.7  584.68  5058.7  587.46  5108.8  586.34  5293.9  593.51
  5616.4  614.77  5638.9  614.68  5784.6  622.47  5884.3  625.62  6074.7  626.92
#Mann= 3 , 0 , 0
  1199.6     .05       0  4922.5     .07       0  5028.7     .05       0
Bank Sta=4922.5,5028.7
XS Rating Curve= 0 ,0
Exp/Cntr=0.3,0.1

Type RM Length L Ch R = 1 ,135344  ,637,637,637
BEGIN DESCRIPTION:
CHRISTMAS CREEK 127.0
END DESCRIPTION:
XS GIS Cut Line= 4
      3381574.08     10587571.03      3380844.91     10585470.34
        3380272.     10584706.45       3379403.9     10584011.98
#Sta/Elev= 30
  2211.8   606.6  2242.9  604.29  2323.4  602.45  2465.2  601.03  2598.3  597.71
  2873.1  595.03  3862.5  588.78  4700.5   586.8  4921.3  585.43  4935.9  584.34
  4965.1  584.13  4994.3  581.72  5008.6  579.28  5015.1  581.57  5021.3  581.99
  5085.9  583.26  5514.9  587.14  5593.4  588.88  5748.7  594.87  5799.9  600.09
  5963.2  607.33    5984  609.19  6004.9  609.16  6019.2  611.06  6041.6  611.65
  6062.4  615.24  6076.8  614.78  6140.8  619.07  6353.7  627.04    6502  627.82
#Mann= 3 , 0 , 0
  2211.8     .05       0  4935.9     .07       0  5085.9     .05       0
Bank Sta=4935.9,5085.9
XS Rating Curve= 0 ,0
Exp/Cntr=0.3,0.1

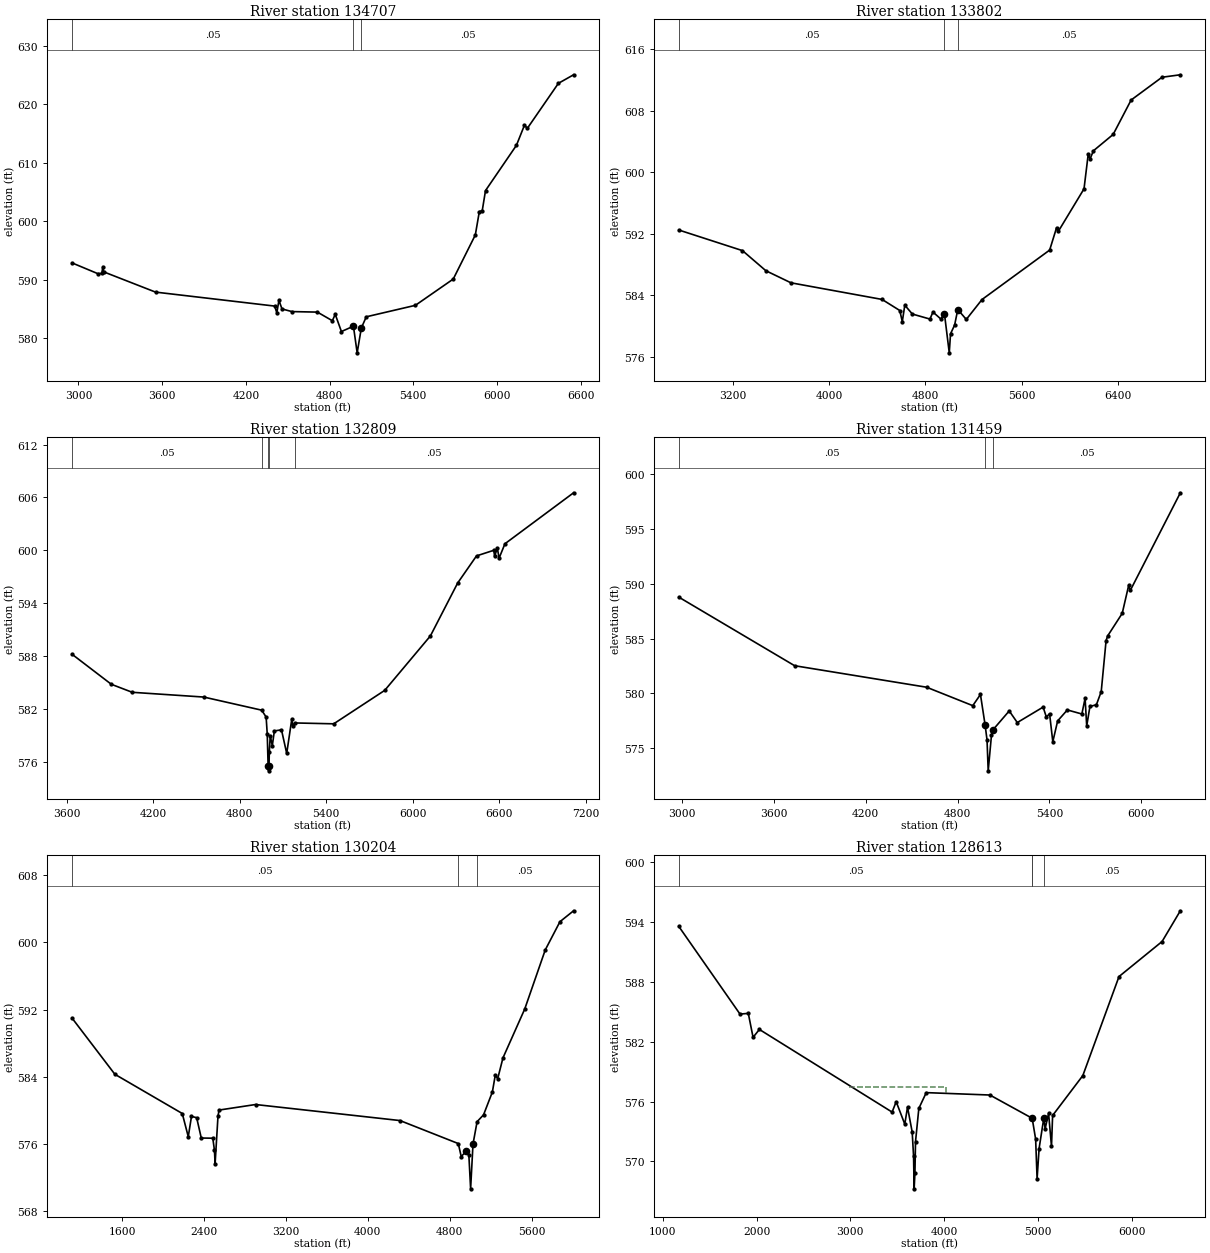
Type RM Length L Ch R = 1 ,134707  ,905,905,905
BEGIN DESCRIPTION:
CHRISTMAS CREEK 125.0
END DESCRIPTION:
XS GIS Cut Line= 3
      3382051.51     10586364.44      3381174.77     10584897.43
      3379638.34     10583803.69
#Sta/Elev= 30
  2953.9  592.88  3137.8  591.05  3166.9  591.07  3174.8  592.24  3180.6  591.35
  3552.2  587.89  4406.3   585.5  4421.8  584.34  4436.7  586.49  4458.8  585.01
  4529.9  584.56  4712.6  584.47  4819.6     583  4840.5  584.09  4884.7  581.15
  4970.8  582.06  4997.6  577.51  5027.4  581.75    5063  583.67    5415  585.63
  5686.4  590.12  5844.6  597.66  5873.3  601.65  5894.2  601.81  5917.6  605.24
  6139.2  612.97  6196.7  616.41  6217.6  615.88  6440.1  623.57  6548.9  625.03
#Mann= 3 , 0 , 0
  2953.9     .05       0  4970.8     .07       0  5027.4     .05       0
Bank Sta=4970.8,5027.4
XS Rating Curve= 0 ,0
Exp/Cntr=0.3,0.1

Type RM Length L Ch R = 1 ,133802  ,993,993,993
BEGIN DESCRIPTION:
CHRISTMAS CREEK 124.0
END DESCRIPTION:
XS GIS Cut Line= 4
      3382216.43      10586277.6      3381626.16     10584324.51
      3381087.97     10584263.74      3379846.84       10583283.
#Sta/Elev= 30
  2753.6   592.5  3282.2  589.82  3476.3  587.21  3684.5  585.64  4440.8  583.48
  4588.2  582.04  4608.9  580.59  4629.8  582.73  4692.5  581.58  4838.3  580.93
  4863.7  581.84  4928.8  580.94    4959  581.61    4999  576.54  5009.4  579.01
  5043.4  580.15  5069.7  582.17  5140.2  580.88    5271  583.47  5832.3  589.89
    5890  592.81  5903.8  592.31  6117.7  597.85  6152.9  602.39  6167.3  601.72
  6196.2   602.8  6359.7  604.92  6508.8  609.39  6765.2  612.35  6917.4  612.67
#Mann= 3 , 0 , 0
  2753.6     .05       0    4959     .07       0  5069.7     .05       0
Bank Sta=4959,5069.7
XS Rating Curve= 0 ,0
Exp/Cntr=0.3,0.1

Type RM Length L Ch R = 1 ,132809  ,1350,1350,1350
BEGIN DESCRIPTION:
CHRISTMAS CREEK 121.8
END DESCRIPTION:
XS GIS Cut Line= 4
      3382531.44       10585353.      3382258.01     10584406.85
      3381533.19     10583551.82      3380231.07      10583109.1
#Sta/Elev= 30
    3636  588.18  3908.5  584.77  4053.8  583.86  4550.2  583.32  4952.2  581.83
  4983.1  581.05  4990.8  579.12    4997  575.44  4999.8  574.94    5003  575.44
  5005.1  577.04  5011.7  578.94  5025.9  577.79  5040.2  579.47  5089.6   579.6
  5125.9  576.92  5161.1  580.81  5167.6     580  5180.3  580.38  5452.2  580.28
  5806.3  584.08  6123.2  590.26  6312.5  596.27  6443.3  599.35  6563.5  599.99
  6568.8  599.31  6587.9  600.22  6600.2   599.1  6640.7  600.73  7117.1  606.52
#Mann= 5 ,-1 , 0
    3636     .05       0  4952.2     .12       0    4997     .07       0
    5003     .12       0  5180.3     .05       0
Bank Sta=4997,5003
XS Rating Curve= 0 ,0
Exp/Cntr=0.3,0.1

Type RM Length L Ch R = 1 ,131459  ,1255,1255,1255
BEGIN DESCRIPTION:
CHRISTMAS CREEK 121.0
END DESCRIPTION:
XS GIS Cut Line= 3
       3382692.1     10585391.61      3382492.11     10583391.64
      3382092.09      10582191.6
#Sta/Elev= 30
  2979.5  588.77  3735.7  582.52  4597.5  580.56    4899  578.88  4949.2   579.9
  4979.4  577.13  4992.1  575.76  4999.7  572.94  5021.1  576.18  5031.6  576.69
    5137   578.4  5189.7  577.34  5358.4  578.75  5379.5  577.84  5400.5  578.15
  5421.6  575.59  5453.2  577.49  5516.5  578.49  5611.4  578.12  5632.4  579.55
    5643  577.03  5664.1  578.81  5706.2  578.96  5737.8  580.16  5769.5  584.81
    5780  585.24  5874.9  587.29    5917  589.84  5927.6  589.38  6254.4  598.28
#Mann= 3 , 0 , 0
  2979.5     .05       0  4979.4     .07       0  5031.6     .05       0
Bank Sta=4979.4,5031.6
XS Rating Curve= 0 ,0
Exp/Cntr=0.3,0.1

Type RM Length L Ch R = 1 ,130204  ,1591,1591,1591
BEGIN DESCRIPTION:
CHRISTMAS CREEK 118.0
END DESCRIPTION:
XS GIS Cut Line= 4
      3385702.04     10585320.93      3384104.79     10584539.67
      3383167.29     10583168.14      3382559.66     10581840.05
#Sta/Elev= 30
  1110.4  590.98  1528.8  584.29  2187.2  579.62  2245.8  576.86  2277.3  579.28
  2327.8  579.12  2372.9   576.7  2485.4  576.68  2501.8  575.23  2507.9  573.62
    2536  579.27  2546.4  580.03  2903.2  580.69  4314.6  578.78  4884.1  576.04
  4912.6  574.49  4964.1  575.18  4987.1   574.7  5004.4  570.65  5027.6  575.98
  5067.7  578.65  5130.7  579.46  5216.8  582.18  5245.8  584.22  5268.8  583.76
  5320.3  586.24    5533  592.06  5733.6   599.1  5877.2  602.46  6010.3  603.76
#Mann= 3 ,-1 , 0
  1110.4     .05       0  4884.1     .07       0  5067.7     .05       0
#XS Ineff= 1 ,-1
 1801.59 2565.66  580.03
Permanent Ineff=
       T
Bank Sta=4964.1,5027.6
XS Rating Curve= 0 ,0
Exp/Cntr=0.3,0.1

Type RM Length L Ch R = 1 ,128613  ,564,564,564
BEGIN DESCRIPTION:
CHRISTMAS CREEK 117.0
END DESCRIPTION:
XS GIS Cut Line= 5
      3386127.37     10585425.12      3385198.54     10583628.21
      3384174.23     10582855.64      3383575.28     10581857.38
      3382820.63     10581406.32
#Sta/Elev= 30
  1170.8  593.55  1823.3  584.77  1911.9  584.84  1962.7  582.44  2030.2  583.23
  3445.6  574.95  3489.3  575.99  3580.9  573.74    3610  575.45    3660  572.95
  3674.6  570.52  3680.6  567.26  3689.1  568.83  3695.4  571.99  3730.8  575.32
  3809.9   576.9  4488.7  576.66  4939.7  574.33  4976.6  572.24  4992.1  568.27
  5013.5   571.3  5064.3  574.39  5077.7  573.27  5114.6  574.82  5145.7  571.51
  5157.6  574.61    5480  578.61  5865.8  588.53  6325.2  592.04  6519.9  595.12
#Mann= 4 ,-1 , 0
  1170.8     .05       0  4939.7     .12       0  4939.7     .07       0
  5064.3     .05       0
#XS Ineff= 1 ,-1
 2985.22 4015.35  577.48
Permanent Ineff=
       T
Bank Sta=4939.7,5064.3
XS Rating Curve= 0 ,0
Exp/Cntr=0.3,0.1

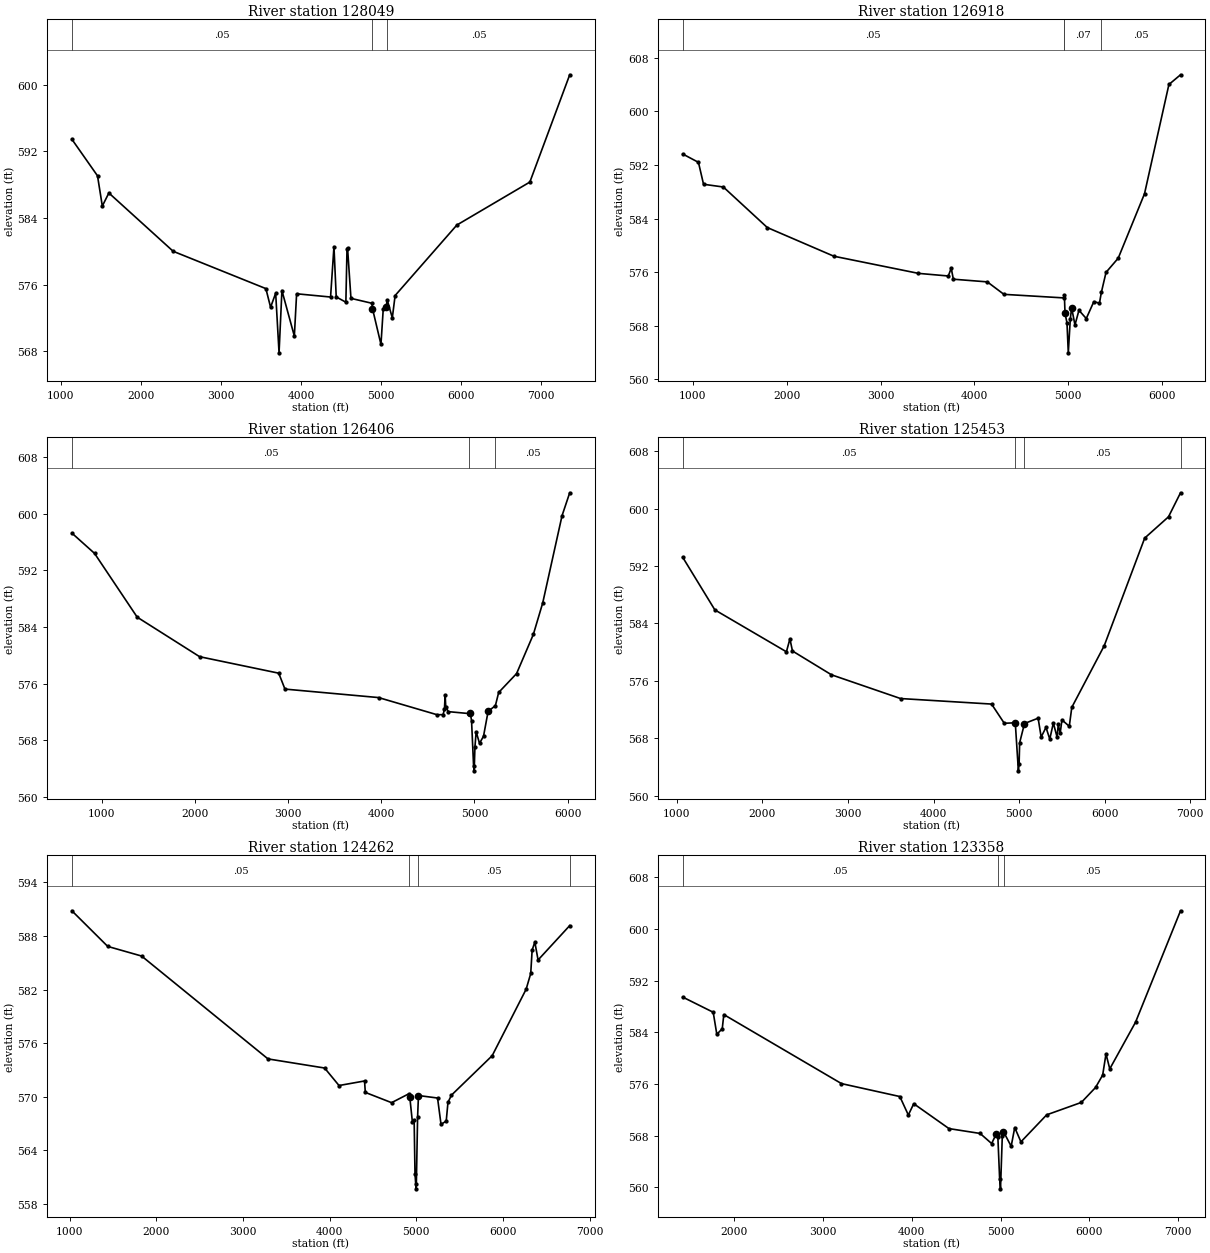
Type RM Length L Ch R = 1 ,128049  ,1131,1131,1131
BEGIN DESCRIPTION:
CHRISTMAS CREEK 116.0
END DESCRIPTION:
XS GIS Cut Line= 5
      3386348.28     10585330.48       3385171.2     10583148.18
      3384504.53     10582445.05      3383994.11     10581887.76
      3382526.25     10580503.18
#Sta/Elev= 30
  1137.5  593.47    1458  589.08    1518  585.45  1599.9  587.02  2403.5  580.02
  3562.2  575.54    3621   573.3  3684.6  574.99  3726.8  567.83  3762.6  575.31
    3918  569.84  3946.3  574.92  4370.6  574.53  4413.1  580.58  4441.4  574.54
  4561.9  573.91  4576.1  580.31    4583   580.4  4625.5  574.37  4887.6  573.78
  4894.4  573.15  5000.4  568.84  5028.8  573.07  5064.6  573.33  5078.7  574.19
  5142.3  572.03  5177.4  574.71  5948.9  583.17  6861.2  588.33  7359.5  601.21
#Mann= 3 ,-1 , 0
  1137.5     .05       0  4887.6     .07       0  5078.7     .05       0
#XS Ineff= 1 ,-1
  2142.8  4601.8 576.422
Permanent Ineff=
       T
Bank Sta=4894.4,5064.6
XS Rating Curve= 0 ,0
Exp/Cntr=0.3,0.1

Type RM Length L Ch R = 1 ,126918  ,512,512,512
BEGIN DESCRIPTION:
CHRISTMAS CREEK 115.0
END DESCRIPTION:
XS GIS Cut Line= 4
      3386548.02     10585374.81      3385384.84     10582423.47
      3384560.19     10581546.73      3384551.51     10580617.89
#Sta/Elev= 30
   891.7  593.65  1059.8   592.4  1113.9  589.13  1325.1  588.72  1793.4  582.67
  2502.7  578.39  3404.1  575.83    3722  575.44  3753.3   576.6  3775.7  574.96
  4137.8  574.56  4314.6   572.7  4951.5  572.17  4958.8  572.62  4965.7  569.89
  4986.7  568.44  5000.6  563.97  5022.3  569.08  5036.5  570.67  5071.7  568.13
  5114.1  570.32  5192.2  569.09  5272.7  571.61  5332.7  571.38  5352.7  572.98
  5402.7  575.98  5532.7   578.1  5812.7  587.71  6072.7  604.02  6196.5  605.47
#Mann= 4 ,-1 , 0
   891.7     .05       0  4951.5     .12       0  4951.5     .07       0
  5352.7     .05       0
Bank Sta=4965.7,5036.5
XS Rating Curve= 0 ,0
Exp/Cntr=0.3,0.1

Type RM Length L Ch R = 1 ,126406  ,953,953,953
BEGIN DESCRIPTION:
CHRISTMAS CREEK 113.0
END DESCRIPTION:
XS GIS Cut Line= 4
      3387364.01     10585218.62      3385784.15     10582076.24
      3384803.25     10581234.23      3384664.34     10580722.03
#Sta/Elev= 30
   681.3  597.28   924.5  594.41  1382.1  585.39  2051.9   579.8  2900.2  577.47
  2967.1  575.22  3971.7  574.02  4600.1  571.59  4663.7  571.61    4678  572.37
  4685.7  574.38  4692.3  572.66  4720.8  572.03  4940.3  571.76  4954.6  571.87
  4968.8  570.77  4990.8   564.3  4997.1  563.66    5005     567  5018.3  569.18
  5054.4  567.55  5097.2  568.55  5146.6  572.08  5224.5  572.87  5259.6  574.74
  5451.7  577.41  5631.5  582.94  5732.2   587.4  5939.8  599.75  6021.9  602.98
#Mann= 3 ,-1 , 0
   681.3     .05       0  4940.3     .07       0  5224.5     .05       0
Bank Sta=4954.6,5146.6
XS Rating Curve= 0 ,0
Exp/Cntr=0.3,0.1

Type RM Length L Ch R = 1 ,125453  ,1191,1191,1191
BEGIN DESCRIPTION:
CHRISTMAS CREEK 111.0
END DESCRIPTION:
XS GIS Cut Line= 3
      3387745.94     10584932.11      3386331.02      10581650.9
      3384516.93     10580331.56
#Sta/Elev= 30
  1069.6  593.22  1445.6  585.88  2281.6  580.04  2322.5  581.84  2352.2  580.15
  2808.1  576.83  3615.2  573.52  4678.3  572.75    4827  570.07  4950.3  570.14
  4956.5  569.95  4991.8  563.44  5000.1  564.45  5006.7  567.37  5063.1  570.04
  5222.3  570.78  5257.9  568.15  5314.3   569.5  5358.4  567.86  5400.1  570.11
  5444.1  568.13  5457.6  569.91  5479.7  568.66  5500.6  570.54  5586.3  569.65
  5615.7  572.29  5994.4  580.88  6467.3  595.89  6745.6  598.86    6886  602.21
#Mann= 4 ,-1 , 0
  1069.6     .05       0  4956.5     .07       0  5063.1     .05       0
    6886     .05       0
Bank Sta=4950.3,5063.1
XS Rating Curve= 0 ,0
Exp/Cntr=0.3,0.1

Type RM Length L Ch R = 1 ,124262  ,904,904,904
BEGIN DESCRIPTION:
CHRISTMAS CREEK 109.0
END DESCRIPTION:
XS GIS Cut Line= 4
      3388023.72     10584888.72      3386973.38     10581598.81
       3386921.3     10580574.51      3386504.65     10579376.63
#Sta/Elev= 30
  1023.9  590.83  1437.8  586.84  1829.1  585.76  3288.2  574.24  3941.7  573.22
  4107.9  571.26  4402.8  571.77  4411.4  570.49  4714.9  569.34  4915.1  570.34
  4925.2  569.95  4955.2  567.15  4975.2  567.42  4985.2  561.37  4997.3  559.69
  5000.6  560.19  5015.3  567.77  5025.3  570.14  5245.6  569.86  5285.6  566.91
  5345.7  567.28  5365.7  569.37  5405.8  570.18  5876.2   574.6  6268.4  582.05
  6321.3  583.81  6337.4  586.42  6368.5  587.33    6406  585.32  6771.3  589.17
#Mann= 4 ,-1 , 0
  1023.9     .05       0  4915.1     .07       0  5015.3     .05       0
  6771.3     .05       0
Bank Sta=4925.2,5025.3
XS Rating Curve= 0 ,0
Exp/Cntr=0.3,0.1

Type RM Length L Ch R = 1 ,123358  ,1198,1198,1198
BEGIN DESCRIPTION:
CHRISTMAS CREEK 107.0
END DESCRIPTION:
XS GIS Cut Line= 4
      3388284.14      10584619.6      3387719.91      10581650.9
      3387685.19     10580470.34      3387615.81     10579065.37
#Sta/Elev= 30
  1418.4  589.44  1762.4  587.09  1803.1  583.68  1864.2  584.54    1882  586.73
  3207.8  576.05  3865.3  574.05  3961.1  571.19  4021.9  572.94  4419.1  569.09
  4769.6  568.34  4899.7  566.78  4949.7  568.21  4969.7  567.85  4989.7  561.36
  4999.5  559.77  5019.8  567.92  5029.8  568.57    5044  568.34  5119.8  566.35
  5159.8  569.25  5229.8  567.04    5520  571.22  5910.4  573.14  6070.6  575.45
  6150.7  577.37  6188.2  580.64  6230.8  578.33  6521.1  585.55    7028  602.79
#Mann= 3 ,-1 , 0
  1418.4     .05       0  4969.7     .07       0    5044     .05       0
Bank Sta=4949.7,5029.8
XS Rating Curve= 0 ,0
Exp/Cntr=0.3,0.1

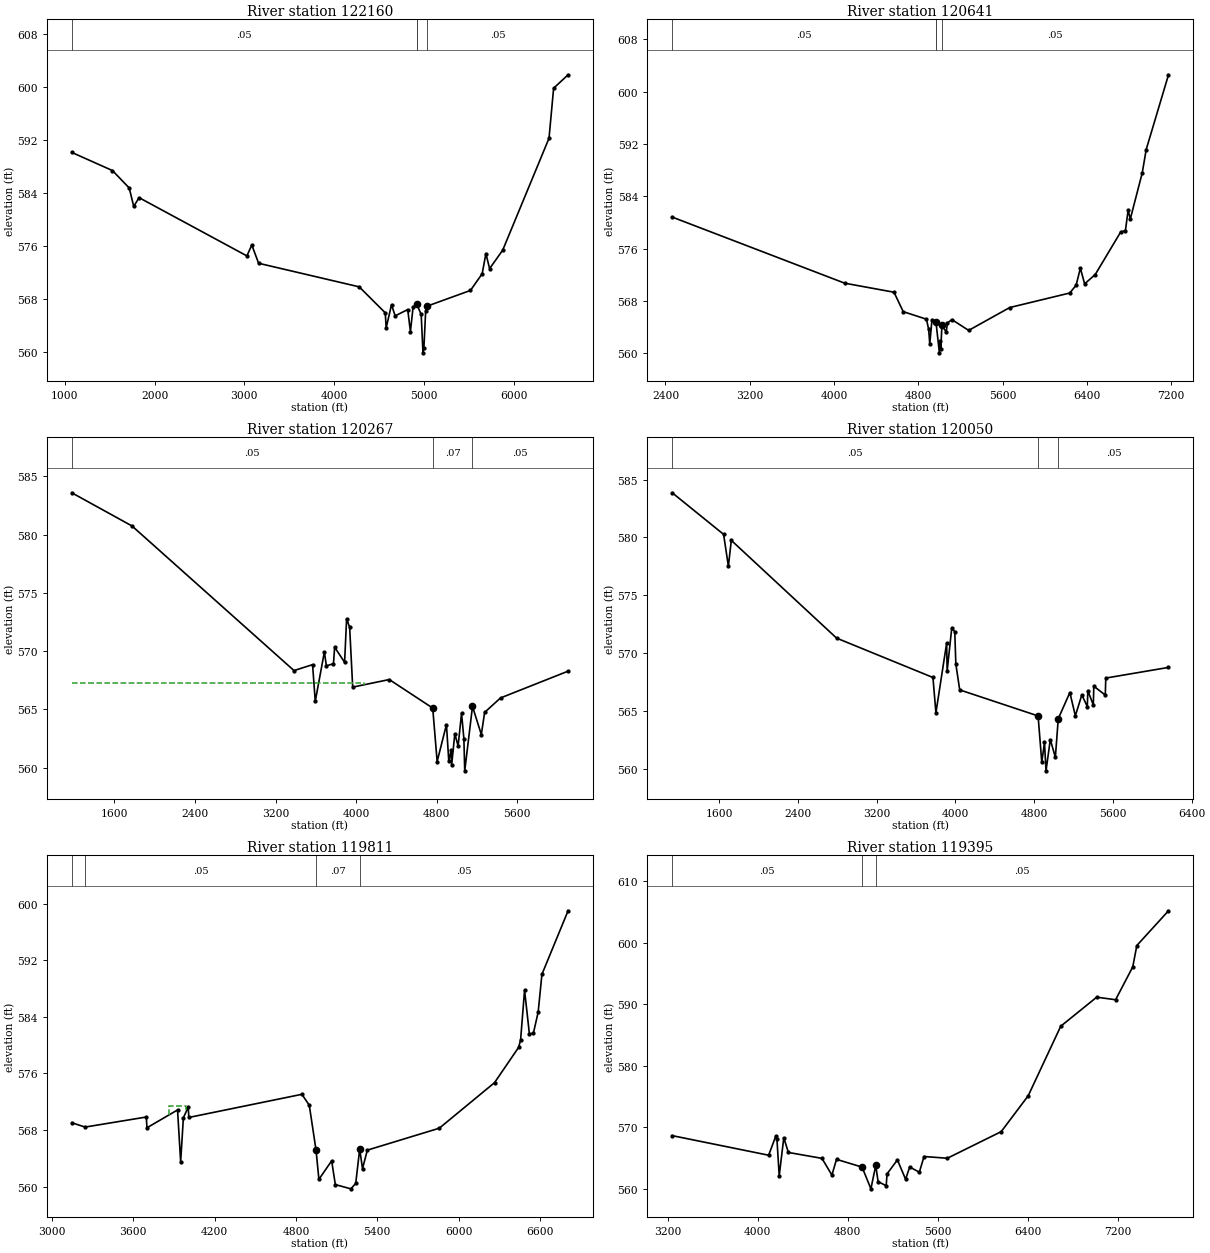
Type RM Length L Ch R = 1 ,122160  ,1519,1519,1519
BEGIN DESCRIPTION:
CHRISTMAS CREEK 105.0
END DESCRIPTION:
XS GIS Cut Line= 4
      3388379.63     10584610.94      3388501.16     10581468.61
      3388544.56     10580322.77       3388232.3     10579125.77
#Sta/Elev= 30
  1077.9  590.09  1531.3  587.35  1717.7  584.72  1767.7  581.95  1827.8  583.26
  3028.7  574.47  3083.1  576.12  3158.8  573.36  4279.6   569.8  4569.8  565.88
  4579.8  563.61  4639.3   567.1  4679.9  565.42    4820  566.37    4850  563.06
    4880  566.76    4920   567.2  4970.1  565.63  4989.8  559.84  5000.1  560.58
  5020.1  566.21  5040.1  566.91  5518.9  569.26  5649.4  571.78  5690.8  574.82
  5732.1  572.55  5878.1  575.34  6393.9  592.23  6445.2  599.78  6606.3  601.81
#Mann= 4 ,-1 , 0
  1077.9     .05       0    4920     .16       0    4920     .07       0
  5040.1     .05       0
Bank Sta=4920,5040.1
XS Rating Curve= 0 ,0
Exp/Cntr=0.3,0.1

Type RM Length L Ch R = 1 ,120641  ,374,374,374
BEGIN DESCRIPTION:
CHRISTMAS CREEK 104.0
END DESCRIPTION:
XS GIS Cut Line= 5
      3390193.87     10583239.46      3389820.61     10580973.81
      3389707.76     10580617.91      3388726.86     10580166.52
      3388605.33     10579211.66
#Sta/Elev= 30
  2463.7  580.82  4101.5  570.72  4569.5  569.34    4657  566.37  4877.6  565.22
  4898.5  563.66    4909  561.45    4930  565.14  4968.4  564.73  5000.4  560.08
  5005.9  561.84  5013.9  560.71  5024.4  564.26  5065.2  563.27  5076.9  564.64
  5118.8  565.16  5278.4  563.51    5668     567  6238.1  569.22  6298.6  570.41
  6338.9  573.01  6379.2  570.62    6480  572.04    6722  578.55  6766.4  578.74
  6792.6  581.88  6812.7  580.51  6926.3  587.57  6963.9  591.14  7175.6  602.56
#Mann= 4 ,-1 , 0
  2463.7     .05       0  4968.4     .12       0  4968.4     .07       0
  5024.4     .05       0
Bank Sta=4968.4,5024.4
XS Rating Curve= 0 ,0
Exp/Cntr=0.3,0.1

Type RM Length L Ch R = 1 ,120267  ,217,217,217
BEGIN DESCRIPTION:
CHRISTMAS CREEK 103.0
END DESCRIPTION:
XS GIS Cut Line= 5
      3392867.47      10582492.9      3391756.37      10580756.8
      3390254.63     10580617.91      3389560.19     10580305.41
      3388978.56      10580175.2
#Sta/Elev= 30
    1177   583.6  1774.7  580.75  3383.1  568.33  3567.3  568.84    3594  565.69
  3684.4  569.93  3704.5  568.74  3774.8  568.92  3786.3  570.34  3885.2  569.04
  3905.3  572.79  3935.4  572.04  3965.6  566.91    4329  567.56  4760.1  565.11
    4804  560.52  4896.4  563.69  4919.6  560.55  4942.7  561.49  4948.2  560.25
  4979.4   562.9  5012.2  561.86  5046.3  564.66  5069.4  562.49  5077.9  559.72
  5154.9  565.25  5242.6  562.84  5275.5  564.74  5433.1  565.98  6103.9  568.28
#Mann= 3 , 0 , 0
    1177     .05       0  4760.1     .07       0  5154.9     .05       0
#XS Ineff= 2 , 0
         4078.41  567.24
Permanent Ineff=
       F       F
Bank Sta=4760.1,5154.9
XS Rating Curve= 0 ,0
Exp/Cntr=0.3,0.1

Type RM Length L Ch R = 1 ,120050  ,239,239,239
BEGIN DESCRIPTION:
CHRISTMAS CREEK 102.0
END DESCRIPTION:
XS GIS Cut Line= 5
      3392919.55     10582293.22       3392277.2     10580678.68
      3390341.44     10580452.98      3390081.02     10580305.41
      3389039.32     10580131.79
#Sta/Elev= 30
  1122.1  583.86  1644.2  580.27  1692.8  577.52  1722.5  579.75    2792  571.31
    3771  567.91  3801.2  564.86  3910.2  570.88  3915.2  568.48  3962.2  572.19
  3992.5  571.87  4003.7  569.07  4042.8  566.84  4839.2  564.59  4876.7  560.59
  4904.1   562.3  4919.7  559.85  4963.2  562.55  5014.7  561.02    5044  564.35
  5161.9  566.61  5217.7   564.6  5283.6  566.41  5339.3  565.39  5344.4  566.77
  5400.2  565.54  5405.2  567.16  5521.8  566.39  5526.9  567.86    6164  568.78
#Mann= 3 , 0 , 0
  1122.1     .05       0  4839.2     .07       0    5044     .05       0
#XS Ineff= 2 , 0
            3850   566.9
Permanent Ineff=
       F       F
Bank Sta=4839.2,5044
XS Rating Curve= 0 ,0
Exp/Cntr=0.3,0.1

Type RM Length L Ch R = 1 ,119811  ,416,416,416
BEGIN DESCRIPTION:
CHRISTMAS CREEK 101.0
END DESCRIPTION:
XS GIS Cut Line= 3
      3392138.36     10580479.03      3390428.25     10580253.33
      3388866.43       10579108.
#Sta/Elev= 30
  3146.6  569.03    3245  568.42  3696.2  569.84  3701.2  568.32  3926.8  570.84
  3949.8  563.52  3969.9  569.74  4005.4  571.22  4010.4  569.78  4844.3  573.05
  4898.8  571.51  4948.9  565.13  4969.8  561.03  5063.9  563.65    5091  560.29
  5205.7  559.69  5241.5  560.46  5270.8  565.32  5291.6  562.54  5327.1  565.16
  5858.1  568.26  6265.7   574.7  6443.2  579.68  6457.9  580.72  6487.2  587.77
  6522.7  581.61    6552  581.66  6587.5  584.66  6615.3  590.01  6808.3  598.99
#Mann= 4 ,-1 , 0
  3146.6     .05       0    3245     .05       0  4948.9     .07       0
  5270.8     .05       0
#XS Ineff= 1 ,-1
  3866.4  3989.2  571.34
Permanent Ineff=
       F
Bank Sta=4948.9,5270.8
XS Rating Curve= 0 ,0
Exp/Cntr=0.3,0.1

Type RM Length L Ch R = 1 ,119395  ,1338,1338,1338
BEGIN DESCRIPTION:
CHRISTMAS CREEK 100.0
END DESCRIPTION:
XS GIS Cut Line= 4
      3392285.85     10580461.66      3390775.47     10580166.52
      3390211.23     10579385.27      3388587.94     10578378.31
#Sta/Elev= 30
  3240.1  568.66  4097.6  565.48  4160.9  568.57  4171.1  568.15  4191.5  562.14
  4232.3  568.32    4273  565.93  4571.7  564.97  4660.2  562.25    4701  564.81
  4928.4  563.55  5006.9  560.02  5049.9  563.82  5070.8   561.2  5142.8  560.52
  5150.5  562.45  5242.5  564.72  5315.5  561.57  5351.6  563.57  5437.5  562.72
  5479.3  565.27  5686.6  564.99  6165.4  569.31  6405.4  575.13  6694.9  586.43
  7014.8  591.15  7182.6  590.73    7335  596.06  7371.6  599.54    7653  605.18
#Mann= 3 , 0 , 0
  3240.1     .05       0  4928.4     .07       0  5049.9     .05       0
#XS Ineff= 1 ,-1
 3475.56 4231.84  566.96
Permanent Ineff=
       F
Bank Sta=4928.4,5049.9
XS Rating Curve= 0 ,0
Exp/Cntr=0.3,0.1