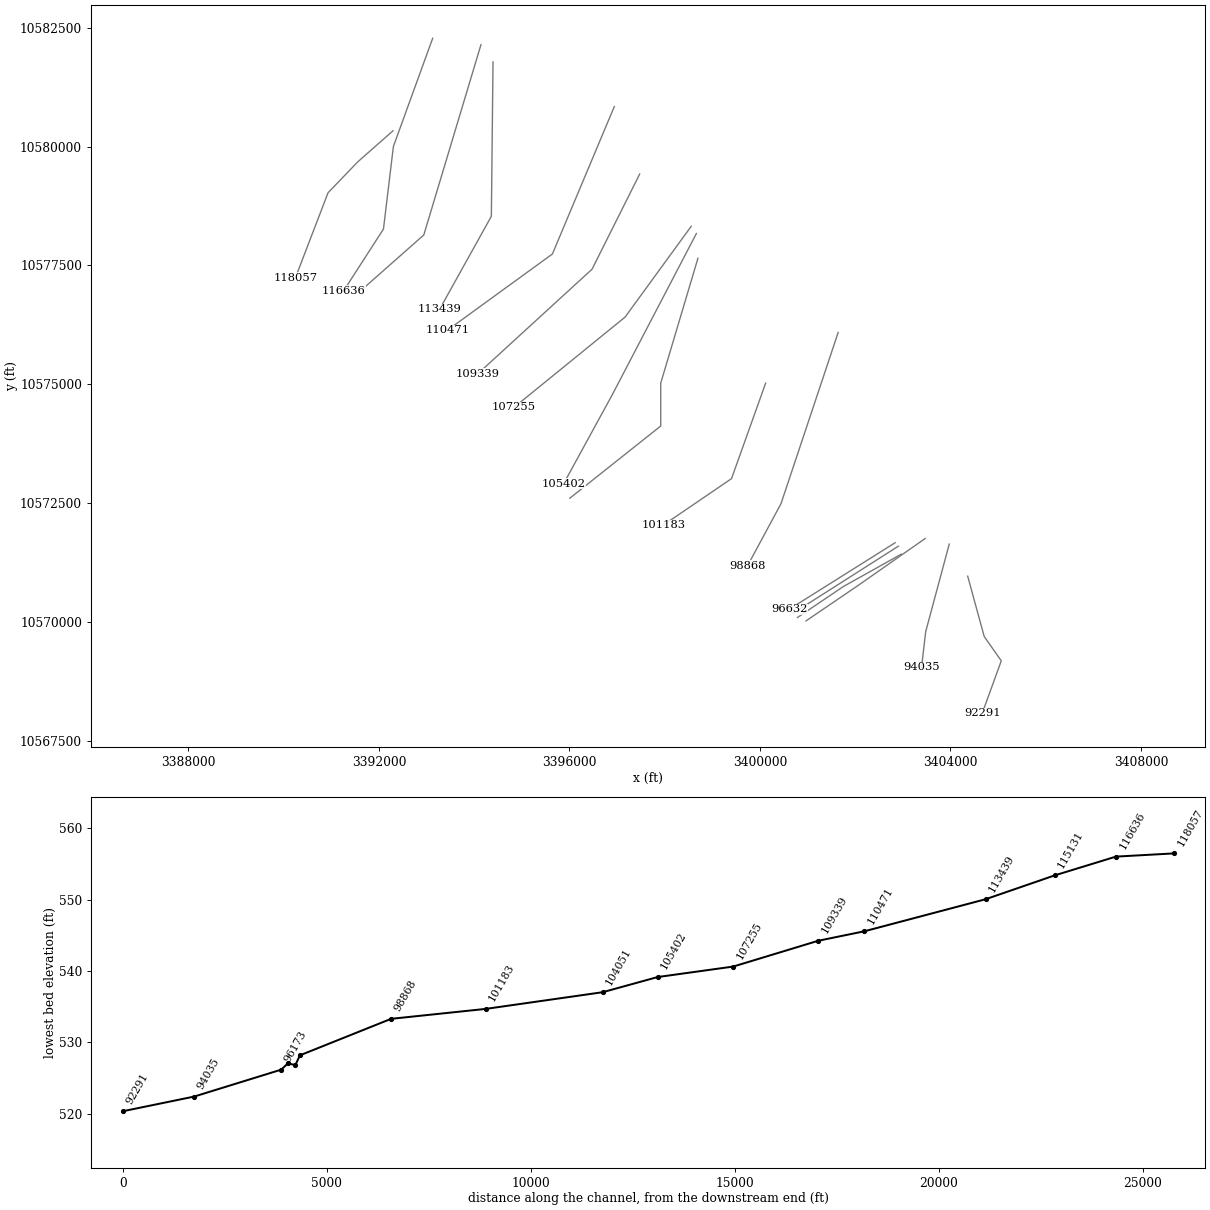
HEC-RAS study CHRISTMAS CREEK.prj: CHRISTMAS CREEK Base Level Engineering

--- CHRISTMAS CREEK.g01 (geometry) --- (continued)

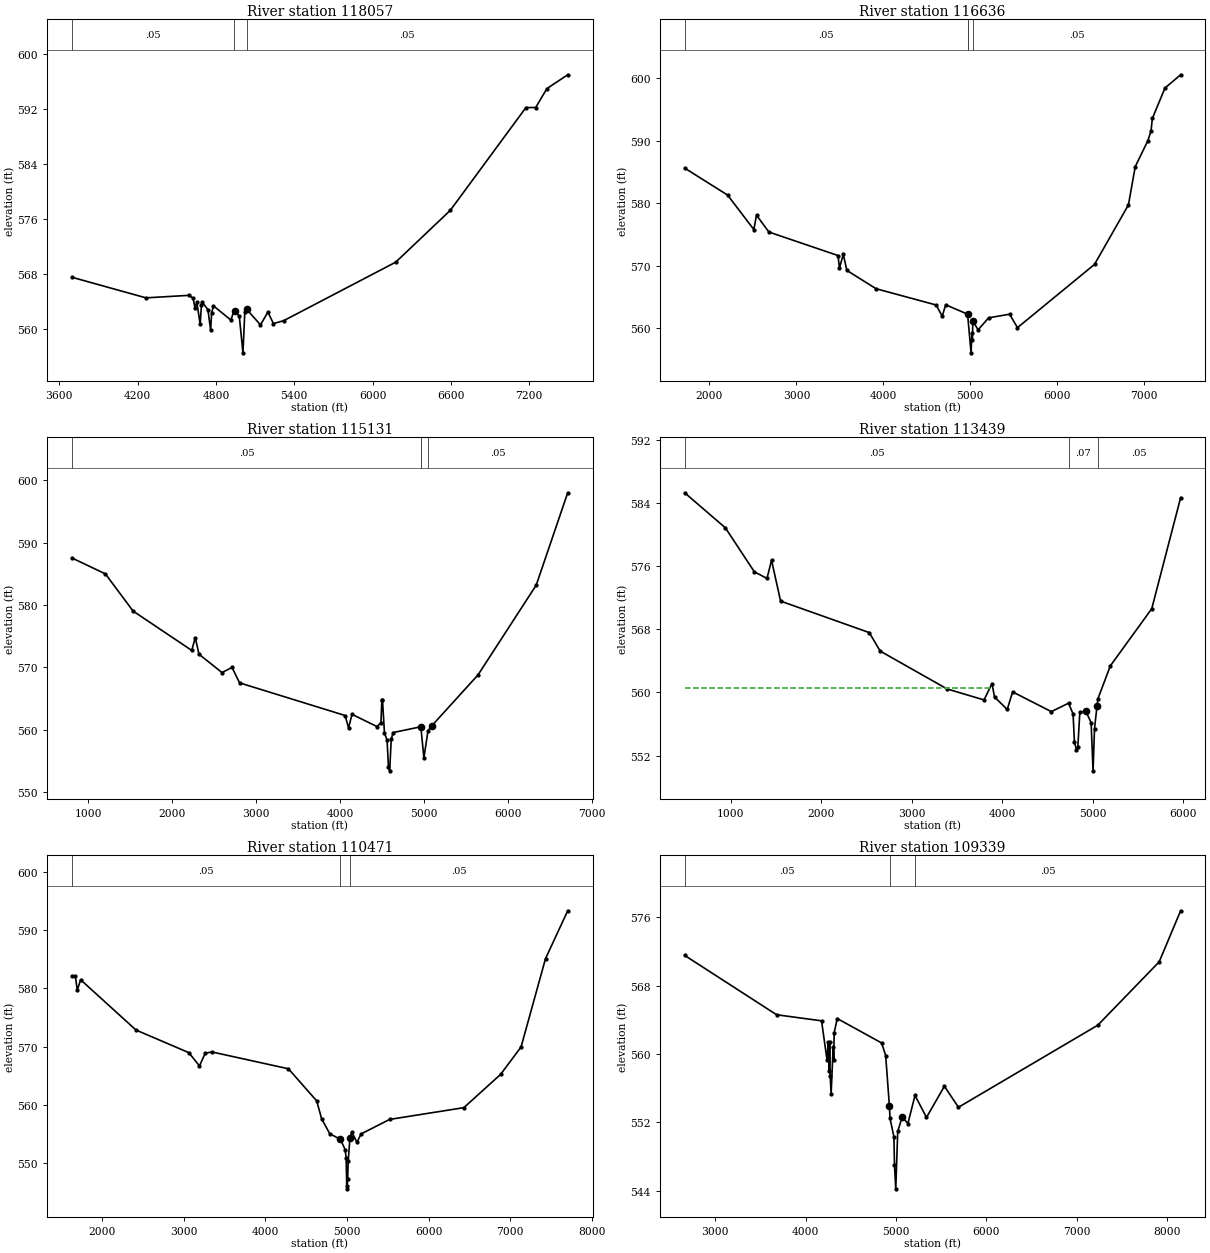
Type RM Length L Ch R = 1 ,118057  ,1421,1421,1421
BEGIN DESCRIPTION:
CHRISTMAS CREEK 98.0
END DESCRIPTION:
XS GIS Cut Line= 4
      3392294.59     10580331.47      3391556.72     10579680.41
      3390931.72     10579029.37      3390246.53     10577242.68
#Sta/Elev= 30
  3695.1  567.49  4263.4  564.49  4589.7  564.85  4624.8  564.47  4639.1  563.02
  4653.3  563.84  4678.9  560.67  4688.7  563.41  4695.6  563.84  4738.1  562.78
  4759.4  559.78  4766.4  562.23  4780.5  563.33  4914.8  561.25  4936.2  562.53
  4943.1  562.56  4978.6  561.85  5006.7  556.49  5021.1  562.43  5035.2  562.83
  5141.2  560.55  5197.8  562.42  5240.3  560.75    5318  561.16  6177.3  569.68
  6595.6  577.22    7175  592.17    7250  592.18  7335.7  594.93  7495.2  596.94
#Mann= 3 ,-1 , 0
  3695.1     .05       0  4936.2     .07       0  5035.2     .05       0
Bank Sta=4943.1,5035.2
XS Rating Curve= 0 ,0
Exp/Cntr=0.3,0.1

Type RM Length L Ch R = 1 ,116636  ,1505,1505,1505
BEGIN DESCRIPTION:
CHRISTMAS CREEK 97.0
END DESCRIPTION:
XS GIS Cut Line= 4
       3393127.9     10582275.91      3392303.25     10580001.59
      3392094.91     10578265.48      3391261.58     10576972.07
#Sta/Elev= 30
  1714.6   585.6  2208.4  581.28  2510.3  575.77  2540.9  578.07  2683.4  575.37
  3478.3  571.61  3495.5  569.63  3539.6  571.79  3580.6  569.23  3916.4   566.3
  4608.6  563.69  4677.6  561.89  4717.9  563.73  4969.7  562.23  5009.8  556.04
  5019.8  559.25  5024.9   558.1  5030.1  561.15  5090.6  559.72  5211.4  561.64
  5453.2  562.22  5543.8  560.07  6430.2  570.19  6820.4  579.71  6898.9  585.83
  7044.2  589.99  7080.5  591.53  7095.6  593.54  7240.9  598.41    7421  600.53
#Mann= 4 ,-1 , 0
  1714.6     .05       0  4969.7     .16       0  4969.7     .07       0
  5030.1     .05       0
Bank Sta=4969.7,5030.1
XS Rating Curve= 0 ,0
Exp/Cntr=0.3,0.1

Type RM Length L Ch R = 1 ,115131  ,1692,1692,1692
BEGIN DESCRIPTION:
CHRISTMAS CREEK 96.0
END DESCRIPTION:
XS GIS Cut Line= 3
      3394142.09     10582141.61      3392942.11     10578141.64
      3391642.14     10576991.67
#Sta/Elev= 30
   802.9  587.53  1203.9  584.97  1533.7  579.01  2233.2   572.7  2274.9  574.76
  2319.3  572.09  2594.2  569.15  2713.4  569.98  2803.1   567.5  4061.1  562.27
    4102  560.29  4143.8  562.46  4440.4   560.5  4488.3   561.1  4498.7  564.69
  4506.6   564.8  4530.1  559.49  4561.4  558.32  4577.9     554  4592.4   553.4
    4611  558.48  4634.5  559.54  4962.5  560.46  4965.8  560.23  5000.3  555.48
  5049.7  559.85  5092.3  560.59  5645.2  568.77  6339.5  583.17  6714.6  597.97
#Mann= 4 ,-1 , 0
   802.9     .05       0  4965.8     .03       0  4965.8     .07       0
  5049.7     .05       0
Bank Sta=4962.5,5092.3
XS Rating Curve= 0 ,0
Exp/Cntr=0.3,0.1

Type RM Length L Ch R = 1 ,113439  ,2968,2968,2968
BEGIN DESCRIPTION:
CHRISTMAS CREEK 94.0
END DESCRIPTION:
XS GIS Cut Line= 3
      3394395.26     10581781.12      3394360.54     10578534.58
       3393276.3     10576582.96
#Sta/Elev= 30
   491.6  585.28   941.1  580.84  1261.1  575.27  1401.1  574.43  1451.1  576.74
  1551.1  571.56  2531.2  567.57  2651.2  565.23  3391.2  560.43  3798.9  559.04
  3887.1  561.12  3914.6  559.41  4055.3  557.84  4114.8  560.06  4542.5  557.56
  4732.5  558.63  4782.7  557.27  4797.7   553.7  4819.4  552.76  4835.4  553.08
  4857.2  557.45  4922.4  557.63  4981.9  556.18  5003.4  550.06  5019.6  555.41
  5047.1  558.24  5057.2  559.19  5194.5  563.36  5652.1   570.6  5970.9  584.66
#Mann= 3 ,-1 , 0
   491.6     .05       0  4732.5     .07       0  5057.2     .05       0
#XS Ineff= 2 , 0
          3862.5  560.56
Permanent Ineff=
       F       F
Bank Sta=4922.4,5047.1
XS Rating Curve= 0 ,0
Exp/Cntr=0.3,0.1

Type RM Length L Ch R = 1 ,110471  ,1132,1132,1132
BEGIN DESCRIPTION:
CHRISTMAS CREEK 93.0
END DESCRIPTION:
XS GIS Cut Line= 3
       3396942.1     10580841.63      3395642.11     10577741.64
      3393442.13     10576141.66
#Sta/Elev= 30
  1624.9  582.06  1668.7   582.1  1692.5  579.71  1733.3   581.5  2412.3  572.86
  3060.8  568.97  3190.5  566.69  3261.9  568.88    3344  569.09  4281.6   566.2
  4628.6  560.68  4688.6  557.62  4789.2  555.03  4918.9  554.09  4977.3  552.31
  4989.5  550.89    4997  546.07  4999.7  545.57  5008.5  547.26  5014.6   550.3
  5035.9  554.24  5058.7  555.34  5122.4  553.55  5171.9     555  5523.2   557.5
  6433.1  559.52  6883.3  565.23  7134.5  569.94  7434.7  585.13  7706.7  593.35
#Mann= 3 , 0 , 0
  1624.9     .05       0  4918.9     .07       0  5035.9     .05       0
Bank Sta=4918.9,5035.9
XS Rating Curve= 0 ,0
Exp/Cntr=0.3,0.1

Type RM Length L Ch R = 1 ,109339  ,2084,2084,2084
BEGIN DESCRIPTION:
CHRISTMAS CREEK 91.0
END DESCRIPTION:
XS GIS Cut Line= 3
      3397474.66     10579421.85      3396474.66     10577421.85
      3394075.86     10575222.95
#Sta/Elev= 30
  2661.7  571.54  3679.3   564.6  4176.8  563.89  4238.3  559.25  4249.5  561.37
  4260.7  558.01  4266.3  561.43  4271.9  557.48    4283  555.36  4305.4  560.87
    4311  559.33  4316.6  562.47  4350.1  564.16    4842   561.3  4886.8  559.82
  4928.3  553.87  4935.1  552.48  4977.7  550.33  4984.4  546.98  4998.4  544.24
  5020.2  550.97  5069.5  552.63    5133  551.88  5211.4  555.17  5338.4  552.59
  5536.9  556.24  5692.3  553.78  7235.1  563.38  7914.6  570.79  8151.9  576.76
#Mann= 3 ,-1 , 0
  2661.7     .05       0  4935.1     .07       0  5211.4     .05       0
Bank Sta=4928.3,5069.5
XS Rating Curve= 0 ,0
Exp/Cntr=0.3,0.1

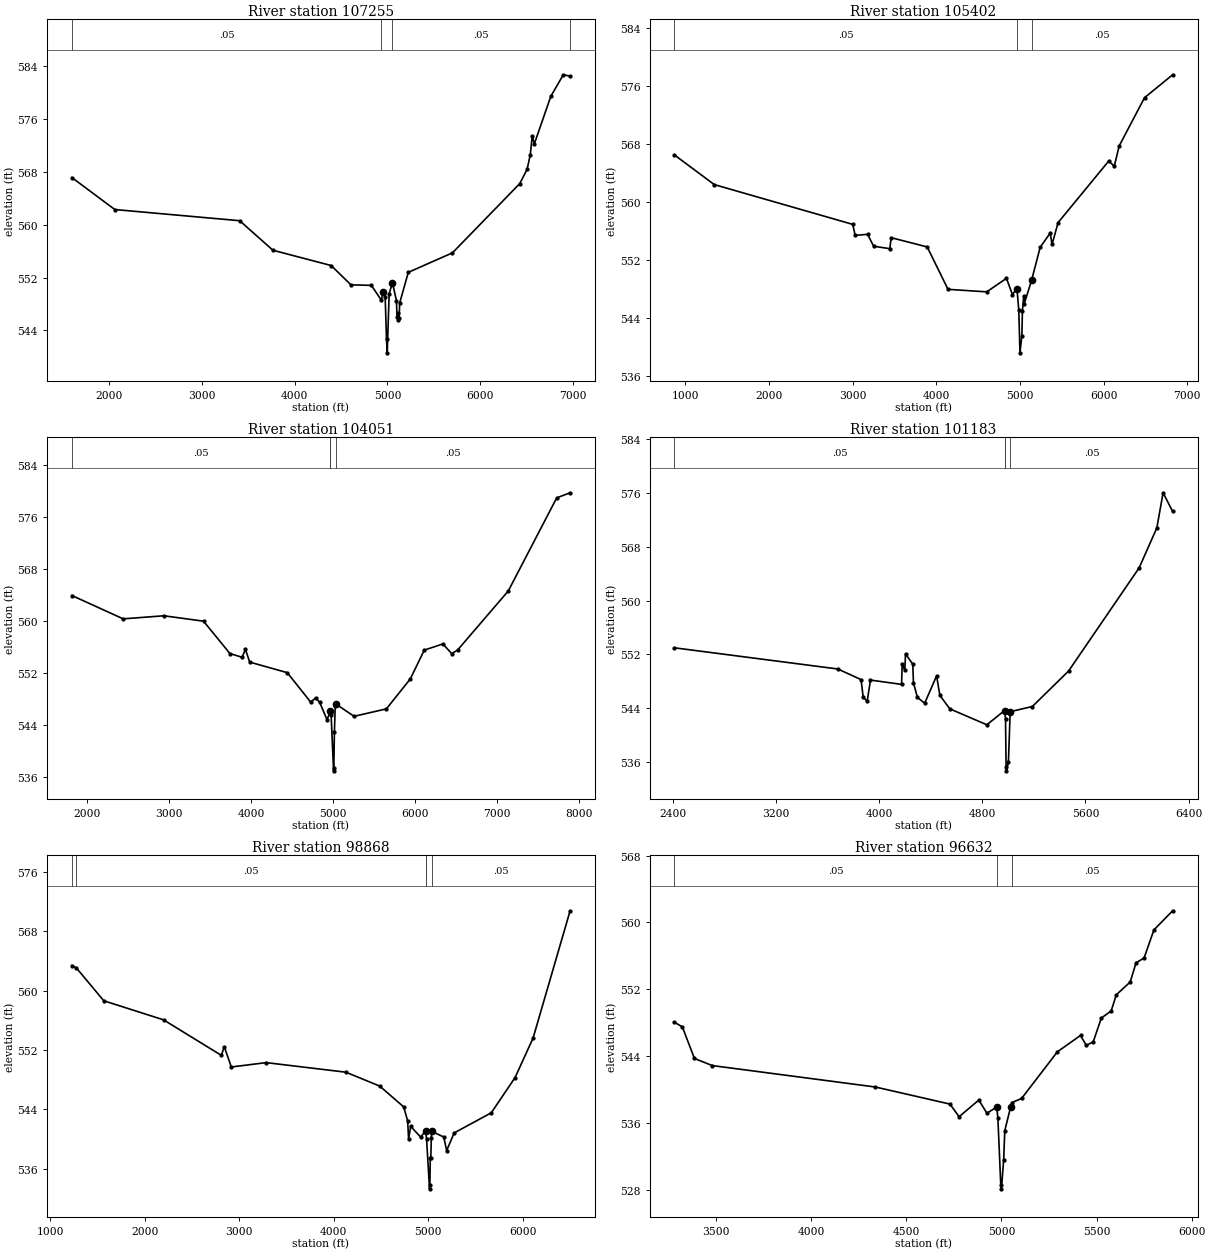
Type RM Length L Ch R = 1 ,107255  ,1853,1853,1853
BEGIN DESCRIPTION:
CHRISTMAS CREEK 90.0
END DESCRIPTION:
XS GIS Cut Line= 3
      3398556.83      10578324.1      3397167.94     10576414.38
      3394835.03     10574515.49
#Sta/Elev= 30
  1599.7  567.14  2062.4   562.3    3408  560.61  3766.6  556.14  4394.1  553.83
  4606.9  550.91  4827.4  550.83  4934.4  548.59  4955.2  549.89    4976  549.14
  4990.4  542.64  4998.1  540.62  5019.1  549.55  5054.3  551.25  5097.4  548.52
  5103.9  546.05  5111.8   545.6  5118.2  546.68  5126.2  545.85  5132.6  548.17
  5225.3   552.8  5701.4  555.75  6426.8  566.23  6505.1  568.37  6540.2   570.6
  6561.1  573.47  6583.3  572.22  6760.7  579.41  6895.5  582.69  6969.1  582.49
#Mann= 4 ,-1 , 0
  1599.7     .05       0  4934.4     .07       0  5054.3     .05       0
  6969.1     .05       0
Bank Sta=4955.2,5054.3
XS Rating Curve= 0 ,0
Exp/Cntr=0.3,0.1

Type RM Length L Ch R = 1 ,105402  ,1351,1351,1351
BEGIN DESCRIPTION:
CHRISTMAS CREEK 89.0
END DESCRIPTION:
XS GIS Cut Line= 3
      3398665.34     10578172.19      3396907.53     10574797.63
      3395876.92     10572909.99
#Sta/Elev= 30
     870  566.51  1346.1  562.41  3001.7  556.91  3030.3  555.39  3179.4  555.53
  3251.3  553.89  3444.5  553.55    3461  555.07  3891.7  553.79  4140.5  547.93
  4602.8  547.58  4839.2  549.45  4910.3  547.21  4964.4  548.04  4986.3   545.1
  5000.5  539.15  5023.6  541.53  5029.9  544.98  5046.1  547.03  5051.7  545.94
  5139.1  549.16  5242.5  553.75  5362.1  555.71  5383.9  554.13  5456.5  557.16
  6060.4  565.65  6128.7  564.97  6185.7  567.73  6489.5  574.42  6825.6  577.59
#Mann= 3 , 0 , 0
     870     .05       0  4964.4     .07       0  5139.1     .05       0
Bank Sta=4964.4,5139.1
XS Rating Curve= 0 ,0
Exp/Cntr=0.3,0.1

Type RM Length L Ch R = 1 ,104051  ,2868,2868,2868
BEGIN DESCRIPTION:
CHRISTMAS CREEK 87.0
END DESCRIPTION:
XS GIS Cut Line= 4
      3398697.89     10577651.37      3397916.64     10575025.49
      3397916.64     10574124.88      3396007.52     10572606.26
#Sta/Elev= 30
  1811.9  563.93  2437.6  560.35    2935  560.82  3418.3  559.99  3739.9  555.03
  3888.3  554.45  3929.6  555.66  3981.7  553.71  4440.1  552.09  4725.4  547.58
  4785.4   548.2  4835.4  547.55  4925.4  544.86  4965.4  546.14  4975.4  545.59
  5005.1  537.02  5008.4  537.52  5015.4  543.02  5025.4  546.91  5035.4  547.25
  5255.4  545.39  5649.6  546.53  5942.2  551.14    6112  555.55  6339.6   556.5
  6446.7  555.01  6518.5  555.56  7137.1  564.63  7728.2  578.92  7891.6   579.7
#Mann= 4 ,-1 , 0
  1811.9     .05       0  4965.4     .16       0  4965.4     .07       0
  5035.4     .05       0
Bank Sta=4965.4,5035.4
XS Rating Curve= 0 ,0
Exp/Cntr=0.3,0.1

Type RM Length L Ch R = 1 ,101183  ,2315,2315,2315
BEGIN DESCRIPTION:
CHRISTMAS CREEK 85.0
END DESCRIPTION:
XS GIS Cut Line= 3
      3400119.33     10575025.48      3399403.19     10573018.11
      3397970.91     10572041.56
#Sta/Elev= 30
  2412.1  552.98  3679.6  549.83  3860.1  548.25  3876.5  545.62  3907.3  545.02
  3932.8  548.18    4174  547.54  4179.3   550.6  4199.5  549.62  4204.8  552.09
  4261.1  550.54  4266.4  547.78  4297.2   545.6  4353.5  544.74  4445.9  548.81
  4471.4   545.9  4548.4   543.9  4835.6  541.53  4973.2  543.65  4980.4  542.46
  4985.1  535.18  4987.9  534.68  5003.1  536.02  5016.7  543.48  5188.6  544.25
  5469.8  549.53  6017.3  564.88  6154.4  570.82  6202.9  576.04  6276.9  573.26
#Mann= 4 ,-1 , 0
  2412.1     .05       0  4973.2     .16       0  4973.2     .07       0
  5016.7     .05       0
#XS Ineff= 2 , 0
         4409.09   546.4
Permanent Ineff=
       F       F
Bank Sta=4973.2,5016.7
XS Rating Curve= 0 ,0
Exp/Cntr=0.3,0.1

Type RM Length L Ch R = 1 ,98868   ,2236,2236,2236
BEGIN DESCRIPTION:
CHRISTMAS CREEK 83.0
END DESCRIPTION:
XS GIS Cut Line= 3
       3401642.1     10576091.63      3400442.11     10572491.64
      3399742.11     10571191.64
#Sta/Elev= 30
  1229.6  563.37  1275.9  563.06  1566.9  558.62  2199.4  556.05  2810.7  551.27
  2842.3  552.43  2916.1   549.7  3285.1  550.29  4128.3     549  4486.7  547.13
  4739.7  544.33  4781.9  542.45  4792.4  539.98  4813.5  541.71  4918.9  540.27
  4971.6  541.06  4982.2  540.01  5013.5  533.29  5016.8  533.79  5021.7  537.51
  5027.2  537.51  5032.4  540.12  5038.1  541.03  5163.9  540.27  5194.7  538.45
  5274.2  540.82  5666.8  543.53  5918.3  548.27  6109.8  553.62  6500.8  570.74
#Mann= 5 ,-1 , 0
  1229.6     .08       0  1275.9     .05       0  4971.6     .16       0
  4971.6     .07       0  5038.1     .05       0
Bank Sta=4971.6,5038.1
XS Rating Curve= 0 ,0
Exp/Cntr=0.3,0.1

Type RM Length L Ch R = 1 ,96632   ,112,112,112
BEGIN DESCRIPTION:
CHRISTMAS CREEK 80.2
END DESCRIPTION:
XS GIS Cut Line= 2
      3402838.88     10571670.98      3400621.31     10570275.89
#Sta/Elev= 30
  3280.1  548.08  3321.7  547.53  3385.3  543.75  3479.5   542.9  4336.8  540.34
  4728.9   538.3  4777.2  536.79  4880.8  538.78  4923.2  537.21    4975  537.94
  4980.9  536.68  4996.2  528.67  4999.8  528.17  5011.5  531.67  5017.4  535.13
    5048  537.95  5053.9  538.47  5105.7  538.97  5294.1  544.55  5415.5   546.5
    5446  545.31  5482.5  545.74    5525  548.58  5576.8  549.43  5603.9  551.36
  5676.9  552.89  5707.5  555.18  5749.9  555.76  5801.7  559.12    5900   561.4
#Mann= 3 ,-1 , 0
  3280.1     .05       0    4975     .07       0  5053.9     .05       0
Bank Sta=4975,5048
XS Rating Curve= 0 ,0
Exp/Cntr=0.3,0.1

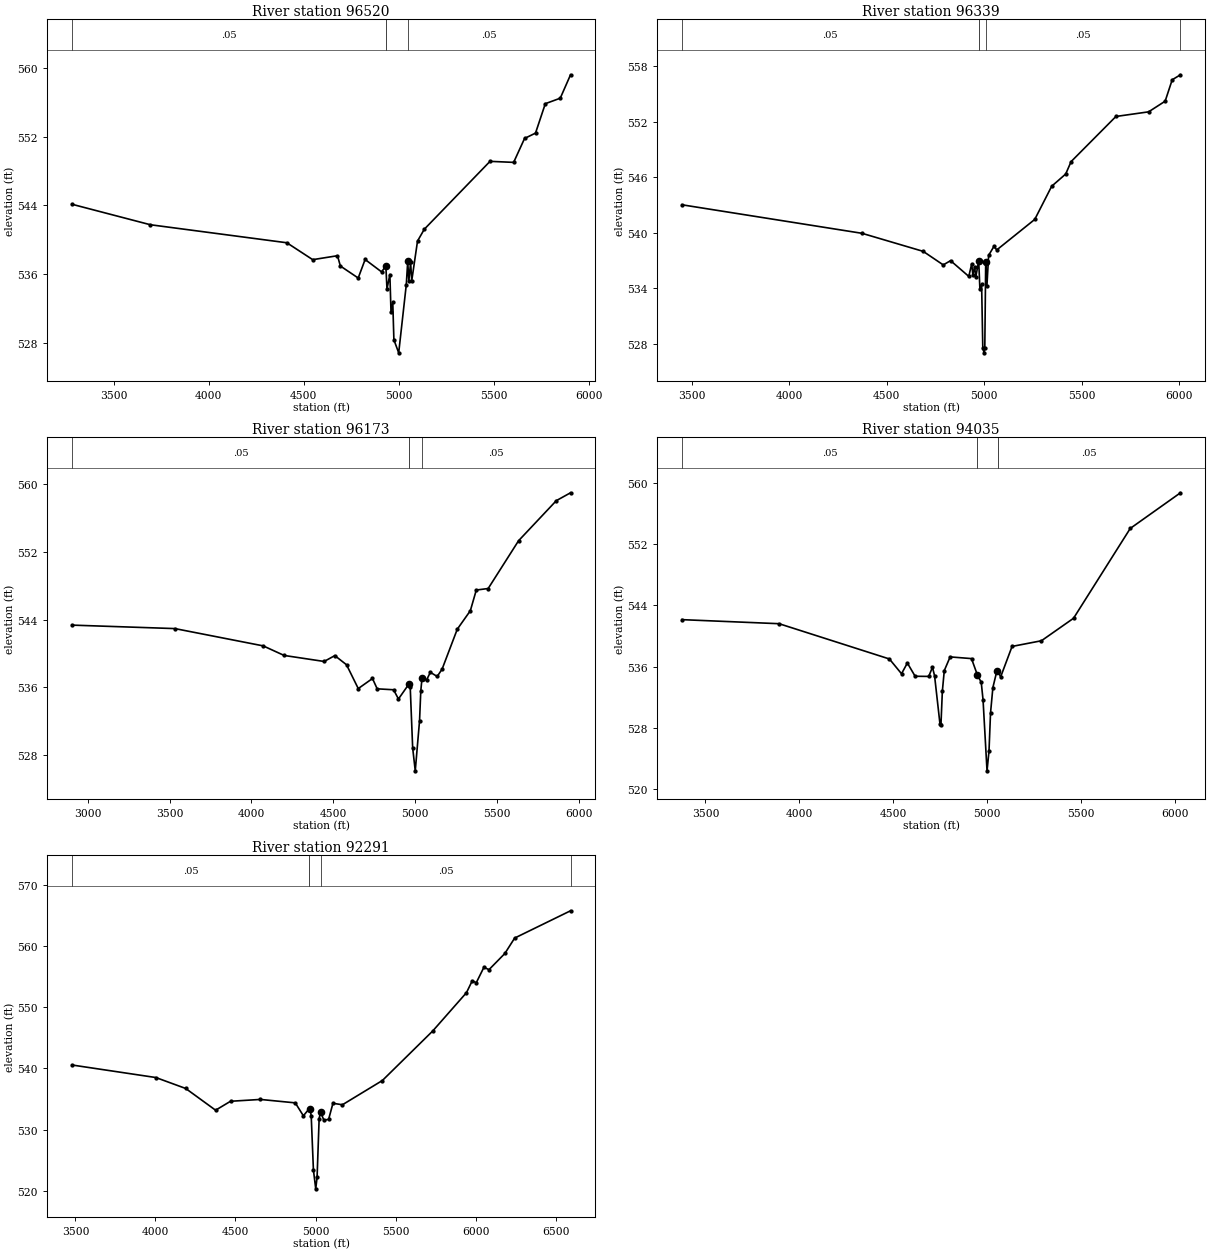
Type RM Length L Ch R = 1 ,96520   ,181,181,181
BEGIN DESCRIPTION:
CHRISTMAS CREEK 80.1
END DESCRIPTION:
XS GIS Cut Line= 2
      3402906.52     10571598.02      3400693.03     10570186.59
#Sta/Elev= 30
  3279.3  544.12  3692.4  541.73  4410.9  539.63  4547.1  537.66  4677.5  538.12
  4692.7  536.92  4786.6  535.52    4823  537.68  4909.4  536.24  4932.2  536.91
  4938.1  534.24  4953.3  535.93  4959.3  531.57  4968.6  532.67  4974.5  528.32
  4999.8   526.8  5039.8  534.75  5047.3  537.46  5053.2  535.18  5062.5  537.37
  5068.4   535.2  5098.9  539.83  5134.7  541.21  5480.6  549.12    5605     549
  5662.5  551.79  5720.1  552.41  5771.7  555.84  5850.4  556.48  5904.5  559.21
#Mann= 4 ,-1 , 0
  3279.3     .05       0  4932.2     .16       0  4932.2     .07       0
  5047.3     .05       0
Bank Sta=4932.2,5047.3
XS Rating Curve= 0 ,0
Exp/Cntr=0.3,0.1

Type RM Length L Ch R = 1 ,96339   ,166,166,166
BEGIN DESCRIPTION:
CHRISTMAS CREEK 80.5
END DESCRIPTION:
XS GIS Cut Line= 3
      3402969.03     10571431.36       3401750.3     10570749.08
      3400786.91     10570098.14
#Sta/Elev= 30
  3448.1  543.03  4372.9  539.95    4687     538  4789.8  536.54  4827.4     537
  4920.9   535.3  4935.8  536.65  4941.8  535.47  4950.8  536.34  4956.8  535.23
  4971.8  536.97  4977.8  533.99  4986.7  534.44  4992.8  527.55  4999.8  527.05
    5003  527.55  5007.7  536.81  5013.8  534.23  5022.7  537.57  5049.7  538.53
  5064.7  538.16  5259.5  541.45  5346.4  545.03  5418.3  546.35  5446.1  547.69
  5676.1  552.56  5843.9  553.06  5928.8  554.21    5965  556.52  6007.5  557.06
#Mann= 5 ,-1 , 0
  3448.1     .05       0  4971.8     .16       0  4971.8     .07       0
  5007.7     .05       0  6007.5     .05       0
Bank Sta=4971.8,5007.7
XS Rating Curve= 0 ,0
Exp/Cntr=0.3,0.1

Type RM Length L Ch R = 1 ,96173   ,2138,2138,2138
BEGIN DESCRIPTION:
CHRISTMAS CREEK 78.1
END DESCRIPTION:
XS GIS Cut Line= 3
      3403469.07     10571759.51      3402057.59     10570769.91
      3400966.56     10570026.97
#Sta/Elev= 30
  2903.9  543.36  3532.6  542.95  4071.3  540.91  4199.4  539.78  4443.5  539.07
  4508.8  539.76  4580.3  538.68  4651.9  535.87  4738.7  537.06  4767.4  535.84
  4867.4  535.73  4897.3  534.64    4961   536.4  4969.1  536.05    4984  528.87
  4999.8  526.16    5026  532.07  5033.6   535.6  5040.9  537.06  5069.9  536.92
  5091.8  537.79  5133.7   537.3  5163.6  538.16  5256.4  542.88  5336.1  545.06
  5372.4   547.5  5444.9  547.68  5630.5  553.32  5860.9  558.05  5947.7  558.98
#Mann= 4 ,-1 , 0
  2903.9     .05       0    4961     .16       0    4961     .07       0
  5040.9     .05       0
Bank Sta=4961,5040.9
XS Rating Curve= 0 ,0
Exp/Cntr=0.3,0.1

Type RM Length L Ch R = 1 ,94035   ,1744,1744,1744
BEGIN DESCRIPTION:
CHRISTMAS CREEK 76.0
END DESCRIPTION:
XS GIS Cut Line= 3
      3403974.87     10571641.72      3403480.07     10569801.42
      3403393.37      10569055.8
#Sta/Elev= 30
  3374.1  542.14  3891.9  541.61  4479.7     537  4544.3  535.07  4575.4  536.47
  4616.8  534.74  4689.3  534.72  4709.1  535.92  4720.3  534.82  4749.1  528.51
  4754.3  528.37  4761.8  532.78  4772.1  535.48  4803.2  537.27  4917.1  537.05
  4948.9  534.88  4968.9  533.96  4978.6  531.66  4999.8  522.38  5010.3  524.96
  5018.5  529.95    5031  533.27  5051.7  535.37  5058.5  535.34  5072.4  534.66
  5133.2  538.64  5289.6  539.38  5460.7  542.32  5762.8  554.06  6030.4  558.72
#Mann= 5 ,-1 , 0
  3374.1     .05       0  4948.9     .16       0  4948.9     .07       0
  5058.5     .16       0  5058.5     .05       0
Bank Sta=4948.9,5051.7
XS Rating Curve= 0 ,0
Exp/Cntr=0.3,0.1

Type RM Length L Ch R = 1 ,92291   ,986,986,986
BEGIN DESCRIPTION:
CHRISTMAS CREEK 74.0
END DESCRIPTION:
XS GIS Cut Line= 4
      3404361.94     10570967.38      3404709.18      10569697.8
      3405067.25     10569187.82      3404666.45     10568082.91
#Sta/Elev= 30
  3478.3  540.57  4002.6  538.52  4189.2  536.73  4375.8  533.18  4469.1  534.64
  4655.8  534.94  4873.6  534.38  4924.1  532.27  4959.8  533.39    4966  533.38
  4973.1  532.27  4986.9  523.42  5001.4  520.33  5009.8   522.2  5022.6  531.78
  5031.3   532.9  5052.2  531.55  5081.9  531.69  5108.9  534.31  5168.1  534.07
  5417.5  538.03  5732.7  546.14    5943  552.39    5979  554.33  6004.3  554.02
  6051.8  556.53  6083.7  556.15  6182.7  558.79  6243.9  561.31    6593  565.77
#Mann= 5 ,-1 , 0
  3478.3     .05       0  4959.8     .16       0  4959.8     .05       0
  5031.3     .05       0    6593     .05       0
Bank Sta=4966,5031.3
XS Rating Curve= 0 ,0
Exp/Cntr=0.3,0.1