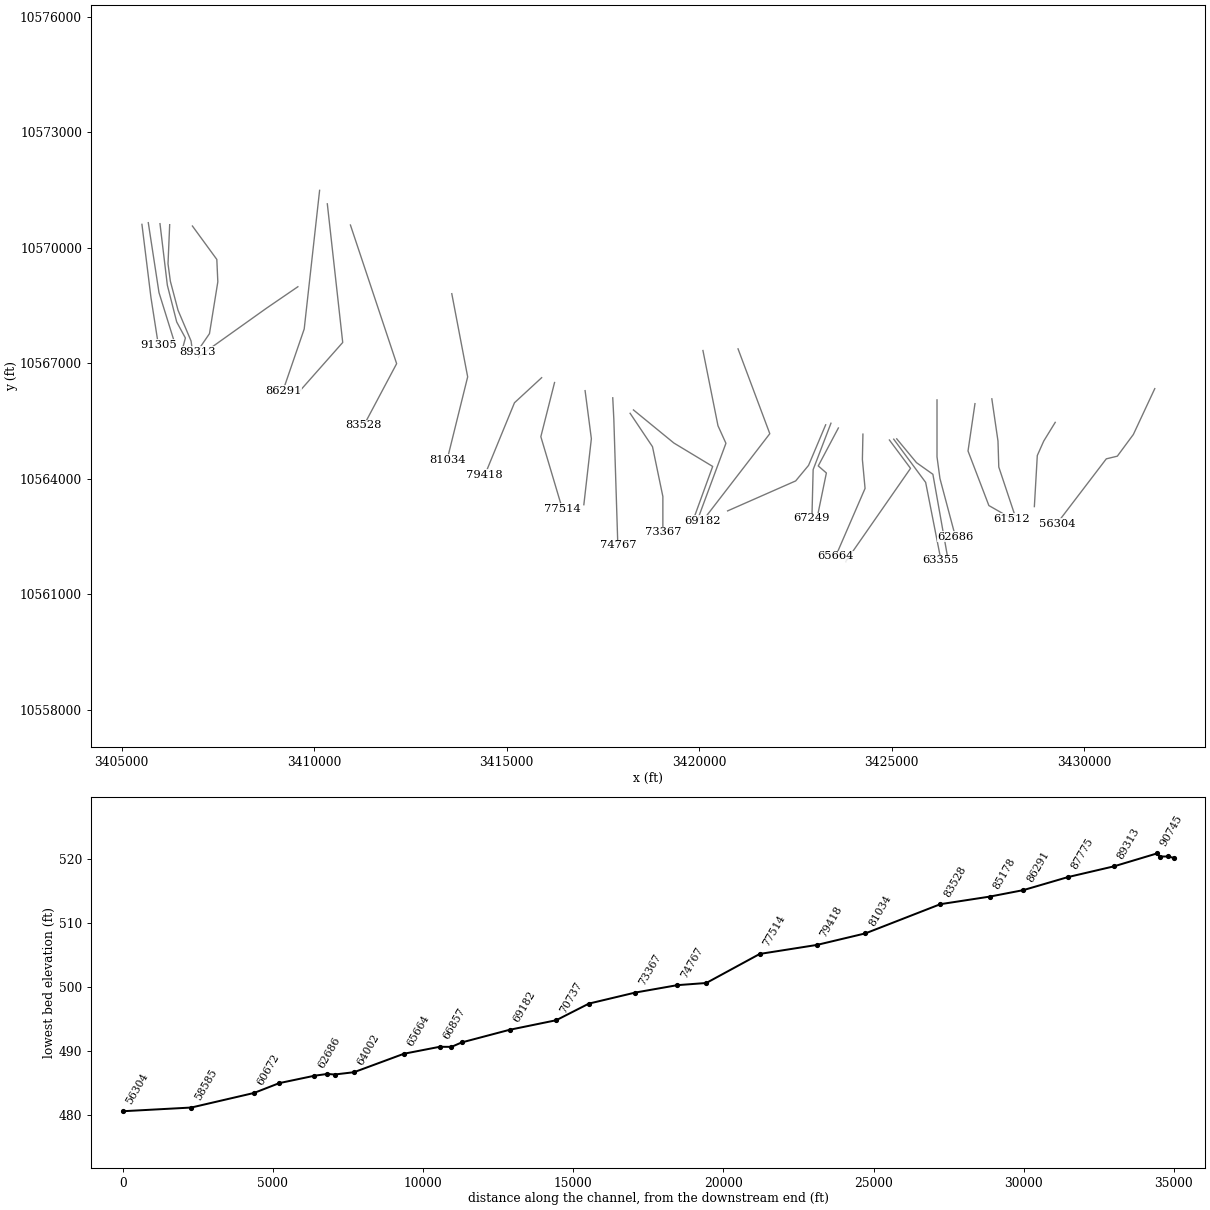
HEC-RAS study CHRISTMAS CREEK.prj: CHRISTMAS CREEK Base Level Engineering

--- CHRISTMAS CREEK.g01 (geometry) --- (continued)

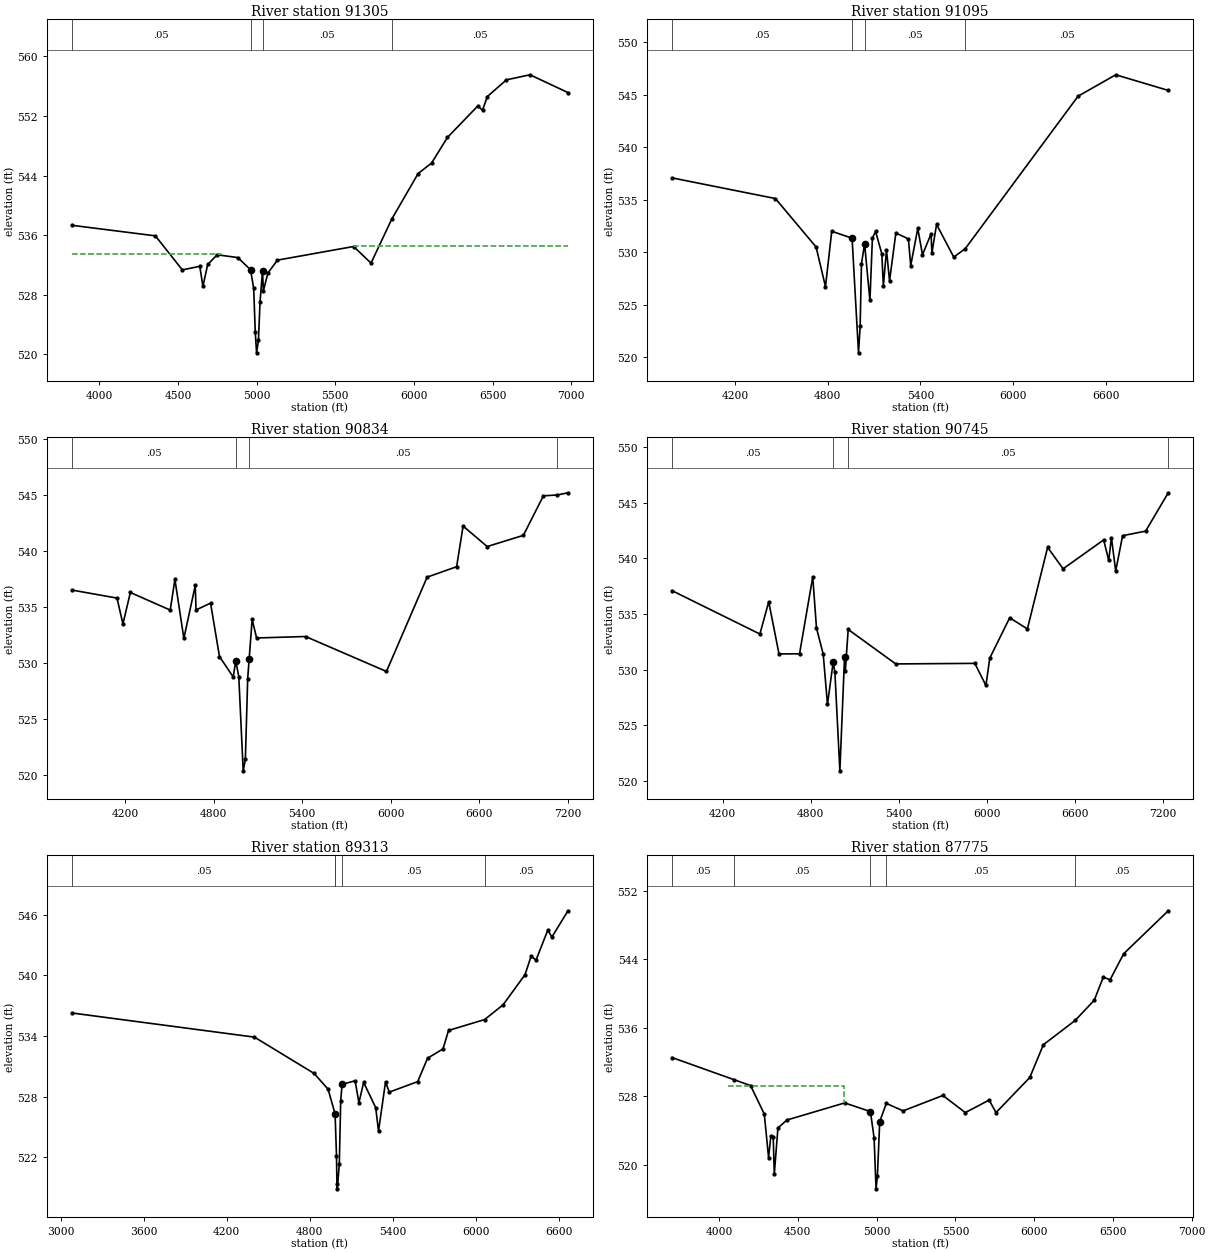
Type RM Length L Ch R = 1 ,91305   ,210,210,210
BEGIN DESCRIPTION:
CHRISTMAS CREEK 71.3
END DESCRIPTION:
XS GIS Cut Line= 3
      3405528.68     10570608.71      3405763.06     10568707.67
       3405953.8     10567485.19
#Sta/Elev= 30
  3825.8  537.32  4356.9   535.9  4528.1  531.33    4639  531.81  4659.1  529.13
  4689.4  532.06  4749.8  533.36  4880.8  532.98  4961.8  531.35  4981.6  528.83
  4991.6  523.01  4999.8  520.19  5011.8  521.87  5021.9  526.98  5037.9  531.21
  5042.9  528.51  5072.2  530.92  5132.7  532.64  5616.3  534.47  5727.2  532.24
  5858.7  538.14  6026.3  544.26  6111.7  545.67  6212.9  549.12  6405.2  553.33
  6435.6  552.77  6465.9   554.6  6587.4  556.85  6737.3  557.53  6978.5  555.14
#Mann= 4 ,-1 , 0
  3825.8     .05       0  4961.8     .07       0  5037.9     .05       0
  5858.7     .05       0
#XS Ineff= 2 , 0
         4774.72  533.42 5616.34          534.55
Permanent Ineff=
       F       F
Bank Sta=4961.8,5037.9
XS Rating Curve= 0 ,0
Exp/Cntr=0.3,0.1

Type RM Length L Ch R = 1 ,91095   ,261,261,261
BEGIN DESCRIPTION:
CHRISTMAS CREEK 71.2
END DESCRIPTION:
XS GIS Cut Line= 3
      3405693.61      10570652.1      3405971.39     10568837.88
      3406379.39     10567527.08
#Sta/Elev= 30
  3794.3  537.09  4462.5  535.12  4725.5   530.5  4786.2  526.72  4826.7     532
  4958.2  531.34  4999.8  520.41  5010.3  522.93  5018.9   528.9  5039.1   530.8
  5073.6   525.4  5089.7  531.35  5109.9  531.99  5150.4  529.86  5160.5  526.77
  5180.7  530.22  5200.4  527.26  5241.4  531.84  5322.4  531.27  5337.3  528.73
  5383.1  532.27  5413.4  529.76  5469.1  531.76  5474.2  529.92  5504.5  532.65
  5615.7  529.54  5689.9  530.34  6419.6  544.88  6663.1  546.92  7002.5  545.43
#Mann= 4 ,-1 , 0
  3794.3     .05       0  4958.2     .07       0  5039.1     .05       0
  5689.9     .05       0
Bank Sta=4958.2,5039.1
XS Rating Curve= 0 ,0
Exp/Cntr=0.3,0.1

Type RM Length L Ch R = 1 ,90834   ,89,89,89
BEGIN DESCRIPTION:
CHRISTMAS CREEK 71.6
END DESCRIPTION:
XS GIS Cut Line= 5
      3405997.44     10570626.02       3406188.4     10569028.85
      3406431.46     10568073.99      3406657.15     10567657.32
      3406579.04     10567370.91
#Sta/Elev= 30
  3837.4  536.54    4144  535.82  4184.2  533.51  4234.6  536.32    4505  534.75
  4536.7  537.49  4597.4  532.22  4674.8  536.95  4679.8  534.76  4778.4  535.37
  4838.9   530.6  4932.1  528.78  4949.6  530.21  4969.8  528.81  4999.8   520.4
  5014.5  521.43  5030.2  528.63  5040.3   530.4  5060.4  533.91  5090.6  532.26
    5423  532.39  5971.1  529.27  6247.1  537.69  6447.1  538.62  6490.8  542.25
  6654.4  540.42  6899.8  541.42  7035.4  544.95  7128.4  545.02    7202  545.22
#Mann= 4 ,-1 , 0
  3837.4     .05       0  4949.6     .07       0  5040.3     .05       0
  7128.4     .05       0
#XS Ineff= 2 , 0
                         5068.18           532.8
Permanent Ineff=
       F       F
Bank Sta=4949.6,5040.3
XS Rating Curve= 0 ,0
Exp/Cntr=0.3,0.1

Type RM Length L Ch R = 1 ,90745   ,1432,1432,1432
BEGIN DESCRIPTION:
CHRISTMAS CREEK 71.9
END DESCRIPTION:
XS GIS Cut Line= 6
      3406249.17     10570600.04      3406205.76     10569584.41
      3406266.53     10569133.02      3406466.18     10568377.81
      3406804.72      10567579.2      3406839.45     10567318.78
#Sta/Elev= 30
  3855.6   537.1  4454.5   533.2  4514.6   536.1  4584.7  531.41  4724.8  531.42
  4814.9  538.34  4840.3  533.74  4886.1   531.4  4915.3  526.86  4953.9  530.66
  4965.8  529.75  4999.8  520.89  5031.7  531.13  5036.8  529.89  5056.6  533.61
  5380.8  530.51  5920.3  530.56  5995.6  528.57  6022.1  531.04  6157.9  534.66
  6278.4  533.66  6416.4     541  6521.9  539.07  6798.6  541.67  6833.1  539.82
  6851.4  541.88  6880.5  538.87  6927.8  542.05  7084.7  542.46  7238.9  545.91
#Mann= 4 ,-1 , 0
  3855.6     .05       0  4953.9     .07       0  5056.6     .05       0
  7238.9     .05       0
#XS Ineff= 2 , 0
       0  4750.2  533.13 5067.13       0  533.13
Permanent Ineff=
       T       T
Bank Sta=4953.9,5031.7
XS Rating Curve= 0 ,0
Exp/Cntr=0.3,0.1

Type RM Length L Ch R = 1 ,89313   ,1538,1538,1538
BEGIN DESCRIPTION:
CHRISTMAS CREEK 71.7
END DESCRIPTION:
XS GIS Cut Line= 5
      3406839.45     10570565.31      3407473.13     10569697.25
      3407499.17     10569115.66      3407282.15     10567770.17
      3406960.99     10567301.44
#Sta/Elev= 30
  3079.7  536.27  4400.3  533.88  4831.8  530.29    4933  528.73  4983.8  526.28
  4993.9  522.12    4997  519.37  4999.8  518.87  5014.2  521.29  5024.3  527.58
  5034.4  529.21  5128.5  529.56    5156  527.39  5190.3   529.4  5277.5   526.9
  5297.8  524.58  5348.4  529.45  5375.7  528.44  5581.4  529.48  5652.3  531.79
  5763.7  532.71  5804.3  534.54  6065.5  535.62  6198.8  537.08  6357.2  540.06
  6400.8  541.87  6437.1  541.51    6522  544.47  6551.5  543.78  6667.7  546.38
#Mann= 5 ,-1 , 0
  3079.7     .05       0  4983.8     .16       0  4983.8     .07       0
  5034.4     .05       0  6065.5     .05       0
Bank Sta=4983.8,5034.4
XS Rating Curve= 0 ,0
Exp/Cntr=0.3,0.1

Type RM Length L Ch R = 1 ,87775   ,1484,1484,1484
BEGIN DESCRIPTION:
CHRISTMAS CREEK 70.0
END DESCRIPTION:
XS GIS Cut Line= 3
       3409577.8     10568988.75       3408765.3      10568433.2
      3407001.65     10567176.42
#Sta/Elev= 30
  3701.4  532.52  4092.4  529.95  4200.1  529.24  4286.8  525.92    4314  520.84
  4328.7  523.35  4343.6  523.24  4350.3  518.89  4373.4  524.29  4430.3  525.22
  4797.2  527.22  4960.7  526.21    4984  523.12  4996.3  517.18  5004.9  518.66
  5019.7  525.04  5061.5  527.16  5168.5  526.29  5420.5  528.09  5563.1  526.09
  5714.3  527.55  5757.9  526.09  5972.4  530.19  6058.5  534.02  6260.1  536.85
  6381.8  539.22  6438.4   541.9  6482.4  541.62  6568.3  544.65  6851.3  549.67
#Mann= 5 ,-1 , 0
  3701.4     .05       0  4092.4     .05       0  4960.7     .07       0
  5061.5     .05       0  6260.1     .05       0
#XS Ineff= 1 ,-1
 4059.44 4795.08529.1756
Permanent Ineff=
       F
Bank Sta=4960.7,5019.7
XS Rating Curve= 0 ,0
Exp/Cntr=0.3,0.1

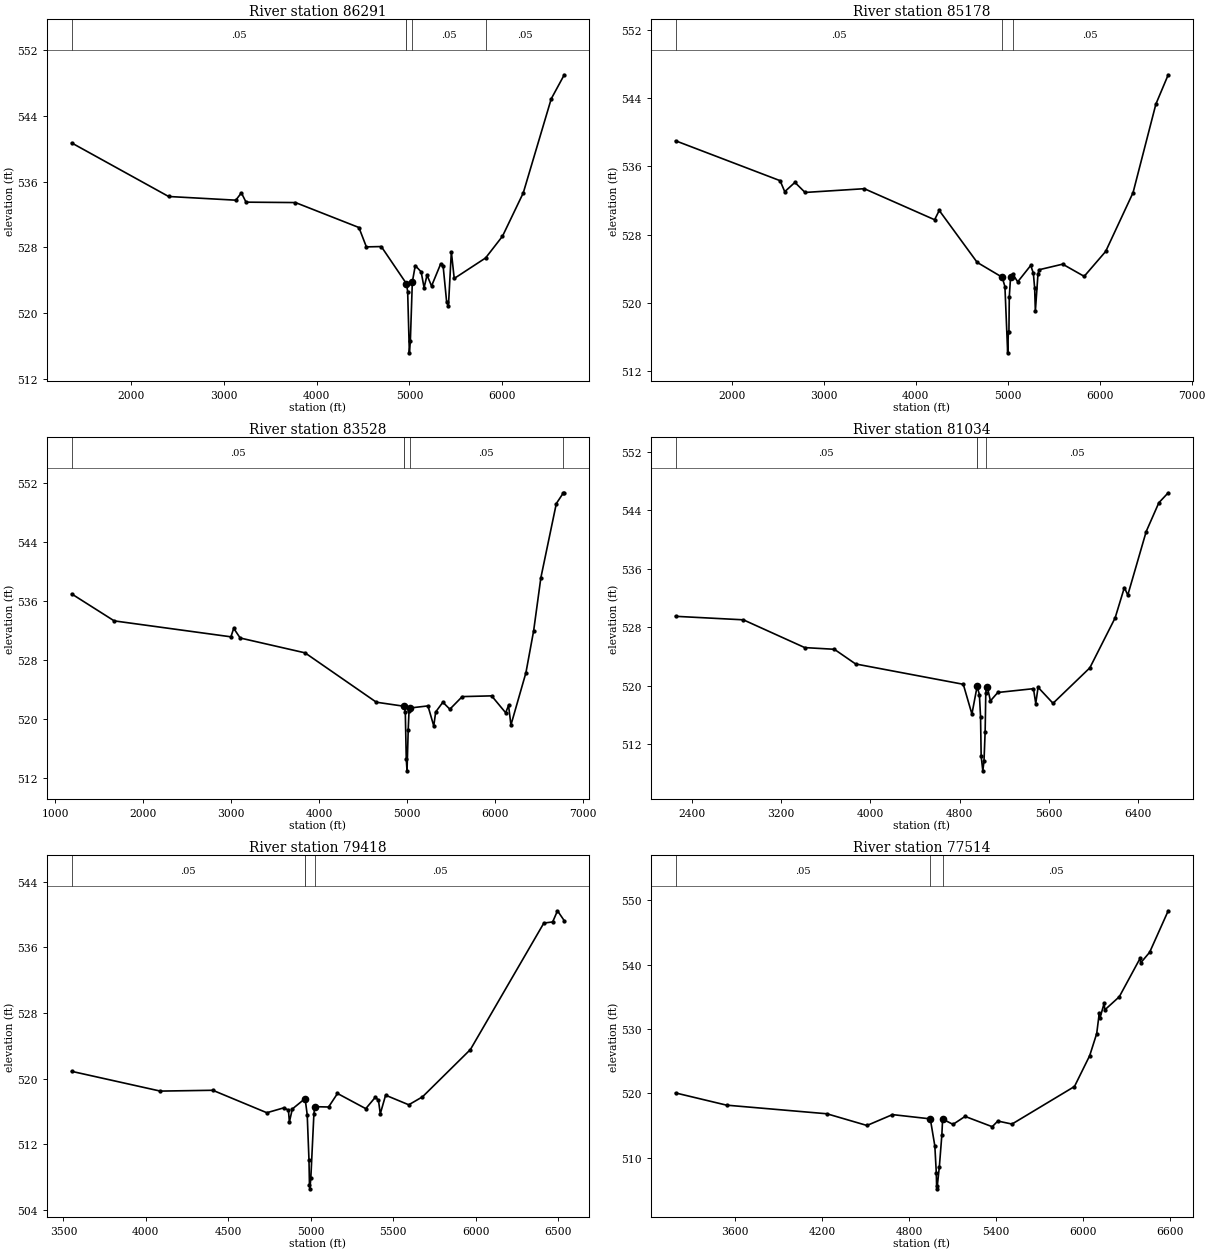
Type RM Length L Ch R = 1 ,86291   ,1113,1113,1113
BEGIN DESCRIPTION:
CHRISTMAS CREEK 69.0
END DESCRIPTION:
XS GIS Cut Line= 3
      3410142.11     10571491.68      3409742.11     10567891.64
       3409192.1     10566291.63
#Sta/Elev= 30
  1356.5  540.72  2402.9  534.19  3127.4  533.74  3187.7  534.63    3238   533.5
  3771.3  533.45  4455.5  530.41    4536  528.05    4697  528.09  4968.6  523.56
  4981.3   522.6  4999.6  515.14  5010.4  516.55  5031.6  523.76  5063.3  525.77
  5126.7  525.01  5158.5  523.08  5190.2  524.61    5239  523.28  5338.2     526
  5363.9  525.72  5401.7  521.35  5421.1  520.83  5452.4  527.46  5483.6   524.2
    5822   526.7  6004.2  529.35  6228.1  534.62    6530  546.09  6670.6  549.02
#Mann= 5 ,-1 , 0
  1356.5     .05       0  4968.6     .16       0  4968.6     .07       0
  5031.6     .05       0    5822     .05       0
Bank Sta=4968.6,5031.6
XS Rating Curve= 0 ,0
Exp/Cntr=0.3,0.1

Type RM Length L Ch R = 1 ,85178   ,1650,1650,1650
BEGIN DESCRIPTION:
CHRISTMAS CREEK 67.0
END DESCRIPTION:
XS GIS Cut Line= 3
       3410342.1     10571141.67      3410742.11     10567541.64
      3409592.13     10566241.67
#Sta/Elev= 30
  1387.2     539  2524.2  534.32  2574.5  533.03  2685.2  534.12  2795.8  532.94
  3439.8  533.38  4204.5  529.74  4254.8  530.83  4667.3  524.74    4939     523
  4969.1   521.9  4999.1  514.13  5006.9  516.62  5012.7  516.62  5016.5  520.67
  5030.7  523.04  5051.6  523.39  5108.5  522.46  5249.8  524.38  5278.3  523.47
  5292.5   521.7  5300.1     519  5328.5  523.36  5342.7  523.88    5597  524.53
  5831.2   523.1  6064.6  526.02  6362.4  532.91  6610.8   543.3    6745  546.74
#Mann= 3 ,-1 , 0
  1387.2     .05       0    4939     .07       0  5051.6     .05       0
Bank Sta=4939,5030.7
XS Rating Curve= 0 ,0
Exp/Cntr=0.3,0.1

Type RM Length L Ch R = 1 ,83528   ,2494,2494,2494
BEGIN DESCRIPTION:
CHRISTMAS CREEK 65.0
END DESCRIPTION:
XS GIS Cut Line= 3
      3410942.11     10570591.63      3412142.11     10566991.64
       3411292.1     10565391.63
#Sta/Elev= 30
  1184.1  536.92    1669  533.26  2997.1   531.1  3028.7  532.25  3102.5  530.94
  3840.4  528.93    4652  522.24  4968.3  521.69  4981.6  520.85  4992.6  514.49
  5001.2  512.94  5014.6  518.47  5024.1  521.11  5030.9  521.45  5239.3  521.74
  5305.4  519.02  5327.3  520.92  5409.1  522.24  5488.4  521.29  5629.4     523
    5964   523.1  6123.7  520.81  6156.3   521.8  6183.9  519.16  6354.1  526.23
  6442.1  531.92  6524.3  539.11  6700.2  549.16  6776.8  550.54  6790.6  550.62
#Mann= 5 ,-1 , 0
  1184.1     .05       0  4968.3     .16       0  4968.3     .07       0
  5030.9     .05       0  6776.8     .05       0
Bank Sta=4968.3,5030.9
XS Rating Curve= 0 ,0
Exp/Cntr=0.3,0.1

Type RM Length L Ch R = 1 ,81034   ,1616,1616,1616
BEGIN DESCRIPTION:
CHRISTMAS CREEK 63.0
END DESCRIPTION:
XS GIS Cut Line= 3
       3413574.2       10568808.      3413986.52     10566648.76
      3413454.84     10564500.32
#Sta/Elev= 30
  2255.5  529.51  2862.6  529.03  3412.4  525.23  3677.1     525  3867.9  522.99
  4831.9  520.21  4909.2  516.14  4955.8  519.92  4976.2   518.8  4986.5   515.8
    4992  510.39  5006.8  508.37  5017.4   509.7  5027.7  513.75  5033.5  519.03
  5038.6  519.64  5048.3  519.79  5074.9  517.94    5141  519.09  5460.3  519.61
  5480.9  517.58  5501.6   519.8  5635.5  517.61  5965.1  522.46  6191.8   529.3
  6274.2  533.44  6305.1  532.42  6469.9  541.11  6583.2  545.05    6667  546.41
#Mann= 4 ,-1 , 0
  2255.5     .05       0  4955.8     .16       0  4955.8     .07       0
  5038.6     .05       0
Bank Sta=4955.8,5048.3
XS Rating Curve= 0 ,0
Exp/Cntr=0.3,0.1

Type RM Length L Ch R = 1 ,79418   ,1904,1904,1904
BEGIN DESCRIPTION:
CHRISTMAS CREEK 61.0
END DESCRIPTION:
XS GIS Cut Line= 3
       3415907.1     10566627.06       3415201.8     10565976.01
      3414431.39     10564098.81
#Sta/Elev= 30
  3549.5  520.89  4087.4  518.48    4406  518.58    4734  515.84  4835.4  516.43
  4864.8  516.17  4870.8  514.72  4888.7   516.3  4966.1  517.57  4978.9   515.6
  4989.7  510.04  4992.5  507.06  4995.2  506.56  5000.9   507.9  5019.4  515.67
  5024.8  516.58  5108.6  516.54  5162.6  518.19  5334.2  516.34    5393  517.75
  5411.3  517.34  5422.3  515.71  5454.5  517.98    5595  516.81  5678.3  517.78
  5969.1  523.55  6414.6  538.97    6468  539.11  6497.4  540.47  6538.5  539.26
#Mann= 4 ,-1 , 0
  3549.5     .05       0  4966.1     .16       0  4966.1     .07       0
  5024.8     .05       0
Bank Sta=4966.1,5024.8
XS Rating Curve= 0 ,0
Exp/Cntr=0.3,0.1

Type RM Length L Ch R = 1 ,77514   ,1780,1780,1780
BEGIN DESCRIPTION:
CHRISTMAS CREEK 60.0
END DESCRIPTION:
XS GIS Cut Line= 3
      3416242.45     10566501.44      3415886.56     10565095.22
      3416442.11     10563228.91
#Sta/Elev= 30
  3188.6  520.06  3540.4  518.16  4232.4  516.82  4508.7     515  4684.6  516.69
  4945.5  516.03  4976.8  511.82  4986.8  507.69    4989  505.65  4991.7  505.15
  5008.1  508.62  5025.2  513.52  5030.4     516    5102  515.17  5185.4  516.41
  5372.6  514.81    5411  515.69  5508.9  515.22  5939.9  521.06  6044.7  525.85
  6093.2  529.29    6111   532.5  6116.2  531.72  6144.2  533.99  6149.4  532.98
  6248.9  535.01  6392.1  540.97  6397.3   540.3  6458.3  541.93  6586.4  548.38
#Mann= 3 , 0 , 0
  3188.6     .05       0  4945.5     .07       0  5030.4     .05       0
Bank Sta=4945.5,5030.4
XS Rating Curve= 0 ,0
Exp/Cntr=0.3,0.1

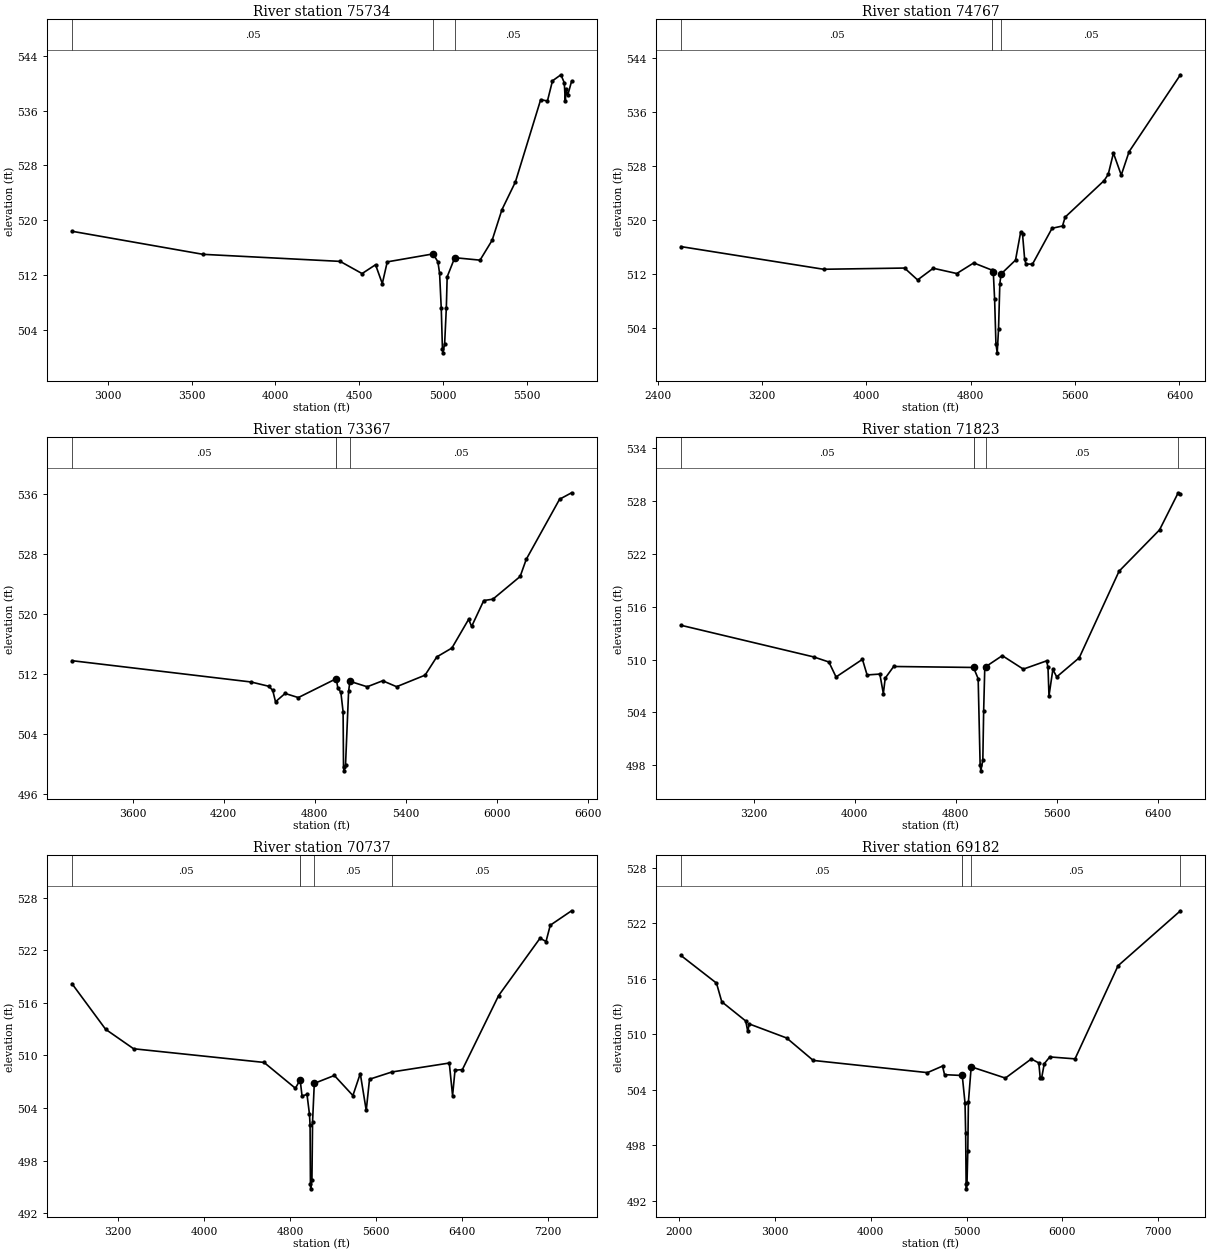
Type RM Length L Ch R = 1 ,75734   ,967,967,967
BEGIN DESCRIPTION:
CHRISTMAS CREEK 59.0
END DESCRIPTION:
XS GIS Cut Line= 3
      3417035.56      10566290.7      3417198.33     10565042.85
      3417003.02     10563328.46
#Sta/Elev= 30
  2784.7  518.36  3567.6  514.99  4386.5  513.96  4517.4  512.18  4597.9  513.47
  4638.2  510.71  4667.8  513.89  4941.2  515.05  4970.3   513.9  4980.4  512.22
  4990.4  507.08  4997.5   501.1  5000.2   500.6  5010.5  501.89  5020.6  507.15
  5025.7  511.71  5070.9   514.5  5221.9  514.14  5294.1  517.04  5352.7  521.51
  5433.3  525.57  5584.2  537.59  5624.5  537.39  5654.7  540.34    5705  541.22
  5725.1  540.06  5731.3  537.36  5736.4  539.14  5745.3   538.2  5768.6  540.26
#Mann= 3 , 0 , 0
  2784.7     .05       0  4941.2     .07       0  5070.9     .05       0
Bank Sta=4941.2,5070.9
XS Rating Curve= 0 ,0
Exp/Cntr=0.3,0.1

Type RM Length L Ch R = 1 ,74767   ,1400,1400,1400
BEGIN DESCRIPTION:
CHRISTMAS CREEK 58.0
END DESCRIPTION:
XS GIS Cut Line= 3
      3417753.63     10566104.73      3417781.41     10565556.15
      3417885.57     10562278.38
#Sta/Elev= 30
  2578.6     516  3672.7  512.64    4293  512.82    4393  511.06  4513.1  512.79
  4693.2  512.01  4823.2  513.58  4963.3  512.51  4973.3  512.18  4983.3  508.18
  4993.3  501.64  5003.1  500.26  5013.3  503.77  5023.3  510.53  5033.3  511.95
  5143.4  513.99  5183.4   518.2  5197.3  517.83  5213.4  514.15  5223.4  513.41
  5273.5   513.4  5423.5  518.71  5503.6  519.05  5523.6  520.36  5822.3  525.77
  5853.8  526.69  5893.8  529.85  5953.8  526.59  6013.8  530.06  6407.3  541.45
#Mann= 4 ,-1 , 0
  2578.6     .05       0  4963.3     .16       0  4963.3     .07       0
  5033.3     .05       0
#XS Ineff= 1 ,-1
 5187.61 5349.39  514.65
Permanent Ineff=
       F
Bank Sta=4973.3,5033.3
XS Rating Curve= 0 ,0
Exp/Cntr=0.3,0.1

Type RM Length L Ch R = 1 ,73367   ,1544,1544,1544
BEGIN DESCRIPTION:
CHRISTMAS CREEK 56.0
END DESCRIPTION:
XS GIS Cut Line= 4
      3418204.24      10565702.9      3418785.86     10564834.81
      3419054.96      10563541.4      3419054.96     10562612.63
#Sta/Elev= 30
  3199.5  513.79  4380.4  510.95  4496.9  510.38  4523.4  509.84  4541.9  508.31
  4605.1  509.42  4692.2  508.87  4942.6  511.39  4952.4   510.2  4972.9  509.56
  4987.6  506.97  4990.3   499.6    4993   499.1  5003.5  499.82  5023.9   509.7
  5032.5  511.04  5146.5  510.31  5248.6  511.11  5340.6  510.32  5528.2  511.86
  5605.3  514.29  5705.3  515.48  5815.3   519.3  5835.3  518.36  5915.3  521.81
  5975.3  521.99  6155.3  525.02  6195.3   527.3  6415.3  535.32  6494.3  536.18
#Mann= 4 ,-1 , 0
  3199.5     .05       0  4942.6     .16       0  4942.6     .07       0
  5032.5     .05       0
Bank Sta=4942.6,5032.5
XS Rating Curve= 0 ,0
Exp/Cntr=0.3,0.1

Type RM Length L Ch R = 1 ,71823   ,1086,1086,1086
BEGIN DESCRIPTION:
CHRISTMAS CREEK 55.0
END DESCRIPTION:
XS GIS Cut Line= 4
      3418291.08     10565789.67      3419341.42     10564930.29
      3420348.36     10564322.65       3419862.4     10562986.26
#Sta/Elev= 30
  2624.3  513.89    3675   510.3  3796.3  509.72  3853.1  508.02    4062  510.02
  4098.9  508.25  4199.8  508.35  4227.5  506.14  4242.5  507.89  4309.2  509.21
  4941.3   509.1  4978.2  507.82  4993.7  498.08  4999.3  497.37  5015.1  498.59
  5021.7  504.18  5030.6  509.09  5036.4  509.17  5169.2  510.44  5335.4  508.91
  5520.3  509.85    5531   509.1  5538.9  505.88  5569.5  508.87  5600.1  508.03
  5778.4   510.2  6093.6  520.02  6414.1  524.71  6561.8  528.92  6579.5  528.76
#Mann= 5 ,-1 , 0
  2624.3     .05       0  4941.3     .16       0  4941.3     .07       0
  5036.4     .05       0  6561.8     .05       0
Bank Sta=4941.3,5036.4
XS Rating Curve= 0 ,0
Exp/Cntr=0.3,0.1

Type RM Length L Ch R = 1 ,70737   ,1555,1555,1555
BEGIN DESCRIPTION:
CHRISTMAS CREEK 54.5
END DESCRIPTION:
XS GIS Cut Line= 4
      3420095.47      10567332.3      3420486.09     10565379.22
      3420692.25      10564923.5      3419943.82     10562905.99
#Sta/Elev= 30
  2773.4  518.19  3086.4  512.98  3346.4  510.76  4558.7   509.2  4850.3  506.25
  4894.3  507.22  4911.9  505.38  4958.2  505.54  4981.3  503.26  4986.7  502.01
    4990  495.27  4992.7  494.77    5004  495.82  5009.9  502.43  5025.9  506.81
  5212.5  507.71  5384.7  505.42  5453.3  507.93  5508.7  503.72  5539.1  507.28
  5747.3  508.11  6280.6  509.13  6311.2  505.41  6333.9  508.31  6402.3  508.38
  6739.2  516.83  7124.4  523.38  7179.8     523  7219.2  524.86  7417.2  526.51
#Mann= 5 ,-1 , 0
  2773.4     .05       0  4894.3     .16       0  4894.3     .07       0
  5025.9     .05       0  5747.3     .05       0
Bank Sta=4894.3,5025.9
XS Rating Curve= 0 ,0
Exp/Cntr=0.3,0.1

Type RM Length L Ch R = 1 ,69182   ,1595,1595,1595
BEGIN DESCRIPTION:
CHRISTMAS CREEK 54.0
END DESCRIPTION:
XS GIS Cut Line= 3
      3421006.92     10567375.75      3421831.57     10565173.06
      3420085.13     10562905.94
#Sta/Elev= 30
  2017.9  518.54  2389.9  515.54  2445.2  513.52    2695  511.44  2716.3  510.32
  2731.9  511.12  3122.1   509.6  3399.7  507.17  4591.4  505.85  4749.1  506.56
  4769.9  505.63  4954.7  505.54  4983.7  502.56  4990.2  499.29  4995.2  493.77
    4998  493.27  5004.5  493.95  5012.7   497.4    5019  502.65    5048  506.48
    5405  505.26    5675  507.33  5753.8   506.9  5768.3  505.29  5782.8  505.25
  5810.7  506.82    5868  507.55  6131.6  507.34  6580.7  517.42  7231.7  523.37
#Mann= 5 ,-1 , 0
  2017.9     .05       0  4954.7     .16       0  4954.7     .07       0
    5048     .05       0  7231.7     .05       0
Bank Sta=4954.7,5048
XS Rating Curve= 0 ,0
Exp/Cntr=0.3,0.1

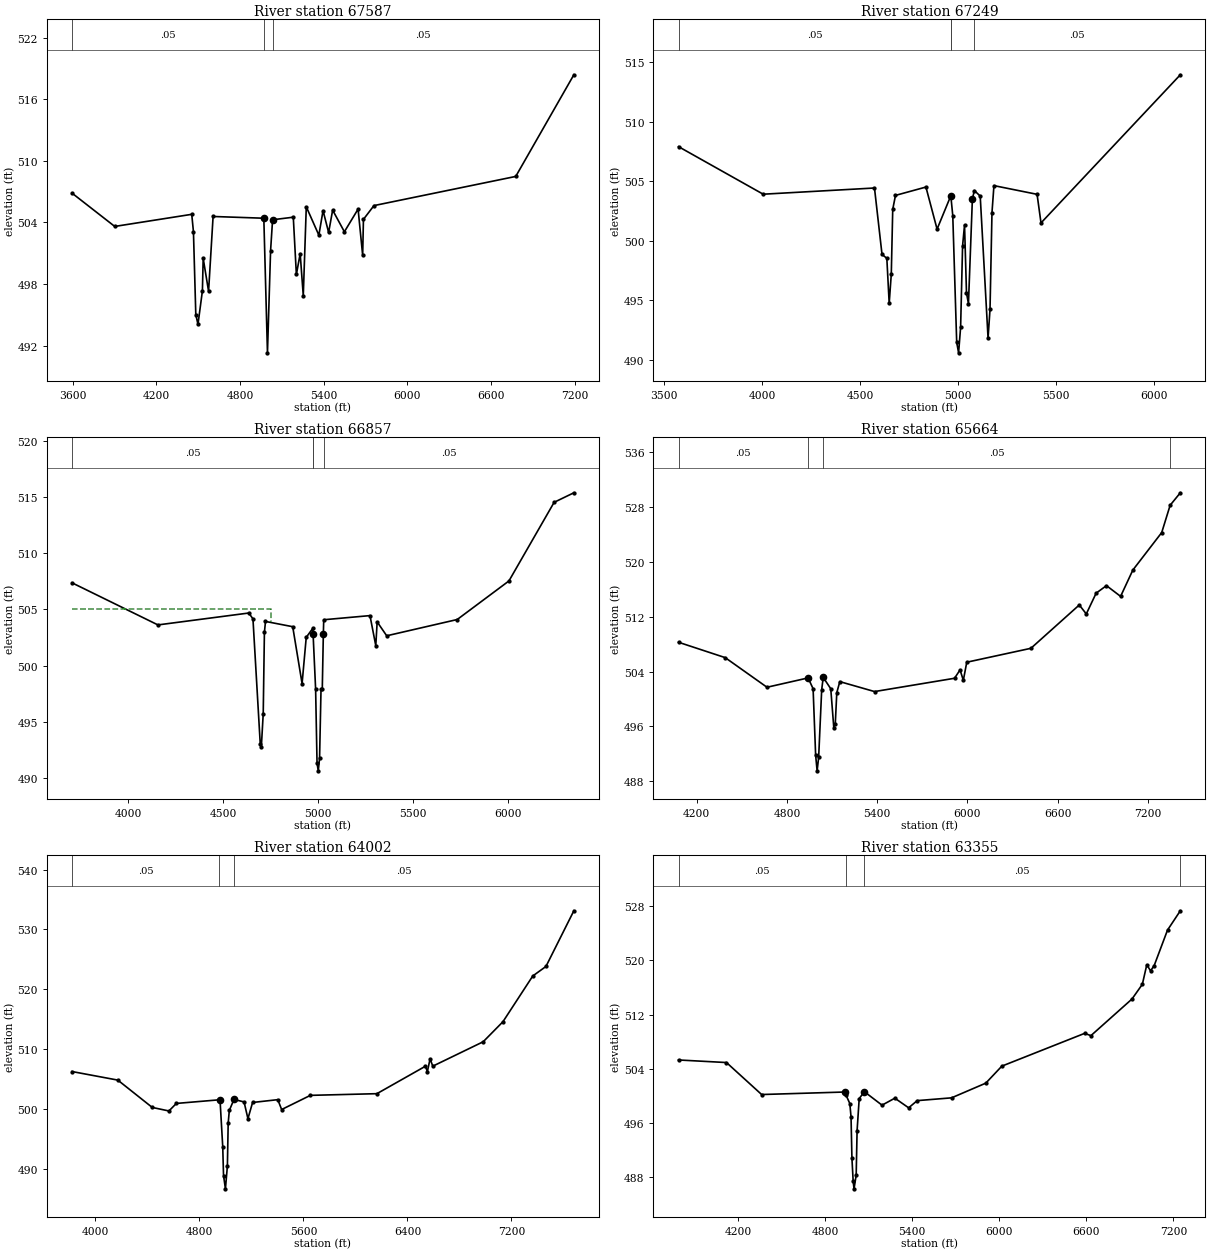
Type RM Length L Ch R = 1 ,67587   ,338,338,338
BEGIN DESCRIPTION:
CHRISTMAS CREEK 53.0
END DESCRIPTION:
XS GIS Cut Line= 4
      3423282.15     10565403.62      3422837.79     10564349.98
      3422503.38     10563946.85      3420736.07      10563168.5
#Sta/Elev= 30
  3596.3  506.84  3902.3   503.6  4454.5  504.78  4466.7  503.08  4483.6  495.02
  4499.2  494.06    4531  497.33  4536.5   500.5  4575.2  497.29  4607.6  504.57
 4971.38   504.4  4997.5  491.29  5019.9  501.25  5034.2  504.25  5182.7   504.5
  5204.8  498.92  5232.1  500.95  5254.3  496.85  5275.9  505.51  5366.1  502.75
  5396.1  505.14  5436.1  503.01  5464.9  505.19  5549.1  503.08  5647.4  505.29
  5680.2  500.79  5685.8  504.29  5761.2  505.63  6777.9  508.47  7194.7  518.37
#Mann= 3 , 0 , 0
  3596.3     .05       0 4971.38     .07       0  5034.2     .05       0
Bank Sta=4971.38,5034.2
XS Rating Curve= 0 ,0
Exp/Cntr=0.3,0.1

Type RM Length L Ch R = 1 ,67249   ,392,392,392
BEGIN DESCRIPTION:
CHRISTMAS CREEK 51.0
END DESCRIPTION:
XS GIS Cut Line= 3
      3423419.59     10565444.87       3422956.9     10564240.03
      3422924.83     10562971.07
#Sta/Elev= 30
  3574.7   507.9  4006.6  503.91  4574.4  504.43  4612.8  498.86  4637.4  498.53
  4649.4  494.75  4660.1   497.2  4667.5  502.64  4681.5  503.81  4836.8  504.51
  4893.7  500.98  4963.8  503.78  4973.8  502.11  4993.8  491.48  5003.5   490.6
  5013.8  492.75  5023.8  499.57  5033.8  501.33  5043.8  495.61  5053.8  494.73
  5073.8   503.5  5083.8  504.22  5113.8  503.75  5153.8  491.84  5163.8  494.26
  5173.8  502.36  5183.8  504.63  5403.9   503.9  5423.9   501.5  6134.7  513.93
#Mann= 4 ,-1 , 0
  3574.7     .05       0  4963.8     .16       0  4963.8     .07       0
  5083.8     .05       0
Bank Sta=4963.8,5073.8
XS Rating Curve= 0 ,0
Exp/Cntr=0.3,0.1

Type RM Length L Ch R = 1 ,66857   ,1193,1193,1193
BEGIN DESCRIPTION:
CHRISTMAS CREEK 50.2
END DESCRIPTION:
XS GIS Cut Line= 4
      3423611.96     10565321.12      3423089.74     10564336.23
      3423300.47       10564153.      3423048.52     10562929.89
#Sta/Elev= 30
  3704.9  507.37  4157.1  503.62  4635.6  504.68  4657.6  504.16    4696  493.01
  4701.6   492.7  4711.7  495.72  4717.9  502.95  4723.6  503.93    4867  503.46
  4916.3  498.39  4938.2  502.51  4973.3  503.33 4974.39  502.77  4987.6   497.9
  4995.1  491.29  5001.6  490.61  5008.4  491.72  5016.1  497.92  5022.7  497.92
 5028.31   502.8  5030.3  504.08  5273.9  504.45  5304.5  501.77  5311.7  503.89
    5362  502.65  5733.3   504.1  6005.8  507.54  6243.8  514.55  6347.7   515.4
#Mann= 4 ,-1 , 0
  3704.9     .05       0  4973.3     .12       0  4973.3     .07       0
  5030.3     .05       0
#XS Ineff= 1 ,-1
 3597.84 4750.62504.9974
Permanent Ineff=
       F
Bank Sta=4974.39,5028.31
XS Rating Curve= 0 ,0
Exp/Cntr=0.3,0.1

Type RM Length L Ch R = 1 ,65664   ,1662,1662,1662
BEGIN DESCRIPTION:
CHRISTMAS CREEK 50.0
END DESCRIPTION:
XS GIS Cut Line= 4
      3424249.54     10565161.77      3424235.65     10564502.05
       3424305.1     10563752.05      3423541.19     10561988.13
#Sta/Elev= 30
  4079.8  508.27    4390  506.03  4667.8  501.71  4940.9  503.07  4974.2   501.5
  4991.1   491.8  5000.9  489.52  5011.2  491.51  5031.3  501.33  5041.4  503.15
  5091.6  501.49  5111.7  495.84  5121.7  496.39  5131.7  500.92  5151.8  502.53
  5382.8  501.08  5914.2  503.02    5951  504.24  5972.8  502.72  5995.6  505.36
    6422  507.39  6743.5  513.71  6790.1   512.4  6855.5  515.43  6924.2  516.53
  7018.1  514.96  7099.5   518.8  7291.4  524.27  7347.4  528.25  7415.1  530.07
#Mann= 4 ,-1 , 0
  4079.8     .05       0  4940.9     .07       0  5041.4     .05       0
  7347.4     .16       0
Bank Sta=4940.9,5041.4
XS Rating Curve= 0 ,0
Exp/Cntr=0.3,0.1

Type RM Length L Ch R = 1 ,64002   ,647,647,647
BEGIN DESCRIPTION:
CHRISTMAS CREEK 49.0
END DESCRIPTION:
XS GIS Cut Line= 3
      3424937.04       10565009.      3425485.65     10564272.89
      3423806.25     10561857.88
#Sta/Elev= 30
  3820.2  506.24    4172  504.81  4436.9  500.24  4565.2  499.65  4622.4  500.91
  4949.5  501.51  4958.2  501.54  4979.1  493.66  4985.2  488.86  4999.8  486.63
  5014.9  490.46    5021  497.62  5029.7  499.74  5065.5  501.58  5143.2  501.16
  5172.9  498.36  5208.7  501.07  5402.5  501.54  5432.2  499.89  5653.3  502.26
  6164.9  502.54  6538.1  507.13  6552.9  506.22  6573.9  508.36  6594.8  507.14
  6982.4  511.22  7134.3  514.57  7363.8  522.22  7465.1  523.81  7679.8  533.12
#Mann= 3 ,-1 , 0
  3820.2     .05       0  4949.5     .07       0  5065.5     .05       0
Bank Sta=4958.2,5065.5
XS Rating Curve= 0 ,0
Exp/Cntr=0.3,0.1

Type RM Length L Ch R = 1 ,63355   ,239,239,239
BEGIN DESCRIPTION:
CHRISTMAS CREEK 48.0
END DESCRIPTION:
XS GIS Cut Line= 3
      3425049.28     10565030.41      3425878.42     10563908.09
      3426276.63     10561884.98
#Sta/Elev= 30
  3790.1  505.29  4120.5  504.91  4362.7  500.19  4934.7  500.56  4943.1  500.15
  4970.2  498.86  4978.6   496.9  4984.8  490.78  4993.2  487.43  4999.2  486.27
  5014.1   488.3  5020.3  494.86  5034.9  499.59  5070.4  500.61    5192  498.62
  5280.5  499.65  5375.5  498.23  5434.6  499.29  5671.1   499.7  5907.1  501.87
  6017.6  504.38  6588.3  509.22  6631.3  508.88  6914.5  514.29  6985.8  516.46
  7016.4  519.35  7042.3  518.44  7067.4  519.23  7159.1  524.46  7247.4  527.31
#Mann= 4 ,-1 , 0
  3790.1     .05       0  4943.1     .07       0  5070.4     .05       0
  7247.4     .05       0
Bank Sta=4934.7,5070.4
XS Rating Curve= 0 ,0
Exp/Cntr=0.3,0.1

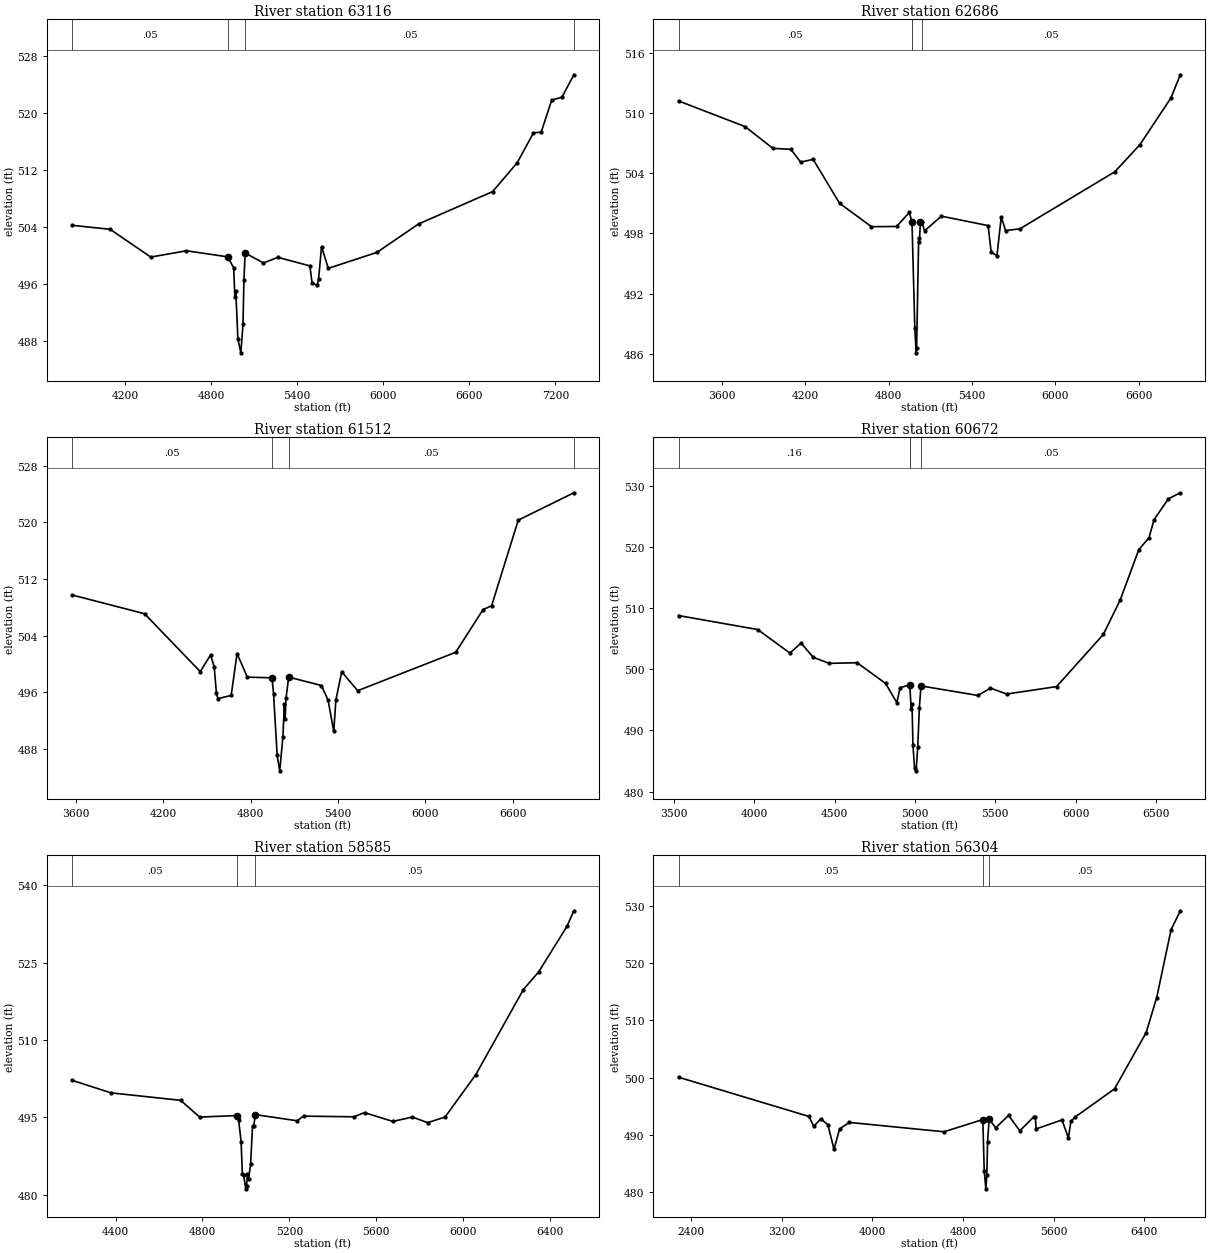
Type RM Length L Ch R = 1 ,63116   ,430,430,430
BEGIN DESCRIPTION:
CHRISTMAS CREEK 47.0
END DESCRIPTION:
XS GIS Cut Line= 4
      3425127.13      10565039.6      3425640.21     10564421.16
      3426066.24     10564118.81      3426446.46     10561979.52
#Sta/Elev= 30
  3829.8  504.23  4094.8  503.67  4378.6  499.78  4627.4  500.66  4914.6  499.81
  4956.4  498.28  4965.1  494.15  4971.2  495.04    4986  488.34  5006.6  486.36
  5021.6  490.36  5028.1  496.58  5036.4  500.35  5164.4  498.95  5264.6  499.74
  5488.1  498.54  5503.5   496.1  5538.9  495.82    5549  496.75  5569.3  501.24
  5616.5   498.2  5955.3  500.43  6245.6  504.42  6761.8  508.95  6933.8     513
  7046.9  517.18  7100.8  517.28  7174.1  521.78  7245.2  522.17  7328.6  525.32
#Mann= 4 ,-1 , 0
  3829.8     .05       0  4914.6     .07       0  5036.4     .05       0
  7328.6     .05       0
Bank Sta=4914.6,5036.4
XS Rating Curve= 0 ,0
Exp/Cntr=0.3,0.1

Type RM Length L Ch R = 1 ,62686   ,1174,1174,1174
BEGIN DESCRIPTION:
CHRISTMAS CREEK 46.5
END DESCRIPTION:
XS GIS Cut Line= 4
      3426173.15     10566050.63      3426173.15      10564571.5
      3426249.54       10564009.      3426652.13     10562495.83
#Sta/Elev= 30
  3287.6  511.22  3766.6  508.66  3966.6  506.49  4096.6  506.39  4166.6  505.11
  4256.6  505.39  4446.6  501.01  4676.6  498.67  4857.4  498.69    4949  500.09
  4968.4  499.12  4988.6  488.57  4998.4  486.08  5001.7  486.58  5016.4  497.53
  5021.5  497.19    5029  499.11  5039.1  499.13  5059.2  498.26  5180.3  499.72
  5516.1  498.78  5538.6  496.14    5580  495.76    5611  499.65  5642.1  498.28
  5745.6  498.46  6428.5  504.15    6609  506.85  6832.1  511.51  6900.2  513.83
#Mann= 4 ,-1 , 0
  3287.6     .05       0  4968.4     .16       0  4968.4     .07       0
  5039.1     .05       0
Bank Sta=4968.4,5029
XS Rating Curve= 0 ,0
Exp/Cntr=0.3,0.1

Type RM Length L Ch R = 1 ,61512   ,840,840,840
BEGIN DESCRIPTION:
CHRISTMAS CREEK 46.4
END DESCRIPTION:
XS GIS Cut Line= 4
      3427158.94     10565952.76      3426978.38     10564723.56
      3427520.05     10563306.89      3428117.15     10562966.68
#Sta/Elev= 30
  3574.3  509.74  4072.2  507.09  4454.8  498.92  4525.5  501.27  4550.5  499.58
  4565.9  495.84    4576  495.11    4667  495.56  4707.4  501.47  4778.2  498.14
  4947.2  498.05  4958.2  495.78  4982.9   487.1  5000.5  484.92  5022.2  489.68
  5032.3   494.3  5037.7  492.28  5043.6  495.17  5062.4  498.15  5286.8  496.96
  5332.6   494.9  5371.6  490.48  5386.2  494.93  5426.4   498.9  5535.9  496.23
  6209.2  501.65  6396.8  507.67  6455.8  508.22  6638.8   520.3  7020.6  524.16
#Mann= 4 ,-1 , 0
  3574.3     .05       0  4947.2     .07       0  5062.4     .05       0
  7020.6     .05       0
Bank Sta=4947.2,5062.4
XS Rating Curve= 0 ,0
Exp/Cntr=0.3,0.1

Type RM Length L Ch R = 1 ,60672   ,2087,2087,2087
BEGIN DESCRIPTION:
CHRISTMAS CREEK 46.3
END DESCRIPTION:
XS GIS Cut Line= 4
      3427596.77     10566078.41      3427756.49     10564981.22
      3427777.32     10564307.61      3428200.94     10563036.74
#Sta/Elev= 30
  3529.2  508.78  4021.8  506.49  4221.9  502.65    4292  504.27  4367.2  501.95
  4465.7  500.96  4640.2  501.06  4817.6  497.68  4887.6  494.53  4907.7  496.97
  4967.7  497.45  4977.1  493.49  4982.1  494.25  4987.7  487.64  4997.7  483.88
  5007.5  483.38  5017.7  487.27  5027.7  493.73  5037.7  497.27    5392  495.71
  5470.2  496.91  5571.2  495.94  5881.3  497.16    6172  505.68  6277.4  511.32
  6393.3  519.56  6456.6  521.52  6488.2  524.47    6577  527.86  6651.5  528.86
#Mann= 4 ,-1 , 0
  3529.2     .16       0  4967.7     .16       0  4967.7     .07       0
  5037.7     .05       0
Bank Sta=4967.7,5037.7
XS Rating Curve= 0 ,0
Exp/Cntr=0.3,0.1

Type RM Length L Ch R = 1 ,58585   ,2281,2281,2281
BEGIN DESCRIPTION:
CHRISTMAS CREEK 46.2
END DESCRIPTION:
XS GIS Cut Line= 4
      3429242.59     10565467.31      3428943.99     10564981.22
      3428777.32     10564606.22      3428700.93     10563279.87
#Sta/Elev= 30
    4200  502.16  4379.6  499.72  4699.6  498.28  4786.9  495.03  4960.7  495.32
    4967  494.37  4977.9  490.26  4983.9  483.93  4989.4  483.77  4999.6   481.1
  5002.8   481.6  5007.2  483.96  5012.6  483.01  5021.7  485.92  5030.4   493.2
  5035.9  493.27  5043.6   495.5  5235.5  494.31  5265.6  495.21  5495.9  495.08
    5546  495.89  5676.2  494.18  5766.4  495.03  5836.5  493.94  5916.6  495.03
    6058  503.26  6277.2  519.78  6347.4   523.2  6477.6  532.03  6509.4  535.06
#Mann= 3 , 0 , 0
    4200     .05       0  4960.7     .07       0  5043.6     .05       0
Bank Sta=4960.7,5043.6
XS Rating Curve= 0 ,0
Exp/Cntr=0.3,0.1

Type RM Length L Ch R = 1 ,56304   ,1556,1556,1556
BEGIN DESCRIPTION:
CHRISTMAS CREEK 46.1
END DESCRIPTION:
XS GIS Cut Line= 5
      3431827.52      10566342.9      3431271.96     10565153.66
      3430855.29     10564589.42      3430568.84     10564519.98
      3429284.35     10562836.26
#Sta/Elev= 30
  2291.5  500.06  3440.8   493.2  3484.9  491.47  3545.2  492.76  3608.2  491.78
  3662.7  487.45  3712.8  491.03  3798.4  492.15  4632.9  490.51  4975.5  492.65
  4988.3  483.61  5002.6  480.52  5011.1  482.93  5017.4  488.76  5031.9  492.74
  5088.7  491.18  5202.4  493.37  5302.5  490.68  5424.7  493.12  5439.3  493.17
  5445.6  491.01  5674.2  492.58  5730.3  489.43  5753.1  492.32  5788.5  493.07
  6137.7  498.02  6416.2  507.85  6509.7  514.01  6636.5  525.89    6718   529.2
#Mann= 3 , 0 , 0
  2291.5     .05       0  4975.5     .07       0  5031.9     .05       0
Bank Sta=4975.5,5031.9
XS Rating Curve= 0 ,0
Exp/Cntr=0.3,0.1