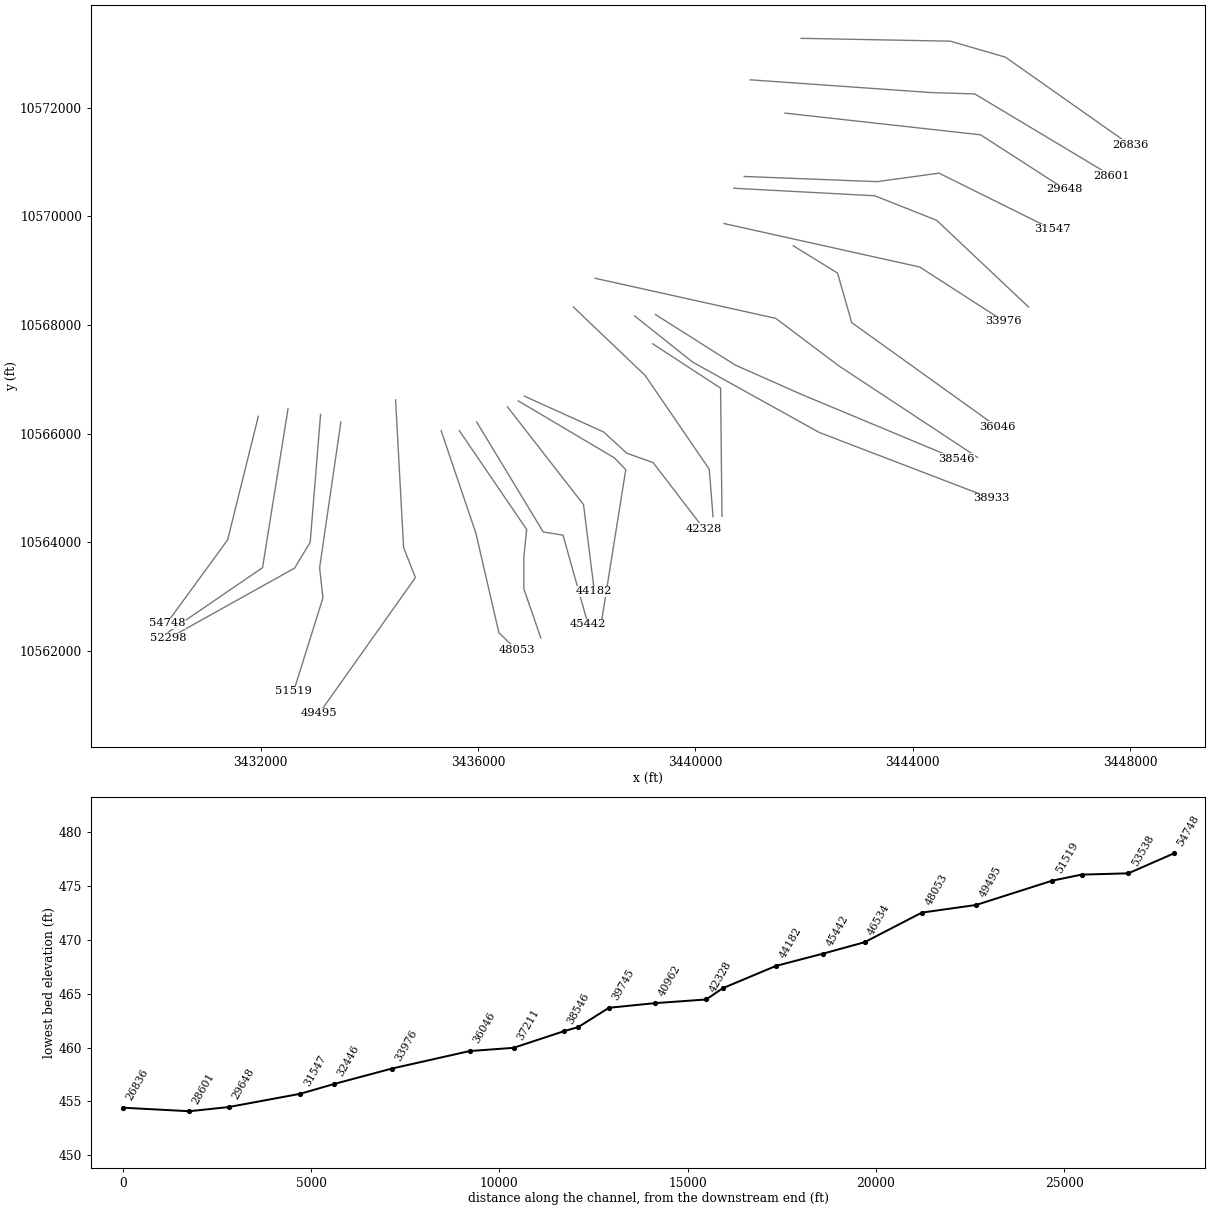
HEC-RAS study CHRISTMAS CREEK.prj: CHRISTMAS CREEK Base Level Engineering

--- CHRISTMAS CREEK.g01 (geometry) --- (continued)

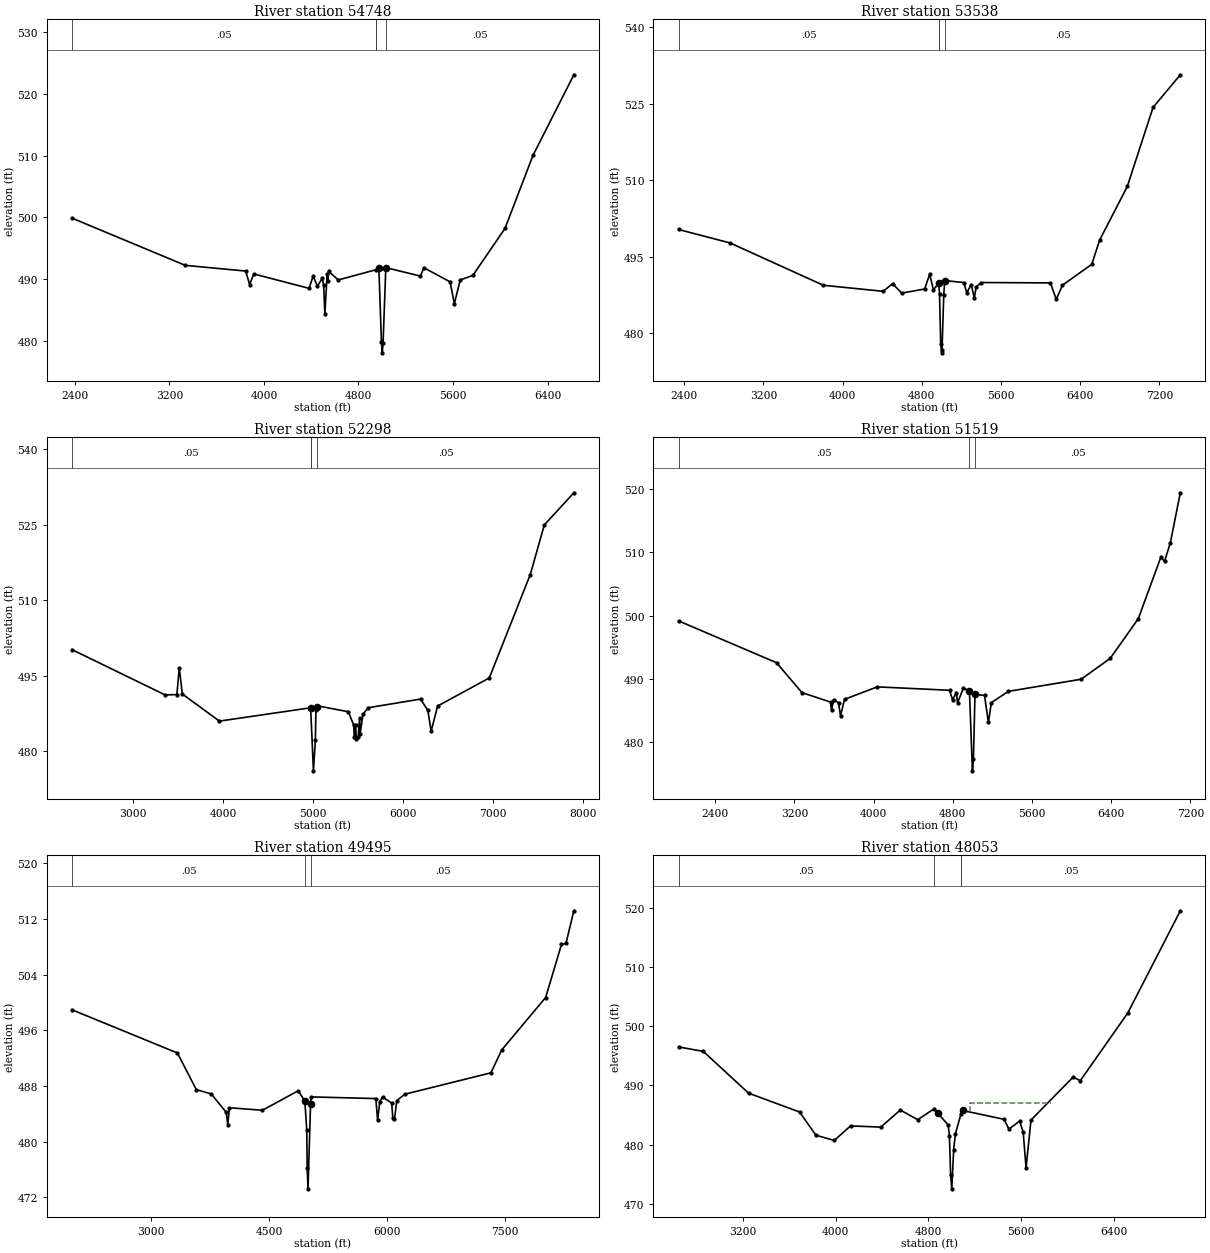
Type RM Length L Ch R = 1 ,54748   ,1210,1210,1210
BEGIN DESCRIPTION:
CHRISTMAS CREEK 46.0
END DESCRIPTION:
XS GIS Cut Line= 3
      3431957.72     10566316.84      3431393.49     10564042.55
      3430273.91     10562506.38
#Sta/Elev= 30
  2377.5  499.85  3335.6   492.2  3845.9  491.28  3878.6   489.1  3914.8  490.81
  4381.7  488.48  4416.4  490.46  4452.6  488.83    4494  490.14  4505.3  488.97
  4515.6  484.38  4535.3  490.81  4540.5  489.64  4546.5  491.26  4628.9  489.84
  4944.6  491.48  4972.4  491.79  4994.1  479.76  5001.5  478.03  5007.9  479.61
  5031.1  491.84  5323.9  490.46  5352.9  491.82    5575  489.53  5610.5     486
  5660.7  489.84  5767.4  490.58  6039.3  498.19  6275.7  510.01  6621.6  523.08
#Mann= 4 ,-1 , 0
  2377.5     .05       0  4944.6     .16       0  4944.6     .07       0
  5031.1     .05       0
Bank Sta=4972.4,5031.1
XS Rating Curve= 0 ,0
Exp/Cntr=0.3,0.1

Type RM Length L Ch R = 1 ,53538   ,1240,1240,1240
BEGIN DESCRIPTION:
CHRISTMAS CREEK 45.5
END DESCRIPTION:
XS GIS Cut Line= 3
      3432504.61     10566455.78      3432035.85     10563530.39
      3430299.72     10562341.14
#Sta/Elev= 30
  2343.9  500.34  2864.6   497.7  3806.5  489.41  4411.4  488.23  4505.3  489.74
  4596.4  487.88  4829.3  488.68    4880   491.6  4917.4   488.5  4971.1  489.85
  4979.4  487.68  4991.4  477.98  5001.3  476.18  5004.5  476.68  5021.8  487.42
  5031.9  490.33  5224.3  489.95  5254.7  487.95  5299.5  489.56  5330.1  486.96
  5351.1  489.16  5401.9  489.95    6099  489.88  6158.1  486.66    6221  489.43
  6516.9  493.52    6596  498.26  6875.6  508.76  7135.6  524.26    7411  530.64
#Mann= 4 ,-1 , 0
  2343.9     .05       0  4971.1     .16       0  4971.1     .07       0
  5031.9     .05       0
Bank Sta=4971.1,5031.9
XS Rating Curve= 0 ,0
Exp/Cntr=0.3,0.1

Type RM Length L Ch R = 1 ,52298   ,779,779,779
BEGIN DESCRIPTION:
CHRISTMAS CREEK 45.4
END DESCRIPTION:
XS GIS Cut Line= 4
      3433103.56     10566351.59      3432912.59     10563999.14
      3432626.13     10563521.71      3430308.45     10562228.33
#Sta/Elev= 30
  2322.9  500.14  3356.2  491.14  3486.7  491.22  3513.3  496.54  3546.9  491.33
  3958.2  485.94  4971.7  488.59  5002.5  476.06  5024.2  482.09    5030   488.2
  5039.7  488.83  5045.6  488.98  5390.8   487.8  5450.2  485.12  5455.9  482.74
  5471.9  485.16  5477.6  482.45  5499.3  482.78  5515.3  486.62    5521  483.39
    5553  487.31  5610.9   488.6  6191.7  490.32  6272.9  488.06  6309.5  483.94
  6381.4  488.94    6955  494.51  7409.8  515.05  7566.3  524.93    7894  531.31
#Mann= 4 ,-1 , 0
  2322.9     .05       0  4971.7     .16       0  4971.7     .07       0
  5045.6     .05       0
Bank Sta=4971.7,5039.7
XS Rating Curve= 0 ,0
Exp/Cntr=0.3,0.1

Type RM Length L Ch R = 1 ,51519   ,2024,2024,2024
BEGIN DESCRIPTION:
CHRISTMAS CREEK 45.3
END DESCRIPTION:
XS GIS Cut Line= 4
      3433476.75     10566211.03      3433086.13     10563528.75
      3433146.89     10562973.19      3432609.05     10561255.57
#Sta/Elev= 30
  2029.5  499.16  3019.2  492.56  3276.5  487.84  3564.9  486.35    3575  485.03
  3595.2  486.74  3645.8  486.22    3666  484.17  3706.4  486.78  4037.1  488.75
  4767.3  488.21  4797.5  486.74  4836.9  487.82  4847.8   486.2  4908.2   488.6
  4968.5  488.02  4998.5   475.5  5008.8   477.4  5024.4  487.55  5120.7   487.4
  5159.7  483.13  5189.8  486.26  5361.7  488.04  6096.5  489.95  6390.4  493.24
  6674.4  499.51  6901.6  509.19  6939.2  508.54  6998.1   511.5  7098.8  519.37
#Mann= 3 , 0 , 0
  2029.5     .05       0  4968.5     .07       0  5024.4     .05       0
Bank Sta=4968.5,5024.4
XS Rating Curve= 0 ,0
Exp/Cntr=0.3,0.1

Type RM Length L Ch R = 1 ,49495   ,1442,1442,1442
BEGIN DESCRIPTION:
CHRISTMAS CREEK 45.2
END DESCRIPTION:
XS GIS Cut Line= 4
       3434483.7     10566618.99      3434631.27     10563902.01
      3434848.28     10563346.46      3433077.54     10560846.58
#Sta/Elev= 30
  1995.5  498.96  3334.8  492.76  3575.2   487.5  3765.5  486.87  3955.7  484.23
  3975.8  482.41  3995.8  484.89  4416.4  484.53  4871.2  487.33  4955.4  485.85
  4979.9  481.72  4985.3   476.2  4995.8  473.24  5028.2  485.36  5034.2  486.45
    5858  486.21  5881.1   483.1  5908.2  485.77  5943.9  486.43  6059.5  485.56
  6074.3  483.42  6095.2  483.23  6124.8  485.91  6225.7  486.83  7322.1  489.91
  7458.7  493.19  8017.4  500.73  8219.2  508.36  8275.8   508.5  8376.4  513.19
#Mann= 3 ,-1 , 0
  1995.5     .05       0  4955.4     .07       0  5034.2     .05       0
Bank Sta=4955.4,5028.2
XS Rating Curve= 0 ,0
Exp/Cntr=0.3,0.1

Type RM Length L Ch R = 1 ,48053   ,1519,1519,1519
BEGIN DESCRIPTION:
CHRISTMAS CREEK 45.1
END DESCRIPTION:
XS GIS Cut Line= 4
       3435321.4     10566053.86       3435961.6     10564165.81
      3436384.78     10562332.05      3436710.27     10562017.41
#Sta/Elev= 30
  2643.9   496.5  2857.4  495.75  3248.1  488.69  3687.8  485.51  3828.9  481.59
  3987.3   480.7  4127.5  483.16  4388.5  482.96  4556.7  485.84  4707.5  484.21
  4847.1  486.03  4877.9  485.35  4969.2  483.33  4980.5  481.54  4990.7  474.95
  5000.8  472.53  5017.1  479.13  5031.8   481.8    5081  485.24  5093.4  485.77
  5452.6  484.27  5493.6  482.63    5586  483.96  5616.8   482.1  5641.4  476.08
  5684.2  484.16  6047.8  491.41  6109.4   490.8  6519.5  502.25  6972.2   519.5
#Mann= 4 ,-1 , 0
  2643.9     .05       0  4847.1     .07       0    5081     .16       0
    5081     .05       0
#XS Ineff= 1 ,-1
  5155.2 5857.31  487.02
Permanent Ineff=
       F
Bank Sta=4877.9,5093.4
XS Rating Curve= 0 ,0
Exp/Cntr=0.3,0.1

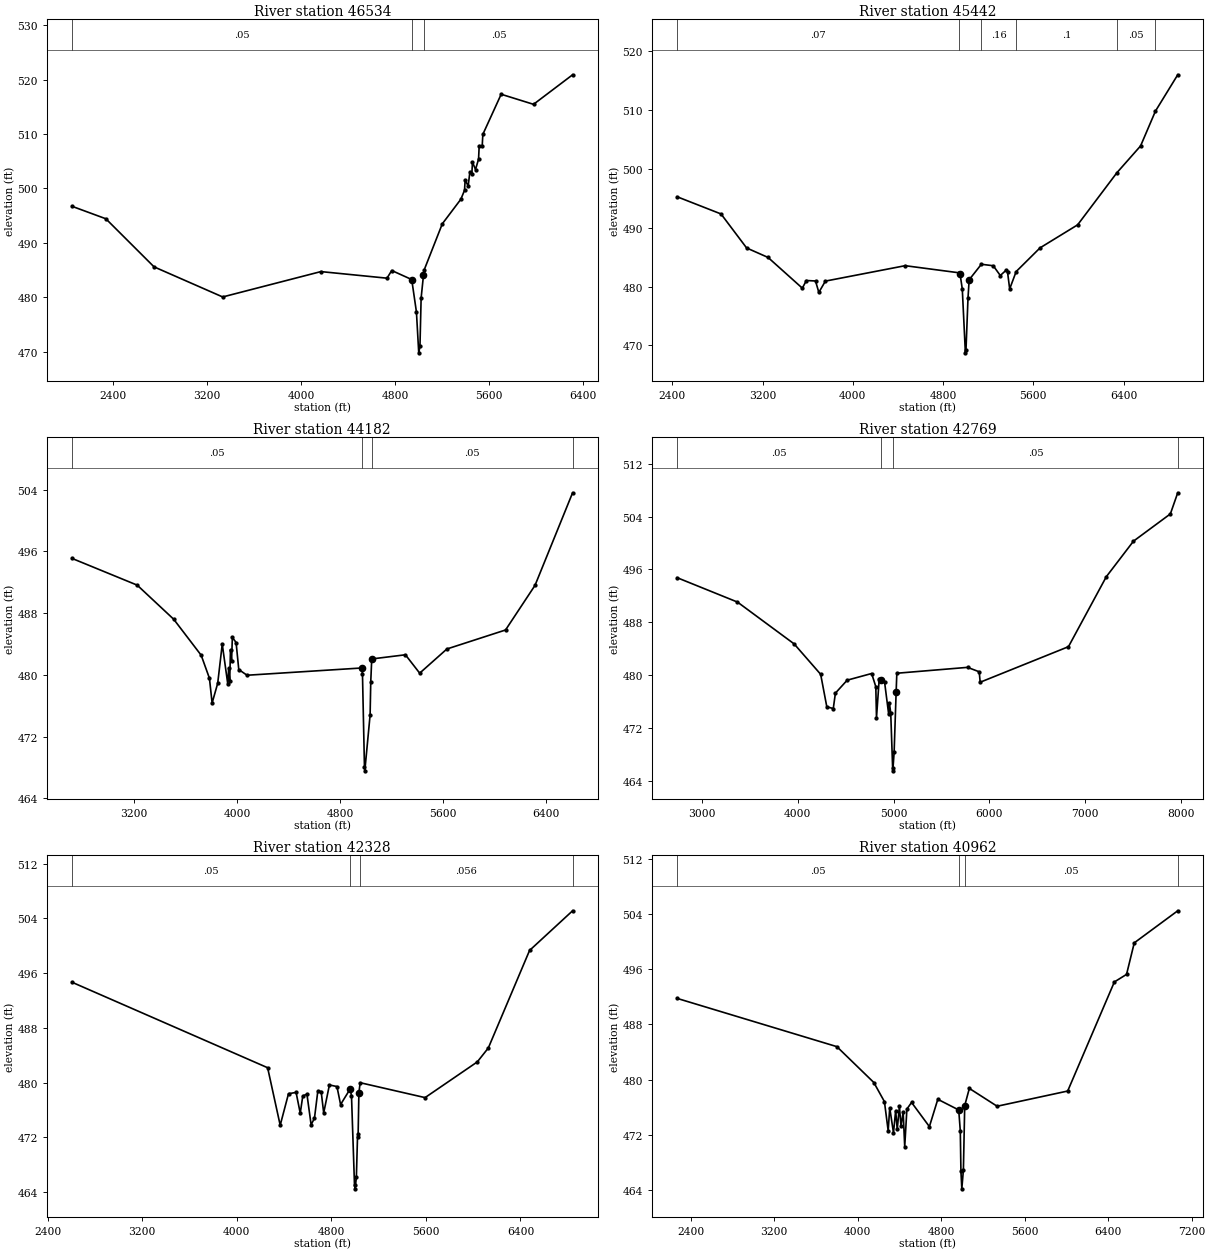
Type RM Length L Ch R = 1 ,46534   ,1092,1092,1092
BEGIN DESCRIPTION:
CHRISTMAS CREEK 45.0
END DESCRIPTION:
XS GIS Cut Line= 5
      3435655.57      10566054.8      3436896.89     10564231.87
      3436844.81      10563728.4      3436844.81     10563138.12
      3437156.98     10562236.29
#Sta/Elev= 30
  2051.9  496.71  2339.5  494.42  2749.5  485.58    3333  480.05  4167.9  484.71
  4730.1   483.5  4770.3  484.91  4940.3  483.25  4980.3   477.3    5000  469.78
  5010.3  470.96  5020.3  479.86  5040.3  484.06  5046.8  485.05  5200.3  493.49
  5358.1  498.01  5389.2  499.65  5394.5  501.52  5420.4  500.45  5434.7  503.03
  5451.5  502.69  5456.8  504.83  5482.7  503.47  5508.6  505.38  5513.9  507.84
  5539.7  507.85    5545  509.93  5700.8   517.3  5975.9  515.45  6308.1  520.88
#Mann= 3 ,-1 , 0
  2051.9     .05       0  4940.3     .07       0  5046.8     .05       0
Bank Sta=4940.3,5040.3
XS Rating Curve= 0 ,0
Exp/Cntr=0.3,0.1

Type RM Length L Ch R = 1 ,45442   ,1260,1260,1260
BEGIN DESCRIPTION:
CHRISTMAS CREEK 44.0
END DESCRIPTION:
XS GIS Cut Line= 4
      3435976.74     10566211.06      3437200.71     10564188.47
       3437565.3     10564127.71      3438025.36     10562487.11
#Sta/Elev= 30
  2442.4  495.25  2831.3  492.33  3058.3  486.55  3248.2  484.94  3552.1  479.72
  3587.9  481.02    3669  480.94  3698.4     479  3756.6  480.92  4463.8  483.54
    4942  482.33  4949.8  482.21  4970.1  479.57  4997.5  468.73  5002.9  469.26
  5020.8  478.07    5031  481.15  5139.2  483.78  5244.7  483.53    5307  481.87
    5359  482.78  5371.3  482.45  5390.1  479.59  5447.6  482.54  5659.6  486.57
  5992.5  490.48  6340.9  499.34  6550.6  503.89  6682.8  509.82    6880  515.98
#Mann= 6 ,-1 , 0
  2442.4     .07       0    4942     .07       0  5139.2     .16       0
  5447.6      .1       0  6340.9     .05       0  6682.8      .1       0
Bank Sta=4949.8,5031
XS Rating Curve= 0 ,0
Exp/Cntr=0.3,0.1

Type RM Length L Ch R = 1 ,44182   ,1413,1413,1413
BEGIN DESCRIPTION:
CHRISTMAS CREEK 42.0
END DESCRIPTION:
XS GIS Cut Line= 3
      3436542.08     10566491.68      3437942.11     10564691.64
       3438142.1     10563091.69
#Sta/Elev= 30
  2716.3  495.09  3223.1  491.63  3507.2  487.21  3720.8  482.55    3785  479.57
  3805.8  476.36  3849.3  478.92  3884.6  483.99    3928  478.78  3934.3  480.84
  3942.5  479.17  3948.8  483.29    3957  481.79  3963.3  484.86  3992.3   484.2
  4013.1   480.7  4077.3  479.96  4968.6   480.9    4975  480.18  4990.5  468.08
  4993.3  467.58  5034.5  474.83  5039.5  479.11  5047.1  482.07  5309.1  482.61
    5420  480.23  5631.6  483.36  6087.6  485.82  6316.9   491.6  6609.1  503.59
#Mann= 4 ,-1 , 0
  2716.3     .05       0  4968.6     .07       0  5047.1     .05       0
  6609.1     .05       0
Bank Sta=4968.6,5047.1
XS Rating Curve= 0 ,0
Exp/Cntr=0.3,0.1

Type RM Length L Ch R = 1 ,42769   ,441,441,441
BEGIN DESCRIPTION:
CHRISTMAS CREEK 41.0
END DESCRIPTION:
XS GIS Cut Line= 4
      3436740.67     10566601.65      3438511.48     10565551.32
      3438719.81      10565334.3       3438268.6     10562505.56
#Sta/Elev= 30
  2741.3  494.74  3370.8  491.05  3962.2  484.72  4238.9  480.12  4303.2   475.2
  4370.7  474.94  4392.9  477.27  4515.7  479.23    4771  480.24  4814.4  478.25
  4821.6  473.53  4849.9  479.39    4871  479.26  4906.5   478.9    4949  474.05
  4955.9  475.76  4970.1  474.33  4991.2  465.51  4994.4  466.01  5005.6  468.29
  5026.7  477.46  5033.9  480.28    5772  481.17  5893.6   480.5  5903.7  478.92
  6825.2   484.3  7220.1  494.89  7503.7  500.27  7888.5  504.39  7965.5  507.59
#Mann= 4 ,-1 , 0
  2741.3     .05       0    4871     .07       0  4994.4     .05       0
  7965.5     .05       0
Bank Sta=4871,5026.7
XS Rating Curve= 0 ,0
Exp/Cntr=0.3,0.1

Type RM Length L Ch R = 1 ,42328   ,1366,1366,1366
BEGIN DESCRIPTION:
CHRISTMAS CREEK 40.0
END DESCRIPTION:
XS GIS Cut Line= 5
      3436853.49     10566688.47      3438311.82     10566028.75
      3438737.17     10565638.12      3439223.28     10565464.51
      3440160.75     10564240.59
#Sta/Elev= 30
  2605.3  494.67  4260.6  482.17    4367  473.76  4437.3  478.37  4501.5  478.56
  4536.6  475.52  4558.2  478.04  4593.3  478.31  4628.5  473.85  4656.8  474.76
  4685.2  478.73  4713.6  478.69  4735.1  475.56  4783.4  479.65  4847.2  479.42
    4878  476.79  4958.6  479.05  4970.3  478.09  4995.8  464.99  5000.9  464.46
  5011.6  466.14  5021.3  472.07  5026.6  472.54  5032.9  478.48  5043.5  479.98
  5592.9   477.8  6034.8  483.02  6128.2  485.06  6477.2  499.32  6841.3  505.12
#Mann= 4 ,-1 , 0
  2605.3     .05       0  4958.6     .07       0  5043.5    .056       0
  6841.3     .05       0
Bank Sta=4958.6,5032.9
XS Rating Curve= 0 ,0
Exp/Cntr=0.3,0.1

Type RM Length L Ch R = 1 ,40962   ,1217,1217,1217
BEGIN DESCRIPTION:
CHRISTMAS CREEK 38.0
END DESCRIPTION:
XS GIS Cut Line= 4
       3437756.3     10568329.06      3439075.71     10567070.41
      3440256.27     10565342.98       3440325.7      10564466.4
#Sta/Elev= 30
  2271.4  491.79  3801.3  484.78  4155.3  479.57  4256.9  476.79  4292.8  472.56
  4307.7   475.9  4343.6  472.26  4364.5  475.49  4379.5  472.75  4400.4  476.13
  4415.4  473.23  4436.3  475.28  4451.2  470.25  4472.2  475.72    4517  476.67
  4687.6  473.16  4768.2  477.13  4968.6  475.58  4983.6  472.54  4989.7  466.71
  4998.2  464.12  5013.4   466.9    5026  476.22  5070.3  478.71  5336.4  476.12
  6012.3  478.33  6459.4  494.18  6576.2  495.28    6650  499.86  7066.5  504.52
#Mann= 4 ,-1 , 0
  2271.4     .05       0  4968.6     .07       0    5026     .05       0
  7066.5      .1       0
Bank Sta=4968.6,5026
XS Rating Curve= 0 ,0
Exp/Cntr=0.3,0.1

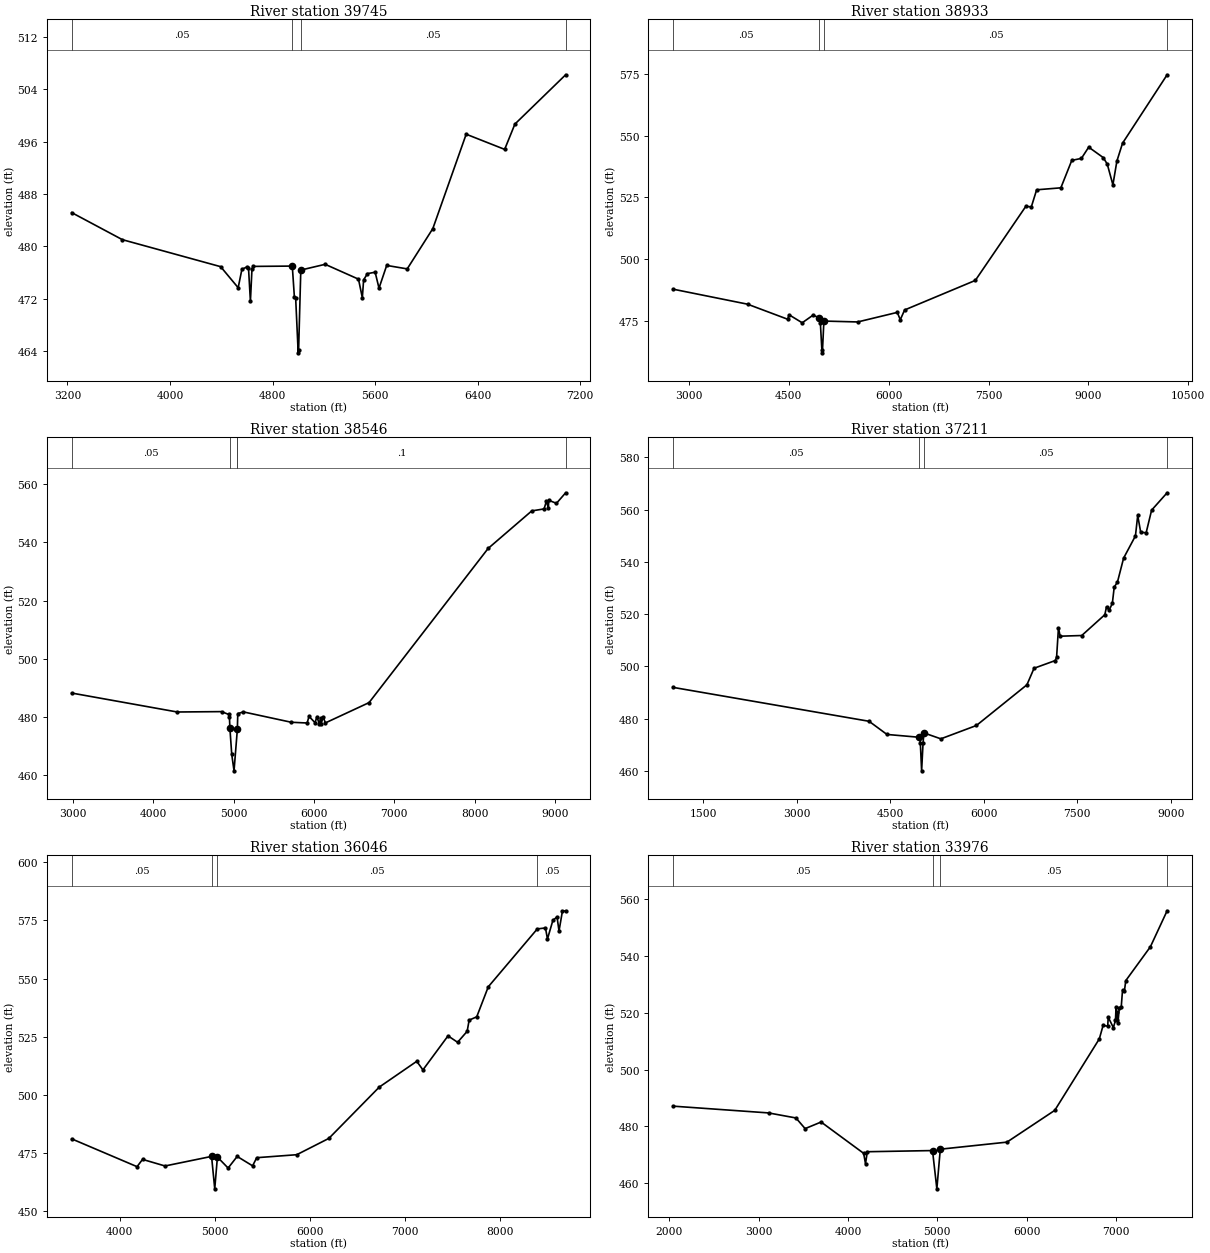
Type RM Length L Ch R = 1 ,39745   ,812,812,812
BEGIN DESCRIPTION:
CHRISTMAS CREEK 37.0
END DESCRIPTION:
XS GIS Cut Line= 3
      3439214.61     10567652.01       3440464.6     10566836.04
      3440490.63     10564475.83
#Sta/Elev= 30
  3233.1  485.14  3628.6     481    4395  476.87  4531.8  473.65  4560.9  476.47
  4603.4  476.86  4612.2  476.74  4627.3  471.58  4639.3  476.45  4648.4  476.91
    4954  476.96  4970.3  472.21  4980.3  472.03    5000  463.69  5003.3  464.19
  5020.3  476.35  5210.3  477.23  5470.3  474.96  5500.3  472.12  5510.3  474.85
  5540.3  475.81  5600.3  476.02  5630.3  473.58  5690.3  477.06  5850.3  476.53
  6050.3   482.7  6310.3  497.13  6610.4  494.81  6690.4  498.68  7086.2  506.22
#Mann= 4 ,-1 , 0
  3233.1     .05       0    4954     .07       0  5020.3     .05       0
  7086.2      .1       0
Bank Sta=4954,5020.3
XS Rating Curve= 0 ,0
Exp/Cntr=0.3,0.1

Type RM Length L Ch R = 1 ,38933   ,387,387,387
BEGIN DESCRIPTION:
CHRISTMAS CREEK 36.0
END DESCRIPTION:
XS GIS Cut Line= 4
      3438884.78     10568164.14      3439952.45     10567313.47
      3442278.84     10566020.07      3445447.18     10564804.81
#Sta/Elev= 30
  2762.8  487.72  3880.1  481.64  4482.2  475.54  4505.1  477.32  4701.5  474.09
  4863.9  477.18  4961.1  476.09  4974.2   474.1  4997.1  462.92  5004.3   461.9
  5026.3  474.26    5032  474.79  5534.8  474.43  6129.8  478.31  6174.6  475.32
  6239.8  479.29  7301.9  491.28  8059.1  521.27  8143.8  521.16  8223.2  528.04
  8586.8  528.84  8750.9  539.97  8895.6  540.78    9005  545.34  9223.8   541.1
  9283.9  538.46  9368.6  530.06  9428.7  539.71  9513.6  546.95 10183.1   574.7
#Mann= 4 ,-1 , 0
  2762.8     .05       0  4961.1     .07       0    5032     .05       0
 10183.1     .05       0
Bank Sta=4961.1,5032
XS Rating Curve= 0 ,0
Exp/Cntr=0.3,0.1

Type RM Length L Ch R = 1 ,38546   ,1335,1335,1335
BEGIN DESCRIPTION:
CHRISTMAS CREEK 35.0
END DESCRIPTION:
XS GIS Cut Line= 4
       3439266.7     10568190.19       3440733.7     10567261.39
      3441966.34     10566714.51      3444796.24     10565533.94
#Sta/Elev= 30
  2982.3  488.24    4297  481.73  4848.1  481.86  4935.7  480.91  4946.6  480.09
  4952.2  476.25  4975.4  467.17  5003.9  461.51  5045.3  475.73  5050.7  481.18
  5120.5  481.76  5717.3   478.2  5914.4  477.95  5937.6  480.23  6012.9  478.05
  6036.2  480.13  6064.5  477.68  6083.2  479.77  6088.6  477.51  6112.4  480.13
  6141.6  477.98  6685.2  484.95  8167.7  537.92  8711.3  550.83  8865.1  551.52
  8894.3  554.25  8918.1   551.7  8923.5  554.48  9018.8  553.43  9133.4  557.06
#Mann= 5 ,-1 , 0
  2982.3     .05       0  4952.2     .07       0  5045.3     .05       0
  5045.3      .1       0  9133.4     .05       0
Bank Sta=4952.2,5045.3
XS Rating Curve= 0 ,0
Exp/Cntr=0.3,0.1

Type RM Length L Ch R = 1 ,37211   ,1165,1165,1165
BEGIN DESCRIPTION:
CHRISTMAS CREEK 34.0
END DESCRIPTION:
XS GIS Cut Line= 4
      3438155.54     10568858.62      3441480.23     10568120.76
      3442643.42     10567244.03       3445195.5       10565560.
#Sta/Elev= 30
  1020.2  491.93  4161.4  478.95  4448.1  473.91  4968.6  472.82  4983.1  470.71
  5003.9  459.97  5026.8  470.66  5041.4  474.49  5312.1  472.23  5882.4  477.34
  6692.1  492.92  6806.5  499.26  7146.7  502.21  7167.8  503.44  7197.9  514.77
  7224.9  511.54  7571.2   511.8  7941.5  519.77  7968.6  522.84  8013.4  521.62
  8061.9  524.15    8092  530.37  8143.2  532.23  8242.5  541.45  8432.2  549.96
  8468.4   557.8  8516.6  551.32  8603.8  551.17  8691.1  559.81    8940  566.47
#Mann= 4 ,-1 , 0
  1020.2     .05       0  4968.6     .07       0  5041.4     .05       0
    8940     .05       0
Bank Sta=4968.6,5041.4
XS Rating Curve= 0 ,0
Exp/Cntr=0.3,0.1

Type RM Length L Ch R = 1 ,36046   ,2070,2070,2070
BEGIN DESCRIPTION:
CHRISTMAS CREEK 33.0
END DESCRIPTION:
XS GIS Cut Line= 4
      3441801.41     10569457.56      3442617.38     10568954.09
       3442877.8     10568042.64      3445551.42     10566124.23
#Sta/Elev= 30
  3493.6  481.14  4181.4  469.19  4239.3  472.32  4475.7  469.49  4965.4   473.6
  4998.9  459.67    5027  473.32  5139.6   468.6    5235  473.59    5397  469.55
  5440.7  473.05  5861.9  474.33  6199.6  481.34  6730.1  503.38  7124.3  514.45
  7189.3  510.76  7453.4  525.38  7554.1  522.62  7654.7  527.33  7675.6  532.14
  7755.4  533.56    7877  546.46  8392.8  571.32  8478.7  571.74  8499.6  566.99
  8556.5  574.97  8600.3  576.49  8621.2  570.44  8656.8   578.9    8691  579.11
#Mann= 4 ,-1 , 0
  3493.6     .05       0  4965.4     .07       0    5027     .05       0
  8392.8     .05       0
Bank Sta=4965.4,5027
XS Rating Curve= 0 ,0
Exp/Cntr=0.3,0.1

Type RM Length L Ch R = 1 ,33976   ,1530,1530,1530
BEGIN DESCRIPTION:
CHRISTMAS CREEK 31.0
END DESCRIPTION:
XS GIS Cut Line= 3
      3440529.97     10569865.94      3444129.95     10569065.95
      3445678.03     10568067.19
#Sta/Elev= 30
  2042.9  487.16  3110.5  484.78  3417.6     483  3520.2  479.25  3699.3  481.57
  4175.8  470.54  4196.3  466.88  4216.8  471.11  4946.5  471.52  4995.1  458.04
  5033.6     472  5779.8  474.49  6315.1  485.68    6814  510.86  6856.2  515.59
  6907.7  515.33  6913.7  518.49  6971.1  514.82  6994.7  517.35  7001.4  522.18
  7007.4  517.54  7016.6  520.35  7022.6  516.54  7037.7  521.82  7058.9  521.93
    7074  528.07  7095.1  527.79  7110.3  531.38  7385.5  543.28    7573  555.97
#Mann= 4 ,-1 , 0
  2042.9     .05       0  4946.5     .07       0  5033.6     .05       0
    7573     .16       0
Bank Sta=4946.5,5033.6
XS Rating Curve= 0 ,0
Exp/Cntr=0.3,0.1

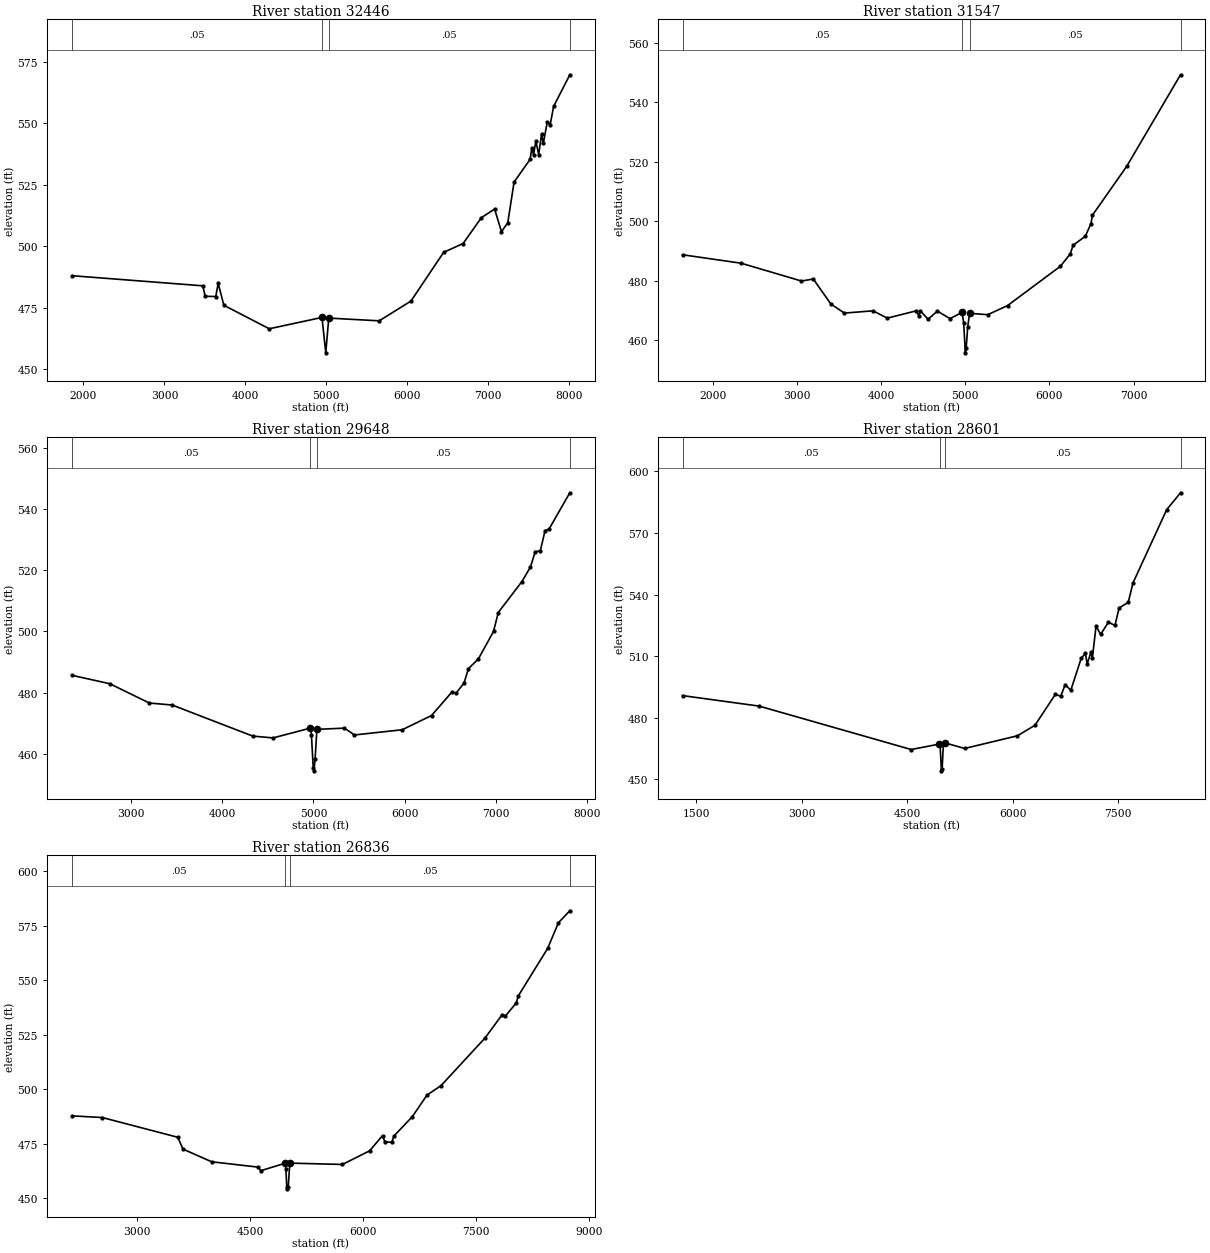
Type RM Length L Ch R = 1 ,32446   ,899,899,899
BEGIN DESCRIPTION:
CHRISTMAS CREEK 28.0
END DESCRIPTION:
XS GIS Cut Line= 4
      3440707.67     10570516.59      3443303.14     10570377.71
       3444440.3     10569926.32      3446133.03     10568329.07
#Sta/Elev= 30
    1857  488.01  3473.7  483.89  3503.8  479.63    3634  479.53    3664  484.88
  3734.1  475.97  4294.9  466.41  4945.8  471.02  4992.8  456.61  5029.5  470.75
  5653.2  469.64    6045  477.69  6448.3  497.52  6688.6   501.1  6915.2  511.66
  7077.8  515.12  7162.8  505.92  7240.5  509.54  7318.3  526.12  7516.4  535.37
  7537.8  540.03  7558.9  537.19  7587.2  542.78  7622.4  537.29    7658   545.7
    7679  541.83  7728.8  550.57    7764  549.34  7806.5   556.9    8007  569.79
#Mann= 4 ,-1 , 0
    1857     .05       0  4945.8     .07       0  5029.5     .05       0
    8007     .16       0
Bank Sta=4945.8,5029.5
XS Rating Curve= 0 ,0
Exp/Cntr=0.3,0.1

Type RM Length L Ch R = 1 ,31547   ,1899,1899,1899
BEGIN DESCRIPTION:
CHRISTMAS CREEK 27.0
END DESCRIPTION:
XS GIS Cut Line= 4
      3440898.66     10570733.61      3443346.55     10570638.12
       3444483.7     10570794.37      3446567.08     10569761.36
#Sta/Elev= 30
  1636.2  488.68  2331.6  485.85  3050.7  479.85  3190.8  480.53    3401   472.1
  3561.1  469.07  3901.4  469.83  4071.5  467.37  4414.6  469.82  4446.1  468.17
    4465  469.84  4555.9     467  4667.4  469.73  4818.3   467.2  4960.6  469.32
  4979.8  465.81  4999.8   455.7  5010.1  457.37  5027.7  464.39  5050.5     469
  5265.5  468.52  5502.1   471.6  6129.8   484.8  6247.7  488.95  6281.2  491.88
  6426.8   494.9  6494.1  499.16  6510.9  501.96    6920  518.46  7559.2  549.21
#Mann= 4 ,-1 , 0
  1636.2     .05       0  4960.6     .07       0  5050.5     .05       0
  7559.2     .16       0
Bank Sta=4960.6,5050.5
XS Rating Curve= 0 ,0
Exp/Cntr=0.3,0.1

Type RM Length L Ch R = 1 ,29648   ,1047,1047,1047
BEGIN DESCRIPTION:
CHRISTMAS CREEK 26.0
END DESCRIPTION:
XS GIS Cut Line= 3
      3441649.05     10571900.32      3445249.05     10571500.32
      3446798.09     10570500.94
#Sta/Elev= 30
  2349.1  485.66  2764.7  482.91  3199.9   476.6  3448.9  475.96  4334.3  465.81
  4558.2  465.22  4968.2  468.43  4978.2  466.23  4998.4  455.44  5005.7  454.47
  5018.5  458.22  5038.6  468.01  5340.5  468.41  5451.1  466.18  5974.7  467.88
  6296.9  472.53  6522.3  480.26  6566.1  479.82  6653.2  483.13  6702.1  487.84
    6811  491.01  6977.3  499.97  7028.8  506.13  7288.8  516.26  7382.5  520.98
    7434  525.94  7491.4  526.35  7542.9   532.9  7585.1  533.32  7814.7  545.23
#Mann= 4 ,-1 , 0
  2349.1     .05       0  4968.2     .07       0  5038.6     .05       0
  7814.7      .1       0
Bank Sta=4968.2,5038.6
XS Rating Curve= 0 ,0
Exp/Cntr=0.3,0.1

Type RM Length L Ch R = 1 ,28601   ,1765,1765,1765
BEGIN DESCRIPTION:
CHRISTMAS CREEK 23.0
END DESCRIPTION:
XS GIS Cut Line= 4
      3441011.44     10572513.13      3444336.13     10572278.75
      3445143.42     10572252.71       3447660.8     10570742.28
#Sta/Elev= 30
  1308.6  490.75  2396.6  485.64  4557.3  464.47  4957.7  467.12  4967.7   466.9
  4987.4  454.08  4997.7  455.18  5014.9  467.15  5037.7  467.69  5317.9  464.99
  6067.6  471.17  6316.4  476.29  6607.9  491.44  6681.8  490.37  6745.9  496.11
  6825.6  493.34  6973.3  508.88  7031.7  511.37  7058.9  506.18  7111.3  511.83
  7132.7  509.27  7185.2  524.71  7249.3  520.56  7360.1  526.53  7453.6  524.95
  7511.9  533.47    7642  536.22    7710  545.71  8188.3  581.37    8385  589.62
#Mann= 4 ,-1 , 0
  1308.6     .05       0  4967.7     .07       0  5037.7     .05       0
    8385     .05       0
Bank Sta=4957.7,5037.7
XS Rating Curve= 0 ,0
Exp/Cntr=0.3,0.1

Type RM Length L Ch R = 1 ,26836   ,1541,1541,1541
BEGIN DESCRIPTION:
CHRISTMAS CREEK 21.0
END DESCRIPTION:
XS GIS Cut Line= 4
      3441948.95     10573277.01      3444692.03     10573224.93
      3445707.66     10572929.79      3447997.17     10571316.73
#Sta/Elev= 30
  2138.5  487.86  2541.7   487.1  3541.9  478.05  3611.9  472.62    3992  466.81
  4612.1  464.35  4642.1  462.72  4965.5  466.13  4975.9   463.4  4987.5  455.35
  4996.5  454.41  5007.1  455.32  5027.9   466.2  5725.7  465.59    6085  471.82
  6257.4  478.79    6287  476.02  6379.3  475.69  6408.9  478.65  6652.8  487.51
  6846.1  497.38  7033.4  501.74  7613.4  523.45  7842.5   534.2  7886.9  533.68
  8029.8  539.59  8059.4  542.98  8446.1  564.61  8588.9  576.38  8740.4  581.87
#Mann= 4 ,-1 , 0
  2138.5     .05       0  4965.5     .07       0  5027.9     .05       0
  8740.4     .05       0
Bank Sta=4965.5,5027.9
XS Rating Curve= 0 ,0
Exp/Cntr=0.3,0.1