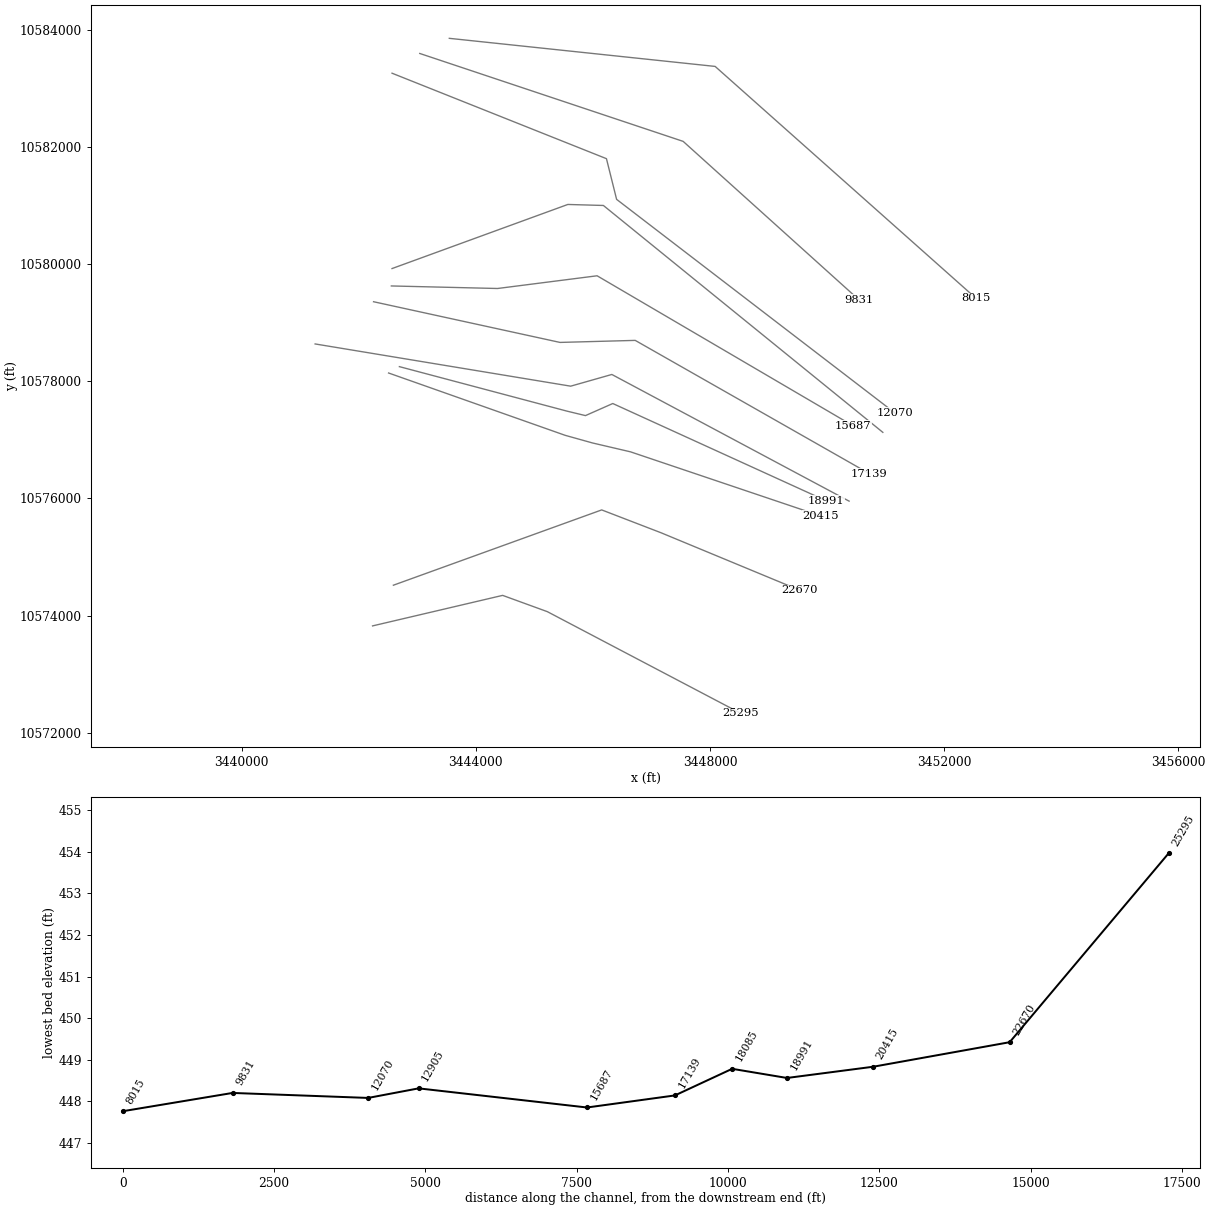
HEC-RAS study CHRISTMAS CREEK.prj: CHRISTMAS CREEK Base Level Engineering

--- CHRISTMAS CREEK.g01 (geometry) --- (continued)

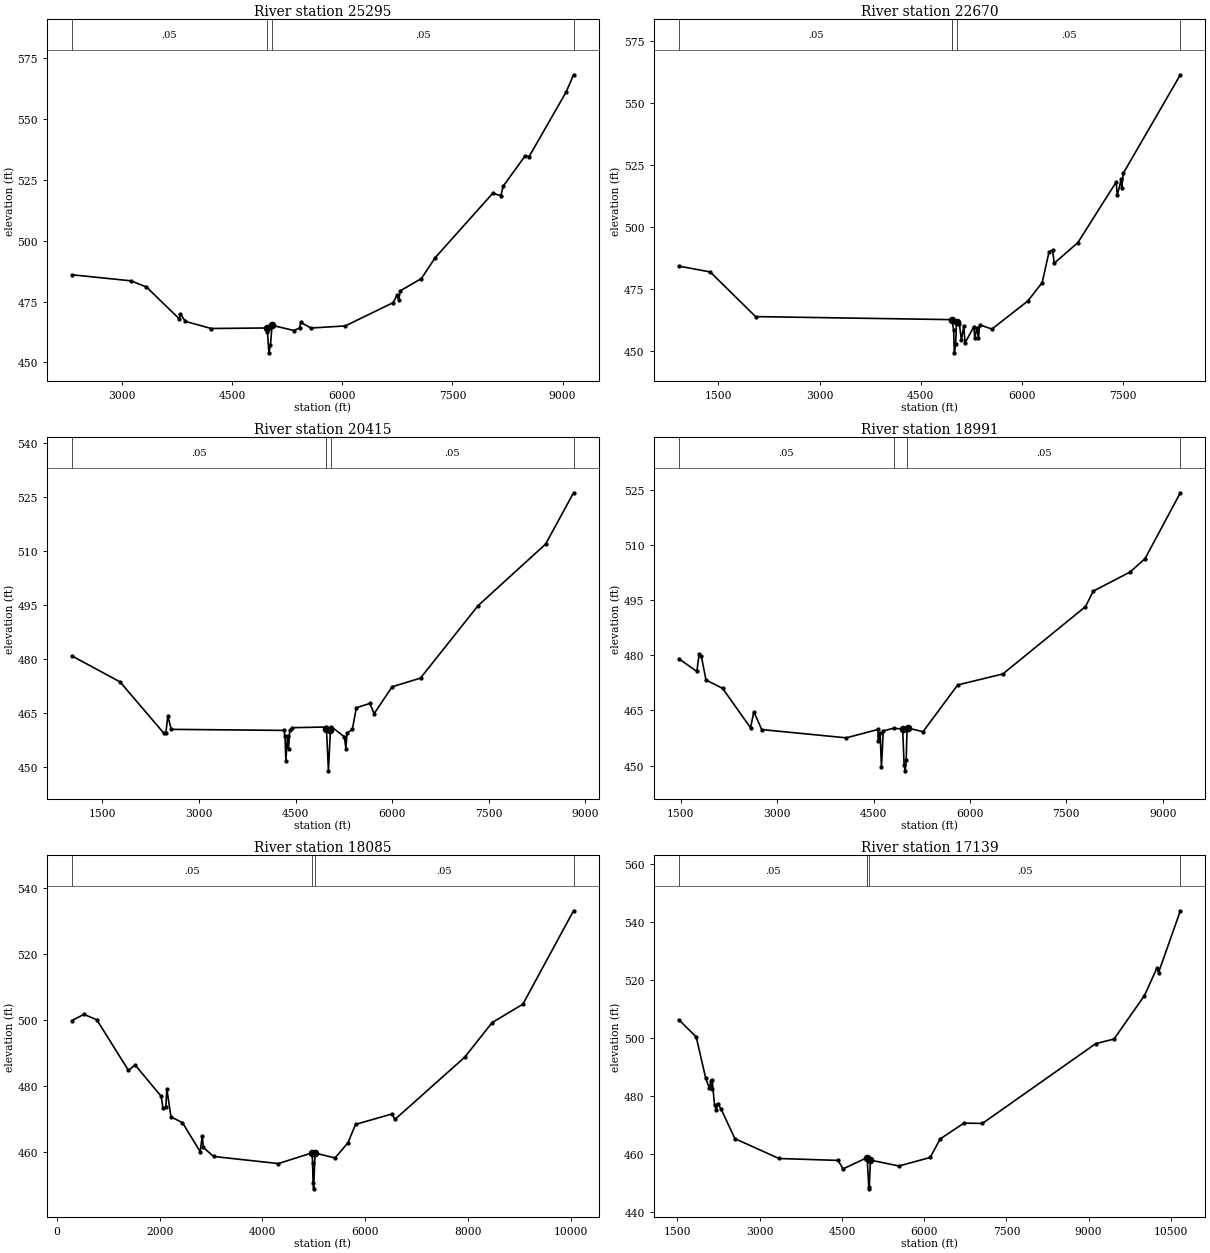
Type RM Length L Ch R = 1 ,25295   ,2625,2625,2625
BEGIN DESCRIPTION:
CHRISTMAS CREEK 20.0
END DESCRIPTION:
XS GIS Cut Line= 4
      3442235.43     10573823.89      3444457.66     10574344.72
      3445221.55     10574066.94        3448528.     10572331.27
#Sta/Elev= 30
  2319.5  485.97  3121.4  483.49  3332.9  480.96  3778.7  467.92  3795.1  469.81
  3863.6  466.86  4213.5  463.94  4968.5  464.16  4980.6  462.51  5000.1  453.96
  5021.7  457.08  5042.9  465.24  5340.9  463.12  5418.2  464.18  5434.6  466.44
  5573.5  464.14  6040.8     465  6691.6  474.54  6745.9  477.62    6768  475.59
    6790  479.41  7076.7  484.42  7263.8  492.95  8046.9  519.33  8159.9  518.45
  8189.5  522.23  8492.6  534.85  8543.9  534.45    9049  560.96  9149.1  567.98
#Mann= 4 ,-1 , 0
  2319.5     .05       0  4968.5     .07       0  5042.9     .05       0
  9149.1     .16       0
Bank Sta=4968.5,5042.9
XS Rating Curve= 0 ,0
Exp/Cntr=0.3,0.1

Type RM Length L Ch R = 1 ,22670   ,2255,2255,2255
BEGIN DESCRIPTION:
CHRISTMAS CREEK 19.0
END DESCRIPTION:
XS GIS Cut Line= 4
      3442591.32     10574518.32      3446150.37     10575803.05
      3447165.99     10575412.43      3449535.82     10574431.51
#Sta/Elev= 30
   912.3  484.33  1377.1  481.97  2050.7     464  4962.6  462.78  4987.2   458.6
  4997.7  449.42  5017.2  452.97  5030.1  461.64  5071.9  461.21  5101.9  454.63
  5137.3  460.11  5156.5  453.38  5287.3  459.99  5301.2  455.22  5331.2   459.5
  5355.8  455.33    5373   460.7  5555.1  458.99  6087.8  470.28  6300.6  477.69
  6401.6  490.01  6454.8  490.77  6478.7  485.47  6829.9  493.78  7396.2  518.09
  7414.3  512.87  7473.3  519.31  7479.3  515.66  7502.6  521.65  8349.1  561.31
#Mann= 5 ,-1 , 0
   912.3     .05       0  4962.6     .16       0  4962.6     .07       0
  5030.1     .05       0  8349.1     .16       0
Bank Sta=4962.6,5030.1
XS Rating Curve= 0 ,0
Exp/Cntr=0.3,0.1

Type RM Length L Ch R = 1 ,20415   ,1424,1424,1424
BEGIN DESCRIPTION:
CHRISTMAS CREEK 18.0
END DESCRIPTION:
XS GIS Cut Line= 5
      3442509.36     10578139.35      3445525.81     10577075.99
      3445992.39     10576945.78      3446643.44     10576793.87
      3449897.91      10575698.2
#Sta/Elev= 30
  1029.5  480.78  1774.6  473.57  2449.6   459.4  2485.9  459.42  2516.9  464.16
  2568.1  460.37  4317.5  460.08  4335.1   458.4  4348.6  451.61  4374.4  458.56
  4390.2  454.83  4408.6  460.09  4442.1  460.83  4973.2  461.02    4979  460.46
  5009.5  448.83  5040.6  460.28  5050.9  461.16  5256.2  458.31  5281.3  455.03
  5297.3  459.31  5380.8  460.34  5442.7  466.38  5651.4  467.57  5719.6  464.76
  5997.8   472.2  6438.8  474.63  7331.5  494.76  8381.1   511.9  8814.8  526.17
#Mann= 5 ,-1 , 0
  1029.5     .05       0  4973.2     .12       0  4973.2     .07       0
  5050.9     .05       0  8814.8     .16       0
Bank Sta=4979,5040.6
XS Rating Curve= 0 ,0
Exp/Cntr=0.3,0.1

Type RM Length L Ch R = 1 ,18991   ,906,906,906
BEGIN DESCRIPTION:
CHRISTMAS CREEK 17.0
END DESCRIPTION:
XS GIS Cut Line= 5
      3442693.77     10578247.87      3445558.37     10577488.32
      3445873.04     10577412.36      3446339.62     10577618.53
      3449985.44     10575958.38
#Sta/Elev= 30
  1470.3  479.07  1750.6  475.61  1785.7  480.31  1820.3  479.77  1892.7  473.28
  2151.4  471.01  2585.9  460.28  2637.6  464.65  2759.6  459.79  4075.7  457.54
  4567.6  459.81  4572.7  456.66  4602.3  458.87  4622.9  449.47  4651.4  459.43
  4811.2  460.15  4953.4  459.94  4975.2  450.22    4991  448.56    5008  451.47
    5020  459.58  5029.9  460.22    5270  459.21  5808.8  471.93  6512.1  474.93
  7797.7  493.25  7918.5  497.46  8489.9  502.65  8724.5   506.3  9273.7  524.23
#Mann= 4 ,-1 , 0
  1470.3     .05       0  4811.2     .07       0    5020     .05       0
  9273.7     .16       0
Bank Sta=4953.4,5029.9
XS Rating Curve= 0 ,0
Exp/Cntr=0.3,0.1

Type RM Length L Ch R = 1 ,18085   ,946,946,946
BEGIN DESCRIPTION:
CHRISTMAS CREEK 16.0
END DESCRIPTION:
XS GIS Cut Line= 4
      3441254.12     10578635.08      3445620.42      10577914.6
      3446323.54     10578114.25      3450377.26     10575952.85
#Sta/Elev= 30
   298.8   499.8   529.8  501.67   779.4  500.02  1395.6  484.67  1523.1  486.35
  2029.9  476.87  2067.9   473.2  2121.1  473.52  2141.4  479.04  2222.4  470.58
  2445.4  468.84    2790  460.05  2830.6  464.85  2850.8  461.32  3050.8  458.59
  4310.3  456.44    4965  459.68  4975.4   456.7  4984.2  450.61  4995.9  448.78
  5023.3  459.62    5412  458.15  5662.8  462.73  5810.9  468.32  6512.9  471.45
  6578.7  469.86  7933.2  488.68  8465.2  499.16  9063.1  504.74   10049  533.06
#Mann= 4 ,-1 , 0
   298.8     .05       0    4965     .07       0  5023.3     .05       0
   10049     .16       0
Bank Sta=4965,5023.3
XS Rating Curve= 0 ,0
Exp/Cntr=0.3,0.1

Type RM Length L Ch R = 1 ,17139   ,1452,1452,1452
BEGIN DESCRIPTION:
CHRISTMAS CREEK 15.0
END DESCRIPTION:
XS GIS Cut Line= 4
      3442252.39     10579355.56      3445438.13     10578661.13
      3446722.85     10578695.85      3450724.58     10576421.54
#Sta/Elev= 30
  1524.9  506.43  1841.9   500.5  2015.9  486.22  2082.8  482.82    2108  485.15
  2126.8  482.71  2131.9  485.75  2175.8  477.13  2210.3  475.25  2230.8  477.54
  2292.2  475.78  2547.9  465.44  3351.3   458.6  4428.5  457.94  4521.5  455.03
  4959.5  458.89  4991.8  448.14  4999.5  448.88  5019.5  458.04  5539.7  456.02
  6109.8  458.95  6292.9  465.36  6725.4  470.79  7062.7  470.69  9130.1   498.2
  9462.9  499.78 10018.2  514.75 10245.1   524.2 10276.2  522.71 10673.5     544
#Mann= 5 ,-1 , 0
  1524.9     .05       0  4959.5     .16       0  4959.5     .07       0
  4999.5     .05       0 10673.5     .16       0
Bank Sta=4959.5,5019.5
XS Rating Curve= 0 ,0
Exp/Cntr=0.3,0.1

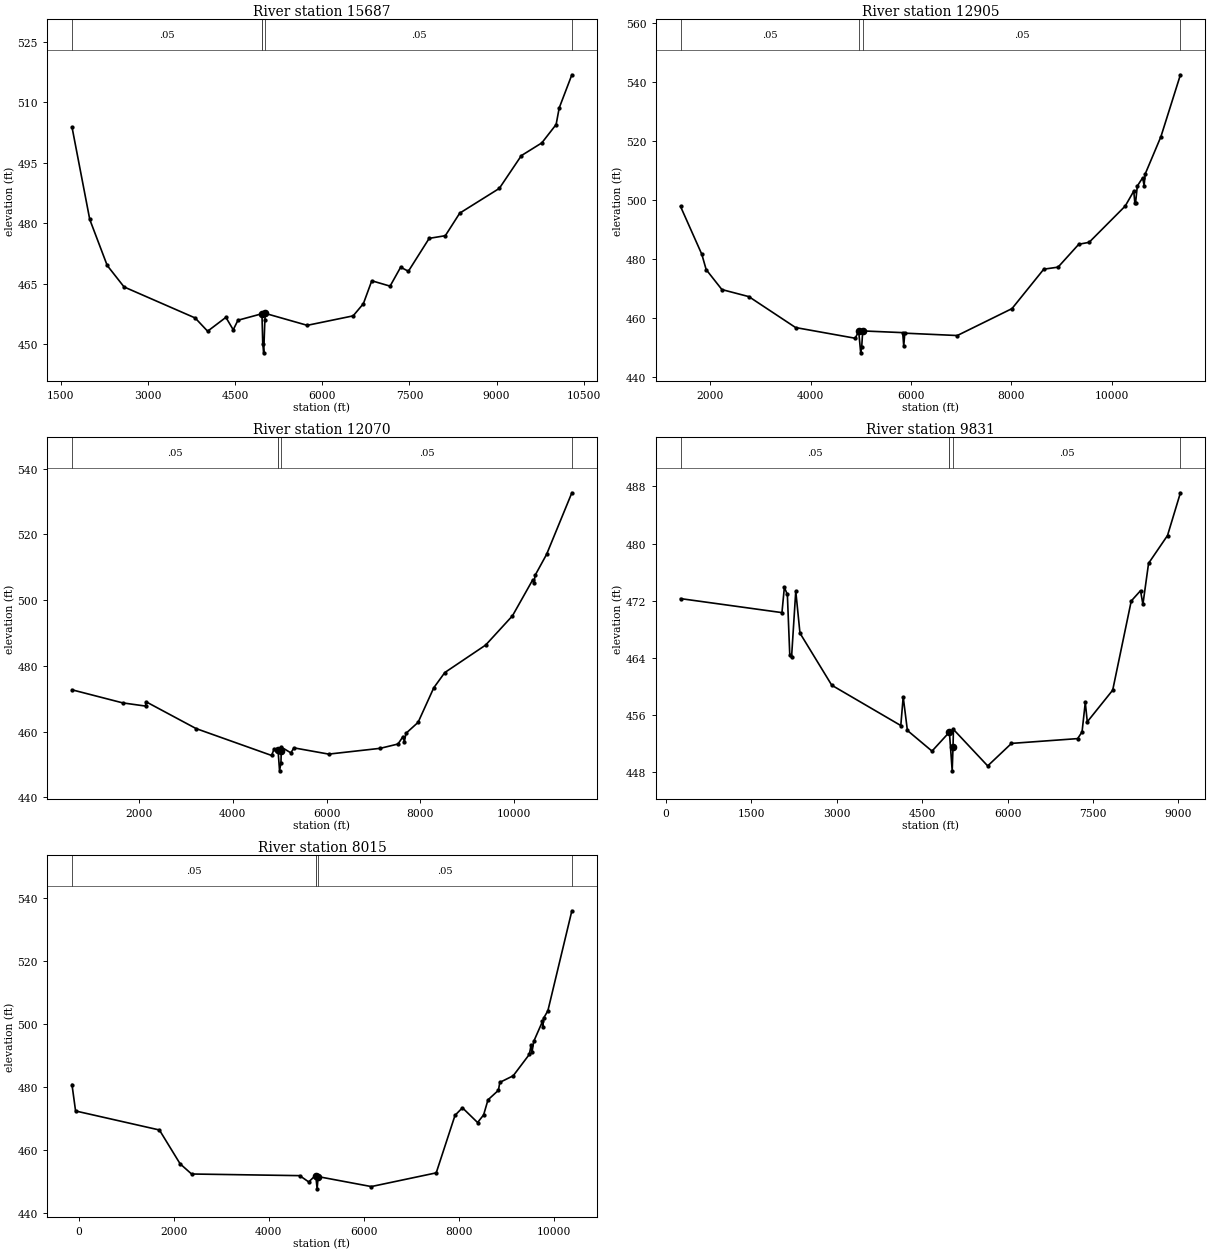
Type RM Length L Ch R = 1 ,15687   ,2782,2782,2782
BEGIN DESCRIPTION:
CHRISTMAS CREEK 13.0
END DESCRIPTION:
XS GIS Cut Line= 4
      3442556.19     10579624.67      3444370.42     10579581.26
      3446071.81     10579798.28      3450446.85     10577237.49
#Sta/Elev= 30
  1695.2  503.93  2001.2  480.96  2301.3  469.54  2591.4  464.21  3814.1  456.51
  4028.7  453.22  4343.1  456.66  4469.3  453.57    4550  455.94  4963.3  457.56
  4976.8  450.13  4993.3  447.85  5013.7  456.07  5023.8  457.63  5742.1  454.68
    6532  457.03  6707.9  460.05  6852.5  465.74  7167.3  464.41  7349.1  469.11
  7482.1   468.1  7839.9  476.27  8117.5  476.93  8365.6  482.53  9046.2  488.67
  9425.5  496.81  9777.4  499.97 10023.7  504.53 10076.5  508.64 10294.5  516.88
#Mann= 5 ,-1 , 0
  1695.2     .05       0  4963.3     .12       0  4963.3     .07       0
  5023.8     .05       0 10294.5     .16       0
Bank Sta=4963.3,5023.8
XS Rating Curve= 0 ,0
Exp/Cntr=0.3,0.1

Type RM Length L Ch R = 1 ,12905   ,835,835,835
BEGIN DESCRIPTION:
CHRISTMAS CREEK 12.0
END DESCRIPTION:
XS GIS Cut Line= 4
      3442568.36     10579921.55      3445571.81     10581015.29
      3446179.45     10580997.93      3450953.64      10577126.5
#Sta/Elev= 30
  1412.1  497.87  1836.3  481.65  1922.7  476.48  2235.6  469.73  2772.1  467.34
  3702.7  456.87  4888.9  453.25  4958.9  455.59  4998.7  448.31    5019  450.44
    5039  455.73  5834.5  455.15  5855.3  450.62  5876.4  454.97  6921.5  454.17
    8010  463.28  8642.9  476.63  8927.4  477.32  9339.7  485.07  9545.7  485.72
 10263.8  497.99 10434.1  503.05 10455.6  499.11   10470  499.09 10505.1  504.79
 10612.2   507.6   10640  504.93 10661.8  508.86 10974.8   521.5   11363  542.44
#Mann= 4 ,-1 , 0
  1412.1     .05       0  4958.9     .07       0    5039     .05       0
   11363     .16       0
Bank Sta=4958.9,5039
XS Rating Curve= 0 ,0
Exp/Cntr=0.3,0.1

Type RM Length L Ch R = 1 ,12070   ,2239,2239,2239
BEGIN DESCRIPTION:
CHRISTMAS CREEK 11.0
END DESCRIPTION:
XS GIS Cut Line= 4
      3442568.29     10583254.89      3446231.53     10581796.54
      3446405.14      10581102.1      3451161.81     10577456.48
#Sta/Elev= 30
   573.7  472.73    1655  468.75  2140.5  467.78  2149.2  469.11  3219.4  460.93
  4826.9  452.76  4882.4  454.77  4964.8  454.36  4996.7  448.08  5026.7  450.55
  5033.1   454.2  5038.2  455.26  5238.1  453.55  5302.5  455.07    6044  453.17
  7142.8  454.93  7520.8  456.24  7626.8   458.5  7655.9  456.94  7691.2   459.5
  7948.7  462.83  8283.2  473.35    8518  477.98  9388.3  486.34  9959.4  495.23
 10394.2  506.25 10416.4  505.36 10444.6  507.62 10686.5  513.92 11225.4  532.66
#Mann= 5 ,-1 , 0
   573.7     .05       0  4964.8     .16       0  4964.8     .07       0
  5038.2     .05       0 11225.4     .16       0
Bank Sta=4964.8,5033.1
XS Rating Curve= 0 ,0
Exp/Cntr=0.3,0.1

Type RM Length L Ch R = 1 ,9831    ,1816,1816,1816
BEGIN DESCRIPTION:
CHRISTMAS CREEK 9.0
END DESCRIPTION:
XS GIS Cut Line= 3
       3443042.1     10583591.64      3447542.11     10582091.64
       3450542.1     10579391.65
#Sta/Elev= 30
   255.2   472.3  2036.6  470.34  2078.8  473.88  2131.5  472.88  2173.7  464.44
  2205.3  464.12  2279.1  473.35  2352.9  467.47  2911.5  460.18  4123.7  454.54
  4165.9  458.55  4239.7  453.85  4671.9  450.96  4977.5  453.62  5026.4   448.2
  5040.9  451.53  5048.3     454    5650  448.89  6067.8  452.04  7229.3  452.71
    7307  453.64  7363.8  457.77    7399  455.06  7845.2  459.49  8171.1  471.97
    8334  473.41  8375.9   471.5  8475.3  477.24  8807.9  481.13  9034.7  487.11
#Mann= 5 ,-1 , 0
   255.2     .05       0  4977.5     .12       0  4977.5     .07       0
  5048.3     .05       0  9034.7     .05       0
Bank Sta=4977.5,5040.9
XS Rating Curve= 0 ,0
Exp/Cntr=0.3,0.1

Type RM Length L Ch R = 1 ,8015    ,0,0,0
BEGIN DESCRIPTION:
CHRISTMAS CREEK 1.0
END DESCRIPTION:
XS GIS Cut Line= 3
      3443546.76     10583849.93      3448088.42     10583370.76
      3452546.72     10579412.45
#Sta/Elev= 30
    -142  480.79   -66.2  472.42  1699.3   466.4  2135.9  455.68  2377.2  452.46
  4653.7  451.94  4844.4  449.95  4993.2  452.11  4994.7  451.67  5021.4  447.76
  5043.4  451.63  6162.4  448.48  7529.7  452.82  7926.1  471.05  8081.6  473.43
  8401.1  468.76  8528.2  471.18  8620.2  475.95  8840.1  478.97  8868.6  481.47
  9151.2  483.56  9491.6  490.35  9526.7  493.21  9548.5  491.14  9583.6  494.46
  9767.6  500.76  9775.1  498.96  9789.3  501.75  9881.3  504.15 10386.8  535.82
#Mann= 5 ,-1 , 0
    -142     .05       0  4993.2     .12       0  4993.2     .07       0
  5043.4     .05       0 10386.8     .16       0
Bank Sta=4994.7,5043.4
XS Rating Curve= 0 ,0
Exp/Cntr=0.3,0.1

Chan Stop Cuts=-1
Use User Specified Reach Order=0
Composite Channel Slope=5