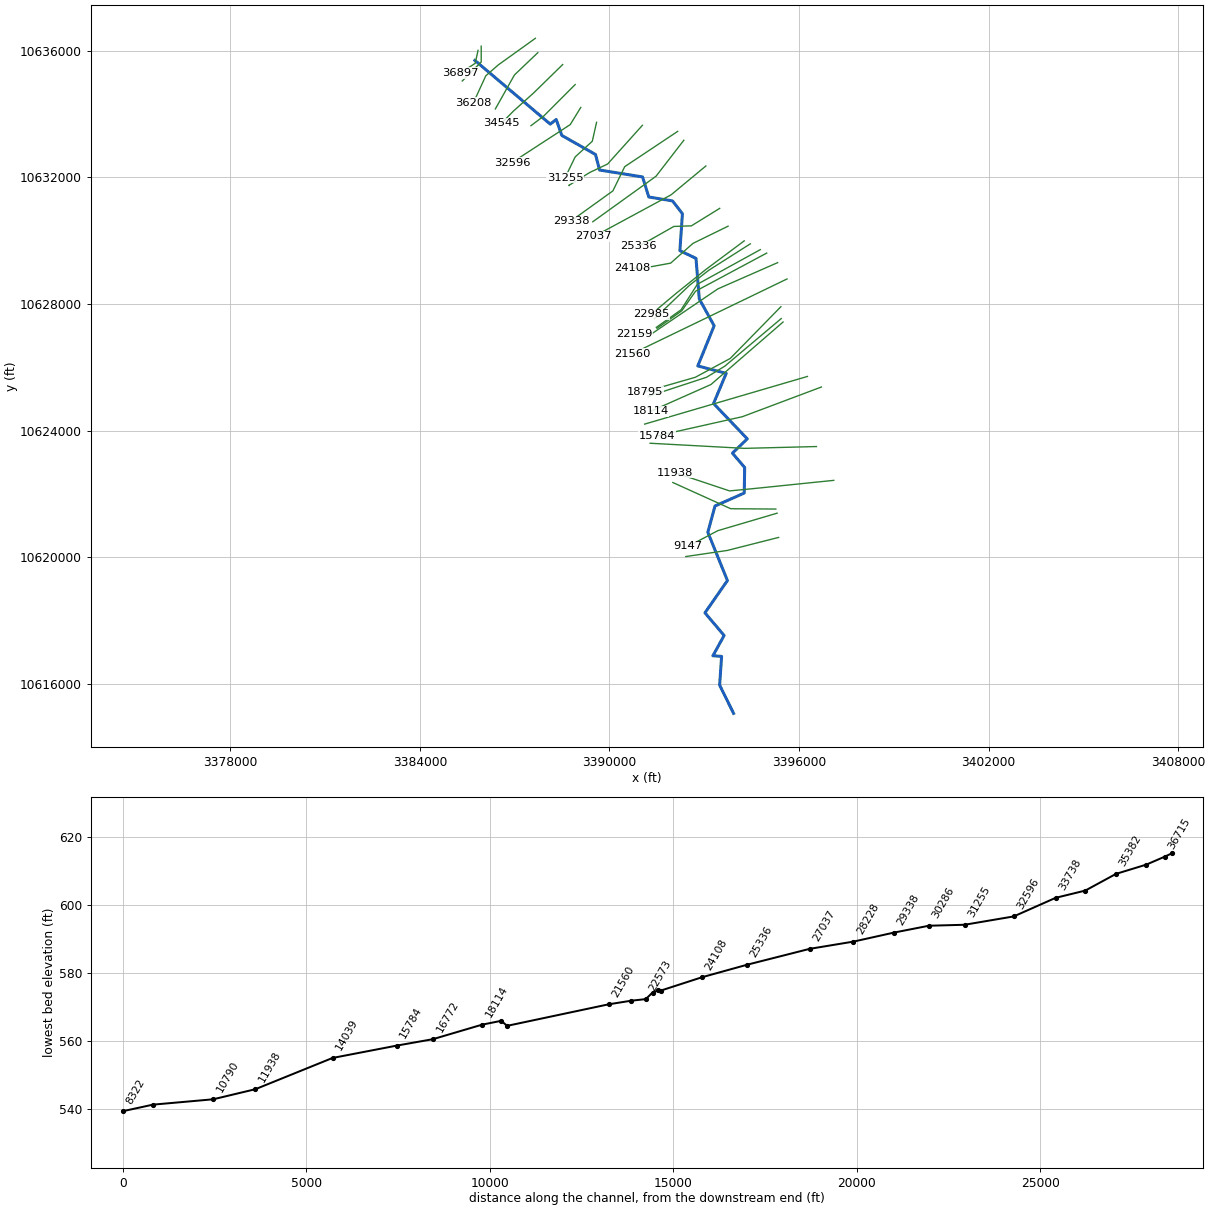
--- GRAYS BRANCH.prj (project) ---

Proj Title=GRAYS BRANCH Base Level Engineering
Current Plan=p01
Default Exp/Contr=0.3,0.1
English Units
Geom File=g01
Flow File=f01
Plan File=p01
BEGIN DESCRIPTION:
GRAYS BRANCH
END DESCRIPTION:

--- GRAYS BRANCH.p01 (plan) ---

Plan Title=Multiple Run
Short Identifier=Multiple
Geom File=g01
Flow File=f01
Subcritical Flow
K Sum by GR= 0
Std Step Tol= 0.01
Critical Tol= 0.01
Num of Std Step Trials= 20
Max Error Tol= 0.3
Flow Tol Ratio= 0.001
Split Flow NTrial= 30
Split Flow Tol= 0.02
Split Flow Ratio= 0.02
Log Output Level= 0
Friction Slope Method= 1
Unsteady Friction Slope Method= 2
Unsteady Bridges Friction Slope Method= 1
Parabolic Critical Depth
Global Vel Dist=  1 , 1 , 1
Global Log Level= 0
CheckData=True
Encroach Param= -1, 0, 0, 0
BEGIN DESCRIPTION:
Multiple Run
END DESCRIPTION:

--- GRAYS BRANCH.f01 (steady flow) ---

Flow Title=Multiple
Number of Profiles=7
Profile Names=10-year,25-year,50-year,1pct_min,100-year,1pct_plu,500-year
River Rch & RM= GRAYS BRANCH,Reach-1,36897
     334     416     476     396     536     725     678
River Rch & RM= GRAYS BRANCH,Reach-1,33738
     504     640     740     622     842    1138    1087
River Rch & RM= GRAYS BRANCH,Reach-1,27037
     566     721     837     705     954    1290    1237
River Rch & RM= GRAYS BRANCH,Reach-1,22912
     661     850     991     839    1135    1535    1487
River Rch & RM= GRAYS BRANCH,Reach-1,18795
     756     974    1138     965    1305    1765    1714
River Rch & RM= GRAYS BRANCH,Reach-1,9147
     875    1137    1335    1137    1538    2080    2039
River Rch & RM= GRAYS BRANCH,Reach-1,7337
     930    1208    1418    1207    1633    2208    2164
Boundary for River Rch & Prof#=GRAYS BRANCH,Reach-1,1
Up Type=0
Dn Type=3
Dn Slope=0.005
Boundary for River Rch & Prof#=GRAYS BRANCH,Reach-1,2
Up Type=0
Dn Type=3
Dn Slope=0.005
Boundary for River Rch & Prof#=GRAYS BRANCH,Reach-1,3
Up Type=0
Dn Type=3
Dn Slope=0.005
Boundary for River Rch & Prof#=GRAYS BRANCH,Reach-1,4
Up Type=0
Dn Type=3
Dn Slope=0.005
Boundary for River Rch & Prof#=GRAYS BRANCH,Reach-1,5
Up Type=0
Dn Type=3
Dn Slope=0.005
Boundary for River Rch & Prof#=GRAYS BRANCH,Reach-1,6
Up Type=0
Dn Type=3
Dn Slope=0.005
Boundary for River Rch & Prof#=GRAYS BRANCH,Reach-1,7
Up Type=0
Dn Type=3
Dn Slope=0.005

--- GRAYS BRANCH.g01 (geometry) ---

Geom Title=Existing Conditions

River Reach=GRAYS BRANCH,Reach-1
Reach XY= 30
      3385741.54     10635691.14      3388125.68     10633679.42
      3388314.11     10633826.17      3388492.35     10633322.29
      3389558.90     10632719.95      3389686.10     10632229.49
      3391046.99     10632011.68      3391245.22     10631377.73
      3391995.44     10631254.46      3392309.00     10630850.33
      3392228.61     10629682.55      3392738.23     10629439.75
      3392841.98     10628160.64      3393312.28     10627310.63
      3392795.04     10626042.88      3393694.18     10625808.23
      3393293.68     10624857.45      3394361.20     10623741.10
      3393891.47     10623288.50      3394278.97     10622835.66
      3394264.41     10622028.97      3393339.48     10621619.63
      3393112.56     10620791.07      3393732.87     10619266.37
      3393021.79     10618247.01      3393627.93     10617530.76
      3393273.29     10616890.42      3393548.40     10616871.04
      3393486.68     10615962.38      3393928.24     10615071.48

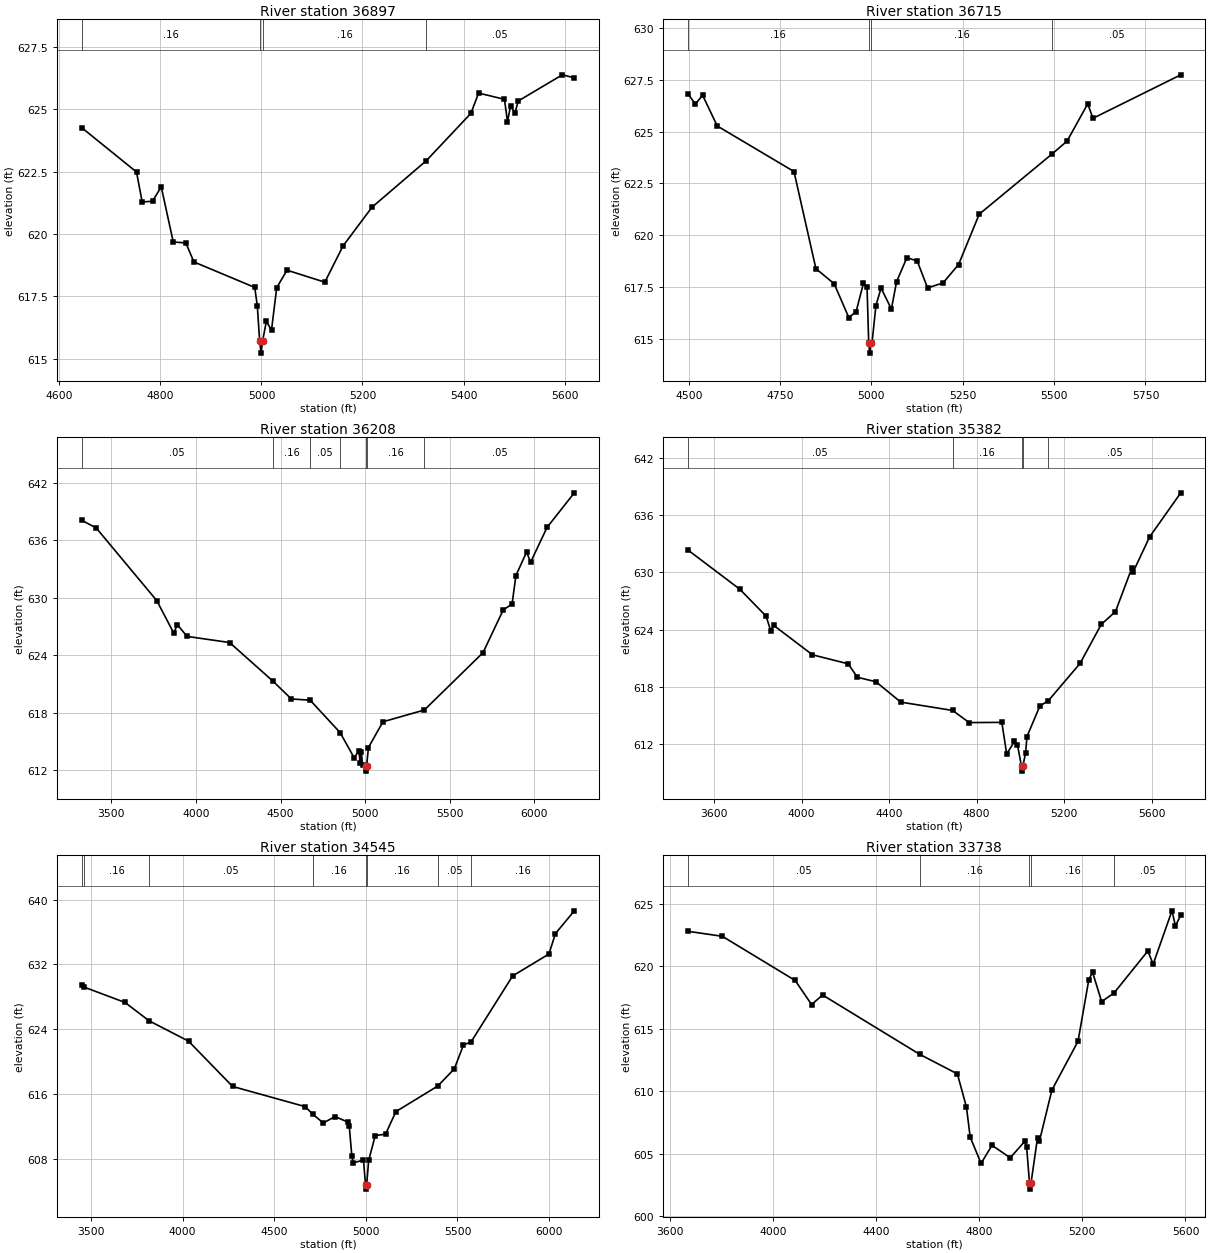
Type RM Length L Ch R = 1,36897,182,182,182
BEGIN DESCRIPTION:
GRAYS BRANCH 52.1
END DESCRIPTION:
XS GIS Cut Line= 3
      3385841.42     10636008.85      3385751.15     10635599.17
      3385286.50     10635294.02
#Sta/Elev= 30
  4643.9  624.26  4752.7  622.48  4763.9  621.28  4784.4  621.31  4801.6  621.89
  4825.4  619.68  4850.4  619.64  4866.3  618.88  4986.7  617.86  4991.8  617.13
  4996.4  615.73  4999.2  615.23  5002.4  615.73  5009.7  616.50  5019.9  616.15
  5030.2  617.85  5050.6  618.55  5125.4  618.07  5161.5  619.52  5218.8  621.07
  5326.2  622.93  5414.7  624.83  5429.8  625.64  5481.0  625.39  5487.0  624.50
  5493.0  625.11  5502.1  624.85  5508.1  625.32  5595.5  626.37  5619.3  626.25
#Mann=4,-1,0
  4643.9    0.16       0  4996.4    0.07       0  5002.4    0.16       0
  5326.2    0.05       0
Bank Sta=4996.4,5002.4
Exp/Cntr=0.3,0.1

Type RM Length L Ch R = 1,36715,507,507,507
BEGIN DESCRIPTION:
GRAYS BRANCH 52.0
END DESCRIPTION:
XS GIS Cut Line= 3
      3385942.11     10636141.68      3385942.11     10635641.64
      3385342.08     10635041.62
#Sta/Elev= 30
  4498.1  626.82  4518.1  626.33  4538.1  626.75  4578.1  625.27  4788.1  623.07
  4848.1  618.38  4898.1  617.65  4938.1  616.02  4958.1  616.30  4978.1  617.67
  4988.1  617.47  4992.6  614.80  4995.4  614.30  4998.6  614.80  5001.7  614.80
  5012.3  616.59  5026.4  617.44  5054.7  616.43  5068.9  617.75  5097.1  618.91
  5125.4  618.75  5153.7  617.45  5196.1  617.69  5238.6  618.58  5295.1  621.01
  5494.6  623.92  5535.5  624.54  5592.1  626.34  5606.3  625.64  5846.7  627.74
#Mann=4,-1,0
  4498.1    0.16       0  4992.6    0.07       0  4998.6    0.16       0
  5494.6    0.05       0
Bank Sta=4992.6,4998.6
Exp/Cntr=0.3,0.1

Type RM Length L Ch R = 1,36208,826,826,826
BEGIN DESCRIPTION:
GRAYS BRANCH 51.0
END DESCRIPTION:
XS GIS Cut Line= 4
      3387654.79     10636388.31      3386482.92     10635549.77
      3386086.85     10635205.34      3385691.25     10634346.65
#Sta/Elev= 30
  3324.4  638.07  3410.4  637.28  3769.1  629.69  3868.7  626.33  3890.8  627.19
  3947.3  625.97  4199.1  625.33  4455.6  621.30  4564.0  619.45  4675.1  619.32
  4851.8  615.95  4935.0  613.32  4963.4  614.07  4970.1  612.74  4977.7  613.92
  4984.3  612.57  5002.2  612.43  5004.9  611.93  5008.2  612.43  5019.4  614.39
  5104.9  617.07  5349.6  618.30  5696.1  624.27  5816.4  628.75  5867.8  629.32
  5890.8  632.31  5954.1  634.78  5977.0  633.68  6074.4  637.32  6235.7  640.93
#Mann=7,-1,0
  3324.4    0.05       0  4455.6    0.16       0  4675.1    0.05       0
  4851.8    0.16       0  5002.2    0.07       0  5008.2    0.16       0
  5349.6    0.05       0
Bank Sta=5002.2,5008.2
Exp/Cntr=0.3,0.1

Type RM Length L Ch R = 1,35382,837,837,837
BEGIN DESCRIPTION:
GRAYS BRANCH 49.0
END DESCRIPTION:
XS GIS Cut Line= 3
      3387732.93     10635935.20      3386993.33     10635232.06
      3386389.18     10634159.17
#Sta/Elev= 30
  3481.3  632.33  3717.7  628.24  3838.2  625.41  3859.2  623.89  3873.4  624.44
  4050.1  621.37  4213.1  620.43  4255.2  619.02  4340.2  618.55  4453.4  616.42
  4690.3  615.55  4766.2  614.28  4915.4  614.30  4937.6  610.98  4972.8  612.31
  4986.6  611.96  5005.3  609.70  5008.1  609.20  5011.3  609.70  5024.2  611.13
  5030.2  612.82  5089.2  616.01  5128.3  616.58  5272.8  620.47  5369.6  624.55
  5434.6  625.89  5509.8  630.47  5515.5  630.04  5590.7  633.71  5733.1  638.32
#Mann=5,-1,0
  3481.3    0.05       0  4690.3    0.16       0  5005.3    0.07       0
  5011.3    0.16       0  5128.3    0.05       0
Bank Sta=5005.3,5011.3
Exp/Cntr=0.3,0.1

Type RM Length L Ch R = 1,34545,807,807,807
BEGIN DESCRIPTION:
GRAYS BRANCH 46.0
END DESCRIPTION:
XS GIS Cut Line= 4
      3388519.40     10635560.22      3387594.33     10634657.44
      3386967.29     10634096.65      3386576.90     10633701.05
#Sta/Elev= 30
  3448.0  629.51  3463.0  629.20  3685.5  627.31  3815.9  625.06  4031.9  622.54
  4272.4  616.95  4668.5  614.46  4711.6  613.49  4767.7  612.44  4831.3  613.24
  4902.3  612.54  4909.0  612.10  4923.2  608.39  4930.7  607.52  4986.8  607.87
  4998.0  604.78  5000.7  604.28  5004.0  604.78  5015.2  607.83  5051.1  610.89
  5107.1  611.06  5164.0  613.85  5392.3  617.00  5482.5  619.12  5532.6  622.06
  5574.1  622.45  5801.1  630.59  5999.1  633.29  6034.5  635.81  6137.6  638.62
#Mann=8,-1,0
  3448.0    0.05       0  3463.0    0.16       0  3815.9    0.05       0
  4711.6    0.16       0  4998.0    0.07       0  5004.0    0.16       0
  5392.3    0.05       0  5574.1    0.16       0
Bank Sta=4998,5004
Exp/Cntr=0.3,0.1

Type RM Length L Ch R = 1,33738,1142,1142,1142
BEGIN DESCRIPTION:
GRAYS BRANCH 45.0
END DESCRIPTION:
XS GIS Cut Line= 3
      3388913.95     10634928.07      3387913.98     10633928.10
      3387515.55     10633629.28
#Sta/Elev= 30
  3669.7  622.80  3802.8  622.40  4085.7  618.86  4149.3  616.93  4191.7  617.70
  4568.4  612.95  4715.0  611.38  4750.3  608.71  4764.5  606.33  4806.9  604.21
  4849.3  605.66  4920.1  604.66  4976.6  605.98  4983.7  605.52  4994.8  602.65
  4997.6  602.15  5000.8  602.65  5026.1  606.28  5033.2  605.98  5081.7  610.08
  5183.1  613.99  5224.8  618.90  5239.4  619.53  5274.8  617.17  5322.9  617.86
  5454.0  621.22  5474.8  620.17  5547.7  624.44  5561.2  623.23  5581.9  624.10
#Mann=5,-1,0
  3669.7    0.05       0  4568.4    0.16       0  4994.8    0.07       0
  5000.8    0.16       0  5322.9    0.05       0
Bank Sta=4994.8,5000.8
Exp/Cntr=0.3,0.1

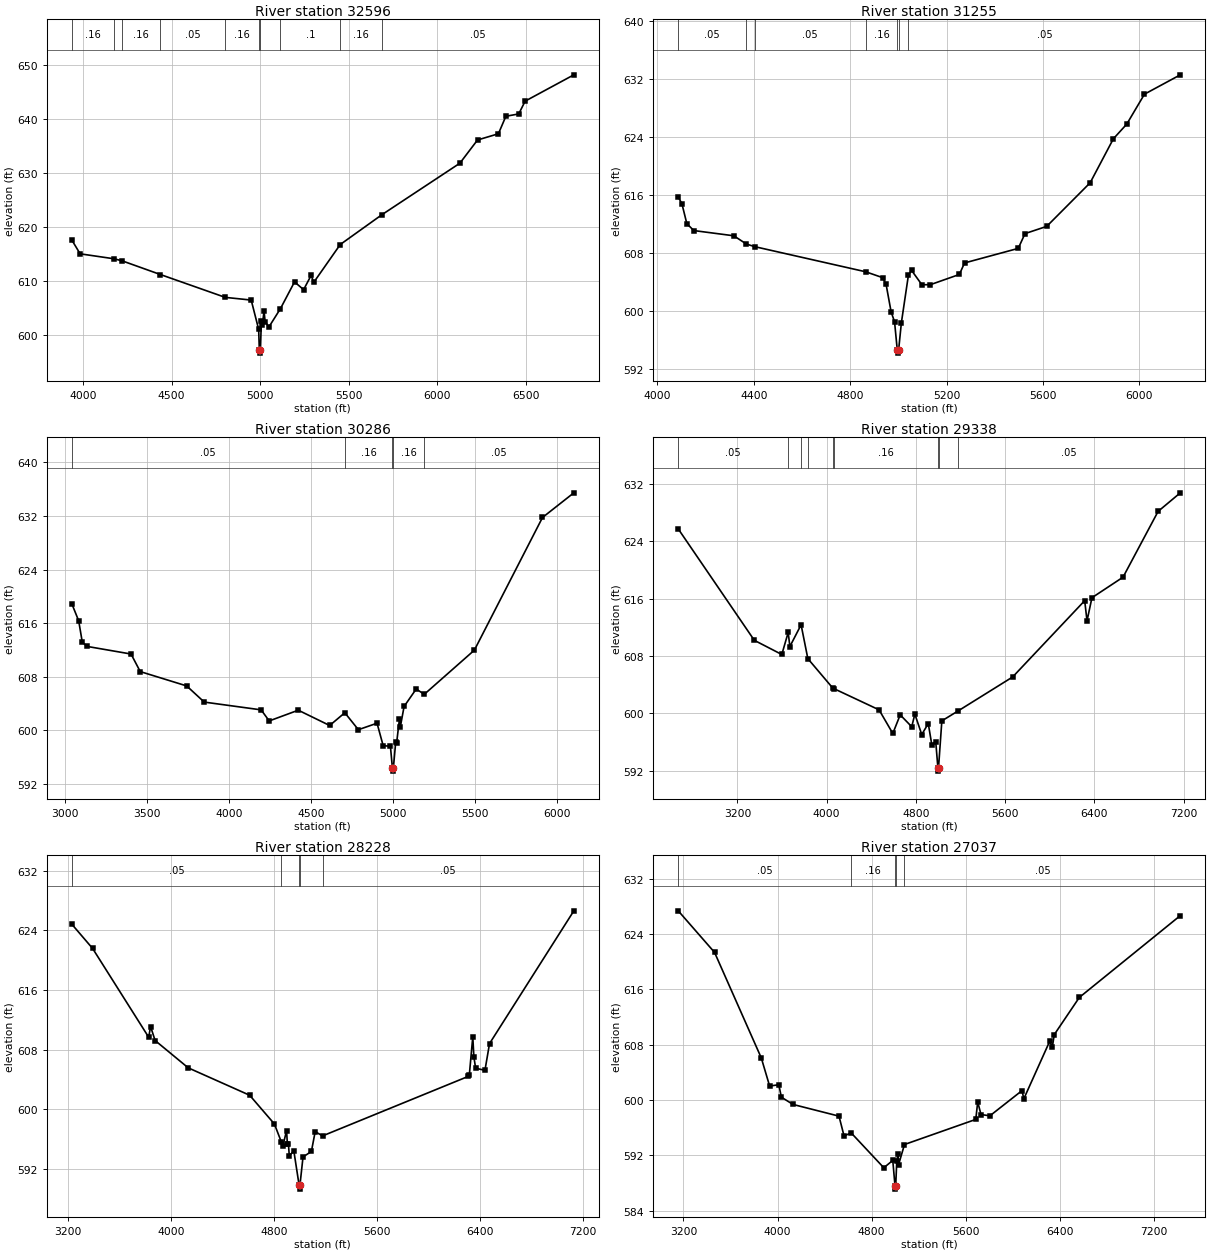
Type RM Length L Ch R = 1,32596,1341,1341,1341
BEGIN DESCRIPTION:
GRAYS BRANCH 43.0
END DESCRIPTION:
XS GIS Cut Line= 3
      3389092.31     10634206.05      3388758.96     10633664.35
      3386916.28     10632467.13
#Sta/Elev= 30
  3936.8  617.62  3984.0  615.05  4175.7  614.13  4222.0  613.74  4436.8  611.22
  4803.0  606.99  4949.4  606.49  4991.6  601.06  4995.4  597.17  4998.2  596.67
  5001.4  597.17  5006.8  602.60  5012.7  601.92  5021.9  604.50  5027.9  602.52
  5049.0  601.49  5114.6  604.91  5193.9  609.85  5245.3  608.42  5287.5  611.05
  5302.7  609.78  5451.9  616.77  5687.1  622.29  6127.1  631.82  6226.7  636.12
  6344.5  637.27  6386.7  640.51  6459.2  640.94  6495.5  643.31  6770.3  648.18
#Mann=10,-1,0
  3936.8    0.16       0  4175.7    0.05       0  4222.0    0.16       0
  4436.8    0.05       0  4803.0    0.16       0  4995.4    0.07       0
  5001.4    0.16       0  5114.6     0.1       0  5451.9    0.16       0
  5687.1    0.05       0
Bank Sta=4995.4,5001.4
Exp/Cntr=0.3,0.1

Type RM Length L Ch R = 1,31255,969,969,969
BEGIN DESCRIPTION:
GRAYS BRANCH 41.0
END DESCRIPTION:
XS GIS Cut Line= 4
      3389592.10     10633736.43      3389456.87     10633138.31
      3388915.21     10632643.52      3388592.30     10631982.08
#Sta/Elev= 30
  4086.7  615.76  4101.9  614.84  4122.4  612.08  4151.4  611.13  4317.2  610.41
  4369.4  609.27  4403.8  608.91  4864.4  605.44  4934.7  604.63  4948.9  603.72
  4969.9  599.90  4984.1  598.54  4995.2  594.71  4998.0  594.21  5001.2  594.71
  5012.4  598.40  5041.8  605.02  5055.0  605.62  5097.5  603.65  5132.7  603.66
  5252.9  605.07  5274.5  606.66  5497.2  608.67  5525.3  610.71  5615.4  611.71
  5795.6  617.73  5891.9  623.80  5947.5  625.83  6020.9  629.96  6169.6  632.63
#Mann=7,-1,0
  4086.7    0.05       0  4369.4    0.16       0  4403.8    0.05       0
  4864.4    0.16       0  4995.2    0.07       0  5001.2    0.16       0
  5041.8    0.05       0
Bank Sta=4995.2,5001.2
Exp/Cntr=0.3,0.1

Type RM Length L Ch R = 1,30286,948,948,948
BEGIN DESCRIPTION:
GRAYS BRANCH 38.0
END DESCRIPTION:
XS GIS Cut Line= 5
      3391042.08     10633641.61      3389941.25     10632419.56
      3389379.93     10632154.37      3388712.08     10631742.48
      3388722.46     10631742.48
#Sta/Elev= 30
  3041.5  618.92  3083.7  616.35  3105.4  613.20  3133.8  612.54  3402.8  611.40
  3458.9  608.78  3742.1  606.64  3849.0  604.23  4195.8  603.07  4245.1  601.42
  4422.3  603.02  4613.6  600.74  4706.0  602.64  4788.6  600.11  4902.4  601.08
  4939.7  597.73  4983.9  597.64  4996.0  594.43  4998.7  593.93  5002.0  594.43
  5016.2  598.27  5021.7  598.13  5039.0  601.69  5044.5  600.55  5067.3  603.58
  5141.1  606.18  5190.4  605.39  5495.8  611.98  5911.0  631.77  6102.1  635.45
#Mann=5,-1,0
  3041.5    0.05       0  4706.0    0.16       0  4996.0    0.07       0
  5002.0    0.16       0  5190.4    0.05       0
Bank Sta=4996,5002
Exp/Cntr=0.3,0.1

Type RM Length L Ch R = 1,29338,1110,1110,1110
BEGIN DESCRIPTION:
GRAYS BRANCH 37.0
END DESCRIPTION:
XS GIS Cut Line= 4
      3392160.02     10633450.83      3390482.92     10632336.23
      3390107.92     10631570.60      3388779.77     10630617.46
#Sta/Elev= 30
  2669.8  625.75  3351.8  610.19  3598.3  608.21  3655.5  611.29  3670.5  609.32
  3771.2  612.36  3831.7  607.63  4056.8  603.49  4062.8  603.46  4470.2  600.48
  4593.4  597.18  4659.6  599.78  4763.0  598.12  4791.0  599.88  4853.0  597.03
  4911.3  598.57  4943.0  595.60  4978.1  596.05  4997.4  592.42  5000.1  591.92
  5003.4  592.42  5033.0  598.94  5174.8  600.29  5667.7  605.07  6313.6  615.73
  6334.4  612.91  6378.6  616.14  6657.4  619.01  6971.8  628.20  7170.8  630.79
#Mann=9,-1,0
  2669.8    0.05       0  3655.5    0.16       0  3771.2    0.05       0
  3831.7    0.16       0  4056.8    0.05       0  4062.8    0.16       0
  4997.4    0.07       0  5003.4    0.16       0  5174.8    0.05       0
Bank Sta=4997.4,5003.4
Exp/Cntr=0.3,0.1

Type RM Length L Ch R = 1,28228,1191,1191,1191
BEGIN DESCRIPTION:
GRAYS BRANCH 34.0
END DESCRIPTION:
XS GIS Cut Line= 3
      3392352.69     10633169.54      3391473.45     10632033.43
      3389472.46     10630596.62
#Sta/Elev= 30
  3230.9  624.84  3393.0  621.57  3828.5  609.65  3843.0  611.09  3878.3  609.21
  4135.5  605.54  4612.7  601.86  4804.9  598.00  4858.5  595.60  4870.0  595.01
  4899.5  597.12  4905.6  595.31  4914.2  595.27  4920.3  593.75  4956.0  594.37
  4997.1  589.75  4999.9  589.25  5003.1  589.75  5027.2  593.57  5092.2  594.31
  5121.7  596.97  5179.2  596.40  6310.3  604.39  6318.8  604.55  6345.9  609.71
  6354.5  606.99  6368.1  605.49  6440.4  605.21  6476.0  608.80  7130.9  626.63
#Mann=5,-1,0
  3230.9    0.05       0  4858.5    0.16       0  4997.1    0.07       0
  5003.1    0.16       0  5179.2    0.05       0
Bank Sta=4997.1,5003.1
Exp/Cntr=0.3,0.1

Type RM Length L Ch R = 1,27037,1701,1701,1701
BEGIN DESCRIPTION:
GRAYS BRANCH 31.0
END DESCRIPTION:
XS GIS Cut Line= 6
      3393050.63     10632357.06      3391950.85     10631447.17
      3389561.04     10630159.15      3389566.25     10630143.52
      3389482.92     10630138.31      3389508.06     10630138.31
#Sta/Elev= 30
  3156.0  627.35  3464.7  621.34  3862.0  606.08  3932.8  602.02  4010.7  602.21
  4032.7  600.41  4131.6  599.36  4522.4  597.67  4565.4  594.80  4625.3  595.26
  4903.2  590.21  4979.4  591.27  4998.3  587.62  5001.1  587.12  5004.3  587.62
  5013.6  591.22  5023.2  592.15  5028.9  590.67  5079.0  593.57  5685.0  597.20
  5701.2  599.73  5729.3  597.90  5805.1  597.72  6078.4  601.37  6092.8  600.16
  6313.6  608.51  6335.5  607.63  6351.7  609.45  6565.0  614.83  7423.3  626.66
#Mann=5,-1,0
  3156.0    0.05       0  4625.3    0.16       0  4998.3    0.07       0
  5004.3    0.16       0  5079.0    0.05       0
Bank Sta=4998.3,5004.3
Exp/Cntr=0.3,0.1

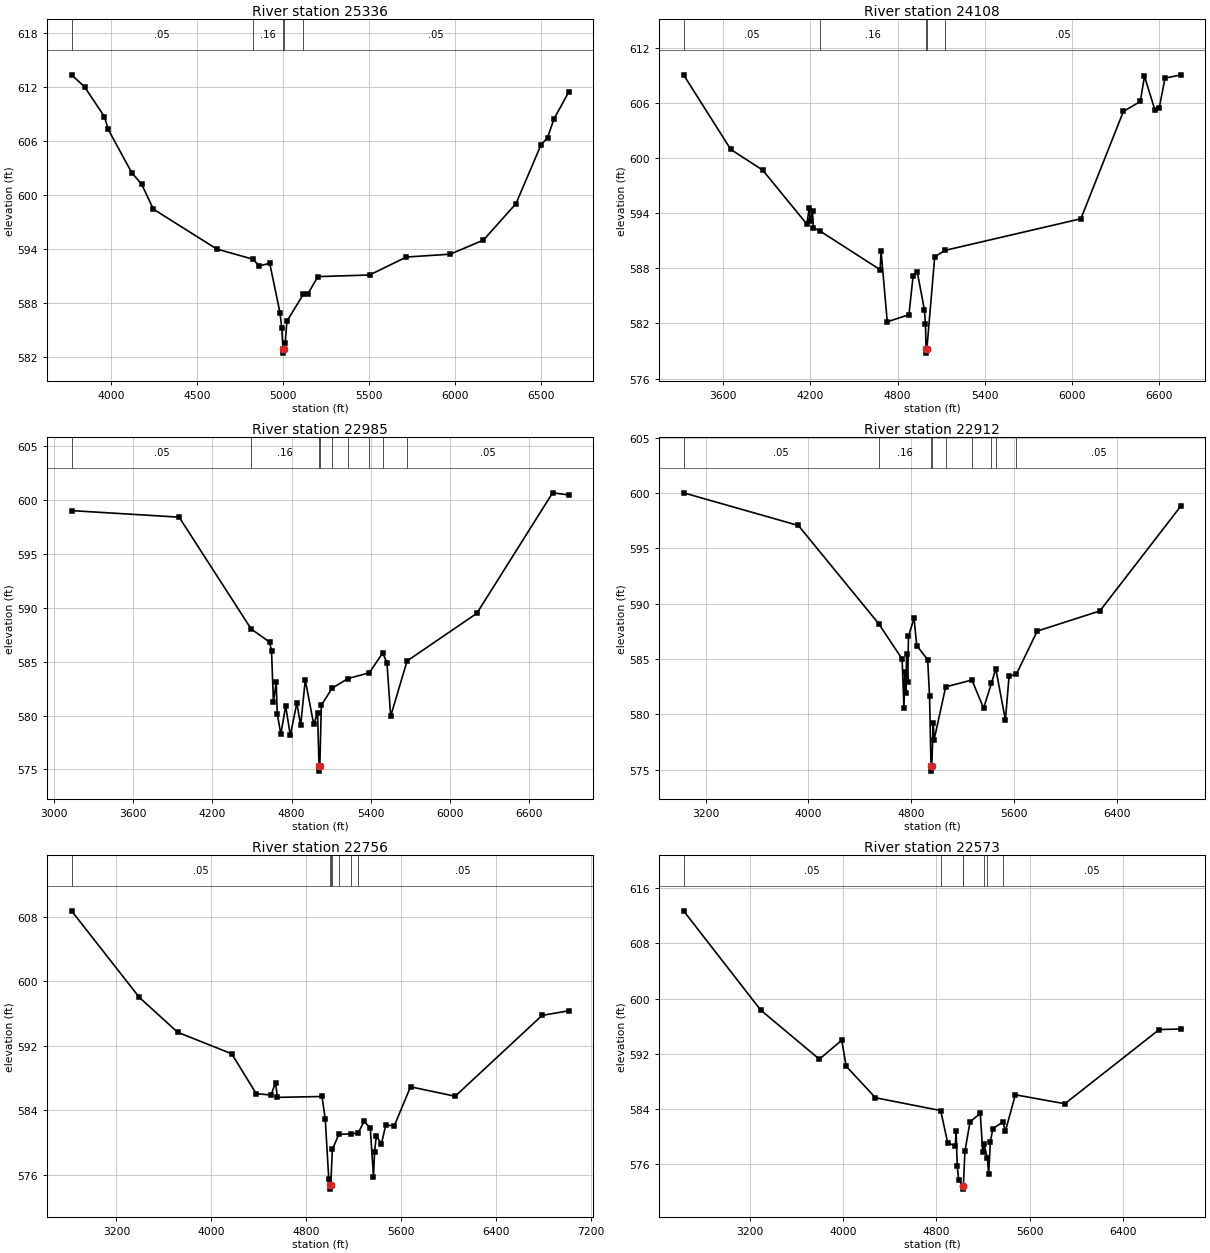
Type RM Length L Ch R = 1,25336,1228,1228,1228
BEGIN DESCRIPTION:
GRAYS BRANCH 29.0
END DESCRIPTION:
XS GIS Cut Line= 4
      3393488.15     10631018.53      3392592.13     10630466.66
      3392038.87     10630448.68      3390921.53     10629816.03
#Sta/Elev= 30
  3768.6  613.33  3844.4  612.00  3960.3  608.68  3981.6  607.28  4118.8  602.47
  4176.8  601.18  4244.3  598.43  4613.3  594.00  4822.0  592.88  4861.0  592.13
  4921.0  592.42  4981.0  586.92  4991.1  585.23  4998.1  582.95  5000.8  582.45
  5004.1  582.95  5011.1  583.62  5021.1  586.00  5117.0  588.99  5141.1  588.97
  5201.2  590.94  5501.7  591.12  5715.5  593.11  5970.6  593.43  6163.7  594.99
  6353.1  599.04  6498.8  605.57  6536.3  606.34  6573.9  608.44  6658.5  611.38
#Mann=5,-1,0
  3768.6    0.05       0  4822.0    0.16       0  4998.1    0.07       0
  5004.1    0.16       0  5117.0    0.05       0
Bank Sta=4998.1,5004.1
Exp/Cntr=0.3,0.1

Type RM Length L Ch R = 1,24108,1123,1123,1123
BEGIN DESCRIPTION:
GRAYS BRANCH 27.0
END DESCRIPTION:
XS GIS Cut Line= 6
      3393753.77     10630456.03      3392644.37     10629914.35
      3391936.04     10629289.35      3390941.25     10629107.06
      3390946.46     10629107.06      3390727.66     10629143.53
#Sta/Elev= 30
  3328.7  609.05  3653.3  600.93  3872.3  598.69  4176.3  592.81  4193.2  594.58
  4198.8  593.12  4215.7  594.19  4221.3  592.40  4267.3  592.05  4680.2  587.85
  4686.9  589.85  4729.5  582.18  4878.5  582.95  4906.9  587.13  4935.4  587.62
  4984.7  583.50  4992.3  581.98  4995.9  579.27  4998.7  578.77  5001.9  579.27
  5055.8  589.26  5127.1  589.95  6060.9  593.39  6352.9  605.06  6469.4  606.15
  6498.1  608.89  6569.5  605.24  6599.9  605.48  6639.5  608.69  6746.3  609.04
#Mann=5,-1,0
  3328.7    0.05       0  4267.3    0.16       0  4995.9    0.07       0
  5001.9    0.16       0  5127.1    0.05       0
Bank Sta=4995.9,5001.9
Exp/Cntr=0.3,0.1

Type RM Length L Ch R = 1,22985,73,73,73
BEGIN DESCRIPTION:
GRAYS BRANCH 26.0
END DESCRIPTION:
XS GIS Cut Line= 5
      3394264.18     10629992.49      3393040.62     10629081.59
      3392092.29     10628320.60      3391316.25     10627669.56
      3391331.88     10627669.56
#Sta/Elev= 30
  3131.3  599.03  3947.7  598.42  4493.9  588.04  4633.8  586.82  4648.4  586.00
  4662.9  581.26  4683.7  583.11  4691.7  580.18  4718.9  578.27  4755.7  580.88
  4790.9  578.16  4840.5  581.17  4869.3  579.09  4904.5  583.31  4968.6  579.17
  4997.4  580.27  5008.8  575.34  5011.5  574.84  5014.8  575.34  5026.2  580.96
  5107.6  582.53  5227.0  583.43  5389.6  583.97  5491.7  585.80  5523.8  584.92
  5552.3  579.94  5676.7  585.07  6205.6  589.49  6780.6  600.68  6901.2  600.49
#Mann=9,-1,0
  3131.3    0.05       0  4493.9    0.16       0  5008.8    0.07       0
  5014.8    0.16       0  5107.6    0.05       0  5227.0    0.16       0
  5389.6    0.05       0  5491.7    0.16       0  5676.7    0.05       0
Bank Sta=5008.8,5014.8
Exp/Cntr=0.3,0.1

Type RM Length L Ch R = 1,22912,156,156,156
BEGIN DESCRIPTION:
GRAYS BRANCH 25.0
END DESCRIPTION:
XS GIS Cut Line= 4
      3394456.85     10629898.71      3393144.37     10629065.40
      3392540.21     10628596.65      3391416.13     10627529.81
#Sta/Elev= 30
  3028.1  600.02  3921.8  597.07  4546.5  588.21  4729.4  585.01  4743.9  580.56
  4750.2  583.83  4758.4  581.93  4764.7  585.47  4772.8  582.93  4779.2  587.08
  4822.6  588.69  4843.4  586.22  4928.5  584.95  4943.0  581.67  4954.5  575.38
  4957.2  574.88  4960.5  575.38  4972.0  579.22  4978.3  577.70  5068.7  582.49
  5272.9  583.11  5363.8  580.57  5424.7  582.80  5458.6  584.14  5533.6  579.49
  5562.0  583.43  5619.9  583.66  5781.2  587.53  6269.0  589.35  6897.2  598.79
#Mann=9,-1,0
  3028.1    0.05       0  4546.5    0.16       0  4954.5    0.07       0
  4960.5    0.16       0  5068.7    0.05       0  5272.9    0.16       0
  5424.7    0.05       0  5458.6    0.16       0  5619.9    0.05       0
Bank Sta=4954.5,4960.5
Exp/Cntr=0.3,0.1

Type RM Length L Ch R = 1,22756,183,183,183
BEGIN DESCRIPTION:
GRAYS BRANCH 24.0
END DESCRIPTION:
XS GIS Cut Line= 4
      3394773.48     10629715.26      3392780.45     10628621.52
      3392266.56     10627815.96      3391481.84     10627260.41
#Sta/Elev= 30
  2821.4  608.74  3393.3  598.01  3715.4  593.70  4172.1  591.02  4378.7  586.08
  4503.8  585.91  4541.7  587.46  4556.8  585.62  4933.1  585.73  4960.6  582.97
  4990.3  575.51  5001.2  574.75  5004.0  574.25  5007.2  574.75  5020.6  579.17
  5075.4  581.03  5173.9  581.10  5237.4  581.19  5288.7  582.65  5340.3  581.82
  5367.5  575.75  5376.7  578.90  5391.2  580.84  5434.2  579.85  5470.6  582.17
  5543.4  582.12  5679.6  586.93  6056.1  585.76  6789.1  595.78  7011.8  596.35
#Mann=7,-1,0
  2821.4    0.05       0  5001.2    0.04       0  5007.2    0.05       0
  5020.6    0.16       0  5075.4    0.05       0  5173.9    0.16       0
  5237.4    0.05       0
Bank Sta=5001.2,5007.2
Exp/Cntr=0.3,0.1

Type RM Length L Ch R = 1,22573,414,414,414
BEGIN DESCRIPTION:
GRAYS BRANCH 23.0
END DESCRIPTION:
XS GIS Cut Line= 4
      3394974.86     10629606.48      3392724.89     10628403.38
      3392287.39     10627783.58      3391506.65     10627231.86
#Sta/Elev= 30
  2630.5  612.74  3292.3  598.33  3796.3  591.19  3988.1  593.95  4026.3  590.17
  4277.9  585.59  4837.8  583.73  4897.6  579.05  4963.5  578.58  4969.6  580.71
  4979.7  575.64  4992.3  573.64  5026.3  572.82  5029.0  572.32  5032.3  572.82
  5045.6  577.83  5089.4  582.09  5177.2  583.32  5198.9  577.69  5210.1  578.87
  5238.9  576.77  5249.4  574.45  5264.2  579.23  5285.1  581.09  5372.4  582.09
  5392.2  580.69  5478.4  586.02  5903.3  584.72  6713.7  595.50  6896.6  595.57
#Mann=7,-1,0
  2630.5    0.05       0  4837.8    0.16       0  5026.3    0.07       0
  5032.3    0.16       0  5210.1    0.05       0  5238.9    0.16       0
  5372.4    0.05       0
Bank Sta=5026.3,5032.3
Exp/Cntr=0.3,0.1

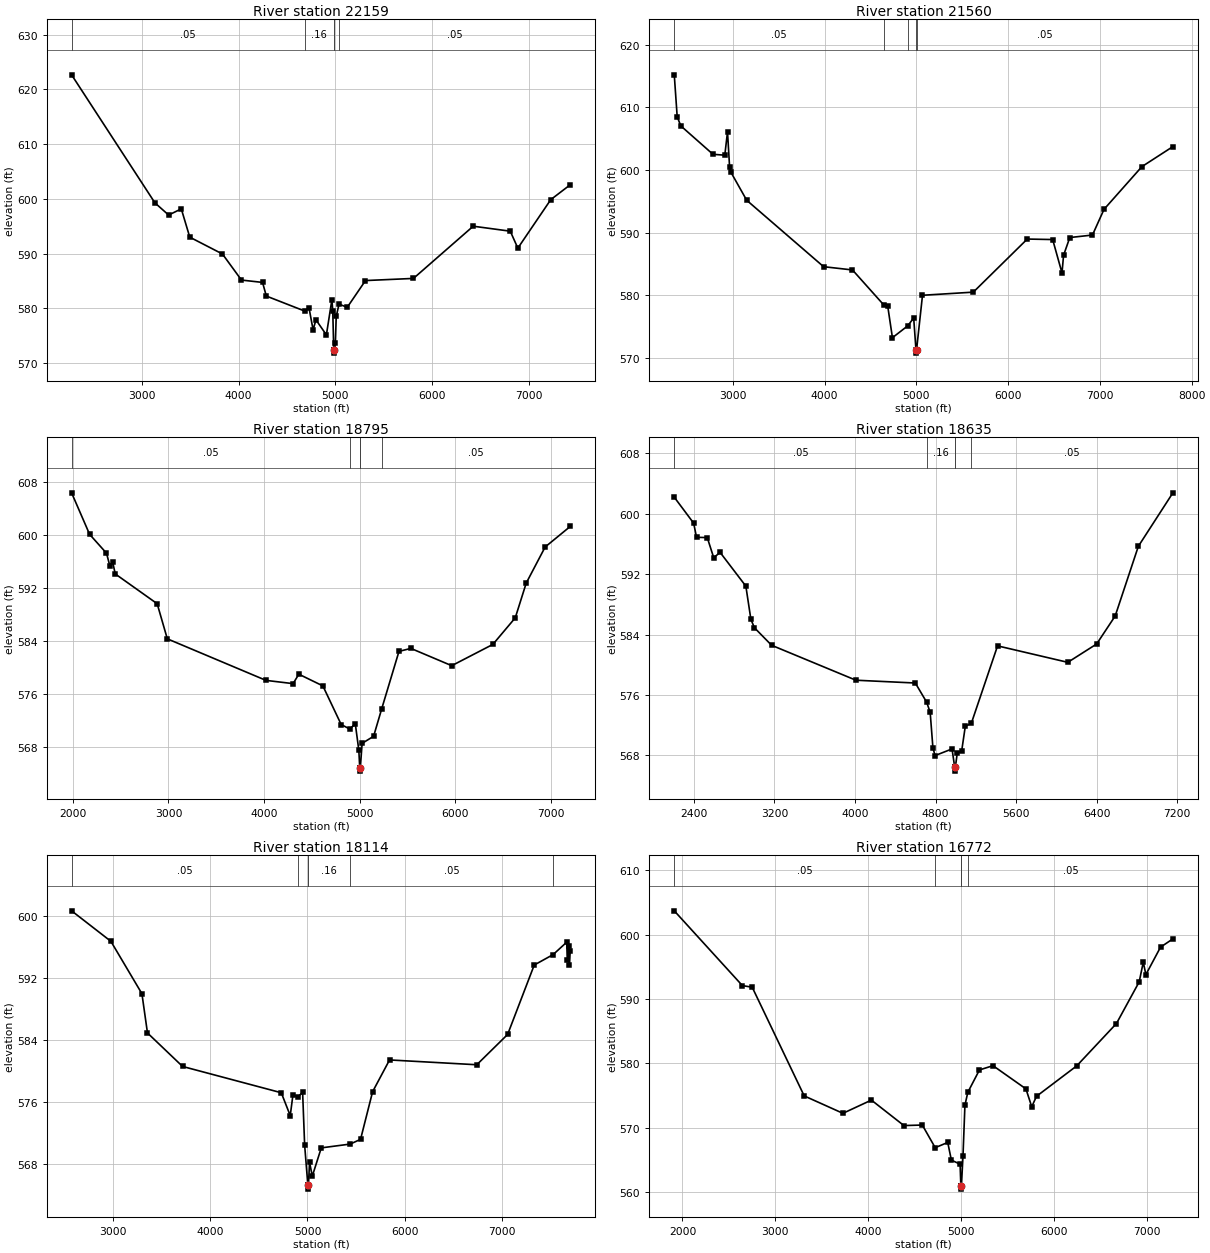
Type RM Length L Ch R = 1,22159,599,599,599
BEGIN DESCRIPTION:
GRAYS BRANCH 22.0
END DESCRIPTION:
XS GIS Cut Line= 5
      3395321.46     10629304.98      3393430.83     10628476.85
      3391347.50     10627065.40      3390779.79     10627039.35
      3390788.70     10627039.35
#Sta/Elev= 30
  2272.7  622.67  3134.5  599.28  3276.4  597.05  3407.4  598.18  3495.0  593.01
  3833.2  589.93  4029.7  585.17  4248.0  584.74  4286.8  582.25  4683.2  579.51
  4728.6  580.08  4770.5  576.10  4800.5  577.90  4908.3  575.15  4965.2  581.59
  4974.1  579.54  4984.5  572.32  4987.2  571.82  4990.5  572.32  5001.2  573.70
  5010.1  578.55  5039.3  580.77  5124.0  580.19  5312.6  585.08  5808.8  585.47
  6427.0  595.01  6810.3  594.10  6888.6  591.00  7229.0  599.86  7430.4  602.58
#Mann=5,-1,0
  2272.7    0.05       0  4683.2    0.16       0  4984.5    0.07       0
  4990.5    0.16       0  5039.3    0.05       0
Bank Sta=4984.5,4990.5
Exp/Cntr=0.3,0.1

Type RM Length L Ch R = 1,21560,2765,2765,2765
BEGIN DESCRIPTION:
GRAYS BRANCH 21.0
END DESCRIPTION:
XS GIS Cut Line= 2
      3395618.30     10628789.34      3390722.45     10626429.96
#Sta/Elev= 30
  2360.7  615.18  2392.6  608.49  2432.3  607.03  2782.7  602.50  2911.5  602.36
  2941.0  606.09  2963.6  600.49  2978.1  599.64  3150.1  595.17  3988.3  584.57
  4303.2  584.05  4648.3  578.40  4687.6  578.25  4738.5  573.24  4905.1  575.13
  4970.2  576.39  4995.4  571.28  4998.2  570.78  5001.4  571.28  5066.3  580.01
  5620.2  580.51  6208.3  588.98  6485.2  588.90  6586.8  583.57  6603.9  586.39
  6671.7  589.22  6918.8  589.62  7044.7  593.72  7457.4  600.53  7795.4  603.73
#Mann=5,-1,0
  2360.7    0.05       0  4648.3    0.16       0  4905.1    0.05       0
  4995.4   0.035       0  5001.4    0.05       0
Bank Sta=4995.4,5001.4
Exp/Cntr=0.3,0.1

Type RM Length L Ch R = 1,18795,160,160,160
BEGIN DESCRIPTION:
GRAYS BRANCH 20.0
END DESCRIPTION:
XS GIS Cut Line= 5
      3395425.65     10627914.39      3393821.46     10626278.94
      3392717.29     10625685.19      3391123.54     10625226.85
      3391138.13     10625226.85
#Sta/Elev= 30
  1986.6  606.30  2174.9  600.06  2351.7  597.22  2387.0  595.31  2415.3  595.93
  2443.6  594.10  2882.1  589.62  2988.1  584.34  4020.6  578.09  4304.3  577.60
  4364.3  579.02  4615.9  577.26  4807.5  571.45  4897.3  570.77  4955.2  571.56
  4992.1  567.58  5001.7  564.94  5004.4  564.44  5007.7  564.94  5026.6  568.62
  5146.7  569.68  5229.8  573.73  5412.2  582.45  5536.6  582.90  5964.2  580.30
  6394.6  583.50  6629.1  587.50  6743.6  592.72  6941.7  598.15  7204.1  601.24
#Mann=5,-1,0
  1986.6    0.05       0  4897.3    0.16       0  5001.7    0.07       0
  5007.7    0.16       0  5229.8    0.05       0
Bank Sta=5001.7,5007.7
Exp/Cntr=0.3,0.1

Type RM Length L Ch R = 1,18635,521,521,521
BEGIN DESCRIPTION:
GRAYS BRANCH 19.0
END DESCRIPTION:
XS GIS Cut Line= 4
      3395436.02     10627539.33      3393649.66     10626036.06
      3393071.46     10625685.19      3391227.68     10625081.01
#Sta/Elev= 30
  2205.7  602.20  2398.3  598.76  2426.9  596.89  2533.5  596.85  2597.3  594.19
  2661.0  594.89  2916.6  590.42  2966.6  586.02  3001.7  584.91  3172.1  582.59
  4009.7  577.96  4599.5  577.59  4711.6  575.06  4746.8  573.71  4774.0  569.02
  4795.3  567.98  4963.9  568.86  4990.7  566.42  4993.5  565.92  4996.7  566.42
  5016.2  568.34  5058.9  568.52  5095.7  571.86  5155.5  572.25  5416.0  582.51
  6113.5  580.33  6400.1  582.76  6584.1  586.47  6814.1  595.70  7157.0  602.78
#Mann=5,-1,0
  2205.7    0.05       0  4711.6    0.16       0  4990.7    0.07       0
  4996.7    0.16       0  5155.5    0.05       0
Bank Sta=4990.7,4996.7
Exp/Cntr=0.3,0.1

Type RM Length L Ch R = 1,18114,1342,1342,1342
BEGIN DESCRIPTION:
GRAYS BRANCH 18.0
END DESCRIPTION:
XS GIS Cut Line= 5
      3395493.32     10627429.97      3393758.96     10625929.98
      3393212.08     10625456.02      3391291.13     10624605.55
      3391297.83     10624609.74
#Sta/Elev= 30
  2575.7  600.68  2979.4  596.75  3298.6  589.99  3355.6  584.93  3716.5  580.61
  4731.0  577.22  4823.1  574.27  4851.3  576.98  4901.5  576.69  4950.4  577.27
  4971.2  570.47  5004.4  565.29  5007.1  564.79  5010.4  565.29  5021.6  568.27
  5049.8  566.46  5142.2  570.11  5439.2  570.60  5545.9  571.21  5669.7  577.35
  5843.9  581.45  6740.7  580.83  7057.8  584.74  7331.2  593.69  7525.7  595.04
  7665.3  596.64  7670.8  594.37  7688.6  596.19  7691.9  593.67  7701.1  595.46
#Mann=6,-1,0
  2575.7    0.05       0  4901.5    0.16       0  5004.4    0.07       0
  5010.4    0.16       0  5439.2    0.05       0  7525.7    0.16       0
Bank Sta=5004.4,5010.4
Exp/Cntr=0.3,0.1

Type RM Length L Ch R = 1,16772,988,988,988
BEGIN DESCRIPTION:
GRAYS BRANCH 17.0
END DESCRIPTION:
XS GIS Cut Line= 2
      3396264.16     10625711.23      3391114.23     10624206.34
#Sta/Elev= 30
  1912.0  603.68  2645.0  592.08  2750.6  591.83  3310.2  574.97  3726.9  572.27
  4033.1  574.32  4383.2  570.37  4581.2  570.45  4719.6  566.94  4854.6  567.75
  4893.8  565.01  4987.5  564.38  4995.8  561.01  4998.6  560.51  5001.8  561.01
  5018.8  565.67  5039.6  573.52  5070.7  575.53  5195.9  579.00  5341.7  579.66
  5696.0  576.06  5758.5  573.29  5809.9  574.91  6242.6  579.63  6670.1  586.20
  6914.7  592.66  6958.6  595.71  6986.8  593.79  7144.1  598.04  7277.3  599.33
#Mann=5,-1,0
  1912.0    0.05       0  4719.6    0.16       0  4995.8    0.07       0
  5001.8    0.16       0  5070.7    0.05       0
Bank Sta=4995.8,5001.8
Exp/Cntr=0.3,0.1

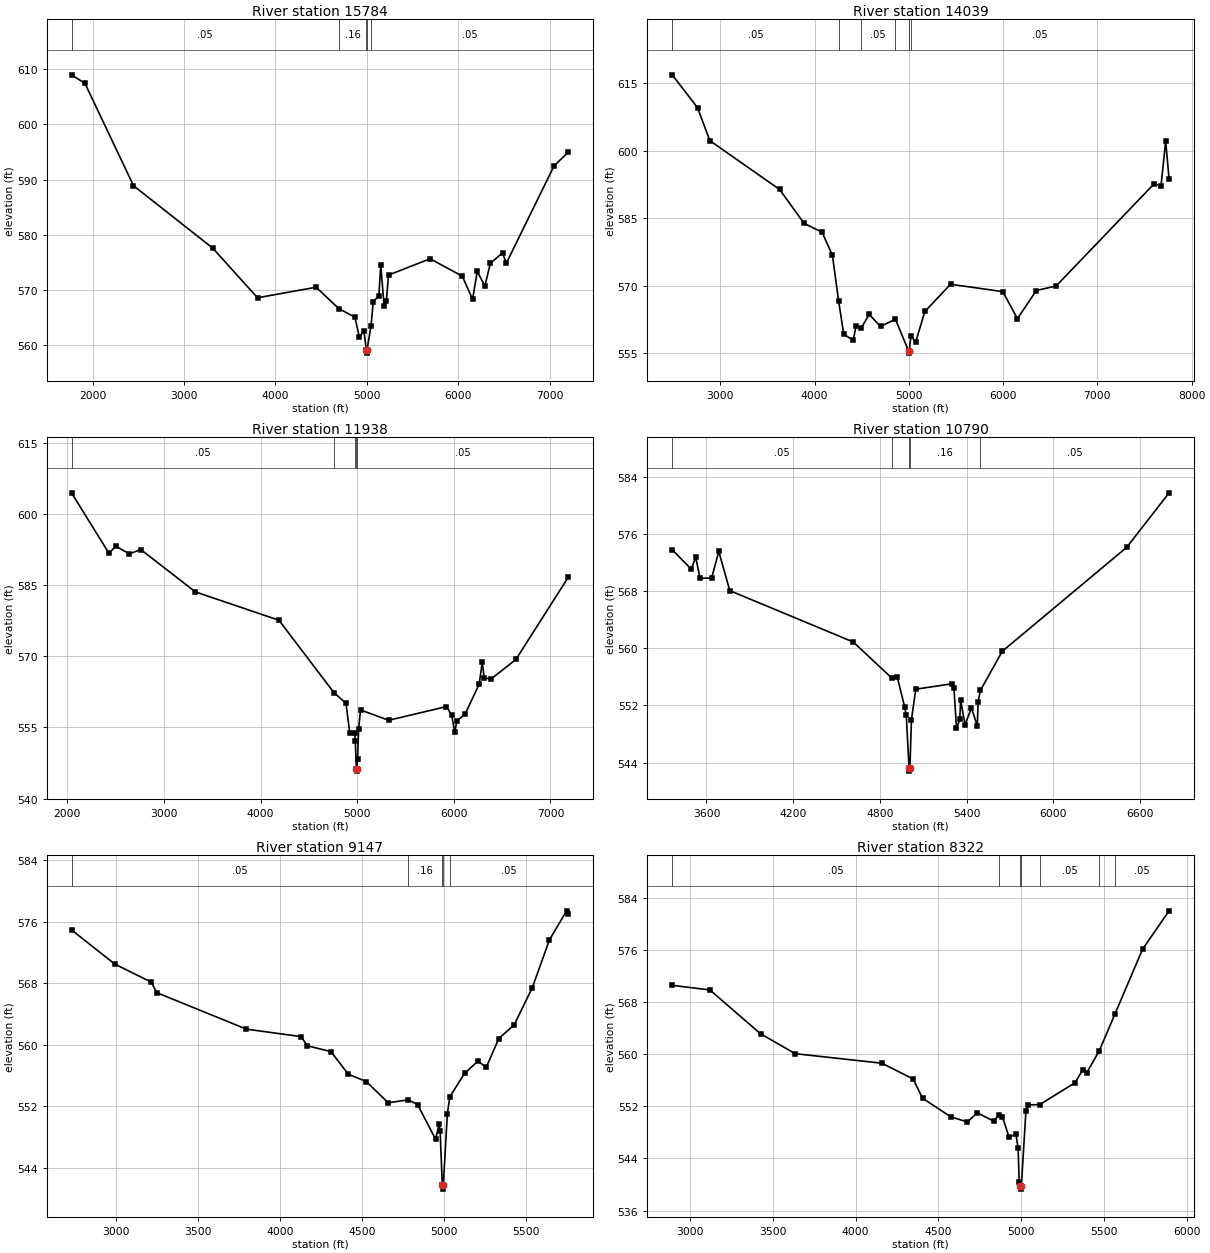
Type RM Length L Ch R = 1,15784,1745,1745,1745
BEGIN DESCRIPTION:
GRAYS BRANCH 15.0
END DESCRIPTION:
XS GIS Cut Line= 3
      3396706.86     10625377.89      3394206.87     10624440.40
      3391509.86     10623836.43
#Sta/Elev= 30
  1769.6  608.99  1917.2  607.43  2447.5  588.92  3314.5  577.61  3803.9  568.63
  4444.6  570.54  4693.7  566.66  4869.2  565.12  4917.7  561.46  4967.1  562.69
  4994.8  559.11  4997.6  558.61  5000.8  559.11  5045.2  563.57  5069.6  567.89
  5131.1  569.01  5151.6  574.58  5188.2  567.13  5213.0  568.12  5236.7  572.74
  5690.9  575.69  6043.1  572.55  6155.8  568.36  6207.1  573.40  6290.7  570.77
  6350.5  574.89  6483.8  576.75  6524.8  574.88  7047.4  592.52  7203.4  594.99
#Mann=5,-1,0
  1769.6    0.05       0  4693.7    0.16       0  4994.8    0.07       0
  5000.8    0.16       0  5045.2    0.05       0
Bank Sta=4994.8,5000.8
Exp/Cntr=0.3,0.1

Type RM Length L Ch R = 1,14039,2101,2101,2101
BEGIN DESCRIPTION:
GRAYS BRANCH 13.0
END DESCRIPTION:
XS GIS Cut Line= 3
      3396550.66     10623497.69      3394274.58     10623440.40
      3391286.03     10623601.80
#Sta/Elev= 30
  2490.9  616.93  2759.5  609.60  2889.6  602.28  3629.8  591.41  3889.9  583.85
  4080.0  581.90  4190.0  576.74  4255.2  566.62  4310.0  559.16  4410.1  557.88
  4440.1  560.91  4494.8  560.53  4580.1  563.60  4700.2  560.91  4857.6  562.53
  4997.5  555.48  5000.3  554.98  5003.5  555.48  5023.5  558.83  5072.3  557.42
  5170.8  564.26  5443.0  570.31  5996.5  568.67  6152.2  562.65  6352.5  568.92
  6562.8  569.93  7604.3  592.73  7674.4  592.12  7724.5  602.12  7760.6  593.67
#Mann=7,-1,0
  2490.9    0.05       0  4255.2    0.16       0  4494.8    0.05       0
  4857.6    0.16       0  4997.5    0.07       0  5003.5    0.16       0
  5023.5    0.05       0
Bank Sta=4997.5,5003.5
Exp/Cntr=0.3,0.1

Type RM Length L Ch R = 1,11938,1148,1148,1148
BEGIN DESCRIPTION:
GRAYS BRANCH 12.0
END DESCRIPTION:
XS GIS Cut Line= 4
      3397097.54     10622429.98      3394660.00     10622179.98
      3393800.62     10622096.65      3392066.66     10622674.63
#Sta/Elev= 30
  2043.8  604.49  2431.3  591.73  2501.6  593.25  2642.4  591.60  2760.3  592.53
  3325.9  583.59  4190.4  577.61  4758.6  562.36  4883.8  560.09  4924.0  553.73
  4974.3  553.75  4980.3  552.23  4991.4  546.28  4994.1  545.78  4997.4  546.28
  5004.4  548.42  5014.5  554.63  5034.5  558.69  5325.9  556.51  5923.3  559.39
  5977.9  557.63  6009.5  553.93  6030.6  556.31  6118.3  557.89  6262.5  564.12
  6294.1  568.75  6315.2  565.37  6389.0  565.27  6642.0  569.33  7185.3  586.71
#Mann=5,-1,0
  2043.8    0.05       0  4758.6    0.16       0  4980.3    0.05       0
  4991.4   0.035       0  4997.4    0.05       0
Bank Sta=4991.4,4997.4
Exp/Cntr=0.3,0.1

Type RM Length L Ch R = 1,10790,1643,1643,1643
BEGIN DESCRIPTION:
GRAYS BRANCH 10.0
END DESCRIPTION:
XS GIS Cut Line= 3
      3395264.15     10621523.73      3393837.08     10621534.15
      3392005.39     10622361.53
#Sta/Elev= 30
  3363.3  573.76  3495.3  571.05  3525.4  572.74  3555.4  569.79  3635.4  569.80
  3685.4  573.53  3761.4  568.05  4615.4  560.87  4882.9  555.81  4920.0  555.96
  4971.7  551.74  4982.4  550.60  5001.4  543.31  5004.1  542.81  5007.4  543.31
  5018.0  550.02  5048.2  554.27  5300.6  555.03  5311.8  554.50  5329.5  548.86
  5352.6  550.04  5358.1  552.78  5388.4  549.28  5432.9  551.65  5473.7  549.12
  5479.2  552.48  5494.6  554.09  5646.5  559.57  6507.6  574.12  6800.3  581.73
#Mann=5,-1,0
  3363.3    0.05       0  4882.9    0.16       0  5001.4    0.07       0
  5007.4    0.16       0  5494.6    0.05       0
Bank Sta=5001.4,5007.4
Exp/Cntr=0.3,0.1

Type RM Length L Ch R = 1,9147,825,825,825
BEGIN DESCRIPTION:
GRAYS BRANCH 8.0
END DESCRIPTION:
XS GIS Cut Line= 3
      3395305.84     10621393.52      3393430.83     10620841.44
      3392477.71     10620341.44
#Sta/Elev= 30
  2729.7  574.97  2994.2  570.51  3216.3  568.17  3249.7  566.80  3796.9  562.05
  4130.0  561.08  4168.6  559.88  4312.4  559.13  4417.6  556.19  4528.0  555.23
  4661.4  552.47  4784.2  552.85  4840.3  552.24  4950.6  547.73  4972.6  549.74
  4978.3  548.79  4991.7  541.73  4994.4  541.23  4997.7  541.73  5022.4  551.05
  5037.7  553.25  5127.0  556.30  5209.6  557.89  5259.4  557.07  5336.3  560.83
  5430.2  562.62  5541.1  567.47  5645.1  573.67  5749.7  577.45  5760.6  577.01
#Mann=5,-1,0
  2729.7    0.05       0  4784.2    0.16       0  4991.7    0.07       0
  4997.7    0.16       0  5037.7    0.05       0
Bank Sta=4991.7,4997.7
Exp/Cntr=0.3,0.1

Type RM Length L Ch R = 1,8322,985,985,985
BEGIN DESCRIPTION:
GRAYS BRANCH 5.0
END DESCRIPTION:
XS GIS Cut Line= 3
      3395352.67     10620627.89      3393727.71     10620216.44
      3392416.11     10620023.86
#Sta/Elev= 30
  2891.9  570.59  3119.4  569.88  3425.2  563.15  3635.3  560.09  4158.0  558.63
  4347.0  556.22  4404.0  553.25  4573.8  550.41  4674.9  549.60  4735.5  551.02
  4836.6  549.69  4864.0  550.73  4887.1  550.37  4927.6  547.23  4968.0  547.75
  4981.5  545.64  4988.2  540.40  4995.3  539.79  4998.1  539.29  5001.3  539.79
  5028.6  551.22  5038.7  552.23  5112.4  552.27  5325.4  555.63  5372.3  557.61
  5395.2  557.11  5471.7  560.53  5565.5  566.11  5734.0  576.16  5893.8  582.03
#Mann=7,-1,0
  2891.9    0.05       0  4864.0    0.16       0  4995.3    0.07       0
  5001.3    0.16       0  5112.4    0.05       0  5471.7    0.16       0
  5565.5    0.05       0
Bank Sta=4995.3,5001.3
Exp/Cntr=0.3,0.1