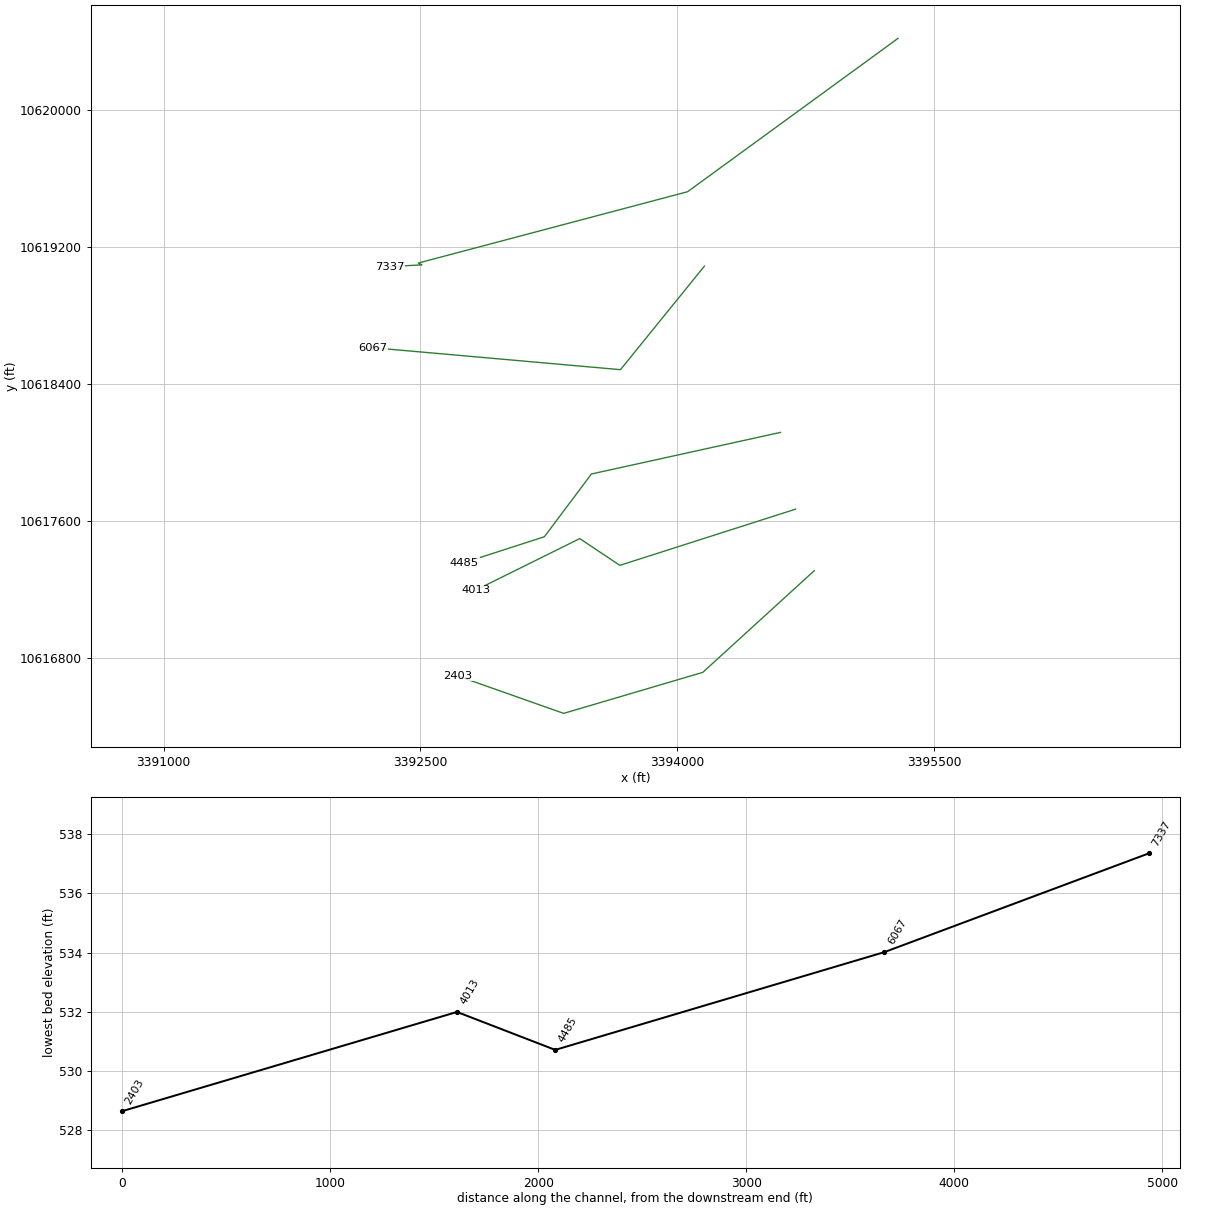
HEC-RAS study GRAYS BRANCH.prj: GRAYS BRANCH Base Level Engineering

--- GRAYS BRANCH.g01 (geometry) --- (continued)

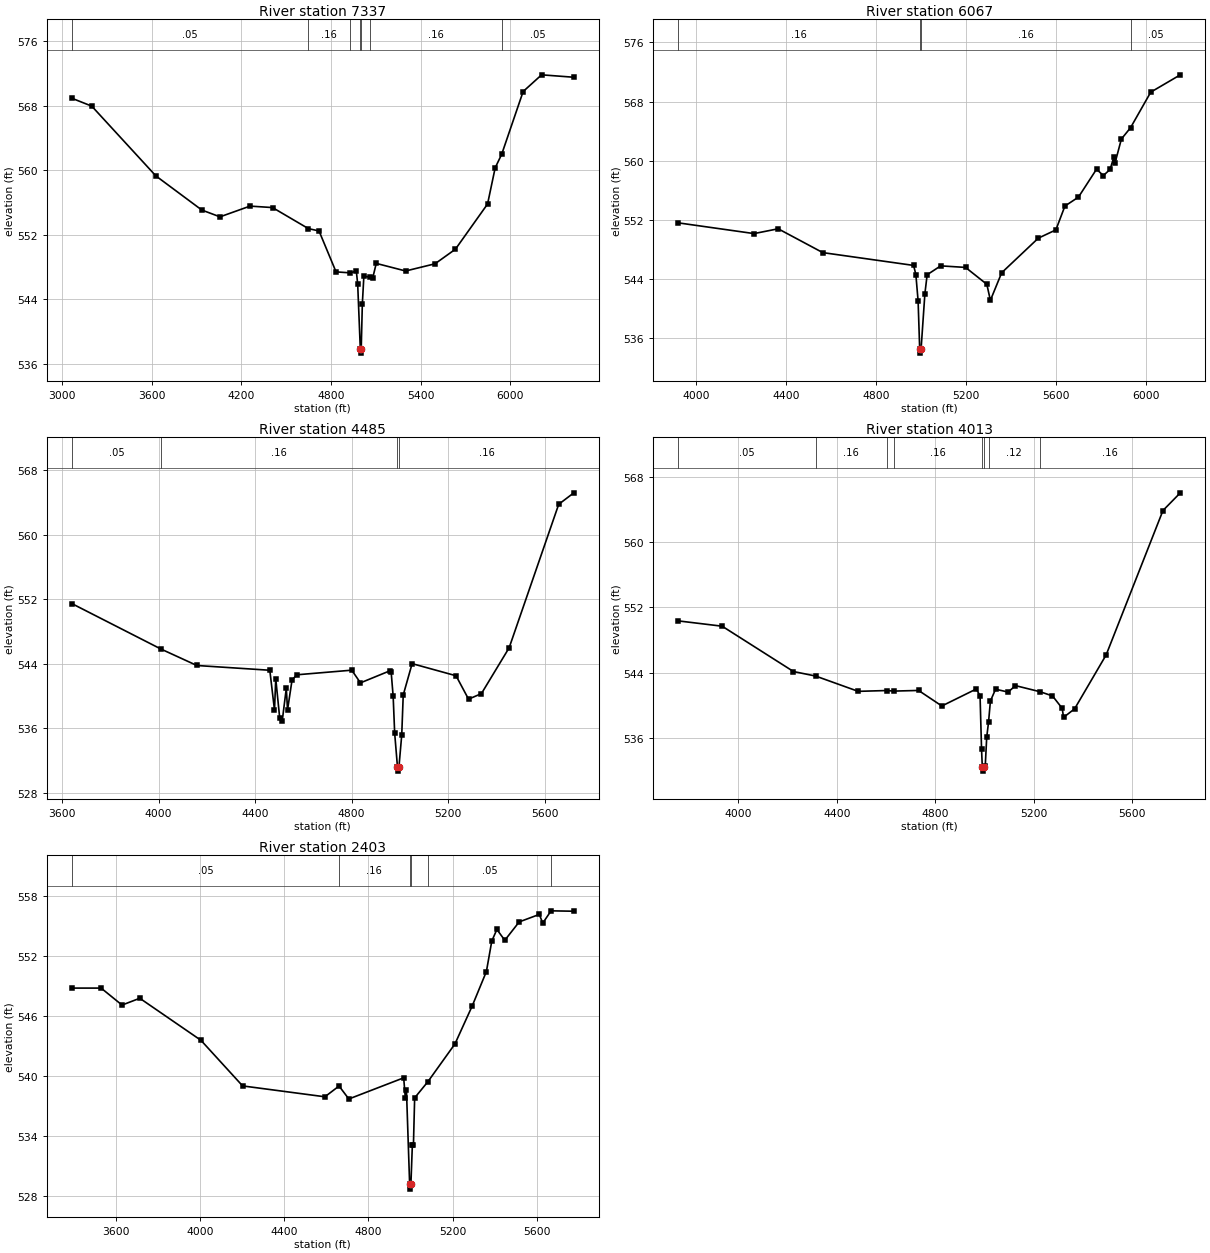
Type RM Length L Ch R = 1,7337,1270,1270,1270
BEGIN DESCRIPTION:
GRAYS BRANCH 4.0
END DESCRIPTION:
XS GIS Cut Line= 6
      3395290.18     10620419.54      3394061.04     10619523.73
      3392488.12     10619107.06      3392498.54     10619101.85
      3392508.96     10619096.65      3392321.45     10619086.23
#Sta/Elev= 30
  3066.2  568.94  3199.9  567.96  3629.1  559.31  3936.6  555.08  4057.9  554.24
  4258.8  555.57  4409.4  555.39  4649.4  552.78  4720.5  552.49  4834.3  547.42
  4927.5  547.30  4970.1  547.50  4979.1  545.93  4996.8  537.85  4999.6  537.35
  5002.8  537.85  5010.3  543.45  5020.5  546.89  5059.1  546.76  5080.4  546.71
  5103.3  548.47  5299.8  547.53  5496.4  548.42  5633.1  550.23  5848.1  555.83
  5899.1  560.32  5942.8  562.00  6086.1  569.77  6209.7  571.84  6425.4  571.54
#Mann=7,-1,0
  3066.2    0.05       0  4649.4    0.16       0  4927.5    0.12       0
  4996.8    0.07       0  5002.8    0.12       0  5059.1    0.16       0
  5942.8    0.05       0
Bank Sta=4996.8,5002.8
Exp/Cntr=0.3,0.1

Type RM Length L Ch R = 1,6067,1582,1582,1582
BEGIN DESCRIPTION:
GRAYS BRANCH 3.0
END DESCRIPTION:
XS GIS Cut Line= 3
      3394158.97     10619089.08      3393668.78     10618484.35
      3392221.20     10618612.62
#Sta/Elev= 30
  3920.8  551.62  4257.9  550.17  4365.0  550.82  4563.3  547.60  4967.0  545.87
  4977.0  544.64  4987.0  541.07  4994.1  534.52  4996.8  534.02  5000.1  534.52
  5017.2  542.06  5027.2  544.61  5087.4  545.81  5197.9  545.60  5292.5  543.32
  5308.3  541.15  5358.5  544.88  5521.2  549.55  5599.4  550.67  5639.6  553.89
  5699.8  555.10  5780.1  558.87  5810.3  558.01  5840.4  558.84  5856.8  560.49
  5861.8  559.65  5890.6  562.95  5931.2  564.47  6021.1  569.28  6152.5  571.62
#Mann=4,-1,0
  3920.8    0.16       0  4994.1    0.07       0  5000.1    0.16       0
  5931.2    0.05       0
Bank Sta=4994.1,5000.1
Exp/Cntr=0.3,0.1

Type RM Length L Ch R = 1,4485,472,472,472
BEGIN DESCRIPTION:
GRAYS BRANCH 2.5
END DESCRIPTION:
XS GIS Cut Line= 4
      3394603.30     10618117.88      3393499.29     10617875.08
      3393224.43     10617508.61      3392757.17     10617357.43
#Sta/Elev= 30
  3640.7  551.47  4009.9  545.84  4158.8  543.80  4461.0  543.21  4480.4  538.28
  4485.6  542.16  4502.0  537.29  4512.2  536.88  4529.3  540.98  4534.4  538.30
  4553.2  542.02  4573.1  542.65  4800.4  543.22  4836.5  541.65  4957.4  543.13
  4963.6  542.99  4971.9  539.98  4978.2  535.40  4989.8  531.22  4992.5  530.72
  4995.8  531.22  5007.4  535.19  5013.6  540.14  5050.4  544.03  5232.4  542.53
  5284.2  539.63  5337.5  540.32  5452.4  546.00  5657.6  563.76  5720.3  565.18
#Mann=4,-1,0
  3640.7    0.05       0  4009.9    0.16       0  4989.8    0.07       0
  4995.8    0.16       0
Bank Sta=4989.8,4995.8
Exp/Cntr=0.3,0.1

Type RM Length L Ch R = 1,4013,1610,1610,1610
BEGIN DESCRIPTION:
GRAYS BRANCH 2.0
END DESCRIPTION:
XS GIS Cut Line= 4
      3394691.29     10617669.58      3393665.21     10617341.44
      3393430.83     10617497.69      3392822.53     10617196.14
#Sta/Elev= 30
  3756.5  550.36  3934.8  549.71  4224.3  544.17  4314.1  543.62  4486.9  541.75
  4603.4  541.85  4631.2  541.78  4732.0  541.86  4826.5  539.96  4966.5  542.04
  4981.6  541.18  4987.6  534.69  4990.7  532.50  4993.5  532.00  4996.7  532.50
  5002.6  532.60  5008.6  536.15  5016.0  537.98  5023.6  540.57  5044.6  542.01
  5095.7  541.66  5125.2  542.45  5225.5  541.70  5275.6  541.19  5314.9  539.68
  5320.5  538.57  5365.3  539.61  5493.5  546.21  5724.0  563.85  5794.4  566.01
#Mann=8,-1,0
  3756.5    0.05       0  4314.1    0.16       0  4603.4    0.05       0
  4631.2    0.16       0  4990.7    0.07       0  4996.7    0.16       0
  5016.0    0.12       0  5225.5    0.16       0
Bank Sta=4990.7,4996.7
Exp/Cntr=0.3,0.1

Type RM Length L Ch R = 1,2403,0,0,0
BEGIN DESCRIPTION:
GRAYS BRANCH 1.0
END DESCRIPTION:
XS GIS Cut Line= 4
      3394800.61     10617310.17      3394149.58     10616716.44
      3393337.08     10616476.85      3392717.25     10616695.62
#Sta/Elev= 30
  3390.2  548.79  3529.6  548.79  3629.0  547.09  3713.4  547.77  4003.9  543.56
  4201.9  538.99  4592.9  537.90  4660.2  538.98  4706.6  537.68  4967.2  539.80
  4975.1  537.77  4980.3  538.62  4995.5  529.15  4998.2  528.65  5001.5  529.15
  5008.4  533.06  5013.6  533.11  5019.3  537.79  5082.1  539.41  5210.9  543.20
  5293.0  547.01  5360.2  550.45  5385.8  553.50  5410.0  554.66  5447.7  553.58
  5516.0  555.42  5611.5  556.17  5628.0  555.30  5667.5  556.53  5775.7  556.49
#Mann=6,-1,0
  3390.2    0.05       0  4660.2    0.16       0  4995.5    0.07       0
  5001.5    0.16       0  5082.1    0.05       0  5667.5    0.16       0
Bank Sta=4995.5,5001.5
Exp/Cntr=0.3,0.1

Chan Stop Cuts=-1