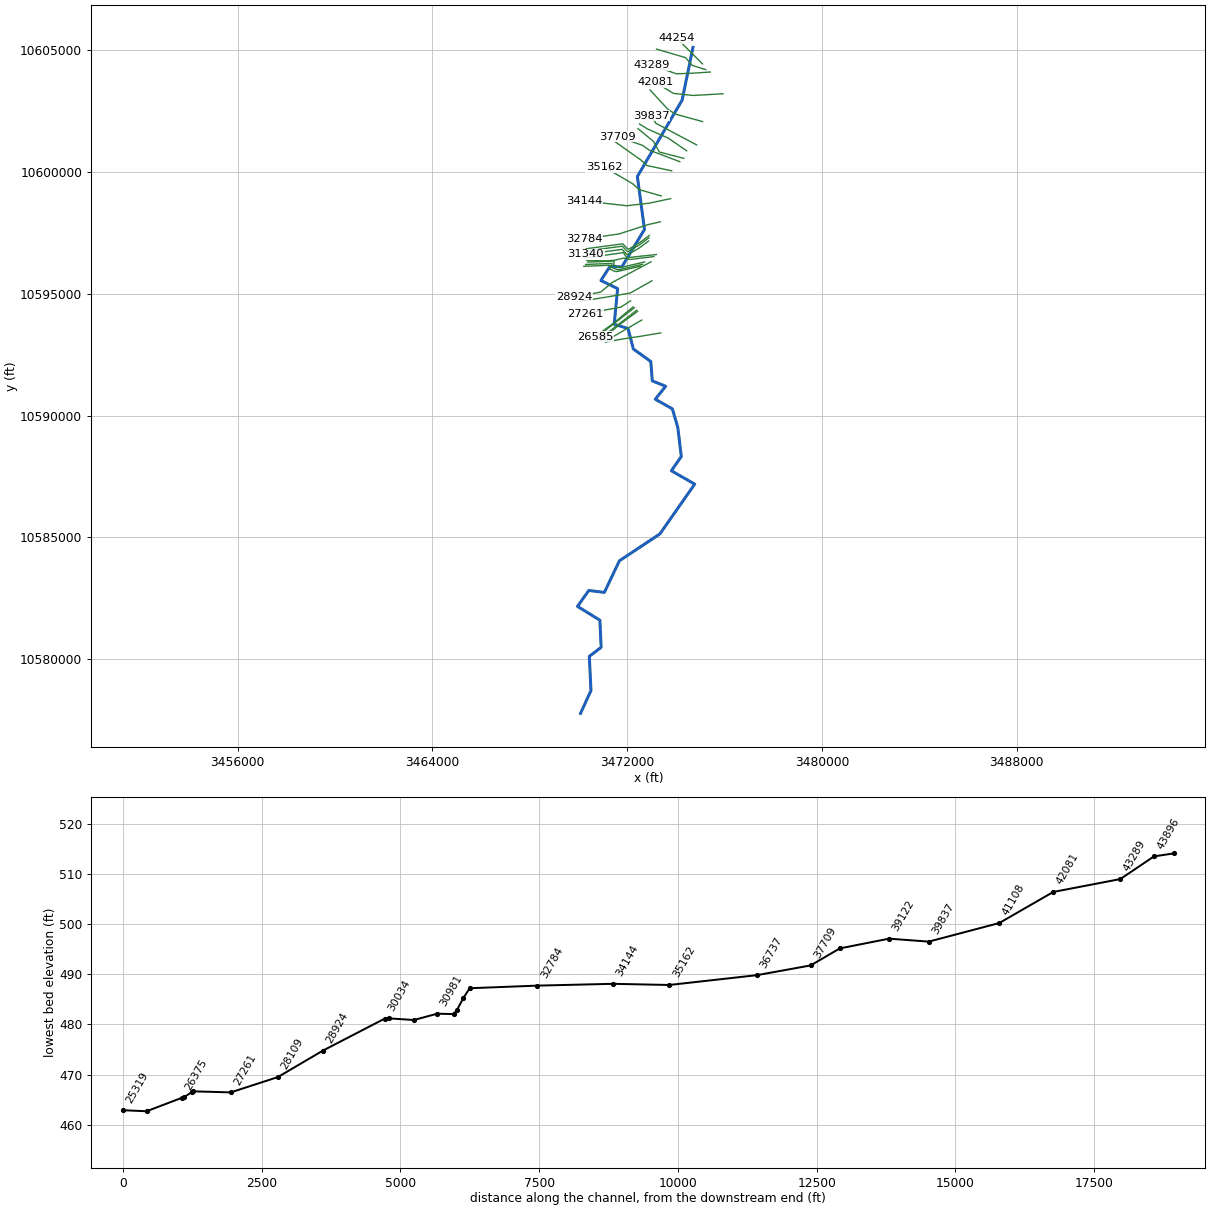
--- JACKS CREEK.prj (project) ---

Proj Title=JACKS CREEK Base Level Engineering
Current Plan=p01
Default Exp/Contr=0.3,0.1
English Units
Geom File=g01
Flow File=f01
Plan File=p01
Y Axis Title=Elevation
X Axis Title(PF)=Main Channel Distance
X Axis Title(XS)=Station
BEGIN DESCRIPTION:
JACKS CREEK
END DESCRIPTION:
DSS Export Rating Curves= 0
DSS Export Rating Curve Sorted= 0
DSS Export Volume Flow Curves= 0
DXF OffsetX= 0
DXF OffsetY= 0
DXF ScaleX= 1
DXF ScaleY= 10

--- JACKS CREEK.p01 (plan) ---

Plan Title=Multiple Run
Program Version=4.10
Short Identifier=Multiple
Geom File=g01
Flow File=f01
Subcritical Flow
K Sum by GR= 0
Std Step Tol= 0.01
Critical Tol= 0.01
Num of Std Step Trials= 20
Max Error Tol= 0.3
Flow Tol Ratio= 0.001
Split Flow NTrial= 30
Split Flow Tol= 0.02
Split Flow Ratio= 0.02
Log Output Level= 0
Friction Slope Method= 1
Unsteady Friction Slope Method= 2
Unsteady Bridges Friction Slope Method= 1
Parabolic Critical Depth
Global Vel Dist= 1 , 1 , 1
Global Log Level= 0
CheckData=True
Encroach Param=-1 ,0,0, 0
BEGIN DESCRIPTION:
Multiple Run
END DESCRIPTION:
Computation Interval=1HOUR
Output Interval=1HOUR
Run HTab= 0
Run UNet= 0
Run PostProcess= 0
Run WQNet= 0
UNET Theta= 1
UNET Theta Warmup= 1
UNET ZTol= 0.02
UNET ZSATol= 0.05
UNET MxIter= 20
UNET MaxInSteps= 0
UNET DtIC= 0
UNET DtMin= 0
UNET MaxCRTS= 20
UNET WFStab= 2
UNET SFStab= 1
UNET WFX= 1
UNET SFX= 1
UNET DSS MLevel= 4
UNET DZMax Abort= 100
UNET Convert EG Bridges= 0
UNET Use Existing IB Tables=-1
UNET Froude Reduction=False
UNET Froude Limit= 1
UNET Froude Power= 10
UNET Time Slicing=0,0, 5
UNET Junction Losses=0
Instantaneous Interval=1HOUR
Write IC File= 0
Write IC File at Sim End=0
Echo Input=False
Echo Parameters=False
Echo Output=False
Write Detailed= 0
WQ AD Non Conservative
WQ ULTIMATE=-1
WQ Max Comp Step=1HOUR
WQ Output Interval=15MIN
WQ Output Selected Increments= 0
WQ Output face flow=0
WQ Output face velocity=0
WQ Output face area=0
WQ Output face dispersion=0
WQ Output cell volume=0
WQ Output cell surface area=0
WQ Output cell continuity=0
WQ Output cumulative cell continuity=0
WQ Output face conc=0
WQ Output face dconc_dx=0
WQ Output face courant=0
WQ Output face peclet=0
WQ Output face adv mass=0
WQ Output face disp mass=0
WQ Output cell mass=0
WQ Output cell source sink temp=0
WQ Output cell source sink nsm=0
WQ Output MaxMinRange=-1
WQ Daily Max Min Mean=-1
WQ Daily Range=0
WQ Daily Time=0
WQ Create Restart=0
WQ Fixed Restart=0
WQ System Summary=0
WQ Use Fixed Temperature=0
Sorting and Armoring Iterations= 10
XS Update Threshold= 0.02
Hydraulics Update Threshold= 0.02
Energy Slope Method= 1
Volume Change Method= 0
XS Weighting Method= 0
Number of US Weighted Cross Sections= 1
Number of DS Weighted Cross Sections= 1
Upstream XS Weight=0.25
Main XS Weight=0.5
Downstream XS Weight=0.25
Number of DS XS's Weighted with US Boundary= 1
Upstream Boundary Weight= 1
Weight of XSs Associated with US Boundary= 0
Number of US XS's Weighted with DS Boundary= 1
Downstream Boundary Weight= 0.5
Weight of XSs Associated with DS Boundary= 0.5
Sediment Output Level= 4
Mass or Volume Output= 0
Output Increment Type= 1
Profile and TS Output Increment= 10
XS Output Flag= 0
XS Output Increment= 10
Disregard all LS=0
Disregard all Conn=0
Disregard all Breaches=0
Disregard all Pumps=0

--- JACKS CREEK.f01 (steady flow) ---

Flow Title=Multiple
Program Version=4.10
Number of Profiles= 7
Profile Names=10-year,25-year,50-year,1pct_min,100-year,1pct_plu,500-year
River Rch & RM=JACKS CREEK,Reach-1         ,44254
     612     790     926     789    1067    1443    1415
River Rch & RM=JACKS CREEK,Reach-1         ,42081
     813    1063    1256    1079    1459    1973    1964
River Rch & RM=JACKS CREEK,Reach-1         ,37709
     829    1082    1277    1094    1480    2001    1985
River Rch & RM=JACKS CREEK,Reach-1         ,34144
     967    1267    1498    1286    1739    2352    2340
River Rch & RM=JACKS CREEK,Reach-1         ,26417
    1008    1322    1563    1342    1815    2455    2443
River Rch & RM=JACKS CREEK,Reach-1         ,25021
    1008    1320    1561    1339    1811    2449    2434
River Rch & RM=JACKS CREEK,Reach-1         ,21942
    1262    1665    1977    1703    2303    3114    3118
River Rch & RM=JACKS CREEK,Reach-1         ,12913
    1983    2661    3197    2782    3762    5088    5202
River Rch & RM=JACKS CREEK,Reach-1         ,6936
    2143    2879    3462    3013    4075    5511    5638
River Rch & RM=JACKS CREEK,Reach-1         ,3395
    2290    3083    3712    3235    4375    5917    6069
River Rch & RM=JACKS CREEK,Reach-1         ,1390
    2452    3308    3990    3482    4709    6369    6551
Boundary for River Rch & Prof#=JACKS CREEK,Reach-1         , 1
Up Type= 0
Dn Type= 3
Dn Slope=0.002
Boundary for River Rch & Prof#=JACKS CREEK,Reach-1         , 2
Up Type= 0
Dn Type= 3
Dn Slope=0.002
Boundary for River Rch & Prof#=JACKS CREEK,Reach-1         , 3
Up Type= 0
Dn Type= 3
Dn Slope=0.002
Boundary for River Rch & Prof#=JACKS CREEK,Reach-1         , 4
Up Type= 0
Dn Type= 3
Dn Slope=0.002
Boundary for River Rch & Prof#=JACKS CREEK,Reach-1         , 5
Up Type= 0
Dn Type= 3
Dn Slope=0.002
Boundary for River Rch & Prof#=JACKS CREEK,Reach-1         , 6
Up Type= 0
Dn Type= 3
Dn Slope=0.002
Boundary for River Rch & Prof#=JACKS CREEK,Reach-1         , 7
Up Type= 0
Dn Type= 3
Dn Slope=0.002
DSS Import GetInterval= 0
DSS Import GetPeak= 0
DSS Import FillOption= 0

--- JACKS CREEK.g01 (geometry) ---

Geom Title=Existing Conditions
Program Version=4.10

River Reach=JACKS CREEK     ,Reach-1
Reach XY= 30
      3474702.11     10605121.64      3474255.67     10602954.88
      3472417.81     10599818.27      3472710.25     10597644.79
      3471780.24     10596105.98      3471288.71     10596121.17
      3470921.51     10595549.86      3471606.65     10595214.36
      3471466.53     10593751.33      3472034.45     10593577.98
       3472252.4     10592736.73      3472969.48     10592220.79
      3473030.24     10591426.82      3473580.07     10591205.93
      3473152.67     10590672.27      3473854.86     10590278.56
      3474080.17     10589506.85       3474220.8     10588321.83
      3473814.35     10587737.63      3474771.91     10587186.19
      3473342.11     10585141.64      3471680.03     10584037.41
       3471063.5     10582742.37      3470422.86     10582819.46
       3469959.2     10582167.95      3470878.68     10581600.42
      3470930.42     10580486.12        3470445.     10580114.05
      3470512.72     10578712.94      3470085.05     10577774.03

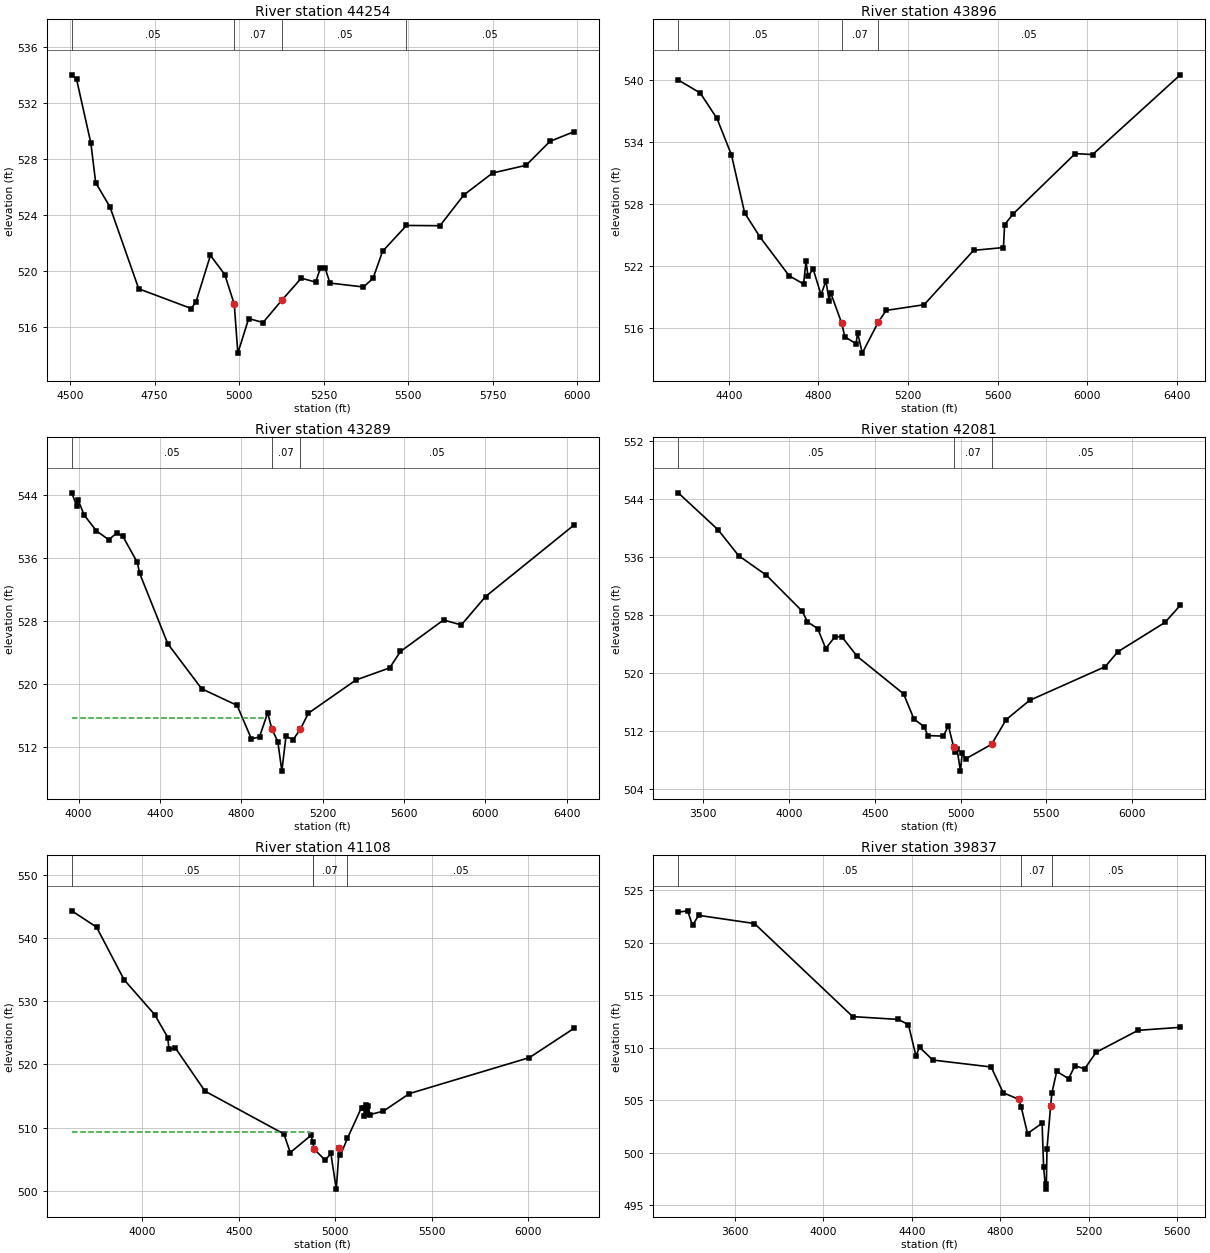
Type RM Length L Ch R = 1 ,44254   ,358,358,358
BEGIN DESCRIPTION:
JACKS CREEK 47.0
END DESCRIPTION:
XS GIS Cut Line= 3
      3475092.09     10604441.65      3474742.11     10604791.64
      3474042.11     10605491.64
#Sta/Elev= 30
  4505.1  534.02  4519.2  533.71  4561.7  529.12  4575.8  526.31  4618.2  524.57
  4703.1  518.72  4858.6  517.31  4872.8  517.81  4915.2  521.11  4957.6  519.74
 4985.63  517.62  4996.3  514.12  5028.3  516.59  5070.8  516.31  5127.3  517.93
  5183.9  519.48  5226.3   519.2  5240.5   520.2  5254.6  520.18  5268.8  519.13
  5367.8  518.85    5396  519.46  5424.3   521.4    5495  523.25    5594  523.23
  5664.7  525.43  5749.6     527  5848.6  527.55  5919.3  529.26    5990  529.95
#Mann= 4 ,-1 , 0
  4505.1     .05       0 4985.63     .07       0  5127.3     .05       0
    5495     .05       0
#XS Ineff= 2 , 0
         4887.27  518.67
Permanent Ineff=
       F       F
Bank Sta=4985.63,5127.3
XS Rating Curve= 0 ,0
Exp/Cntr=0.3,0.1

Type RM Length L Ch R = 1 ,43896   ,607,607,607
BEGIN DESCRIPTION:
JACKS CREEK 46.0
END DESCRIPTION:
XS GIS Cut Line= 4
      3475225.86     10604205.27      3474670.31     10604382.35
      3474396.01     10604698.32      3473206.03     10605048.72
#Sta/Elev= 30
  4174.1     540  4272.3  538.74  4347.2  536.27  4411.7  532.74  4470.8  527.11
  4540.5  524.74  4669.3  521.03  4733.7  520.23  4744.8  522.42  4753.6  520.99
  4776.7  521.67  4811.8  519.19  4833.7  520.53    4848  518.62  4854.6  519.39
    4904  516.44  4918.2   515.1  4968.1  514.45  4975.2  515.51  4995.8  513.53
  5067.3  516.53  5102.4  517.67  5272.1  518.22    5493  523.49  5626.3  523.76
  5631.5  525.98  5670.1  527.03  5947.2  532.87  6024.3  532.77  6416.1   540.5
#Mann= 3 , 0 , 0
  4174.1     .05       0    4904     .07       0  5067.3     .05       0
Bank Sta=4904,5067.3
XS Rating Curve= 0 ,0
Exp/Cntr=0.3,0.1

Type RM Length L Ch R = 1 ,43289   ,1208,1208,1208
BEGIN DESCRIPTION:
JACKS CREEK 44.0
END DESCRIPTION:
XS GIS Cut Line= 4
      3475413.32     10604108.04      3474663.37     10604059.43
      3474024.48     10604035.13      3473007.14     10604389.28
#Sta/Elev= 30
  3966.2  544.26  3990.1  542.63  3997.5  543.33  4027.5  541.43  4087.7  539.43
  4147.8  538.32  4187.9  539.17  4217.9  538.73  4288.1  535.45  4300.1  534.05
  4438.4  525.13    4605  519.43    4779  517.33  4849.1  513.09  4889.1  513.33
  4929.1  516.39  4949.2  514.39  4979.2  512.72  4998.9     509  5019.2  513.41
  5054.2  512.99  5089.3  514.28  5129.3  516.34  5363.3  520.55    5529  522.08
    5582  524.16  5793.7  528.15  5881.2  527.52  6000.3  531.12  6434.3  540.16
#Mann= 3 , 0 , 0
  3966.2     .05       0  4949.2     .07       0  5089.3     .05       0
#XS Ineff= 2 , 0
       0 4921.07  515.78               0
Permanent Ineff=
       T       F
Bank Sta=4949.2,5089.3
XS Rating Curve= 0 ,0
Exp/Cntr=0.3,0.1

Type RM Length L Ch R = 1 ,42081   ,973,973,973
BEGIN DESCRIPTION:
JACKS CREEK 42.0
END DESCRIPTION:
XS GIS Cut Line= 4
      3475934.15     10603215.68      3474715.45     10603146.24
      3473899.48     10603229.57      3473145.99     10603698.33
#Sta/Elev= 30
  3353.3  544.84  3585.7  539.74  3705.9  536.16  3867.4  533.47  4076.5   528.5
  4106.6  527.04  4166.7   526.1  4213.5  523.35  4266.8  524.97  4306.9  524.99
    4397  522.27  4667.8  517.09  4728.1  513.62  4788.4  512.54  4808.5  511.34
    4899  511.26  4929.2  512.67  4959.3  509.79    4968  509.02  4979.4  509.48
  4999.3  506.43  5009.6   508.9  5029.7  508.13  5180.5  510.12  5266.4  513.55
  5402.3  516.19  5843.8  520.85    5917   522.9    6192  526.95  6281.6  529.32
#Mann= 3 , 0 , 0
  3353.3     .05       0  4959.3     .07       0  5180.5     .05       0
Bank Sta=4959.3,5180.5
XS Rating Curve= 0 ,0
Exp/Cntr=0.3,0.1

Type RM Length L Ch R = 1 ,41108   ,1271,1271,1271
BEGIN DESCRIPTION:
JACKS CREEK 41.0
END DESCRIPTION:
XS GIS Cut Line= 4
      3475093.89     10602073.33      3473986.28     10602378.88
      3473677.26     10602573.32      3472937.64     10603371.96
#Sta/Elev= 30
  3634.7  544.36  3763.1  541.78  3905.7  533.44  4063.9  527.92  4132.7  524.27
  4137.8  522.44  4172.2  522.59  4325.2  515.77  4734.3  508.98  4767.3  506.03
  4875.3  508.77  4883.1  507.74  4890.6  506.59  4948.3  504.82  4977.7   505.9
  5005.8  500.23  5021.3  506.77  5027.2   505.6  5063.7  508.29  5136.7  513.17
  5148.8  513.14  5151.2  511.76  5158.5  513.55  5165.3  512.17  5172.7   513.4
  5179.5  512.04  5250.4   512.6  5384.8  515.38  6007.3  521.09  6237.3  525.71
#Mann= 4 ,-1 , 0
  3634.7     .05       0  4883.1     .16       0  4883.1     .07       0
  5063.7     .05       0
#XS Ineff= 2 , 0
       0 4872.16  509.26               0
Permanent Ineff=
       T       F
Bank Sta=4890.6,5021.3
XS Rating Curve= 0 ,0
Exp/Cntr=0.3,0.1

Type RM Length L Ch R = 1 ,39837   ,715,715,715
BEGIN DESCRIPTION:
JACKS CREEK 40.0
END DESCRIPTION:
XS GIS Cut Line= 3
      3474851.78      10601115.1      3473176.43     10602004.86
      3472976.92     10602321.48
#Sta/Elev= 30
    3343  522.91  3385.6  523.04  3407.6  521.65  3435.2  522.61  3687.7  521.83
  4132.3  512.96    4339  512.69  4384.3  512.19  4418.3  509.22  4434.4  510.04
  4494.7  508.82  4758.5  508.16  4813.1   505.7  4884.8  505.07  4893.9  504.39
  4923.1  501.82    4989   502.8  4995.8  498.59  5005.1  496.52  5008.3  497.02
    5011  500.33  5027.3   504.4    5033  505.64    5055  507.74    5109  507.04
  5137.2  508.28  5181.2  507.98  5233.5  509.56  5422.8  511.65  5614.2  511.94
#Mann= 3 ,-1 , 0
    3343     .05       0  4893.9     .07       0    5033     .05       0
Bank Sta=4884.8,5027.3
XS Rating Curve= 0 ,0
Exp/Cntr=0.3,0.1

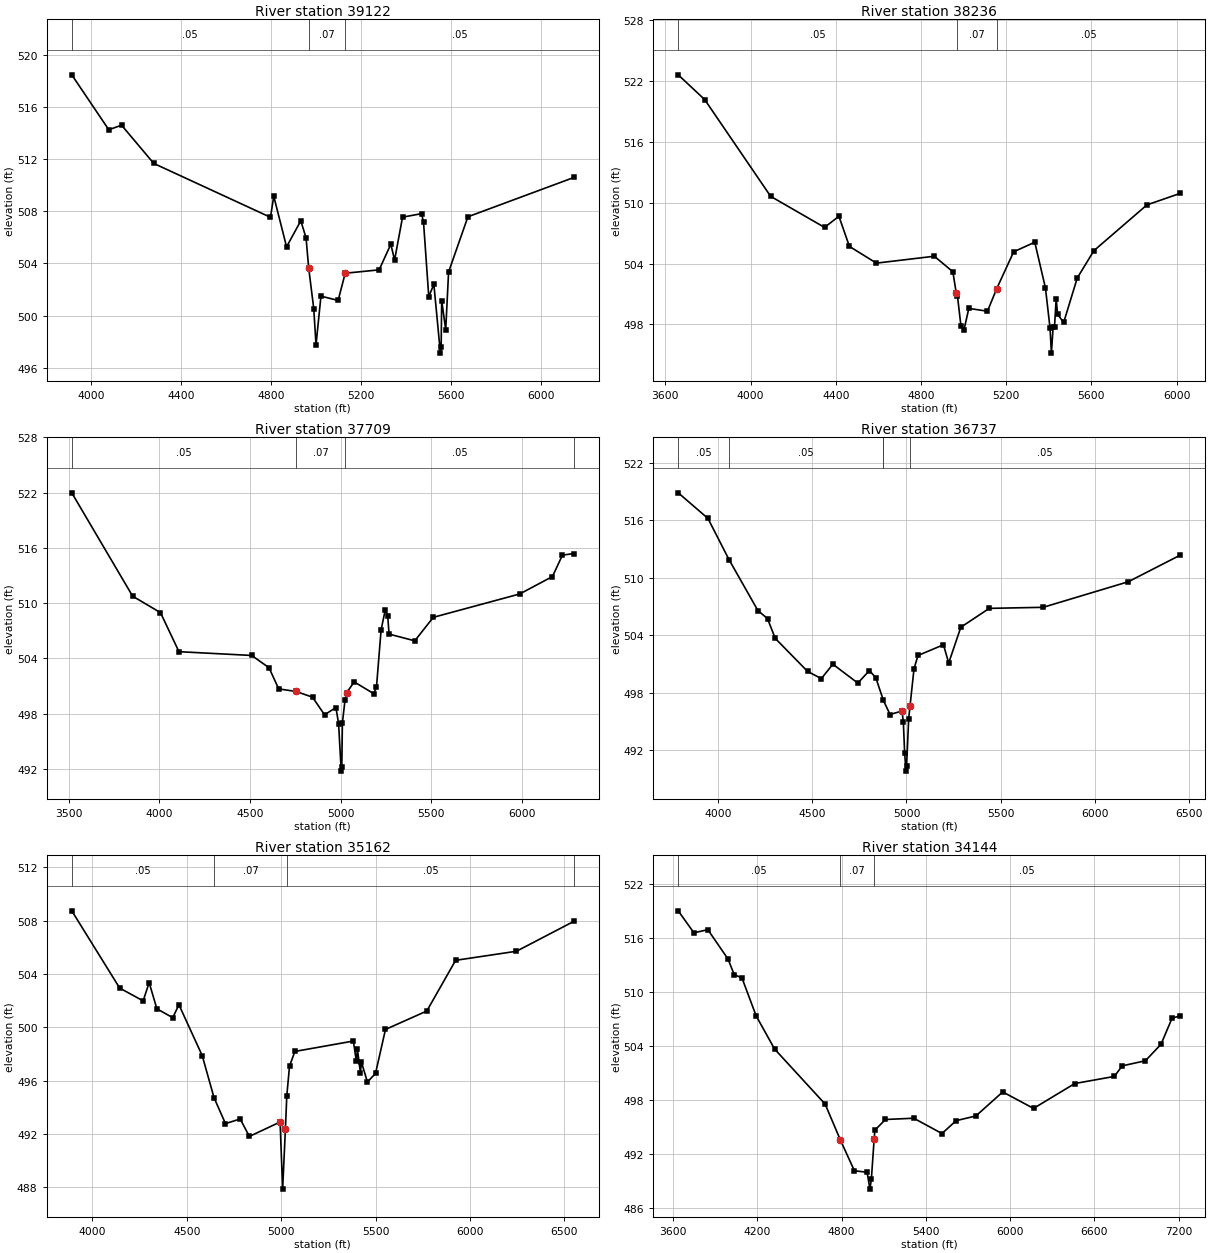
Type RM Length L Ch R = 1 ,39122   ,886,886,886
BEGIN DESCRIPTION:
JACKS CREEK 39.1
END DESCRIPTION:
XS GIS Cut Line= 4
      3474442.72     10600873.14       3473682.3     10601396.58
      3472835.94     10601768.97      3472506.19      10601971.5
#Sta/Elev= 30
  3913.5   518.5  4078.3  514.28  4135.1  514.63  4278.5  511.69    4798  507.55
  4812.6  509.17  4869.6  505.28  4932.9  507.28  4956.3  505.97    4968  503.67
  4990.5  500.54  5000.7  497.75  5022.6  501.49  5099.1  501.16  5130.6  503.25
  5281.6  503.51  5333.7  505.48  5350.4  504.26  5385.8  507.56  5470.5  507.83
  5479.2  507.17  5502.5  501.45  5525.2   502.4  5554.4  497.11  5557.7  497.61
  5560.1  501.15    5578   498.9  5590.7  503.34  5676.8  507.59  6148.3  510.61
#Mann= 3 , 0 , 0
  3913.5     .05       0    4968     .07       0  5130.6     .05       0
Bank Sta=4968,5130.6
XS Rating Curve= 0 ,0
Exp/Cntr=0.3,0.1

Type RM Length L Ch R = 1 ,38236   ,527,527,527
BEGIN DESCRIPTION:
JACKS CREEK 39.0
END DESCRIPTION:
XS GIS Cut Line= 4
      3474322.29     10600563.88      3473319.66     10600824.31
      3473076.61     10601262.67      3472442.92     10601783.51
#Sta/Elev= 30
  3660.4   522.6  3784.6  520.16  4094.5  510.62  4347.6  507.56  4414.8  508.66
  4464.1  505.69  4590.9  504.04  4862.8  504.72  4949.8  503.19  4965.8  501.09
  4971.5   500.8  4987.6  497.88    5002  497.45  5024.8  499.58  5112.3   499.3
  5155.8  501.53  5235.5  505.16  5334.5   506.1  5384.6  501.59  5406.3   497.6
  5412.5  495.17  5420.6  497.71  5427.1  497.76    5435  500.54  5441.4     499
  5470.1  498.19    5534  502.58  5612.2  505.27  5861.1  509.78  6017.8  510.92
#Mann= 3 ,-1 , 0
  3660.4     .05       0  4971.5     .07       0  5155.8     .05       0
Bank Sta=4965.8,5155.8
XS Rating Curve= 0 ,0
Exp/Cntr=0.3,0.1

Type RM Length L Ch R = 1 ,37709   ,972,972,972
BEGIN DESCRIPTION:
JACKS CREEK 38.0
END DESCRIPTION:
XS GIS Cut Line= 4
      3474159.85      10600427.5      3472909.89     10600899.71
      3472635.59     10601094.15      3471600.85     10601458.74
#Sta/Elev= 30
  3516.6  521.99  3852.3  510.77  4005.9  508.98  4107.9  504.74  4509.1  504.33
  4604.6     503    4658   500.7    4754  500.42  4844.6   499.8  4910.9  497.89
  4973.6  498.67  4988.4  496.94  5002.9  491.77  5006.2  492.27  5009.4  497.01
  5024.1  499.54  5032.7  500.28  5074.6  501.46  5181.6  500.19  5197.3  500.87
  5222.9  507.11  5245.7  509.26  5259.2  508.66  5266.9  506.65  5408.6  505.92
  5510.8  508.47  5987.9  511.01  6168.1   512.9    6223  515.22  6286.1   515.4
#Mann= 4 ,-1 , 0
  3516.6     .05       0    4754     .07       0  5024.1     .05       0
  6286.1     .05       0
Bank Sta=4754,5032.7
XS Rating Curve= 0 ,0
Exp/Cntr=0.3,0.1

Type RM Length L Ch R = 1 ,36737   ,1575,1575,1575
BEGIN DESCRIPTION:
JACKS CREEK 37.0
END DESCRIPTION:
XS GIS Cut Line= 4
      3473826.52      10600052.5      3472798.78     10600271.24
      3472580.03     10600483.04      3471507.12     10601243.46
#Sta/Elev= 30
    3786  518.87  3943.9   516.2  4056.3  511.89  4209.7  506.58  4260.8  505.74
  4301.7  503.68  4474.4  500.22  4547.1  499.48  4608.4  500.98  4741.3  499.01
  4802.7  500.32  4836.8  499.57  4877.1  497.21  4912.5  495.73  4976.1   496.1
  4983.3  494.94  4990.2  491.69  4997.2  489.82  5000.4  490.32  5011.6  495.28
  5018.5  496.57  5039.9  500.49    5061  501.89  5196.6  503.01  5224.5  501.11
  5288.9  504.84  5440.2  506.81    5727  506.92  6179.8  509.59  6456.3  512.37
#Mann= 5 ,-1 , 0
    3786     .05       0  4056.3     .05       0  4877.1      .1       0
  4877.1     .07       0  5018.5     .05       0
Bank Sta=4976.1,5018.5
XS Rating Curve= 0 ,0
Exp/Cntr=0.3,0.1

Type RM Length L Ch R = 1 ,35162   ,1018,1018,1018
BEGIN DESCRIPTION:
JACKS CREEK 36.0
END DESCRIPTION:
XS GIS Cut Line= 4
      3473396.02     10599021.23      3472500.17     10599278.18
      3472229.34     10599517.76      3471052.23     10600208.75
#Sta/Elev= 30
    3891  508.73  4144.7  502.94  4268.9  501.98  4300.8  503.35  4341.5  501.39
  4425.6  500.72  4458.4  501.69  4581.7  497.88  4644.1  494.73  4704.9  492.78
  4782.8  493.13  4831.4  491.82    4994   492.9  5007.6  487.87  5022.1  492.36
  5029.6  494.87  5043.9  497.08  5072.3  498.19  5382.1  498.97  5397.8  497.46
  5403.6  498.35  5419.2  496.61    5425  497.38  5456.4   495.9  5499.3  496.54
  5552.1  499.84  5770.9  501.22  5923.5  505.02  6245.7   505.7  6549.5  507.94
#Mann= 4 ,-1 , 0
    3891     .05       0  4644.1     .07       0  5029.6     .05       0
  6549.5     .05       0
Bank Sta=4994,5022.1
XS Rating Curve= 0 ,0
Exp/Cntr=0.3,0.1

Type RM Length L Ch R = 1 ,34144   ,1360,1360,1360
BEGIN DESCRIPTION:
JACKS CREEK 35.0
END DESCRIPTION:
XS GIS Cut Line= 4
      3473784.88     10598910.12      3472902.95     10598722.63
      3471979.34     10598618.46      3470245.19     10598812.68
#Sta/Elev= 30
  3636.6  518.99  3748.2  516.55  3847.4   516.9  3991.1  513.64  4035.5   511.9
  4090.3  511.55  4191.5  507.33  4322.9  503.65  4682.9  497.54  4790.7  493.58
  4891.3  490.14  4981.9  489.97  5001.8   488.1  5012.1  489.19  5032.2   493.7
  5037.5  494.65  5112.7  495.83    5314  495.97  5515.2  494.27  5615.9   495.7
  5756.7  496.22  5947.9  498.89  6167.2  497.06  6461.1  499.82  6742.9  500.61
  6798.6  501.78  6964.2  502.35  7074.9  504.17  7154.4  507.09  7212.7  507.33
#Mann= 3 ,-1 , 0
  3636.6     .05       0  4790.7     .07       0  5032.2     .05       0
Bank Sta=4790.7,5032.2
XS Rating Curve= 0 ,0
Exp/Cntr=0.3,0.1

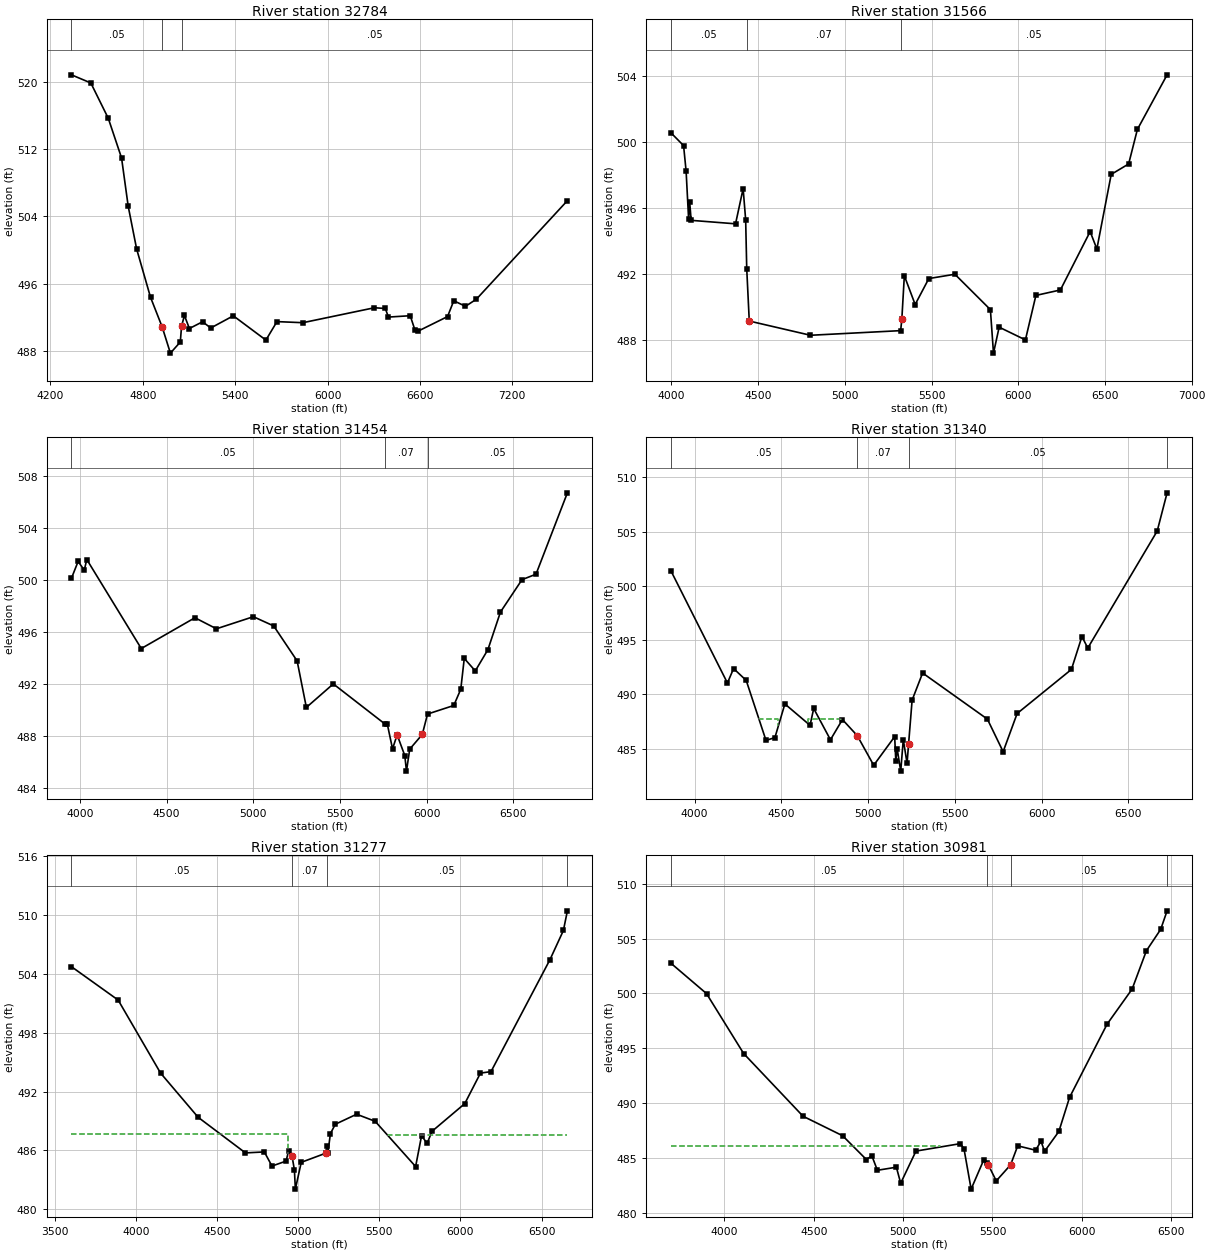
Type RM Length L Ch R = 1 ,32784   ,1218,1218,1218
BEGIN DESCRIPTION:
JACKS CREEK 34.0
END DESCRIPTION:
XS GIS Cut Line= 5
      3473364.79     10597958.75      3472861.28     10597844.15
      3471663.37     10597458.74      3470267.53     10597257.35
      3470232.82     10597246.94
#Sta/Elev= 30
  4336.3  520.85  4462.1  519.88  4575.6  515.67  4661.7  510.96  4704.7  505.23
  4759.5  500.14  4849.7  494.39  4925.4  490.86  4978.9  487.74  5043.3  489.06
  5051.4  490.95  5070.1  492.22  5102.2  490.67    5188  491.47  5241.1  490.73
  5387.6  492.18  5599.2  489.29  5671.2  491.49  5839.3  491.36  6304.3  493.14
    6375  493.05  6395.2  492.03  6536.7  492.19    6567  490.51  6587.2  490.35
  6779.2  492.09  6819.6  493.97  6895.7  493.31  6966.1  494.15  7557.6  505.88
#Mann= 3 , 0 , 0
  4336.3     .05       0  4925.4     .07       0  5051.4     .05       0
Bank Sta=4925.4,5051.4
XS Rating Curve= 0 ,0
Exp/Cntr=0.3,0.1

Type RM Length L Ch R = 1 ,31566   ,112,112,112
BEGIN DESCRIPTION:
JACKS CREEK 32.2
END DESCRIPTION:
XS GIS Cut Line= 6
        3472907.     10597397.71       3472534.6     10597116.46
      3472064.55     10596837.81      3472000.75     10596858.65
      3471818.46     10597055.26      3470322.35     10596852.78
#Sta/Elev= 30
  3998.3  500.53  4069.9  499.77  4084.5  498.22    4099  495.31  4105.3  496.33
  4113.6  495.25  4369.6  495.04  4413.3  497.17  4427.9  495.28  4434.1  492.32
  4448.7  489.16  4801.7   488.3  5321.7  488.58 5328.48  489.26    5343   491.9
  5405.4  490.16  5484.2  491.73  5634.5  491.99  5839.3  489.85  5857.1  487.22
  5889.8  488.79  6041.2  488.02  6101.7  490.71    6243  491.04  6414.5  494.57
  6453.3  493.52    6536  498.03  6636.5  498.66    6687  500.75  6858.3  504.05
#Mann= 3 ,-1 , 0
  3998.3     .05       0  4434.1     .07       0  5321.7     .05       0
#XS Ineff= 1 ,-1
 5365.22 6893.66490.9199
Permanent Ineff=
       F
Bank Sta=4448.7,5328.48
XS Rating Curve= 0 ,0
Exp/Cntr=0.3,0.1

Type RM Length L Ch R = 1 ,31454   ,114,114,114
BEGIN DESCRIPTION:
JACKS CREEK 32.3
END DESCRIPTION:
XS GIS Cut Line= 6
      3472887.45     10597300.03      3472515.07      10597018.8
      3472045.02     10596740.16      3471981.22     10596760.99
      3471798.93      10596957.6      3470302.79     10596755.12
#Sta/Elev= 30
    3951  500.14  3989.4  501.43  4024.8  500.76  4039.4  501.58  4353.6  494.73
  4663.1   497.1  4787.1  496.25  5000.1  497.18  5117.2  496.47  5252.4  493.78
  5305.7   490.2    5461  492.01  5756.5  488.95  5772.3  488.93  5802.6  487.01
  5829.1  488.09  5873.2   486.5    5883   485.3  5901.7  486.99  5974.1  488.12
  6004.4  489.69  6155.8  490.35  6196.1   491.6  6216.3  493.97  6279.8  493.01
  6352.4  494.64    6425  497.54  6549.3  500.03    6630  500.45    6811  506.71
#Mann= 3 ,-1 , 0
    3951     .05       0  5756.5     .07       0  6004.4     .05       0
Bank Sta=5829.1,5974.1
XS Rating Curve= 0 ,0
Exp/Cntr=0.3,0.1

Type RM Length L Ch R = 1 ,31340   ,63,63,63
BEGIN DESCRIPTION:
JACKS CREEK 32.1
END DESCRIPTION:
XS GIS Cut Line= 6
      3472878.81     10597169.86      3472506.39     10596888.59
      3472036.34     10596609.95      3471972.54     10596630.78
      3471790.25      10596827.4      3470295.65     10596625.12
#Sta/Elev= 30
  3864.9  501.35  4189.2  491.06  4224.6  492.39  4297.4   491.3  4411.5  485.77
  4462.9  486.03  4520.3  489.13  4665.4  487.16  4686.5  488.71    4783  485.83
  4852.1  487.69  4937.5  486.21  5032.3  483.48  5153.2  486.12  5159.6   483.9
  5167.6  484.99  5188.1  482.94  5202.8  485.85  5224.6  483.66  5233.5  485.47
  5253.7  489.48  5314.2  491.98  5687.6  487.73  5778.4  484.73  5859.1  488.25
    6172  492.31  6232.5  495.34  6266.3  494.28  6666.4  505.06  6723.4  508.58
#Mann= 4 ,-1 , 0
  3864.9     .05       0  4937.5     .07       0  5233.5     .05       0
  6723.4     .05       0
#XS Ineff= 3 ,-1
 4365.07  4482.5 487.761  4651.9 4846.47 487.765 5657.19 5860.18 487.765
Permanent Ineff=
       T       T       T
Bank Sta=4937.5,5233.5
XS Rating Curve= 0 ,0
Exp/Cntr=0.3,0.1

Type RM Length L Ch R = 1 ,31277   ,296,296,296
BEGIN DESCRIPTION:
JACKS CREEK 31.1
END DESCRIPTION:
XS GIS Cut Line= 4
      3473198.09     10596614.99      3471982.81     10596483.04
      3471843.92     10596691.38      3470275.79     10596472.81
#Sta/Elev= 30
  3602.7  504.72  3890.4  501.32  4151.9  493.88  4383.2  489.38  4674.9  485.75
  4791.2  485.85  4838.4  484.41  4925.6  484.92  4940.6  485.97  4961.6  485.46
  4976.6  484.01  4982.4  482.06  5018.7  484.79  5168.2  485.71  5177.7  486.45
  5182.8  485.75  5198.5  487.72  5228.8  488.67    5360  489.69  5474.1  488.97
  5723.5  484.36  5760.3  487.51  5794.2  486.71  5824.5  487.95  6026.4  490.77
  6123.1  493.88    6188  494.03  6551.5  505.44  6634.2  508.41  6658.8  510.41
#Mann= 4 ,-1 , 0
  3602.7     .05       0  4961.6     .07       0  5177.7     .05       0
  6658.8     .05       0
#XS Ineff= 2 , 0
       0 4936.22  487.68 5553.73       0  487.59
Permanent Ineff=
       T       T
Bank Sta=4961.6,5168.2
XS Rating Curve= 0 ,0
Exp/Cntr=0.3,0.1

Type RM Length L Ch R = 1 ,30981   ,420,420,420
BEGIN DESCRIPTION:
JACKS CREEK 30.0
END DESCRIPTION:
XS GIS Cut Line= 6
       3473094.9      10596530.3      3472111.86     10596410.95
      3471857.95     10596469.54      3471458.65     10596376.22
      3471120.11     10596354.52      3470346.27     10596367.54
#Sta/Elev= 30
  3701.6  502.73  3899.4  499.98  4107.4  494.51  4439.8  488.79  4661.4  487.01
  4794.2  484.84    4825  485.18  4855.8  483.86  4962.2  484.14  4986.3  482.68
  5071.8  485.61  5320.2  486.29  5340.5  485.83  5380.6  482.14    5451   484.8
  5471.1  484.56  5477.6  484.33  5521.2  482.89  5601.3  484.35  5641.4  486.09
  5741.5  485.69  5771.6  486.51  5791.6  485.59  5871.6   487.4  5931.6  490.51
  6141.6  497.19  6281.7  500.39  6361.7  503.89  6441.7  505.84  6477.5  507.53
#Mann= 4 ,-1 , 0
  3701.6     .05       0  5471.1     .07       0  5601.3     .05       0
  6477.5     .05       0
#XS Ineff= 2 , 0
         5206.65  486.12
Permanent Ineff=
       F       F
Bank Sta=5477.6,5601.3
XS Rating Curve= 0 ,0
Exp/Cntr=0.3,0.1

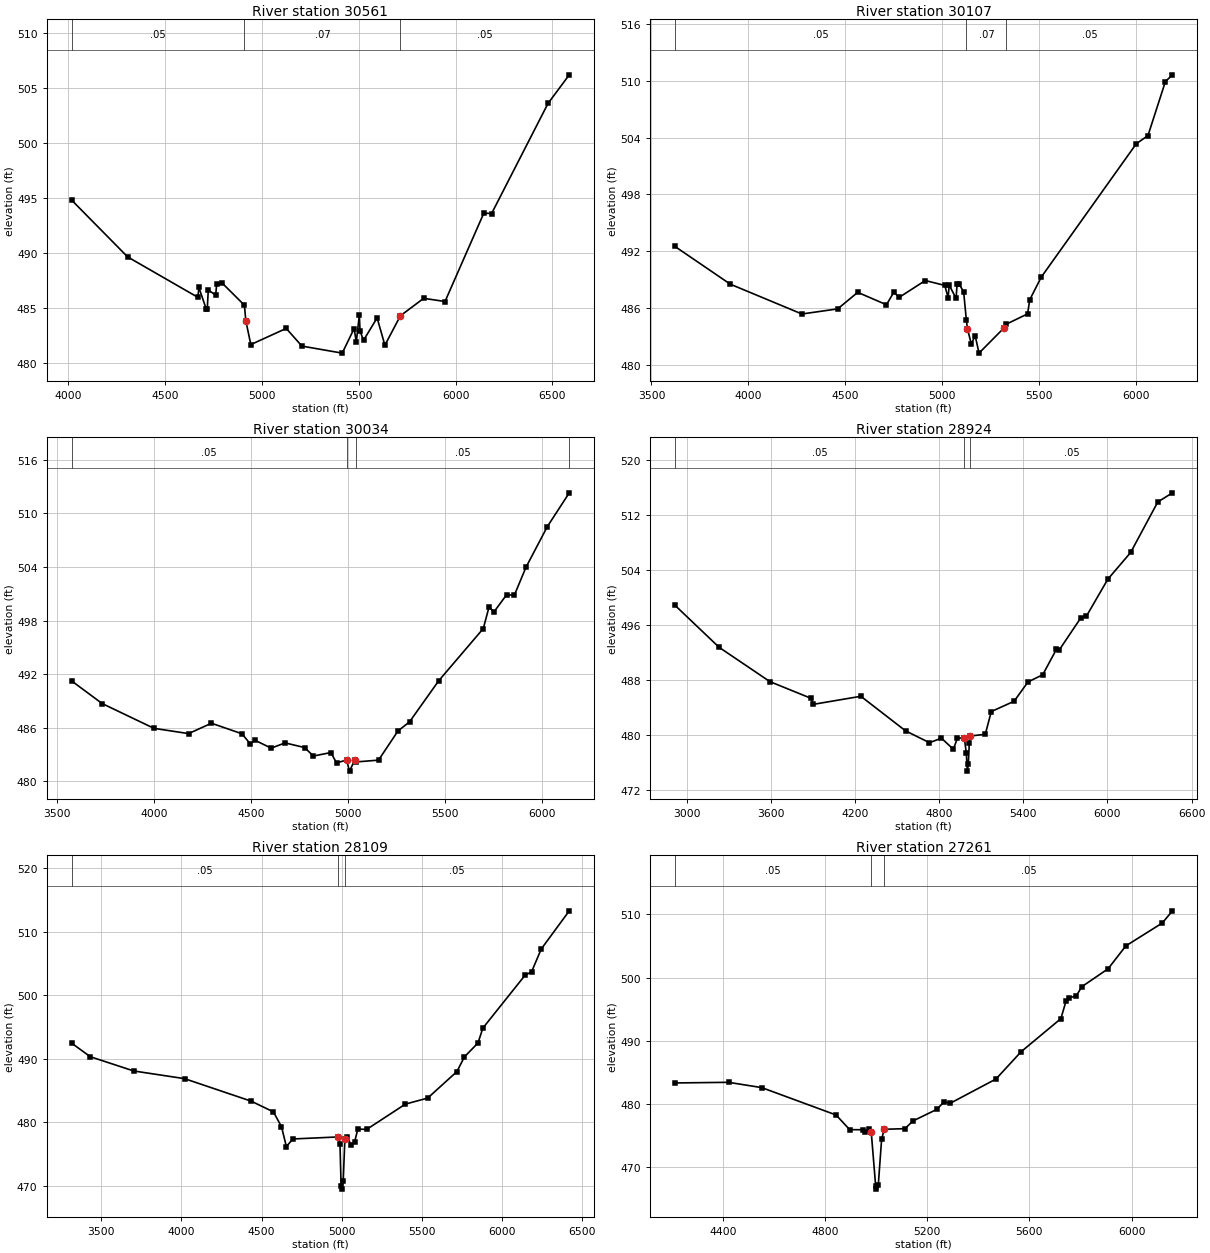
Type RM Length L Ch R = 1 ,30561   ,454,454,454
BEGIN DESCRIPTION:
JACKS CREEK 29.2
END DESCRIPTION:
XS GIS Cut Line= 6
      3472719.17     10596310.01       3471760.6     10596088.42
      3471673.36     10596086.68       3471446.8     10596189.55
      3471463.73     10596346.67       3470381.7     10596301.96
#Sta/Elev= 30
  4019.1  494.82  4308.5  489.64  4670.8  485.96  4675.9  486.86    4713  484.94
  4719.3  484.93  4724.4  486.63  4762.6  486.16  4767.7  487.16  4794.9  487.28
 4910.94  485.24  4917.9  483.84  4943.9  481.66  5126.6  483.13  5207.3  481.52
  5415.4  480.88  5476.9  483.12  5487.9  481.89  5503.7  484.34  5507.3  482.89
  5525.4  482.05  5595.4  484.09  5635.5   481.6  5715.5  484.28  5835.7  485.87
  5945.7  485.58  6145.9  493.63    6186  493.59  6477.2  503.62  6586.7  506.22
#Mann= 3 ,-1 , 0
  4019.1     .05       0 4910.94     .07       0  5715.5     .05       0
#XS Ineff= 2 , 0
         4724.43  485.89
Permanent Ineff=
       F       F
Bank Sta=4917.9,5715.5
XS Rating Curve= 0 ,0
Exp/Cntr=0.3,0.1

Type RM Length L Ch R = 1 ,30107   ,73,73,73
BEGIN DESCRIPTION:
JACKS CREEK 29.0
END DESCRIPTION:
XS GIS Cut Line= 6
      3472631.96      10596214.1      3471673.36      10595992.5
      3471586.12     10595990.76      3471359.56     10596093.63
      3471376.49     10596250.75      3470295.78     10596206.09
#Sta/Elev= 30
    3620  492.51  3906.8   488.5  4275.7  485.35  4460.2  485.89  4563.4  487.64
  4711.5  486.33  4749.6  487.65  4777.2  487.11  4911.9  488.89  5012.5  488.37
  5029.8  487.05  5034.9  488.42  5070.7  486.99  5075.9  488.57  5086.1   488.5
  5109.4  487.72 5123.76  484.68  5129.1   483.8  5149.1  482.18  5169.1  483.05
  5188.9  481.21  5319.2  483.91  5329.2  484.27  5439.3  485.36  5450.3  486.85
  5509.4  489.24  5999.8  503.36  6059.9  504.22  6149.9  509.94  6186.3  510.65
#Mann= 3 ,-1 , 0
    3620     .05       0 5123.76     .07       0  5329.2     .05       0
Bank Sta=5129.1,5319.2
XS Rating Curve= 0 ,0
Exp/Cntr=0.3,0.1

Type RM Length L Ch R = 1 ,30034   ,1110,1110,1110
BEGIN DESCRIPTION:
JACKS CREEK 29.1
END DESCRIPTION:
XS GIS Cut Line= 6
      3472556.43     10596138.58      3471597.84     10595916.98
       3471510.6     10595915.24      3471284.04     10596018.11
      3471300.97     10596175.23      3470218.96     10596130.52
#Sta/Elev= 30
  3574.6  491.25  3732.8  488.71  3999.7  485.94  4178.2  485.35  4296.4  486.51
  4453.8  485.33  4495.6  484.22  4522.4  484.59  4604.5  483.72  4675.8  484.31
  4776.7  483.79  4822.1  482.84 4912.58  483.23  4941.4  482.07  4993.2  482.39
  5008.5  481.15  5036.9  482.45  5043.3  482.18  5158.2  482.38  5258.3  485.64
  5318.3  486.67  5468.5  491.26  5698.7  497.11  5728.7  499.56  5752.7  498.94
  5818.8  500.89  5858.8  500.84  5918.9  503.97    6029  508.52  6142.2   512.3
#Mann= 4 ,-1 , 0
  3574.6     .05       0  4993.2     .07       0  5043.3     .05       0
  6142.2     .05       0
Bank Sta=4993.2,5036.9
XS Rating Curve= 0 ,0
Exp/Cntr=0.3,0.1

Type RM Length L Ch R = 1 ,28924   ,815,815,815
BEGIN DESCRIPTION:
JACKS CREEK 28.0
END DESCRIPTION:
XS GIS Cut Line= 4
      3472982.84     10596316.39      3471385.59     10595469.15
      3470913.37     10595073.32      3469809.18     10594864.98
#Sta/Elev= 30
  2915.4  498.95  3231.3  492.81  3593.8  487.81  3889.7  485.36  3901.6   484.5
  4242.1  485.68  4560.7  480.65  4730.9  478.93  4816.8  479.58  4901.4  477.97
    4930  479.57  4979.4  479.66  4993.7  477.44  5001.3  474.79    5008  475.78
  5015.1   478.9  5022.4  479.91    5129  480.14  5171.6  483.45  5334.6  484.96
  5433.6  487.77  5538.4  488.81    5636  492.51  5656.4  492.42  5810.6  497.11
  5849.7  497.33  6002.4  502.71  6165.2   506.6  6358.6  513.95  6463.3  515.28
#Mann= 3 , 0 , 0
  2915.4     .05       0  4979.4     .07       0  5022.4     .05       0
Bank Sta=4979.4,5022.4
XS Rating Curve= 0 ,0
Exp/Cntr=0.3,0.1

Type RM Length L Ch R = 1 ,28109   ,848,848,848
BEGIN DESCRIPTION:
JACKS CREEK 27.0
END DESCRIPTION:
XS GIS Cut Line= 4
      3473017.54     10595535.13      3472118.23     10595031.65
      3471111.28     10594861.51      3470069.66     10594691.38
#Sta/Elev= 30
    3314  492.49  3431.4  490.34    3702   488.1  4019.3  486.89  4435.9  483.34
    4574  481.66  4624.7  479.33  4655.1  476.19  4695.7  477.39  4979.8  477.71
  4989.8  476.53  4996.9  469.99  4999.7  469.49  5010.1  470.78  5020.2  477.33
  5035.2  477.64  5060.8   476.4  5081.1  476.93  5101.4  478.96  5156.1  478.89
  5398.3  482.88  5537.3  483.83  5719.7     488  5766.8  490.32  5851.4  492.51
  5881.8  494.85  6145.4  503.18  6185.8  503.71  6246.6  507.32  6421.3  513.32
#Mann= 3 , 0 , 0
    3314     .05       0  4979.8     .07       0  5020.2     .05       0
Bank Sta=4979.8,5020.2
XS Rating Curve= 0 ,0
Exp/Cntr=0.3,0.1

Type RM Length L Ch R = 1 ,27261   ,676,676,676
BEGIN DESCRIPTION:
JACKS CREEK 25.4
END DESCRIPTION:
XS GIS Cut Line= 3
      3472138.96     10594714.39      3471737.92     10594453.97
      3470292.63     10594190.95
#Sta/Elev= 30
  4212.4  483.28    4423  483.38  4552.8  482.54  4843.5   478.2  4896.9  475.87
  4950.2  475.86  4955.3  475.47  4970.9  475.92  4981.1  475.52  4998.4  466.94
  5001.2  466.44  5008.6  467.05  5021.7  474.33  5031.9  475.93  5113.2  476.03
  5143.7  477.24  5237.2  479.08  5265.7  480.27  5290.6  480.07    5469   483.9
  5567.4  488.23  5723.1  493.48  5743.4   496.3  5753.6  496.73  5784.1  497.13
  5804.4  498.53  5907.8  501.39  5977.2  505.02  6119.5  508.64  6159.6  510.58
#Mann= 3 , 0 , 0
  4212.4     .05       0  4981.1     .07       0  5031.9     .05       0
Bank Sta=4981.1,5031.9
XS Rating Curve= 0 ,0
Exp/Cntr=0.3,0.1

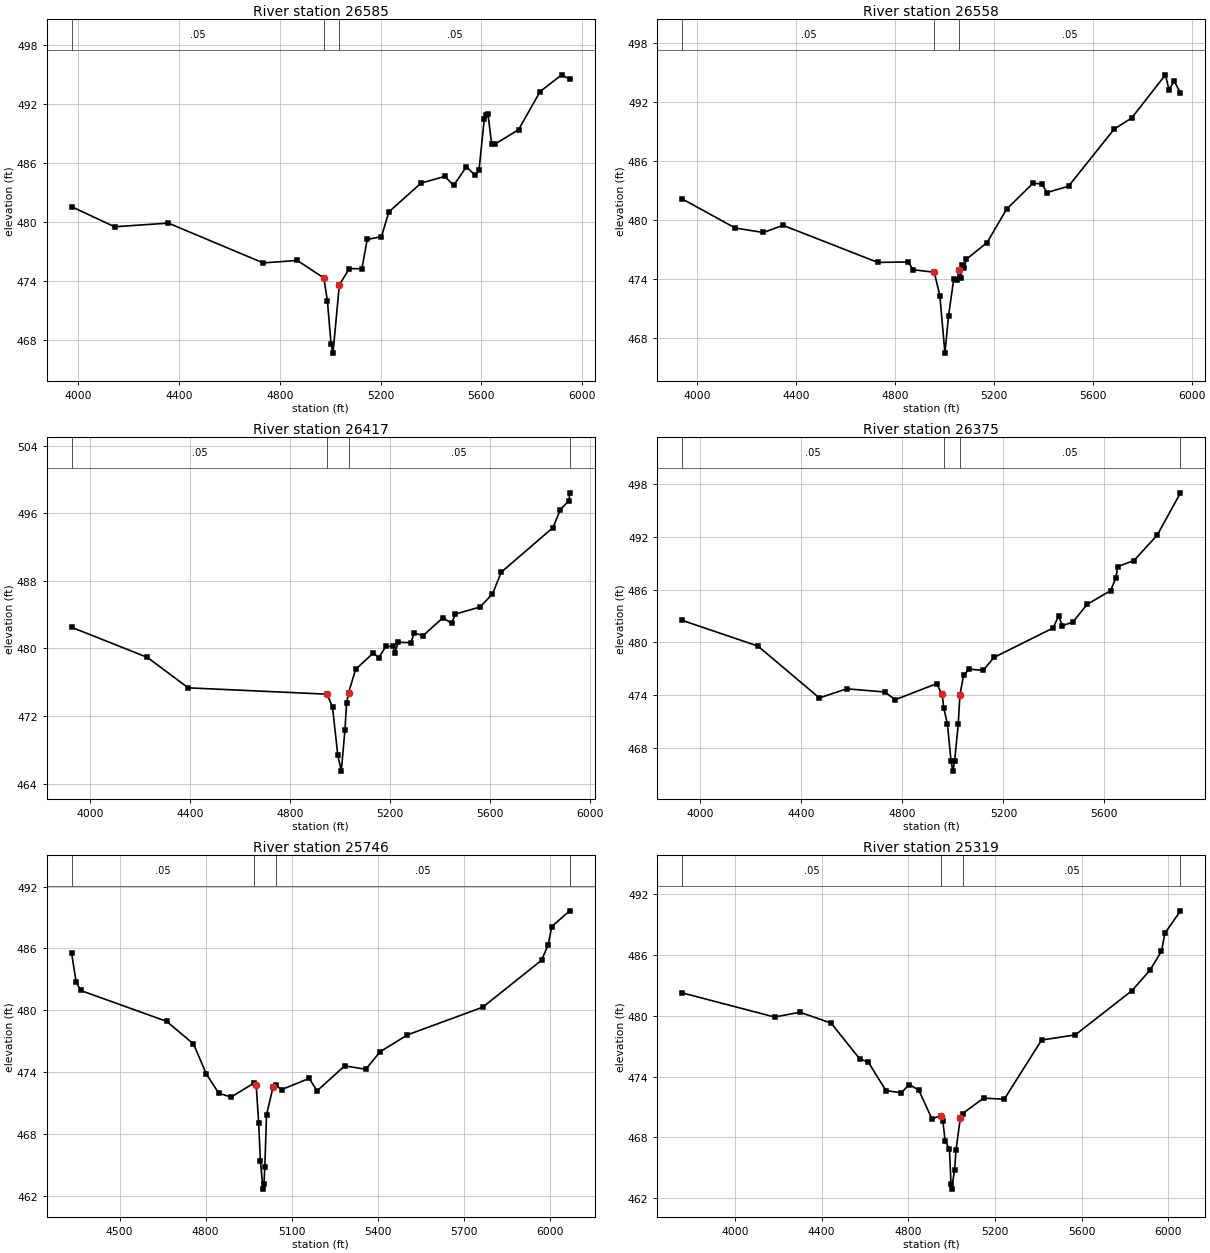
Type RM Length L Ch R = 1 ,26585   ,27,27,27
BEGIN DESCRIPTION:
JACKS CREEK 27.2
END DESCRIPTION:
XS GIS Cut Line= 3
      3472242.27     10594462.65      3471421.51     10593781.08
      3470684.76     10593245.85
#Sta/Elev= 30
  3972.8  481.55  4143.6  479.51  4357.2  479.88  4733.5  475.83  4868.9  476.08
  4974.4   474.3  4988.7  471.93    5003  467.55  5010.6  466.65    5036   473.6
  5075.5  475.25  5125.4  475.24  5146.6  478.22  5203.1   478.5  5232.4  481.02
  5360.3  483.95  5454.3  484.63  5489.8  483.72  5540.1  485.61  5575.6  484.74
  5590.3  485.25  5611.2  490.46  5619.7  490.89  5625.9  491.03  5640.5  487.94
  5655.2  487.94  5747.2  489.38    5833  493.27  5918.8  494.97  5950.3  494.53
#Mann= 3 , 0 , 0
  3972.8     .05       0  4974.4     .07       0    5036     .05       0
Bank Sta=4974.4,5036
XS Rating Curve= 0 ,0
Exp/Cntr=0.3,0.1

Type RM Length L Ch R = 1 ,26558   ,141,141,141
BEGIN DESCRIPTION:
JACKS CREEK 25.1
END DESCRIPTION:
XS GIS Cut Line= 2
      3472292.63     10594430.55      3470705.55      10593192.1
#Sta/Elev= 30
  3941.9  482.13  4155.7  479.18  4269.7  478.73  4348.4  479.46  4731.9  475.69
    4854  475.74  4874.8  474.95  4959.9  474.69  4982.5  472.31    5003  466.48
  5017.7  470.29  5038.5  473.98    5053  473.93  5059.4  474.95  5067.5  474.14
  5073.8  475.43    5082  475.11  5088.3  475.99  5173.3   477.7    5252  481.09
  5359.7  483.75  5394.9  483.64  5415.7  482.79  5502.6  483.43  5687.1  489.23
  5757.7  490.36  5894.2  494.74  5908.6  493.23  5929.5  494.11    5955  492.89
#Mann= 3 , 0 , 0
  3941.9     .05       0  4959.9     .07       0  5059.4     .05       0
Bank Sta=4959.9,5059.4
XS Rating Curve= 0 ,0
Exp/Cntr=0.3,0.1

Type RM Length L Ch R = 1 ,26417   ,42,42,42
BEGIN DESCRIPTION:
JACKS CREEK 25.2
END DESCRIPTION:
XS GIS Cut Line= 2
      3472391.55     10594328.96      3470814.48     10593105.82
#Sta/Elev= 30
  3924.6   482.5    4228  478.94  4392.1  475.33    4949  474.58  4970.3  473.02
  4991.1  467.39  5005.4  465.47  5020.1  470.37  5026.4  473.51  5034.6  474.77
  5062.9  477.52  5134.1  479.47    5155  478.87  5183.9  480.23  5212.9  480.24
  5219.2  479.46  5233.7  480.72  5283.5  480.68    5298  481.82  5333.3  481.52
  5412.1  483.62  5447.4  482.97  5461.8  484.06  5561.4   484.9  5611.2  486.46
  5646.5  489.03  5853.8  494.31  5882.8  496.42  5918.1  497.51  5920.4  498.42
#Mann= 4 ,-1 , 0
  3924.6     .05       0    4949     .07       0  5034.6     .05       0
  5920.4     .08       0
Bank Sta=4949,5034.6
XS Rating Curve= 0 ,0
Exp/Cntr=0.3,0.1

Type RM Length L Ch R = 1 ,26375   ,629,629,629
BEGIN DESCRIPTION:
JACKS CREEK 27.1
END DESCRIPTION:
XS GIS Cut Line= 3
      3472429.79     10594282.11      3471693.65      10593743.9
      3470885.99     10593057.56
#Sta/Elev= 30
  3929.3  482.51  4228.3  479.59  4471.5  473.68  4579.6  474.72  4730.2  474.36
  4771.9  473.48  4935.6   475.3  4957.6  474.08  4964.2  472.49  4978.5  470.72
  4992.8  466.51  5000.2  465.34  5007.1  466.53  5021.3  470.69  5027.9  473.98
  5042.2  476.24  5064.2  476.96  5120.2  476.82    5163   478.3  5396.9  481.65
  5418.9  483.03  5433.2  481.91  5474.9  482.32    5532  484.35  5624.3   485.9
  5645.1  487.33  5652.9  488.65  5716.6  489.33  5808.8  492.22  5901.1  497.05
#Mann= 4 ,-1 , 0
  3929.3     .05       0  4964.2     .07       0  5027.9     .05       0
  5901.1     .08       0
Bank Sta=4957.6,5027.9
XS Rating Curve= 0 ,0
Exp/Cntr=0.3,0.1

Type RM Length L Ch R = 1 ,25746   ,427,427,427
BEGIN DESCRIPTION:
JACKS CREEK 25.3
END DESCRIPTION:
XS GIS Cut Line= 2
      3472599.89     10593925.32      3471097.28     10593052.92
#Sta/Elev= 30
  4332.5  485.55  4348.5  482.75  4364.3  481.93    4664  478.94  4757.8  476.75
  4803.1  473.81  4846.1  471.97  4889.1   471.6  4969.4  472.97  4976.5  472.76
  4985.2  469.08    4991  465.44  5000.4  462.68  5003.6  463.18  5006.7  464.86
  5012.5  469.87  5035.3  472.57    5044  472.75  5065.5  472.33  5161.5  473.41
  5188.8   472.2  5284.9  474.62  5359.1   474.3  5408.2  475.98  5504.3  477.63
  5766.7  480.31  5971.9  484.86    5995  486.36  6007.6  488.13    6070  489.65
#Mann= 4 ,-1 , 0
  4332.5     .05       0  4969.4     .07       0    5044     .05       0
    6070     .08       0
Bank Sta=4976.5,5035.3
XS Rating Curve= 0 ,0
Exp/Cntr=0.3,0.1

Type RM Length L Ch R = 1 ,25319   ,69,69,69
BEGIN DESCRIPTION:
JACKS CREEK 24.0
END DESCRIPTION:
XS GIS Cut Line= 4
      3473378.63     10593396.23      3472503.64      10593250.4
      3471892.53     10593160.13      3471111.28     10593021.24
#Sta/Elev= 30
  3757.7  482.26    4183  479.88  4299.6  480.35  4443.6  479.29  4575.3  475.76
  4615.9  475.41  4696.9  472.61  4767.6   472.4  4805.2  473.21  4848.5  472.65
  4909.1  469.83  4949.6  470.12  4959.7  469.59  4969.8  467.67    4990  466.83
  4997.1  463.38  4999.9  462.88  5013.9  464.81  5020.3  466.78  5040.5  469.95
  5050.6  470.35  5148.1  471.87  5242.7  471.76  5415.3  477.61  5570.4  478.11
  5831.7  482.48  5914.4  484.48  5968.4  486.38  5984.1  488.15    6056  490.37
#Mann= 4 ,-1 , 0
  3757.7     .05       0  4949.6     .07       0  5050.6     .05       0
    6056     .08       0
#XS Ineff= 2 , 0
         4805.68  473.14
Permanent Ineff=
       F       F
Bank Sta=4949.6,5040.5
XS Rating Curve= 0 ,0
Exp/Cntr=0.3,0.1