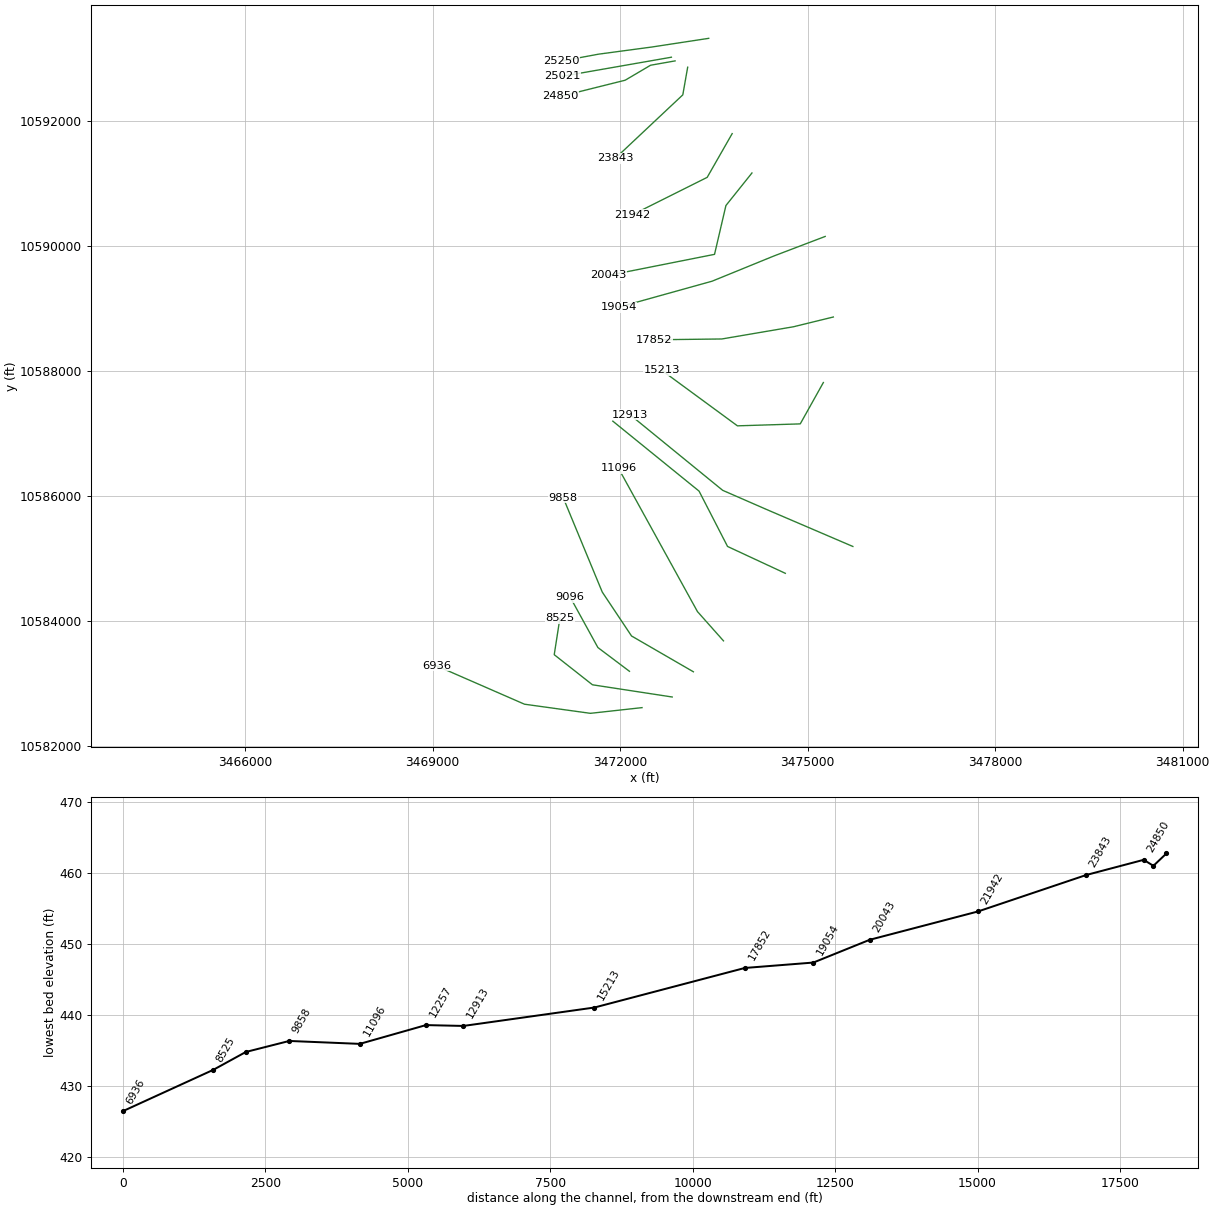
HEC-RAS study JACKS CREEK.prj: JACKS CREEK Base Level Engineering

--- JACKS CREEK.g01 (geometry) --- (continued)

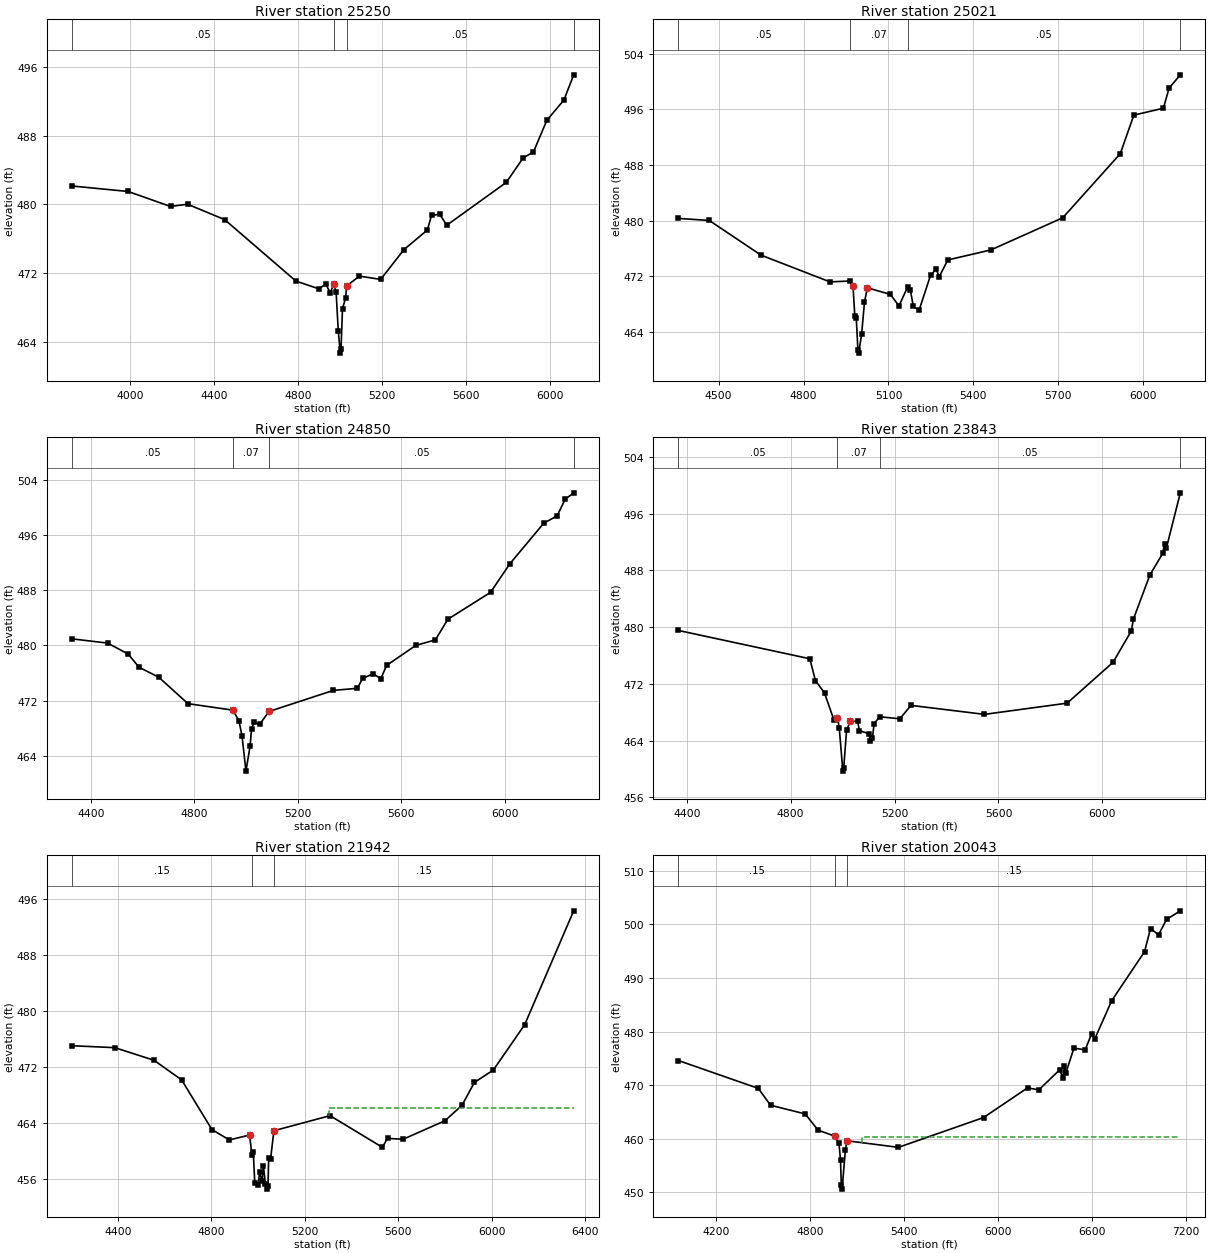
Type RM Length L Ch R = 1 ,25250   ,229,229,229
BEGIN DESCRIPTION:
JACKS CREEK 23.0
END DESCRIPTION:
XS GIS Cut Line= 4
      3473416.85     10593316.38      3472507.12     10593177.49
      3471652.95      10593062.9      3471056.38     10592951.91
#Sta/Elev= 30
  3722.2  482.15  3990.3  481.51  4192.3  479.77  4273.3  480.03  4449.8  478.24
  4788.8   471.1  4899.8  470.18    4930  470.76  4952.5  469.76  4970.4   470.8
  4980.5  469.77  4990.6  465.29  5000.4  462.72  5003.7  463.22  5010.8   467.9
  5025.4   469.1  5030.9  470.54  5091.5  471.67  5192.4  471.29  5303.4  474.76
  5414.3  477.02  5434.5  478.72    5473  478.86  5507.3  477.59    5790  482.56
  5871.5  485.44  5919.2  486.08  5983.2  489.78  6064.6  492.14  6111.1  495.07
#Mann= 4 ,-1 , 0
  3722.2     .05       0  4970.4     .07       0  5030.9     .05       0
  6111.1     .08       0
Bank Sta=4970.4,5030.9
XS Rating Curve= 0 ,0
Exp/Cntr=0.3,0.1

Type RM Length L Ch R = 1 ,25021   ,171,171,171
BEGIN DESCRIPTION:
JACKS CREEK 22.0
END DESCRIPTION:
XS GIS Cut Line= 2
      3472819.63     10593014.29      3471073.06     10592708.73
#Sta/Elev= 30
  4357.8  480.34    4467  480.04  4649.7  475.06  4893.3  471.22  4964.4  471.34
  4974.6   470.6  4981.1   466.3  4986.1  466.09  4991.9  461.48  4994.6  460.98
    5005  463.67  5015.2  468.32  5025.3  470.37  5106.5  469.42    5137  467.77
  5167.4  470.47  5177.6  469.98  5187.7  467.69    5208  467.14  5248.7  472.18
  5268.2  473.03  5279.1  471.97  5309.6  474.37  5461.8  475.81  5715.6  480.43
  5918.7  489.63  5966.7  495.18    6071  496.17  6091.3  499.06  6130.9  500.97
#Mann= 4 ,-1 , 0
  4357.8     .05       0  4964.4     .07       0  5167.4     .05       0
  6130.9     .08       0
Bank Sta=4974.6,5025.3
XS Rating Curve= 0 ,0
Exp/Cntr=0.3,0.1

Type RM Length L Ch R = 1 ,24850   ,1007,1007,1007
BEGIN DESCRIPTION:
JACKS CREEK 21.0
END DESCRIPTION:
XS GIS Cut Line= 4
      3472878.63     10592955.26      3472486.28     10592885.82
      3472080.03     10592646.24      3471040.03     10592386.23
#Sta/Elev= 30
  4325.4  480.96  4464.1  480.34  4543.6  478.76  4585.9  476.84  4661.9  475.41
  4775.1  471.58  4949.3  470.64  4972.4  469.07  4984.1  466.93  4999.4  461.82
  5015.3  465.43  5021.1  467.92  5030.5  468.89  5052.4  468.58  5088.6  470.45
  5337.7   473.5  5430.4   473.8    5451  475.24  5492.3  475.91  5520.9  475.17
  5543.8  477.12  5657.2  480.02  5732.2   480.8  5780.9   483.8  5945.8  487.68
  6020.8  491.83    6152   497.7  6203.5  498.75  6234.4  501.15  6267.5  502.08
#Mann= 4 ,-1 , 0
  4325.4     .05       0  4949.3     .07       0  5088.6     .05       0
  6267.5     .05       0
Bank Sta=4949.3,5088.6
XS Rating Curve= 0 ,0
Exp/Cntr=0.3,0.1

Type RM Length L Ch R = 1 ,23843   ,1901,1901,1901
BEGIN DESCRIPTION:
JACKS CREEK 20.0
END DESCRIPTION:
XS GIS Cut Line= 3
      3473080.03     10592854.58      3473001.91     10592411.86
      3471921.41     10591396.45
#Sta/Elev= 30
  4367.8  479.52  4873.8  475.53  4895.3  472.46  4930.5   470.7  4966.1  466.94
  4980.3  467.24  4987.1  465.74    5001  459.69  5004.3  460.19  5015.4  465.46
  5029.6  466.72  5057.9  466.71  5064.8  465.38  5100.4  464.99  5107.3  463.95
  5114.6   464.3  5121.4   466.4  5142.9  467.35  5220.6  467.07  5263.1  468.96
  5545.9  467.69  5864.3  469.27  6041.1  475.03  6111.9  479.48  6119.2  481.09
  6182.8  487.33  6232.1  490.37  6239.4  491.77  6246.3  491.12  6300.1  498.92
#Mann= 4 ,-1 , 0
  4367.8     .05       0  4980.3     .07       0  5142.9     .05       0
  6300.1     .05       0
Bank Sta=4980.3,5029.6
XS Rating Curve= 0 ,0
Exp/Cntr=0.3,0.1

Type RM Length L Ch R = 1 ,21942   ,1899,1899,1899
BEGIN DESCRIPTION:
JACKS CREEK 19.0
END DESCRIPTION:
XS GIS Cut Line= 3
      3473792.12     10591791.66      3473392.11     10591091.64
      3472192.09     10590491.64
#Sta/Elev= 30
  4202.3  475.04  4386.6  474.76  4554.3  472.96  4672.4  470.16    4802  463.07
  4876.8  461.58  4963.2  462.29  4973.3  459.43    4979  459.85  4985.5  455.43
  5000.6  455.15  5005.7  456.99  5016.9   455.7  5022.5  457.89  5030.9  455.33
    5039  454.56  5042.3  455.06  5044.9  458.99  5053.3  458.88  5067.2   462.9
  5307.6  465.05  5531.2  460.54  5553.6   461.8  5620.7  461.69  5799.6  464.33
  5872.2  466.53  5925.3  469.79  6006.4  471.57  6140.6  478.05  6350.2   494.3
#Mann= 3 ,-1 , 0
  4202.3     .15       0  4973.3     .12       0  5067.2     .15       0
#XS Ineff= 2 , 0
       0                 5302.62       0  466.12
Permanent Ineff=
       F       T
Bank Sta=4963.2,5067.2
XS Rating Curve= 0 ,0
Exp/Cntr=0.3,0.1

Type RM Length L Ch R = 1 ,20043   ,989,989,989
BEGIN DESCRIPTION:
JACKS CREEK 17.0
END DESCRIPTION:
XS GIS Cut Line= 4
      3474108.67     10591161.86      3473692.01     10590641.03
      3473509.72     10589859.78      3471805.58     10589521.55
#Sta/Elev= 30
  3959.3  474.59  4469.7  469.39  4548.2  466.24  4769.4  464.62  4851.6   461.6
  4957.7  460.47  4985.1   459.2  4995.1  455.94  5000.2  451.36  5005.3  450.58
  5026.1  457.93  5036.4  459.61    5365  458.38  5908.6  463.94  6190.7   469.5
  6261.7   469.1  6394.6  472.84    6415  471.42  6425.5   473.5  6435.4  472.35
  6486.4  476.91  6557.7  476.58  6598.5  479.52  6618.9  478.59  6727.4  485.76
  6937.2   494.9  6975.7  499.24  7026.7  498.06  7077.7  500.94  7165.9  502.54
#Mann= 3 ,-1 , 0
  3959.3     .15       0  4957.7     .12       0  5036.4     .15       0
#XS Ineff= 2 , 0
       0                  5130.3       0  460.37
Permanent Ineff=
       F       T
Bank Sta=4957.7,5036.4
XS Rating Curve= 0 ,0
Exp/Cntr=0.3,0.1

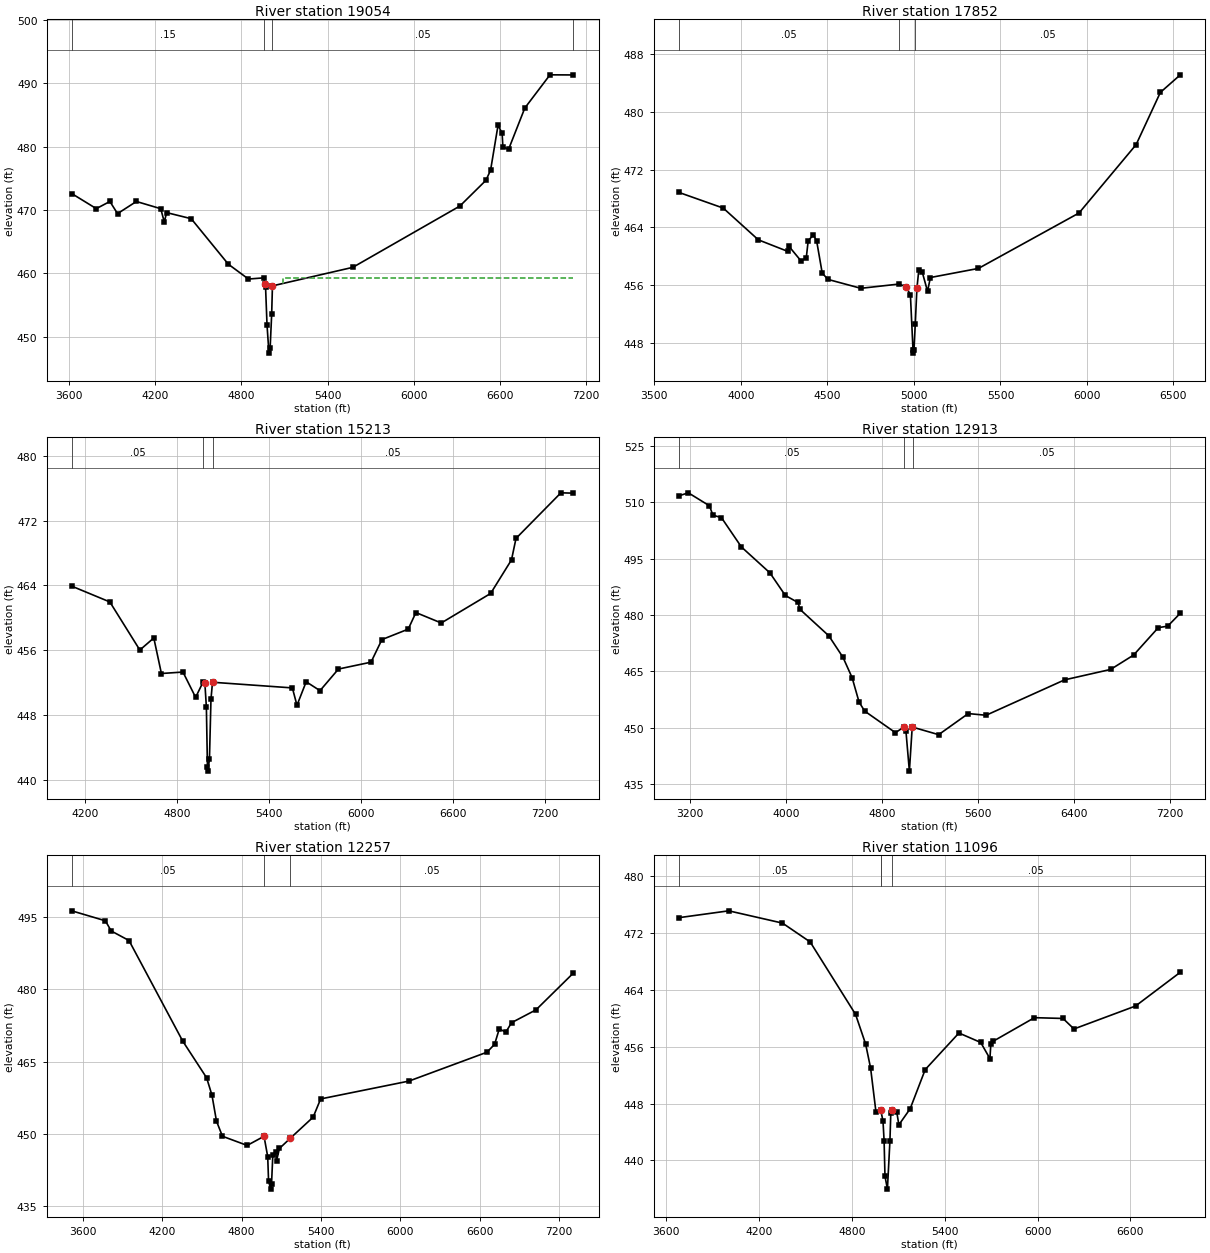
Type RM Length L Ch R = 1 ,19054   ,1202,1202,1202
BEGIN DESCRIPTION:
JACKS CREEK 15.0
END DESCRIPTION:
XS GIS Cut Line= 4
      3475280.55     10590146.24      3474460.24     10589833.74
      3473470.66     10589430.09      3471975.23     10589013.97
#Sta/Elev= 30
  3616.4   472.6  3787.6  470.22  3882.3  471.35  3935.8  469.43  4067.1  471.35
    4237  470.21  4261.7  468.11  4278.2  469.59  4449.4  468.63  4708.2  461.44
  4848.6  459.09  4956.6  459.28  4962.6   458.3    4968  457.82  4978.2   451.8
  4991.7  447.38  4999.8  448.13  5010.6  453.55    5016  458.01  5576.4  460.94
  6323.1  470.63  6504.6  474.69  6537.2   476.3  6589.1  483.39  6617.7  482.15
  6622.8  480.04  6662.3  479.57  6775.9  486.12  6951.6  491.37  7115.2  491.35
#Mann= 4 ,-1 , 0
  3616.4     .15       0  4956.6     .07       0    5016     .05       0
  7115.2     .05       0
#XS Ineff= 2 , 0
       0                 5087.02       0  459.19
Permanent Ineff=
       F       T
Bank Sta=4962.6,5016
XS Rating Curve= 0 ,0
Exp/Cntr=0.3,0.1

Type RM Length L Ch R = 1 ,17852   ,2639,2639,2639
BEGIN DESCRIPTION:
JACKS CREEK 14.0
END DESCRIPTION:
XS GIS Cut Line= 4
      3475410.81     10588857.19      3474772.74     10588700.92
      3473626.91     10588505.61      3472546.67      10588492.6
#Sta/Elev= 30
    3640  468.85  3897.9  466.67  4100.8  462.28  4272.4  460.67  4277.5  461.39
  4348.3  459.34  4377.8  459.81  4388.9  462.16  4419.3  462.97    4438  462.09
    4470  457.68  4503.2  456.81  4693.2  455.58  4914.4  456.17  4956.9  455.78
  4979.7  454.63  4994.5  447.12  4997.3  446.62  5000.5  447.12  5007.7  450.64
 5017.15  455.56    5028  458.08  5048.2  457.81  5078.7  455.16    5095  457.07
  5372.9  458.33  5954.1  465.99  6284.1  475.44  6424.2  482.66  6539.6  485.09
#Mann= 3 ,-1 , 0
    3640     .05       0  4914.4     .07       0  5007.7     .05       0
#XS Ineff= 2 , 0
       0                 5049.21       0  457.38
Permanent Ineff=
       T       T
Bank Sta=4956.9,5017.15
XS Rating Curve= 0 ,0
Exp/Cntr=0.3,0.1

Type RM Length L Ch R = 1 ,15213   ,2300,2300,2300
BEGIN DESCRIPTION:
JACKS CREEK 13.0
END DESCRIPTION:
XS GIS Cut Line= 4
      3475251.13     10587808.26      3474881.36     10587146.83
      3473876.15     10587115.58      3472662.58     10588006.22
#Sta/Elev= 30
  4115.3  463.91  4363.5  461.96  4558.9  456.02  4649.9  457.51  4699.4  453.12
  4839.9   453.3  4922.4  450.17  4972.4  452.13  4982.4  451.99  4992.4  448.97
  4999.4  441.56  5002.1  441.06  5012.4  442.51  5022.4  449.97  5032.4  452.04
  5552.7  451.34  5582.7  449.19  5642.7   452.1  5732.7     451  5852.8  453.67
  6065.1  454.52  6136.1  457.31  6307.4   458.6  6357.6  460.65  6522.7  459.36
  6844.5  463.01  6980.4  467.16  7009.7  469.81  7302.2  475.44  7384.1   475.4
#Mann= 3 ,-1 , 0
  4115.3     .05       0  4972.4     .07       0  5032.4     .05       0
Bank Sta=4982.4,5032.4
XS Rating Curve= 0 ,0
Exp/Cntr=0.3,0.1

Type RM Length L Ch R = 1 ,12913   ,656,656,656
BEGIN DESCRIPTION:
JACKS CREEK 12.0
END DESCRIPTION:
XS GIS Cut Line= 4
      3475723.29     10585185.29      3474356.07     10585771.24
      3473639.93     10586083.74      3472156.33     10587294.04
#Sta/Elev= 30
  3106.6  511.68  3187.8   512.5  3363.7  509.05  3392.7  506.55  3463.5  505.91
  3630.1   498.1  3867.8  491.21  3996.6  485.19  4101.7  483.33  4119.7  481.47
  4359.2  474.46  4477.1  468.75  4553.2  463.34  4611.2  456.85    4658  454.44
  4914.8  448.69 4989.82  450.32  5002.1  449.13  5030.8  438.47  5054.4  450.17
  5059.9  450.15  5274.9  448.17  5521.7  453.78  5670.4  453.33  6325.2  462.75
  6708.6  465.52  6900.3  469.34  7106.4  476.64  7184.7  477.03  7290.1  480.48
#Mann= 3 ,-1 , 0
  3106.6     .05       0 4989.82     .07       0  5059.9     .05       0
Bank Sta=4989.82,5054.4
XS Rating Curve= 0 ,0
Exp/Cntr=0.3,0.1

Type RM Length L Ch R = 1 ,12257   ,1161,1161,1161
BEGIN DESCRIPTION:
JACKS CREEK 10.0
END DESCRIPTION:
XS GIS Cut Line= 4
      3474642.55      10584755.6      3473718.05      10585185.3
      3473262.32     10586070.72      3471882.14     10587190.49
#Sta/Elev= 30
    3516  496.23  3770.1  494.17  3814.2  492.06  3948.8  490.08  4354.6  469.26
  4535.5  461.65    4576  458.04  4610.1  452.67  4655.1  449.54  4842.1  447.64
  4969.5  449.53  4997.3  445.32  5003.7   440.3  5019.2  438.59  5026.2  439.66
    5036  445.69  5058.2  446.27  5063.8  444.44    5086  447.02    5169  449.15
  5340.8   453.5  5397.4  457.27  6065.2  460.97    6655  466.95  6712.5  468.59
  6747.7  471.77  6797.3   471.1  6840.4  473.06  7025.3  475.72  7308.6  483.36
#Mann= 3 , 0 , 0
    3516     .05       0  4969.5     .07       0    5169     .05       0
Bank Sta=4969.5,5169
XS Rating Curve= 0 ,0
Exp/Cntr=0.3,0.1

Type RM Length L Ch R = 1 ,11096   ,1238,1238,1238
BEGIN DESCRIPTION:
JACKS CREEK 7.0
END DESCRIPTION:
XS GIS Cut Line= 3
      3473652.93      10583674.9      3473236.28     10584143.63
      3471973.27     10586435.29
#Sta/Elev= 30
  3679.3  474.18  4003.4  475.15  4350.9  473.42  4529.7  470.77  4823.2  460.57
  4888.5  456.38  4920.7  452.98    4955  446.85    4986  447.08  5000.7  445.54
  5007.8  442.78  5013.5  437.77  5029.3  435.95  5045.6  442.78  5051.3  446.74
  5057.8  447.05  5089.2  446.87  5103.4  445.01  5176.3  447.27  5273.7  452.79
  5491.7  457.94  5632.5  456.61  5692.1  454.33  5697.9  456.37  5713.9  456.79
  5979.9   460.1  6164.5  459.99  6235.5  458.51  6633.5  461.74  6923.1   466.5
#Mann= 4 ,-1 , 0
  3679.3     .05       0    4986     .16       0    4986     .07       0
  5057.8     .05       0
Bank Sta=4986,5057.8
XS Rating Curve= 0 ,0
Exp/Cntr=0.3,0.1

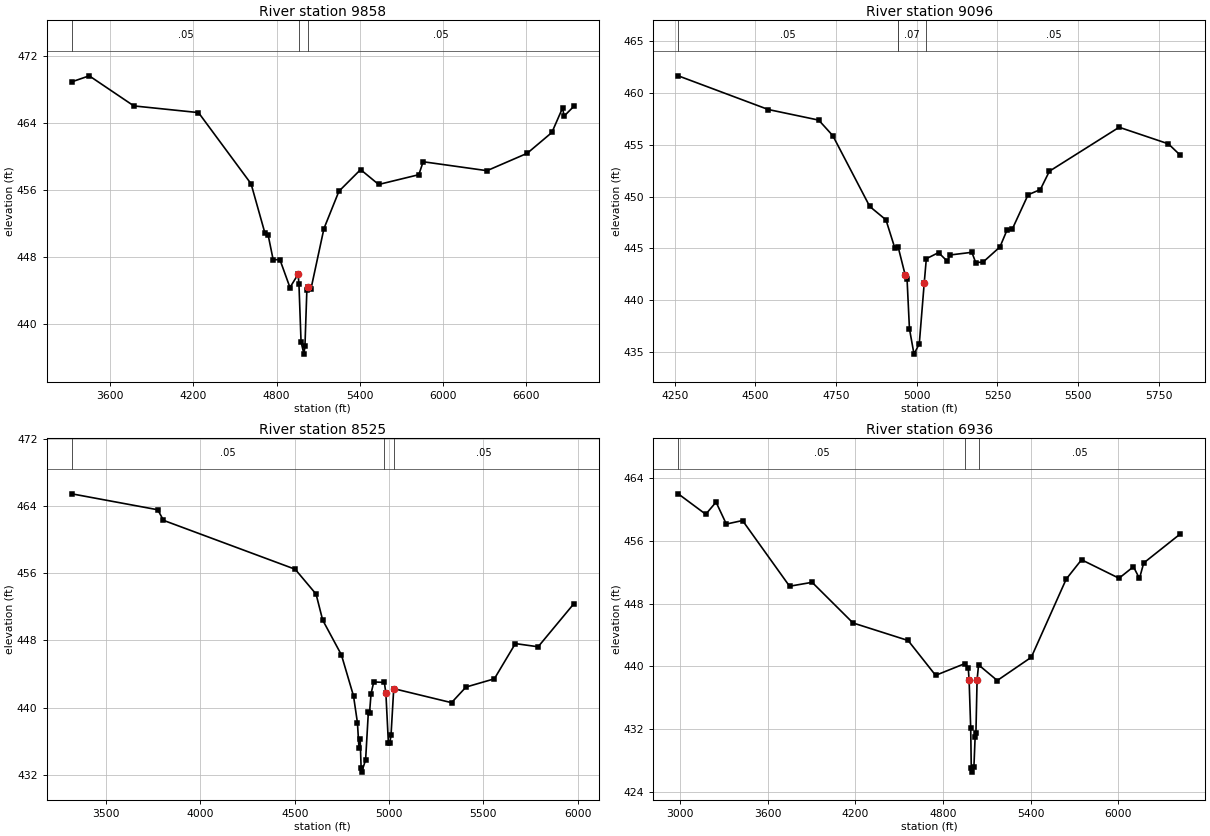
Type RM Length L Ch R = 1 ,9858    ,762,762,762
BEGIN DESCRIPTION:
JACKS CREEK 5.0
END DESCRIPTION:
XS GIS Cut Line= 4
      3473171.16      10583180.1       3472181.6     10583753.01
      3471712.85     10584456.13      3471087.85     10585966.54
#Sta/Elev= 30
  3322.2  468.94  3448.2  469.66  3770.2  466.06  4236.6  465.26  4616.1  456.74
  4716.4  450.82  4739.3  450.61  4775.3  447.67  4824.6  447.65  4896.7  444.33
  4955.6  445.92  4961.6  444.71  4976.7  437.85  4997.4  436.36  5004.8   437.3
  5018.7  444.02  5027.7  444.41  5048.8   444.2  5141.9  451.38  5250.1  455.85
  5406.4  458.44  5536.7  456.66  5826.7  457.83  5857.8  459.38  6318.6  458.31
  6608.6  460.39  6786.7  462.88  6863.8  465.81  6875.1  464.84  6945.3  466.01
#Mann= 3 ,-1 , 0
  3322.2     .05       0  4961.6     .07       0  5027.7     .05       0
Bank Sta=4955.6,5027.7
XS Rating Curve= 0 ,0
Exp/Cntr=0.3,0.1

Type RM Length L Ch R = 1 ,9096    ,571,571,571
BEGIN DESCRIPTION:
JACKS CREEK 5.1
END DESCRIPTION:
XS GIS Cut Line= 3
       3472148.5     10583187.63      3471643.27     10583567.86
      3471198.28     10584377.16
#Sta/Elev= 30
  4260.9  461.65    4540   458.4  4696.2  457.38  4739.9  455.88  4854.4  449.05
  4904.6  447.76  4932.1  445.04  4942.5  445.13  4964.3  442.43    4970  442.04
  4977.4  437.26  4991.5  434.81  5007.9  435.81  5023.1  441.63  5029.7  444.01
  5067.5   444.6    5095  443.76    5103  444.37  5170.8  444.63  5182.8  443.64
  5205.7  443.69  5257.9  445.15  5279.7  446.77  5295.8  446.85  5345.1  450.18
    5383  450.68  5411.1  452.45  5627.3  456.69  5779.8  455.09  5816.8  453.99
#Mann= 4 ,-1 , 0
  4260.9     .05       0  4942.5     .12       0  4942.5     .07       0
  5029.7     .05       0
Bank Sta=4964.3,5023.1
XS Rating Curve= 0 ,0
Exp/Cntr=0.3,0.1

Type RM Length L Ch R = 1 ,8525    ,1589,1589,1589
BEGIN DESCRIPTION:
JACKS CREEK 4.0
END DESCRIPTION:
XS GIS Cut Line= 4
      3472832.65     10582776.44       3471556.6     10582971.76
      3470944.62     10583453.53      3471035.54     10584038.02
#Sta/Elev= 30
  3318.2  465.47    3774  463.57  3804.3  462.31  4502.4  456.48  4613.1  453.52
    4648  450.43  4747.4  446.28  4811.6  441.38  4832.4  438.19  4840.5  435.18
  4846.8  436.28  4851.9   432.8  4854.6   432.3  4875.7  433.75  4890.2  439.43
  4896.5  439.36  4904.6  441.66    4919  443.05  4975.1  442.99  4983.2  441.69
  4996.6  435.74    5004  435.79  5010.4  436.69  5024.8  442.25  5331.1  440.58
  5407.8  442.44  5558.1  443.42  5669.5  447.62  5790.2  447.24  5979.5  452.37
#Mann= 3 ,-1 , 0
  3318.2     .05       0  4975.1     .07       0  5024.8     .05       0
Bank Sta=4983.2,5024.8
XS Rating Curve= 0 ,0
Exp/Cntr=0.3,0.1

Type RM Length L Ch R = 1 ,6936    ,1224,1224,1224
BEGIN DESCRIPTION:
JACKS CREEK 3.0
END DESCRIPTION:
XS GIS Cut Line= 4
      3472349.22     10582606.35      3471523.73     10582515.21
      3470469.04     10582661.04      3469057.83     10583276.98
#Sta/Elev= 30
  2988.2  462.02  3176.4  459.41  3246.9  460.96  3317.3  458.16    3428  458.61
  3749.9  450.22  3904.2  450.72  4183.8  445.53  4560.8  443.29  4749.1  438.84
  4949.2  440.34  4972.6  439.75  4978.3  438.21  4989.2  432.06    4993  426.98
  4995.8  426.48    5011  427.08  5019.4  430.98  5024.9  431.54  5032.8  438.25
  5042.9  440.18  5170.8  438.18  5403.8  441.15  5642.9  451.14  5747.4   453.6
  6003.9  451.24  6102.5  452.71  6143.8  451.21  6172.7  453.19  6423.2   456.9
#Mann= 3 ,-1 , 0
  2988.2     .05       0  4949.2     .07       0  5042.9     .05       0
Bank Sta=4978.3,5032.8
XS Rating Curve= 0 ,0
Exp/Cntr=0.3,0.1