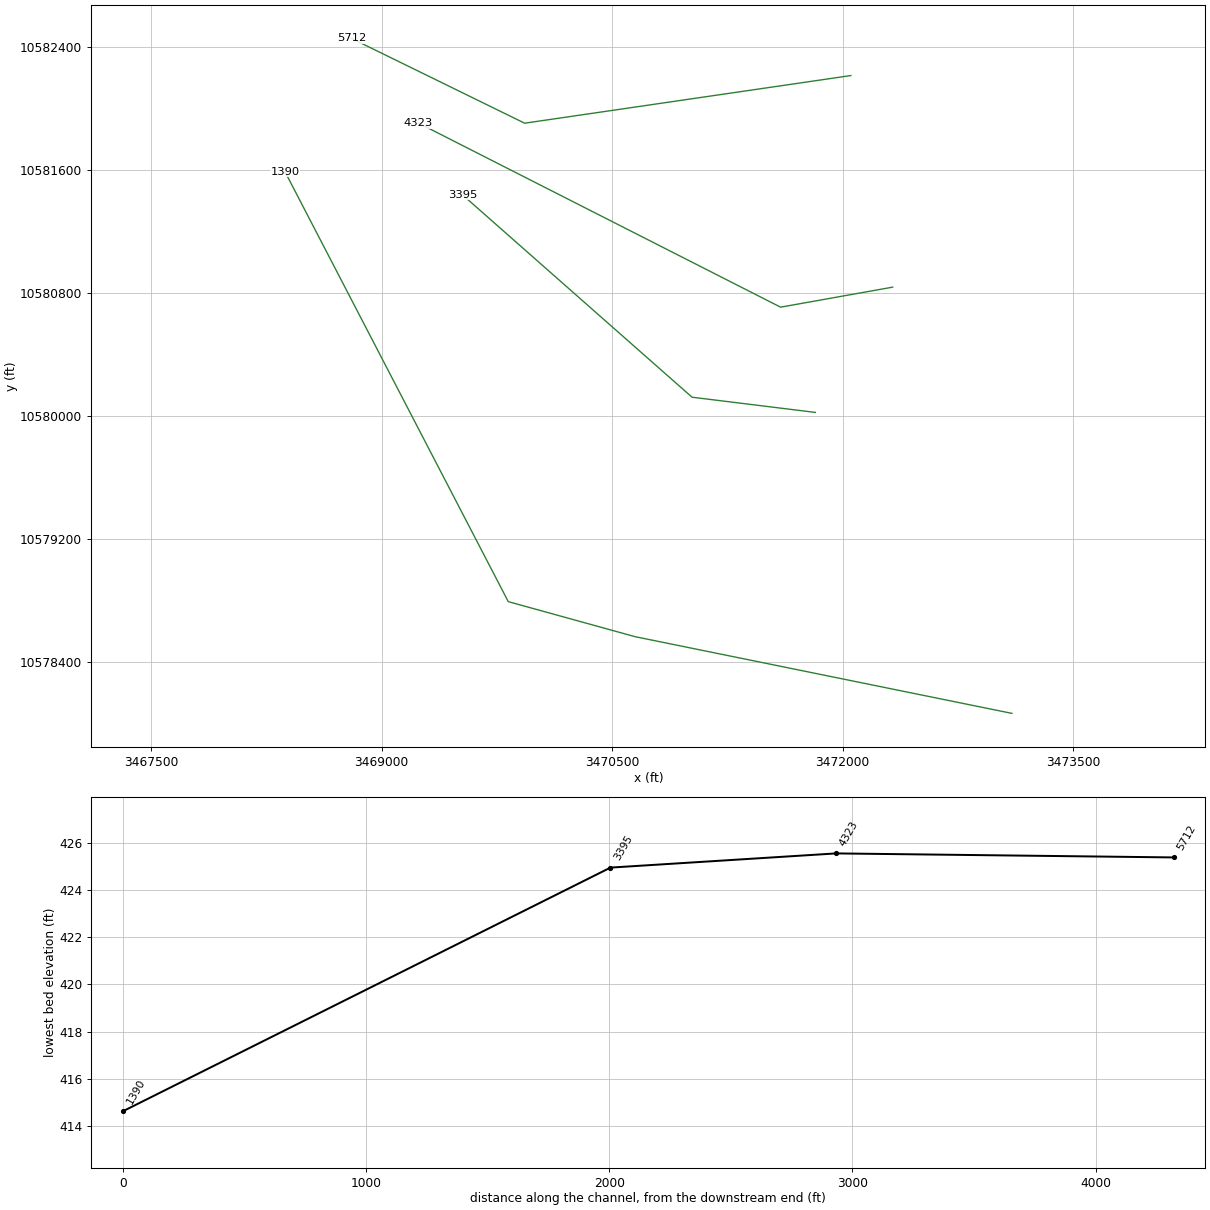
HEC-RAS study JACKS CREEK.prj: JACKS CREEK Base Level Engineering

--- JACKS CREEK.g01 (geometry) --- (continued)

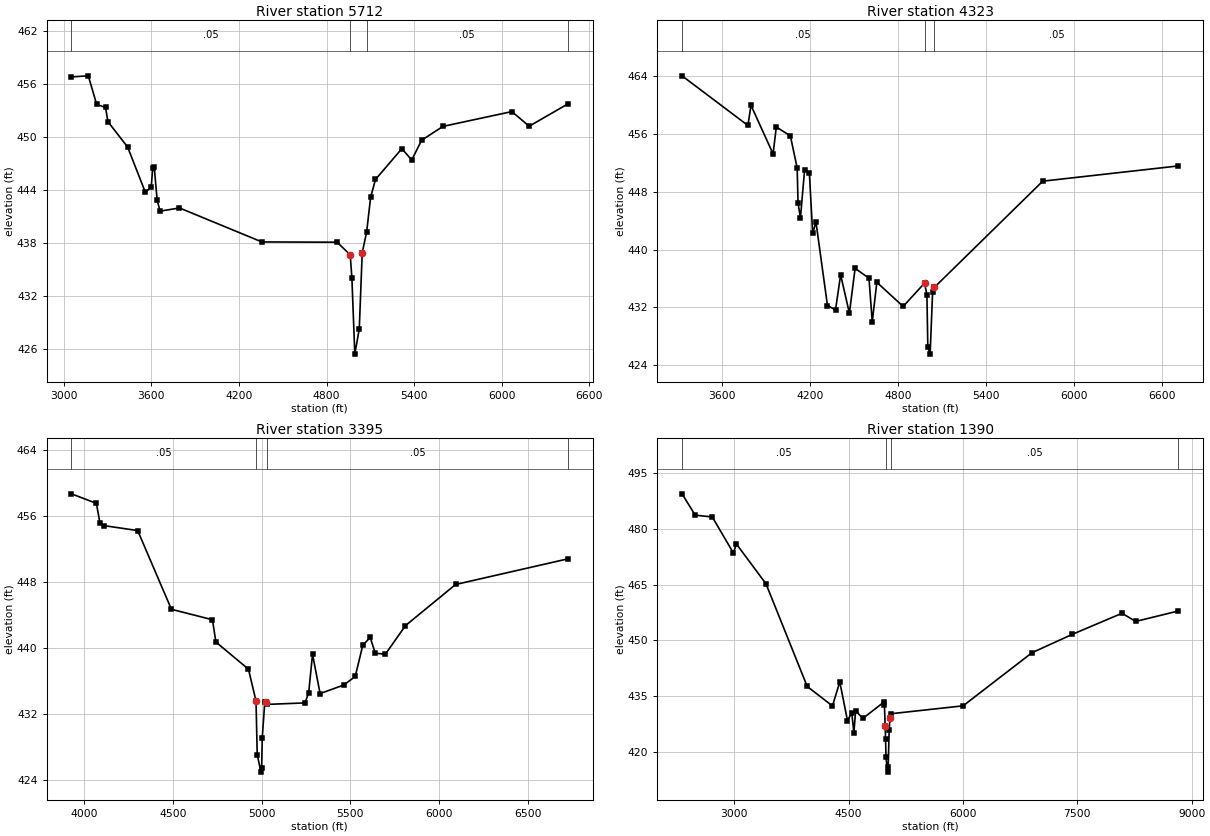
Type RM Length L Ch R = 1 ,5712    ,1389,1389,1389
BEGIN DESCRIPTION:
JACKS CREEK 2.1
END DESCRIPTION:
XS GIS Cut Line= 3
      3472052.78     10582213.02      3469930.41     10581903.13
      3468802.78     10582455.22
#Sta/Elev= 30
    3053  456.78  3168.1   456.9  3225.5  453.66  3286.1  453.32    3303   451.7
  3437.7  448.83    3559   443.7  3599.4  444.32  3609.5  446.47  3619.6  446.61
  3639.8  442.81    3660  441.57  3792.9  441.93  4357.4  438.08  4872.8  438.05
  4962.3  436.62  4973.8  433.99  4993.8  425.37  5024.4  428.23  5044.6  436.86
  5074.9  439.21  5102.2  443.15  5135.5  445.16  5316.2  448.65  5383.8  447.36
  5451.3   449.6  5597.4  451.17    6070  452.85  6188.1  451.19  6453.4  453.72
#Mann= 4 ,-1 , 0
    3053     .05       0  4962.3     .07       0  5074.9     .05       0
  6453.4     .05       0
Bank Sta=4962.3,5044.6
XS Rating Curve= 0 ,0
Exp/Cntr=0.3,0.1

Type RM Length L Ch R = 1 ,4323    ,928,928,928
BEGIN DESCRIPTION:
JACKS CREEK 2.0
END DESCRIPTION:
XS GIS Cut Line= 3
      3472324.82     10580836.34      3471595.66     10580706.13
      3469238.92     10581904.03
#Sta/Elev= 30
  3325.8  464.06  3774.8  457.19  3795.8  459.98  3946.5  453.25  3968.5  456.98
  4064.3  455.75  4110.8   451.3  4116.4   446.5    4133  444.38  4160.9  450.96
  4193.9  450.62  4216.3  442.25  4238.7  443.85  4317.3  432.26  4372.2  431.66
    4407  436.52  4466.8   431.2  4505.7  437.41  4600.3  436.05  4622.6     430
  4653.8  435.48  4833.3  432.14  4979.1  435.37  4995.2  433.78  5001.5  426.47
  5017.2  425.54  5034.1  434.08  5046.4  434.79  5785.1  449.48  6710.2  451.59
#Mann= 3 , 0 , 0
  3325.8     .05       0  4979.1     .07       0  5046.4     .05       0
Bank Sta=4979.1,5046.4
XS Rating Curve= 0 ,0
Exp/Cntr=0.3,0.1

Type RM Length L Ch R = 1 ,3395    ,2005,2005,2005
BEGIN DESCRIPTION:
JACKS CREEK 2.2
END DESCRIPTION:
XS GIS Cut Line= 3
      3471821.65     10580021.37      3471019.55     10580120.33
      3469524.73     10581438.07
#Sta/Elev= 30
  3926.6  458.71  4067.2  457.55  4087.4  455.14  4107.5  454.86  4300.1  454.25
  4490.4   444.7  4722.1  443.43  4741.2  440.73  4925.2  437.43  4967.9  433.56
  4974.6  427.03  4996.1  424.94  4999.4  425.44    5003  429.09  5017.3   433.5
  5024.7  433.43  5031.5  433.16    5244  433.34  5264.9  434.57  5286.7  439.24
  5329.3  434.47    5464  435.52  5527.6  436.55  5570.3  440.34  5612.1  441.28
  5640.5  439.38  5697.4  439.24  5811.2  442.72    6094  447.71  6727.5  450.82
#Mann= 4 ,-1 , 0
  3926.6     .05       0  4967.9     .07       0  5031.5     .05       0
  6727.5     .05       0
#XS Ineff= 2 , 0
       0                 5294.64       0  437.36
Permanent Ineff=
       F       T
Bank Sta=4967.9,5024.7
XS Rating Curve= 0 ,0
Exp/Cntr=0.3,0.1

Type RM Length L Ch R = 1 ,1390    ,0,0,0
BEGIN DESCRIPTION:
JACKS CREEK 1.0
END DESCRIPTION:
XS GIS Cut Line= 4
      3473100.81     10578063.24      3470648.58     10578562.36
      3469823.93     10578790.23      3468370.72     10581588.19
#Sta/Elev= 30
  2315.3  489.36  2487.7  483.63    2712  483.15  2988.4  473.49  3028.3  475.89
  3416.1  465.21    3957  437.64  4288.2  432.41  4384.3  438.87  4485.4  428.45
  4541.1  430.63  4569.3   425.2  4591.7   431.1  4687.7  429.08  4959.4  433.39
  4969.8  432.69  4979.5  426.91  4984.7  423.61  4990.5  418.63    5011  414.64
    5019   415.9    5032  425.95  5042.4  429.24  5052.8  430.31  6001.7  432.44
    6906  446.71  7432.8  451.62  8086.4  457.29  8265.5   455.1  8826.2  457.91
#Mann= 4 ,-1 , 0
  2315.3     .05       0  4984.7     .07       0  5052.8     .05       0
  8826.2     .05       0
Bank Sta=4979.5,5042.4
XS Rating Curve= 0 ,0
Exp/Cntr=0.3,0.1

Chan Stop Cuts=-1
Use User Specified Reach Order=0
Composite Channel Slope=5