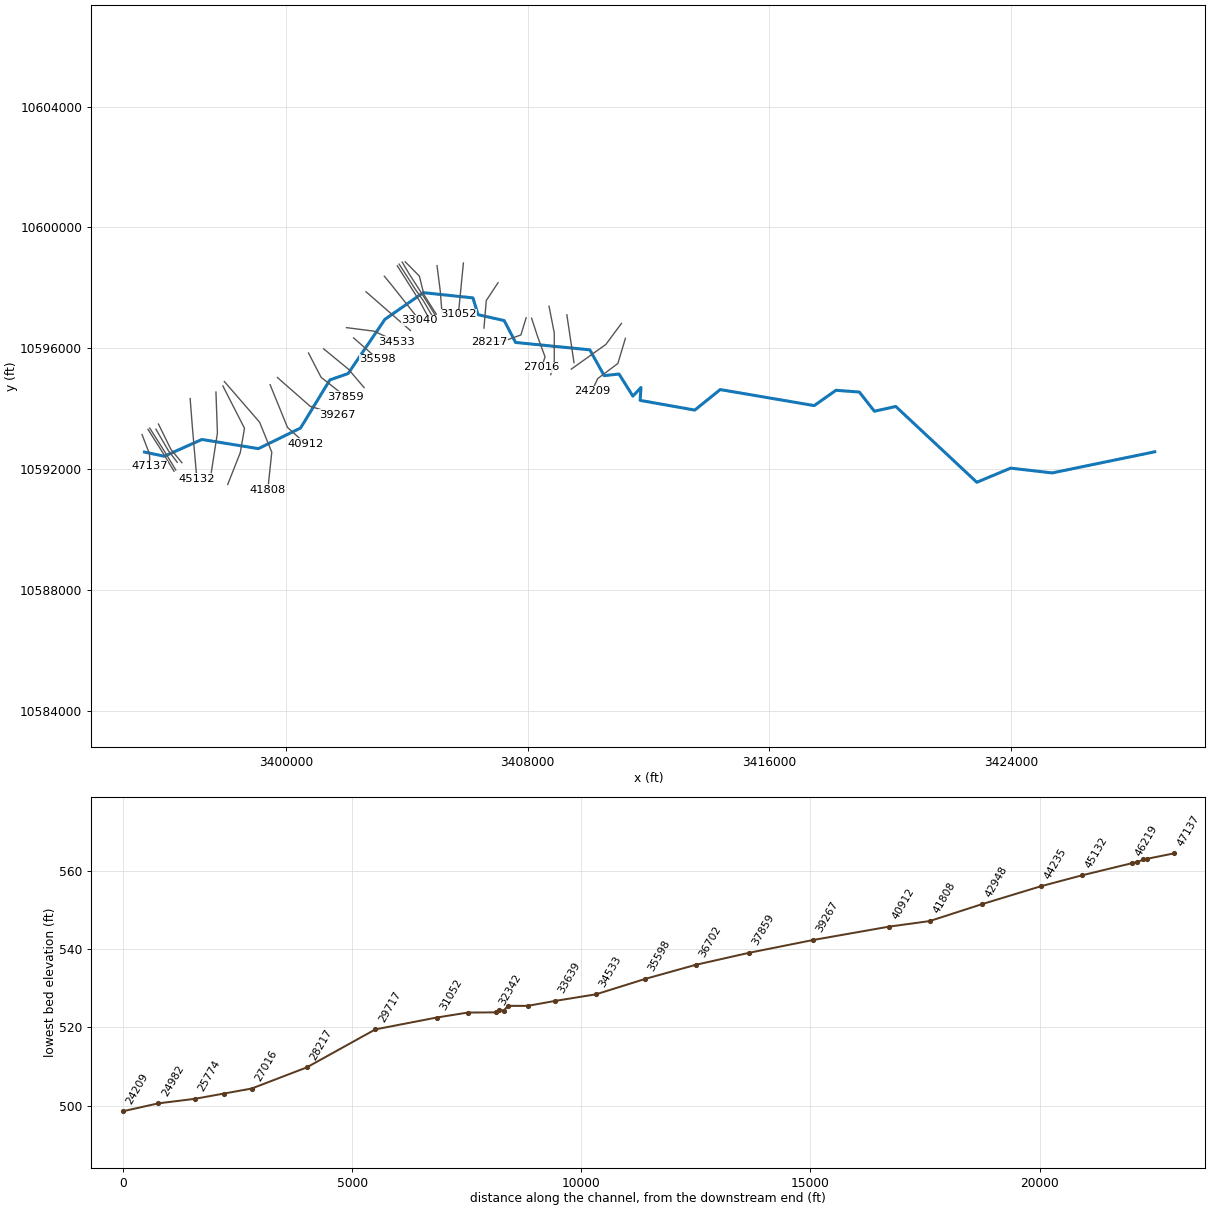
--- MUSTANG CREEK.prj (project) ---

Proj Title=MUSTANG CREEK Base Level Engineering
Current Plan=p01
Default Exp/Contr=0.3,0.1
English Units
Geom File=g01
Flow File=f01
Plan File=p01
Y Axis Title=Elevation
X Axis Title(PF)=Main Channel Distance
X Axis Title(XS)=Station
BEGIN DESCRIPTION:
MUSTANG CREEK
END DESCRIPTION:
DSS File=dss
DSS Export Rating Curves= 0
DSS Export Rating Curve Sorted= 0
DSS Export Volume Flow Curves= 0
DXF OffsetX= 0
DXF OffsetY= 0
DXF ScaleX= 1
DXF ScaleY= 10

--- MUSTANG CREEK.p01 (plan) ---

Plan Title=Multiple Run
Program Version=4.10
Short Identifier=Multiple Run
Geom File=g01
Flow File=f01
Subcritical Flow
K Sum by GR= 0
Std Step Tol= 0.01
Critical Tol= 0.01
Num of Std Step Trials= 20
Max Error Tol= 0.3
Flow Tol Ratio= 0.001
Split Flow NTrial= 30
Split Flow Tol= 0.02
Split Flow Ratio= 0.02
Log Output Level= 0
Friction Slope Method= 1
Unsteady Friction Slope Method= 2
Unsteady Bridges Friction Slope Method= 1
Parabolic Critical Depth
Global Vel Dist= 1 , 1 , 1
Global Log Level= 0
CheckData=True
Encroach Param=-1 ,0,0, 0
BEGIN DESCRIPTION:
Multiple Run
END DESCRIPTION:
Computation Interval=1HOUR
Output Interval=1HOUR
Run HTab= 0
Run UNet= 0
Run PostProcess= 0
Run WQNet= 0
UNET Theta= 1
UNET Theta Warmup= 1
UNET ZTol= 0.02
UNET ZSATol= 0.05
UNET MxIter= 20
UNET MaxInSteps= 0
UNET DtIC= 0
UNET DtMin= 0
UNET MaxCRTS= 20
UNET WFStab= 2
UNET SFStab= 1
UNET WFX= 1
UNET SFX= 1
UNET DSS MLevel= 4
UNET DZMax Abort= 100
UNET Convert EG Bridges= 0
UNET Use Existing IB Tables=-1
UNET Froude Reduction=False
UNET Froude Limit= 1
UNET Froude Power= 10
UNET Time Slicing=0,0, 5
UNET Junction Losses=0
Instantaneous Interval=1HOUR
DSS File=dss
Write IC File= 0
Write IC File at Sim End=0
Echo Input=False
Echo Parameters=False
Echo Output=False
Write Detailed= 0
WQ AD Non Conservative
WQ ULTIMATE=-1
WQ Max Comp Step=1HOUR
WQ Output Interval=15MIN
WQ Output Selected Increments= 0
WQ Output face flow=0
WQ Output face velocity=0
WQ Output face area=0
WQ Output face dispersion=0
WQ Output cell volume=0
WQ Output cell surface area=0
WQ Output cell continuity=0
WQ Output cumulative cell continuity=0
WQ Output face conc=0
WQ Output face dconc_dx=0
WQ Output face courant=0
WQ Output face peclet=0
WQ Output face adv mass=0
WQ Output face disp mass=0
WQ Output cell mass=0
WQ Output cell source sink temp=0
WQ Output cell source sink nsm=0
WQ Output MaxMinRange=-1
WQ Daily Max Min Mean=-1
WQ Daily Range=0
WQ Daily Time=0
WQ Create Restart=0
WQ Fixed Restart=0
WQ System Summary=0
WQ Use Fixed Temperature=0
Sorting and Armoring Iterations= 10
XS Update Threshold= 0.02
Hydraulics Update Threshold= 0.02
Energy Slope Method= 1
Volume Change Method= 0
XS Weighting Method= 0
Number of US Weighted Cross Sections= 1
Number of DS Weighted Cross Sections= 1
Upstream XS Weight=0.25
Main XS Weight=0.5
Downstream XS Weight=0.25
Number of DS XS's Weighted with US Boundary= 1
Upstream Boundary Weight= 1
Weight of XSs Associated with US Boundary= 0
Number of US XS's Weighted with DS Boundary= 1
Downstream Boundary Weight= 0.5
Weight of XSs Associated with DS Boundary= 0.5
Sediment Output Level= 4
Mass or Volume Output= 0
Output Increment Type= 1
Profile and TS Output Increment= 10
XS Output Flag= 0
XS Output Increment= 10
Disregard all LS=0
Disregard all Conn=0
Disregard all Breaches=0
Disregard all Pumps=0

--- MUSTANG CREEK.f01 (steady flow) ---

Flow Title=Multiple
Program Version=4.10
Number of Profiles= 7
Profile Names=10-year,25-year,50-year,1pct_min,100-year,1pct_plu,500-year
River Rch & RM=MUSTANG CREEK,Reach-1         ,47137
     412     524     608     514     695     940     906
River Rch & RM=MUSTANG CREEK,Reach-1         ,46543
     568     734     859     732     990    1339    1312
River Rch & RM=MUSTANG CREEK,Reach-1         ,44235
     600     773     904     768    1039    1405    1371
River Rch & RM=MUSTANG CREEK,Reach-1         ,40912
     749     971    1140     971    1314    1777    1744
River Rch & RM=MUSTANG CREEK,Reach-1         ,32613
     852    1110    1308    1118    1512    2044    2018
River Rch & RM=MUSTANG CREEK,Reach-1         ,27016
    1273    1688    2011    1737    2349    3177    3203
River Rch & RM=MUSTANG CREEK,Reach-1         ,24209
    1283    1699    2022    1744    2359    3190    3209
River Rch & RM=MUSTANG CREEK,Reach-1         ,20301
    1655    2205    2635    2281    3085    4172    4223
River Rch & RM=MUSTANG CREEK,Reach-1         ,12532
    1673    2223    2651    2289    3096    4186    4217
River Rch & RM=MUSTANG CREEK,Reach-1         ,6286
    1997    2666    3190    2762    3735    5051    5115
Boundary for River Rch & Prof#=MUSTANG CREEK,Reach-1         , 1
Up Type= 0
Dn Type= 3
Dn Slope=0.002
Boundary for River Rch & Prof#=MUSTANG CREEK,Reach-1         , 2
Up Type= 0
Dn Type= 3
Dn Slope=0.002
Boundary for River Rch & Prof#=MUSTANG CREEK,Reach-1         , 3
Up Type= 0
Dn Type= 3
Dn Slope=0.002
Boundary for River Rch & Prof#=MUSTANG CREEK,Reach-1         , 4
Up Type= 0
Dn Type= 3
Dn Slope=0.002
Boundary for River Rch & Prof#=MUSTANG CREEK,Reach-1         , 5
Up Type= 0
Dn Type= 3
Dn Slope=0.002
Boundary for River Rch & Prof#=MUSTANG CREEK,Reach-1         , 6
Up Type= 0
Dn Type= 3
Dn Slope=0.002
Boundary for River Rch & Prof#=MUSTANG CREEK,Reach-1         , 7
Up Type= 0
Dn Type= 3
Dn Slope=0.002
DSS Import GetInterval= 0
DSS Import GetPeak= 0
DSS Import FillOption= 0

--- MUSTANG CREEK.g01 (geometry) ---

Geom Title=Existing Conditions
Program Version=4.10

River Reach=MUSTANG CREEK   ,Reach-1
Reach XY= 30
      3395322.94     10592562.56      3395978.71     10592424.18
      3397221.48     10592979.54      3399090.82      10592676.3
      3400484.88      10593356.8      3401458.56     10594953.09
       3402061.1     10595162.21      3403278.43     10596958.47
      3404547.63      10597841.1      3406190.49     10597668.09
      3406359.92     10597111.94      3407224.81     10596916.67
      3407601.94     10596192.34      3410059.08     10595946.93
      3410532.84      10595093.5       3411024.4     10595146.65
      3411483.63      10594414.6      3411750.75     10594699.29
        3411723.     10594274.14      3413531.58     10593952.94
      3414373.78     10594631.74      3417483.24      10594101.6
      3418203.79     10594608.44      3418976.91     10594549.81
      3419473.73     10593914.83      3420182.11     10594071.64
      3422863.31     10591562.68       3423982.7      10592030.2
       3425357.6     10591872.07      3428752.11     10592571.64

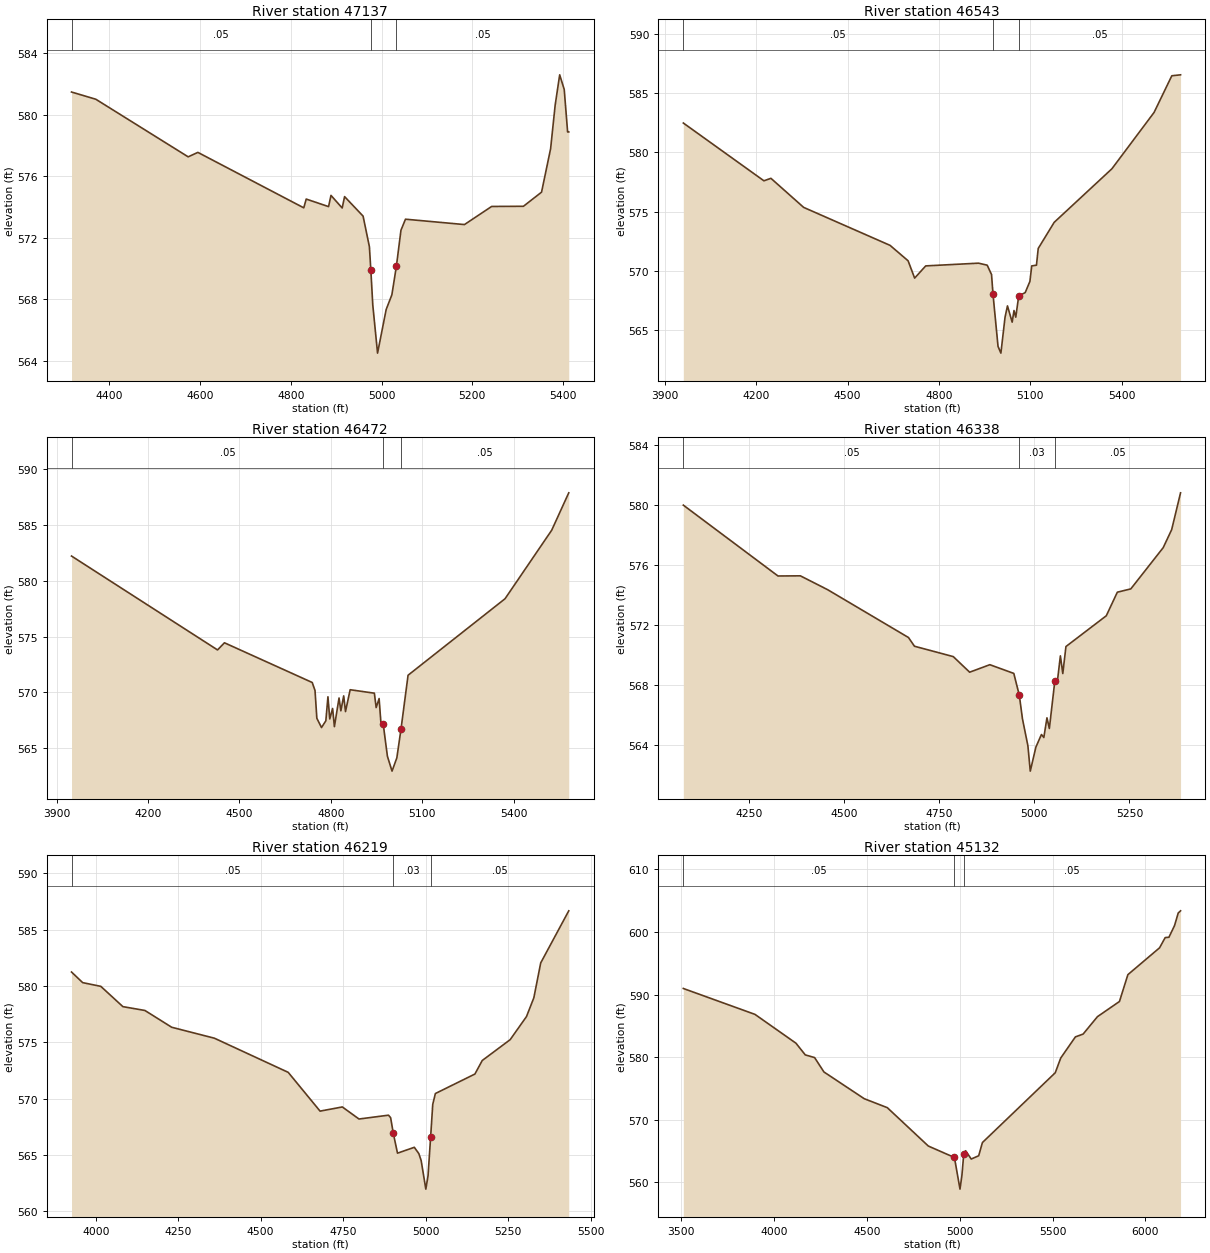
Type RM Length L Ch R = 1 ,47137   ,594,594,594
BEGIN DESCRIPTION:
MUSTANG CREEK 64.0
END DESCRIPTION:
XS GIS Cut Line= 3
       3395242.1     10593141.65      3395492.11     10592491.64
      3395492.11     10592091.67
#Sta/Elev= 30
  4316.5  581.49  4370.1  581.02  4573.7  577.27  4595.1  577.56  4828.6  573.95
    4834  574.52  4883.3  574.03  4888.6  574.76  4913.3  573.94  4918.6  574.68
  4959.4  573.41  4973.3  571.42 4976.45  569.93  4980.8  567.62  4991.3  564.49
  5010.3  567.33  5022.9  568.29  5032.9  570.16  5042.9  572.49  5052.9  573.21
  5182.9  572.86  5242.9  574.04  5312.9  574.05  5352.9  574.97  5372.9   577.8
  5382.9  580.63  5392.9  582.61  5402.9  581.66  5410.4  578.89  5412.9  578.89
#Mann= 3 , 0 , 0
  4316.5     .05       0 4976.45     .03       0  5032.9     .05       0
Bank Sta=4976.45,5032.9
XS Rating Curve= 0 ,0
Exp/Cntr=0.3,0.1

Type RM Length L Ch R = 1 ,46543   ,71,71,71
BEGIN DESCRIPTION:
MUSTANG CREEK 63.5
END DESCRIPTION:
XS GIS Cut Line= 3
      3395438.02     10593314.27       3395932.8     10592535.64
      3396300.01     10591928.84
#Sta/Elev= 30
  3960.9  582.48  4225.4  577.61  4248.4  577.82  4355.8  575.37  4639.4  572.17
  4698.6  570.87    4720  569.41  4756.4  570.44  4929.7  570.67  4958.2   570.5
  4972.4  569.71 4977.21  568.05  4993.7  563.66  5003.1  563.09  5016.7  566.11
  5024.7  567.07  5040.1   565.7  5046.1  566.68  5051.9  566.12  5061.6  567.91
  5082.9  568.19  5098.4  569.14  5104.3  570.44  5119.8   570.5  5125.6  571.91
    5178  574.11  5367.3  578.62  5505.8  583.37    5564  586.46  5592.7  586.54
#Mann= 3 , 0 , 0
  3960.9     .05       0 4977.21     .03       0  5061.6     .05       0
Bank Sta=4977.21,5061.6
XS Rating Curve= 0 ,0
Exp/Cntr=0.3,0.1

Type RM Length L Ch R = 1 ,46472   ,134,134,134
BEGIN DESCRIPTION:
MUSTANG CREEK 63.0
END DESCRIPTION:
XS GIS Cut Line= 3
      3395495.29     10593355.98      3395990.09      10592577.3
      3396357.17     10591970.71
#Sta/Elev= 30
  3949.2  582.23  4428.3  573.81    4451  574.45    4739  570.89  4748.2  570.17
  4754.2  567.68  4769.5  566.85  4783.7  567.45  4790.6  569.61  4796.6  567.62
  4805.9  568.56  4811.8  566.93    4827   569.5    4833  568.35  4842.3  569.69
  4848.2  568.28  4863.5  570.24    4943  569.93  4948.8  568.64  4958.5  569.45
  4964.3  567.32  4971.9  567.18  4985.7  564.28  5000.9  562.94  5016.7  564.13
  5030.4  566.72  5053.5  571.54  5371.7   578.4  5524.9  584.55  5580.8   587.9
#Mann= 3 , 0 , 0
  3949.2     .05       0  4971.9     .03       0  5030.4     .05       0
#XS Ineff= 2 , 0
         4824.77  568.71
Permanent Ineff=
       F       F
Bank Sta=4971.9,5030.4
XS Rating Curve= 0 ,0
Exp/Cntr=0.3,0.1

Type RM Length L Ch R = 1 ,46338   ,119,119,119
BEGIN DESCRIPTION:
MUSTANG CREEK 62.0
END DESCRIPTION:
XS GIS Cut Line= 3
      3395701.02     10593319.52       3396117.7     10592600.74
      3396406.78     10592223.11
#Sta/Elev= 30
  4077.8  579.98  4326.5  575.26  4385.3  575.27  4456.8  574.35  4669.4  571.16
  4685.1  570.58    4787  569.89  4830.1  568.85  4883.1  569.35  4946.1  568.77
  4960.6  567.31  4968.8  565.75  4983.1  563.95  4989.4  562.26  5004.1  563.86
  5018.7   564.7    5025   564.5  5033.2  565.81  5039.5   565.1    5054  568.29
  5060.3  568.18  5068.5  569.94  5074.8  568.76  5083.1  570.56  5189.1  572.61
  5218.1  574.18  5253.5   574.4  5338.7  577.15  5360.9  578.35  5384.2   580.8
#Mann= 3 , 0 , 0
  4077.8     .05       0  4960.6     .03       0    5054     .05       0
Bank Sta=4960.6,5054
XS Rating Curve= 0 ,0
Exp/Cntr=0.3,0.1

Type RM Length L Ch R = 1 ,46219   ,1087,1087,1087
BEGIN DESCRIPTION:
MUSTANG CREEK 61.0
END DESCRIPTION:
XS GIS Cut Line= 3
      3395784.35     10593491.39      3396193.22     10592658.03
      3396560.38     10592210.15
#Sta/Elev= 30
  3926.6  581.24  3960.4   580.3  4015.4  579.97  4082.3  578.17  4149.1  577.83
  4230.3  576.34  4359.7  575.37  4583.5  572.34  4680.1   568.9  4747.6  569.27
  4798.1   568.2  4887.5  568.54    4894  568.32  4901.9  566.96  4914.8  565.17
  4965.8  565.69  4979.5  565.13  4986.6  564.51  5000.7  561.98  5007.4  563.16
  5015.3  566.62  5021.7   569.5  5029.6  570.46  5149.5  572.19  5171.7  573.39
  5256.4  575.24  5305.9  577.29  5328.2  578.96    5349  582.05    5434  586.67
#Mann= 3 , 0 , 0
  3926.6     .05       0  4901.9     .03       0  5015.3     .05       0
Bank Sta=4901.9,5015.3
XS Rating Curve= 0 ,0
Exp/Cntr=0.3,0.1

Type RM Length L Ch R = 1 ,45132   ,897,897,897
BEGIN DESCRIPTION:
MUSTANG CREEK 59.0
END DESCRIPTION:
XS GIS Cut Line= 3
      3396833.09     10594335.97      3396909.48      10593363.7
      3397055.32     10591669.23
#Sta/Elev= 30
  3512.8  590.97  3898.3  586.83    4119  582.22  4169.1  580.35  4219.3  579.92
  4269.5  577.62  4486.6  573.34  4610.6  571.91  4831.4  565.77  4971.9  563.94
  5001.8  558.88  5012.1  561.06  5022.1  564.53  5032.1  565.02  5062.2  563.69
  5102.4  564.22  5122.5  566.33  5514.4  577.49    5544  579.85  5622.9  583.23
  5664.5  583.68  5741.5  586.46    5860  588.89  5905.3  593.18    6076  597.48
  6106.1  599.11  6126.2  599.16  6156.3  601.02  6176.3  603.04  6188.8  603.39
#Mann= 3 , 0 , 0
  3512.8     .05       0  4971.9     .03       0  5022.1     .05       0
Bank Sta=4971.9,5022.1
XS Rating Curve= 0 ,0
Exp/Cntr=0.3,0.1

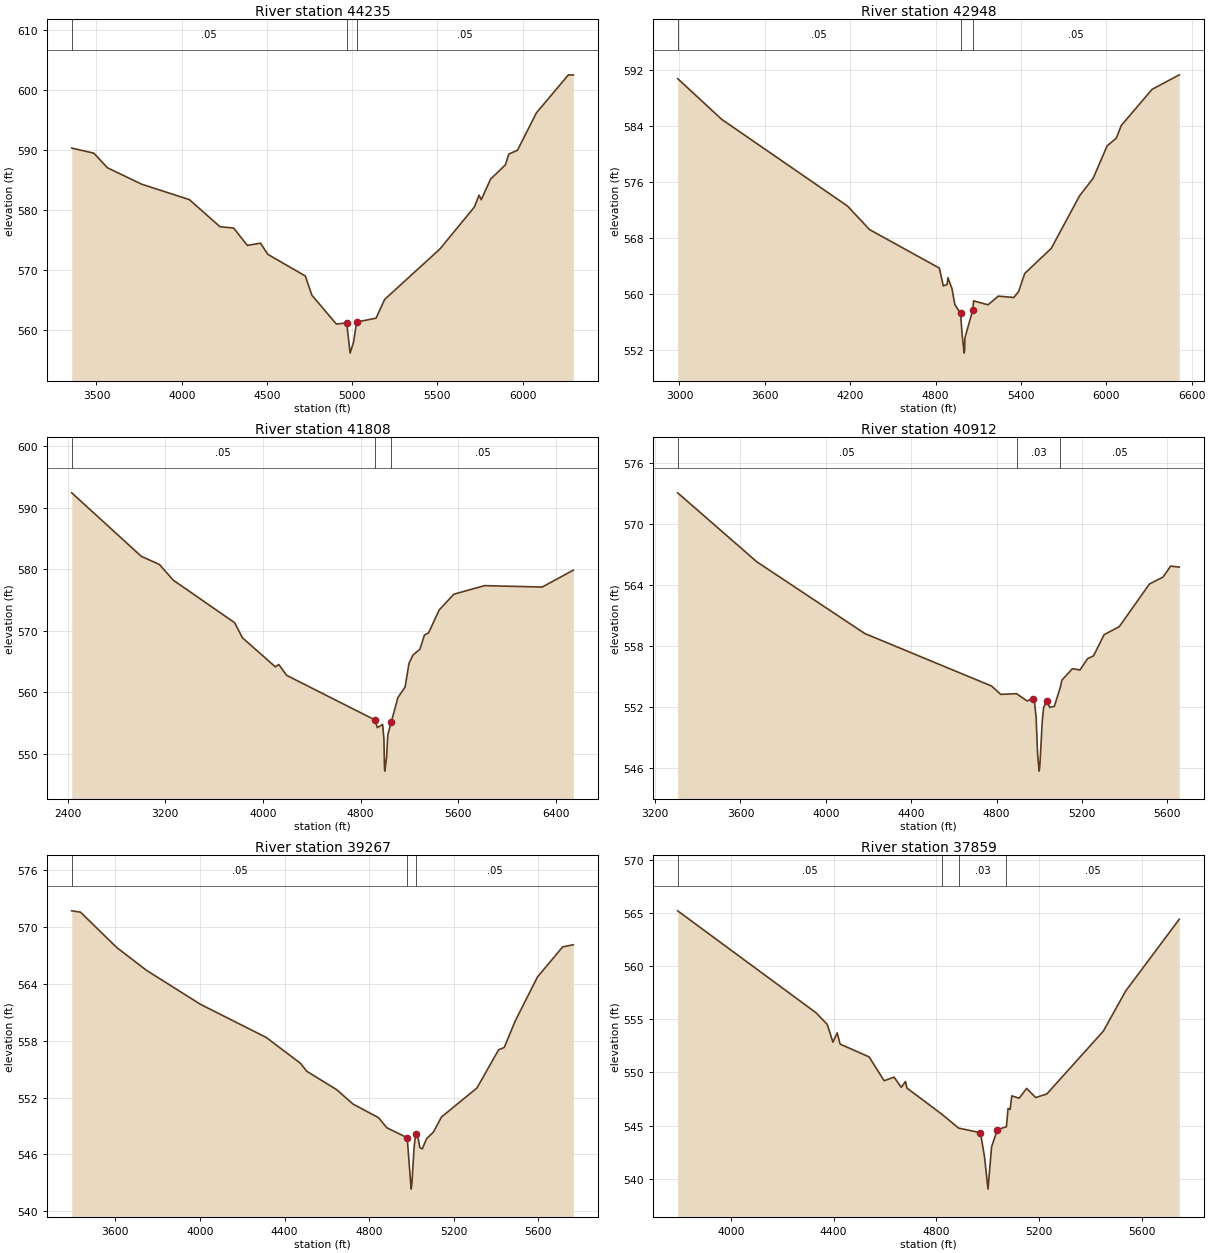
Type RM Length L Ch R = 1 ,44235   ,1287,1287,1287
BEGIN DESCRIPTION:
MUSTANG CREEK 58.0
END DESCRIPTION:
XS GIS Cut Line= 3
      3397687.26     10594551.24      3397735.87     10593197.04
      3397492.82     10591627.62
#Sta/Elev= 30
  3354.8  590.35  3484.5   589.5  3564.5  587.06  3764.7  584.32  4044.8  581.74
    4225  577.21    4305  576.99  4385.1  574.09  4462.8  574.46  4505.1   572.6
  4725.5  568.98    4764  565.76  4907.6  560.95  4968.3  561.14  4988.3  556.09
  5008.8  557.97  5026.2  561.28  5140.3  561.93  5190.9  565.06  5514.8  573.48
  5717.1  580.49  5744.9  582.47  5757.6  581.72  5812.9  585.18  5899.3  587.54
  5919.5  589.35  5970.1  589.98  6081.4  596.24  6269.3  602.59    6298  602.56
#Mann= 3 , 0 , 0
  3354.8     .05       0  4968.3     .03       0  5026.2     .05       0
Bank Sta=4968.3,5026.2
XS Rating Curve= 0 ,0
Exp/Cntr=0.3,0.1

Type RM Length L Ch R = 1 ,42948   ,1140,1140,1140
BEGIN DESCRIPTION:
MUSTANG CREEK 56.0
END DESCRIPTION:
XS GIS Cut Line= 4
      3397916.41     10594752.63       3398631.7     10593349.81
      3398492.81     10592544.26      3398076.63     10591489.92
#Sta/Elev= 30
  2987.4  590.82  3297.2  584.98  4180.8  572.57  4336.5  569.19  4826.8  563.68
  4854.5  561.13  4881.6  561.34  4886.7   562.3  4915.4  560.75  4935.7  558.46
  4976.2  557.18  4986.4  554.24  5001.1   551.5  5004.4     552  5006.7  553.71
  5061.2  557.64  5067.6  558.99  5169.1  558.42  5240.8  559.66  5350.4  559.47
  5383.6  560.31  5426.5   562.9  5613.2   566.5  5812.3  574.03  5908.1  576.56
  6005.9  581.18  6070.4  582.29  6105.6  584.11    6322  589.28    6513  591.36
#Mann= 3 , 0 , 0
  2987.4     .05       0  4976.2     .03       0  5061.2     .05       0
Bank Sta=4976.2,5061.2
XS Rating Curve= 0 ,0
Exp/Cntr=0.3,0.1

Type RM Length L Ch R = 1 ,41808   ,896,896,896
BEGIN DESCRIPTION:
MUSTANG CREEK 54.0
END DESCRIPTION:
XS GIS Cut Line= 4
      3397965.06     10594898.39       3399131.7      10593551.2
      3399534.48     10592558.15      3399402.54     10591308.15
#Sta/Elev= 30
  2433.5  592.43  3003.2  582.11  3152.4  580.78  3265.4  578.23  3768.7  571.31
  3832.4  568.86  4102.1  564.14  4130.6  564.51  4194.3  562.76  4916.5  555.52
  4938.2  554.25  4981.3  554.78  4992.1  552.42  4996.5  547.68  4999.3  547.18
  5013.7  549.43  5023.6  553.07  5053.1  555.23  5106.7  559.15  5165.7  560.87
  5197.2  564.69  5229.5  566.04  5287.3  567.01    5324  569.32  5358.3  569.67
  5444.6  573.38  5565.3  575.95  5816.7  577.34  6289.3  577.11  6544.2  579.86
#Mann= 3 ,-1 , 0
  2433.5     .05       0  4916.5     .03       0  5053.1     .05       0
Bank Sta=4916.5,5053.1
XS Rating Curve= 0 ,0
Exp/Cntr=0.3,0.1

Type RM Length L Ch R = 1 ,40912   ,1645,1645,1645
BEGIN DESCRIPTION:
MUSTANG CREEK 51.0
END DESCRIPTION:
XS GIS Cut Line= 3
      3399478.93     10594794.26      3400055.31     10593377.59
      3400666.45     10592828.96
#Sta/Elev= 30
  3305.6  573.05  3676.6  566.28  4182.9  559.24  4776.7  554.09  4819.9  553.27
  4893.8  553.34  4943.1  552.63  4971.5  552.85  4978.5  552.43  4985.7  550.93
  4992.4  547.42  4999.7  545.74  5002.9  546.24  5014.1  550.59  5020.8  551.99
    5035  552.62  5049.2     552  5070.9   552.1  5099.3     554  5106.1  554.66
  5155.4  555.79  5191.3  555.67  5226.4  556.77  5254.8  557.06  5304.1  559.13
  5375.2  559.92  5516.4   564.1  5580.7  564.79  5615.9  565.86  5656.3  565.76
#Mann= 3 ,-1 , 0
  3305.6     .05       0  4893.8     .03       0  5099.3     .05       0
Bank Sta=4971.5,5035
XS Rating Curve= 0 ,0
Exp/Cntr=0.3,0.1

Type RM Length L Ch R = 1 ,39267   ,1408,1408,1408
BEGIN DESCRIPTION:
MUSTANG CREEK 48.0
END DESCRIPTION:
XS GIS Cut Line= 3
      3399721.97     10595030.38      3400805.31     10594078.98
      3401694.21      10593801.2
#Sta/Elev= 30
  3393.4  571.73  3434.8  571.59  3605.6  567.87  3746.9  565.45  4002.2  561.86
  4313.4  558.36  4476.6  555.61  4505.1  554.79  4646.5  552.85  4724.5  551.32
  4845.3  549.88  4884.2  548.82  4980.5  547.77  4999.2  542.34  5002.5  542.84
  5012.9  546.68  5020.4  548.16  5030.9  547.91  5040.2  546.73  5051.9  546.59
  5072.7  547.69  5104.2  548.35  5142.8  549.96  5310.5  553.02  5413.2  557.06
  5439.5   557.3  5491.9  560.11  5596.7  564.74  5715.9  567.92  5766.5  568.15
#Mann= 3 , 0 , 0
  3393.4     .05       0  4980.5     .07       0  5020.4     .05       0
Bank Sta=4980.5,5020.4
XS Rating Curve= 0 ,0
Exp/Cntr=0.3,0.1

Type RM Length L Ch R = 1 ,37859   ,1157,1157,1157
BEGIN DESCRIPTION:
MUSTANG CREEK 45.0
END DESCRIPTION:
XS GIS Cut Line= 3
      3400749.77     10595842.84      3401166.43     10595037.31
       3401985.9     10594391.45
#Sta/Elev= 30
  3793.7  565.18  4330.9  555.62  4375.2  554.52  4397.4  552.84  4413.9  553.72
  4425.5  552.66  4538.1  551.46  4596.6  549.22  4635.3  549.56  4663.1   548.6
  4679.6  549.15  4685.2  548.53  4820.3  546.09  4886.1  544.77  4971.1  544.34
    4987  542.04  5000.4  539.04  5014.2  543.01  5036.7  544.62    5072   544.9
  5078.3  546.62  5086.4  546.52  5092.8   547.8  5121.7  547.58  5150.6   548.5
  5185.8  547.64  5229.2  547.98  5448.8  553.88  5535.4  557.64    5744  564.39
#Mann= 4 ,-1 , 0
  3793.7     .05       0  4820.3     .16       0  4886.1     .03       0
    5072     .05       0
Bank Sta=4971.1,5036.7
XS Rating Curve= 0 ,0
Exp/Cntr=0.3,0.1

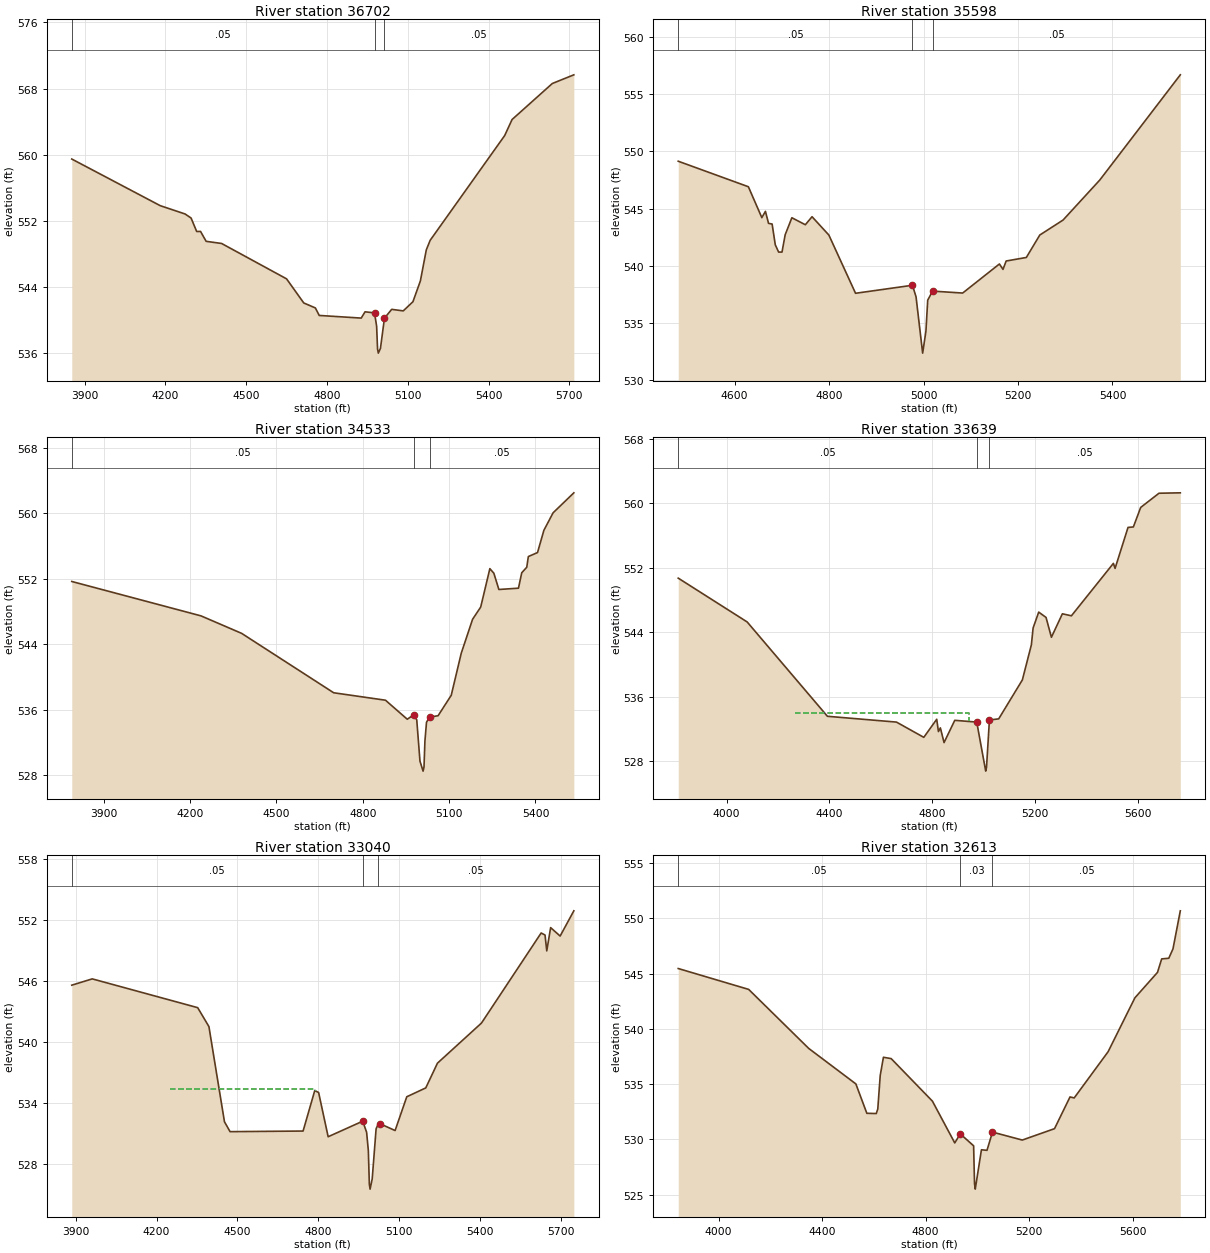
Type RM Length L Ch R = 1 ,36702   ,1104,1104,1104
BEGIN DESCRIPTION:
MUSTANG CREEK 44.0
END DESCRIPTION:
XS GIS Cut Line= 3
      3401249.74     10595981.77       3402069.2     10595308.15
      3402590.01     10594697.07
#Sta/Elev= 30
  3852.7  559.47  4180.8  553.83  4273.3  552.82  4295.6  552.33  4316.4   550.7
  4330.7  550.71  4351.5  549.51  4408.9  549.25    4650  544.97  4713.9  542.05
  4756.9  541.45  4771.3  540.54  4927.1  540.22  4941.4  540.98  4976.5  540.85
  4984.3  539.25  4987.8  536.48  4990.6  535.98  4998.5  536.55  5013.4  540.21
  5040.3  541.28  5083.1  541.09  5119.1   542.2  5146.7  544.71  5168.7  548.47
    5183  549.63  5459.7  562.31  5487.1  564.25  5636.5  568.61  5716.4  569.66
#Mann= 3 , 0 , 0
  3852.7     .05       0  4976.5     .07       0  5013.4     .05       0
Bank Sta=4976.5,5013.4
XS Rating Curve= 0 ,0
Exp/Cntr=0.3,0.1

Type RM Length L Ch R = 1 ,35598   ,1065,1065,1065
BEGIN DESCRIPTION:
MUSTANG CREEK 42.0
END DESCRIPTION:
XS GIS Cut Line= 3
      3402242.11     10596341.64      3402642.11     10595991.64
      3403042.09     10595641.65
#Sta/Elev= 30
  4480.6  549.14  4629.1  546.91  4657.6  544.21  4665.2  544.76  4671.8  543.71
  4679.4  543.65  4686.1  541.83  4693.2   541.2  4700.3   541.2    4707  542.71
  4721.2   544.2  4749.7  543.59  4763.9  544.29  4799.5  542.69    4856   537.6
  4976.5   538.3  4984.1  537.29  4998.1  532.37    5005  534.28  5008.8     537
  5019.2  537.79  5082.8  537.62  5160.6  540.16  5168.2  539.69  5174.9  540.42
  5217.6  540.73  5246.1  542.69  5295.4     544  5373.2   547.5  5543.6  556.69
#Mann= 3 , 0 , 0
  4480.6     .05       0  4976.5     .03       0  5019.2     .05       0
Bank Sta=4976.5,5019.2
XS Rating Curve= 0 ,0
Exp/Cntr=0.3,0.1

Type RM Length L Ch R = 1 ,34533   ,894,894,894
BEGIN DESCRIPTION:
MUSTANG CREEK 39.0
END DESCRIPTION:
XS GIS Cut Line= 3
      3402006.72     10596683.15      3402923.37     10596565.09
      3403666.43     10596217.87
#Sta/Elev= 30
  3788.9  551.67    4238  547.46  4379.1  545.32  4698.9  538.05  4878.8  537.14
  4954.6  534.81  4976.6  535.35  4987.5  534.74  4998.7  529.68  5009.5  528.46
  5012.7  528.96  5015.9  532.15  5021.4  534.44  5031.8  535.07  5061.6  535.24
  5107.3  537.74  5142.2   542.9  5181.4  547.04  5209.7  548.54  5241.5  553.24
  5255.4  552.68  5272.8  550.69  5340.9  550.85  5352.3  552.74  5369.7  553.41
  5375.2  554.72  5407.1  555.21  5429.2  557.93  5461.1  560.07  5533.3  562.52
#Mann= 3 ,-1 , 0
  3788.9     .05       0  4976.6     .03       0  5031.8     .05       0
Bank Sta=4976.6,5031.8
XS Rating Curve= 0 ,0
Exp/Cntr=0.3,0.1

Type RM Length L Ch R = 1 ,33639   ,599,599,599
BEGIN DESCRIPTION:
MUSTANG CREEK 38.0
END DESCRIPTION:
XS GIS Cut Line= 2
      3402652.52     10597870.66      3404124.32     10596586.31
#Sta/Elev= 30
  3811.8  550.69  4079.9  545.26  4392.2  533.56  4660.9  532.84  4767.2  530.95
  4817.5  533.19  4824.1  531.67  4831.7  532.12    4846   530.3  4887.7  533.06
  4973.2  532.84  5008.1  526.76  5011.3  527.26  5022.5   533.1  5058.6  533.24
  5150.7  538.07  5185.8  542.43  5192.5  544.51  5214.3  546.48  5242.8  545.82
  5263.7  543.36  5306.4  546.27  5341.5  546.02  5504.8  552.52  5511.4   551.9
  5561.8  556.98  5582.6  557.04  5611.1  559.46  5682.3  561.22  5765.2  561.27
#Mann= 3 , 0 , 0
  3811.8     .05       0  4973.2     .03       0  5022.5     .05       0
#XS Ineff= 1 ,-1
 4267.77 4943.13533.9606
Permanent Ineff=
       F
Bank Sta=4973.2,5022.5
XS Rating Curve= 0 ,0
Exp/Cntr=0.3,0.1

Type RM Length L Ch R = 1 ,33040   ,427,427,427
BEGIN DESCRIPTION:
MUSTANG CREEK 36.0
END DESCRIPTION:
XS GIS Cut Line= 3
      3403258.82     10598385.21      3403521.43     10598065.74
      3404420.21     10596928.73
#Sta/Elev= 30
  3885.6  545.55  3961.5  546.17  4352.8  543.34  4394.5  541.48  4452.2  532.12
    4473  531.15  4743.9  531.21  4787.2  535.19  4801.5     535  4836.9  530.65
  4965.2  532.18  4979.6  531.09    4986   529.3  4989.7     526  4992.5   525.5
  5000.4  526.52  5014.8  531.43  5021.2  531.81  5029.3  531.93  5085.3  531.26
  5128.6  534.58  5199.1  535.45  5242.4  537.88  5405.9  541.83  5627.2  550.68
  5641.6  550.48    5648  548.92  5662.4  551.21  5697.6  550.38  5748.5  552.86
#Mann= 3 ,-1 , 0
  3885.6     .05       0  4965.2     .03       0  5021.2     .05       0
#XS Ineff= 1 ,-1
 4249.67 4787.98  535.32
Permanent Ineff=
       F
Bank Sta=4965.2,5029.3
XS Rating Curve= 0 ,0
Exp/Cntr=0.3,0.1

Type RM Length L Ch R = 1 ,32613   ,100,100,100
BEGIN DESCRIPTION:
MUSTANG CREEK 35.0
END DESCRIPTION:
XS GIS Cut Line= 3
      3403686.57     10598731.68      3404406.65     10597594.71
      3404690.89     10597072.24
#Sta/Elev= 30
  3843.9  545.46  4116.2  543.57  4348.3  538.23  4530.5  535.02  4572.9  532.36
  4609.3  532.34  4615.2  532.75  4624.6  535.78    4637  537.43  4666.9  537.31
  4826.4  533.46  4912.7  529.68  4933.9   530.5  4985.6  529.42  4989.1     526
  4991.9   525.5  5015.8  529.06  5037.3  529.01  5058.5  530.66  5173.7  529.94
  5298.3  530.97  5358.2  533.84  5374.3  533.75  5505.4  537.93    5609  542.81
  5696.3  545.11  5712.5  546.33    5740  546.39  5756.2  547.24  5784.5  550.68
#Mann= 3 , 0 , 0
  3843.9     .05       0  4933.9     .03       0  5058.5     .05       0
Bank Sta=4933.9,5058.5
XS Rating Curve= 0 ,0
Exp/Cntr=0.3,0.1

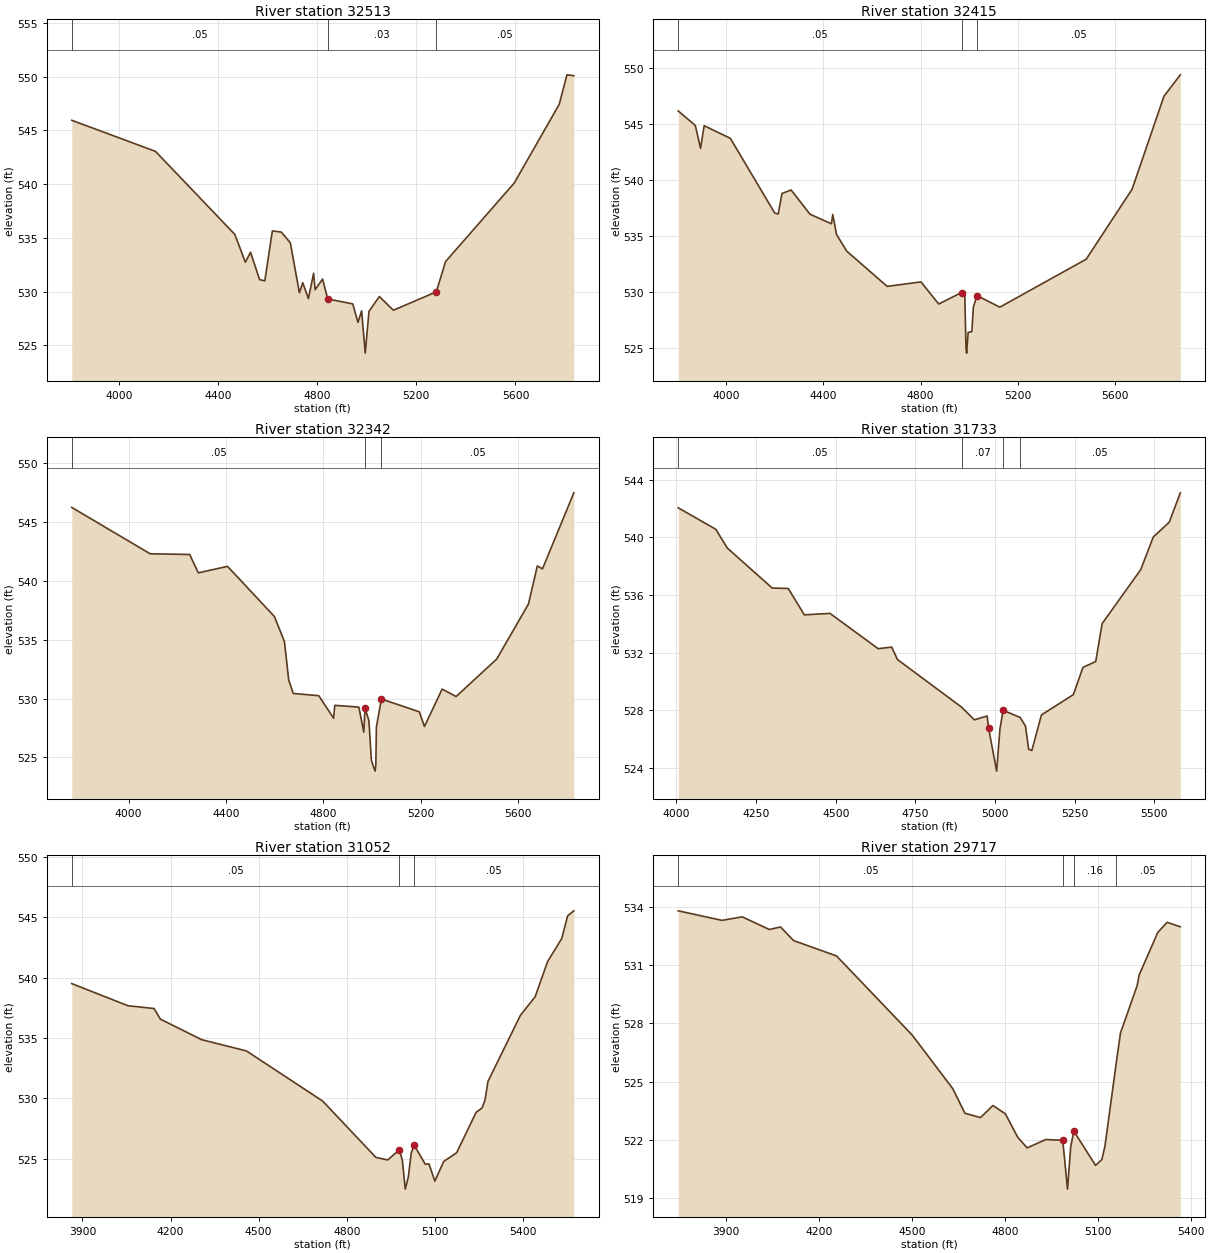
Type RM Length L Ch R = 1 ,32513   ,98,98,98
BEGIN DESCRIPTION:
MUSTANG CREEK 35.3
END DESCRIPTION:
XS GIS Cut Line= 4
      3403748.82     10598785.84      3404287.54     10597946.63
      3404544.71     10597581.17      3404839.79     10597080.35
#Sta/Elev= 30
    3810  545.93  4147.7  543.04  4467.9  535.31  4510.2  532.73  4531.3  533.65
  4567.7  531.11  4588.8  530.99  4619.2  535.64  4655.5  535.53  4691.9  534.52
  4728.2  529.89  4741.9  530.82  4764.6  529.34  4785.7   531.7  4791.6  530.17
  4821.7  531.16  4842.6  529.31  4943.6  528.85  4964.5  527.13  4979.3   528.2
  4993.9  524.27  5008.9  528.15  5050.8  529.54  5107.4  528.26  5280.6  529.97
  5317.7  532.78  5594.8  540.09  5776.3  547.41  5807.6  550.16  5835.4  550.08
#Mann= 3 , 0 , 0
    3810     .05       0  4842.6     .03       0  5280.6     .05       0
#XS Ineff= 2 , 0
         4595.08  531.28
Permanent Ineff=
       F       F
Bank Sta=4842.6,5280.6
XS Rating Curve= 0 ,0
Exp/Cntr=0.3,0.1

Type RM Length L Ch R = 1 ,32415   ,73,73,73
BEGIN DESCRIPTION:
MUSTANG CREEK 35.1
END DESCRIPTION:
XS GIS Cut Line= 5
      3403849.01     10598853.47      3404084.51     10598455.56
      3404368.75     10598014.31      3404671.94     10597535.15
      3404942.63     10597099.35
#Sta/Elev= 30
  3802.1   546.2  3872.5   544.9    3894  542.85  3908.8  544.88  4016.8  543.75
  4199.3  537.07  4213.7  536.98  4229.3  538.82  4266.9  539.13  4344.8  536.96
  4432.6  536.11  4438.5  536.93  4453.7  535.16    4496  533.66  4662.3  530.51
  4801.7  530.91  4874.6  528.93  4968.7  529.96  4981.8  529.92  4986.9  525.04
  4989.6  524.54  4995.8  526.39  5011.1  526.47  5017.3  528.66  5032.2  529.69
  5126.3  528.65    5482  532.94  5670.9   539.2    5802  547.51  5869.4  549.43
#Mann= 3 , 0 , 0
  3802.1     .05       0  4968.7     .03       0  5032.2     .05       0
Bank Sta=4968.7,5032.2
XS Rating Curve= 0 ,0
Exp/Cntr=0.3,0.1

Type RM Length L Ch R = 1 ,32342   ,609,609,609
BEGIN DESCRIPTION:
MUSTANG CREEK 35.2
END DESCRIPTION:
XS GIS Cut Line= 4
      3403949.14     10598864.34      3404417.48     10598390.59
      3404571.78     10597767.96      3404977.45     10597129.71
#Sta/Elev= 30
  3766.2  546.24  4088.4   542.3    4251  542.24  4286.4  540.68  4406.6  541.23
  4599.2  536.97  4640.6  534.83  4657.9  531.58  4676.8  530.43  4781.6  530.24
  4842.4  528.33  4847.5  529.42  4946.4  529.27  4966.6  527.14  4971.7  529.17
  4987.6  528.13  4997.9  524.74  5012.9  523.83  5016.1  524.33  5018.5  527.58
  5039.1  529.96  5194.8  528.87  5215.9  527.62  5288.8   530.8  5346.3  530.17
  5513.2  533.36  5643.6  538.03    5680  541.27  5701.2  541.02  5830.1  547.48
#Mann= 3 , 0 , 0
  3766.2     .05       0  4971.7     .03       0  5039.1     .05       0
Bank Sta=4971.7,5039.1
XS Rating Curve= 0 ,0
Exp/Cntr=0.3,0.1

Type RM Length L Ch R = 1 ,31733   ,681,681,681
BEGIN DESCRIPTION:
MUSTANG CREEK 34.2
END DESCRIPTION:
XS GIS Cut Line= 3
      3405002.21     10598734.37      3405110.49     10597889.78
      3405167.13      10597166.9
#Sta/Elev= 30
  4005.5  542.06  4123.4  540.57  4159.5  539.27  4300.6  536.49    4351  536.46
  4401.4  534.63  4482.1  534.73  4633.3  532.28  4675.9  532.39  4693.8  531.53
  4895.3  528.22  4935.4  527.34  4975.5  527.61  4980.2  526.75  5005.3  523.78
  5015.6  526.69  5025.7     528  5079.1  527.51  5095.9  526.91  5105.9   525.3
  5115.9  525.21    5146  527.68  5246.3  529.09  5276.4  530.98  5316.5  531.39
  5336.6  534.02  5457.9  537.77  5497.1  540.03  5547.3  541.06  5582.1   543.1
#Mann= 4 ,-1 , 0
  4005.5     .05       0  4895.3     .07       0  5025.7     .16       0
  5079.1     .05       0
Bank Sta=4980.2,5025.7
XS Rating Curve= 0 ,0
Exp/Cntr=0.3,0.1

Type RM Length L Ch R = 1 ,31052   ,1335,1335,1335
BEGIN DESCRIPTION:
MUSTANG CREEK 34.0
END DESCRIPTION:
XS GIS Cut Line= 2
      3405874.76     10598822.02      3405708.09     10597120.67
#Sta/Elev= 30
  3863.6   539.5  4054.9  537.67  4143.8  537.44  4165.4  536.56  4306.1  534.86
  4458.4  533.93  4718.1  529.78  4898.9  525.13  4939.1  524.91  4979.3  525.75
  4989.3  524.86  4999.1   522.5  5009.4  523.49  5019.5   525.5  5029.5  526.13
  5067.5  524.55  5079.8  524.59  5099.9  523.16    5130  524.79  5174.1  525.51
  5240.5  528.86  5260.6  529.21  5270.6  529.86  5280.7  531.41  5391.3  536.88
  5441.5  538.42  5483.7  541.32  5531.9  543.23    5552  545.11  5573.1  545.52
#Mann= 3 , 0 , 0
  3863.6     .05       0  4979.3     .03       0  5029.5     .05       0
Bank Sta=4979.3,5029.5
XS Rating Curve= 0 ,0
Exp/Cntr=0.3,0.1

Type RM Length L Ch R = 1 ,29717   ,1500,1500,1500
BEGIN DESCRIPTION:
MUSTANG CREEK 33.0
END DESCRIPTION:
XS GIS Cut Line= 3
      3407020.62      10598169.3       3406631.7     10597578.98
      3406555.32      10596669.3
#Sta/Elev= 30
  3744.8  533.79  3885.7   533.3  3951.3  533.48  4038.7  532.83  4074.8  532.96
    4117  532.26  4255.5  531.47  4499.2  527.41  4630.4  524.65  4669.8  523.38
    4720  523.16  4760.1  523.78  4800.3  523.35  4840.4  522.14  4870.5   521.6
  4930.7  522.03  4985.3  521.99  5000.7  519.48    5011  521.66  5021.1  522.46
  5091.3   520.7  5111.4     521  5121.4  521.68    5156  525.74  5171.6  527.51
  5225.3  529.94  5231.8  530.49    5292  532.68  5322.1   533.2  5364.6  532.97
#Mann= 4 ,-1 , 0
  3744.8     .05       0  4985.3     .07       0  5021.1     .16       0
    5156     .05       0
Bank Sta=4985.3,5021.1
XS Rating Curve= 0 ,0
Exp/Cntr=0.3,0.1

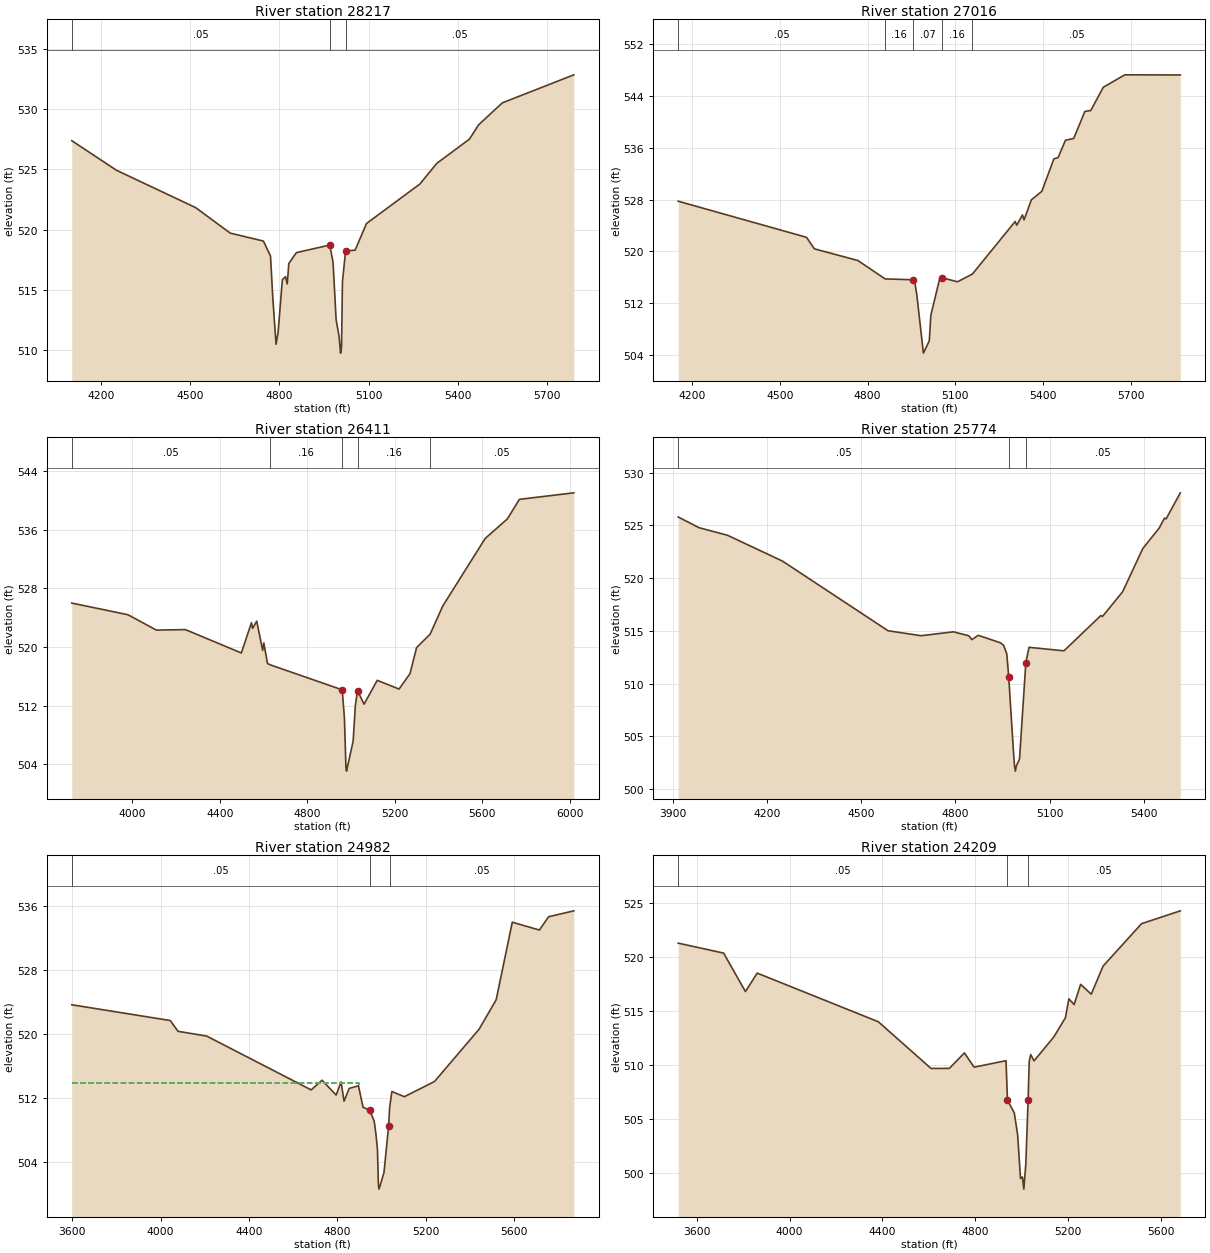
Type RM Length L Ch R = 1 ,28217   ,1201,1201,1201
BEGIN DESCRIPTION:
MUSTANG CREEK 32.0
END DESCRIPTION:
XS GIS Cut Line= 4
      3407951.15     10597009.53      3407777.54     10596440.09
      3407215.04      10596238.7      3406721.96     10596217.87
#Sta/Elev= 30
  4102.5  527.39  4252.7  524.93  4518.5  521.83  4634.7  519.71  4746.1  519.05
    4770  517.81  4777.9  514.25  4788.6  510.48  4795.5  511.46  4809.8  515.84
  4820.4  516.09  4826.2  515.49  4831.5  517.19    4857  518.09  4969.1  518.72
  4980.1  517.27  4990.4  512.52  5000.2  511.15  5005.3  509.74  5008.5  510.24
  5011.6  515.66  5022.2  518.24  5054.1  518.29  5092.5  520.51  5271.8  523.79
  5328.2   525.5  5438.3  527.52  5468.4  528.69  5548.4  530.53  5788.8  532.86
#Mann= 3 ,-1 , 0
  4102.5     .05       0  4969.1     .03       0  5022.2     .05       0
Bank Sta=4969.1,5022.2
XS Rating Curve= 0 ,0
Exp/Cntr=0.3,0.1

Type RM Length L Ch R = 1 ,27016   ,605,605,605
BEGIN DESCRIPTION:
MUSTANG CREEK 30.0
END DESCRIPTION:
XS GIS Cut Line= 4
      3408131.69     10596995.68      3408333.09     10596377.59
      3408576.15     10595717.87      3408465.04     10595370.66
#Sta/Elev= 30
  4152.1  527.74    4591  522.18  4617.7  520.41  4766.4  518.61  4860.2  515.77
  4955.4  515.64  4960.7  515.49  4968.4   513.3  4990.9  504.34    5011  506.23
  5016.3  510.18  5046.7  515.82  5053.6  515.96  5107.6  515.33  5158.5  516.52
  5304.8  524.62  5310.1  524.04  5329.9  525.62  5335.2  524.87  5360.4  527.96
  5396.1  529.27  5437.3  534.27  5451.7  534.46  5476.8  537.13  5505.2  537.41
  5543.3  541.57  5563.4  541.71  5606.3  545.29  5679.8  547.21  5869.8  547.19
#Mann= 5 ,-1 , 0
  4152.1     .05       0  4860.2     .16       0  4955.4     .07       0
  5053.6     .16       0  5158.5     .05       0
Bank Sta=4955.4,5053.6
XS Rating Curve= 0 ,0
Exp/Cntr=0.3,0.1

Type RM Length L Ch R = 1 ,26411   ,637,637,637
BEGIN DESCRIPTION:
MUSTANG CREEK 29.0
END DESCRIPTION:
XS GIS Cut Line= 4
       3408708.1     10597391.47       3408881.7     10596509.54
       3408881.7     10595578.98      3408763.64     10595127.58
#Sta/Elev= 30
  3723.3  525.99    3980   524.4  4110.4   522.3  4242.9  522.37  4498.8  519.18
  4545.1  523.31  4550.2  522.53  4569.1  523.52  4596.4  519.54  4601.5  520.54
  4618.5  517.74  4631.9  517.55  4960.1  514.15  4970.1  510.34  4977.1  503.56
  4979.8  503.06  5010.1  507.17  5020.1  512.03  5030.1     514  5060.1   512.2
  5120.1  515.45  5220.1  514.26  5270.1  516.36  5300.1  519.91  5362.1  521.75
  5420.1   525.6  5613.8   534.8  5715.3  537.47  5770.3  540.14  6019.3  541.03
#Mann= 5 ,-1 , 0
  3723.3     .05       0  4631.9     .16       0  4960.1     .07       0
  5030.1     .16       0  5362.1     .05       0
Bank Sta=4960.1,5030.1
XS Rating Curve= 0 ,0
Exp/Cntr=0.3,0.1

Type RM Length L Ch R = 1 ,25774   ,792,792,792
BEGIN DESCRIPTION:
MUSTANG CREEK 28.0
END DESCRIPTION:
XS GIS Cut Line= 2
      3409298.37     10597106.76      3409534.24     10595525.05
#Sta/Elev= 30
  3917.4  525.79  3983.2  524.78  4074.2  524.06  4249.5  521.61  4585.8  515.01
    4691  514.54  4793.7  514.91  4842.6  514.54  4852.7  514.17    4873  514.58
  4943.7  513.87  4953.9  513.62 4963.93  512.81 4970.06  510.65  4984.2  503.98
  4988.4  502.21  4991.2  501.71  4994.4  502.21  5004.4  502.84  5024.6  511.99
  5034.7  513.44    5146  513.11  5263.5  516.45  5268.6  516.36  5332.8   518.7
  5397.1   522.8  5449.3  524.74  5466.3  525.69  5471.4  525.61  5516.6  528.08
#Mann= 3 , 0 , 0
  3917.4     .05       0 4970.06     .07       0  5024.6     .05       0
Bank Sta=4970.06,5024.6
XS Rating Curve= 0 ,0
Exp/Cntr=0.3,0.1

Type RM Length L Ch R = 1 ,24982   ,773,773,773
BEGIN DESCRIPTION:
MUSTANG CREEK 26.0
END DESCRIPTION:
XS GIS Cut Line= 3
      3411103.94     10596822.06      3410590.04     10596127.59
       3409445.7     10595309.21
#Sta/Elev= 30
  3598.6   523.6    4044  521.63  4079.4  520.28  4208.7  519.69  4681.3  512.96
  4730.5  514.17  4794.4  512.32  4816.5  513.96  4830.1  511.55  4853.4  513.15
  4895.2  513.47  4916.1  510.79  4945.6  510.43  4966.5  509.05    4975  507.28
  4981.2  505.52  4985.6  501.06  4988.4  500.56  5010.7  502.64  5031.6  508.45
 5036.22  510.74  5046.3  512.76  5102.8  512.11  5239.2  514.01  5440.7  520.54
  5518.1  524.22    5591  533.92  5713.5  532.94  5755.3   534.6  5869.4  535.34
#Mann= 3 ,-1 , 0
  3598.6     .05       0  4945.6     .07       0 5036.22     .05       0
#XS Ineff= 2 , 0
         4896.31  513.82
Permanent Ineff=
       F       F
Bank Sta=4945.6,5031.6
XS Rating Curve= 0 ,0
Exp/Cntr=0.3,0.1

Type RM Length L Ch R = 1 ,24209   ,1354,1354,1354
BEGIN DESCRIPTION:
MUSTANG CREEK 25.0
END DESCRIPTION:
XS GIS Cut Line= 4
      3411235.87     10596328.99      3410985.87     10595495.65
       3410319.2     10594995.65      3410124.75     10594578.96
#Sta/Elev= 30
  3520.6  521.29  3716.2  520.37  3810.2  516.81  3860.7  518.52  4382.7  514.02
  4609.9   509.7    4689  509.71  4753.6  511.14  4795.3  509.82  4932.8  510.42
 4939.17  506.75  4968.2  505.61  4982.8  503.61  4995.3  499.52  5003.6  499.66
  5009.6  498.54  5018.2  500.87 5028.15  506.82  5032.8  510.35    5039  510.99
  5053.6   510.4    5139  512.62    5189   514.4  5203.6  516.14  5226.4  515.61
  5254.3  517.48    5300  516.57  5351.2  519.17  5516.8  523.09  5683.8  524.28
#Mann= 3 , 0 , 0
  3520.6     .05       0 4939.17     .07       0 5028.15     .05       0
Bank Sta=4939.17,5028.15
XS Rating Curve= 0 ,0
Exp/Cntr=0.3,0.1