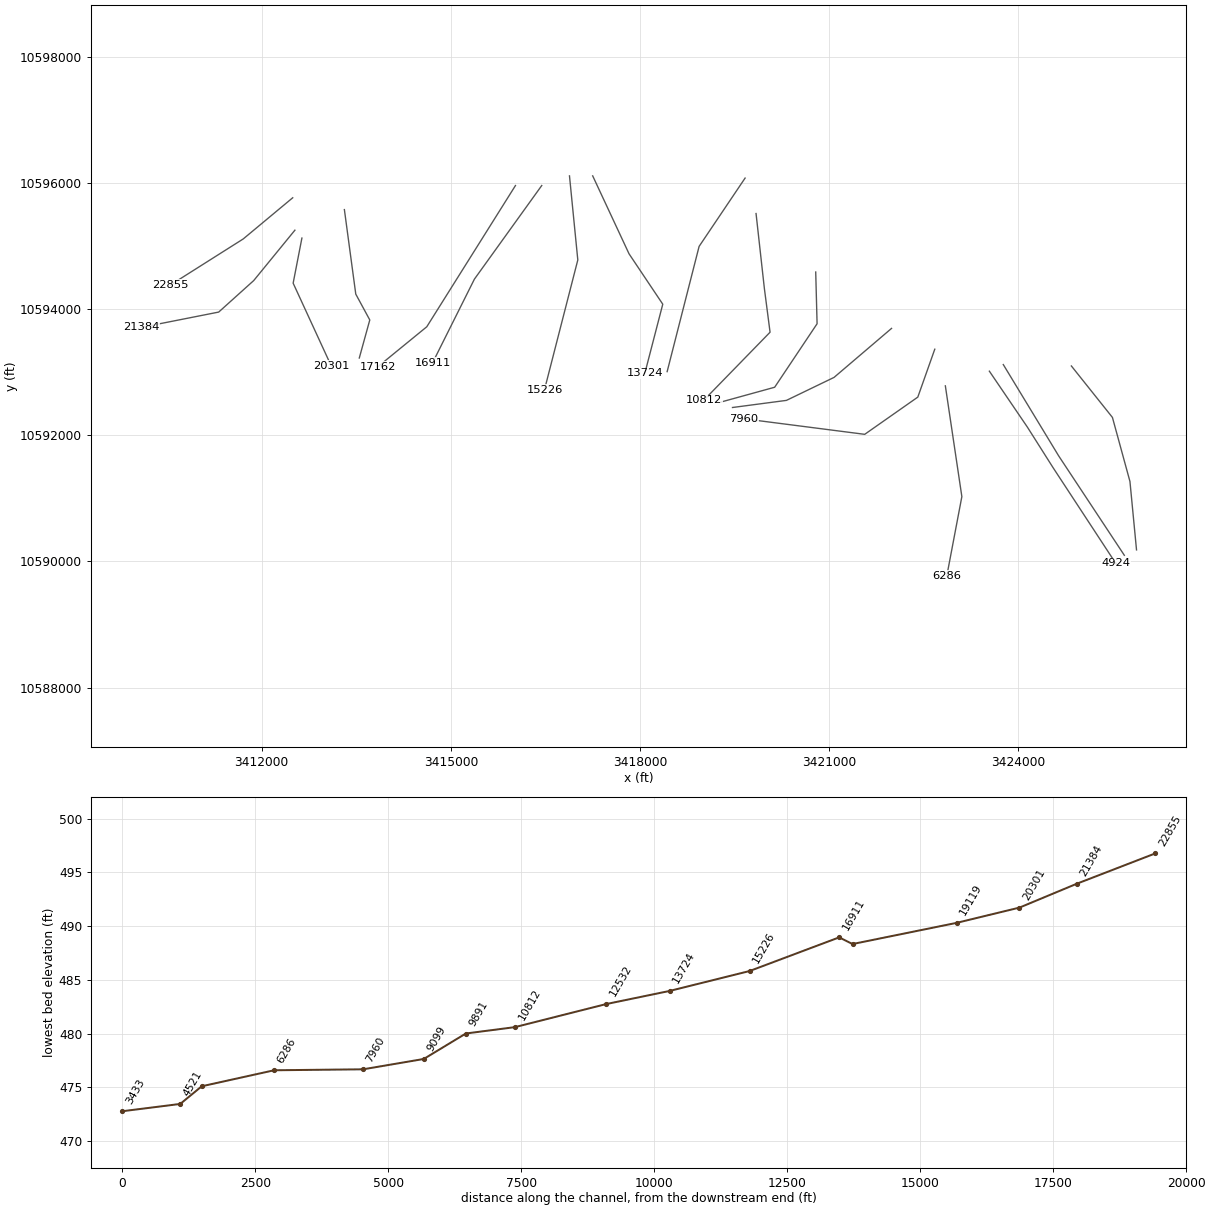
HEC-RAS study MUSTANG CREEK.prj: MUSTANG CREEK Base Level Engineering

--- MUSTANG CREEK.g01 (geometry) --- (continued)

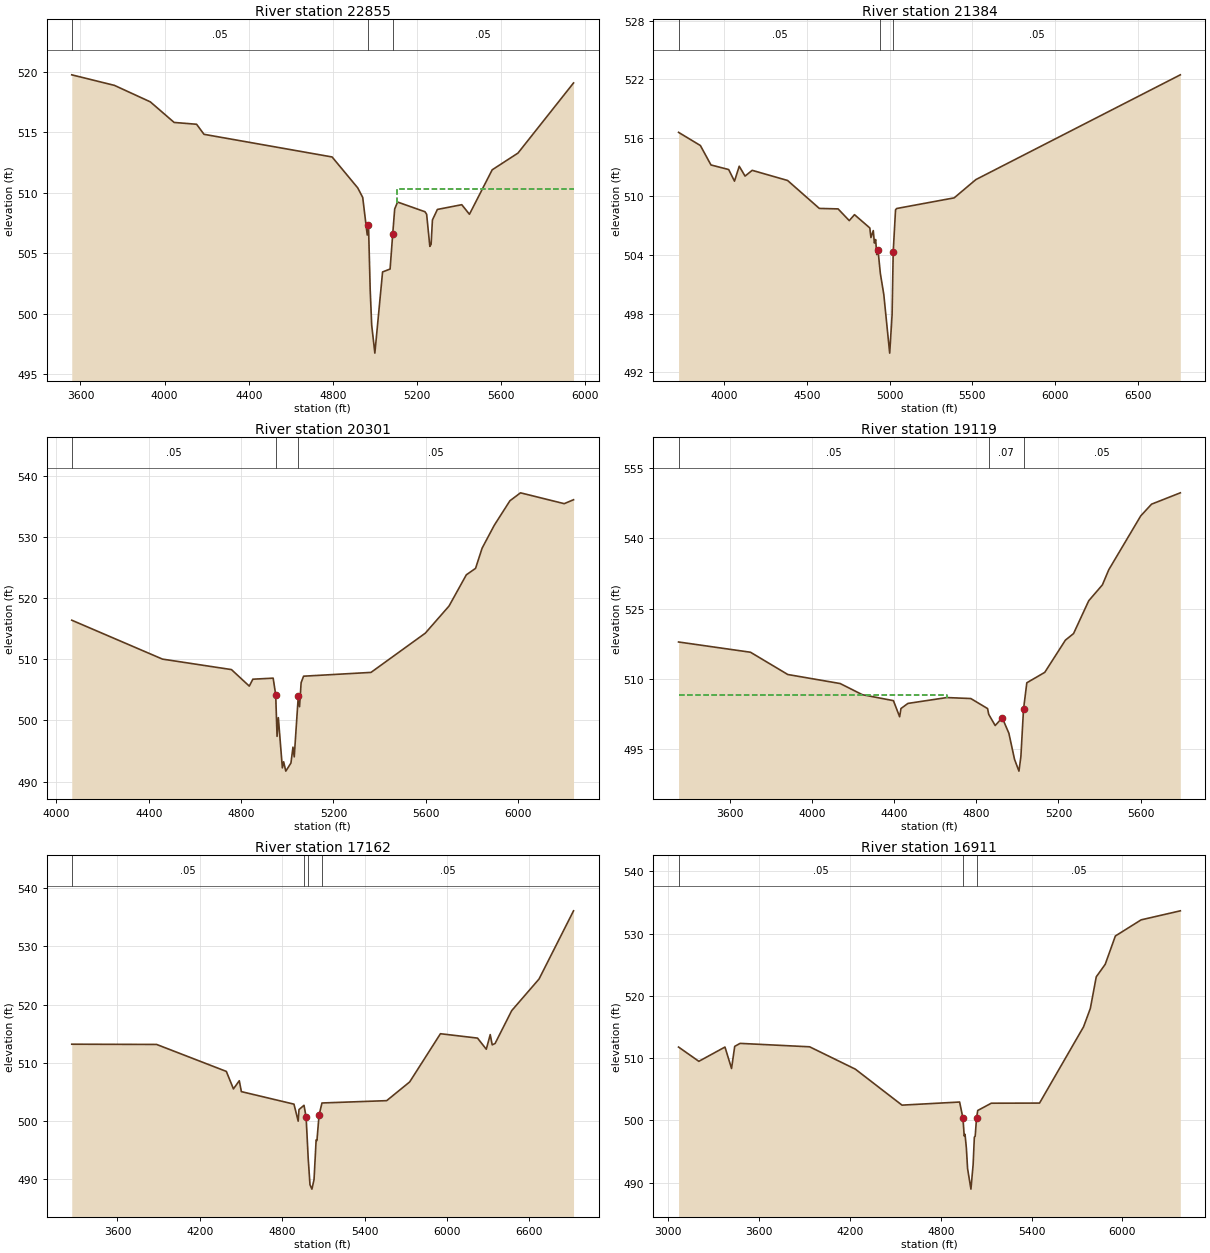
Type RM Length L Ch R = 1 ,22855   ,1471,1471,1471
BEGIN DESCRIPTION:
MUSTANG CREEK 22.0
END DESCRIPTION:
XS GIS Cut Line= 3
      3412492.79     10595766.46      3411708.09      10595113.7
      3410555.34     10594384.55
#Sta/Elev= 30
  3558.5  519.73  3761.2  518.86  3931.8   517.5  4045.1   515.8  4151.8  515.65
    4187  514.82  4795.8  512.95  4917.6   510.4  4941.3  509.61  4962.8  506.51
  4968.7  507.37  4976.8     502    4984  499.07    4999  496.76  5035.7  503.46
  5071.4   503.7    5084  506.62  5093.3  508.66  5106.9  509.23  5237.1  508.43
  5245.1  508.22  5260.3  505.57  5266.3  505.74  5272.6  507.75  5296.2  508.62
  5412.1  509.01  5448.5  508.22  5556.6  511.89  5679.1  513.27  5943.2  519.06
#Mann= 3 , 0 , 0
  3558.5     .05       0  4968.7     .07       0    5084     .05       0
#XS Ineff= 2 , 0
                         5105.11          510.33
Permanent Ineff=
       F       F
Bank Sta=4968.7,5084
XS Rating Curve= 0 ,0
Exp/Cntr=0.3,0.1

Type RM Length L Ch R = 1 ,21384   ,1083,1083,1083
BEGIN DESCRIPTION:
MUSTANG CREEK 21.0
END DESCRIPTION:
XS GIS Cut Line= 4
      3412527.56     10595252.62      3411874.76     10594453.98
       3411319.2     10593953.98      3410090.02     10593710.92
#Sta/Elev= 30
    3725  516.56    3857  515.21  3920.9  513.22  4027.9  512.75    4063  511.56
  4091.7  513.09  4126.9  512.08    4170  512.67  4383.9  511.63  4575.6  508.77
    4689  508.72  4756.5  507.52  4788.1  508.13  4880.7  506.77  4887.5  505.79
  4901.7   506.5  4908.4  505.22  4915.9  505.58  4922.6  504.04  4930.1  504.53
  4944.3  502.12  4965.2  499.96  5000.8  493.95  5015.3  497.88    5022  504.29
  5036.2  508.63  5042.9  508.76  5390.5  509.85  5521.3  511.72  6756.9  522.45
#Mann= 3 ,-1 , 0
    3725     .05       0  4944.3     .07       0    5022     .05       0
Bank Sta=4930.1,5022
XS Rating Curve= 0 ,0
Exp/Cntr=0.3,0.1

Type RM Length L Ch R = 1 ,20301   ,1182,1182,1182
BEGIN DESCRIPTION:
MUSTANG CREEK 20.0
END DESCRIPTION:
XS GIS Cut Line= 3
      3412638.64     10595127.55      3412499.76     10594412.31
      3413103.94     10593099.79
#Sta/Elev= 30
  4066.3  516.38  4459.4  510.02  4758.1  508.31  4835.3  505.61  4850.7  506.74
  4938.7  506.91  4949.7  504.21  4955.6   497.4  4961.1  500.46  4978.6  492.25
  4984.1  493.24  4993.5  491.72  5015.8  493.05  5024.5  495.64    5030  494.05
  5047.5  503.94    5053  502.24  5059.8  506.16  5070.4  507.23  5362.5  507.85
  5597.7  514.26  5700.6   518.7  5775.4  523.79  5815.4  524.85  5843.9  528.16
  5896.5  531.89  5964.2  535.89  6010.1  537.19  6199.4  535.42  6239.8  536.06
#Mann= 3 , 0 , 0
  4066.3     .05       0  4949.7     .07       0  5047.5     .05       0
Bank Sta=4949.7,5047.5
XS Rating Curve= 0 ,0
Exp/Cntr=0.3,0.1

Type RM Length L Ch R = 1 ,19119   ,1957,1957,1957
BEGIN DESCRIPTION:
MUSTANG CREEK 17.0
END DESCRIPTION:
XS GIS Cut Line= 4
      3413312.25     10595579.01      3413492.81      10594238.7
      3413715.04     10593828.98      3413548.62     10593225.74
#Sta/Elev= 30
  3349.7  517.86  3700.2  515.67  3881.8  510.92  4137.1  508.99  4245.1  506.61
  4396.4  505.34  4426.7   501.9  4433.2  503.66  4467.1  504.75  4656.5     506
  4773.4  505.79  4855.1  503.65  4860.8   502.4  4892.2  500.03  4926.4  501.69
  4958.8  498.39  4986.3  492.83  5007.9   490.3  5017.3  493.38  5030.1  503.47
  5046.2  509.15  5133.7  511.38  5234.3  518.26  5273.8  519.65  5347.7  526.65
  5414.4  530.05  5445.5  533.28  5601.2  544.77  5653.8  547.27    5794  549.69
#Mann= 3 ,-1 , 0
  3349.7     .05       0  4860.8     .07       0  5030.1     .05       0
#XS Ineff= 2 , 0
         4658.52   506.6
Permanent Ineff=
       F       F
Bank Sta=4926.4,5030.1
XS Rating Curve= 0 ,0
Exp/Cntr=0.3,0.1

Type RM Length L Ch R = 1 ,17162   ,251,251,251
BEGIN DESCRIPTION:
MUSTANG CREEK 15.0
END DESCRIPTION:
XS GIS Cut Line= 3
      3416025.05     10595960.56      3414618.79     10593720.96
      3413837.52     10593082.92
#Sta/Elev= 30
  3267.5  513.21  3885.2  513.17  4392.9  508.54  4444.7  505.54  4487.2  506.94
  4502.5  505.07  4885.3  502.92    4916     500  4921.9  501.99  4958.4  502.72
  4973.7  500.71    4989  493.61    5002  489.08  5015.9  488.33  5031.4  489.96
  5046.7  496.78  5052.6  496.67  5067.9  501.01  5089.1  503.12  5560.4  503.52
  5727.6  506.73  5951.7  515.01  6221.6  514.26  6285.5  512.35  6314.2  514.86
  6328.6   513.1  6349.4  513.33  6470.7  518.98  6669.5   524.4  6920.7  536.11
#Mann= 4 ,-1 , 0
  3267.5     .05       0  4958.4     .07       0    4989     .07       0
  5089.1     .05       0
Bank Sta=4973.7,5067.9
XS Rating Curve= 0 ,0
Exp/Cntr=0.3,0.1

Type RM Length L Ch R = 1 ,16911   ,1685,1685,1685
BEGIN DESCRIPTION:
MUSTANG CREEK 13.0
END DESCRIPTION:
XS GIS Cut Line= 3
      3416441.69     10595960.53      3415373.99     10594476.17
      3414709.91     10593148.01
#Sta/Elev= 30
  3068.7  511.77  3202.8  509.48  3375.3  511.77  3418.7  508.33  3439.6  511.88
  3475.2  512.36  3934.3  511.81  4236.2  508.22  4544.3  502.44  4924.6  502.94
    4947  500.33  4954.9  497.49  4960.5  497.75  4969.3  495.55  4977.3  492.25
  4999.4  488.95    5014  492.92    5022   497.3  5027.6  497.46  5036.4  500.36
  5044.4  501.58  5133.8  502.75  5452.4  502.77  5743.1  515.02  5787.9  517.97
    5827  523.05  5886.1  525.06  5953.2  529.61  6123.3   532.2  6382.1  533.65
#Mann= 3 , 0 , 0
  3068.7     .05       0    4947     .07       0  5036.4     .05       0
Bank Sta=4947,5036.4
XS Rating Curve= 0 ,0
Exp/Cntr=0.3,0.1

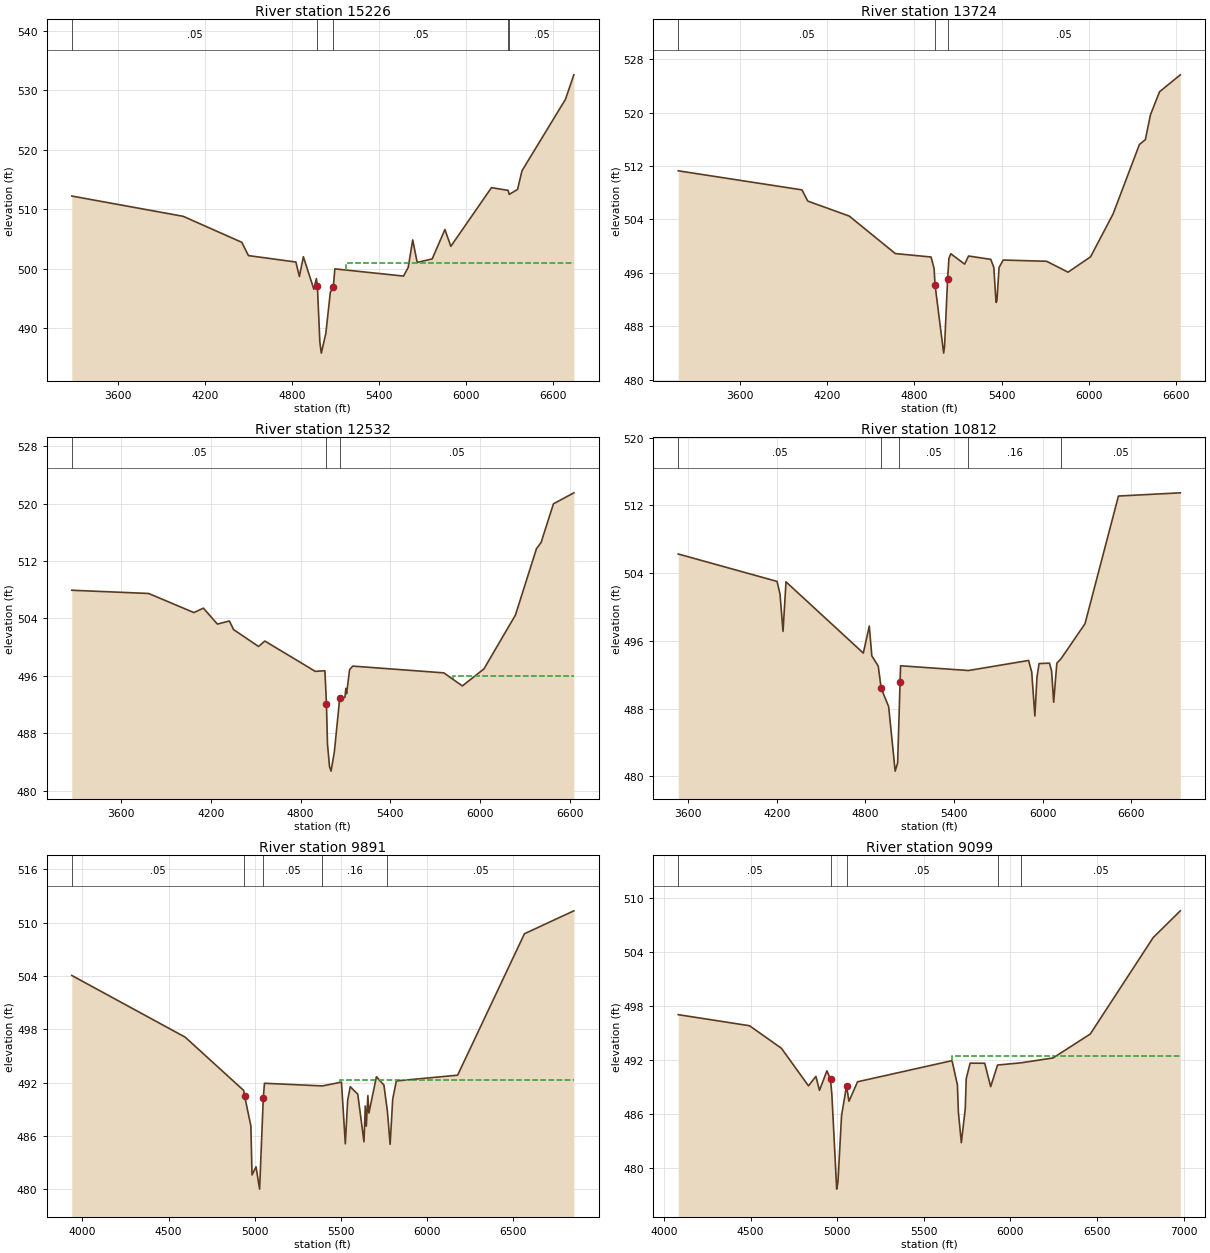
Type RM Length L Ch R = 1 ,15226   ,1502,1502,1502
BEGIN DESCRIPTION:
MUSTANG CREEK 10.0
END DESCRIPTION:
XS GIS Cut Line= 3
       3416881.7     10596113.74      3417013.65     10594780.37
       3416486.1      10592725.7
#Sta/Elev= 30
  3280.1  512.22  4048.4  508.81  4452.5  504.44  4498.1  502.21  4825.2  501.13
  4849.2  498.69  4876.8  502.02  4949.1  496.55  4966.3  498.35 4973.42   497.1
  4990.3   487.7  5000.4  485.82  5031.6  489.14  5062.6  496.05  5083.3  496.95
  5093.7  499.98  5567.2  498.77  5599.5  500.24  5630.5  504.85  5661.4  501.06
  5764.7  501.65  5852.5  506.59  5893.3  503.77  6173.4  513.63  6288.4  513.17
  6295.7  512.49  6353.2  513.33  6384.1  516.48  6683.5  528.47  6741.3  532.59
#Mann= 5 ,-1 , 0
  3280.1     .05       0 4973.42     .07       0  5083.3     .05       0
  6288.4      .1       0  6295.7     .05       0
#XS Ineff= 2 , 0
         4870.45  501.25 5172.95          500.95
Permanent Ineff=
       F       F
Bank Sta=4973.42,5083.3
XS Rating Curve= 0 ,0
Exp/Cntr=0.3,0.1

Type RM Length L Ch R = 1 ,13724   ,1192,1192,1192
BEGIN DESCRIPTION:
MUSTANG CREEK 9.0
END DESCRIPTION:
XS GIS Cut Line= 4
      3417249.75     10596113.72      3417826.15     10594877.59
      3418360.87     10594078.98      3418076.62     10592983.56
#Sta/Elev= 30
  3173.8  511.29  4025.7  508.43  4065.5  506.75  4350.9  504.51  4668.2  498.89
  4914.4  498.37  4935.4  496.66    4942  494.18  5001.2  483.97  5007.5  485.02
  5028.5  495.13  5037.5  498.16  5050.3  498.86  5145.6  497.31  5172.6  498.52
  5325.7  498.02  5346.7   496.8  5361.7  491.57  5367.7  491.77  5382.7  496.81
  5411.4  497.92  5710.3  497.73  5857.6   496.1  6012.6   498.4  6167.6  504.82
  6349.1  515.24  6389.7  515.95  6425.1  519.69  6487.8  523.14  6630.5  525.67
#Mann= 3 , 0 , 0
  3173.8     .05       0    4942     .07       0  5028.5     .05       0
#XS Ineff= 2 , 0
       0                 5313.64       0  497.83
Permanent Ineff=
       F       T
Bank Sta=4942,5028.5
XS Rating Curve= 0 ,0
Exp/Cntr=0.3,0.1

Type RM Length L Ch R = 1 ,12532   ,1720,1720,1720
BEGIN DESCRIPTION:
MUSTANG CREEK 7.0
END DESCRIPTION:
XS GIS Cut Line= 3
      3419666.43     10596078.98      3418937.26     10594995.65
       3418430.3      10593009.5
#Sta/Elev= 30
  3271.2  507.93  3784.8  507.48  4087.7  504.82  4150.8  505.44  4244.4  503.22
  4324.7  503.65  4352.9  502.45  4519.6   500.1  4561.6  500.86  4898.6  496.64
  4963.1  496.72  4973.4  492.16  4980.3  486.54    4994  483.39  5004.1  482.75
  5026.3  485.44    5062   492.9  5097.2  493.03  5102.9  494.27    5108  493.53
  5128.2  496.88  5148.9  497.37  5757.8  496.43  5881.6  494.61  6026.1  496.98
  6236.6  504.48    6377  513.71    6408  514.58  6490.5  519.96  6626.9  521.49
#Mann= 3 , 0 , 0
  3271.2     .05       0  4973.4     .03       0    5062     .05       0
#XS Ineff= 2 , 0
                         5815.91          495.96
Permanent Ineff=
       F       F
Bank Sta=4973.4,5062
XS Rating Curve= 0 ,0
Exp/Cntr=0.3,0.1

Type RM Length L Ch R = 1 ,10812   ,921,921,921
BEGIN DESCRIPTION:
MUSTANG CREEK 6.0
END DESCRIPTION:
XS GIS Cut Line= 4
      3419840.04     10595516.46      3419971.98     10594328.98
      3420062.26     10593634.54      3419013.65     10592558.15
#Sta/Elev= 30
    3534  506.26  4202.9  503.02    4223  501.51  4243.2  497.11  4263.3  502.97
  4786.6  494.55  4826.9  497.75  4844.1  494.22  4887.5  493.02  4907.6  490.39
    4958  488.22  5002.1   480.6  5018.5  481.55  5028.6  487.19  5035.3  491.13
  5038.7  493.05  5498.2  492.49  5905.1  493.68  5926.2  492.31  5947.5  487.12
  5961.7  491.69  5975.8  493.31  6046.5  493.36  6060.7  492.44  6074.8  488.74
    6096  493.35  6124.9  493.89  6286.8  498.02  6513.2  513.11  6931.8  513.49
#Mann= 5 ,-1 , 0
    3534     .05       0  4907.6     .07       0  5028.6     .05       0
  5498.2     .16       0  6124.9     .05       0
#XS Ineff= 2 , 0
       0                 5905.63       0  493.05
Permanent Ineff=
       F       T
Bank Sta=4907.6,5035.3
XS Rating Curve= 0 ,0
Exp/Cntr=0.3,0.1

Type RM Length L Ch R = 1 ,9891    ,792,792,792
BEGIN DESCRIPTION:
MUSTANG CREEK 4.0
END DESCRIPTION:
XS GIS Cut Line= 4
      3420786.25     10594589.15      3420807.95     10593768.86
      3420135.21     10592761.91      3419285.83      10592527.9
#Sta/Elev= 30
  3937.8  504.05  4595.5  497.11  4934.7  491.12  4940.7  490.47  4976.7  487.13
  4983.5  481.61  5006.7  482.52  5027.5  480.01  5048.8  490.25  5055.7  491.92
  5391.8  491.62  5502.3  492.05  5524.7  485.11  5538.3  490.01  5553.4  491.53
  5596.9  490.69    5633  485.34  5640.5  489.36  5646.5  487.09  5655.5  490.53
  5661.5  488.57  5705.1  492.65  5748.6  491.72    5769  488.75  5784.6  485.05
  5799.6  490.14  5820.7  492.18  6176.2  492.83  6563.8  508.74  6850.4  511.32
#Mann= 5 ,-1 , 0
  3937.8     .05       0  4934.7     .07       0  5048.8     .05       0
  5391.8     .16       0    5769     .05       0
#XS Ineff= 2 , 0
       0                 5495.74       0  492.27
Permanent Ineff=
       F       T
Bank Sta=4940.7,5048.8
XS Rating Curve= 0 ,0
Exp/Cntr=0.3,0.1

Type RM Length L Ch R = 1 ,9099    ,1139,1139,1139
BEGIN DESCRIPTION:
MUSTANG CREEK 2.0
END DESCRIPTION:
XS GIS Cut Line= 4
      3421988.51     10593695.08      3421077.05     10592918.16
      3420321.84     10592553.58      3419466.91     10592440.75
#Sta/Elev= 30
  4082.1  497.03  4493.6   495.8  4678.1  493.29    4834  489.12  4876.8  490.17
  4897.7  488.62  4940.5  490.79  4961.3  489.83  4969.1  488.14  4996.9  477.64
  5004.2  478.42    5025  485.82  5053.6   489.1  5067.9  487.41  5117.3  489.57
  5662.8  491.92  5693.9  489.23  5699.5   486.2  5716.5   482.8  5739.1  486.56
  5744.7  489.91  5767.3  491.64  5851.6  491.63  5885.9  489.03  5925.5  491.43
  6061.9  491.68    6246  492.22    6461  494.88  6824.2   505.6  6980.7  508.57
#Mann= 5 ,-1 , 0
  4082.1     .05       0  4961.3     .07       0  5053.6     .05       0
  5925.5     .16       0  6061.9     .05       0
#XS Ineff= 2 , 0
       0                 5661.93       0  492.39
Permanent Ineff=
       F       T
Bank Sta=4961.3,5053.6
XS Rating Curve= 0 ,0
Exp/Cntr=0.3,0.1

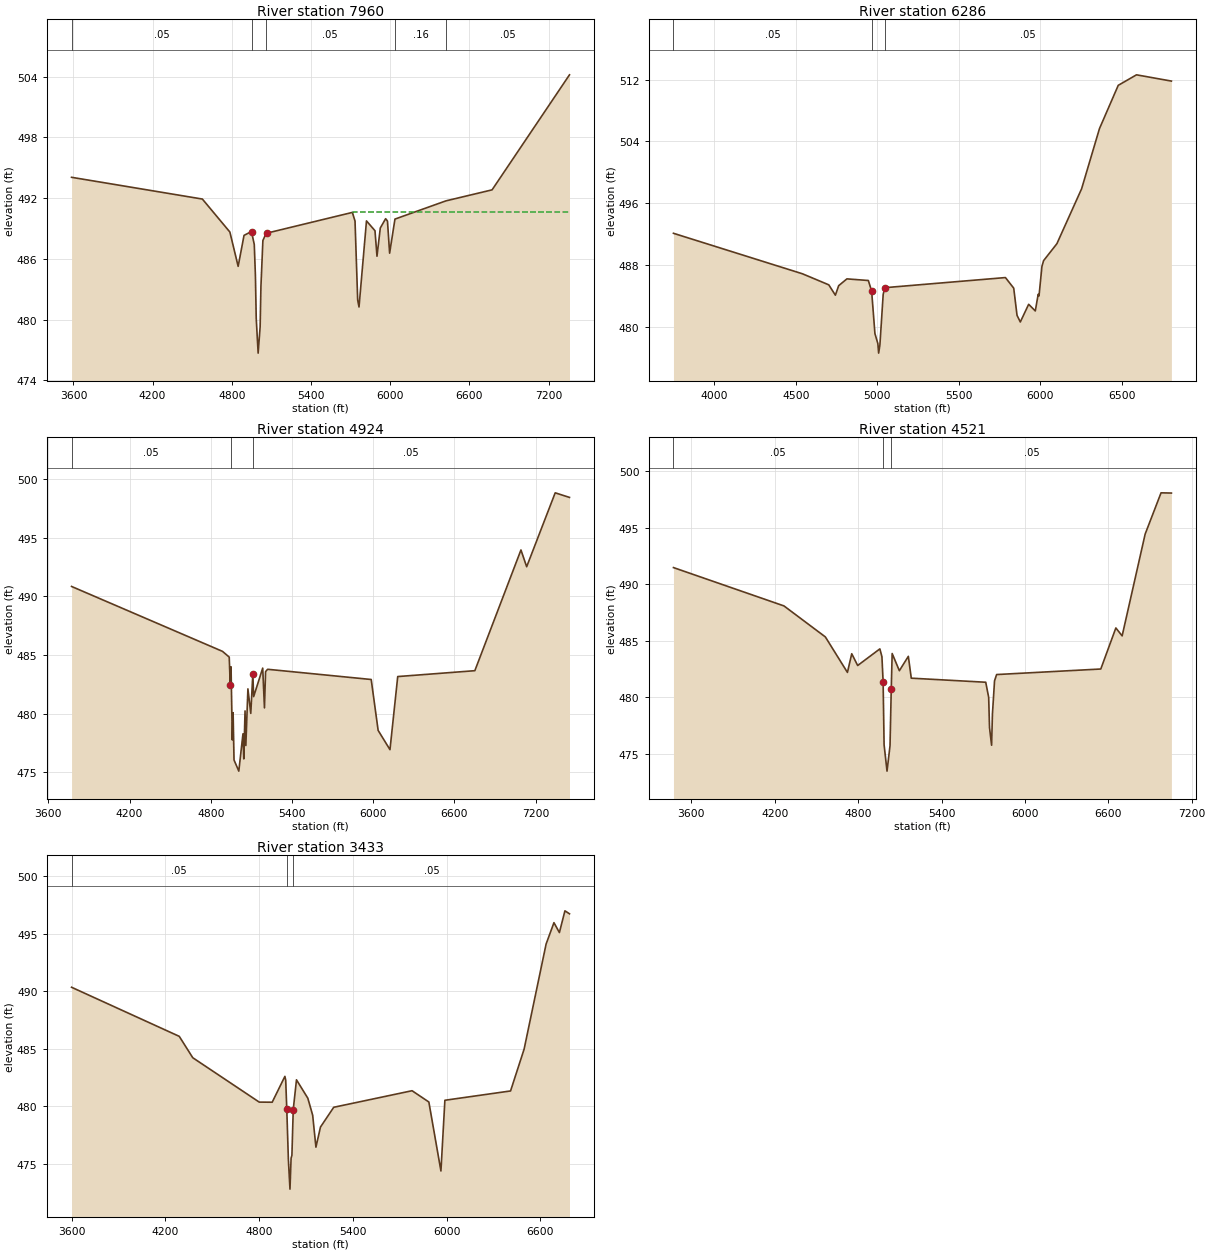
Type RM Length L Ch R = 1 ,7960    ,1674,1674,1674
BEGIN DESCRIPTION:
MUSTANG CREEK 1.0
END DESCRIPTION:
XS GIS Cut Line= 4
      3422674.29     10593365.26      3422405.18     10592605.66
      3421563.16     10592015.39      3419640.37     10592262.79
#Sta/Elev= 30
  3585.9  494.06  4577.1  491.91  4785.5  488.65  4848.2  485.26  4892.7  488.32
  4949.3   488.7  4970.3  487.42    4979  484.31  4985.1  480.12  4999.6  476.68
  5014.7  479.28  5020.8   483.3  5035.6  487.81  5056.6  488.42  5065.3  488.54
  5713.5  490.59  5733.7  489.73  5753.8  481.93  5763.9  481.24  5820.5  489.75
  5884.9  488.78  5900.1  486.26  5925.2  489.05  5965.6  489.97  5979.6  489.73
  5995.8  486.56  6036.2  489.93  6422.3  491.73  6772.2  492.82  7358.7  504.19
#Mann= 5 ,-1 , 0
  3585.9     .05       0  4949.3     .07       0  5056.6     .05       0
  6036.2     .16       0  6422.3     .05       0
#XS Ineff= 2 , 0
       0                 5714.61       0  490.62
Permanent Ineff=
       F       T
Bank Sta=4949.3,5065.3
XS Rating Curve= 0 ,0
Exp/Cntr=0.3,0.1

Type RM Length L Ch R = 1 ,6286    ,1362,1362,1362
BEGIN DESCRIPTION:
UNT0021 IN CHRS 1.4
END DESCRIPTION:
XS GIS Cut Line= 3
      3422841.92     10592783.97      3423103.63     10591027.64
      3422865.18     10589771.39
#Sta/Elev= 30
  3749.1   492.1  4540.1  486.86  4701.8  485.43  4742.3  484.09  4762.5  485.32
    4813   486.2  4944.5  485.99  4964.7  484.62  4984.9  479.12  5002.8  477.83
  5007.6  476.59  5015.3  477.62  5035.5  484.19  5045.6  485.06  5785.4  486.37
  5836.3     485  5856.6  481.48  5876.7  480.62  5927.9  482.91  5968.6  482.05
  5986.3   484.2  5991.4  483.99  6009.3  487.81  6019.5  488.56    6101  490.75
  6252.7  497.86  6362.3  505.65  6477.5  511.25  6589.5  512.61  6803.5   511.8
#Mann= 3 , 0 , 0
  3749.1     .05       0  4964.7     .07       0  5045.6     .05       0
#XS Ineff= 2 , 0
       0                 5778.96       0  486.33
Permanent Ineff=
       F       T
Bank Sta=4964.7,5045.6
XS Rating Curve= 0 ,0
Exp/Cntr=0.3,0.1

Type RM Length L Ch R = 1 ,4924    ,403,403,403
BEGIN DESCRIPTION:
UNT0021 IN CHRS 1.5
END DESCRIPTION:
XS GIS Cut Line= 5
      3423539.83     10593016.59      3424144.64     10592126.81
      3424545.93     10591492.89      3425552.05     10589957.54
      3425546.66      10589973.7
#Sta/Elev= 30
  3771.1  490.84  4885.8  485.31  4935.9  484.82  4943.5  482.44  4949.4  483.99
  4958.7  477.76  4964.6  480.08  4971.4  476.05  5006.8   475.1  5037.5  478.28
  5043.5  476.14  5052.8  480.23  5058.7  477.28    5074  482.11  5095.2  480.02
  5110.4   483.4  5116.4  481.45  5183.3  483.88  5196.3  480.49  5204.5  483.58
  5219.8  483.78  5984.9  482.91  6036.2  478.57  6123.6  476.93  6180.9  483.16
  6750.6  483.66  7091.3  493.95  7133.5  492.52  7344.3  498.82  7449.9  498.43
#Mann= 3 ,-1 , 0
  3771.1     .05       0  4949.4     .03       0  5110.4     .05       0
Bank Sta=4943.5,5110.4
XS Rating Curve= 0 ,0
Exp/Cntr=0.3,0.1

Type RM Length L Ch R = 1 ,4521    ,1088,1088,1088
BEGIN DESCRIPTION:
UNT0021 IN CHRS 1.6
END DESCRIPTION:
XS GIS Cut Line= 3
      3423760.79     10593121.31      3424638.98     10591673.18
      3425679.97     10590097.15
#Sta/Elev= 30
  3471.4  491.46  4266.3  488.07    4564  485.33    4723  482.19    4754  483.84
  4796.7   482.8  4956.3  484.27  4971.2  483.58  4979.7  481.36  4986.7   475.8
  5007.8  473.46  5029.4   475.7  5038.2   480.7  5044.8  483.86  5096.6  482.34
  5161.2  483.61  5182.3  481.68  5718.1  481.32  5739.2  479.98  5745.2  477.31
  5760.2  475.75  5766.2   478.5  5781.3  481.44  5796.3     482  6545.8  482.49
  6654.2  486.12  6699.4  485.42  6864.9  494.42  6979.3  498.07  7053.8  498.05
#Mann= 3 , 0 , 0
  3471.4     .05       0  4979.7     .04       0  5038.2     .05       0
Bank Sta=4979.7,5038.2
XS Rating Curve= 0 ,0
Exp/Cntr=0.3,0.1

Type RM Length L Ch R = 1 ,3433    ,1255,1255,1255
BEGIN DESCRIPTION:
UNT0021 IN CHRS 1.3
END DESCRIPTION:
XS GIS Cut Line= 4
      3424840.29     10593099.29      3425491.35      10592283.3
      3425769.13     10591267.67       3425873.3     10590182.59
#Sta/Elev= 30
  3600.1  490.34  4289.4  486.07  4375.9  484.21  4801.2  480.35  4884.2  480.34
  4965.5  482.59  4970.7  482.26  4977.5  479.76  4987.8  475.35    4998  472.78
  5005.2  475.48  5010.4  475.72  5018.9   479.7  5039.7  482.29  5112.2  480.69
  5143.3  479.21  5164.1  476.43  5193.2  478.18  5278.1   479.9  5779.4  481.34
  5886.9  480.36  5964.2  474.36  5989.5  480.51  6409.8  481.32  6496.6  484.96
  6637.3   494.1  6687.5  495.96  6722.4   495.1  6757.8  496.99    6787  496.73
#Mann= 3 , 0 , 0
  3600.1     .05       0  4977.5    .035       0  5018.9     .05       0
Bank Sta=4977.5,5018.9
XS Rating Curve= 0 ,0
Exp/Cntr=0.3,0.1