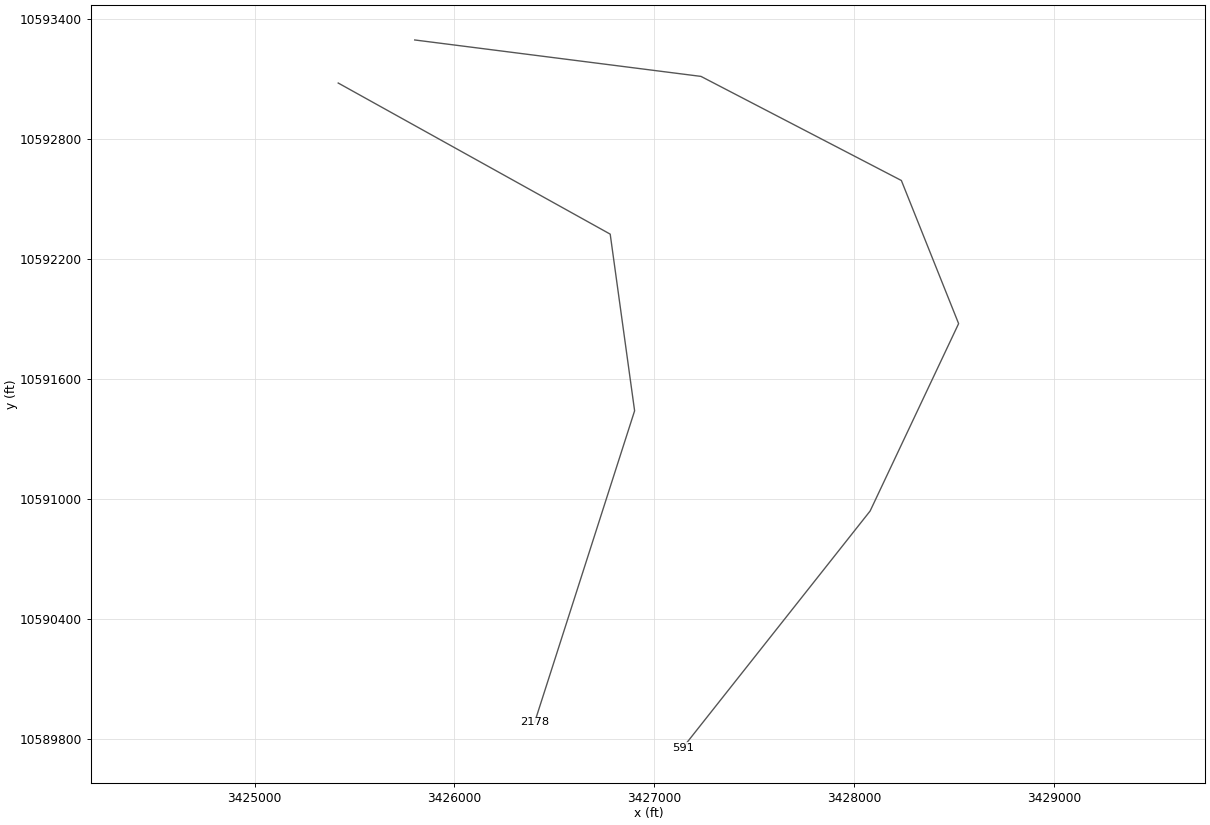
HEC-RAS study MUSTANG CREEK.prj: MUSTANG CREEK Base Level Engineering

--- MUSTANG CREEK.g01 (geometry) --- (continued)

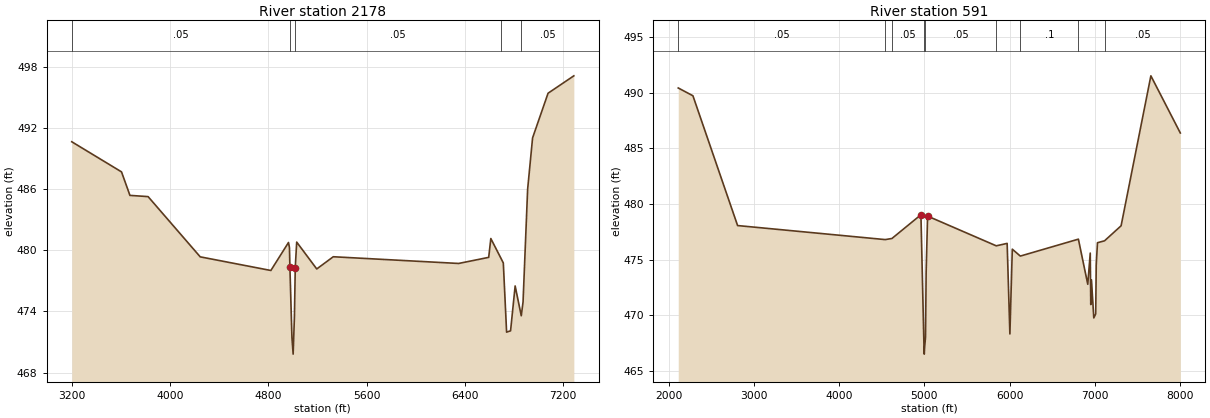
Type RM Length L Ch R = 1 ,2178    ,1600,1600,1600
BEGIN DESCRIPTION:
UNT0021 IN CHRS 1.7
END DESCRIPTION:
XS GIS Cut Line= 4
      3425418.29     10593080.58      3426779.16     10592324.54
      3426901.29     10591440.55      3426401.13     10589881.91
#Sta/Elev= 30
  3199.8  490.68  3604.7  487.72  3673.2  485.41  3820.9  485.29  4245.2  479.37
  4820.1  478.03  4963.6  480.78  4971.5  480.27 4974.98  478.39  4991.7  471.42
  5001.5  469.81  5011.9   473.5 5018.66  478.32  5030.4  480.82  5193.6  478.18
    5328  479.38  6348.1  478.72    6593  479.32  6610.3  481.17  6689.2  479.31
  6711.9  478.77  6738.7  471.97  6770.9   472.1  6808.2  476.51    6858  473.58
  6872.5  474.93  6909.8  486.01  6950.1  491.06  7076.1  495.45  7285.9  497.16
#Mann= 5 ,-1 , 0
  3199.8     .05       0 4974.98     .03       0 5018.66     .05       0
  6689.2     .16       0    6858     .05       0
#XS Ineff= 2 , 0
       0                  6610.8       0  479.85
Permanent Ineff=
       F       T
Bank Sta=4974.98,5018.66
XS Rating Curve= 0 ,0
Exp/Cntr=0.3,0.1

Type RM Length L Ch R = 1 ,591     ,0,0,0
BEGIN DESCRIPTION:
MUSTANG CREEK 1.55
END DESCRIPTION:
XS GIS Cut Line= 6
      3425801.09     10593296.06      3427233.42     10593113.76
      3428236.02     10592592.93      3428522.48     10591876.78
      3428079.77     10590939.28      3427143.14     10589755.49
#Sta/Elev= 30
  2112.9  490.41  2285.3  489.71  2809.5  478.06  4541.6   476.8  4620.5   476.9
  4960.7  479.03    4997  467.02  4999.8  466.52    5003  467.02  5014.5  468.04
  5021.9   473.9  5038.8  478.91  5844.6  476.24  5972.3  476.46  6004.5  468.33
  6032.8  475.94  6126.9  475.32  6808.3  476.84  6918.4  472.79  6947.3  475.59
  6953.7  470.97  6961.7  473.19    6989  469.77  7011.4  470.13  7017.8  474.55
  7032.2  476.52    7115  476.69  7309.5  478.04  7658.9   491.5  8004.2  486.37
#Mann= 9 ,-1 , 0
  2112.9     .05       0  4541.6     .16       0  4620.5     .05       0
    4997     .03       0    5003     .05       0  5844.6     .16       0
  6126.9      .1       0  6808.3     .16       0    7115     .05       0
Bank Sta=4960.7,5038.8
XS Rating Curve= 0 ,0
Exp/Cntr=0.3,0.1

Chan Stop Cuts=-1
Use User Specified Reach Order=0
Composite Channel Slope=5