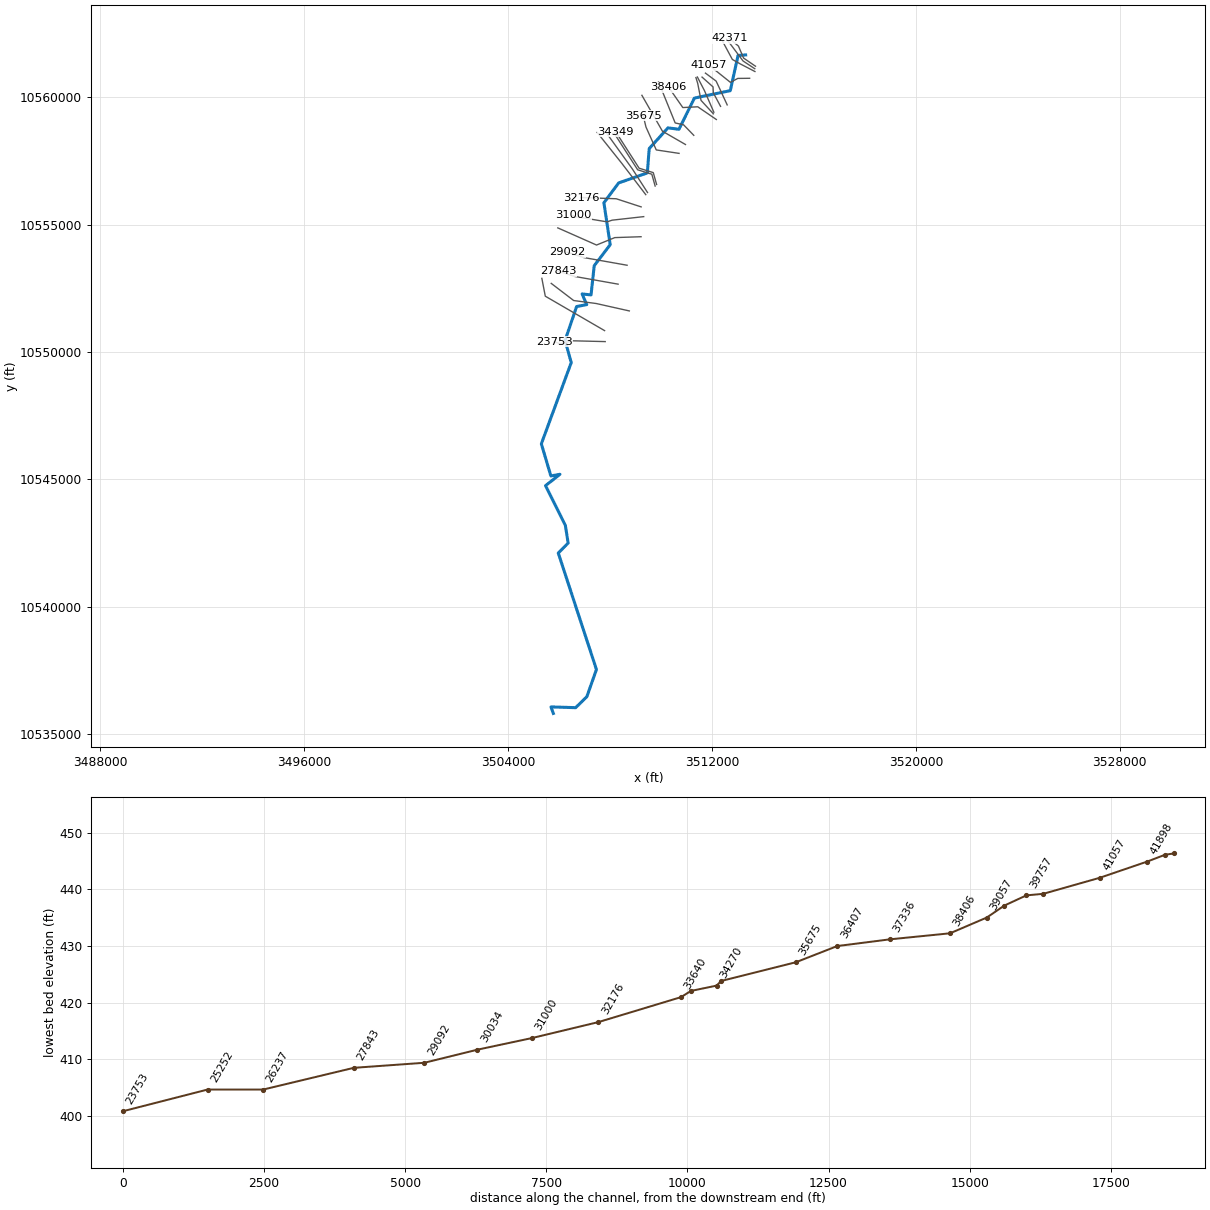
--- PIN OAK CREEK 2.prj (project) ---

Proj Title=PIN OAK CREEK 2 Base Level Engineering
Current Plan=p01
Default Exp/Contr=0.3,0.1
English Units
Geom File=g01
Flow File=f01
Plan File=p01
Y Axis Title=Elevation
X Axis Title(PF)=Main Channel Distance
X Axis Title(XS)=Station
BEGIN DESCRIPTION:
PIN OAK CREEK 2
END DESCRIPTION:
DSS File=dss
DSS Export Rating Curves= 0
DSS Export Rating Curve Sorted= 0
DSS Export Volume Flow Curves= 0
DXF OffsetX= 0
DXF OffsetY= 0
DXF ScaleX= 1
DXF ScaleY= 10

--- PIN OAK CREEK 2.p01 (plan) ---

Plan Title=Multiple Run
Program Version=4.10
Geom File=g01
Flow File=f01
Subcritical Flow
K Sum by GR= 0
Std Step Tol= 0.01
Critical Tol= 0.01
Num of Std Step Trials= 20
Max Error Tol= 0.3
Flow Tol Ratio= 0.001
Split Flow NTrial= 30
Split Flow Tol= 0.02
Split Flow Ratio= 0.02
Log Output Level= 0
Friction Slope Method= 1
Unsteady Friction Slope Method= 2
Unsteady Bridges Friction Slope Method= 1
Parabolic Critical Depth
Global Vel Dist= 1 , 1 , 1
Global Log Level= 0
CheckData=True
Encroach Param=-1 ,0,0, 0
BEGIN DESCRIPTION:
Multiple Run
END DESCRIPTION:
Computation Interval=1HOUR
Output Interval=1HOUR
Run HTab= 0
Run UNet= 0
Run PostProcess= 0
Run WQNet= 0
UNET Theta= 1
UNET Theta Warmup= 1
UNET ZTol= 0.02
UNET ZSATol= 0.05
UNET MxIter= 20
UNET MaxInSteps= 0
UNET DtIC= 0
UNET DtMin= 0
UNET MaxCRTS= 20
UNET WFStab= 2
UNET SFStab= 1
UNET WFX= 1
UNET SFX= 1
UNET DSS MLevel= 4
UNET DZMax Abort= 100
UNET Convert EG Bridges= 0
UNET Use Existing IB Tables=-1
UNET Froude Reduction=False
UNET Froude Limit= 1
UNET Froude Power= 10
UNET Time Slicing=0,0, 5
UNET Junction Losses=0
Instantaneous Interval=1HOUR
DSS File=dss
Write IC File= 0
Write IC File at Sim End=0
Echo Input=False
Echo Parameters=False
Echo Output=False
Write Detailed= 0
WQ AD Non Conservative
WQ ULTIMATE=-1
WQ Max Comp Step=1HOUR
WQ Output Interval=15MIN
WQ Output Selected Increments= 0
WQ Output face flow=0
WQ Output face velocity=0
WQ Output face area=0
WQ Output face dispersion=0
WQ Output cell volume=0
WQ Output cell surface area=0
WQ Output cell continuity=0
WQ Output cumulative cell continuity=0
WQ Output face conc=0
WQ Output face dconc_dx=0
WQ Output face courant=0
WQ Output face peclet=0
WQ Output face adv mass=0
WQ Output face disp mass=0
WQ Output cell mass=0
WQ Output cell source sink temp=0
WQ Output cell source sink nsm=0
WQ Output MaxMinRange=-1
WQ Daily Max Min Mean=-1
WQ Daily Range=0
WQ Daily Time=0
WQ Create Restart=0
WQ Fixed Restart=0
WQ System Summary=0
WQ Use Fixed Temperature=0
Sorting and Armoring Iterations= 10
XS Update Threshold= 0.02
Hydraulics Update Threshold= 0.02
Energy Slope Method= 1
Volume Change Method= 0
XS Weighting Method= 0
Number of US Weighted Cross Sections= 1
Number of DS Weighted Cross Sections= 1
Upstream XS Weight=0.25
Main XS Weight=0.5
Downstream XS Weight=0.25
Number of DS XS's Weighted with US Boundary= 1
Upstream Boundary Weight= 1
Weight of XSs Associated with US Boundary= 0
Number of US XS's Weighted with DS Boundary= 1
Downstream Boundary Weight= 0.5
Weight of XSs Associated with DS Boundary= 0.5
Sediment Output Level= 4
Mass or Volume Output= 0
Output Increment Type= 1
Profile and TS Output Increment= 10
XS Output Flag= 0
XS Output Increment= 10
Disregard all LS=0
Disregard all Conn=0
Disregard all Breaches=0
Disregard all Pumps=0

--- PIN OAK CREEK 2.f01 (steady flow) ---

Flow Title=Multiple
Program Version=4.10
Number of Profiles= 7
Profile Names=10-year,25-year,50-year,1pct_min,100-year,1pct_plu,500-year
River Rch & RM=PIN OAK CREEK 2,Reach-1         ,42371
     457     574     660     552     747    1010     954
River Rch & RM=PIN OAK CREEK 2,Reach-1         ,41057
     536     679     784     658     890    1204    1146
River Rch & RM=PIN OAK CREEK 2,Reach-1         ,39366
     717     919    1071     906    1226    1657    1603
River Rch & RM=PIN OAK CREEK 2,Reach-1         ,37336
     852    1099    1285    1091    1475    1995    1940
River Rch & RM=PIN OAK CREEK 2,Reach-1         ,33814
     972    1257    1474    1253    1694    2291    2235
River Rch & RM=PIN OAK CREEK 2,Reach-1         ,25252
    1027    1331    1562    1329    1797    2431    2376
River Rch & RM=PIN OAK CREEK 2,Reach-1         ,22925
    1036    1340    1571    1335    1806    2442    2382
River Rch & RM=PIN OAK CREEK 2,Reach-1         ,18978
    1607    2119    2516    2164    2926    3957    3950
River Rch & RM=PIN OAK CREEK 2,Reach-1         ,13244
    1932    2554    3036    2613    3533    4778    4776
Boundary for River Rch & Prof#=PIN OAK CREEK 2,Reach-1         , 1
Up Type= 0
Dn Type= 3
Dn Slope=0.002
Boundary for River Rch & Prof#=PIN OAK CREEK 2,Reach-1         , 2
Up Type= 0
Dn Type= 3
Dn Slope=0.002
Boundary for River Rch & Prof#=PIN OAK CREEK 2,Reach-1         , 3
Up Type= 0
Dn Type= 3
Dn Slope=0.002
Boundary for River Rch & Prof#=PIN OAK CREEK 2,Reach-1         , 4
Up Type= 0
Dn Type= 3
Dn Slope=0.002
Boundary for River Rch & Prof#=PIN OAK CREEK 2,Reach-1         , 5
Up Type= 0
Dn Type= 3
Dn Slope=0.002
Boundary for River Rch & Prof#=PIN OAK CREEK 2,Reach-1         , 6
Up Type= 0
Dn Type= 3
Dn Slope=0.002
Boundary for River Rch & Prof#=PIN OAK CREEK 2,Reach-1         , 7
Up Type= 0
Dn Type= 3
Dn Slope=0.002
DSS Import GetInterval= 0
DSS Import GetPeak= 0
DSS Import FillOption= 0

--- PIN OAK CREEK 2.g01 (geometry) ---

Geom Title=Existing Conditions
Program Version=4.10

River Reach=PIN OAK CREEK 2 ,Reach-1
Reach XY= 30
      3513322.11     10561651.64      3513025.43     10561630.68
      3512721.06     10560251.01       3511313.6     10559959.08
      3510705.81     10558734.54      3510277.09     10558791.52
      3509539.61     10557978.76      3509466.14     10557023.65
      3508341.96     10556631.14        3507763.     10555852.14
      3508010.37     10554207.17      3507383.63     10553386.12
      3507257.56     10552238.26      3506907.39     10552274.55
       3507089.9     10551857.19      3506692.11     10551781.64
       3506240.5     10550453.48       3506480.9     10549582.29
      3505308.51     10546396.11      3505682.29     10545136.16
      3506037.94     10545201.02      3505472.05     10544755.28
      3506250.58     10543196.31      3506359.19     10542503.08
      3505972.64       10542112.       3507469.9       10537543.
      3507093.93      10536476.8      3506655.31     10536045.68
      3505685.09     10536075.26      3505779.13     10535821.69

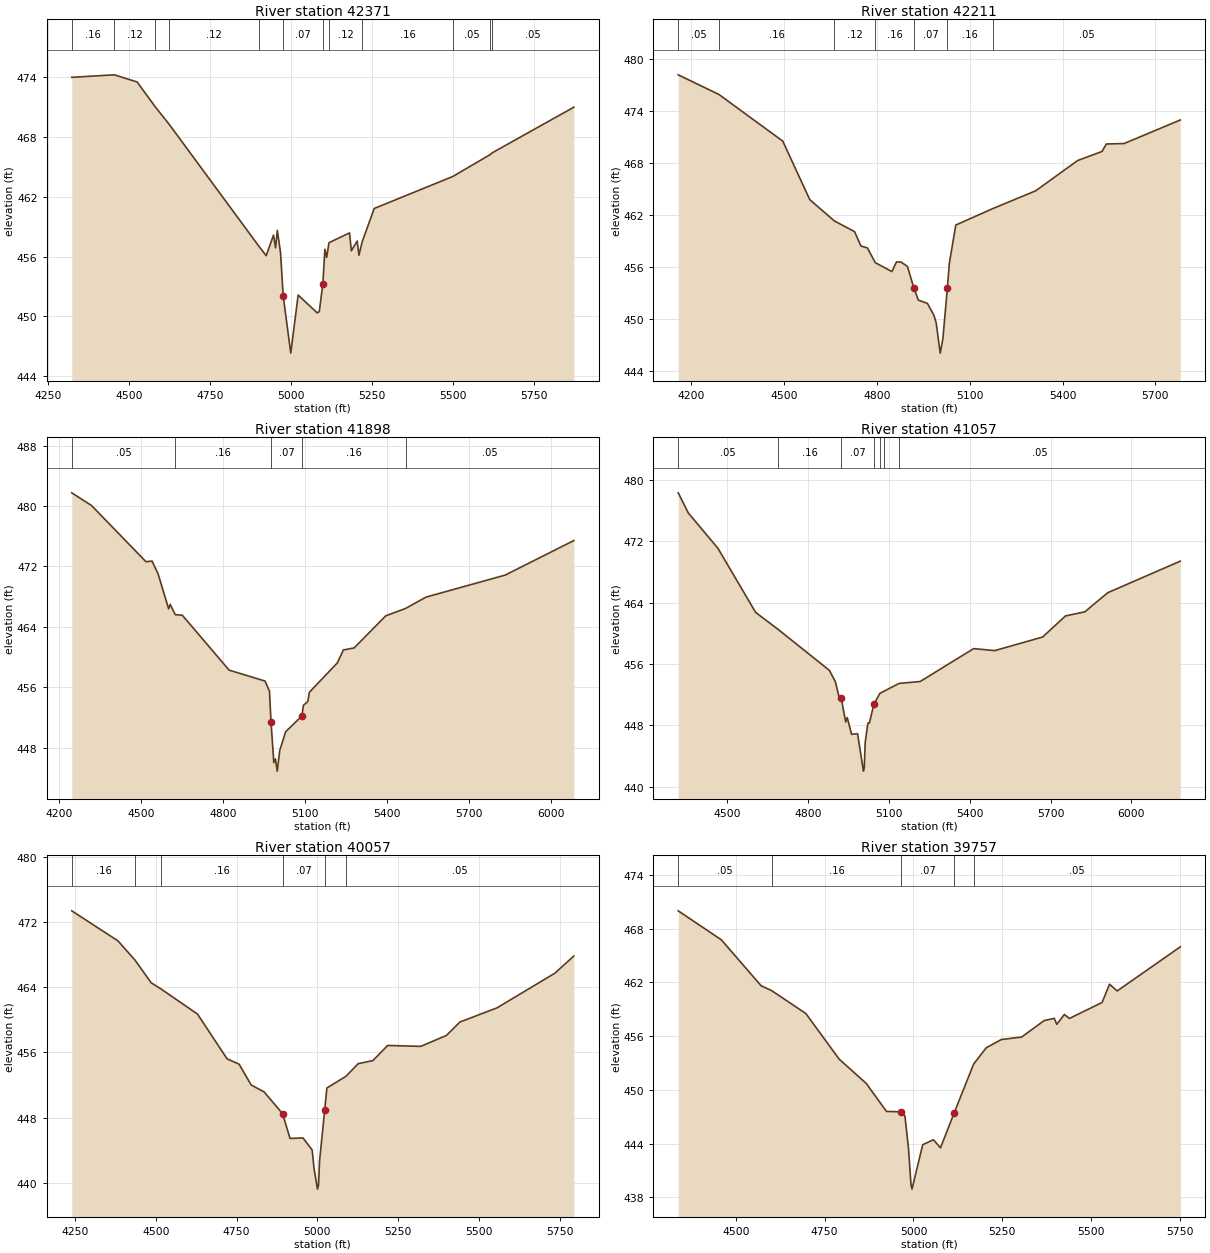
Type RM Length L Ch R = 1 ,42371   ,160,160,160
BEGIN DESCRIPTION:
PIN OAK CREEK 2 71.2
END DESCRIPTION:
XS GIS Cut Line= 4
      3513709.36     10561209.56      3513242.75     10561528.59
      3513040.93     10561999.51      3512678.52     10562303.32
#Sta/Elev= 30
  4322.2  474.01  4453.7  474.26  4524.2  473.54  4579.3  471.08  4623.3  469.28
  4899.4  457.08  4922.6   456.1  4945.2  458.17  4951.6  456.89    4957  458.64
  4966.9  456.41  4975.1  452.08  4998.5  446.32  5021.3  452.15  5080.3  450.36
  5086.6  450.49 5097.65   453.3  5103.9  456.75  5109.3  455.93  5116.6  457.41
    5180  458.39  5185.5  456.59  5203.6  457.57  5209.1  456.15  5219.3  457.52
  5256.2  460.84  5499.3  464.06  5615.2  466.27  5619.5  466.41  5872.7  471.01
#Mann= 12 ,-1 , 0
  4322.2     .16       0  4453.7     .12       0  4579.3     .16       0
  4623.3     .12       0  4899.4     .16       0  4975.1     .07       0
 5097.65     .16       0  5116.6     .12       0  5219.3     .16       0
  5499.3     .05       0  5615.2     .16       0  5619.5     .05       0
Bank Sta=4975.1,5097.65
XS Rating Curve= 0 ,0
Exp/Cntr=0.3,0.1

Type RM Length L Ch R = 1 ,42211   ,313,313,313
BEGIN DESCRIPTION:
PIN OAK CREEK 2 71.1
END DESCRIPTION:
XS GIS Cut Line= 3
       3513681.1     10561111.93      3513221.05     10561415.74
      3512578.69     10562272.95
#Sta/Elev= 30
  4158.1  478.18  4289.8  475.91  4495.9  470.53  4583.2  463.78  4662.3  461.33
  4727.9  460.09  4748.7  458.42  4769.5  458.21  4794.7  456.51  4848.7  455.48
  4863.3  456.59  4877.9  456.58  4898.7  456.08  4919.5  453.59  4934.1  452.19
  4963.3  451.81  4984.1  450.46  4991.7  449.56  5004.7  446.07  5013.3  447.72
  5027.9   453.6  5034.1   456.4    5055  460.85  5176.3  462.77  5313.3   464.8
  5448.8  468.29  5527.9  469.34  5541.5   470.2  5598.8  470.25  5780.6  472.97
#Mann= 7 ,-1 , 0
  4158.1     .05       0  4289.8     .16       0  4662.3     .12       0
  4794.7     .16       0  4919.5     .07       0  5027.9     .16       0
  5176.3     .05       0
Bank Sta=4919.5,5027.9
XS Rating Curve= 0 ,0
Exp/Cntr=0.3,0.1

Type RM Length L Ch R = 1 ,41898   ,841,841,841
BEGIN DESCRIPTION:
PIN OAK CREEK 2 71.0
END DESCRIPTION:
XS GIS Cut Line= 4
      3513687.77     10561001.48      3513110.52     10561300.96
      3512802.36     10561474.57      3512407.78     10562207.38
#Sta/Elev= 30
  4247.2  481.75  4319.5  480.07  4518.7  472.62  4540.8  472.71  4562.9  471.02
  4601.5  466.38  4607.1  466.97  4625.7  465.61  4651.4  465.54  4822.7  458.26
  4954.3  456.81  4970.3  455.46    4976  451.38  4986.2     446  4991.9   446.5
  4998.7  444.88  5007.8  447.61  5029.5   450.1  5088.8  452.18  5094.5   453.6
  5110.4   454.1  5116.2  455.33  5218.7  459.23  5240.4  460.93  5279.8   461.2
  5395.5  465.45  5467.9  466.43  5543.2  467.94  5832.3  470.85  6083.5  475.43
#Mann= 5 ,-1 , 0
  4247.2     .05       0  4625.7     .16       0    4976     .07       0
  5088.8     .16       0  5467.9     .05       0
Bank Sta=4976,5088.8
XS Rating Curve= 0 ,0
Exp/Cntr=0.3,0.1

Type RM Length L Ch R = 1 ,41057   ,1000,1000,1000
BEGIN DESCRIPTION:
PIN OAK CREEK 2 69.0
END DESCRIPTION:
XS GIS Cut Line= 4
      3513479.58     10560736.07      3513016.01     10560730.86
      3512724.35     10560577.22      3511888.41     10561246.49
#Sta/Elev= 30
  4317.3  478.32  4354.8  475.69  4464.8  471.08  4604.8  462.72  4687.7  460.52
  4878.6  455.16  4900.6  453.69    4917  451.31  4922.6  451.51    4939  448.43
  4944.7  449.01    4961  446.82  4983.1  446.91  5004.9  442.02  5008.1  442.52
  5011.4  445.76  5021.5  448.29  5027.1   448.3  5043.5  450.73  5066.1  452.17
  5080.9  452.44  5137.3  453.46  5215.6  453.71  5414.1     458  5492.5  457.74
  5670.2  459.51    5755  462.26    5827   462.8  5911.9  465.29  6181.4  469.41
#Mann= 7 ,-1 , 0
  4317.3     .05       0  4687.7     .16       0  4922.6     .07       0
  5043.5     .16       0  5066.1     .05       0  5080.9     .16       0
  5137.3     .05       0
Bank Sta=4922.6,5043.5
XS Rating Curve= 0 ,0
Exp/Cntr=0.3,0.1

Type RM Length L Ch R = 1 ,40057   ,300,300,300
BEGIN DESCRIPTION:
PIN OAK CREEK 2 67.0
END DESCRIPTION:
XS GIS Cut Line= 4
      3512599.35      10559691.8      3512312.89     10560311.59
      3512164.45      10560626.7      3511746.16     10560938.47
#Sta/Elev= 30
  4240.3  473.41  4383.2  469.72  4436.5  467.32    4486  464.56  4516.9  463.79
  4629.1  460.72  4720.8  455.21  4757.9  454.56  4795.2     452    4835  451.16
  4892.4  448.47  4915.3  445.43  4955.4  445.49  4983.8  444.01  4989.5  441.77
  5000.3   439.2  5003.5   439.7  5006.6  442.63  5022.6  448.93  5029.3  451.63
  5088.3  453.07    5126  454.62  5171.6     455  5217.2  456.86  5319.7  456.75
    5399  458.09  5440.7  459.74  5555.4  461.48  5734.7  465.75  5793.1  467.86
#Mann= 6 ,-1 , 0
  4240.3     .16       0  4436.5     .05       0  4516.9     .16       0
  4892.4     .07       0  5022.6     .16       0  5088.3     .05       0
Bank Sta=4892.4,5022.6
XS Rating Curve= 0 ,0
Exp/Cntr=0.3,0.1

Type RM Length L Ch R = 1 ,39757   ,391,391,391
BEGIN DESCRIPTION:
PIN OAK CREEK 2 66.0
END DESCRIPTION:
XS GIS Cut Line= 4
      3512338.95     10559634.47      3512055.08     10560165.76
      3512044.66     10560397.53       3511612.4     10560782.92
#Sta/Elev= 30
  4337.7  469.98  4459.2  466.74    4571  461.62  4600.4  461.08    4697  458.52
  4790.5  453.44  4866.9  450.72  4924.1  447.59    4966  447.55    4976  447.05
    4986  443.47    4993  439.42  4995.8  438.92    5026  443.88  5056.1  444.43
  5076.1  443.53  5114.4  447.41  5169.4  452.88  5204.9   454.7  5247.5  455.62
  5304.4  455.89  5367.9  457.73  5396.4  457.98  5403.3  457.31  5424.8  458.41
    5439  457.97    5531  459.75  5551.9  461.79  5573.6  461.04  5751.2  465.96
#Mann= 5 ,-1 , 0
  4337.7     .05       0  4600.4     .16       0    4966     .07       0
  5114.4     .16       0  5169.4     .05       0
Bank Sta=4966,5114.4
XS Rating Curve= 0 ,0
Exp/Cntr=0.3,0.1

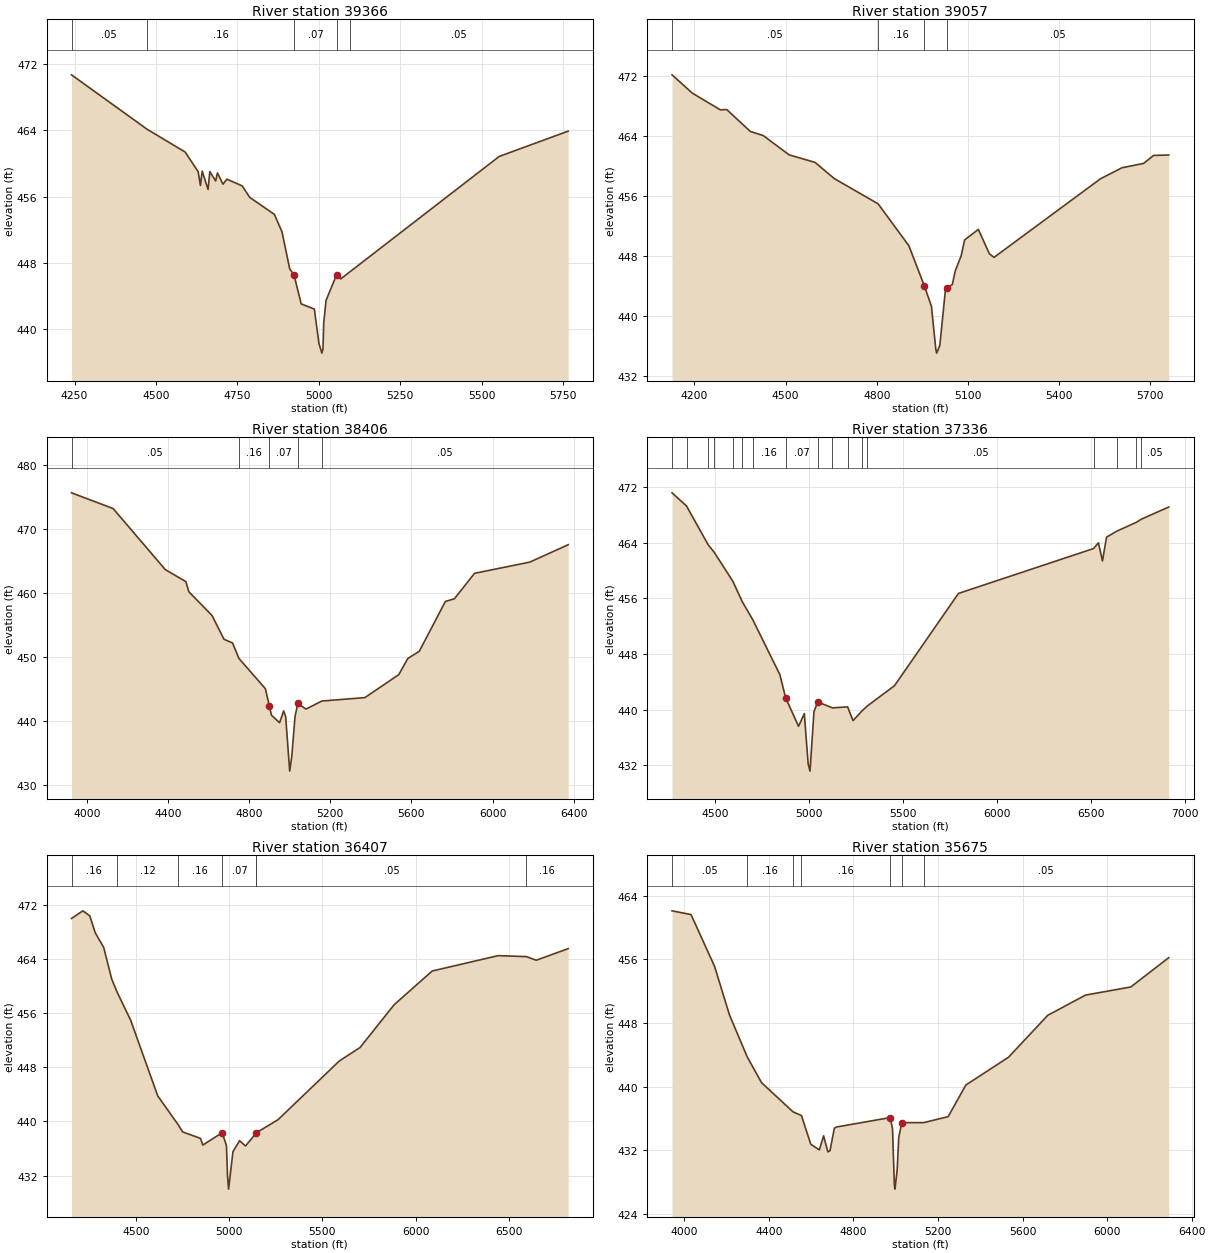
Type RM Length L Ch R = 1 ,39366   ,309,309,309
BEGIN DESCRIPTION:
PIN OAK CREEK 2 65.0
END DESCRIPTION:
XS GIS Cut Line= 3
      3512075.91     10559405.34      3511703.51     10560259.51
      3511430.07     10560785.57
#Sta/Elev= 30
  4240.6  470.68  4472.6  464.12  4589.5  461.37  4629.3  459.01  4636.4  457.34
  4641.8  459.07  4659.8  456.86  4665.2  459.01  4683.2  457.88  4688.6  458.85
  4705.7  457.49  4717.5   458.1  4764.4  457.29  4787.8   455.9  4863.5  453.85
  4886.9  451.73  4910.3  447.31  4923.8  446.53  4945.7  443.06  4986.1  442.43
  5000.2  438.28  5009.2  437.12  5012.5  437.62  5014.9  440.79    5022  443.48
  5054.7   446.6  5067.2  446.07  5094.4   446.9  5553.6  460.84  5765.3  463.89
#Mann= 5 ,-1 , 0
  4240.6     .05       0  4472.6     .16       0  4923.8     .07       0
  5054.7     .16       0  5094.4     .05       0
Bank Sta=4923.8,5054.7
XS Rating Curve= 0 ,0
Exp/Cntr=0.3,0.1

Type RM Length L Ch R = 1 ,39057   ,651,651,651
BEGIN DESCRIPTION:
PIN OAK CREEK 2 64.0
END DESCRIPTION:
XS GIS Cut Line= 4
      3512057.65     10559342.87      3511573.31     10559868.88
       3511443.1     10560532.95       3511372.8     10560764.67
#Sta/Elev= 30
  4126.5  472.22    4193  469.78  4285.4  467.54  4306.4  467.58  4384.1  464.65
  4426.6   464.1  4511.7  461.52  4596.8  460.52  4660.3  458.35  4804.3  454.98
  4905.5  449.38  4956.4  444.01  4979.8  441.28  4994.2  435.52    4997  435.02
  5007.4  436.06  5026.2  443.64  5031.3  443.76  5048.2  444.17  5058.3  446.03
  5077.6  448.04  5088.9  450.15  5134.2  451.56  5170.4   448.3  5185.7  447.82
  5535.7  458.32  5606.7   459.8  5677.8  460.38  5710.7  461.45  5760.4   461.5
#Mann= 4 ,-1 , 0
  4126.5     .05       0  4804.3     .16       0  4956.4     .07       0
  5031.3     .05       0
Bank Sta=4956.4,5031.3
XS Rating Curve= 0 ,0
Exp/Cntr=0.3,0.1

Type RM Length L Ch R = 1 ,38406   ,1070,1070,1070
BEGIN DESCRIPTION:
PIN OAK CREEK 2 63.0
END DESCRIPTION:
XS GIS Cut Line= 4
      3512173.56     10559118.89       3511444.4     10559618.02
      3510858.46     10559587.63      3510298.59     10560390.56
#Sta/Elev= 30
    3924  475.69  4129.1  473.24  4386.3  463.71  4487.9  461.83  4502.8  460.24
  4616.5  456.56  4676.2  452.82  4718.1  452.25  4749.8  449.83    4880  445.11
    4900  442.38  4910.1  440.97  4950.1   439.8  4970.1  441.64  4980.2  440.73
  4999.9  432.24  5010.2  434.54  5026.2  440.77  5040.2   442.8  5080.3  441.93
  5158.2  443.18  5370.7  443.72    5538  447.31  5582.1  449.82  5639.2  450.96
  5767.5  458.73    5812  459.15  5911.3  463.12  6184.5  464.88  6373.2  467.59
#Mann= 5 ,-1 , 0
    3924     .05       0  4749.8     .16       0    4900     .07       0
  5040.2     .16       0  5158.2     .05       0
Bank Sta=4900,5040.2
XS Rating Curve= 0 ,0
Exp/Cntr=0.3,0.1

Type RM Length L Ch R = 1 ,37336   ,929,929,929
BEGIN DESCRIPTION:
PIN OAK CREEK 2 61.0
END DESCRIPTION:
XS GIS Cut Line= 4
      3511288.14     10558498.23      3510888.84     10558910.55
      3510558.98     10558984.33      3509908.67     10560588.44
#Sta/Elev= 30
  4272.5  471.17  4349.4  469.28  4464.9   463.7  4497.6  462.59  4596.4  458.44
  4645.8  455.54  4702.5  452.91  4846.5  445.02  4876.7  441.72  4945.6  437.61
  4976.3  439.44  4996.8  432.21  5006.6  431.17  5027.6  439.72  5048.1  441.11
  5125.9  440.26  5206.7  440.41  5235.5  438.43  5283.9  439.84  5310.9  440.52
  5456.2  443.45  5796.5  456.71  6515.1  463.16  6541.2  463.99  6562.8  461.39
  6584.4   464.8  6638.4  465.65  6742.9  466.93  6769.3  467.38  6915.4  469.13
#Mann= 17 ,-1 , 0
  4272.5     .05       0  4349.4     .12       0  4464.9     .05       0
  4497.6     .16       0  4596.4     .05       0  4645.8     .12       0
  4702.5     .16       0  4876.7     .07       0  5048.1     .16       0
  5125.9     .12       0  5206.7     .05       0  5283.9     .16       0
  5310.9     .05       0  6515.1     .16       0  6638.4     .05       0
  6742.9     .16       0  6769.3     .05       0
Bank Sta=4876.7,5048.1
XS Rating Curve= 0 ,0
Exp/Cntr=0.3,0.1

Type RM Length L Ch R = 1 ,36407   ,732,732,732
BEGIN DESCRIPTION:
PIN OAK CREEK 2 59.0
END DESCRIPTION:
XS GIS Cut Line= 3
      3510962.62     10558137.98      3510059.85     10558658.81
      3509253.36     10560068.01
#Sta/Elev= 30
  4153.3  470.02    4214  471.15  4251.4  470.41  4280.9  467.89    4326  465.75
  4369.1  461.07  4396.7  459.21  4471.1  454.95  4616.2  443.78  4726.3   439.5
  4749.7  438.46  4845.9  437.49  4858.1  436.51    4962  438.33  4985.1  436.43
    4991  431.81  4996.5  429.99  5019.8  435.53  5055.6  437.16  5087.2  436.37
  5146.1  438.33  5261.8  440.26  5590.5  448.94  5702.2  450.94    5885  457.26
  6089.3  462.25  6443.2  464.52  6594.5  464.38  6647.7  463.84  6819.2  465.56
#Mann= 7 ,-1 , 0
  4153.3     .16       0  4396.7     .12       0  4726.3     .16       0
    4962     .07       0  5146.1     .16       0  5146.1     .05       0
  6594.5     .16       0
Bank Sta=4962,5146.1
XS Rating Curve= 0 ,0
Exp/Cntr=0.3,0.1

Type RM Length L Ch R = 1 ,35675   ,1326,1326,1326
BEGIN DESCRIPTION:
PIN OAK CREEK 2 56.0
END DESCRIPTION:
XS GIS Cut Line= 4
      3510710.93     10557790.75       3509816.8     10557925.31
      3509413.15     10558823.74      3509304.64     10559270.82
#Sta/Elev= 30
  3942.4  462.08  4032.2  461.61  4143.5  455.11  4214.2     449  4297.8  443.75
  4365.9   440.5  4514.9  436.84  4554.4  436.38  4598.5  432.78    4639  432.06
  4659.2  433.83  4679.4  431.81  4689.5  431.97  4709.8  434.76    4718  434.93
  4974.1  436.12  4985.1  434.74  4993.9  427.64  4996.6  427.14    5007  429.51
  5014.6  433.61  5028.9  435.49  5132.9  435.49  5248.2  436.24  5332.1  440.21
  5533.9   443.7  5719.2  448.96  5897.9   451.5    6112  452.52  6291.6   456.2
#Mann= 7 ,-1 , 0
  3942.4     .05       0  4297.8     .16       0  4514.9     .05       0
  4554.4     .16       0  4974.1     .07       0  5028.9     .16       0
  5132.9     .05       0
Bank Sta=4974.1,5028.9
XS Rating Curve= 0 ,0
Exp/Cntr=0.3,0.1

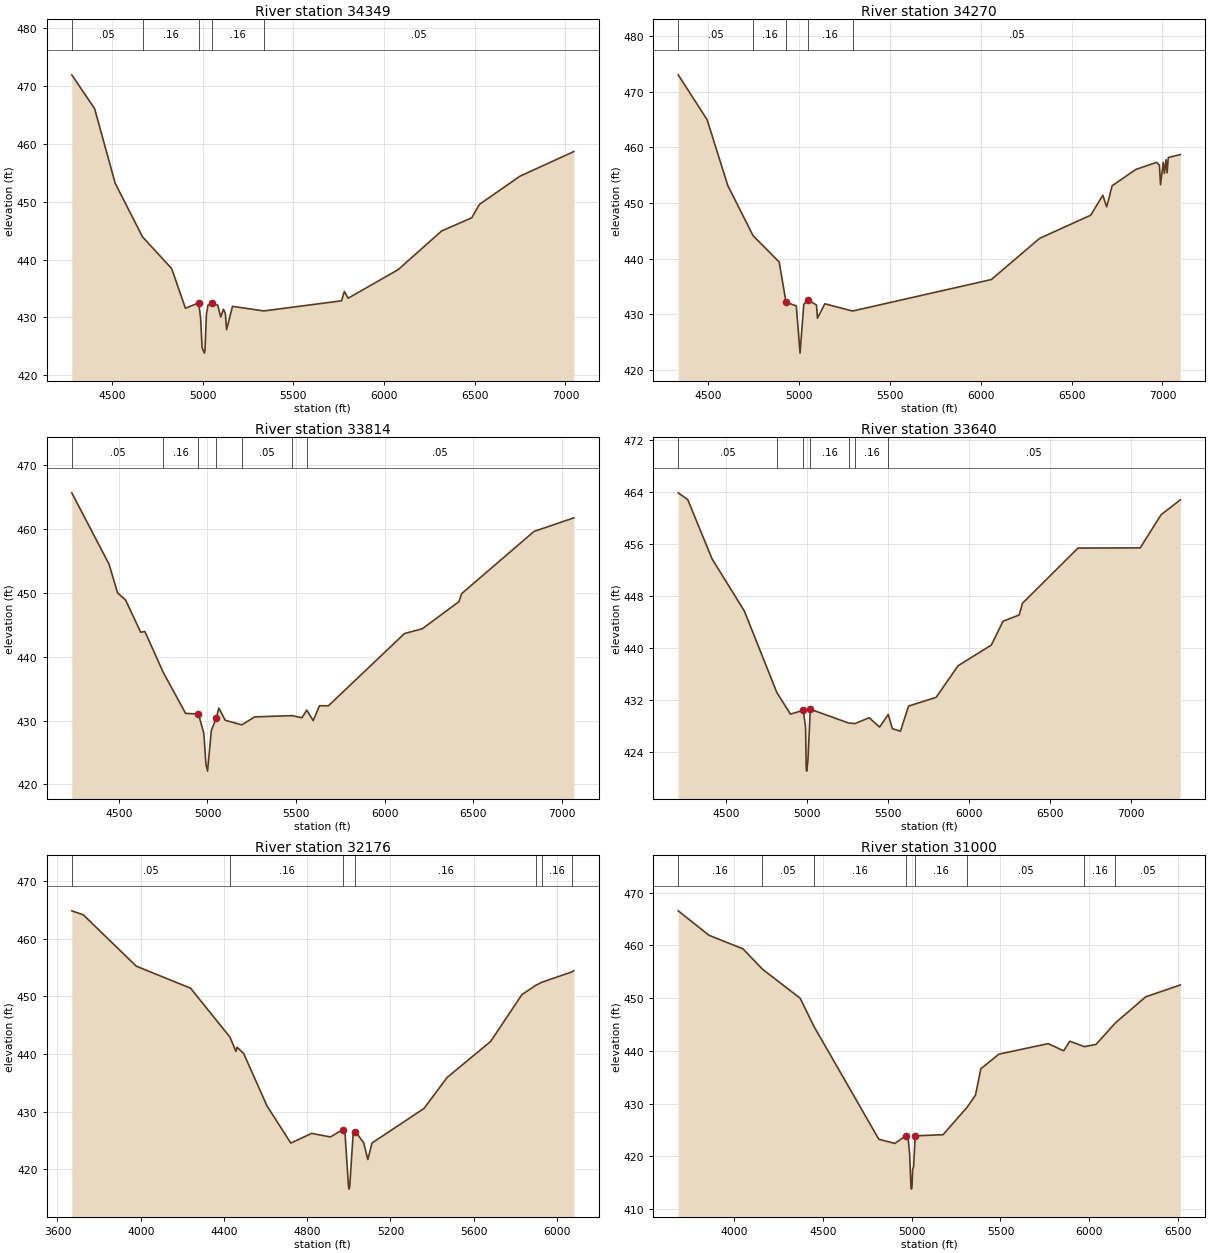
Type RM Length L Ch R = 1 ,34349   ,79,79,79
BEGIN DESCRIPTION:
PIN OAK CREEK 2 55.5
END DESCRIPTION:
XS GIS Cut Line= 4
      3509829.83      10556571.1      3509699.61     10557035.55
      3509144.05     10557209.16      3508223.91     10558641.45
#Sta/Elev= 30
  4279.4  471.97  4405.2  466.13  4518.8   453.2  4669.6  443.93  4829.9  438.46
  4905.8  431.59  4979.2  432.53  4989.6  429.83  4997.5   424.8  5010.3  423.83
  5013.6  424.33  5021.1  430.46    5030  432.14  5052.5  432.49  5083.9  432.11
  5100.2  430.08  5115.4  431.43  5125.8  430.69  5132.6  427.88  5165.1  431.92
    5338  431.13  5766.2  432.88  5781.4   434.5  5802.5  433.33    6078  438.27
  6317.1  444.95  6483.6  447.24  6525.8  449.56  6749.7  454.44  7046.2   458.7
#Mann= 5 ,-1 , 0
  4279.4     .05       0  4669.6     .16       0  4979.2     .07       0
  5052.5     .16       0    5338     .05       0
Bank Sta=4979.2,5052.5
XS Rating Curve= 0 ,0
Exp/Cntr=0.3,0.1

Type RM Length L Ch R = 1 ,34270   ,456,456,456
BEGIN DESCRIPTION:
PIN OAK CREEK 2 55.0
END DESCRIPTION:
XS GIS Cut Line= 4
      3509772.54      10556508.6      3509642.32     10556973.05
      3509086.76     10557146.66      3508167.59     10558577.44
#Sta/Elev= 30
  4333.5     473  4492.4  464.95  4606.7   453.1  4745.7  444.11  4889.4  439.39
  4927.3  432.13  4983.7  431.51  5004.4  423.02  5024.7  431.76  5046.6   432.6
  5094.9  431.67  5100.2  429.29  5140.9  431.88  5293.6  430.58  6057.5  436.23
  6323.7  443.63    6605  447.79  6671.8  451.37  6692.9  449.29  6723.1  453.08
  6853.4  456.01  6968.3  457.28  6983.5  456.75  6989.5  453.27  7004.7   457.3
  7010.6  455.29  7019.9  457.75  7025.8  455.39  7032.2  458.15  7098.5  458.68
#Mann= 5 ,-1 , 0
  4333.5     .05       0  4745.7     .16       0  4927.3     .07       0
  5046.6     .16       0  5293.6     .05       0
Bank Sta=4927.3,5046.6
XS Rating Curve= 0 ,0
Exp/Cntr=0.3,0.1

Type RM Length L Ch R = 1 ,33814   ,174,174,174
BEGIN DESCRIPTION:
PIN OAK CREEK 2 54.0
END DESCRIPTION:
XS GIS Cut Line= 3
       3509473.9     10556254.31       3508879.3     10557178.78
      3507864.64     10558588.03
#Sta/Elev= 30
  4233.6  465.69    4444  454.52  4492.2  450.03  4537.8  448.87  4622.8  443.85
  4646.6  443.96  4750.1  437.56  4876.6  431.13  4949.2  431.03  4979.5  428.01
  4991.5  423.15  5000.5  422.08  5021.8  428.45  5050.8  430.48  5064.1  431.96
  5100.4  430.05    5194  429.33  5266.8  430.58  5477.3  430.78  5533.5  430.45
  5560.9  431.64  5597.2     430  5632.8  432.33  5683.2  432.32  6112.7  443.64
  6213.4  444.39  6420.8  448.65  6435.5  449.89  6844.2  459.64  7069.3  461.77
#Mann= 7 ,-1 , 0
  4233.6     .05       0  4750.1     .16       0  4949.2     .07       0
  5050.8     .16       0    5194     .05       0  5477.3     .16       0
  5560.9     .05       0
Bank Sta=4949.2,5050.8
XS Rating Curve= 0 ,0
Exp/Cntr=0.3,0.1

Type RM Length L Ch R = 1 ,33640   ,1464,1464,1464
BEGIN DESCRIPTION:
PIN OAK CREEK 2 53.0
END DESCRIPTION:
XS GIS Cut Line= 3
      3509404.46     10556171.84      3508471.31     10557391.45
       3507495.9     10558613.96
#Sta/Elev= 30
  4204.7  463.86  4263.6  462.81  4413.2   453.7  4612.7  445.66  4813.3  433.11
  4897.4  429.77  4976.3  430.36  4990.8  427.77  4994.7  421.49  4997.4  420.99
  5005.4  422.62  5019.9  430.53  5257.4  428.39  5295.4  428.32  5383.5  429.21
  5447.9  427.78  5501.6  429.73  5526.5  427.53  5576.7  427.14  5626.5  431.01
  5796.7  432.35  5932.5  437.23  6137.7  440.41  6209.8  444.08  6309.1  445.04
  6329.9  446.85  6672.6  455.35  7056.9  455.38    7185  460.47  7304.3  462.78
#Mann= 7 ,-1 , 0
  4204.7     .05       0  4813.3     .16       0  4976.3     .07       0
  5019.9     .16       0  5257.4     .05       0  5295.4     .16       0
  5501.6     .05       0
Bank Sta=4976.3,5019.9
XS Rating Curve= 0 ,0
Exp/Cntr=0.3,0.1

Type RM Length L Ch R = 1 ,32176   ,1176,1176,1176
BEGIN DESCRIPTION:
PIN OAK CREEK 2 49.0
END DESCRIPTION:
XS GIS Cut Line= 3
      3509223.92     10555690.93      3508244.75     10556010.38
      3506862.77     10556058.99
#Sta/Elev= 30
  3668.7  464.83  3723.9  464.14  3979.1  455.23  4239.6  451.42  4429.1  442.93
  4457.6  440.46  4462.9  441.19  4494.8  440.11  4606.8  431.02  4721.3  424.57
  4821.4  426.25  4911.4  425.64  4971.5  426.91  4981.5  426.53  4998.5  417.09
  5001.2  416.59  5004.5  417.09  5021.5  426.53  5031.5  426.57  5071.5  424.64
  5091.5  421.72  5111.6  424.59  5361.7  430.58  5471.8  435.92  5681.9   442.2
    5832  450.31  5899.4  451.94  5929.9  452.48  6070.4  454.22  6081.5  454.45
#Mann= 7 ,-1 , 0
  3668.7     .05       0  4429.1     .16       0  4971.5     .07       0
  5031.5     .16       0  5899.4     .12       0  5929.9     .16       0
  6070.4     .12       0
Bank Sta=4971.5,5031.5
XS Rating Curve= 0 ,0
Exp/Cntr=0.3,0.1

Type RM Length L Ch R = 1 ,31000   ,966,966,966
BEGIN DESCRIPTION:
PIN OAK CREEK 2 47.0
END DESCRIPTION:
XS GIS Cut Line= 5
      3509324.59     10555308.98      3508085.02      10555170.1
      3507887.11     10555104.13      3506567.66     10555322.88
      3506553.77     10555354.13
#Sta/Elev= 30
  3685.1  466.57  3858.7  461.92  4049.8  459.36  4159.2  455.51  4371.9  449.99
  4449.7  444.63  4814.6  423.25  4905.2  422.44  4967.1  423.93  4978.9  423.77
  4988.2  420.52  4995.7  414.28  4998.5  413.78  5001.7  414.28  5005.3  417.57
  5010.6  417.99  5019.8  423.88  5176.5  424.11  5312.3  429.32    5359  431.59
  5389.4  436.61  5490.8  439.38  5768.7  441.38  5855.7  440.01  5890.6  441.84
  5972.2  440.81  6038.1  441.23  6146.5  445.29  6317.5  450.25  6512.7  452.51
#Mann= 8 ,-1 , 0
  3685.1     .16       0  4159.2     .05       0  4449.7     .16       0
  4967.1     .07       0  5019.8     .16       0  5312.3     .05       0
  5972.2     .16       0  6146.5     .05       0
Bank Sta=4967.1,5019.8
XS Rating Curve= 0 ,0
Exp/Cntr=0.3,0.1

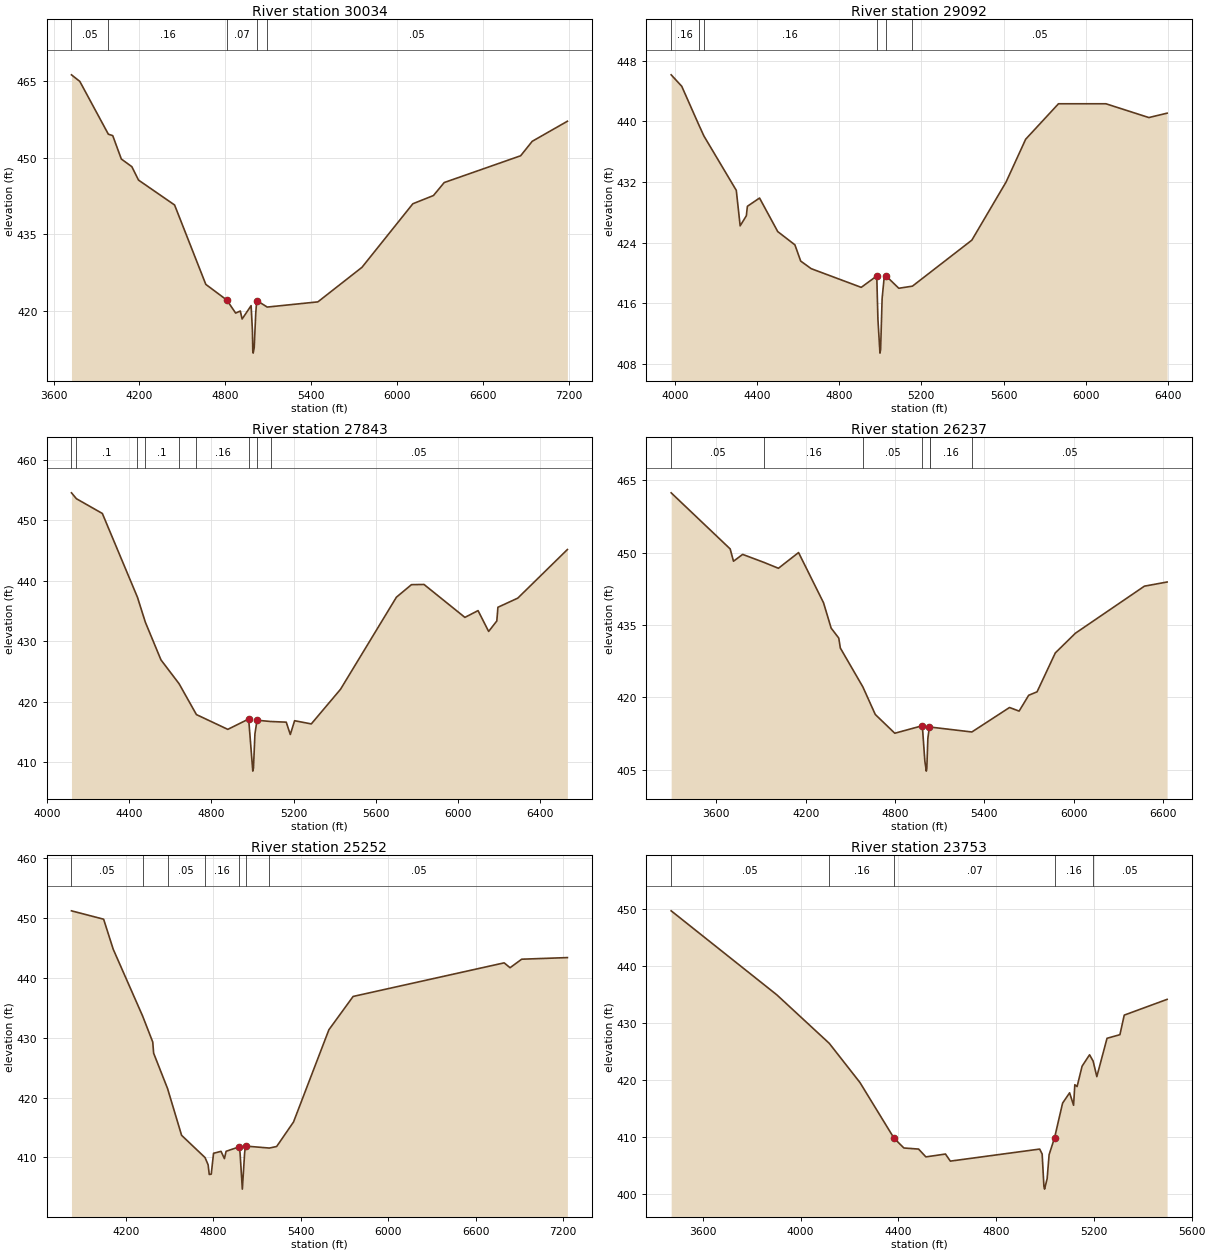
Type RM Length L Ch R = 1 ,30034   ,942,942,942
BEGIN DESCRIPTION:
PIN OAK CREEK 2 45.0
END DESCRIPTION:
XS GIS Cut Line= 4
      3509220.45     10554520.79      3508189.19     10554486.07
      3507473.91      10554194.4      3505954.67     10554867.31
#Sta/Elev= 30
  3725.5   466.3  3783.9  465.01  3983.2  454.66    4014  454.38    4074  449.79
  4147.6  448.29  4194.1  445.66  4446.2  440.78  4664.4  425.21  4811.2  422.14
    4873  419.58  4905.4  419.99  4918.2  418.42    4981  421.04  4990.3  416.07
  4992.7  412.23  4995.4  411.73  5002.6  412.78  5013.4  419.56  5019.7  421.84
  5025.1  421.97  5093.5  420.76  5447.6  421.78    5756  428.56  6111.4  441.02
  6255.3  442.63  6330.6  445.18  6864.7  450.43  6945.5  453.26  7191.4   457.2
#Mann= 5 ,-1 , 0
  3725.5     .05       0  3983.2     .16       0  4811.2     .07       0
  5025.1     .16       0  5093.5     .05       0
Bank Sta=4811.2,5025.1
XS Rating Curve= 0 ,0
Exp/Cntr=0.3,0.1

Type RM Length L Ch R = 1 ,29092   ,1249,1249,1249
BEGIN DESCRIPTION:
PIN OAK CREEK 2 43.0
END DESCRIPTION:
XS GIS Cut Line= 3
      3508672.67     10553401.87      3506971.31     10553703.95
      3506318.52     10553912.29
#Sta/Elev= 30
  3982.7  446.15  4034.1  444.64  4116.9  439.57  4142.2  438.07  4299.6   430.9
  4318.4  426.22  4348.5  427.55  4353.6   428.8  4412.7  429.89  4501.3  425.46
  4584.8  423.71    4613  421.57  4663.8  420.57  4907.5   418.1  4983.1   419.6
  4988.8  413.86  4998.7  409.42  5001.9  409.92  5009.1   416.6  5019.2  419.43
  5029.4  419.58  5090.3  417.98  5156.7  418.26  5445.8  424.33  5612.5  432.01
  5707.7  437.65  5867.3  442.33  6098.2  442.33  6307.2  440.51  6395.9  441.09
#Mann= 6 ,-1 , 0
  3982.7     .16       0  4116.9     .12       0  4142.2     .16       0
  4983.1     .07       0  5029.4     .16       0  5156.7     .05       0
Bank Sta=4983.1,5029.4
XS Rating Curve= 0 ,0
Exp/Cntr=0.3,0.1

Type RM Length L Ch R = 1 ,27843   ,1606,1606,1606
BEGIN DESCRIPTION:
PIN OAK CREEK 2 42.0
END DESCRIPTION:
XS GIS Cut Line= 3
      3508321.16     10552659.68      3506619.75     10552961.77
        3505967.     10553170.09
#Sta/Elev= 30
  4118.6  454.51    4143  453.53  4268.9   451.1  4439.8  437.25  4478.2  433.13
  4554.1  426.91  4642.1  422.98  4726.7  417.87  4879.4  415.43  4980.9  417.14
    5001  408.53  5004.2  409.03  5011.4  414.69  5021.6  416.94  5087.2  416.73
  5163.7  416.62  5183.5  414.58  5204.4  416.86  5285.6  416.33  5427.8  422.05
  5699.9  437.27  5773.1  439.34  5834.1  439.37  6033.1  433.93  6097.1  435.05
  6148.6  431.61  6188.4  433.34  6193.7   435.6  6290.3  437.11  6531.8  445.14
#Mann= 9 ,-1 , 0
  4118.6     .05       0    4143      .1       0  4439.8     .05       0
  4478.2      .1       0  4642.1     .05       0  4726.7     .16       0
  4980.9     .07       0  5021.6     .16       0  5087.2     .05       0
Bank Sta=4980.9,5021.6
XS Rating Curve= 0 ,0
Exp/Cntr=0.3,0.1

Type RM Length L Ch R = 1 ,26237   ,985,985,985
BEGIN DESCRIPTION:
PIN OAK CREEK 2 41.0
END DESCRIPTION:
XS GIS Cut Line= 4
      3508760.57     10551609.21      3507462.87       10551900.
      3506577.45     10552017.18      3505696.75     10552689.64
#Sta/Elev= 30
  3296.9  462.43  3693.3  450.79  3715.5  448.24    3777  449.66  3920.9  447.99
  4017.4  446.78  4152.6  450.04  4320.1  439.64  4371.4  434.37  4422.6   432.3
  4433.2  430.23  4584.5  422.17  4667.9  416.45    4799  412.56    4984  414.12
  5000.8  406.78  5010.6   404.7  5013.9   405.2    5021  411.47    5031  413.86
  5032.1  413.86  5316.6  412.82  5569.6   417.9    5634  417.15  5698.4  420.44
  5754.6  421.15  5877.1  429.22  6012.2  433.31  6475.7  443.07    6628  443.93
#Mann= 7 ,-1 , 0
  3296.9     .05       0  3920.9     .16       0  4584.5     .05       0
    4984    .035       0  5032.1     .05       0  5032.1     .16       0
  5316.6     .05       0
Bank Sta=4984,5031
XS Rating Curve= 0 ,0
Exp/Cntr=0.3,0.1

Type RM Length L Ch R = 1 ,25252   ,1499,1499,1499
BEGIN DESCRIPTION:
PIN OAK CREEK 2 36.0
END DESCRIPTION:
XS GIS Cut Line= 3
      3507789.86     10550836.78       3505463.5     10552187.46
      3505328.28     10552887.79
#Sta/Elev= 30
  3825.8  451.18  4046.6  449.78  4112.3  444.77  4313.6  433.64  4383.6  429.27
  4389.8   427.4  4485.2   421.5  4581.5  413.69  4742.5  409.97  4763.6  408.77
  4771.4  407.15  4785.1   407.2  4800.9  410.69  4852.3  411.01  4875.4  409.79
    4887  411.02  4977.2  411.76    4983  410.69  4998.5   404.7  5014.2  410.76
  5020.2  411.89    5184  411.56  5233.9  411.82  5349.6  415.91  5592.3  431.31
  5758.7  436.88  6795.1  442.49  6835.8  441.68  6915.5   443.1  7229.1  443.37
#Mann= 7 ,-1 , 0
  3825.8     .05       0  4313.6     .16       0  4485.2     .05       0
  4742.5     .16       0  4977.2     .07       0  5020.2     .16       0
    5184     .05       0
Bank Sta=4977.2,5020.2
XS Rating Curve= 0 ,0
Exp/Cntr=0.3,0.1

Type RM Length L Ch R = 1 ,23753   ,636,636,636
BEGIN DESCRIPTION:
PIN OAK CREEK 2 34.0
END DESCRIPTION:
XS GIS Cut Line= 4
       3507814.2     10550406.21      3506564.19     10550437.46
      3506029.47     10550326.35      3505810.73      10550406.2
#Sta/Elev= 30
  3470.1  449.66  3902.3  434.94  4117.1  426.43  4242.4  419.58  4382.5  409.78
  4422.5  408.09  4482.5   407.9  4512.5  406.53  4592.5  407.03  4612.5  405.79
    4978   407.9  4988.2  407.03  4995.4  401.38  4998.1  400.88  5008.6  402.71
  5016.6  406.91  5039.2  409.92  5071.8  415.95  5100.5  417.76  5116.8  415.58
  5121.9  419.18  5131.2  418.86  5151.6  422.43  5182.2  424.43  5196.8  423.32
  5211.9   420.6  5253.7  427.32  5306.4  427.95  5324.1  431.38  5499.5  434.14
#Mann= 5 ,-1 , 0
  3470.1     .05       0  4117.1     .16       0  4382.5     .07       0
  5039.2     .16       0  5196.8     .05       0
Bank Sta=4382.5,5039.2
XS Rating Curve= 0 ,0
Exp/Cntr=0.3,0.1