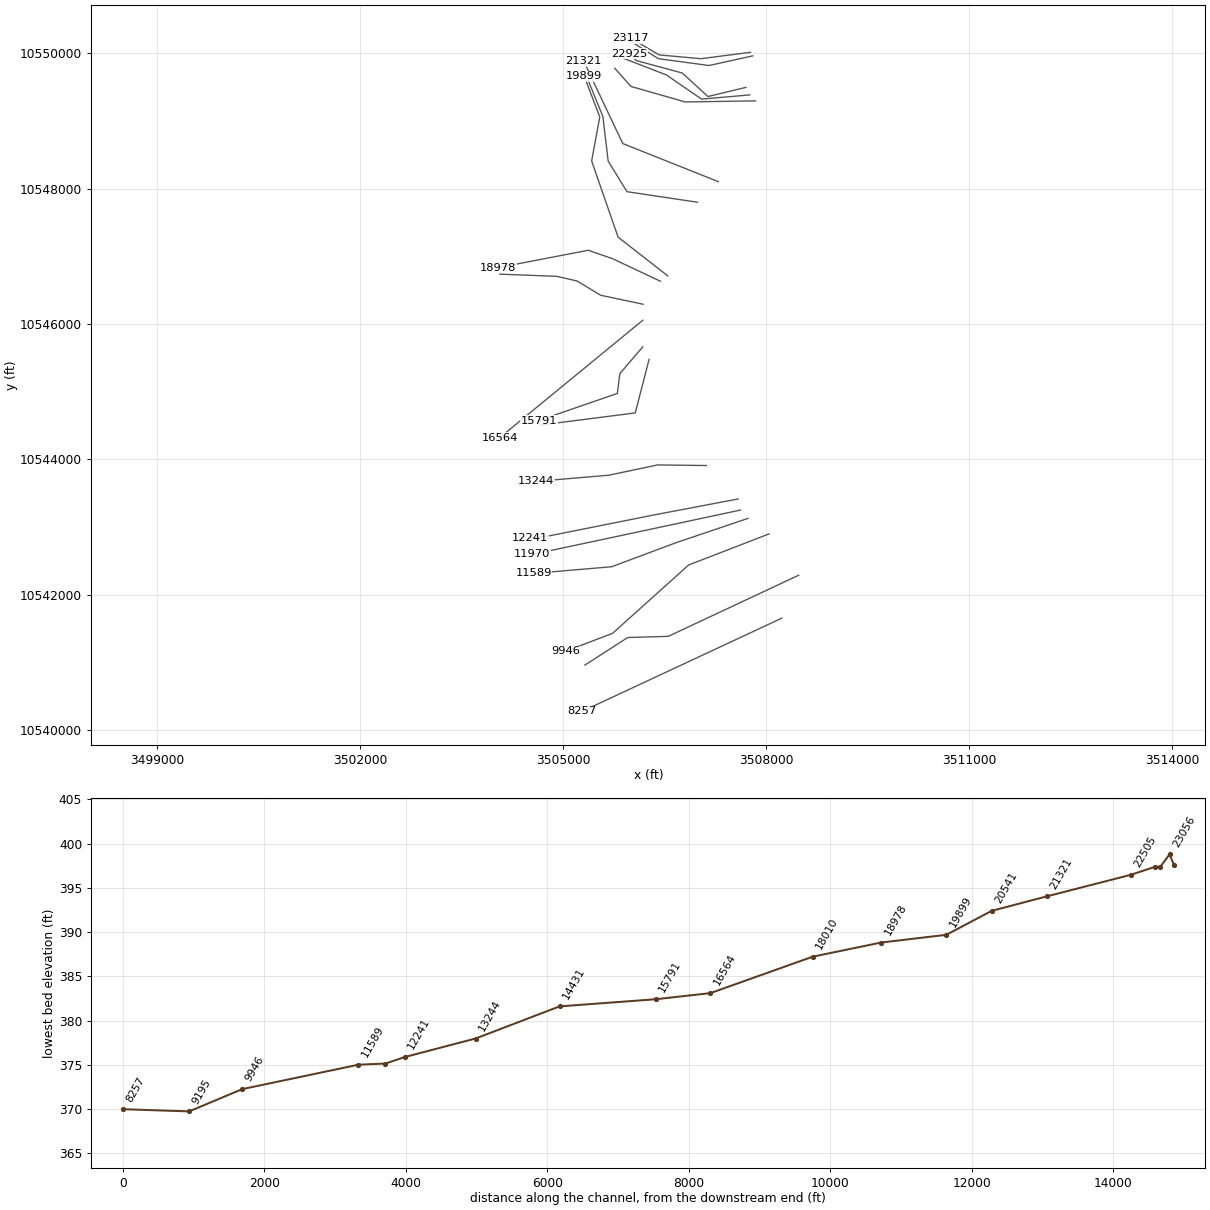
HEC-RAS study PIN OAK CREEK 2.prj: PIN OAK CREEK 2 Base Level Engineering

--- PIN OAK CREEK 2.g01 (geometry) --- (continued)

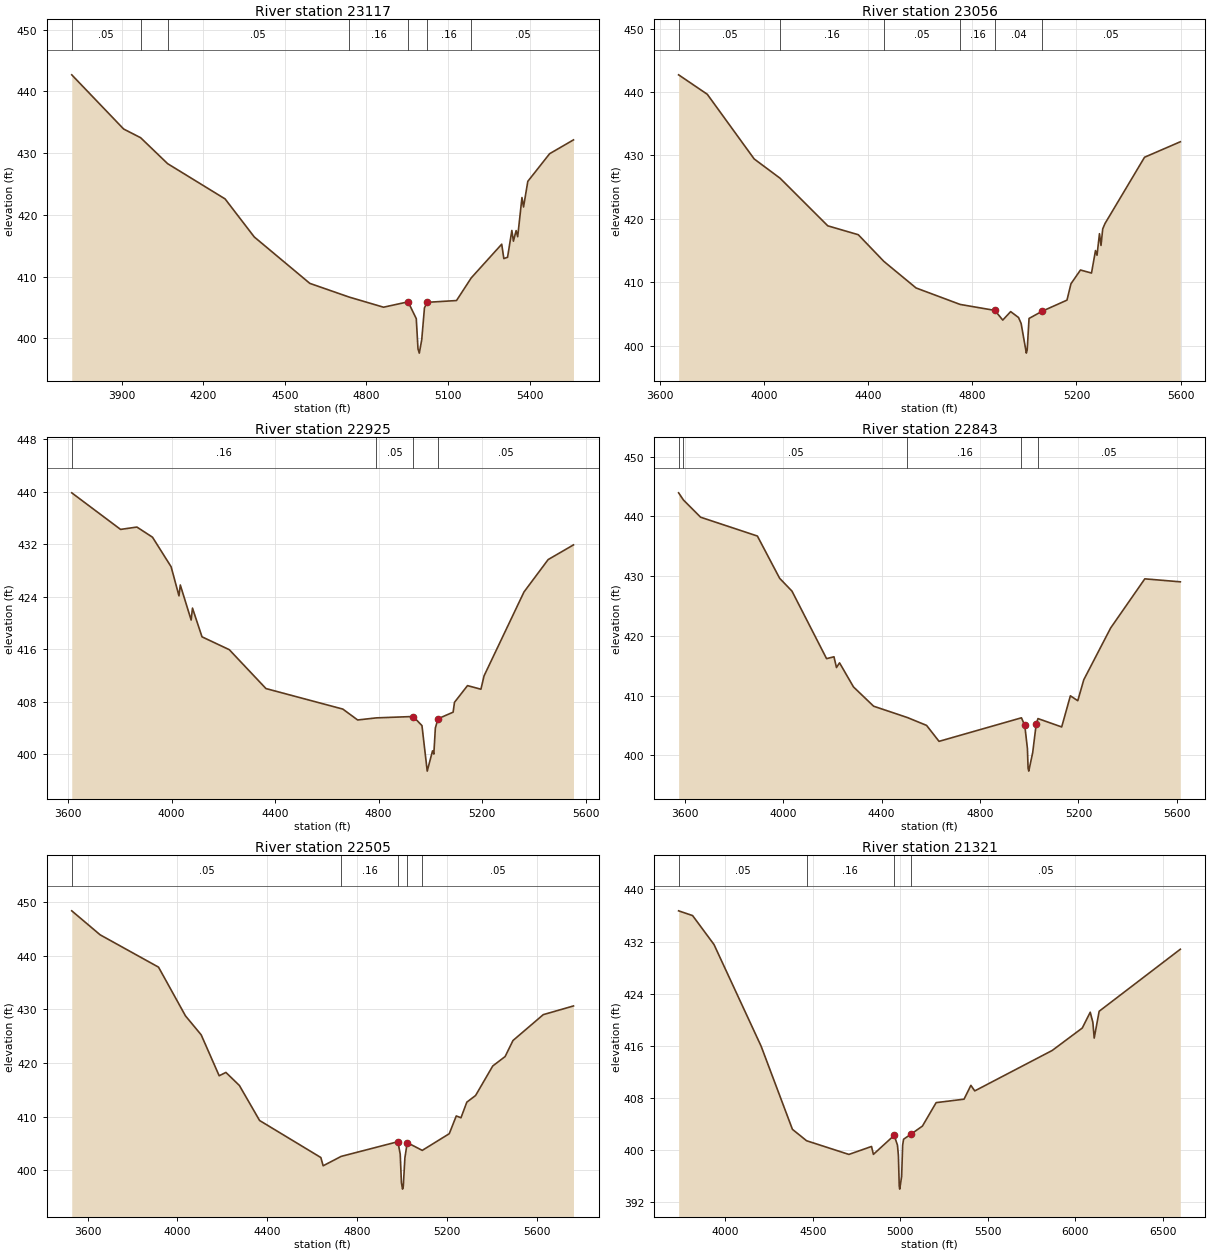
Type RM Length L Ch R = 1 ,23117   ,61,61,61
BEGIN DESCRIPTION:
PIN OAK CREEK 2 32.1
END DESCRIPTION:
XS GIS Cut Line= 4
      3507771.51     10550012.09       3507038.9     10549918.34
      3506424.32      10549973.9       3506000.7     10550220.43
#Sta/Elev= 30
  3715.7   442.7  3906.6  433.92  3969.1  432.51  4068.3  428.31  4279.7   422.6
  4387.2  416.43  4591.6  408.91  4735.7   406.7  4862.7  405.05  4953.1  405.92
  4983.2  403.19  4989.5   398.3  4994.3  397.61  5003.3  399.79  5013.3  404.95
  5023.4  405.84  5131.2  406.13  5185.6  409.81  5297.5  415.26  5305.3  412.93
    5319  413.14  5334.8  417.48  5340.6  415.75  5350.5  417.46  5356.3  416.47
    5372  422.82  5377.8  421.29  5393.5  425.44  5473.8  429.92  5561.5  432.16
#Mann= 7 ,-1 , 0
  3715.7     .05       0  3969.1     .16       0  4068.3     .05       0
  4735.7     .16       0  4953.1     .07       0  5023.4     .16       0
  5185.6     .05       0
Bank Sta=4953.1,5023.4
XS Rating Curve= 0 ,0
Exp/Cntr=0.3,0.1

Type RM Length L Ch R = 1 ,23056   ,131,131,131
BEGIN DESCRIPTION:
PIN OAK CREEK 2 32.0
END DESCRIPTION:
XS GIS Cut Line= 4
       3507806.3     10549960.02      3507160.43     10549817.65
      3506410.43     10549918.34      3505979.84      10550189.2
#Sta/Elev= 30
    3672   442.7  3782.2  439.63  3962.2  429.43    4062  426.38  4244.9  418.88
    4362  417.48  4460.3  413.27  4583.9  409.08  4753.3  406.48  4886.6  405.54
  4916.9  404.01  4947.2  405.35  4977.4  404.42  4987.5  403.47  5007.4   398.8
  5010.7   399.3  5017.8  404.27  5068.2  405.41  5163.5  407.16  5178.8  409.74
  5215.3  411.91  5257.7  411.43    5273  414.98  5278.9  414.24  5288.3  417.64
  5294.2  415.79  5300.8   418.4  5309.5  419.24  5461.4   429.7  5598.8  432.14
#Mann= 6 ,-1 , 0
    3672     .05       0    4062     .16       0  4460.3     .05       0
  4753.3     .16       0  4886.6     .04       0  5068.2     .05       0
Bank Sta=4886.6,5068.2
XS Rating Curve= 0 ,0
Exp/Cntr=0.3,0.1

Type RM Length L Ch R = 1 ,22925   ,82,82,82
BEGIN DESCRIPTION:
PIN OAK CREEK 2 31.0
END DESCRIPTION:
XS GIS Cut Line= 5
       3507705.6     10549494.74      3507143.07     10549359.32
       3506764.6     10549706.54      3506084.04     10549890.57
      3505986.96     10549994.58
#Sta/Elev= 30
  3613.8  439.84  3802.5  434.26  3865.7  434.62    3926  433.07    3998  428.56
  4028.3  424.13  4033.4  425.79  4075.4  420.44  4080.5  422.26  4117.3  417.88
  4222.8  415.92  4364.6  409.99  4661.8  406.86    4719   405.2    4791  405.52
  4933.8  405.73  4967.6  404.34    4988   397.4  5008.4  400.49  5013.5     400
  5019.4  403.98  5029.7  405.39  5088.1  406.39  5093.3  407.89  5143.7  410.44
  5195.5  409.89  5207.7  411.93    5362  424.72  5455.4  429.66  5553.3   431.9
#Mann= 4 ,-1 , 0
  3613.8     .16       0    4791     .05       0  4933.8     .05       0
  5029.7     .05       0
Bank Sta=4933.8,5029.7
XS Rating Curve= 0 ,0
Exp/Cntr=0.3,0.1

Type RM Length L Ch R = 1 ,22843   ,338,338,338
BEGIN DESCRIPTION:
PIN OAK CREEK 2 31.1
END DESCRIPTION:
XS GIS Cut Line= 4
      3507761.12     10549383.62      3507049.32     10549321.12
      3506528.48     10549678.76      3505882.62     10549928.77
#Sta/Elev= 30
    3575  443.93  3594.5  442.74  3664.4  439.85  3895.2   436.7  3985.6  429.63
  4035.8  427.48  4176.3  416.19  4206.4   416.5  4216.5   414.7    4229  415.49
  4285.6  411.46  4367.5  408.23  4504.5  406.34  4582.7  405.02  4633.4  402.35
  4968.3  406.29  4981.8  405.01  4992.5  401.15  4995.2  397.87    4998  397.37
    5014  400.48  5028.2  405.24  5035.4  406.16  5131.8  404.76  5167.1  409.97
  5197.1  409.15  5221.6  412.66  5330.6  421.31  5469.6  429.54  5613.9  429.04
#Mann= 5 ,-1 , 0
    3575     .16       0  3594.5     .05       0  4504.5     .16       0
  4968.3     .07       0  5035.4     .05       0
Bank Sta=4981.8,5028.2
XS Rating Curve= 0 ,0
Exp/Cntr=0.3,0.1

Type RM Length L Ch R = 1 ,22505   ,1184,1184,1184
BEGIN DESCRIPTION:
PIN OAK CREEK 2 29.0
END DESCRIPTION:
XS GIS Cut Line= 4
      3507848.54      10549295.1       3506806.9     10549279.47
      3506004.82     10549508.64      3505767.44     10549776.98
#Sta/Elev= 30
  3529.4  448.35  3655.8  443.88  3915.9  437.85  4035.9  428.77  4105.9  425.23
  4185.9  417.61  4215.9  418.23  4275.9   415.8  4365.9  409.27  4638.7  402.37
  4648.9  400.83    4729  402.58  4981.7  405.32  4992.1     403  4997.5  397.66
  5002.5  396.48  5005.7  396.98  5012.9   402.3  5023.3  405.15  5090.2   403.7
  5210.5  406.81  5241.7  410.12  5262.6  409.78  5288.7  412.69  5327.7  413.93
  5404.1  419.43  5459.2  421.19  5494.3  424.18    5629     429  5763.6  430.62
#Mann= 5 ,-1 , 0
  3529.4     .05       0    4729     .16       0  4981.7     .07       0
  5023.3     .16       0  5090.2     .05       0
Bank Sta=4981.7,5023.3
XS Rating Curve= 0 ,0
Exp/Cntr=0.3,0.1

Type RM Length L Ch R = 1 ,21321   ,780,780,780
BEGIN DESCRIPTION:
PIN OAK CREEK 2 27.0
END DESCRIPTION:
XS GIS Cut Line= 3
      3507296.44     10548102.41      3505885.02     10548664.89
      3505307.02     10549883.38
#Sta/Elev= 30
  3732.2  436.72  3812.2  435.99  3934.4  431.56    4204  415.96  4382.8  403.22
  4463.6  401.47  4705.7  399.37  4834.9  400.59  4845.7  399.38  4964.3  402.29
  4983.2   400.8  4988.6  399.23  4993.4  394.55  4996.1  394.05  5007.1  395.98
  5012.9  400.78  5018.2   401.7  5060.9  402.48  5126.1  403.72  5204.3  407.31
  5363.8  407.84  5402.9  409.96  5425.1  409.11  5867.8  415.31  6039.7  418.75
  6085.2  421.17  6100.2  419.63  6107.9  417.21  6136.2  421.32  6600.2  430.83
#Mann= 4 ,-1 , 0
  3732.2     .05       0  4463.6     .16       0  4964.3     .07       0
  5060.9     .05       0
Bank Sta=4964.3,5060.9
XS Rating Curve= 0 ,0
Exp/Cntr=0.3,0.1

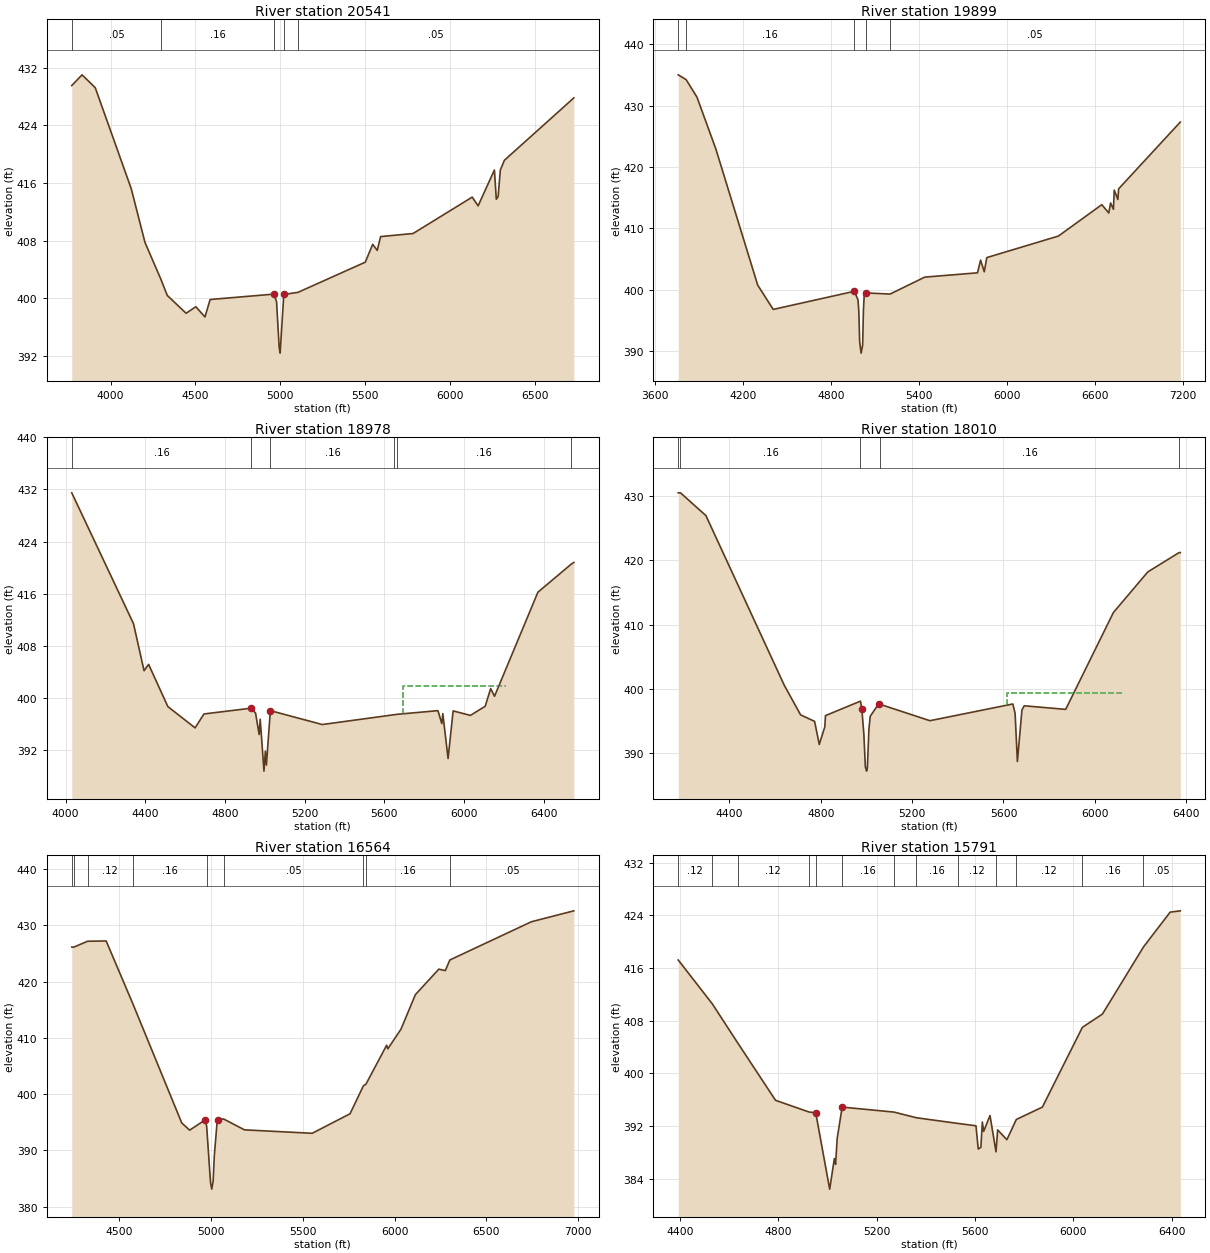
Type RM Length L Ch R = 1 ,20541   ,642,642,642
BEGIN DESCRIPTION:
PIN OAK CREEK 2 26.3
END DESCRIPTION:
XS GIS Cut Line= 5
      3506988.85     10547797.91      3505947.16     10547954.17
      3505669.38     10548405.56      3505591.25     10549065.28
      3505322.15     10549725.02
#Sta/Elev= 30
    3771  429.54  3831.6  431.03  3909.3  429.25  4121.6  415.23  4202.5  407.78
  4296.3  402.67    4334  400.42  4445.2  397.94  4502.4  398.85  4556.4  397.43
  4586.8  399.85  4963.1   400.6  4978.5  399.53  4993.9  393.18  4999.5  392.41
  5021.1  400.56  5104.4  400.84  5501.5  405.03  5545.3  407.51    5572  406.67
  5592.1  408.58  5783.4  409.01  6131.9  414.06  6166.7  412.85  6262.9  417.82
    6274  413.77  6284.8  414.14  6297.7  417.82  6321.7  419.17  6731.2  427.83
#Mann= 5 ,-1 , 0
    3771     .05       0  4296.3     .16       0  4963.1     .07       0
  5021.1     .16       0  5104.4     .05       0
Bank Sta=4963.1,5021.1
XS Rating Curve= 0 ,0
Exp/Cntr=0.3,0.1

Type RM Length L Ch R = 1 ,19899   ,921,921,921
BEGIN DESCRIPTION:
PIN OAK CREEK 2 26.2
END DESCRIPTION:
XS GIS Cut Line= 5
       3506550.3     10546709.77      3505815.96     10547282.66
      3505425.34     10548407.66      3505545.13      10549058.7
      3505315.97     10549657.63
#Sta/Elev= 30
    3758  435.03  3811.9  434.25  3885.9  431.39  4014.4  422.97  4300.2  400.78
  4406.1  396.82  4959.2  399.77  4984.7  398.37  4990.4  396.33  4995.7  391.58
  5005.6   389.7  5016.2     391  5021.5   396.7    5027  399.21  5037.6  399.51
  5203.4  399.32  5439.9  402.08  5799.8  402.78    5821  404.85  5845.9  402.95
  5863.3  405.26    6352  408.77  6647.9  413.88  6695.3  412.53    6708  414.15
  6727.3  413.13  6732.7  416.26  6757.4  414.72  6762.7  416.46  7183.5  427.34
#Mann= 5 ,-1 , 0
    3758     .05       0  3811.9     .16       0  4959.2     .07       0
  5037.6     .16       0  5203.4     .05       0
Bank Sta=4959.2,5037.6
XS Rating Curve= 0 ,0
Exp/Cntr=0.3,0.1

Type RM Length L Ch R = 1 ,18978   ,968,968,968
BEGIN DESCRIPTION:
PIN OAK CREEK 2 26.1
END DESCRIPTION:
XS GIS Cut Line= 4
       3506442.5      10546630.6      3505732.45     10546965.01
      3505375.14      10547088.7      3504042.07     10546832.16
#Sta/Elev= 30
  4031.2  431.48  4341.1  411.43  4394.1  404.22  4416.9  405.19  4513.6  398.72
  4650.3  395.46  4694.8  397.59  4932.8  398.48    4954  397.71  4971.9  394.45
  4977.2  396.78  4996.1  388.83    5003  391.88  5008.3  389.76  5028.1   398.1
  5288.9  395.97  5651.1  397.48  5665.7  397.54  5869.4   398.1  5888.8  396.12
  5893.9  397.64  5920.3  390.77  5945.8  398.06  6032.3  397.37  6106.7  398.77
  6134.1  401.48  6153.5   400.3  6371.3  416.25    6537  420.51  6551.7  420.81
#Mann= 6 ,-1 , 0
  4031.2     .16       0  4932.8     .07       0  5028.1     .16       0
  5651.1     .12       0  5665.7     .16       0    6537     .05       0
#XS Ineff= 1 ,-1
 5696.17 6213.34  401.93
Permanent Ineff=
       F
Bank Sta=4932.8,5028.1
XS Rating Curve= 0 ,0
Exp/Cntr=0.3,0.1

Type RM Length L Ch R = 1 ,18010   ,1446,1446,1446
BEGIN DESCRIPTION:
PIN OAK CREEK 2 26.0
END DESCRIPTION:
XS GIS Cut Line= 5
      3506185.99      10546291.6      3505558.38     10546424.46
      3505210.22     10546635.18      3504907.88     10546703.89
      3504069.53     10546735.96
#Sta/Elev= 30
  4176.4   430.5  4186.2   430.5  4297.6  426.96  4640.4  400.59  4711.9  395.98
  4773.2  394.97  4793.7  391.38  4817.9  394.11  4820.8  395.86    4974  398.11
  4979.9  396.94  4988.9  392.96  4995.4   387.9  5000.9  387.23  5004.2  387.73
  5010.9  393.72  5016.7  395.76  5053.5  397.67  5059.4  397.62    5278  395.07
  5640.8  397.67  5650.8  396.23  5660.8  388.73  5680.8  396.75  5690.8  397.39
  5872.2  396.83  6081.1  411.89  6231.2  418.19  6368.1   421.2  6373.9  421.21
#Mann= 5 ,-1 , 0
  4176.4     .12       0  4186.2     .16       0    4974     .07       0
  5059.4     .16       0  6368.1     .05       0
#XS Ineff= 1 ,-1
 5616.23 6117.83399.4532
Permanent Ineff=
       F
Bank Sta=4979.9,5053.5
XS Rating Curve= 0 ,0
Exp/Cntr=0.3,0.1

Type RM Length L Ch R = 1 ,16564   ,773,773,773
BEGIN DESCRIPTION:
PIN OAK CREEK 2 25.0
END DESCRIPTION:
XS GIS Cut Line= 2
      3506181.86     10546055.49      3504067.34     10544321.16
#Sta/Elev= 30
  4241.8  426.16  4252.5  426.14  4328.3  427.19  4429.1  427.24  4574.7  416.06
    4841  394.87  4884.1   393.6  4968.8  395.43  4976.7  394.27  4997.5  384.29
  5004.3  383.11  5011.8  384.51  5018.3  389.08  5032.6  394.73  5040.5  395.46
  5069.2  395.58  5182.6  393.65  5551.5  393.04  5757.5  396.51  5830.6   401.5
  5843.7  401.75    5957   408.7  5963.4  408.06  6035.2  411.57  6113.4  417.69
  6241.1  422.23  6276.3  421.97  6301.3  423.86  6745.6  430.66  6976.6   432.6
#Mann= 9 ,-1 , 0
  4241.8     .12       0  4252.5     .16       0  4328.3     .12       0
  4574.7     .16       0  4976.7     .07       0  5069.2     .05       0
  5830.6     .12       0  5843.7     .16       0  6301.3     .05       0
Bank Sta=4968.8,5040.5
XS Rating Curve= 0 ,0
Exp/Cntr=0.3,0.1

Type RM Length L Ch R = 1 ,15791   ,1360,1360,1360
BEGIN DESCRIPTION:
PIN OAK CREEK 2 24.0
END DESCRIPTION:
XS GIS Cut Line= 4
      3506180.22     10545662.06      3505841.69     10545266.23
      3505805.23     10544974.57      3504645.41     10544574.09
#Sta/Elev= 30
  4392.9  417.22  4532.1  410.53  4634.4  404.65  4788.6  395.91  4924.3  394.14
  4952.2  394.01  5008.8  382.42  5027.8  387.06  5032.8  386.18  5039.3  390.12
  5059.5  394.88  5270.3  394.12  5361.6  393.26  5529.8   392.4  5603.7  392.04
    5613  388.51  5623.6  388.76  5629.6  392.61  5634.9  391.19  5660.8   393.6
  5685.2  388.09  5691.9  391.42  5729.4  389.93  5767.8     393  5873.8  394.88
  6036.4  406.99    6118  409.01  6284.9   419.2  6393.4  424.49  6434.7  424.69
#Mann= 13 ,-1 , 0
  4392.9     .12       0  4532.1     .16       0  4634.4     .12       0
  4924.3     .16       0  4952.2     .07       0  5059.5     .16       0
  5270.3     .05       0  5361.6     .16       0  5529.8     .12       0
  5685.2     .16       0  5767.8     .12       0  6036.4     .16       0
  6284.9     .05       0
Bank Sta=4952.2,5059.5
XS Rating Curve= 0 ,0
Exp/Cntr=0.3,0.1

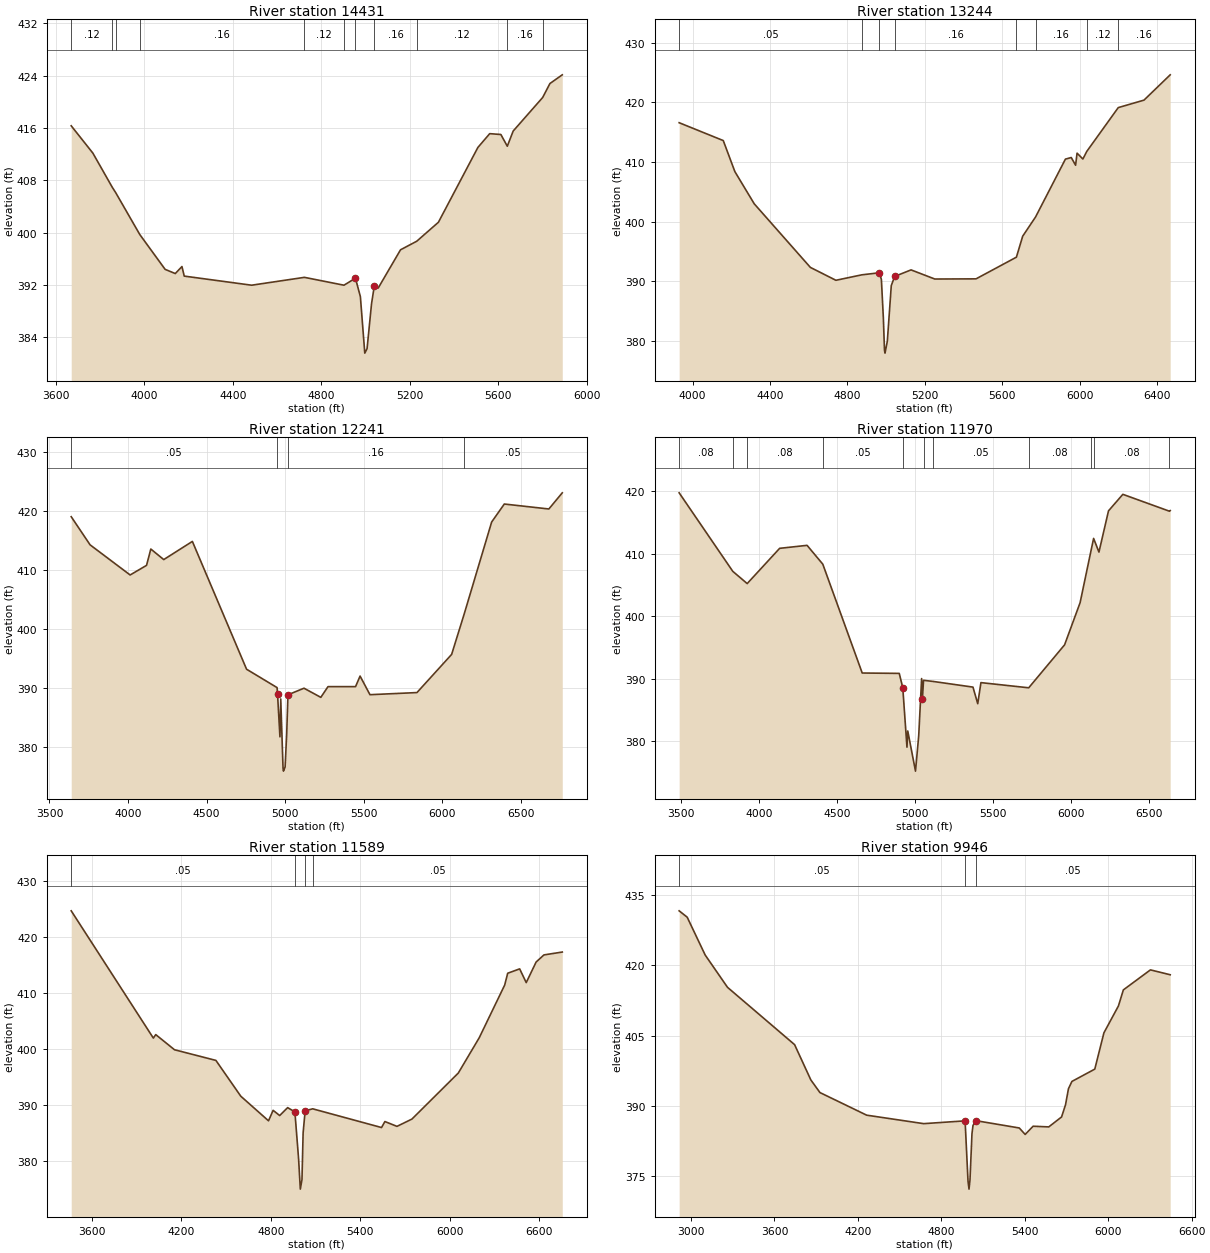
Type RM Length L Ch R = 1 ,14431   ,1187,1187,1187
BEGIN DESCRIPTION:
PIN OAK CREEK 2 21.0
END DESCRIPTION:
XS GIS Cut Line= 3
      3506273.62     10545476.35      3506069.64     10544686.45
      3504676.76     10544508.55
#Sta/Elev= 30
  3669.7  416.35  3767.5  412.18  3855.8  406.93  3870.9  406.13  3979.8  399.73
  4094.3  394.41  4140.1  393.77  4170.3  394.84  4180.7  393.38  4485.4  391.99
  4723.9  393.19  4902.8  391.99  4954.7  393.06    4977  390.24  4996.9  381.61
  5007.2  382.29  5027.4  389.15  5039.5   391.8  5057.6  391.56  5158.5   397.4
  5231.8  398.71  5329.8  401.61  5508.2  413.04  5561.7  415.15  5612.1  415.02
  5641.2  413.23  5667.8  415.55  5801.2  420.68  5833.9  422.81  5889.7  424.14
#Mann= 11 ,-1 , 0
  3669.7     .12       0  3855.8     .16       0  3870.9     .12       0
  3979.8     .16       0  4723.9     .12       0  4902.8     .16       0
  4954.7     .07       0  5039.5     .16       0  5231.8     .12       0
  5641.2     .16       0  5801.2     .05       0
Bank Sta=4954.7,5039.5
XS Rating Curve= 0 ,0
Exp/Cntr=0.3,0.1

Type RM Length L Ch R = 1 ,13244   ,1003,1003,1003
BEGIN DESCRIPTION:
PIN OAK CREEK 2 20.0
END DESCRIPTION:
XS GIS Cut Line= 4
      3507119.98     10543909.54       3506399.5     10543918.22
      3505679.01     10543766.32      3504602.63     10543675.17
#Sta/Elev= 30
  3930.7  416.57  4158.6  413.58  4218.6  408.38  4318.6  402.99  4608.6  392.34
  4740.5  390.18  4874.1  391.09  4965.4  391.44  4975.6  390.32  4985.8  383.85
  4991.6  378.48  4994.3  377.98  5006.3  379.98  5026.7   389.3  5044.4  390.83
  5128.9  391.92  5251.5  390.39  5464.7  390.42  5673.2  394.05  5705.6  397.56
  5772.1  400.78  5926.4  410.47  5956.5  410.74  5978.9  409.45  5986.6  411.47
  6016.7  410.49  6036.5  411.75  6199.4   419.1  6332.3  420.35  6467.8  424.59
#Mann= 8 ,-1 , 0
  3930.7     .05       0  4874.1     .16       0  4965.4     .07       0
  5044.4     .16       0  5673.2     .12       0  5772.1     .16       0
  6036.5     .12       0  6199.4     .16       0
Bank Sta=4965.4,5044.4
XS Rating Curve= 0 ,0
Exp/Cntr=0.3,0.1

Type RM Length L Ch R = 1 ,12241   ,271,271,271
BEGIN DESCRIPTION:
PIN OAK CREEK 2 19.0
END DESCRIPTION:
XS GIS Cut Line= 4
      3507590.17     10543415.84      3506342.77     10543178.86
      3504816.73     10542874.18      3504517.21     10542840.32
#Sta/Elev= 30
  3638.4  419.02  3758.6  414.25  4013.7  409.14  4118.1  410.77  4145.4  413.54
  4227.7  411.75    4410  414.83  4755.1  393.16  4949.6  390.04  4952.2  389.01
  4967.7   381.7  4972.8  388.12  4987.4  376.38  4990.1  375.88  5000.6  376.59
  5010.8  382.26  5018.7  388.82  5120.8  389.94    5228  388.39  5273.9  390.21
  5449.3  390.21    5478     392    5541  388.84  5840.3   389.2  6061.1  395.67
  6141.6  402.57    6316  418.12  6396.6  421.17  6680.3  420.33  6765.7  423.07
#Mann= 4 ,-1 , 0
  3638.4     .05       0  4949.6     .07       0  5018.7     .16       0
  6141.6     .05       0
Bank Sta=4952.2,5018.7
XS Rating Curve= 0 ,0
Exp/Cntr=0.3,0.1

Type RM Length L Ch R = 1 ,11970   ,381,381,381
BEGIN DESCRIPTION:
PIN OAK CREEK 2 18.0
END DESCRIPTION:
XS GIS Cut Line= 3
      3507624.06     10543251.79      3505806.31     10542863.76
      3504545.24     10542595.94
#Sta/Elev= 30
  3489.9  419.77  3833.8  407.18  3926.1  405.22  4134.1  410.87  4309.9  411.35
  4410.8  408.33  4663.4  390.88  4900.8  390.82  4923.4  388.54  4950.3  378.99
  4955.4  381.59    5005  375.15  5025.7  380.85  5044.2  389.99  5049.3  386.69
  5056.4  389.71  5117.9  389.53  5373.4  388.62    5404  385.96  5424.5  389.34
  5730.8  388.51  5960.8   395.4  6060.1  402.15  6131.8  410.69  6146.8  412.46
    6181  410.27  6242.3  416.88  6334.3  419.53  6633.1  416.82  6637.8  416.92
#Mann= 11 ,-1 , 0
  3489.9     .08       0  3833.8     .05       0  3926.1     .08       0
  4410.8     .05       0  4923.4     .07       0  5056.4     .16       0
  5117.9     .05       0  5730.8     .08       0  6131.8     .05       0
  6146.8     .08       0  6633.1     .05       0
Bank Sta=4923.4,5049.3
XS Rating Curve= 0 ,0
Exp/Cntr=0.3,0.1

Type RM Length L Ch R = 1 ,11589   ,1643,1643,1643
BEGIN DESCRIPTION:
PIN OAK CREEK 2 17.0
END DESCRIPTION:
XS GIS Cut Line= 4
      3507733.98     10543128.43      3506655.86     10542763.85
      3505723.57     10542414.89      3504567.36     10542315.94
#Sta/Elev= 30
  3460.8  424.64  4011.7  401.95  4027.9  402.57  4153.7  399.87  4431.4  397.97
  4598.2  391.59  4784.4   387.2  4815.1  389.07  4859.2  388.14  4912.6  389.55
  4961.2  388.79  4986.1  380.41  4997.7  375.02  5008.7  376.71  5016.4  385.05
    5030  388.98  5080.5  389.34  5542.5     386    5565  387.07    5646  386.21
  5746.4  387.51  6057.5  395.72    6198  402.02  6368.6  411.41  6388.7  413.51
    6469  414.29  6513.1  411.84  6579.4  415.51  6631.9  416.78  6754.8  417.29
#Mann= 4 ,-1 , 0
  3460.8     .05       0  4961.2    .035       0    5030     .16       0
  5080.5     .05       0
Bank Sta=4961.2,5030
XS Rating Curve= 0 ,0
Exp/Cntr=0.3,0.1

Type RM Length L Ch R = 1 ,9946    ,751,751,751
BEGIN DESCRIPTION:
PIN OAK CREEK 2 15.0
END DESCRIPTION:
XS GIS Cut Line= 4
      3508046.51     10542899.28      3506858.98     10542440.93
      3505733.98     10541430.52      3505036.63     10541165.11
#Sta/Elev= 30
  2914.5   431.6  2972.4  430.24  3101.4  422.19  3262.2  415.29  3744.6  403.07
  3861.6  395.54  3926.9  392.85  4262.9  388.03  4673.3  386.22  4970.8  386.82
  4991.7     374  4998.9  372.26  5005.9   374.2  5020.1  384.06  5027.6  385.84
  5048.5  386.86  5360.2   385.3  5402.8  383.92  5459.7  385.67  5572.5  385.53
  5664.5  387.65  5692.9  390.24    5714  393.66  5738.8  395.22  5903.4  397.85
  5969.1  405.59  6073.3  411.31  6108.8  414.74  6303.5  419.01  6445.7  417.97
#Mann= 3 , 0 , 0
  2914.5     .05       0  4970.8    .035       0  5048.5     .05       0
Bank Sta=4970.8,5048.5
XS Rating Curve= 0 ,0
Exp/Cntr=0.3,0.1

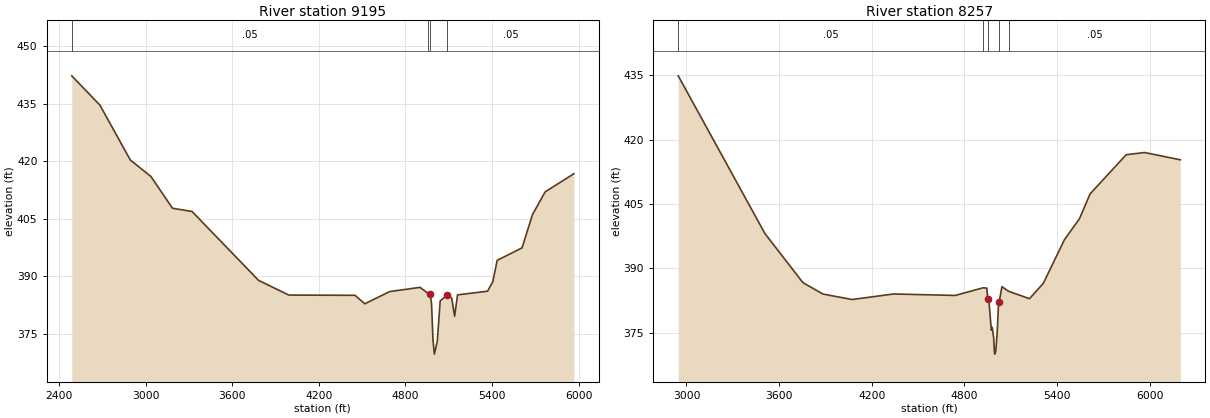
Type RM Length L Ch R = 1 ,9195    ,938,938,938
BEGIN DESCRIPTION:
PIN OAK CREEK 2 14.0
END DESCRIPTION:
XS GIS Cut Line= 4
      3508484.07     10542289.25      3506556.97     10541386.46
      3505958.01      10541369.1      3505325.72     10540962.01
#Sta/Elev= 30
  2488.4  442.22  2683.5  434.59  2894.5  420.28    3037  416.01  3186.3  407.74
  3321.9  406.89  3782.6  388.96  3992.4  385.12  4450.9  385.06  4519.4  382.85
  4691.4  386.03  4901.5  387.13  4960.4  385.48  4971.5  385.51  4981.5  382.95
  4991.5  373.46  5001.3  369.74  5021.5  373.09  5041.5   383.6  5091.6  385.21
  5121.6  384.32  5141.6   379.6  5161.6  385.17  5369.7  386.13    5406  388.57
  5436.4  394.16  5608.7  397.41  5681.3  406.09  5769.1  412.01  5967.7  416.71
#Mann= 4 ,-1 , 0
  2488.4     .05       0  4960.4     .12       0  4971.5     .07       0
  5091.6     .05       0
Bank Sta=4971.5,5091.6
XS Rating Curve= 0 ,0
Exp/Cntr=0.3,0.1

Type RM Length L Ch R = 1 ,8257    ,1350,1350,1350
BEGIN DESCRIPTION:
PIN OAK CREEK 2 13.0
END DESCRIPTION:
XS GIS Cut Line= 2
        3508234.     10541654.48      3505286.55      10540279.7
#Sta/Elev= 30
  2946.6  434.86  3507.6  398.13  3754.2  386.66  3884.4  383.99  4072.8  382.72
  4340.9  384.01  4740.6  383.67  4921.3  385.45  4945.9  385.37  4951.9  382.75
  4957.4  383.28  4974.7  375.59  4980.2  376.27    4990  373.72  4994.6  370.49
  4997.3  369.99  5003.1   370.6  5012.1  374.61  5020.5  381.03    5026  382.21
  5043.3  385.72  5087.1  384.63  5221.8  382.91  5311.4  386.48  5448.5  396.68
  5545.5  401.54  5614.1  407.32  5848.2  416.47  5968.1  416.98  6198.9  415.29
#Mann= 5 ,-1 , 0
  2946.6     .05       0  4921.3     .12       0  4951.9     .07       0
    5026     .12       0  5087.1     .05       0
Bank Sta=4951.9,5026
XS Rating Curve= 0 ,0
Exp/Cntr=0.3,0.1