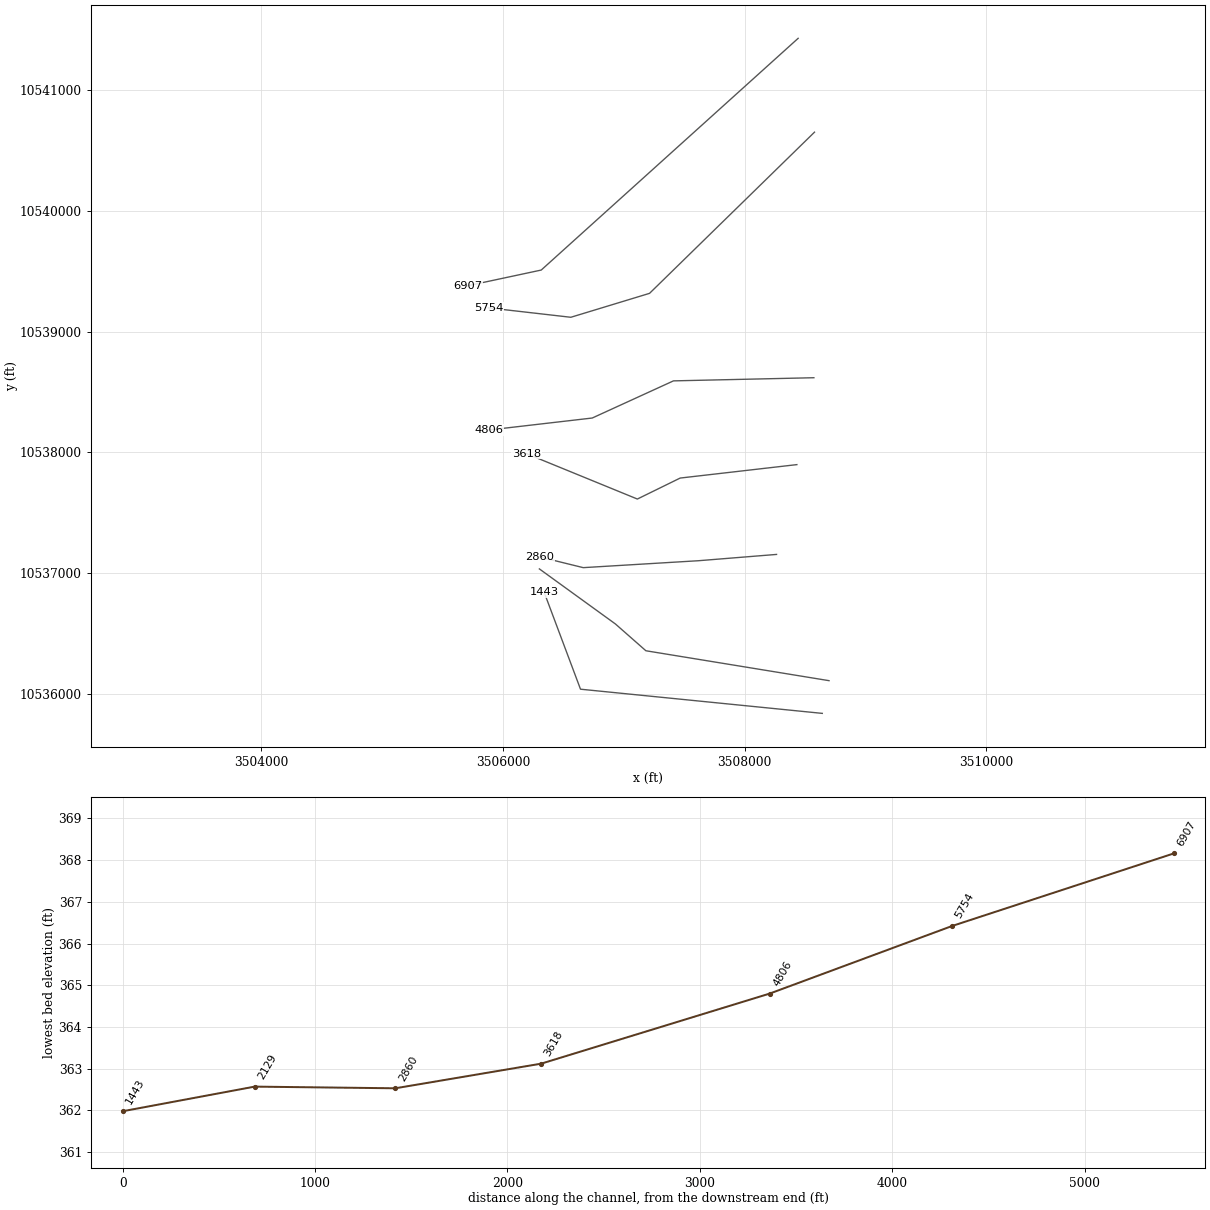
HEC-RAS study PIN OAK CREEK 2.prj: PIN OAK CREEK 2 Base Level Engineering

--- PIN OAK CREEK 2.g01 (geometry) --- (continued)

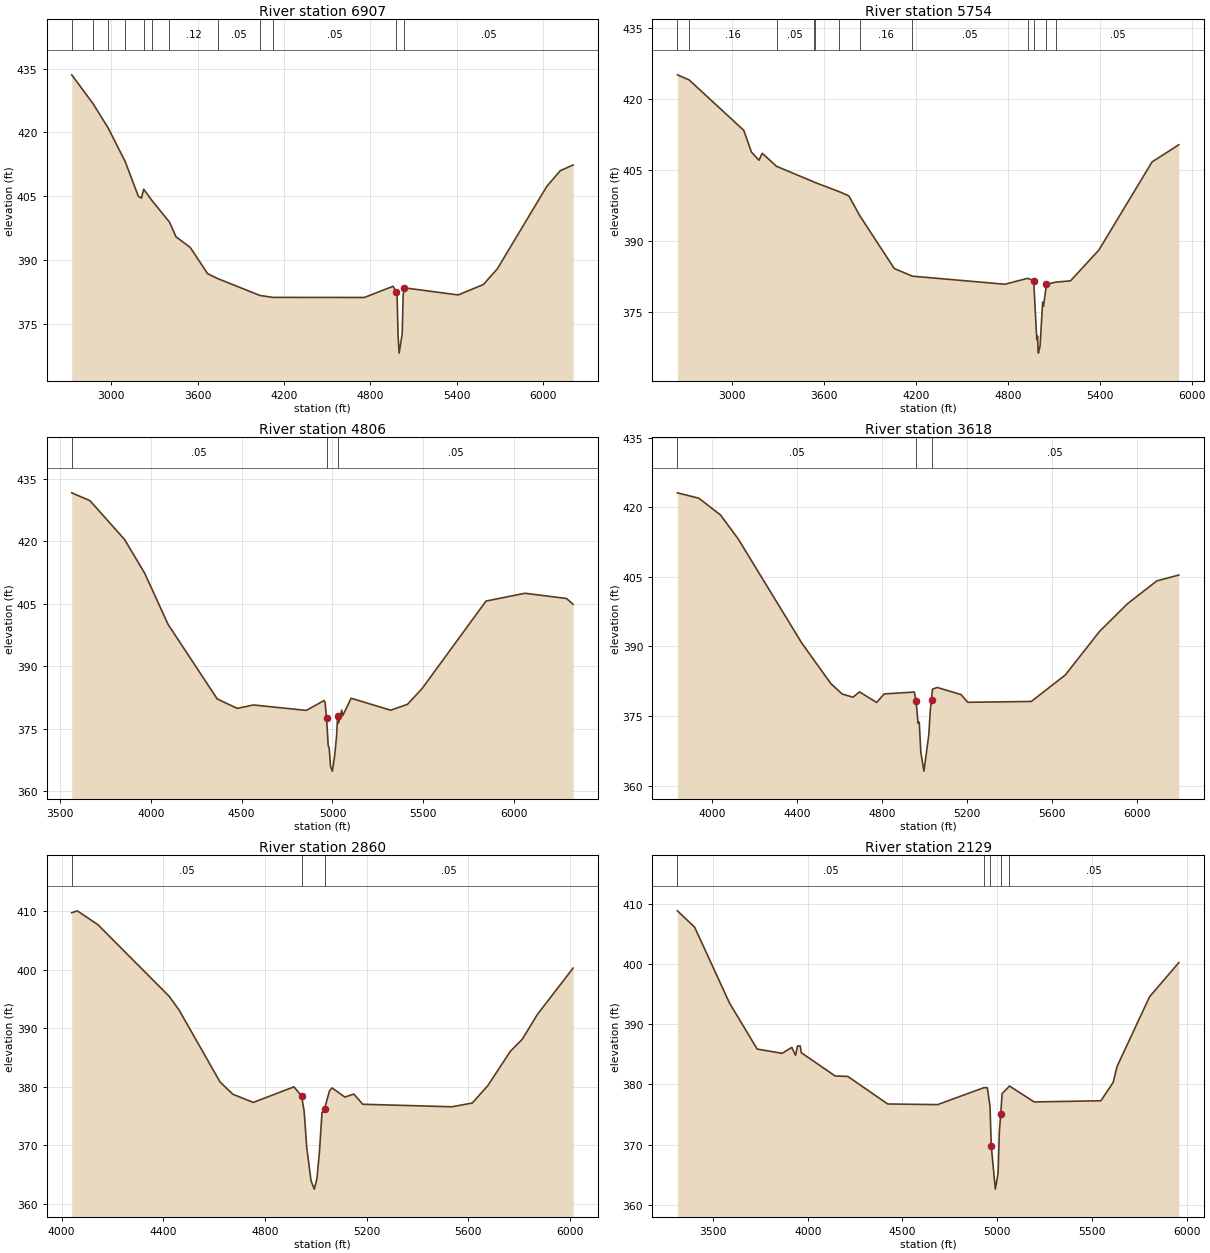
Type RM Length L Ch R = 1 ,6907    ,1153,1153,1153
BEGIN DESCRIPTION:
PIN OAK CREEK 2 11.0
END DESCRIPTION:
XS GIS Cut Line= 3
      3508442.29     10541425.29      3506317.32     10539508.64
      3505707.93     10539378.43
#Sta/Elev= 30
  2724.6  433.53  2871.6  426.82  2976.9  421.11  3096.3  413.15  3187.4  405.01
  3209.1  404.56  3224.8  406.66  3283.3  403.96  3404.1  398.93  3449.7  395.47
  3548.4  392.98  3668.7  386.84  3739.1  385.67    4033   381.7  4124.3  381.25
  4759.1  381.24  4957.9  383.86  4978.8  382.62  4986.3   381.3    4993  372.26
  5000.2  368.16  5021.4  372.68  5028.1  381.67  5035.6   383.5  5410.8  381.83
  5586.3  384.28  5683.6  388.01  6026.3  407.31  6120.2  411.02  6209.4  412.36
#Mann= 12 ,-1 , 0
  2724.6     .05       0  2871.6     .16       0  2976.9     .12       0
  3096.3     .16       0  3224.8     .12       0  3283.3     .16       0
  3404.1     .12       0  3739.1     .05       0    4033     .07       0
  4124.3     .05       0  4978.8    .035       0  5035.6     .05       0
Bank Sta=4978.8,5035.6
XS Rating Curve= 0 ,0
Exp/Cntr=0.3,0.1

Type RM Length L Ch R = 1 ,5754    ,948,948,948
BEGIN DESCRIPTION:
PIN OAK CREEK 2 9.0
END DESCRIPTION:
XS GIS Cut Line= 4
      3508577.72     10540649.26      3507213.15     10539315.93
      3506562.11     10539118.02      3505879.86     10539196.14
#Sta/Elev= 30
  2641.2  425.04  2717.5  423.97  3074.8  413.34  3124.4  408.77  3173.9  407.04
    3195  408.52  3288.8  405.77  3532.6  402.48  3541.3  402.35  3699.2  400.41
  3760.8  399.54  3832.3  395.38  4057.8  384.23  4176.3  382.63  4780.1  380.93
  4929.3  382.18  4968.2  381.69  4988.7  369.22  4993.9  369.99  4996.6  366.92
  4999.3  366.42    5010  367.94  5026.8  377.18    5032  376.26  5051.8  380.92
    5114  381.38  5208.6  381.64  5394.4  388.14  5741.3  406.69  5916.2  410.31
#Mann= 12 ,-1 , 0
  2641.2     .05       0  2717.5     .16       0  3288.8     .05       0
  3532.6     .16       0  3541.3     .05       0  3699.2     .12       0
  3832.3     .16       0  4176.3     .05       0  4929.3     .16       0
  4968.2     .07       0  5051.8     .16       0    5114     .05       0
Bank Sta=4968.2,5051.8
XS Rating Curve= 0 ,0
Exp/Cntr=0.3,0.1

Type RM Length L Ch R = 1 ,4806    ,1188,1188,1188
BEGIN DESCRIPTION:
PIN OAK CREEK 2 7.0
END DESCRIPTION:
XS GIS Cut Line= 4
      3508572.56     10538618.02      3507411.07     10538591.97
      3506739.19     10538284.68       3505886.1     10538185.85
#Sta/Elev= 30
  3564.9  431.68  3665.4  429.79  3855.4  420.48  3965.5  412.44  4095.5  400.04
  4365.6  382.15  4475.6  379.88  4565.6   380.7  4855.9  379.39  4953.4  381.76
  4958.9  381.38  4967.5  377.58  4976.4  370.96  4981.9  370.37  4989.5  365.88
  4999.2   364.8  5011.4   368.3  5022.4  373.13    5028  378.01  5033.5  376.37
    5051  379.46  5056.5  378.13  5102.5  382.32  5320.7  379.43  5412.8  380.86
  5492.8  384.62  5845.1  405.67  6059.1  407.54    6288  406.29  6324.3   404.9
#Mann= 3 , 0 , 0
  3564.9     .05       0  4967.5    .035       0    5028     .05       0
Bank Sta=4967.5,5028
XS Rating Curve= 0 ,0
Exp/Cntr=0.3,0.1

Type RM Length L Ch R = 1 ,3618    ,758,758,758
BEGIN DESCRIPTION:
PIN OAK CREEK 2 6.0
END DESCRIPTION:
XS GIS Cut Line= 4
      3508431.88     10537899.26      3507466.62     10537788.15
      3507112.46     10537614.54      3506196.41     10537989.29
#Sta/Elev= 30
  3838.4  423.08  3938.8  421.92  4040.4  418.33  4124.4  413.12    4422  390.76
  4559.4  381.97  4613.3  379.71  4663.6  379.05  4693.8   380.2  4774.3  377.91
  4809.8  379.75    4952  380.16  4959.8  378.18    4969  373.43  4974.5  373.69
  4982.1  367.16  4996.8  363.12  5019.5  370.98  5026.7  376.31  5032.2  378.53
  5036.4  380.76  5058.9  381.15  5171.4   379.6  5202.1  377.95  5501.2  378.13
  5661.5  383.86  5821.8  393.23  5952.6  399.17  6090.8   404.1  6194.2  405.37
#Mann= 3 , 0 , 0
  3838.4     .05       0  4959.8    .035       0  5032.2     .05       0
Bank Sta=4959.8,5032.2
XS Rating Curve= 0 ,0
Exp/Cntr=0.3,0.1

Type RM Length L Ch R = 1 ,2860    ,731,731,731
BEGIN DESCRIPTION:
PIN OAK CREEK 2 5.0
END DESCRIPTION:
XS GIS Cut Line= 4
      3508263.75     10537156.42       3507617.9     10537104.34
      3506664.78     10537047.04      3506306.29     10537135.37
#Sta/Elev= 30
  4040.1  409.78  4061.8  410.11  4142.1  407.78    4423  395.52  4463.1  393.09
  4623.6  380.84  4673.8  378.75    4754  377.35  4914.2  380.02  4944.3  378.45
  4954.3  375.81  4964.3   369.7  4981.2  363.98  4994.1  362.53  5004.4  364.28
  5014.4  368.91  5024.4   375.6  5034.5   376.3  5054.5   379.4  5064.5  379.83
  5114.6  378.26  5149.6  378.79  5184.7  377.04  5535.4  376.61  5615.5  377.25
  5676.5  380.22  5765.3  386.09    5812  388.15  5872.2  392.43  6012.1  400.32
#Mann= 3 , 0 , 0
  4040.1     .05       0  4944.3    .035       0  5034.5     .05       0
Bank Sta=4944.3,5034.5
XS Rating Curve= 0 ,0
Exp/Cntr=0.3,0.1

Type RM Length L Ch R = 1 ,2129    ,686,686,686
BEGIN DESCRIPTION:
PIN OAK CREEK 2 2.0
END DESCRIPTION:
XS GIS Cut Line= 4
      3508697.72     10536112.22      3507182.91     10536359.62
      3506931.18     10536580.98      3506301.84      10537036.7
#Sta/Elev= 30
  3312.1  408.91  3402.7   406.2    3587  393.56  3733.2  385.89  3864.9  385.18
  3915.6  386.17  3935.9  384.85    3946  386.41  3960.6   386.4  3966.3  385.28
  4144.8  381.41  4211.3  381.34  4422.2  376.75  4685.7  376.64    4929  379.45
  4948.2  379.47  4962.4  376.35  4969.1  369.71  4990.6  362.57  5005.1  365.22
  5011.8   372.2  5019.3  375.12    5026  378.45  5065.2  379.74  5195.7  377.09
  5547.6  377.28  5612.5  380.33  5633.4  383.01  5805.1  394.62  5959.2  400.28
#Mann= 5 ,-1 , 0
  3312.1     .05       0    4929     .16       0  4962.4     .07       0
  5019.3     .16       0  5065.2     .05       0
Bank Sta=4969.1,5019.3
XS Rating Curve= 0 ,0
Exp/Cntr=0.3,0.1

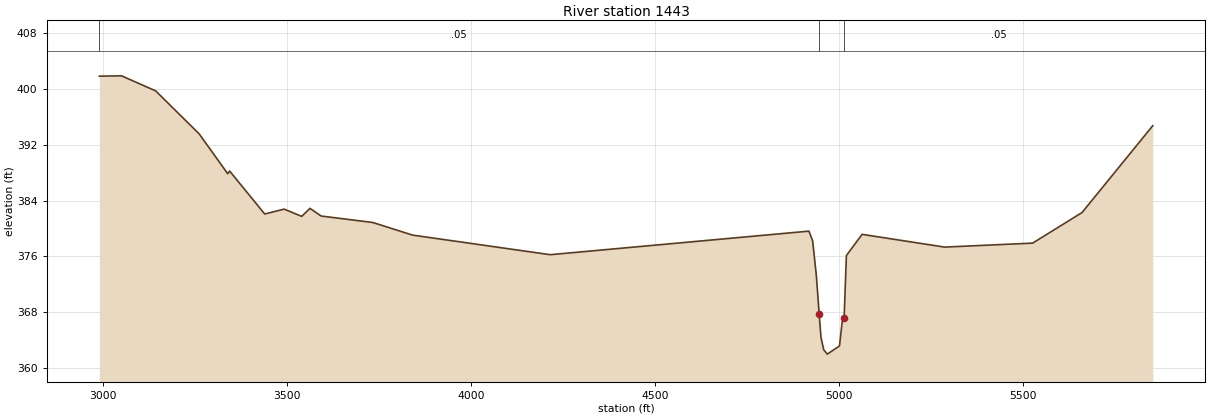
Type RM Length L Ch R = 1 ,1443    ,0,0,0
BEGIN DESCRIPTION:
PIN OAK CREEK 2 1.0
END DESCRIPTION:
XS GIS Cut Line= 3
      3508642.07     10535841.65      3506642.11     10536041.64
      3506342.12     10536841.61
#Sta/Elev= 30
    2989  401.87  3049.3  401.92  3142.2  399.76  3260.3   393.6  3338.2  387.86
  3343.2  388.26  3438.7  382.09  3491.5  382.79  3539.2  381.75  3561.8   382.9
    3592   381.8  3732.7  380.87  3840.7  379.06    4215  376.25  4918.5  379.63
  4928.6  378.23  4938.6  373.26  4946.2  367.81  4951.2  364.38  4958.7   362.6
  4968.5  361.98  5001.6  363.16  5008.7  366.56  5014.1  367.13  5020.3  376.13
    5063  379.17  5287.3  377.34  5526.7  377.91  5661.1   382.3  5853.3  394.76
#Mann= 3 , 0 , 0
    2989     .05       0  4946.2    .035       0  5014.1     .05       0
Bank Sta=4946.2,5014.1
XS Rating Curve= 0 ,0
Exp/Cntr=0.3,0.1

Chan Stop Cuts=-1
Use User Specified Reach Order=0
Composite Channel Slope=5