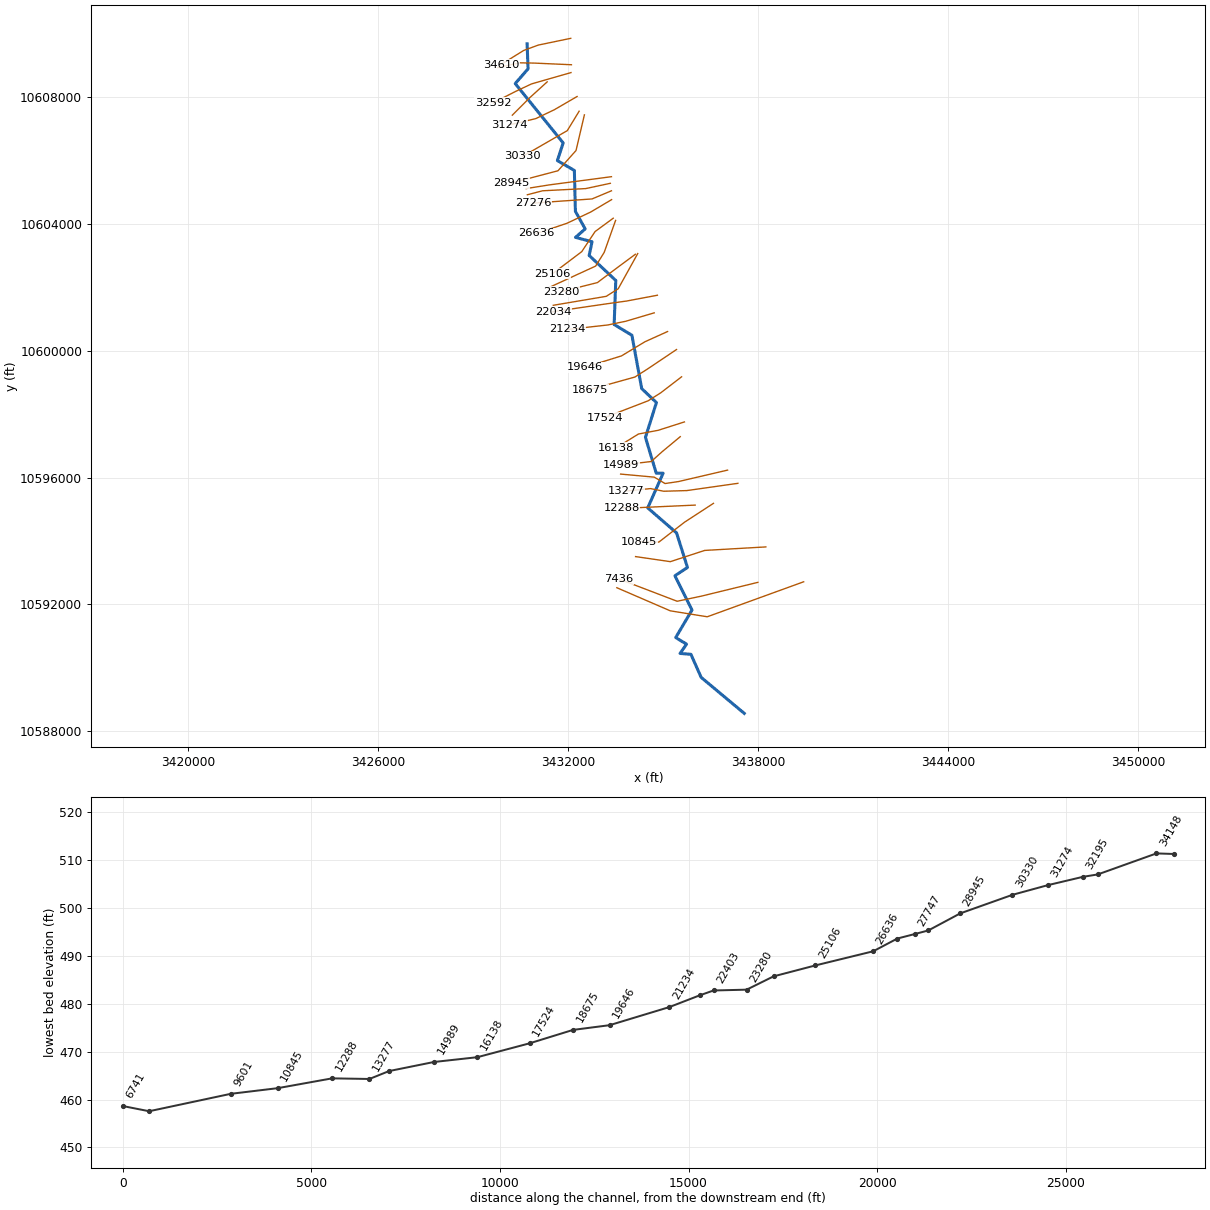
--- PIN OAK CREEK.prj (project) ---

Proj Title=PIN OAK CREEK Base Level Engineering
Current Plan=p01
Default Exp/Contr=0.3,0.1
English Units
Geom File=g01
Flow File=f01
Plan File=p01
BEGIN DESCRIPTION:
PIN OAK CREEK
END DESCRIPTION:

--- PIN OAK CREEK.p01 (plan) ---

Plan Title=Multiple Run
Short Identifier=Multiple
Geom File=g01
Flow File=f01
Subcritical Flow
K Sum by GR= 0
Std Step Tol= 0.01
Critical Tol= 0.01
Num of Std Step Trials= 20
Max Error Tol= 0.3
Flow Tol Ratio= 0.001
Split Flow NTrial= 30
Split Flow Tol= 0.02
Split Flow Ratio= 0.02
Log Output Level= 0
Friction Slope Method= 1
Unsteady Friction Slope Method= 2
Unsteady Bridges Friction Slope Method= 1
Parabolic Critical Depth
Global Vel Dist=  1 , 1 , 1
Global Log Level= 0
CheckData=True
Encroach Param= -1, 0, 0, 0
BEGIN DESCRIPTION:
Multiple Run
END DESCRIPTION:

--- PIN OAK CREEK.f01 (steady flow) ---

Flow Title=Multiple
Number of Profiles=7
Profile Names=10-year,25-year,50-year,1pct_min,100-year,1pct_plu,500-year
River Rch & RM= PIN OAK CREEK,Reach-1,34610
     482     605     694     579     783    1058     994
River Rch & RM= PIN OAK CREEK,Reach-1,27747
     850    1096    1282    1088    1471    1990    1935
River Rch & RM= PIN OAK CREEK,Reach-1,23280
     881    1135    1326    1124    1520    2055    1993
River Rch & RM= PIN OAK CREEK,Reach-1,18675
     928    1197    1400    1187    1605    2171    2108
River Rch & RM= PIN OAK CREEK,Reach-1,13797
    1071    1385    1622    1376    1860    2516    2446
Boundary for River Rch & Prof#=PIN OAK CREEK,Reach-1,1
Up Type=0
Dn Type=3
Dn Slope=0.005
Boundary for River Rch & Prof#=PIN OAK CREEK,Reach-1,2
Up Type=0
Dn Type=3
Dn Slope=0.005
Boundary for River Rch & Prof#=PIN OAK CREEK,Reach-1,3
Up Type=0
Dn Type=3
Dn Slope=0.005
Boundary for River Rch & Prof#=PIN OAK CREEK,Reach-1,4
Up Type=0
Dn Type=3
Dn Slope=0.005
Boundary for River Rch & Prof#=PIN OAK CREEK,Reach-1,5
Up Type=0
Dn Type=3
Dn Slope=0.005
Boundary for River Rch & Prof#=PIN OAK CREEK,Reach-1,6
Up Type=0
Dn Type=3
Dn Slope=0.005
Boundary for River Rch & Prof#=PIN OAK CREEK,Reach-1,7
Up Type=0
Dn Type=3
Dn Slope=0.005

--- PIN OAK CREEK.g01 (geometry) ---

Geom Title=Existing Conditions

River Reach=PIN OAK CREEK,Reach-1
Reach XY= 30
      3430708.88     10609695.13      3430739.05     10608902.98
      3430333.13     10608437.81      3431846.89     10606564.50
      3431664.03     10606007.52      3432200.12     10605695.92
      3432232.89     10604405.70      3432541.40     10603851.54
      3432235.82     10603583.30      3432758.20     10603445.89
      3432666.85     10603013.66      3433507.08     10602223.72
      3433455.78     10600833.68      3434016.71     10600494.53
      3434325.18     10598812.91      3434789.79     10598370.21
      3434443.36     10597271.98      3434784.86     10596142.03
      3435001.26     10596140.90      3434515.68     10595046.31
      3435424.71     10594257.79      3435770.16     10593166.57
      3435373.98     10592905.73      3435912.30     10591822.75
      3435398.44     10590953.90      3435740.67     10590746.12
      3435535.60     10590453.20      3435879.22     10590425.79
      3436202.42     10589696.73      3437562.11     10588561.64

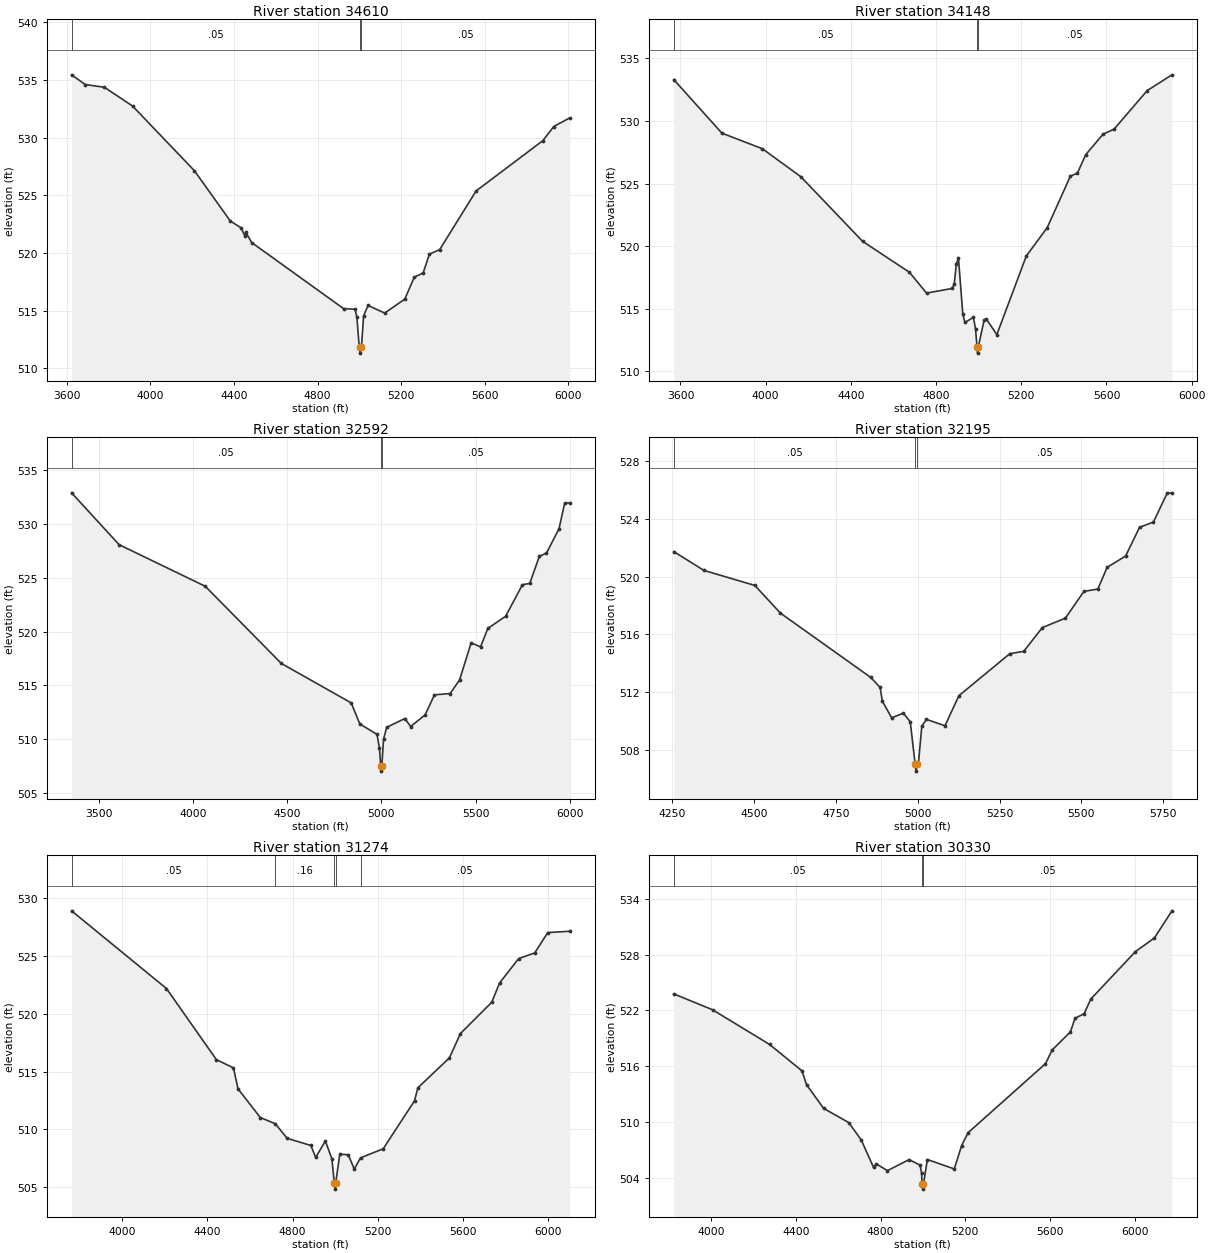
Type RM Length L Ch R = 1,34610,462,462,462
BEGIN DESCRIPTION:
PIN OAK CREEK 47.0
END DESCRIPTION:
XS GIS Cut Line= 4
      3432086.05     10609865.50      3431061.72     10609652.82
      3430601.66     10609483.55      3429881.26     10609036.56
#Sta/Elev= 30
  3622.8  535.43  3688.1  534.59  3780.0  534.35  3915.1  532.72  4210.8  527.12
  4382.6  522.76  4433.7  522.18  4451.2  521.51  4456.3  521.80  4484.7  520.90
  4924.3  515.18  4979.7  515.12  4988.2  514.42  4998.9  511.98  5001.8  511.82
  5004.6  511.32  5007.8  511.82  5010.2  511.86  5020.2  514.53  5041.5  515.45
  5121.4  514.79  5217.5  516.00  5262.9  517.90  5305.4  518.27  5335.2  519.89
  5384.5  520.29  5558.8  525.37  5878.3  529.73  5930.2  530.95  6007.0  531.70
#Mann=3,-1,0
  3622.8    0.05       0  5001.8   0.035       0  5007.8    0.05       0
Bank Sta=5001.8,5007.8
Exp/Cntr=0.3,0.1

Type RM Length L Ch R = 1,34148,1556,1556,1556
BEGIN DESCRIPTION:
PIN OAK CREEK 46.0
END DESCRIPTION:
XS GIS Cut Line= 4
      3432107.71     10609032.17      3430931.52     10609084.25
      3430480.13     10609092.93      3429786.35     10608941.17
#Sta/Elev= 30
  3568.5  533.31  3794.3  529.03  3984.5  527.78  4164.7  525.55  4455.0  520.38
  4675.2  517.90  4755.3  516.24  4875.3  516.61  4885.3  516.94  4895.3  518.60
  4905.3  519.01  4925.3  514.60  4935.3  513.89  4975.3  514.30  4985.3  513.37
  4992.3  511.94  4995.1  511.44  4998.3  511.94  5025.3  514.05  5035.3  514.18
  5085.3  512.92  5223.8  519.21  5321.8  521.47  5430.7  525.59  5463.6  525.83
  5502.4  527.30  5584.3  528.95  5635.5  529.34  5791.2  532.43  5907.5  533.69
#Mann=3,-1,0
  3568.5    0.05       0  4992.3   0.035       0  4998.3    0.05       0
Bank Sta=4992.3,4998.3
Exp/Cntr=0.3,0.1

Type RM Length L Ch R = 1,32592,397,397,397
BEGIN DESCRIPTION:
PIN OAK CREEK 45.0
END DESCRIPTION:
XS GIS Cut Line= 4
      3432094.75     10608784.78      3430853.39     10608428.87
      3430354.26     10608194.49      3429638.11     10607829.91
#Sta/Elev= 30
  3354.3  532.87  3606.7  528.06  4064.4  524.20  4468.6  517.04  4839.8  513.38
  4885.4  511.43  4976.6  510.46  4989.6  509.22  4996.4  507.55  4999.2  507.05
  5002.4  507.55  5011.7  510.02  5027.8  511.11  5124.6  511.93  5155.3  511.19
  5232.0  512.26  5282.1  514.13  5365.4  514.25  5415.5  515.52  5476.7  518.95
  5526.8  518.58  5565.6  520.29  5660.2  521.42  5749.3  524.35  5788.1  524.46
  5839.1  526.98  5877.0  527.28  5943.7  529.54  5973.8  531.93  6000.7  531.93
#Mann=3,-1,0
  3354.3    0.05       0  4996.4   0.035       0  5002.4    0.05       0
Bank Sta=4996.4,5002.4
Exp/Cntr=0.3,0.1

Type RM Length L Ch R = 1,32195,921,921,921
BEGIN DESCRIPTION:
PIN OAK CREEK 44.0
END DESCRIPTION:
XS GIS Cut Line= 3
      3431342.10     10608491.63      3430792.11     10607991.64
      3430242.11     10607441.65
#Sta/Elev= 30
  4255.3  521.73  4347.5  520.43  4502.9  519.39  4580.7  517.48  4857.0  513.02
  4885.4  512.33  4892.2  511.38  4920.5  510.23  4956.4  510.55  4977.3  509.96
  4992.2  507.04  4995.0  506.54  4998.2  507.04  5002.1  507.04  5012.7  509.66
  5026.9  510.12  5083.4  509.68  5125.9  511.76  5281.4  514.67  5323.9  514.83
  5380.4  516.47  5451.1  517.13  5507.7  518.98  5550.1  519.14  5578.4  520.64
  5635.0  521.43  5677.4  523.41  5719.8  523.78  5762.3  525.80  5776.4  525.77
#Mann=3,-1,0
  4255.3    0.05       0  4992.2   0.035       0  4998.2    0.05       0
Bank Sta=4992.2,4998.2
Exp/Cntr=0.3,0.1

Type RM Length L Ch R = 1,31274,944,944,944
BEGIN DESCRIPTION:
PIN OAK CREEK 42.0
END DESCRIPTION:
XS GIS Cut Line= 4
      3432285.72     10608029.58      3431569.54     10607612.89
      3430979.26     10607330.78      3430141.54     10607131.11
#Sta/Elev= 30
  3760.5  528.92  4207.0  522.19  4442.0  516.03  4522.2  515.32  4543.7  513.50
  4648.6  511.02  4719.2  510.48  4774.7  509.22  4886.4  508.60  4909.1  507.56
  4954.5  508.99  4985.2  507.45  4996.8  505.32  4999.6  504.82  5002.8  505.32
  5022.5  507.84  5062.3  507.80  5090.6  506.56  5119.9  507.53  5226.6  508.31
  5374.0  512.47  5390.0  513.60  5538.5  516.19  5589.9  518.29  5737.3  521.00
  5774.3  522.67  5863.7  524.78  5939.4  525.27  6001.1  527.04  6104.5  527.15
#Mann=5,-1,0
  3760.5    0.05       0  4719.2    0.16       0  4996.8    0.07       0
  5002.8    0.16       0  5119.9    0.05       0
Bank Sta=4996.8,5002.8
Exp/Cntr=0.3,0.1

Type RM Length L Ch R = 1,30330,1385,1385,1385
BEGIN DESCRIPTION:
PIN OAK CREEK 41.0
END DESCRIPTION:
XS GIS Cut Line= 3
      3432350.80     10607565.17      3431977.52     10606953.17
      3430562.60     10606137.20
#Sta/Elev= 30
  3824.7  523.77  4007.5  522.07  4276.6  518.34  4429.6  515.50  4450.9  514.02
  4531.6  511.47  4650.3  509.94  4709.2  508.07  4767.1  505.12  4779.6  505.51
  4832.7  504.78  4934.7  505.96  4986.5  505.37  4993.6  504.52  4996.4  503.29
  4999.1  502.79  5002.4  503.29  5021.1  505.97  5148.1  504.96  5182.7  507.47
  5213.4  508.86  5578.2  516.27  5609.8  517.75  5696.0  519.69  5717.6  521.15
  5760.7  521.65  5792.2  523.22  6002.3  528.31  6092.4  529.79  6174.9  532.70
#Mann=3,-1,0
  3824.7    0.05       0  4996.4   0.035       0  5002.4    0.05       0
Bank Sta=4996.4,5002.4
Exp/Cntr=0.3,0.1

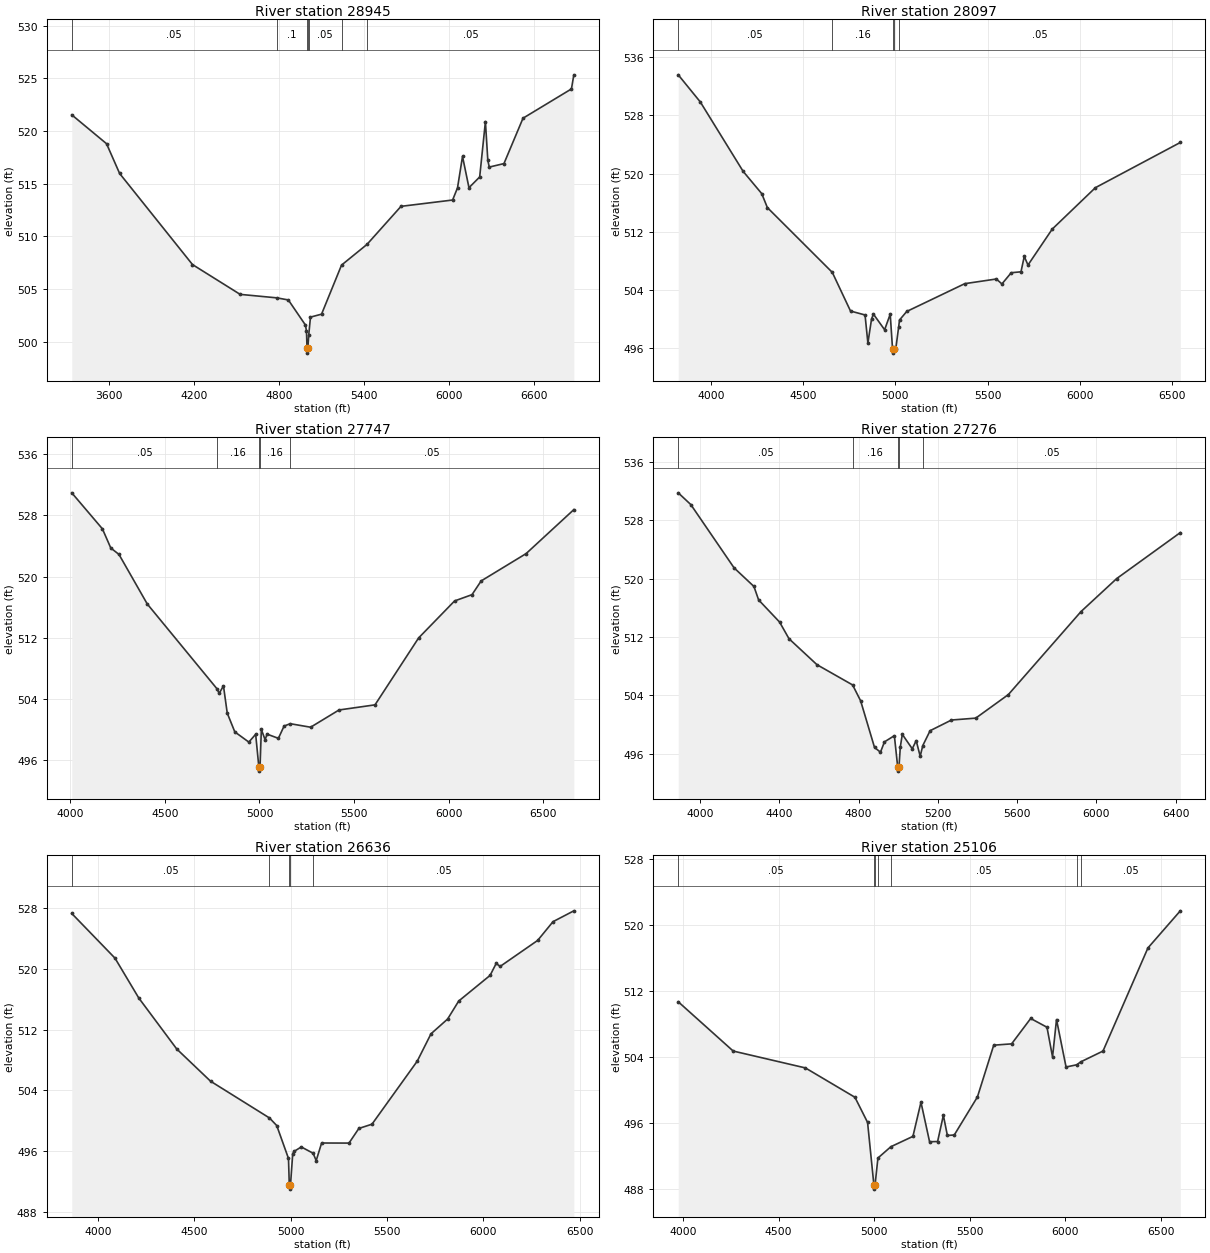
Type RM Length L Ch R = 1,28945,848,848,848
BEGIN DESCRIPTION:
PIN OAK CREEK 40.0
END DESCRIPTION:
XS GIS Cut Line= 4
      3432516.65     10607450.15      3432252.76     10606325.13
      3431683.32     10605686.24      3430205.62     10605297.74
#Sta/Elev= 30
  3340.5  521.54  3585.5  518.80  3677.9  515.97  4191.5  507.32  4527.5  504.49
  4785.5  504.16  4867.2  503.96  4987.6  501.58  4995.1  501.01  4998.8  499.41
  5001.5  498.91  5004.8  499.41  5011.1  500.66  5023.2  502.33  5101.3  502.61
  5242.2  507.27  5421.2  509.23  5661.5  512.85  6025.2  513.45  6059.8  514.61
  6095.0  517.59  6140.5  514.62  6216.0  515.64  6256.4  520.90  6273.4  517.21
  6283.7  516.58  6387.1  516.91  6521.5  521.22  6862.8  524.00  6879.8  525.34
#Mann=7,-1,0
  3340.5    0.05       0  4785.5     0.1       0  4998.8    0.07       0
  5004.8     0.1       0  5011.1    0.05       0  5242.2     0.1       0
  5421.2    0.05       0
Bank Sta=4998.8,5004.8
Exp/Cntr=0.3,0.1

Type RM Length L Ch R = 1,28097,350,350,350
BEGIN DESCRIPTION:
PIN OAK CREEK 39.0
END DESCRIPTION:
XS GIS Cut Line= 3
      3433370.78     10605498.73      3431419.43     10605241.79
      3430676.74     10605123.80
#Sta/Elev= 30
  3823.4  533.56  3943.1  529.83  4175.1  520.30  4275.9  517.24  4306.2  515.33
  4658.1  506.43  4756.8  501.12  4835.5  500.58  4850.9  496.72  4871.0  500.06
  4881.1  500.69  4941.6  498.55  4971.9  500.69  4984.7  495.84  4987.5  495.34
  4990.7  495.84  5002.2  495.96  5017.4  498.90  5022.3  499.89  5061.3  501.06
  5375.9  504.88  5546.8  505.52  5577.1  504.84  5627.5  506.38  5680.4  506.51
  5698.1  508.62  5718.3  507.44  5849.6  512.37  6083.5  518.06  6543.6  524.27
#Mann=5,-1,0
  3823.4    0.05       0  4658.1    0.16       0  4984.7    0.07       0
  4990.7    0.16       0  5017.4    0.05       0
Bank Sta=4984.7,4990.7
Exp/Cntr=0.3,0.1

Type RM Length L Ch R = 1,27747,471,471,471
BEGIN DESCRIPTION:
PIN OAK CREEK 38.0
END DESCRIPTION:
XS GIS Cut Line= 4
      3433336.09     10605290.41      3432558.32     10605123.74
      3431197.20     10605054.29      3430718.06     10604929.30
#Sta/Elev= 30
  4007.9  530.93  4169.8  526.23  4214.1  523.73  4257.4  522.89  4406.7  516.43
  4776.2  505.33  4786.8  504.75  4809.6  505.74  4829.6  502.18  4869.6  499.73
  4943.7  498.40  4979.8  499.42  4996.8  495.11  4999.6  494.61  5002.8  495.11
  5009.8  500.05  5029.8  498.70  5039.9  499.44  5099.9  498.89  5130.0  500.49
  5162.4  500.80  5270.2  500.34  5420.3  502.59  5610.6  503.26  5840.9  511.99
  6031.1  516.82  6123.2  517.64  6171.5  519.43  6409.2  523.00  6661.4  528.74
#Mann=5,-1,0
  4007.9    0.05       0  4776.2    0.16       0  4996.8    0.07       0
  5002.8    0.16       0  5162.4    0.05       0
Bank Sta=4996.8,5002.8
Exp/Cntr=0.3,0.1

Type RM Length L Ch R = 1,27276,640,640,640
BEGIN DESCRIPTION:
PIN OAK CREEK 37.0
END DESCRIPTION:
XS GIS Cut Line= 3
      3433370.77     10605054.28      3432759.70     10604797.35
      3430891.64     10604665.40
#Sta/Elev= 30
  3888.7  531.72  3952.3  530.11  4170.6  521.46  4271.0  518.91  4294.7  517.07
  4400.6  514.04  4448.1  511.76  4589.3  508.21  4769.3  505.44  4809.8  503.27
  4880.0  496.89  4910.1  496.24  4930.1  497.65  4980.2  498.50  4997.3  494.15
  5000.0  493.65  5003.3  494.15  5010.3  496.97  5020.3  498.68  5070.5  496.71
  5090.5  497.82  5110.6  495.68  5123.8  497.15  5160.7  499.18  5268.6  500.64
  5391.3  500.90  5555.9  504.12  5922.6  515.47  6103.0  519.99  6424.3  526.28
#Mann=5,-1,0
  3888.7    0.05       0  4769.3    0.16       0  4997.3    0.07       0
  5003.3    0.16       0  5123.8    0.05       0
Bank Sta=4997.3,5003.3
Exp/Cntr=0.3,0.1

Type RM Length L Ch R = 1,26636,1530,1530,1530
BEGIN DESCRIPTION:
PIN OAK CREEK 34.0
END DESCRIPTION:
XS GIS Cut Line= 4
      3433375.11     10604774.36      3432715.37     10604383.73
      3431964.50     10604027.82      3431009.63     10603706.64
#Sta/Elev= 30
  3864.3  527.33  4088.6  521.44  4211.9  516.19  4408.8  509.47  4584.3  505.22
  4890.2  500.37  4927.8  499.37  4988.8  495.03  4993.0  491.49  4995.8  490.99
  4999.0  491.49  5010.9  495.68  5018.8  495.98  5055.2  496.55  5116.7  495.72
  5132.5  494.75  5160.7  497.07  5302.7  497.06  5353.9  498.99  5422.0  499.55
  5656.8  507.86  5728.3  511.47  5814.3  513.41  5872.1  515.79  6034.9  519.17
  6066.4  520.74  6087.0  520.35  6281.7  523.78  6361.3  526.25  6469.4  527.68
#Mann=5,-1,0
  3864.3    0.05       0  4890.2    0.16       0  4993.0    0.07       0
  4999.0    0.16       0  5116.7    0.05       0
Bank Sta=4993,4999
Exp/Cntr=0.3,0.1

Type RM Length L Ch R = 1,25106,1112,1112,1112
BEGIN DESCRIPTION:
PIN OAK CREEK 32.0
END DESCRIPTION:
XS GIS Cut Line= 4
      3433427.16     10604188.41      3432854.26     10603767.41
      3432433.25     10603133.73      3431509.90     10602435.79
#Sta/Elev= 30
  3974.0  510.70  4261.8  504.74  4639.9  502.70  4899.3  499.15  4965.5  496.11
  4998.6  488.54  5001.3  488.04  5004.6  488.54  5019.7  491.80  5087.5  493.17
  5203.0  494.42  5245.1  498.55  5290.2  493.77  5332.3  493.80  5362.4  496.97
  5383.4  494.53  5419.5  494.59  5540.8  499.19  5626.1  505.45  5719.8  505.61
  5819.7  508.68  5905.0  507.62  5934.1  504.03  5954.9  508.55  6004.9  502.81
  6061.0  503.08  6081.6  503.43  6198.4  504.74  6433.6  517.21  6603.2  521.70
#Mann=7,-1,0
  3974.0    0.05       0  4998.6   0.035       0  5004.6    0.05       0
  5019.7    0.16       0  5087.5    0.05       0  6061.0    0.16       0
  6081.6    0.05       0
Bank Sta=4998.6,5004.6
Exp/Cntr=0.3,0.1

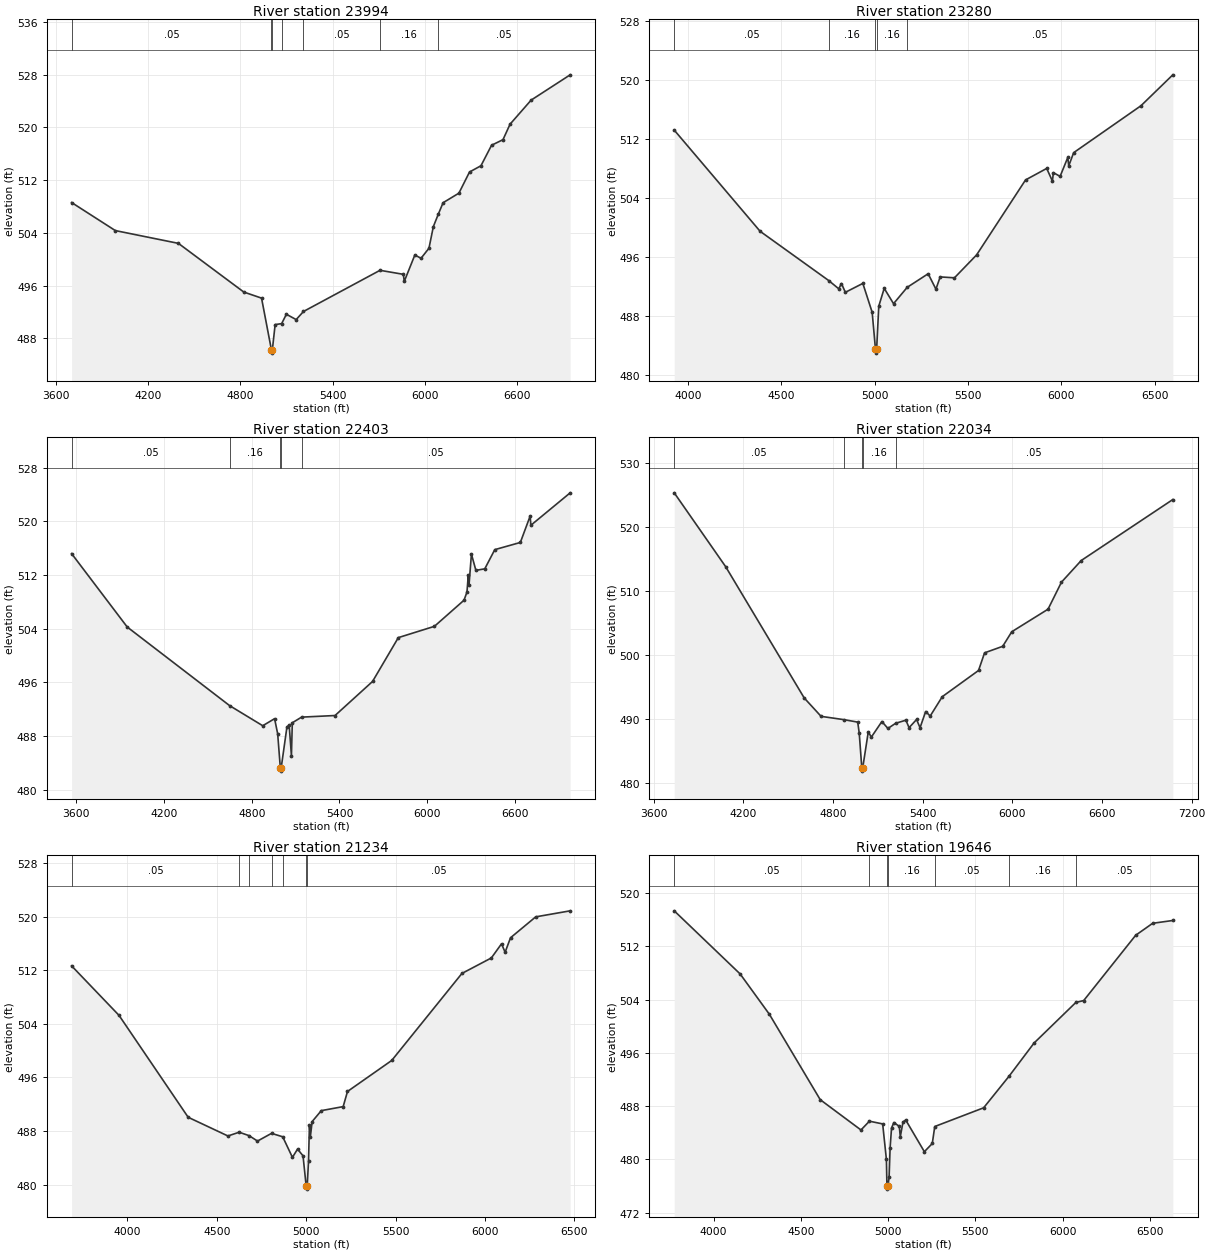
Type RM Length L Ch R = 1,23994,714,714,714
BEGIN DESCRIPTION:
PIN OAK CREEK 30.0
END DESCRIPTION:
XS GIS Cut Line= 4
      3433500.96     10604118.96      3433140.72     10603107.69
      3432871.62     10602678.00      3431361.23     10601983.56
#Sta/Elev= 30
  3702.3  508.61  3986.7  504.35  4397.0  502.41  4822.3  495.02  4937.8  494.10
  5002.0  486.25  5004.7  485.75  5008.0  486.25  5026.2  490.08  5068.6  490.23
  5099.3  491.65  5162.9  490.84  5210.5  492.07  5708.4  498.32  5860.3  497.71
  5865.9  496.63  5934.8  500.64  5975.2  500.15  6026.7  501.67  6055.2  504.95
  6087.8  506.86  6118.6  508.58  6221.5  510.03  6290.4  513.24  6364.9  514.19
  6433.8  517.30  6508.2  518.15  6554.2  520.50  6691.1  524.15  6945.2  527.99
#Mann=7,-1,0
  3702.3    0.05       0  5002.0   0.035       0  5008.0    0.05       0
  5068.6    0.16       0  5210.5    0.05       0  5708.4    0.16       0
  6087.8    0.05       0
Bank Sta=5002,5008
Exp/Cntr=0.3,0.1

Type RM Length L Ch R = 1,23280,877,877,877
BEGIN DESCRIPTION:
PIN OAK CREEK 29.0
END DESCRIPTION:
XS GIS Cut Line= 4
      3434125.98     10603051.28      3433540.02     10602617.23
      3432928.04     10602157.16      3431786.86     10601870.78
#Sta/Elev= 30
  3925.9  513.23  4386.1  499.50  4753.5  492.82  4807.4  491.70  4821.9  492.41
  4842.8  491.22  4936.5  492.43  4986.5  488.51  5004.3  483.47  5007.1  482.97
  5010.3  483.47  5021.9  489.34  5051.0  491.76  5101.0  489.68  5174.3  491.90
  5286.4  493.74  5328.1  491.65  5350.9  493.31  5427.4  493.19  5545.8  496.29
  5808.3  506.47  5921.7  508.03  5952.2  506.31  5957.4  507.46  5993.4  506.95
  6034.6  509.52  6039.7  508.38  6066.1  510.17  6426.9  516.54  6597.3  520.73
#Mann=5,-1,0
  3925.9    0.05       0  4753.5    0.16       0  5004.3    0.07       0
  5010.3    0.16       0  5174.3    0.05       0
Bank Sta=5004.3,5010.3
Exp/Cntr=0.3,0.1

Type RM Length L Ch R = 1,22403,369,369,369
BEGIN DESCRIPTION:
PIN OAK CREEK 28.0
END DESCRIPTION:
XS GIS Cut Line= 4
      3434199.74     10603072.95      3433583.43     10601961.85
      3433205.82     10601723.14      3431535.96     10601441.21
#Sta/Elev= 30
  3567.5  515.19  3948.0  504.26  4648.1  492.56  4875.1  489.56  4956.1  490.61
  4977.3  488.36  4995.4  483.30  4998.2  482.80  5001.4  483.30  5040.8  489.40
  5056.1  489.60  5071.4  485.10  5077.3  490.00  5140.8  490.84  5369.7  491.08
  5626.2  496.15  5802.6  502.68  6049.5  504.36  6252.0  508.25  6272.3  509.47
  6281.2  511.99  6286.2  510.49  6302.7  515.12  6333.2  512.70  6394.0  512.92
  6462.5  515.78  6637.4  516.85  6704.4  520.78  6709.4  519.41  6978.3  524.24
#Mann=5,-1,0
  3567.5    0.05       0  4648.1    0.16       0  4995.4    0.07       0
  5001.4    0.16       0  5140.8    0.05       0
Bank Sta=4995.4,5001.4
Exp/Cntr=0.3,0.1

Type RM Length L Ch R = 1,22034,800,800,800
BEGIN DESCRIPTION:
PIN OAK CREEK 27.0
END DESCRIPTION:
XS GIS Cut Line= 5
      3434820.38     10601757.86      3433852.52     10601575.57
      3433201.48     10601484.42      3431539.16     10601241.37
      3431526.60     10601237.18
#Sta/Elev= 30
  3738.0  525.33  4082.2  513.77  4607.6  493.23  4720.5  490.35  4872.0  489.84
  4965.6  489.45  4975.7  487.72  4992.9  482.28  4995.7  481.78  4998.9  482.28
  5036.3  487.94  5056.5  487.10  5127.2  489.54  5167.6  488.46  5219.4  489.27
  5287.9  489.75  5309.0  488.58  5359.3  489.86  5382.5  488.57  5420.1  491.11
  5450.4  490.40  5531.2  493.43  5773.8  497.53  5814.2  500.29  5935.5  501.31
  5996.1  503.59  6238.7  507.12  6328.6  511.35  6461.0  514.74  7073.5  524.28
#Mann=5,-1,0
  3738.0    0.05       0  4872.0    0.16       0  4992.9    0.07       0
  4998.9    0.16       0  5219.4    0.05       0
Bank Sta=4992.9,4998.9
Exp/Cntr=0.3,0.1

Type RM Length L Ch R = 1,21234,1588,1588,1588
BEGIN DESCRIPTION:
PIN OAK CREEK 25.0
END DESCRIPTION:
XS GIS Cut Line= 4
      3434720.55     10601202.30      3433826.48     10600937.55
      3433262.25     10600820.36      3431990.51     10600677.13
#Sta/Elev= 30
  3687.5  512.65  3952.9  505.26  4339.5  490.06  4561.9  487.27  4624.6  487.83
  4680.1  487.32  4727.2  486.51  4805.7  487.66  4868.2  487.15  4922.6  484.08
  4951.2  485.31  4981.9  484.31  4999.3  479.84  5002.1  479.34  5005.3  479.84
  5012.5  483.49  5017.7  488.89  5022.8  487.13  5032.9  489.42  5084.0  491.05
  5206.4  491.65  5230.5  493.91  5478.1  498.54  5870.6  511.52  6035.1  513.83
  6092.0  515.94  6112.1  514.68  6142.3  516.84  6283.2  519.96  6476.0  520.86
#Mann=7,-1,0
  3687.5    0.05       0  4624.6    0.16       0  4680.1    0.05       0
  4805.7    0.16       0  4868.2    0.05       0  4999.3    0.04       0
  5005.3    0.05       0
Bank Sta=4999.3,5005.3
Exp/Cntr=0.3,0.1

Type RM Length L Ch R = 1,19646,971,971,971
BEGIN DESCRIPTION:
PIN OAK CREEK 22.0
END DESCRIPTION:
XS GIS Cut Line= 4
      3435141.55     10600612.01      3434429.78     10600290.85
      3433687.59     10599843.80      3432533.09     10599483.56
#Sta/Elev= 30
  3774.3  517.33  4152.1  507.85  4319.5  501.80  4610.8  488.98  4844.3  484.43
  4892.6  485.75  4968.6  485.34  4990.0  480.01  4993.1  476.05  4995.8  475.55
  4999.1  476.05  5005.5  477.37  5011.3  481.79  5019.4  484.72  5032.7  485.55
  5063.8  484.97  5069.6  483.41  5085.1  485.62  5100.6  485.93  5207.5  481.17
  5252.9  482.40  5267.1  484.95  5547.1  487.76  5692.1  492.48  5835.9  497.48
  6075.7  503.58  6120.5  503.86  6418.2  513.66  6515.7  515.46  6631.0  515.88
#Mann=7,-1,0
  3774.3    0.05       0  4892.6    0.16       0  4993.1    0.07       0
  4999.1    0.16       0  5267.1    0.05       0  5692.1    0.16       0
  6075.7    0.05       0
Bank Sta=4993.1,4999.1
Exp/Cntr=0.3,0.1

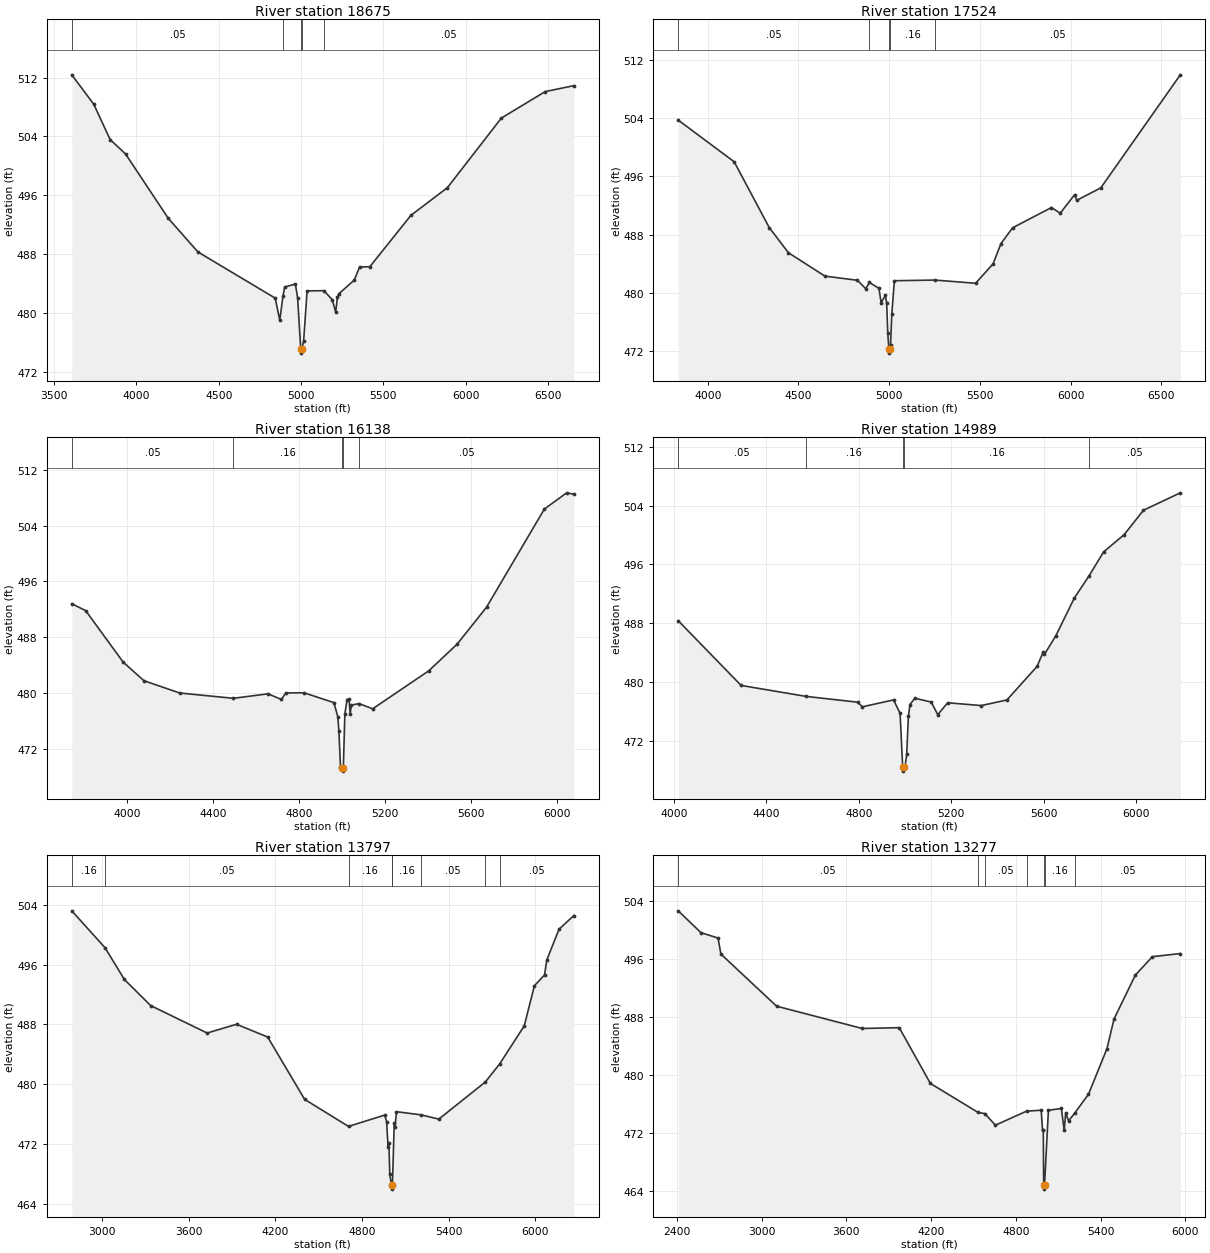
Type RM Length L Ch R = 1,18675,1151,1151,1151
BEGIN DESCRIPTION:
PIN OAK CREEK 20.0
END DESCRIPTION:
XS GIS Cut Line= 4
      3435423.67     10600044.30      3434513.98     10599433.21
      3434111.20     10599176.26      3432687.55     10598780.42
#Sta/Elev= 30
  3606.7  512.37  3740.5  508.37  3839.6  503.58  3933.9  501.61  4193.6  492.86
  4373.6  488.30  4843.1  482.03  4870.9  479.03  4889.9  482.26  4900.6  483.54
  4965.8  483.95  4979.3  482.07  4998.3  475.06  5001.1  474.56  5004.3  475.06
  5015.7  476.20  5036.9  483.02  5139.4  483.04  5189.8  481.81  5210.5  480.15
  5221.2  482.15  5231.3  482.65  5323.9  484.49  5355.9  486.26  5418.1  486.30
  5668.3  493.29  5889.3  497.03  6217.3  506.49  6483.7  510.09  6658.0  510.90
#Mann=5,-1,0
  3606.7    0.05       0  4889.9    0.16       0  4998.3    0.07       0
  5004.3    0.16       0  5139.4    0.05       0
Bank Sta=4998.3,5004.3
Exp/Cntr=0.3,0.1

Type RM Length L Ch R = 1,17524,1386,1386,1386
BEGIN DESCRIPTION:
PIN OAK CREEK 18.0
END DESCRIPTION:
XS GIS Cut Line= 4
      3435583.43     10599183.21      3434923.70     10598676.26
      3434527.87     10598426.26      3433159.83     10597898.49
#Sta/Elev= 30
  3837.7  503.72  4146.1  498.00  4339.2  488.98  4445.2  485.52  4646.4  482.32
  4825.4  481.75  4870.9  480.59  4891.2  481.45  4943.6  480.65  4955.6  478.68
  4979.1  479.68  4986.2  478.65  4992.1  474.56  4998.5  472.26  5001.2  471.76
  5004.5  472.26  5007.4  472.82  5014.6  477.15  5028.6  481.69  5251.4  481.78
  5476.3  481.34  5572.8  484.02  5615.7  486.77  5680.0  488.95  5894.3  491.73
  5942.6  490.95  6021.7  493.49  6033.7  492.72  6166.2  494.43  6604.2  509.93
#Mann=5,-1,0
  3837.7    0.05       0  4891.2    0.16       0  4998.5    0.07       0
  5004.5    0.16       0  5251.4    0.05       0
Bank Sta=4998.5,5004.5
Exp/Cntr=0.3,0.1

Type RM Length L Ch R = 1,16138,1149,1149,1149
BEGIN DESCRIPTION:
PIN OAK CREEK 16.0
END DESCRIPTION:
XS GIS Cut Line= 4
      3435673.75     10597759.61      3434847.31     10597495.71
      3434222.31     10597377.65      3433515.55     10596941.12
#Sta/Elev= 30
  3742.2  492.81  3806.9  491.82  3981.1  484.46  4077.6  481.80  4243.8  480.04
  4493.5  479.28  4654.6  479.92  4717.2  479.11  4737.2  480.05  4821.9  480.07
  4961.1  478.66  4979.1  476.65  4984.2  474.62  4991.6  469.44  4998.8  469.36
  5001.5  468.86  5004.8  469.36  5011.9  477.06  5022.1  479.09  5031.5  479.17
  5036.6  477.09  5042.5  478.31  5077.8  478.52  5141.3  477.78  5402.3  483.22
  5533.6  487.02  5670.7  492.32  5939.5  506.36  6043.2  508.68  6076.5  508.48
#Mann=5,-1,0
  3742.2    0.05       0  4493.5    0.16       0  4998.8    0.07       0
  5004.8    0.16       0  5077.8    0.05       0
Bank Sta=4998.8,5004.8
Exp/Cntr=0.3,0.1

Type RM Length L Ch R = 1,14989,1192,1192,1192
BEGIN DESCRIPTION:
PIN OAK CREEK 14.0
END DESCRIPTION:
XS GIS Cut Line= 4
      3435541.75     10597294.31      3434965.37     10596815.15
      3434625.09     10596509.60      3433666.98     10596398.51
#Sta/Elev= 30
  4019.2  488.34  4291.2  479.53  4571.4  478.04  4794.9  477.25  4815.8  476.62
  4950.3  477.56  4978.7  475.73  4990.0  468.36  4992.7  467.86  4996.0  468.36
  5000.4  468.48  5007.2  470.14  5014.6  475.31  5021.4  476.93  5042.3  477.78
  5113.3  477.27  5141.7  475.55  5184.3  477.17  5329.7  476.79  5440.5  477.55
  5571.4  482.13  5597.8  484.10  5602.8  483.76  5651.9  486.27  5732.4  491.44
  5796.7  494.49  5858.9  497.72  5947.6  500.06  6031.3  503.39  6190.6  505.76
#Mann=5,-1,0
  4019.2    0.05       0  4571.4    0.16       0  4990.0    0.07       0
  4996.0    0.16       0  5796.7    0.05       0
Bank Sta=4990,4996
Exp/Cntr=0.3,0.1

Type RM Length L Ch R = 1,13797,520,520,520
BEGIN DESCRIPTION:
PIN OAK CREEK 13.0
END DESCRIPTION:
XS GIS Cut Line= 5
      3437034.78     10596238.75      3435486.20     10595877.65
      3435062.59     10595815.15      3434722.31     10596016.54
      3433659.77     10596113.77
#Sta/Elev= 30
  2787.7  503.20  3018.4  498.26  3152.1  494.02  3334.7  490.52  3725.9  486.85
  3930.2  488.02  4145.9  486.31  4402.2  477.97  4706.2  474.35  4957.6  475.87
  4970.5  474.98  4980.4  471.64  4986.2  472.19  4992.5  467.95  5004.6  466.46
  5007.4  465.96  5010.6  466.46  5023.2  474.75  5029.0  474.31  5038.9  476.32
  5209.4  475.90  5332.2  475.33  5654.0  480.28  5753.7  482.70  5924.6  487.81
  5994.9  493.17  6065.2  494.62  6080.4  496.59  6165.6  500.74  6268.4  502.57
#Mann=8,-1,0
  2787.7    0.16       0  3018.4    0.05       0  4706.2    0.16       0
  5004.6    0.07       0  5010.6    0.16       0  5209.4    0.05       0
  5654.0    0.16       0  5753.7    0.05       0
Bank Sta=5004.6,5010.6
Exp/Cntr=0.3,0.1

Type RM Length L Ch R = 1,13277,989,989,989
BEGIN DESCRIPTION:
PIN OAK CREEK 12.0
END DESCRIPTION:
XS GIS Cut Line= 5
      3437361.20     10595822.10      3435750.09     10595592.93
      3435020.93     10595572.10      3434604.26     10595655.43
      3433835.24     10595579.22
#Sta/Elev= 30
  2410.1  502.61  2570.8  499.61  2692.0  498.86  2712.2  496.66  3106.1  489.49
  3712.2  486.42  3974.8  486.53  4195.5  478.85  4532.7  474.87  4581.0  474.70
  4655.7  473.11  4876.0  475.04  4979.8  475.17  4989.5  472.38  4994.6  472.42
  4997.2  464.81  5000.0  464.31  5003.2  464.81  5030.8  475.16  5122.6  475.41
  5142.5  472.40  5153.2  474.81  5173.6  473.70  5219.3  474.83  5314.6  477.37
  5445.2  483.63  5495.4  487.73  5646.2  493.76  5766.8  496.30  5964.6  496.73
#Mann=7,-1,0
  2410.1    0.05       0  4532.7    0.16       0  4581.0    0.05       0
  4876.0    0.16       0  4997.2    0.07       0  5003.2    0.16       0
  5219.3    0.05       0
Bank Sta=4997.2,5003.2
Exp/Cntr=0.3,0.1

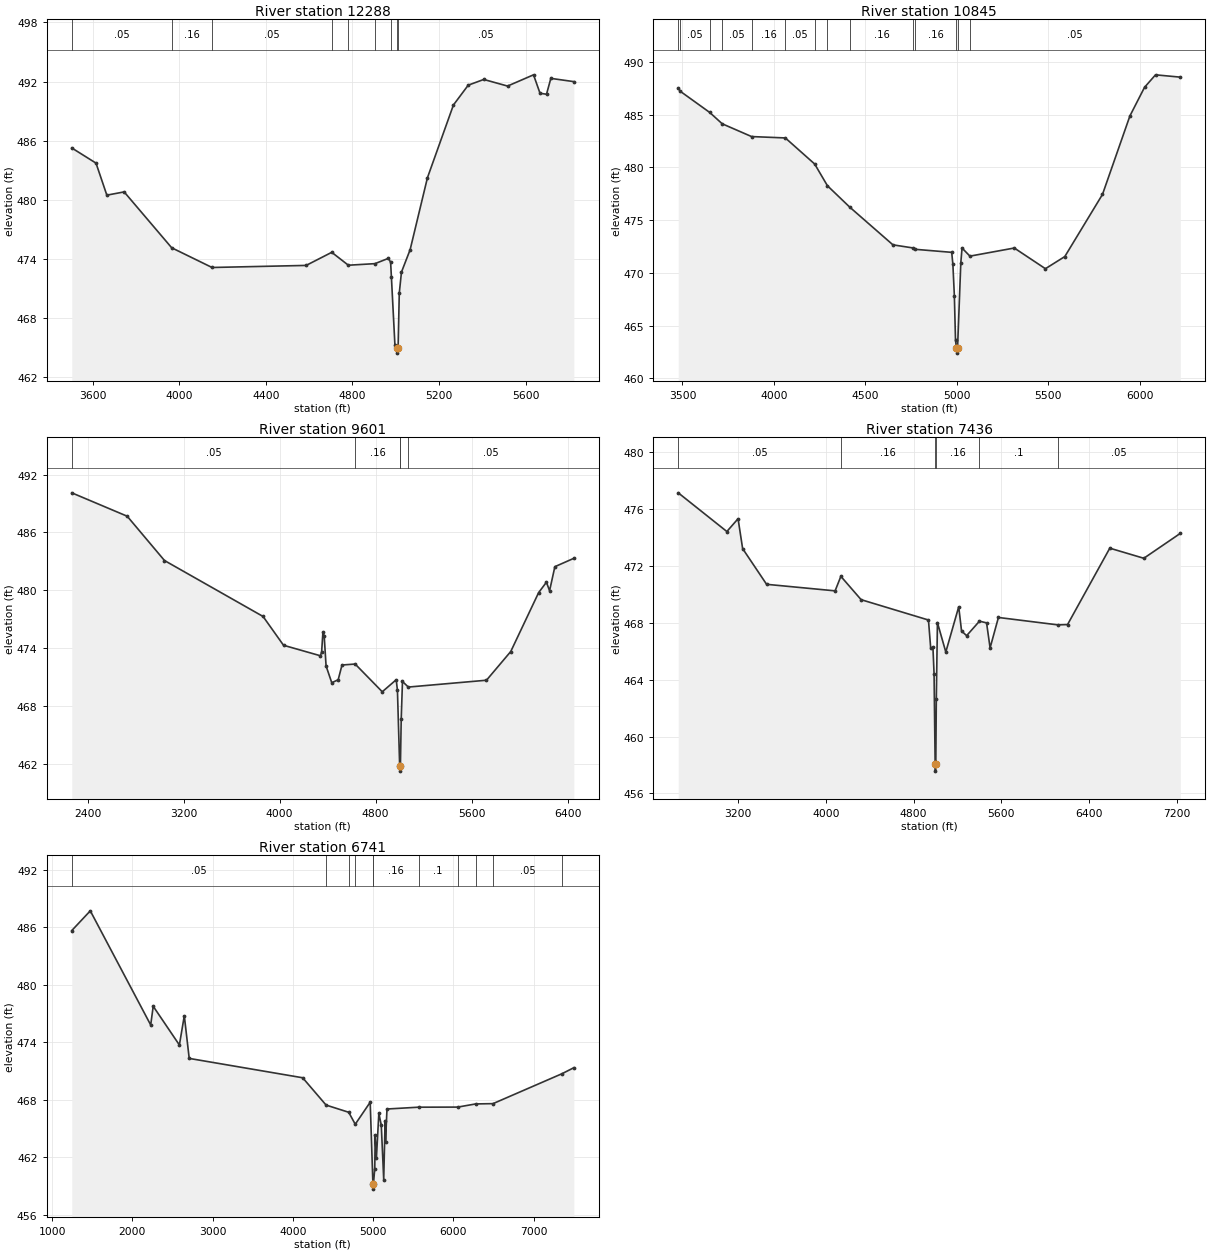
Type RM Length L Ch R = 1,12288,1443,1443,1443
BEGIN DESCRIPTION:
PIN OAK CREEK 10.0
END DESCRIPTION:
XS GIS Cut Line= 4
      3436014.00     10595134.60      3435083.43     10595092.93
      3434180.65     10595051.26      3433695.79     10595051.26
#Sta/Elev= 30
  3502.8  485.26  3614.8  483.72  3664.9  480.47  3744.9  480.80  3964.5  475.13
  4151.0  473.13  4585.8  473.34  4704.2  474.67  4780.9  473.36  4903.9  473.52
  4966.2  474.06  4976.2  473.66  4979.8  472.18  4996.2  465.22  5004.8  464.94
  5007.6  464.44  5010.8  464.94  5016.2  470.52  5026.3  472.66  5066.3  474.93
  5146.4  482.24  5266.5  489.62  5334.8  491.63  5406.6  492.21  5516.6  491.54
  5636.6  492.68  5666.6  490.81  5696.6  490.71  5716.6  492.32  5822.9  491.99
#Mann=9,-1,0
  3502.8    0.05       0  3964.5    0.16       0  4151.0    0.05       0
  4704.2    0.16       0  4780.9    0.12       0  4903.9    0.16       0
  4979.8    0.05       0  5004.8   0.035       0  5010.8    0.05       0
Bank Sta=5004.8,5010.8
Exp/Cntr=0.3,0.1

Type RM Length L Ch R = 1,10845,1244,1244,1244
BEGIN DESCRIPTION:
PIN OAK CREEK 9.0
END DESCRIPTION:
XS GIS Cut Line= 4
      3436590.40     10595190.17      3435673.70     10594592.93
      3434868.15     10593967.93      3434236.67     10593981.81
#Sta/Elev= 30
  3476.9  487.51  3487.3  487.21  3648.7  485.20  3717.4  484.12  3878.0  482.91
  4062.5  482.78  4222.9  480.31  4292.7  478.25  4414.3  476.23  4650.9  472.65
  4763.0  472.35  4770.3  472.23  4972.2  471.94  4978.6  470.81  4986.7  467.84
  4993.0  463.62  4998.2  462.89  5001.0  462.39  5004.2  462.89  5022.0  470.94
  5028.7  472.35  5071.8  471.58  5314.4  472.35  5484.6  470.39  5590.6  471.54
  5796.7  477.43  5946.7  484.87  6026.7  487.58  6086.7  488.76  6222.2  488.54
#Mann=14,-1,0
  3476.9    0.16       0  3487.3    0.05       0  3648.7    0.16       0
  3717.4    0.05       0  3878.0    0.16       0  4062.5    0.05       0
  4222.9    0.16       0  4292.7    0.05       0  4414.3    0.16       0
  4763.0    0.05       0  4770.3    0.16       0  4998.2    0.07       0
  5004.2    0.16       0  5071.8    0.05       0
Bank Sta=4998.2,5004.2
Exp/Cntr=0.3,0.1

Type RM Length L Ch R = 1,9601,2165,2165,2165
BEGIN DESCRIPTION:
PIN OAK CREEK 8.0
END DESCRIPTION:
XS GIS Cut Line= 4
      3438243.10     10593815.15      3436312.59     10593704.04
      3435229.26     10593349.87      3434131.99     10593509.60
#Sta/Elev= 30
  2268.9  490.11  2730.7  487.68  3041.2  483.08  3862.5  477.27  4032.8  474.28
  4339.9  473.19  4350.1  473.56  4360.9  475.62  4371.5  475.26  4387.3  472.13
  4434.6  470.39  4488.2  470.70  4520.0  472.23  4629.5  472.33  4855.4  469.45
  4971.5  470.70  4981.7  469.61  5000.4  461.71  5003.1  461.21  5006.4  461.71
  5013.2  466.61  5023.7  470.52  5072.4  469.94  5723.5  470.65  5925.6  473.63
  6158.0  479.75  6223.0  480.83  6249.0  479.94  6293.1  482.44  6451.2  483.31
#Mann=5,-1,0
  2268.9    0.05       0  4629.5    0.16       0  5000.4    0.07       0
  5006.4    0.16       0  5072.4    0.05       0
Bank Sta=5000.4,5006.4
Exp/Cntr=0.3,0.1

Type RM Length L Ch R = 1,7436,695,695,695
BEGIN DESCRIPTION:
PIN OAK CREEK 6.0
END DESCRIPTION:
XS GIS Cut Line= 4
      3437993.12     10592697.09      3436229.26     10592266.54
      3435444.54     10592099.87      3433611.20     10592801.26
#Sta/Elev= 30
  2653.4  477.13  3097.1  474.41  3199.2  475.31  3240.9  473.21  3459.5  470.70
  4084.6  470.24  4137.2  471.26  4322.0  469.62  4936.4  468.19  4956.8  466.21
  4977.3  466.26  4987.5  464.42  4997.4  458.07  5000.2  457.57  5003.4  458.07
  5008.0  462.62  5018.2  468.01  5094.6  465.94  5212.4  469.12  5238.3  467.42
  5284.6  467.09  5401.7  468.11  5466.6  467.99  5498.7  466.23  5574.6  468.37
  6115.9  467.85  6205.4  467.87  6590.8  473.24  6901.3  472.53  7234.2  474.28
#Mann=6,-1,0
  2653.4    0.05       0  4137.2    0.16       0  4997.4    0.07       0
  5003.4    0.16       0  5401.7     0.1       0  6115.9    0.05       0
Bank Sta=4997.4,5003.4
Exp/Cntr=0.3,0.1

Type RM Length L Ch R = 1,6741,0,0,0
BEGIN DESCRIPTION:
PIN OAK CREEK 1.0
END DESCRIPTION:
XS GIS Cut Line= 4
      3439436.37     10592714.53      3436394.67     10591610.35
      3435228.00     10591797.85      3433540.92     10592526.83
#Sta/Elev= 30
  1244.4  485.63  1475.2  487.69  2227.7  475.78  2259.1  477.73  2585.2  473.69
  2646.4  476.74  2707.6  472.29  4121.3  470.27  4413.1  467.42  4694.8  466.67
  4776.3  465.42  4962.6  467.72  4996.5  459.15  4999.2  458.65  5002.5  459.15
  5019.4  460.80  5024.5  464.27  5040.0  461.89  5070.4  466.58  5100.7  465.31
  5131.1  459.64  5148.3  465.80  5153.3  463.52  5171.6  467.01  5565.4  467.20
  6053.4  467.21  6276.6  467.54  6492.5  467.57  7351.3  470.69  7499.8  471.32
#Mann=11,-1,0
  1244.4    0.05       0  4413.1    0.16       0  4694.8    0.05       0
  4776.3    0.16       0  4996.5    0.07       0  5002.5    0.16       0
  5565.4     0.1       0  6053.4    0.05       0  6276.6     0.1       0
  6492.5    0.05       0  7351.3    0.16       0
Bank Sta=4996.5,5002.5
Exp/Cntr=0.3,0.1

Chan Stop Cuts=-1