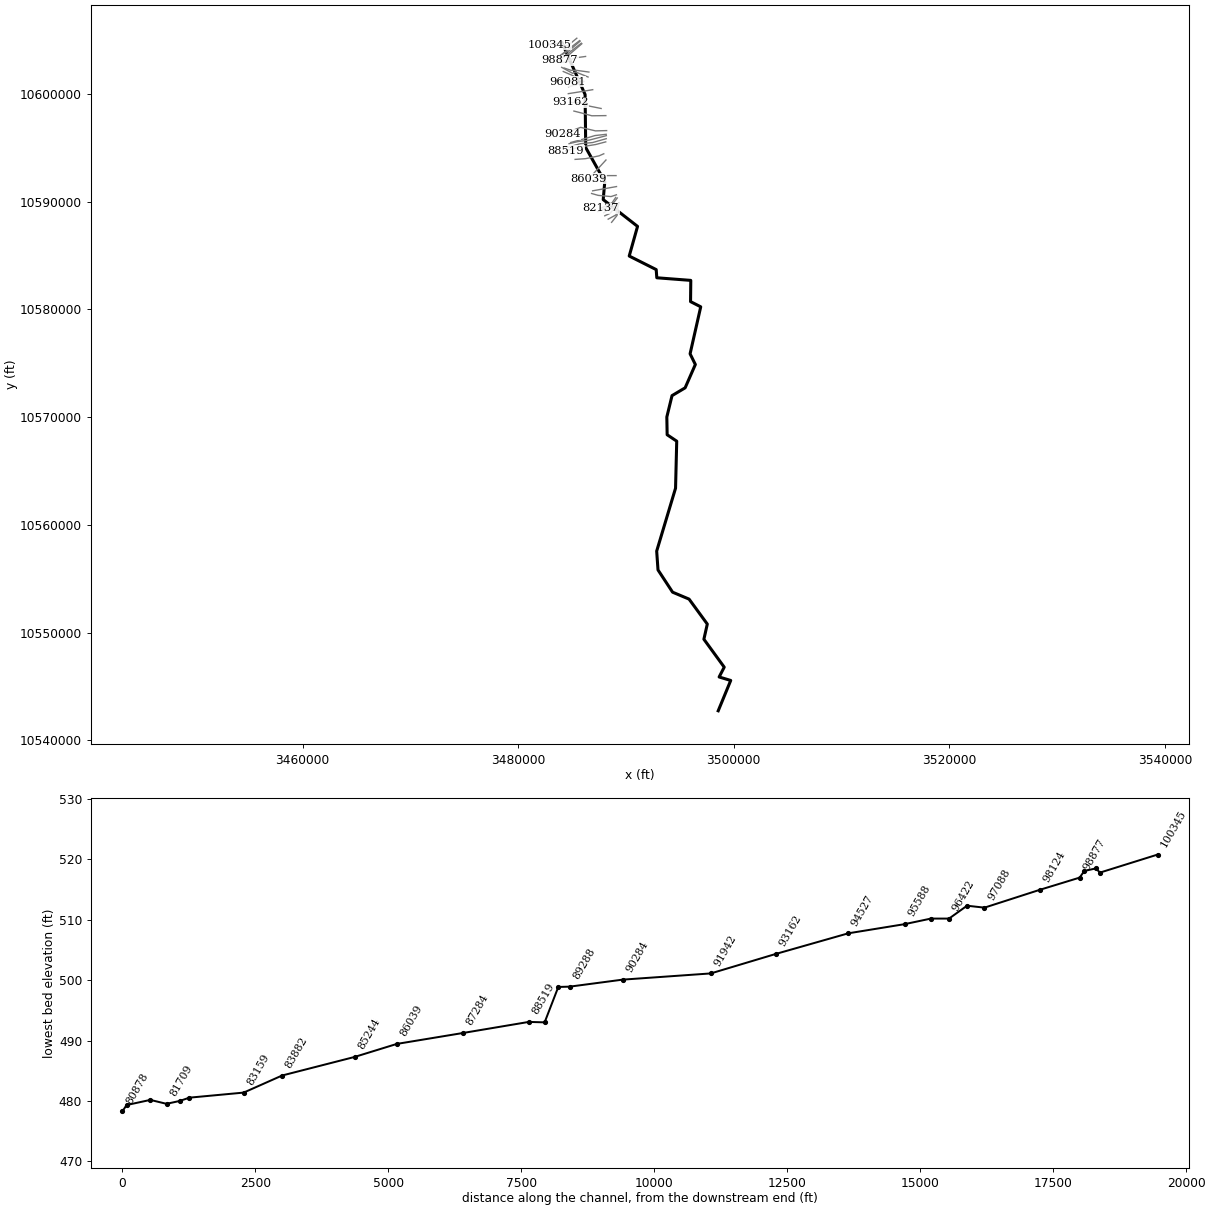
--- PLUMMERS CREEK.prj (project) ---

Proj Title=PLUMMERS CREEK Base Level Engineering
Current Plan=p01
Default Exp/Contr=0.3,0.1
English Units
Geom File=g01
Flow File=f01
Plan File=p01
Y Axis Title=Elevation
X Axis Title(PF)=Main Channel Distance
X Axis Title(XS)=Station
BEGIN DESCRIPTION:
PLUMMERS CREEK
END DESCRIPTION:
DSS Export Rating Curves= 0
DSS Export Rating Curve Sorted= 0
DSS Export Volume Flow Curves= 0
DXF OffsetX= 0
DXF OffsetY= 0
DXF ScaleX= 1
DXF ScaleY= 10

--- PLUMMERS CREEK.p01 (plan) ---

Plan Title=Multiple Run
Short Identifier=Multiple
Geom File=g01
Flow File=f01
Subcritical Flow
K Sum by GR= 0
Std Step Tol= 0.01
Critical Tol= 0.01
Num of Std Step Trials= 20
Max Error Tol= 0.3
Flow Tol Ratio= 0.001
Split Flow NTrial= 30
Split Flow Tol= 0.02
Split Flow Ratio= 0.02
Log Output Level= 0
Friction Slope Method= 1
Unsteady Friction Slope Method= 2
Unsteady Bridges Friction Slope Method= 1
Parabolic Critical Depth
Global Vel Dist=  1 , 1 , 1
Global Log Level= 0
CheckData=True
Encroach Param= -1, 0, 0, 0
BEGIN DESCRIPTION:
Multiple Run
END DESCRIPTION:

--- PLUMMERS CREEK.f01 (steady flow) ---

Flow Title=Multiple
Program Version=4.10
Number of Profiles= 7
Profile Names=10-year,25-year,50-year,1pct_min,100-year,1pct_plu,500-year
River Rch & RM=PLUMMERS CREEK,Reach-1         ,100345
     485     605     691     574     776    1049     977
River Rch & RM=PLUMMERS CREEK,Reach-1         ,91942
     653     825     953     798    1079    1459    1382
River Rch & RM=PLUMMERS CREEK,Reach-1         ,88818
     784    1000    1160     976    1321    1786    1708
River Rch & RM=PLUMMERS CREEK,Reach-1         ,82137
     917    1176    1371    1159    1567    2119    2043
River Rch & RM=PLUMMERS CREEK,Reach-1         ,79423
    1151    1490    1747    1484    2007    2714    2644
River Rch & RM=PLUMMERS CREEK,Reach-1         ,71532
    1247    1619    1902    1618    2188    2960    2893
River Rch & RM=PLUMMERS CREEK,Reach-1         ,64373
    1536    2010    2374    2030    2745    3713    3665
River Rch & RM=PLUMMERS CREEK,Reach-1         ,59903
    1798    2363    2799    2399    3244    4387    4350
River Rch & RM=PLUMMERS CREEK,Reach-1         ,52133
    1914    2520    2989    2564    3468    4690    4660
River Rch & RM=PLUMMERS CREEK,Reach-1         ,42357
    2273    3012    3586    3089    4177    5649    5656
River Rch & RM=PLUMMERS CREEK,Reach-1         ,39215
    2989    3988    4773    4128    5582    7550    7622
River Rch & RM=PLUMMERS CREEK,Reach-1         ,33955
    3073    4096    4899    4234    5726    7743    7805
River Rch & RM=PLUMMERS CREEK,Reach-1         ,26365
    3149    4187    4999    4312    5831    7886    7918
River Rch & RM=PLUMMERS CREEK,Reach-1         ,15003
    3511    4677    5592    4829    6531    8832    8886
Boundary for River Rch & Prof#=PLUMMERS CREEK,Reach-1         , 1
Up Type= 0
Dn Type= 3
Dn Slope=0.002
Boundary for River Rch & Prof#=PLUMMERS CREEK,Reach-1         , 2
Up Type= 0
Dn Type= 3
Dn Slope=0.002
Boundary for River Rch & Prof#=PLUMMERS CREEK,Reach-1         , 3
Up Type= 0
Dn Type= 3
Dn Slope=0.002
Boundary for River Rch & Prof#=PLUMMERS CREEK,Reach-1         , 4
Up Type= 0
Dn Type= 3
Dn Slope=0.002
Boundary for River Rch & Prof#=PLUMMERS CREEK,Reach-1         , 5
Up Type= 0
Dn Type= 3
Dn Slope=0.002
Boundary for River Rch & Prof#=PLUMMERS CREEK,Reach-1         , 6
Up Type= 0
Dn Type= 3
Dn Slope=0.002
Boundary for River Rch & Prof#=PLUMMERS CREEK,Reach-1         , 7
Up Type= 0
Dn Type= 3
Dn Slope=0.002
DSS Import GetInterval= 0
DSS Import GetPeak= 0
DSS Import FillOption= 0

--- PLUMMERS CREEK.g01 (geometry) ---

Geom Title=Existing Conditions
Program Version=4.10

River Reach=PLUMMERS CREEK  ,Reach-1
Reach XY= 30
      3484082.11     10604721.64      3486210.05     10599940.37
      3486269.21     10595018.41      3488037.99     10591854.65
      3487891.18     10590190.51      3491076.96     10587704.09
      3490304.23     10584952.77      3492808.55     10583694.19
      3492863.54     10582934.93      3496016.53     10582693.38
      3495995.51     10580722.97      3496939.23     10580241.22
      3495952.54     10575878.57      3496440.24     10574886.79
       3495492.2     10572722.03      3494276.34     10571998.19
      3493793.46     10570015.71      3493824.51     10568367.43
      3494712.11     10567771.64       3494603.1     10563409.14
      3492852.01     10557570.67      3492975.61     10555823.08
      3494327.93     10553759.11      3495858.52     10553115.25
      3497548.81     10550800.02      3497232.78     10549391.82
      3499119.39     10546800.19      3498647.54     10545889.11
      3499722.16     10545566.69      3498562.11     10542751.64

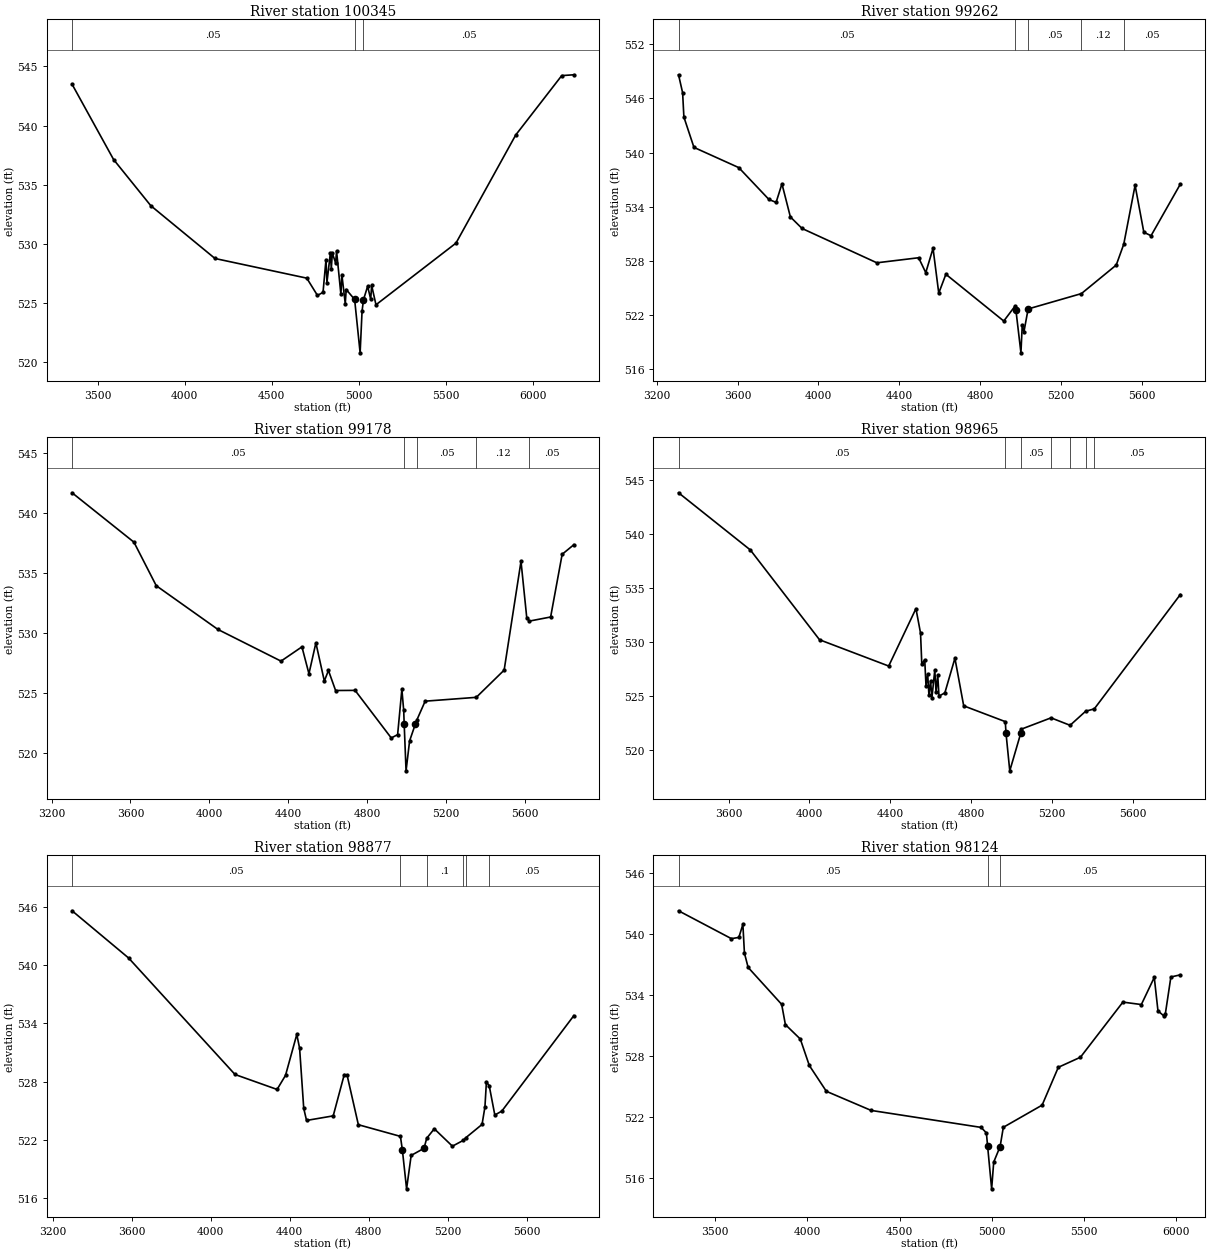
Type RM Length L Ch R = 1 ,100345  ,1083,1083,1083
BEGIN DESCRIPTION:
PLUMMERS CREEK 107.0
END DESCRIPTION:
XS GIS Cut Line= 5
      3485443.42     10605166.44        3484558.     10604437.28
      3483818.42     10604713.32      3482891.34     10604588.32
      3482891.34     10604577.93
#Sta/Elev= 30
  3353.3  543.49  3591.8  537.13  3805.6  533.23  4174.3  528.77  4701.4  527.11
  4762.8  525.65  4794.8  525.91  4811.9  528.68  4817.3  526.74  4836.9  529.22
  4842.3   527.9  4848.2  529.22  4867.2  528.39  4872.6   529.4  4897.5  525.73
  4902.9  527.41  4922.5  524.96  4927.9  526.15  4976.3  525.31  5007.9   520.8
    5019  524.31 5027.22  525.29    5051  526.42  5068.7  525.33  5074.1  526.49
    5099  524.86  5558.5  530.07  5901.5   539.2  6165.9  544.22  6235.6  544.29
#Mann= 3 , 0 , 0
  3353.3     .05       0  4976.3    .035       0 5027.22     .05       0
#XS Ineff= 2 , 0
       0  4976.3  525.31 5027.22       0  525.29
Permanent Ineff=
       T       T
Bank Sta=4976.3,5027.22
XS Rating Curve= 0 ,0
Exp/Cntr=0.3,0.1

Type RM Length L Ch R = 1 ,99262   ,84,84,84
BEGIN DESCRIPTION:
PLUMMERS CREEK 106.0
END DESCRIPTION:
XS GIS Cut Line= 4
      3485698.62     10604942.48      3484526.75     10604036.23
      3484094.46     10603708.11      3483719.43     10603442.46
#Sta/Elev= 30
  3308.1  548.61  3328.3  546.62  3334.6  543.93  3384.4  540.57  3606.3  538.33
  3755.7   534.8    3791  534.48    3820  536.53  3861.7  532.87  3919.6  531.59
  4289.7  527.79  4496.5  528.35  4531.8   526.7  4567.8  529.39  4596.1  524.43
  4631.4  526.52  4917.9  521.34  4974.1  523.01 4978.05  522.54  5002.9  517.82
  5009.4  520.93  5017.7  520.15  5038.5  522.68  5302.2  524.38  5474.6  527.54
  5511.8  529.85  5567.9  536.37  5611.2  531.17  5646.9  530.79  5791.8   536.5
#Mann= 5 ,-1 , 0
  3308.1     .05       0  4974.1    .035       0  5038.5     .05       0
  5302.2     .12       0  5511.8     .05       0
Bank Sta=4978.05,5038.5
XS Rating Curve= 0 ,0
Exp/Cntr=0.3,0.1

Type RM Length L Ch R = 1 ,99178   ,213,213,213
BEGIN DESCRIPTION:
PLUMMERS CREEK 105.2
END DESCRIPTION:
XS GIS Cut Line= 4
      3485745.49     10604890.39      3484636.13     10603937.28
      3484302.79     10603807.07      3483724.68     10603374.78
#Sta/Elev= 30
  3304.1  541.69  3617.6  537.57  3730.6  533.94  4043.3  530.29  4362.7  527.65
  4468.7  528.84  4504.2   526.6  4539.4  529.17  4582.2  525.99    4603  526.87
  4639.2   525.2    4738  525.21  4921.3  521.24  4953.5  521.52    4975   525.3
  4984.3  523.54 4986.69  522.44  4996.2   518.5  5014.2     521    5044  522.43
  5050.1  522.71    5093  524.31    5352  524.63  5493.2   526.9  5578.6  535.97
  5607.8  531.26  5621.3  530.99  5728.7  531.33  5787.1  536.56  5846.4  537.36
#Mann= 5 ,-1 , 0
  3304.1     .05       0  4984.3    .035       0  5050.1     .05       0
    5352     .12       0  5621.3     .05       0
#XS Ineff= 2 , 0
       0 4986.69  522.44    5044       0  522.43
Permanent Ineff=
       T       T
Bank Sta=4986.69,5044
XS Rating Curve= 0 ,0
Exp/Cntr=0.3,0.1

Type RM Length L Ch R = 1 ,98965   ,88,88,88
BEGIN DESCRIPTION:
PLUMMERS CREEK 105.1
END DESCRIPTION:
XS GIS Cut Line= 4
      3485860.07     10604702.89      3484688.21     10603796.65
      3484255.92     10603468.53      3483880.88     10603202.88
#Sta/Elev= 30
    3352  543.79  3707.6   538.5  4049.9   530.2  4392.2  527.77  4527.1  533.08
  4549.8  530.82  4556.1  527.94  4570.6  528.35  4576.9  525.94  4585.1  527.03
  4591.4  525.08  4599.6   526.4  4605.9   524.8  4620.4   527.4  4626.7  525.33
  4634.9  526.94  4641.2  524.99  4670.2  525.29    4720  528.49  4763.5  524.09
  4969.3  522.63 4972.97  521.54  4991.5  518.08 5046.07  521.57  5048.3  521.93
  5195.8  522.98  5290.1  522.29    5367  523.59  5409.9  523.81  5835.7  534.38
#Mann= 7 ,-1 , 0
    3352     .05       0  4969.3     .04       0  5048.3     .05       0
  5195.8      .1       0  5290.1     .05       0    5367      .1       0
  5409.9     .05       0
#XS Ineff= 2 , 0
       0                 5209.09       0  522.66
Permanent Ineff=
       F       T
Bank Sta=4972.97,5046.07
XS Rating Curve= 0 ,0
Exp/Cntr=0.3,0.1

Type RM Length L Ch R = 1 ,98877   ,753,753,753
BEGIN DESCRIPTION:
PLUMMERS CREEK 105.0
END DESCRIPTION:
XS GIS Cut Line= 4
      3485906.93     10604650.79      3484797.59     10603697.69
      3484464.25     10603567.48      3483887.56     10603136.26
#Sta/Elev= 30
  3298.1   545.6  3584.3  540.74  4123.1  528.75    4336  527.21  4378.8  528.66
  4435.8  532.87  4450.1  531.45    4471  525.26  4485.2  524.02  4620.2  524.49
  4676.2  528.74  4690.4  528.69  4747.5  523.58  4960.5  522.38  4970.5  520.96
  4991.7  516.98  5014.9  520.42  5079.9  521.15  5093.7  522.19    5132  523.16
  5223.7  521.37    5278  521.96  5290.3  522.22  5373.8  523.61  5388.4  525.41
  5395.9  528.01  5410.3  527.57  5438.4  524.58  5473.8  524.98  5838.6  534.81
#Mann= 6 ,-1 , 0
  3298.1     .05       0  4960.5    .035       0  5093.7      .1       0
    5278     .05       0  5290.3      .1       0  5410.3     .05       0
Bank Sta=4970.5,5079.9
XS Rating Curve= 0 ,0
Exp/Cntr=0.3,0.1

Type RM Length L Ch R = 1 ,98124   ,1036,1036,1036
BEGIN DESCRIPTION:
PLUMMERS CREEK 104.0
END DESCRIPTION:
XS GIS Cut Line= 4
      3486255.93     10603473.74      3485271.54     10603338.32
      3484422.59     10602947.69      3483630.93     10602926.86
#Sta/Elev= 30
  3301.1  542.29  3587.6  539.55    3628  539.67  3649.9  540.95  3658.3  538.13
  3678.4  536.72  3860.1  533.09  3880.3   531.1  3961.1  529.68    4010  527.08
  4102.4  524.54  4345.1  522.66  4941.4  520.99  4969.9  520.45  4976.6  519.13
  4998.4  514.95  5009.6  517.58  5044.3  519.11  5061.7     521    5272  523.18
  5359.8   526.9  5479.8  527.89  5709.9  533.31  5809.9  533.07    5880  535.74
    5900  532.45    5930  531.98    5940  532.16    5970  535.78  6021.2  535.99
#Mann= 3 , 0 , 0
  3301.1     .05       0  4976.6    .035       0  5044.3     .05       0
Bank Sta=4976.6,5044.3
XS Rating Curve= 0 ,0
Exp/Cntr=0.3,0.1

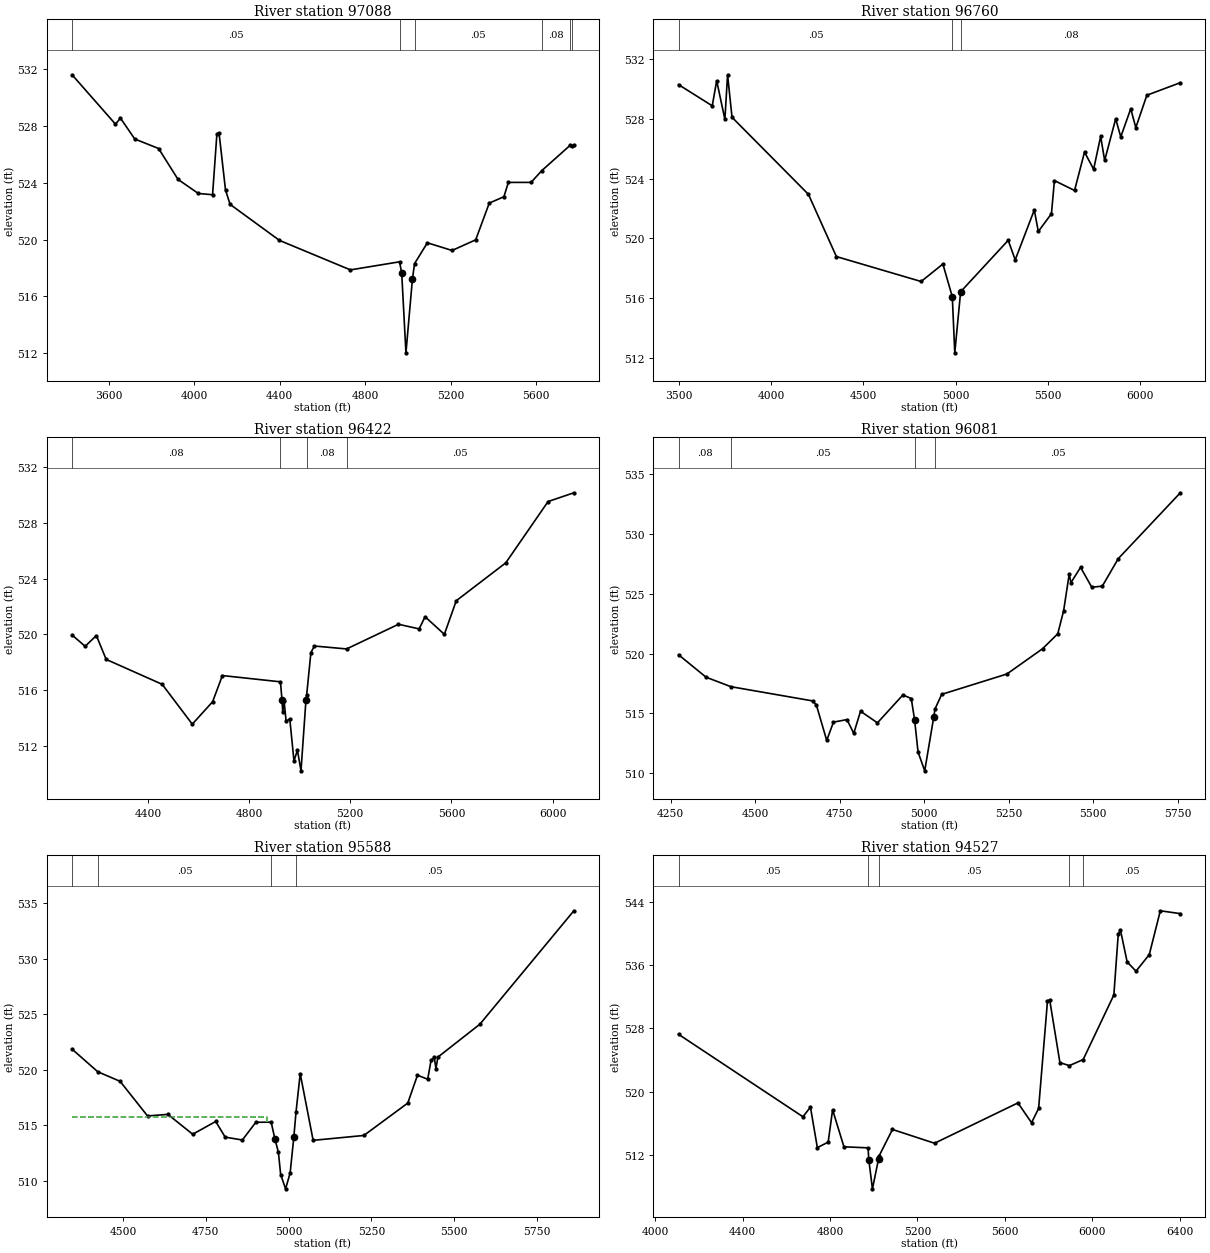
Type RM Length L Ch R = 1 ,97088   ,328,328,328
BEGIN DESCRIPTION:
PLUMMERS CREEK 103.0
END DESCRIPTION:
XS GIS Cut Line= 4
       3486563.2     10602025.82      3485396.54     10602187.28
      3484906.96     10602187.28      3484261.11     10602400.82
#Sta/Elev= 30
  3429.1  531.62  3632.1  528.14  3655.6  528.56  3722.4  527.09    3834  526.42
  3924.9  524.24  4019.7  523.25  4086.4  523.16  4106.6  527.43  4116.7  527.52
    4147  523.49  4168.4  522.48  4399.4  519.94  4731.3  517.86  4961.3  518.43
  4971.3  517.63  4991.1  512.01  5021.3  517.19  5031.3   518.3  5091.3  519.77
  5206.9  519.23  5317.5  519.98  5380.9  522.57  5449.6  523.02  5470.2  524.03
  5576.5  524.03  5626.6  524.86  5760.4  526.66  5767.1  526.58  5776.7  526.68
#Mann= 6 ,-1 , 0
  3429.1     .05       0  4961.3     .03       0  5031.3     .05       0
  5626.6     .08       0  5760.4     .05       0  5767.1     .08       0
Bank Sta=4971.3,5021.3
XS Rating Curve= 0 ,0
Exp/Cntr=0.3,0.1

Type RM Length L Ch R = 1 ,96760   ,338,338,338
BEGIN DESCRIPTION:
PLUMMERS CREEK 102.0
END DESCRIPTION:
XS GIS Cut Line= 4
      3486485.05      10601567.5      3485313.21     10602041.44
      3485068.42     10601900.82      3484037.21     10602463.29
#Sta/Elev= 30
  3497.6   530.3  3680.4  528.88  3704.5  530.56  3748.9  527.97  3763.5  530.96
  3787.7  528.11  4201.9  522.95  4353.6  518.78  4813.1  517.11    4931  518.28
  4982.1  516.09  4995.5  512.33  5027.3  516.42  5285.3  519.87  5323.2  518.56
  5426.7   521.9  5448.5  520.46  5519.7  521.65  5535.9  523.87    5645  523.21
  5699.1  525.78  5748.5  524.63  5786.5  526.83  5808.3  525.22  5868.1  528.01
  5895.6   526.8  5949.7  528.68  5977.3  527.42  6037.1  529.59  6218.6  530.43
#Mann= 3 , 0 , 0
  3497.6     .05       0  4982.1    .035       0  5027.3     .08       0
Bank Sta=4982.1,5027.3
XS Rating Curve= 0 ,0
Exp/Cntr=0.3,0.1

Type RM Length L Ch R = 1 ,96422   ,341,341,341
BEGIN DESCRIPTION:
PLUMMERS CREEK 101.0
END DESCRIPTION:
XS GIS Cut Line= 4
      3485974.67     10601223.74        3485308.     10601567.48
      3484938.21     10601754.98       3484184.5     10602077.26
#Sta/Elev= 30
  4099.8  519.95  4151.5  519.14  4195.9  519.91  4234.6   518.2  4456.2  516.41
  4575.2  513.55  4655.6  515.16  4694.3  517.04  4923.8  516.59 4930.07  515.28
  4932.9  514.43  4938.5  515.19  4946.2  513.75  4960.8  513.93  4977.4   510.9
    4991  511.69  5005.1   510.2 5024.82   515.3  5027.6  515.66  5044.3  518.69
  5058.3  519.16  5185.4  518.95  5390.6  520.72  5472.3  520.39  5495.8  521.26
  5572.1     520  5619.1  522.41  5814.9  525.13  5982.2  529.53  6084.2  530.16
#Mann= 4 ,-1 , 0
  4099.8     .08       0  4923.8     .07       0  5027.6     .08       0
  5185.4     .05       0
Bank Sta=4930.07,5024.82
XS Rating Curve= 0 ,0
Exp/Cntr=0.3,0.1

Type RM Length L Ch R = 1 ,96081   ,493,493,493
BEGIN DESCRIPTION:
PLUMMERS CREEK 100.0
END DESCRIPTION:
XS GIS Cut Line= 4
      3485990.31     10601161.23       3485620.5     10601338.32
      3485167.38     10601317.48      3484570.21     10601146.12
#Sta/Elev= 30
  4273.3   519.9  4354.9  518.02  4428.4  517.23  4670.5  516.04  4681.4  515.68
  4711.8  512.74  4731.8  514.27  4771.8  514.48  4791.8  513.33  4811.9  515.18
  4861.9  514.21  4937.3  516.54    4962  516.24    4972  514.43    4982  511.78
  5001.8   510.2  5028.5  514.69  5032.1  515.36  5052.1  516.59    5245  518.29
  5350.5   520.4  5395.5  521.65  5412.9  523.58  5429.3  526.62  5434.5  525.92
    5463   527.2  5496.1  525.54  5527.3  525.63  5574.6  527.93  5758.2  533.43
#Mann= 4 ,-1 , 0
  4273.3     .08       0  4428.4     .05       0    4972    .035       0
  5032.1     .05       0
#XS Ineff= 2 , 0
       0 4917.27  515.88               0
Permanent Ineff=
       T       F
Bank Sta=4972,5028.5
XS Rating Curve= 0 ,0
Exp/Cntr=0.3,0.1

Type RM Length L Ch R = 1 ,95588   ,1061,1061,1061
BEGIN DESCRIPTION:
PLUMMERS CREEK 98.0
END DESCRIPTION:
XS GIS Cut Line= 3
      3486099.64     10601156.01      3485406.96     10600843.53
       3484672.6     10600671.66
#Sta/Elev= 30
  4346.6  521.87  4424.2  519.83  4491.5  518.97  4574.3  515.85  4635.7  515.99
  4710.6   514.2    4780  515.35  4808.6  513.94  4860.4  513.68  4901.1  515.28
  4947.3  515.29  4958.4  513.81  4969.2  512.57    4976  510.57  4990.9  509.28
  5004.6  510.71 5015.75  513.95  5022.3  516.19    5035  519.66    5074  513.65
    5227  514.09  5359.6  517.01  5388.8  519.52  5419.6  519.16  5429.9  520.87
  5439.4  521.13  5444.6  520.11  5450.4  521.15  5577.2  524.12  5860.7  534.34
#Mann= 4 ,-1 , 0
  4346.6     .08       0  4424.2     .05       0  4947.3    .035       0
  5022.3     .05       0
#XS Ineff= 2 , 0
       0 4934.32  515.78               0
Permanent Ineff=
       T       F
Bank Sta=4958.4,5015.75
XS Rating Curve= 0 ,0
Exp/Cntr=0.3,0.1

Type RM Length L Ch R = 1 ,94527   ,1365,1365,1365
BEGIN DESCRIPTION:
PLUMMERS CREEK 96.0
END DESCRIPTION:
XS GIS Cut Line= 3
      3486917.36      10600390.4      3485604.88     10600171.65
      3484651.76     10600020.61
#Sta/Elev= 30
    4107  527.25  4676.1  516.85  4710.5  518.06    4742  512.96  4791.6  513.65
  4811.8  517.73  4863.7  513.06  4974.1  512.93  4977.3  511.46  4994.1  507.76
 5021.88  511.51  5024.7  511.92  5085.6  515.25  5278.2  513.51  5659.7   518.6
    5722   516.1  5754.3   517.9  5794.8  531.43  5804.9   531.6  5851.7  523.68
  5895.1   523.3  5958.2  524.07  6098.5  532.21  6118.8  539.95  6128.9  540.38
  6159.3  536.38  6199.8  535.21  6260.5   537.3  6311.1  542.83  6402.6  542.47
#Mann= 5 ,-1 , 0
    4107     .05       0  4974.1    .035       0  5024.7     .05       0
  5895.1     .08       0  5958.2     .05       0
Bank Sta=4977.3,5021.88
XS Rating Curve= 0 ,0
Exp/Cntr=0.3,0.1

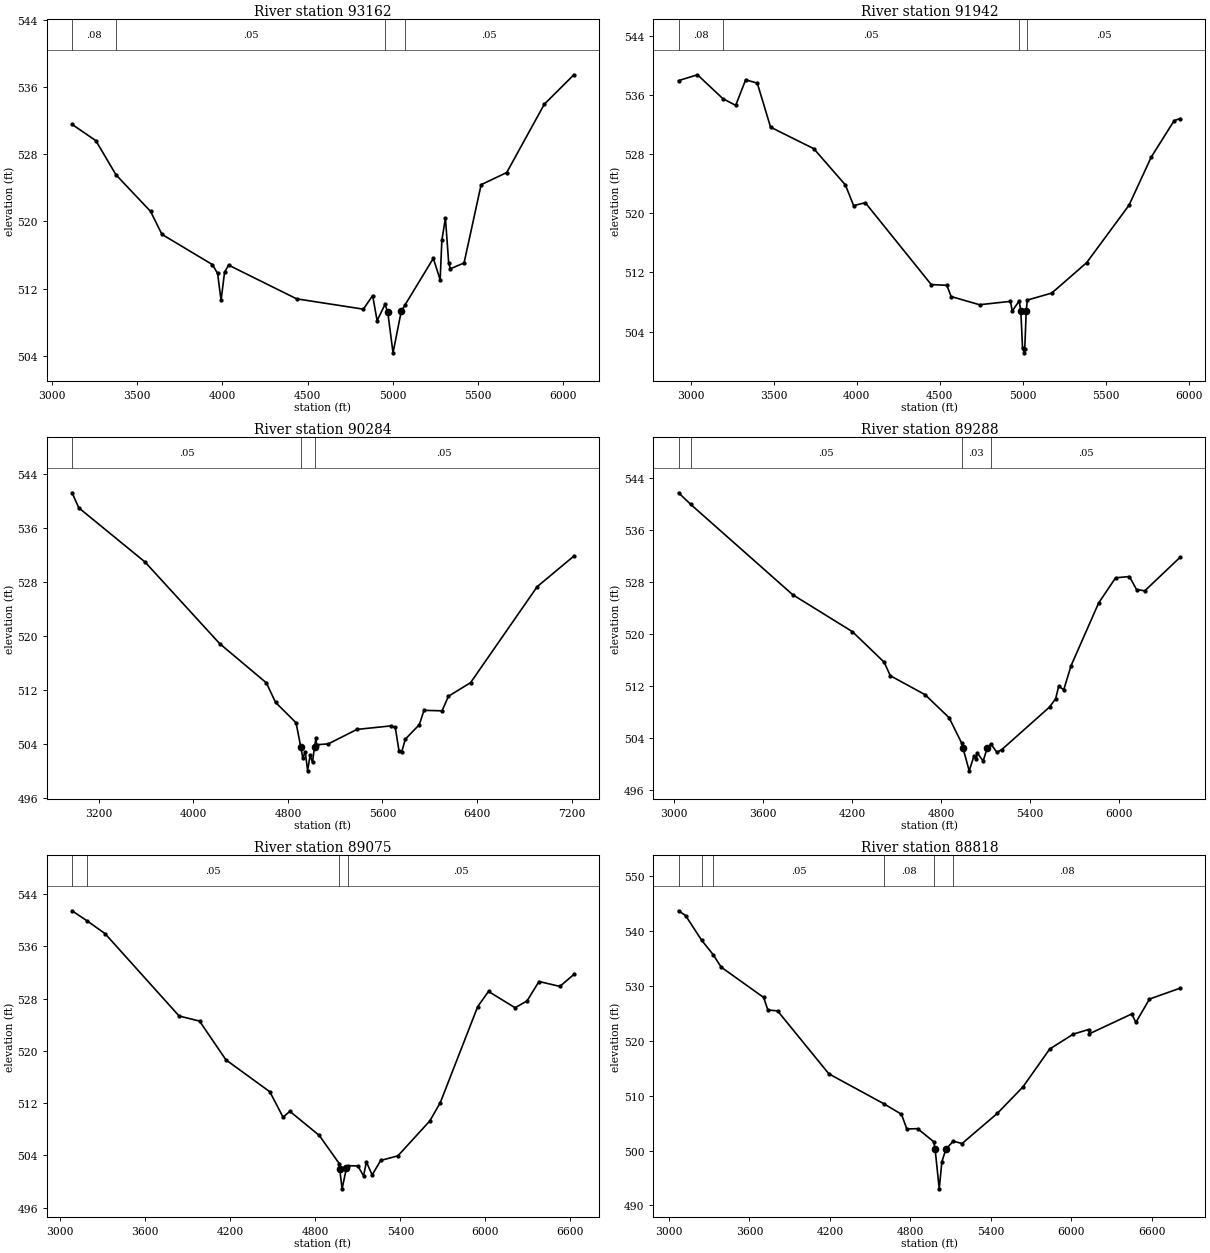
Type RM Length L Ch R = 1 ,93162   ,1220,1220,1220
BEGIN DESCRIPTION:
PLUMMERS CREEK 93.0
END DESCRIPTION:
XS GIS Cut Line= 4
      3487698.65     10598645.61      3486537.17     10598879.98
      3485688.21     10599171.65      3484828.87     10599213.32
#Sta/Elev= 30
    3119  531.54  3258.3  529.61  3376.6  525.54  3579.4  521.18    3646  518.45
  3941.8  514.85  3972.4  513.81  3992.8  510.58  4013.2  513.92  4036.5  514.79
  4436.1  510.77  4827.4  509.54  4881.9  511.16  4907.9  508.17  4954.2   510.1
  4970.4  509.19  5001.4  504.34  5049.4  509.27  5070.6  510.01  5237.7  515.59
  5277.7  513.04  5287.8  517.76  5308.7  520.38  5327.8  515.04  5337.8  514.35
  5417.9  515.04    5518  524.36  5668.2  525.81  5888.5  533.94  6061.9  537.45
#Mann= 4 ,-1 , 0
    3119     .08       0  3376.6     .05       0  4954.2    .035       0
  5070.6     .05       0
Bank Sta=4970.4,5049.4
XS Rating Curve= 0 ,0
Exp/Cntr=0.3,0.1

Type RM Length L Ch R = 1 ,91942   ,1658,1658,1658
BEGIN DESCRIPTION:
PLUMMERS CREEK 90.0
END DESCRIPTION:
XS GIS Cut Line= 4
      3488136.11     10597984.15      3486834.04     10597968.53
      3485828.84     10598239.36      3485172.59     10598406.03
#Sta/Elev= 30
  2927.3  537.96  3041.3  538.75  3194.1  535.52  3271.3  534.61  3331.3  538.07
  3401.3  537.62  3481.3  531.66  3741.4  528.75  3931.4  523.85  3981.4  521.04
  4051.4  521.44  4448.3  510.36  4542.2  510.26  4568.1  508.74  4738.9  507.63
  4925.4  508.09  4935.7  506.77  4977.1  508.13 4987.46  506.84  4997.9  501.75
    5008  501.12  5011.2  501.62 5020.12  506.83  5026.6  508.26  5173.9  509.21
  5383.6  513.32  5638.6  521.09  5772.7  527.62  5910.7  532.55  5947.6  532.83
#Mann= 4 ,-1 , 0
  2927.3     .08       0  3194.1     .05       0  4977.1     .03       0
  5026.6     .05       0
Bank Sta=4987.46,5020.12
XS Rating Curve= 0 ,0
Exp/Cntr=0.3,0.1

Type RM Length L Ch R = 1 ,90284   ,996,996,996
BEGIN DESCRIPTION:
PLUMMERS CREEK 88.0
END DESCRIPTION:
XS GIS Cut Line= 4
      3488209.02     10596593.53      3487172.59     10596567.48
      3485797.59     10596895.61      3484120.55       10596255.
#Sta/Elev= 30
  2973.8  541.23  3030.7     539  3590.9  530.99  4222.1  518.92  4617.6  513.11
  4695.5  510.22    4869   507.2 4909.33  503.57    4926     502  4946.6  502.92
  4966.9  500.09  4987.7  502.38  5008.3  501.36 5025.28  503.69  5037.4  504.89
  5042.6  503.95  5141.9  504.08  5384.5  506.22  5672.2  506.74  5708.4  506.53
  5740.5  502.97  5762.4  502.87    5794  504.79  5911.8  506.92  5951.5  509.04
  6104.4  508.97    6158  511.12  6345.7  513.14  6909.6  527.35  7219.4  531.86
#Mann= 3 , 0 , 0
  2973.8     .05       0 4909.33     .03       0 5025.28     .05       0
#XS Ineff= 2 , 0
       0                 5702.27       0  504.94
Permanent Ineff=
       F       T
Bank Sta=4909.33,5025.28
XS Rating Curve= 0 ,0
Exp/Cntr=0.3,0.1

Type RM Length L Ch R = 1 ,89288   ,213,213,213
BEGIN DESCRIPTION:
PLUMMERS CREEK 87.0
END DESCRIPTION:
XS GIS Cut Line= 4
      3488167.39     10596249.78      3487136.13     10596135.19
        3485933.     10595775.82      3484880.96     10595489.37
#Sta/Elev= 30
  3028.9   541.7  3111.7   539.9  3798.9  526.02  4201.2  520.34  4415.6  515.64
  4456.9  513.56    4691  510.65  4853.4   507.1  4938.5  503.18  4947.4   502.4
  4988.9  498.93  5020.4  501.16  5037.9  500.75  5043.1  501.69  5083.1  500.43
  5109.4  502.39  5135.2  503.05  5175.6  501.78  5208.3  502.19  5530.4  508.74
  5571.8  510.03  5592.6  511.98  5626.2  511.38  5675.5  515.09    5862  524.76
    5976  528.62  6069.3  528.82  6117.2  526.81  6172.9  526.62  6412.5  531.81
#Mann= 4 ,-1 , 0
  3028.9      .1       0  3111.7     .05       0  4938.5     .03       0
  5135.2     .05       0
Bank Sta=4947.4,5109.4
XS Rating Curve= 0 ,0
Exp/Cntr=0.3,0.1

Type RM Length L Ch R = 1 ,89075   ,257,257,257
BEGIN DESCRIPTION:
PLUMMERS CREEK 86.0
END DESCRIPTION:
XS GIS Cut Line= 4
      3488183.05     10596124.79      3486604.88     10595713.32
      3485537.17     10595572.69      3484725.94     10595380.28
#Sta/Elev= 30
  3082.8  541.46  3187.2  539.94  3314.8  537.98  3838.2  525.35  3982.4  524.57
  4168.9  518.63  4478.9  513.74  4571.9  509.85  4619.9  510.75  4827.5  507.06
  4968.7  502.74 4971.34  501.98  4988.6  498.88  5019.1  502.04  5029.2  502.42
  5099.8  502.39  5140.2  500.87  5160.3     503  5200.7  501.01  5261.2  503.23
  5382.4  503.93  5608.2  509.29  5681.8  512.09  5945.9  526.79    6022  529.11
  6209.5  526.61  6293.9  527.65  6378.4  530.63  6525.6  529.88  6624.4  531.71
#Mann= 4 ,-1 , 0
  3082.8      .1       0  3187.2     .05       0  4968.7     .04       0
  5029.2     .05       0
Bank Sta=4971.34,5019.1
XS Rating Curve= 0 ,0
Exp/Cntr=0.3,0.1

Type RM Length L Ch R = 1 ,88818   ,299,299,299
BEGIN DESCRIPTION:
PLUMMERS CREEK 85.0
END DESCRIPTION:
XS GIS Cut Line= 4
      3488172.58     10595843.53      3486906.96     10595484.15
      3485781.96     10595379.98      3484532.71     10595036.44
#Sta/Elev= 30
  3071.1   543.7  3123.6  542.83  3242.5  538.36  3328.6  535.73  3388.9  533.43
  3705.7   527.9  3736.9  525.62  3809.7  525.45  4191.8  513.98  4601.6  508.53
  4733.1  506.61  4773.3  503.93  4853.6  503.99  4974.1   501.6  4984.2   500.2
  5014.7  493.02  5034.4  497.95  5064.5  500.25  5119.4   501.7    5185  501.28
  5447.8  506.77    5639   511.6  5837.9  518.49  6014.2  521.22  6127.9  522.06
    6133  521.27  6449.8  524.89  6480.9  523.36  6582.3  527.61  6812.2  529.61
#Mann= 6 ,-1 , 0
  3071.1      .1       0  3242.5     .08       0  3328.6     .05       0
  4601.6     .08       0  4974.1     .07       0  5119.4     .08       0
Bank Sta=4984.2,5064.5
XS Rating Curve= 0 ,0
Exp/Cntr=0.3,0.1

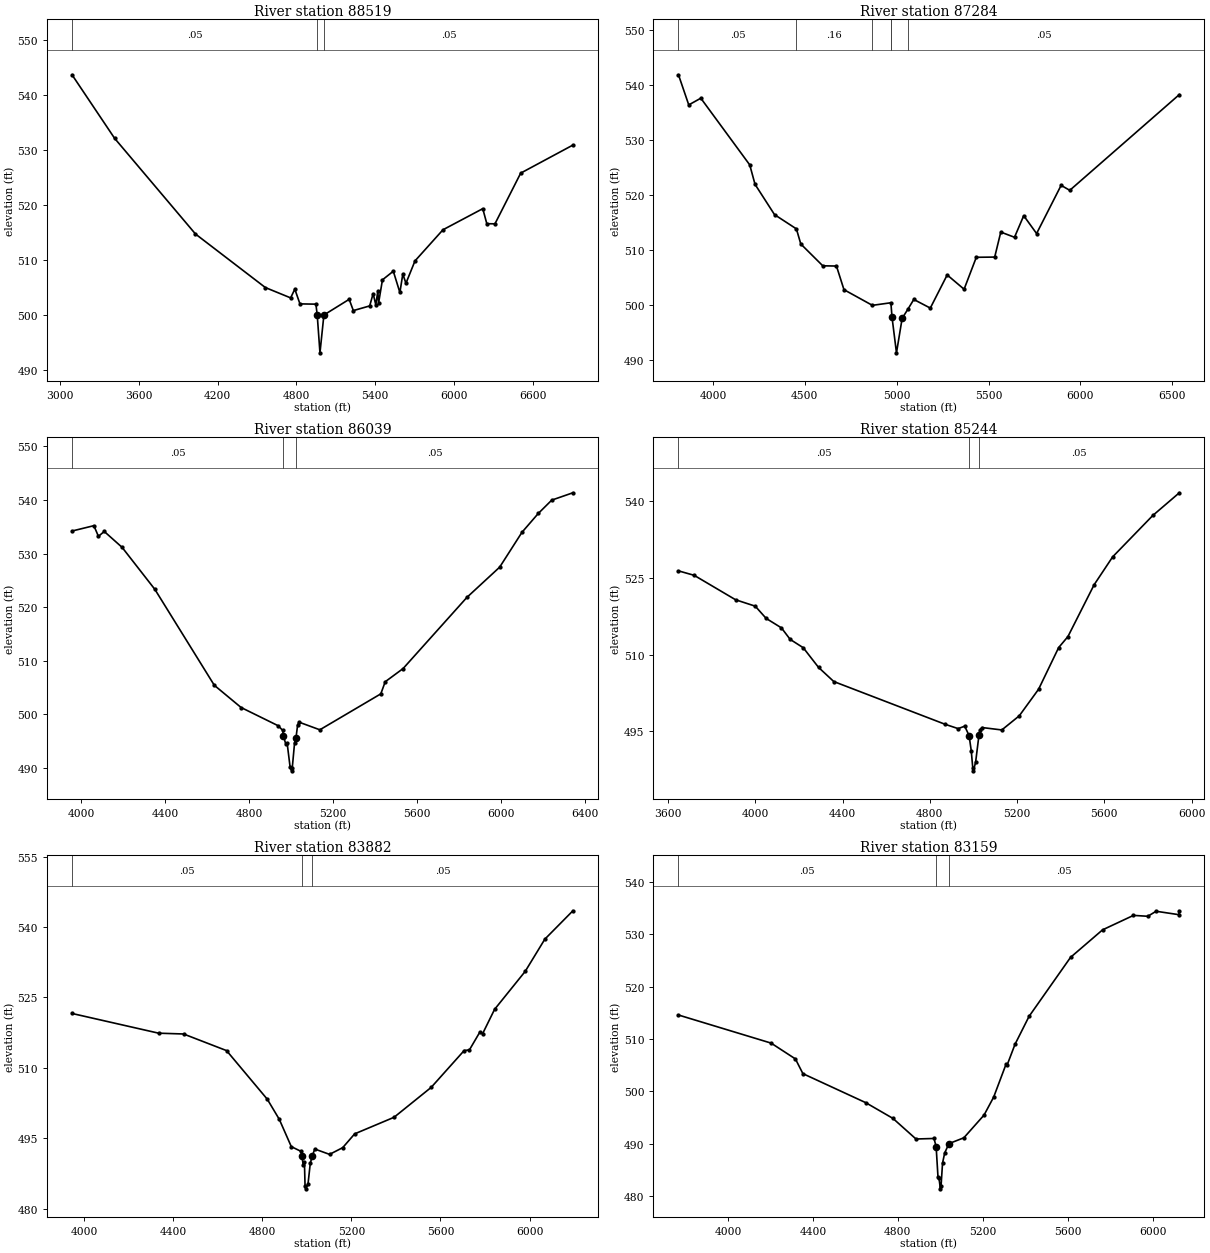
Type RM Length L Ch R = 1 ,88519   ,1235,1235,1235
BEGIN DESCRIPTION:
PLUMMERS CREEK 84.0
END DESCRIPTION:
XS GIS Cut Line= 4
      3488125.71     10595546.65      3487198.63     10595301.86
      3485823.63     10595083.11      3484407.04     10594723.76
#Sta/Elev= 30
  3091.9  543.64  3416.3  532.08  4031.8  514.69  4563.6  504.96    4756  503.08
  4787.8  504.67  4826.9  501.99  4948.4  501.94  4958.6  499.89  4979.2  493.09
  5009.2  499.97  5201.6  502.82  5233.3  500.77  5357.7  501.62  5383.8  503.85
  5404.1  501.85  5419.9  504.32    5425  502.09  5454.9  506.36  5537.5  507.93
  5587.6  504.06  5609.7   507.4  5633.8  505.74  5702.5   509.8  5915.4  515.46
  6218.4   519.3  6249.3  516.57  6311.2  516.54  6507.2  525.76  6904.5  530.86
#Mann= 3 , 0 , 0
  3091.9     .05       0  4958.6    .035       0  5009.2     .05       0
Bank Sta=4958.6,5009.2
XS Rating Curve= 0 ,0
Exp/Cntr=0.3,0.1

Type RM Length L Ch R = 1 ,87284   ,1245,1245,1245
BEGIN DESCRIPTION:
PLUMMERS CREEK 82.0
END DESCRIPTION:
XS GIS Cut Line= 4
      3487943.38     10594442.47      3487505.92     10594249.78
      3486255.92     10593989.36      3485287.14     10593921.65
#Sta/Elev= 30
  3812.1  541.84  3868.1  536.36  3933.7  537.58    4200  525.45  4228.8  521.91
  4334.9   516.4  4453.9  513.81  4477.9  511.06  4597.5  507.09    4672  507.05
  4712.8  502.75  4867.5   499.9  4968.2  500.37 4974.33  497.75  4998.6  491.26
  5029.5  497.54  5060.1  499.16  5092.9  500.97  5182.7   499.4  5274.6  505.43
  5366.6  502.83  5433.1  508.64  5533.2  508.68  5566.3  513.23    5641  512.28
  5691.1  516.21  5761.2  512.96  5894.7  521.73  5941.7  520.82  6538.1  538.24
#Mann= 6 ,-1 , 0
  3812.1     .05       0  4453.9     .16       0  4867.5     .05       0
  4968.2     .05       0  4968.2     .03       0  5060.1     .05       0
Bank Sta=4974.33,5029.5
XS Rating Curve= 0 ,0
Exp/Cntr=0.3,0.1

Type RM Length L Ch R = 1 ,86039   ,795,795,795
BEGIN DESCRIPTION:
PLUMMERS CREEK 79.0
END DESCRIPTION:
XS GIS Cut Line= 2
      3488146.57     10593864.39      3486531.97     10592109.16
#Sta/Elev= 30
  3956.6  534.21  4060.7  535.21  4082.3  533.22  4110.1  534.13  4195.1  531.16
  4351.1  523.32  4634.1  505.42  4761.7  501.27  4938.6  497.86  4959.6     497
 4963.37  495.95  4973.8  494.51  4980.6  494.71  4994.8  490.22  5001.9  489.45
  5005.2  489.95  5016.3  494.69  5023.1  495.64  5030.5  497.92  5037.3  498.54
  5136.6  497.11  5426.9  503.82  5447.9  506.08    5533  508.54    5837  521.83
  5992.9  527.47    6099  533.97  6176.7  537.49  6240.8  539.98  6341.5  541.35
#Mann= 3 , 0 , 0
  3956.6     .05       0 4963.37     .03       0  5023.1     .05       0
Bank Sta=4963.37,5023.1
XS Rating Curve= 0 ,0
Exp/Cntr=0.3,0.1

Type RM Length L Ch R = 1 ,85244   ,1362,1362,1362
BEGIN DESCRIPTION:
PLUMMERS CREEK 77.0
END DESCRIPTION:
XS GIS Cut Line= 4
      3489084.04     10592416.44      3488417.38     10592416.44
       3487495.5     10592406.03      3486990.33     10591911.27
#Sta/Elev= 30
  3648.1  526.37    3720   525.5    3910  520.72    4000  519.47    4050  517.08
    4120  515.23    4160  512.98    4220  511.35    4290  507.51    4360  504.74
  4870.1  496.39  4930.1  495.54  4960.1  496.02  4980.1  494.18  4990.1  491.21
  4997.1  487.79  4999.8  487.29  5010.1  488.98  5025.5   494.3  5030.1  495.34
  5040.1  495.75  5130.1  495.28  5210.1  498.04  5298.7  503.24  5390.7  511.38
  5433.2  513.53  5553.3  523.66  5638.2  529.11  5822.1  537.19  5943.8  541.63
#Mann= 3 , 0 , 0
  3648.1     .05       0  4980.1    .035       0  5025.5     .05       0
Bank Sta=4980.1,5025.5
XS Rating Curve= 0 ,0
Exp/Cntr=0.3,0.1

Type RM Length L Ch R = 1 ,83882   ,723,723,723
BEGIN DESCRIPTION:
PLUMMERS CREEK 74.0
END DESCRIPTION:
XS GIS Cut Line= 2
        3489125.     10591399.77      3486911.46     10591004.81
#Sta/Elev= 30
  3946.2  521.57  4335.1  517.37  4446.9   517.2  4639.9  513.66  4822.9   503.3
  4876.7  499.02  4930.6  493.21  4975.1  492.18 4978.18  491.19  4984.5  489.22
  4989.5  489.96  4992.4  484.72  4995.2  484.22  5005.6  485.24  5015.7  489.63
 5024.21  491.15    5036   492.7  5102.3  491.56  5161.3  492.99  5215.1  495.93
  5391.9  499.46  5558.6  505.83  5706.5  513.67  5730.3  513.82  5777.6  517.65
  5789.3  517.25  5843.1  522.44  5980.7  530.54  6068.7  537.39  6194.7  543.44
#Mann= 3 , 0 , 0
  3946.2     .05       0 4978.18     .03       0 5024.21     .05       0
Bank Sta=4978.18,5024.21
XS Rating Curve= 0 ,0
Exp/Cntr=0.3,0.1

Type RM Length L Ch R = 1 ,83159   ,1022,1022,1022
BEGIN DESCRIPTION:
PLUMMERS CREEK 72.0
END DESCRIPTION:
XS GIS Cut Line= 4
      3489116.38      10590635.9       3488617.2     10590470.96
      3487419.29      10590583.8      3486812.99     10590757.03
#Sta/Elev= 30
  3766.5  514.56  4202.8   509.2  4317.4  506.18  4352.7  503.37  4648.9  497.83
  4776.9  494.83  4885.4   490.9  4970.3     491  4980.3  489.45    4989  483.67
    4994  483.39  5000.2  481.39  5003.4  481.89  5010.5   486.3  5020.5  488.22
  5040.6  490.02  5110.9  491.13  5206.1  495.47  5251.5  498.91  5309.6  505.17
  5314.6     505    5352  508.98  5418.2  514.31  5613.5  525.56  5764.3  530.81
  5909.9  533.57  5977.5   533.4  6016.5  534.36  6123.1  533.71    6126  534.45
#Mann= 3 , 0 , 0
  3766.5     .05       0  4980.3    .035       0  5040.6     .05       0
Bank Sta=4980.3,5040.6
XS Rating Curve= 0 ,0
Exp/Cntr=0.3,0.1

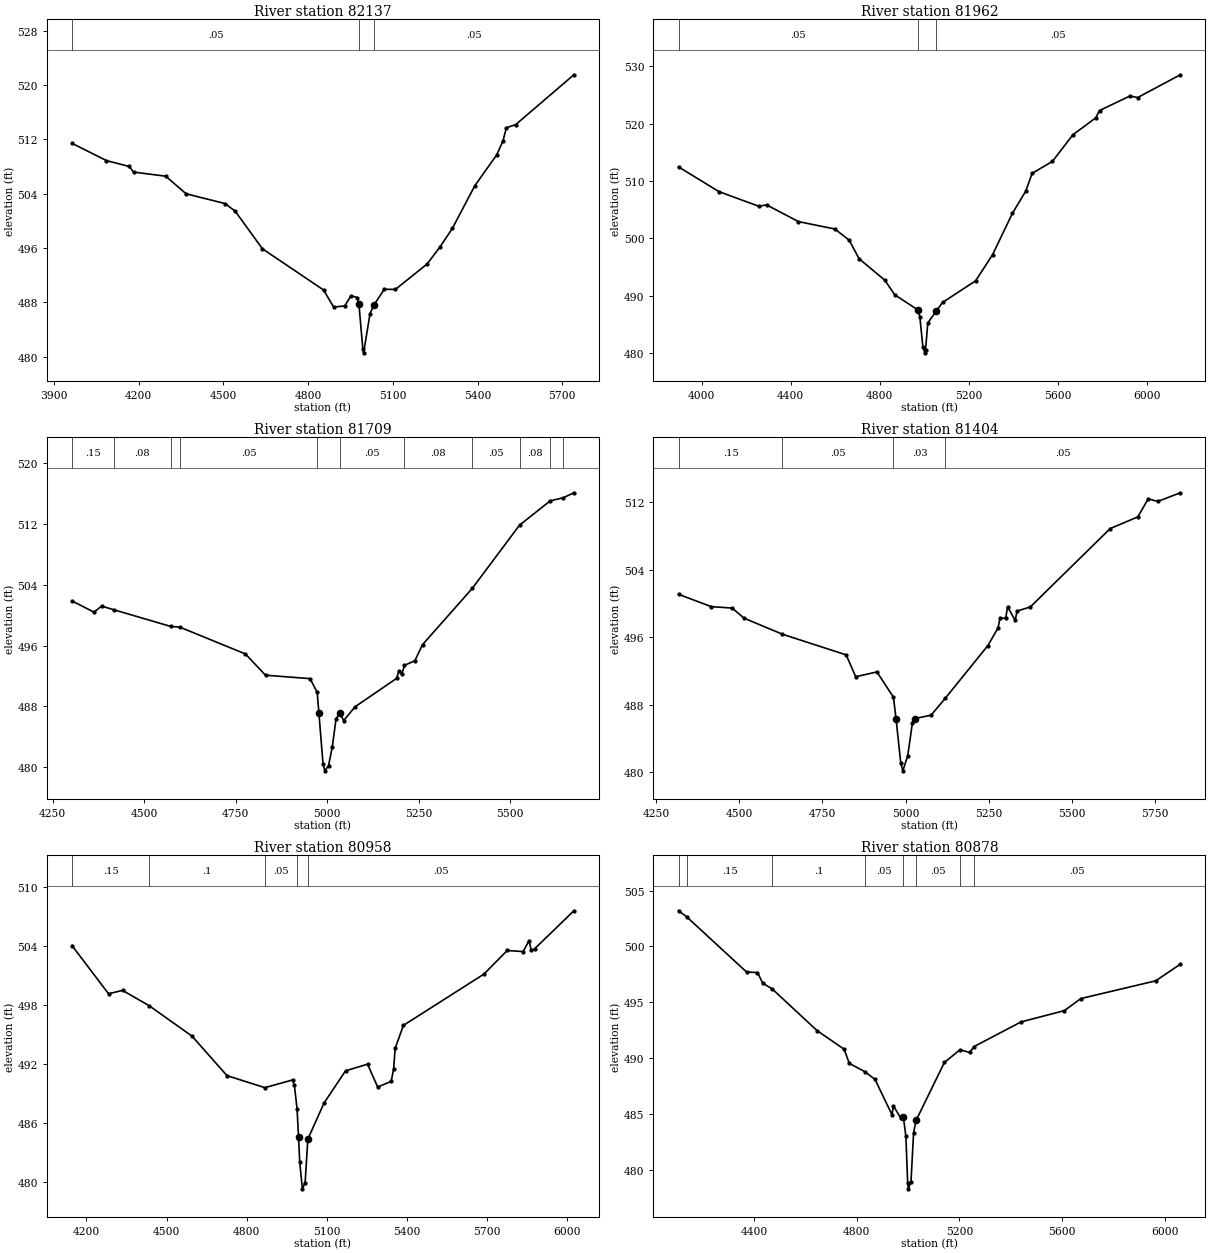
Type RM Length L Ch R = 1 ,82137   ,175,175,175
BEGIN DESCRIPTION:
PLUMMERS CREEK 71.0
END DESCRIPTION:
XS GIS Cut Line= 3
      3489051.24     10590392.84      3488725.71     10589906.72
      3487657.96     10589377.19
#Sta/Elev= 30
  3963.9  511.41  4085.7  508.87  4166.5     508  4181.5  507.18  4295.6  506.57
  4367.6  503.98  4505.7  502.54  4541.7  501.41  4637.9  495.88  4854.4  489.81
  4890.1   487.3  4929.3  487.45  4951.7  488.97  4974.2  488.69  4979.7  487.74
  4993.6  481.05  4996.3  480.55    5019  486.33    5033  487.61  5069.4  489.92
  5108.7  489.89  5220.7  493.62  5265.6  496.08  5310.4  498.87  5390.1  505.17
  5467.3  509.69  5489.7  511.75  5501.8  513.71  5534.6  514.16  5740.8  521.51
#Mann= 3 , 0 , 0
  3963.9     .05       0  4979.7    .035       0    5033     .05       0
Bank Sta=4979.7,5033
XS Rating Curve= 0 ,0
Exp/Cntr=0.3,0.1

Type RM Length L Ch R = 1 ,81962   ,253,253,253
BEGIN DESCRIPTION:
PLUMMERS CREEK 70.0
END DESCRIPTION:
XS GIS Cut Line= 4
      3489198.79     10590340.73      3488717.03     10589720.09
      3488152.79     10589424.95      3487397.56     10589073.37
#Sta/Elev= 30
  3896.1  512.46  4078.4  508.14  4256.7   505.6    4292  505.84    4435  502.92
  4598.8  501.63  4663.1  499.68  4707.5  496.45  4823.5  492.69  4867.9  490.15
  4972.4   487.5  4980.8  486.29  4994.5  480.97  5003.1  480.02  5006.3  480.52
  5016.5  485.23  5055.1  487.35  5082.8  488.81  5231.6  492.59    5308  497.17
  5396.5  504.34  5456.9  508.25  5485.3  511.33  5576.8  513.43  5668.4  518.06
  5771.6  521.03  5788.3   522.3  5925.5  524.84  5959.4  524.56  6151.6  528.54
#Mann= 3 , 0 , 0
  3896.1     .05       0  4972.4    .035       0  5055.1     .05       0
Bank Sta=4972.4,5055.1
XS Rating Curve= 0 ,0
Exp/Cntr=0.3,0.1

Type RM Length L Ch R = 1 ,81709   ,305,305,305
BEGIN DESCRIPTION:
PLUMMERS CREEK 69.1
END DESCRIPTION:
XS GIS Cut Line= 4
      3488990.47      10589763.5      3488773.45     10589403.25
      3488404.53     10589307.76      3487945.79      10588970.2
#Sta/Elev= 30
  4302.8  501.88  4362.5  500.41  4383.8   501.2  4417.1  500.72  4572.1  498.53
  4596.9  498.44  4776.4  494.91  4831.4  492.11  4953.2  491.66  4972.7  489.84
 4977.22  487.17  4988.7  480.39  4993.6  479.53  5003.7  480.23    5014   482.7
  5024.1  486.38  5034.6  487.13    5045  486.15    5076  487.95  5189.4  491.69
  5195.6  492.62  5204.1  492.28  5211.2  493.41  5239.6  494.02  5260.4  496.13
  5396.2  503.52  5525.5  511.85  5609.4  515.05  5644.8  515.45    5674  516.11
#Mann= 11 ,-1 , 0
  4302.8     .15       0  4417.1     .08       0  4572.1     .15       0
  4596.9     .05       0  4972.7     .03       0  5034.6     .05       0
  5211.2     .08       0  5396.2     .05       0  5525.5     .08       0
  5609.4     .05       0  5644.8     .08       0
Bank Sta=4977.22,5034.6
XS Rating Curve= 0 ,0
Exp/Cntr=0.3,0.1

Type RM Length L Ch R = 1 ,81404   ,446,446,446
BEGIN DESCRIPTION:
PLUMMERS CREEK 69.0
END DESCRIPTION:
XS GIS Cut Line= 4
      3489046.89     10589720.08      3488847.24     10589294.74
      3488539.08     10588921.48      3488036.37     10588687.46
#Sta/Elev= 30
  4317.5  501.08  4415.9  499.62  4478.8  499.45  4514.6  498.25    4630  496.35
  4821.4  493.91  4850.1  491.32  4913.9  491.89  4963.4  488.91  4971.3  486.37
  4985.6  481.08  4991.8  480.18  5006.4  481.97  5020.7   485.9  5027.2  486.37
  5076.7  486.77  5119.7  488.79  5247.4  495.01  5278.2  497.12  5283.7  498.24
  5301.1  498.27  5306.6  499.61  5329.5  497.99    5335  499.09  5375.2  499.59
    5615  508.86  5698.2  510.25  5729.4  512.39  5757.8  512.07  5825.9   513.1
#Mann= 4 ,-1 , 0
  4317.5     .15       0    4630     .05       0  4963.4     .03       0
  5119.7     .05       0
Bank Sta=4971.3,5027.2
XS Rating Curve= 0 ,0
Exp/Cntr=0.3,0.1

Type RM Length L Ch R = 1 ,80958   ,80,80,80
BEGIN DESCRIPTION:
PLUMMERS CREEK 68.1
END DESCRIPTION:
XS GIS Cut Line= 3
      3489220.51     10589806.93      3489090.29     10588778.25
      3488352.48     10588374.62
#Sta/Elev= 30
  4146.2  504.01  4282.6  499.13  4335.3  499.47  4434.5  497.92    4595  494.83
  4725.9  490.82  4867.6   489.6  4971.3  490.38  4978.1  489.84  4988.2  487.48
 4993.61  484.62  4998.2  482.04  5008.1  479.33  5018.4  479.96  5028.5  484.37
    5089  488.03  5169.6  491.31    5252  491.98    5290  489.66  5340.6  490.24
  5349.7  491.52  5355.4   493.6  5386.2  495.92  5687.4  501.12  5774.7  503.52
  5834.4  503.41  5856.2  504.52  5864.9  503.52    5878  503.71  6024.1  507.55
#Mann= 5 ,-1 , 0
  4146.2     .15       0  4434.5      .1       0  4867.6     .05       0
  4988.2     .03       0  5028.5     .05       0
Bank Sta=4993.61,5028.5
XS Rating Curve= 0 ,0
Exp/Cntr=0.3,0.1

Type RM Length L Ch R = 1 ,80878   ,293,293,293
BEGIN DESCRIPTION:
PLUMMERS CREEK 68.0
END DESCRIPTION:
XS GIS Cut Line= 4
      3489346.38     10589841.66      3489211.82       10589247.
       3489177.1     10588721.82      3488669.26     10588079.43
#Sta/Elev= 30
  4106.1   503.2  4137.8  502.66  4371.1  497.71  4413.7  497.66  4434.2  496.71
  4471.3  496.19  4645.5  492.46  4751.2  490.79  4771.3  489.52  4831.5  488.78
  4871.5  488.08  4937.8  484.91  4942.8  485.72  4971.7  484.63  4981.7  484.75
  4991.8  482.99  4998.8  478.77  5001.5  478.27  5011.8  478.92  5021.8   483.3
  5031.8  484.42  5142.1  489.61  5202.7  490.74  5239.7   490.5  5257.8  491.03
  5439.9  493.23  5609.3  494.25  5673.4  495.33  5965.2  496.92    6061  498.41
#Mann= 8 ,-1 , 0
  4106.1      .1       0  4137.8     .15       0  4471.3      .1       0
  4831.5     .05       0  4981.7     .03       0  5031.8     .05       0
  5202.7     .08       0  5257.8     .05       0
Bank Sta=4981.7,5031.8
XS Rating Curve= 0 ,0
Exp/Cntr=0.3,0.1