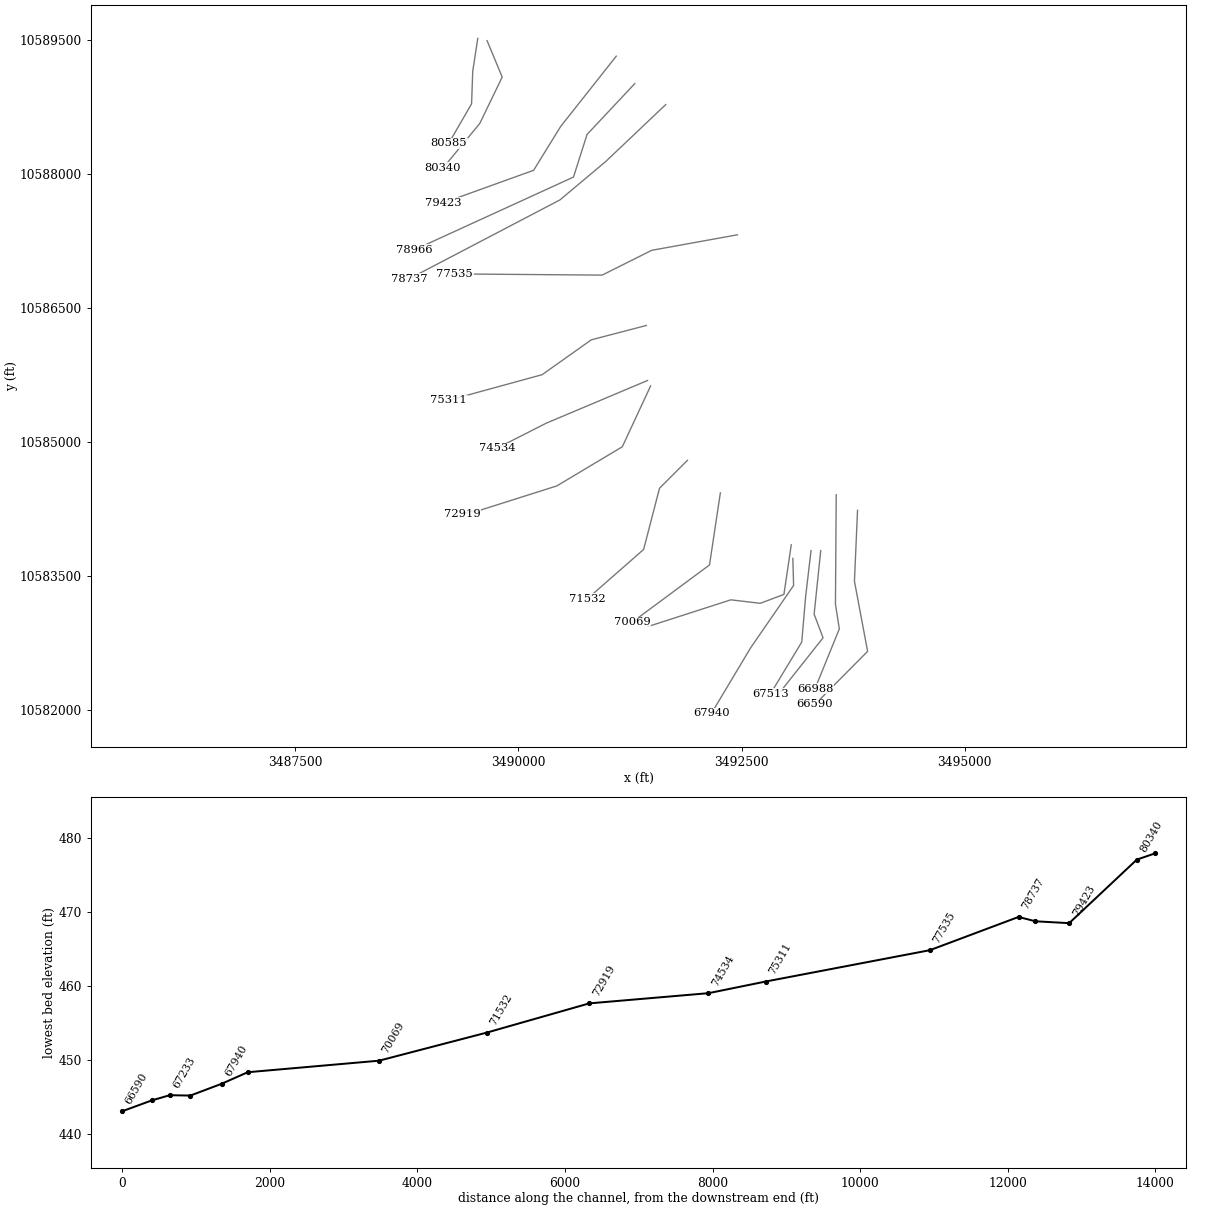
HEC-RAS study PLUMMERS CREEK.prj: PLUMMERS CREEK Base Level Engineering

--- PLUMMERS CREEK.g01 (geometry) --- (continued)

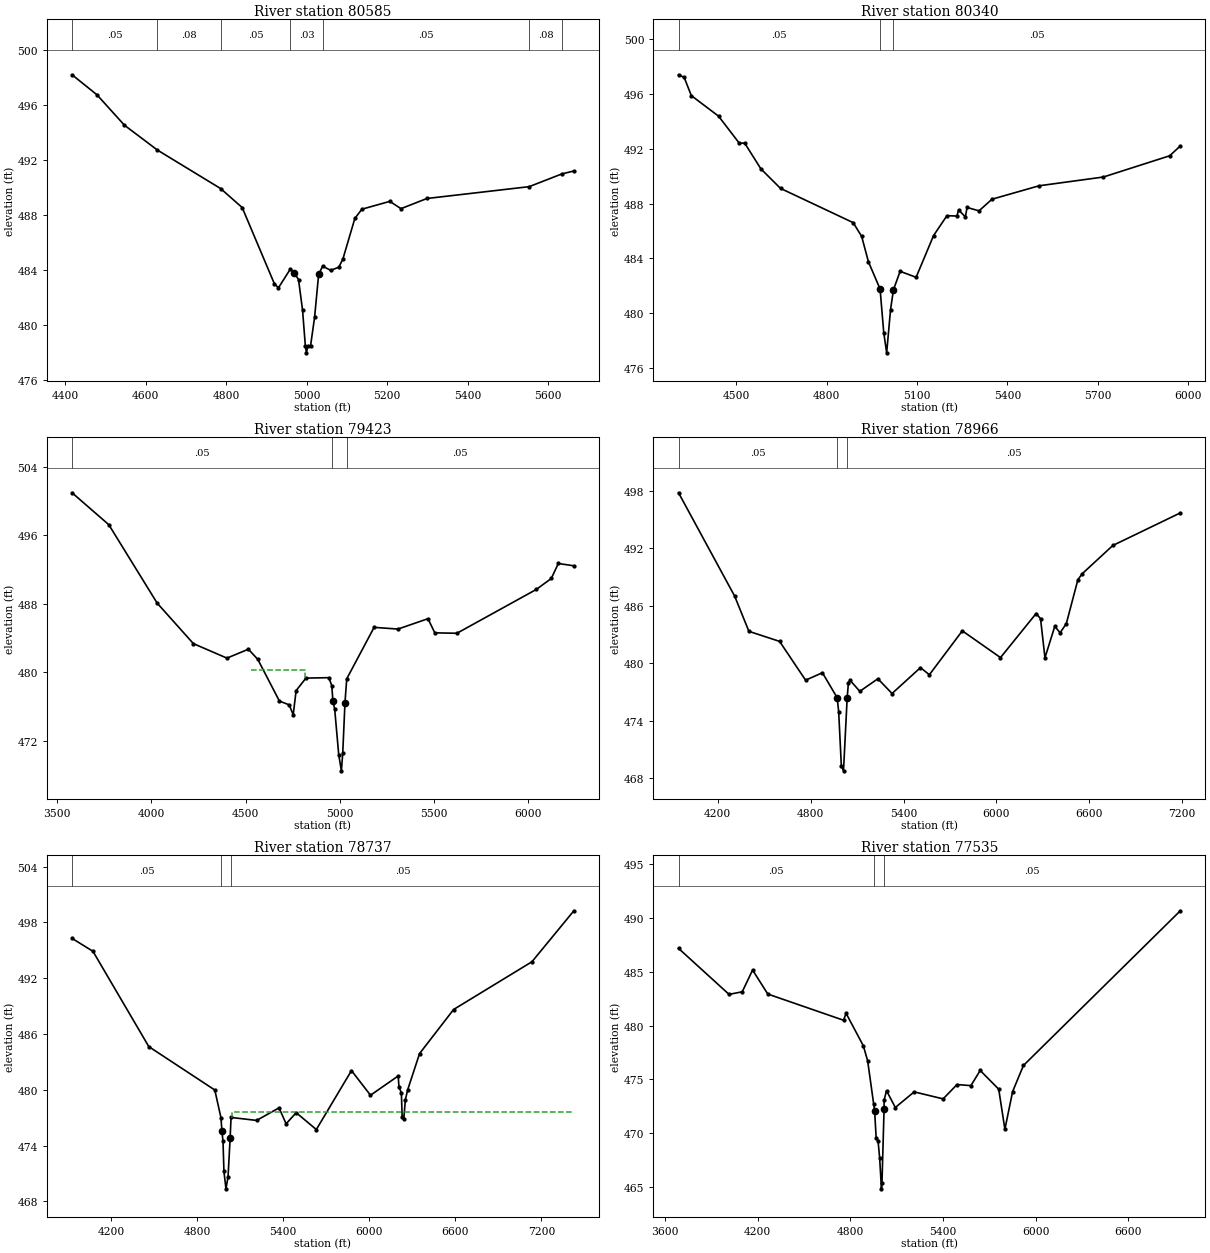
Type RM Length L Ch R = 1 ,80585   ,245,245,245
BEGIN DESCRIPTION:
PLUMMERS CREEK 67.0
END DESCRIPTION:
XS GIS Cut Line= 4
      3489546.02     10589520.41       3489489.6     10589151.51
      3489476.58     10588786.93      3489221.23     10588345.47
#Sta/Elev= 30
  4416.5  498.18  4478.2  496.73  4546.8  494.51  4628.9   492.7  4786.1   489.9
  4839.6  488.52  4919.6  482.98  4929.7  482.68  4959.7  484.06  4969.7  483.74
  4979.7  483.28  4989.7  481.07  4996.7  478.45  4999.4  477.95  5002.7  478.45
  5009.7  478.47  5019.7  480.54  5029.7  483.65  5039.7  484.26  5059.7  483.95
  5079.7  484.18  5089.8  484.75  5119.8  487.73  5137.3   488.4  5206.8  488.97
  5234.5  488.44  5299.2  489.18  5553.3  490.04  5634.9  490.97  5664.5  491.18
#Mann= 7 ,-1 , 0
  4416.5     .05       0  4628.9     .08       0  4786.1     .05       0
  4959.7     .03       0  5039.7     .05       0  5553.3     .08       0
  5634.9     .05       0
Bank Sta=4969.7,5029.7
XS Rating Curve= 0 ,0
Exp/Cntr=0.3,0.1

Type RM Length L Ch R = 1 ,80340   ,917,917,917
BEGIN DESCRIPTION:
PLUMMERS CREEK 66.3
END DESCRIPTION:
XS GIS Cut Line= 4
      3489650.18     10589494.42      3489819.46     10589086.41
      3489567.73     10588565.57      3489156.31     10588067.54
#Sta/Elev= 30
    4308   497.4  4326.7  497.21  4350.5  495.88  4440.9  494.38    4510   492.4
  4527.5  492.42  4581.6  490.53  4646.6  489.11  4887.9  486.61    4916  485.61
  4938.6  483.75  4977.2  481.77  4989.4  478.59  4999.1  477.11    5012  480.27
  5021.6  481.71  5043.8  483.06  5096.8  482.62  5154.9  485.67  5199.3  487.12
  5232.4  487.09  5237.9  487.54  5260.5  487.03  5266.1  487.72  5305.7  487.47
  5348.8  488.32  5505.2   489.3  5718.8  489.94    5939  491.49  5974.2  492.21
#Mann= 3 , 0 , 0
    4308     .05       0  4977.2     .03       0  5021.6     .05       0
Bank Sta=4977.2,5021.6
XS Rating Curve= 0 ,0
Exp/Cntr=0.3,0.1

Type RM Length L Ch R = 1 ,79423   ,457,457,457
BEGIN DESCRIPTION:
PLUMMERS CREEK 66.2
END DESCRIPTION:
XS GIS Cut Line= 4
       3491096.9     10589320.59      3490473.86     10588532.64
      3490171.52     10588042.47      3489154.56       10587676.
#Sta/Elev= 30
  3579.2  500.95  3773.9  497.23  4030.4  488.08  4222.7  483.35  4400.6  481.66
  4514.4   482.7  4564.1  481.52  4678.9  476.65  4730.8  476.21  4752.1  475.05
  4767.5  477.87  4819.6  479.33  4941.3  479.38  4956.7  478.44  4962.6  476.65
  4972.1  475.72  4993.4  470.41  5007.6  468.51  5014.7  470.54 5026.68  476.48
    5036  479.25  5181.2  485.25  5307.8  485.05  5466.9  486.26  5502.9  484.61
  5620.3  484.56  6041.2  489.67  6120.8  490.95  6158.2   492.7  6240.6  492.43
#Mann= 3 ,-1 , 0
  3579.2     .05       0  4956.7     .03       0    5036     .05       0
#XS Ineff= 1 ,-1
  4528.4 4813.74  480.23
Permanent Ineff=
       F
Bank Sta=4962.6,5026.68
XS Rating Curve= 0 ,0
Exp/Cntr=0.3,0.1

Type RM Length L Ch R = 1 ,78966   ,229,229,229
BEGIN DESCRIPTION:
PLUMMERS CREEK 66.1
END DESCRIPTION:
XS GIS Cut Line= 4
      3491303.81      10589012.6      3490769.98     10588444.05
      3490618.07     10587966.62      3488835.69     10587151.32
#Sta/Elev= 30
  3946.7  497.78  4309.3  486.99  4401.2  483.32  4599.4  482.27  4767.4  478.22
    4876     479  4971.3  476.39    4981  474.93  4998.3  469.26  5012.2  468.76
  5035.8  476.36  5043.9  477.94  5054.4  478.21  5117.4  477.06  5234.2  478.37
  5325.7  476.83  5509.1  479.53  5566.8  478.79  5779.5  483.37  6026.1  480.58
  6256.3  485.18  6284.8  484.64  6313.3  480.56  6376.9  483.85  6410.9  483.16
  6451.4  484.13    6526  488.71  6554.5  489.34  6751.7  492.28  7187.6  495.68
#Mann= 3 , 0 , 0
  3946.7     .05       0  4971.3     .03       0  5035.8     .05       0
Bank Sta=4971.3,5035.8
XS Rating Curve= 0 ,0
Exp/Cntr=0.3,0.1

Type RM Length L Ch R = 1 ,78737   ,1202,1202,1202
BEGIN DESCRIPTION:
PLUMMERS CREEK 66.0
END DESCRIPTION:
XS GIS Cut Line= 4
      3491651.05     10588778.24      3490978.32     10588140.23
      3490466.16     10587710.54      3488782.13     10586829.46
#Sta/Elev= 30
  3929.2  496.29  4074.7   494.9  4463.8  484.65  4923.7  479.98  4966.6     477
  4973.1   475.6  4980.9  474.45  4987.4  471.22  5001.5  469.35  5016.1  470.66
  5030.4  474.77  5036.9  477.03  5215.1  476.71  5371.2  478.06  5420.6  476.35
    5491  477.54  5631.1  475.73  5876.1  482.07  6008.5  479.42  6201.5  481.49
  6207.1  480.27  6223.6  479.69  6229.2   477.1    6240  476.83  6251.8  478.95
  6267.7  480.01  6350.4   483.9  6587.5  488.64  7133.7  493.78  7425.5  499.26
#Mann= 3 ,-1 , 0
  3929.2     .05       0  4966.6    .035       0  5036.9     .05       0
#XS Ineff= 2 , 0
       0                 5045.45       0  477.57
Permanent Ineff=
       F       T
Bank Sta=4973.1,5030.4
XS Rating Curve= 0 ,0
Exp/Cntr=0.3,0.1

Type RM Length L Ch R = 1 ,77535   ,2224,2224,2224
BEGIN DESCRIPTION:
PLUMMERS CREEK 63.2
END DESCRIPTION:
XS GIS Cut Line= 4
      3492453.97     10587319.91      3491494.81      10587146.3
      3490939.25     10586868.53      3489286.38     10586881.54
#Sta/Elev= 30
  3688.1  487.17  4015.2   482.9  4100.5  483.14  4167.6  485.16    4266  482.93
  4756.2   480.5    4773  481.14  4884.8  478.12  4912.7  476.72  4951.9  472.68
  4957.5  472.12  4967.7  469.56  4979.8   469.3  4990.1  467.74  5001.9  464.85
  5005.2  465.35 5018.82  472.28    5019  473.09  5034.8  473.96  5091.6   472.4
  5213.7  473.85  5401.1   473.2  5491.1  474.53  5581.1  474.43  5641.1  475.84
  5761.1   474.1  5801.1  470.38  5851.1  473.88  5921.1   476.3  6936.9  490.66
#Mann= 3 ,-1 , 0
  3688.1     .05       0  4951.9     .03       0    5019     .05       0
#XS Ineff= 1 ,-1
 5654.56 6019.81  475.25
Permanent Ineff=
       F
Bank Sta=4957.5,5018.82
XS Rating Curve= 0 ,0
Exp/Cntr=0.3,0.1

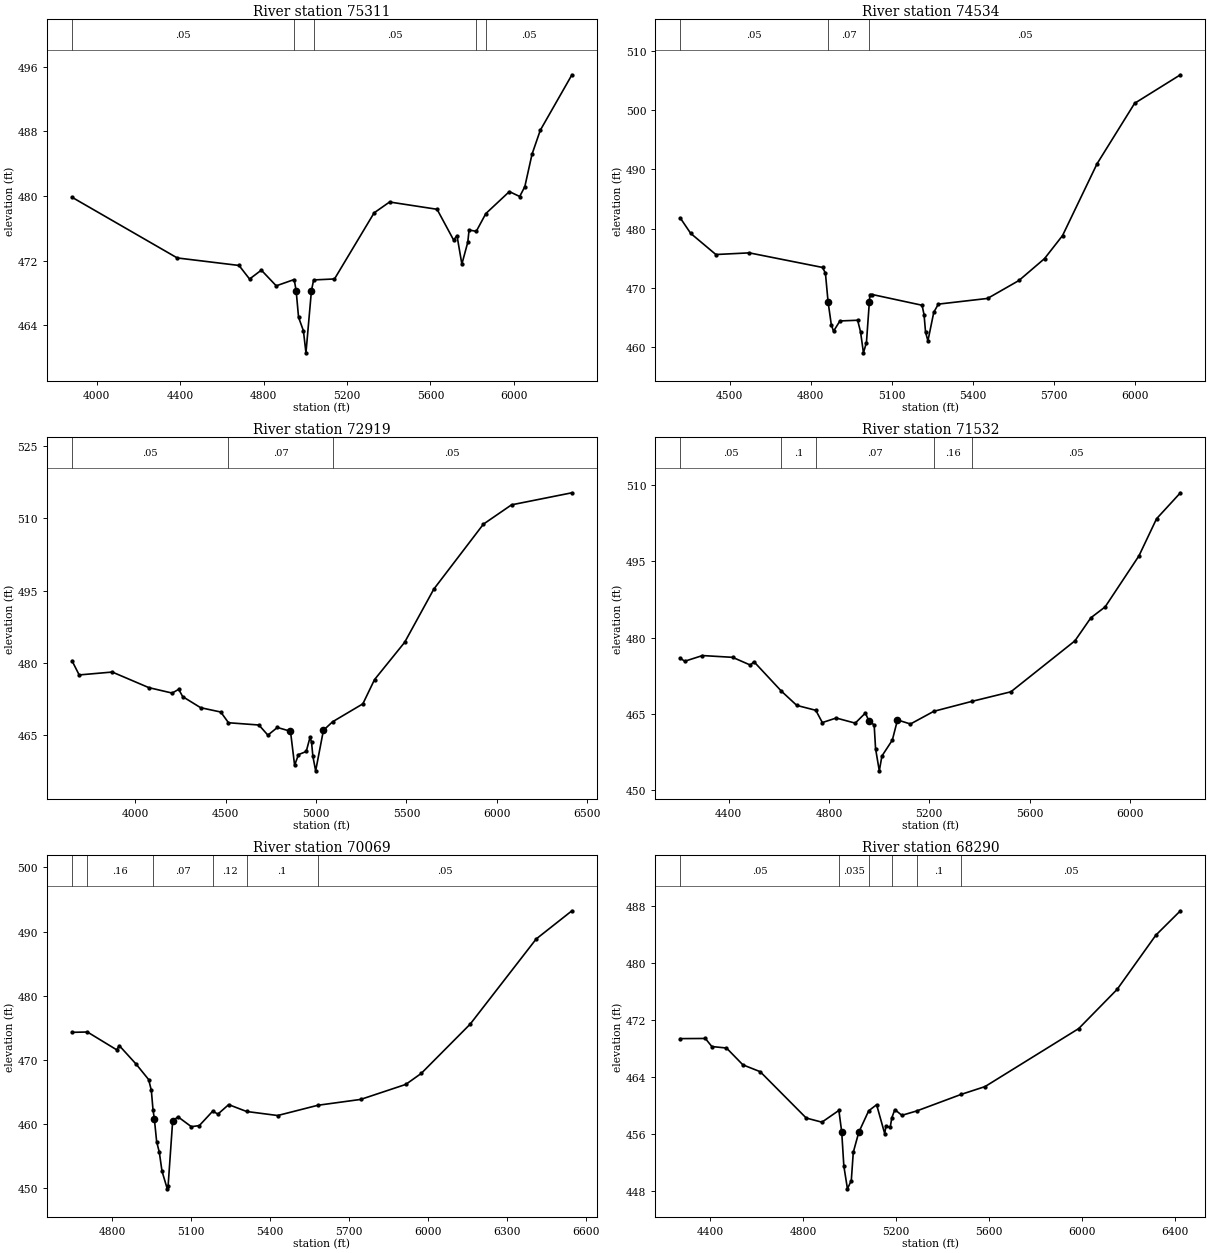
Type RM Length L Ch R = 1 ,75311   ,777,777,777
BEGIN DESCRIPTION:
PLUMMERS CREEK 63.1
END DESCRIPTION:
XS GIS Cut Line= 4
      3491434.07      10586304.3      3490817.73      10586143.7
      3490266.51     10585753.07      3489220.54     10585466.63
#Sta/Elev= 30
  3881.4  479.86  4386.1  472.35  4682.3  471.42  4732.8  469.74  4789.3  470.84
  4860.7   468.9  4946.8  469.68 4956.18  468.29  4967.7  465.01    4991  463.34
  5003.2  460.61  5029.5  468.31    5040  469.63    5140  469.75    5330  477.93
  5404.1  479.27  5631.7  478.37  5711.1  474.57  5727.3  475.11  5750.7  471.59
  5779.1   474.3  5785.2  475.81  5819.7  475.64  5865.6  477.84  5978.4  480.56
  6027.9  479.95  6052.5  481.17    6087  485.18  6126.7  488.15  6278.4  495.01
#Mann= 5 ,-1 , 0
  3881.4     .05       0  4946.8    .035       0    5040     .05       0
  5819.7     .16       0  5865.6     .05       0
Bank Sta=4956.18,5029.5
XS Rating Curve= 0 ,0
Exp/Cntr=0.3,0.1

Type RM Length L Ch R = 1 ,74534   ,1615,1615,1615
BEGIN DESCRIPTION:
PLUMMERS CREEK 63.0
END DESCRIPTION:
XS GIS Cut Line= 3
      3491447.07     10585687.97      3490314.25     10585210.54
      3489758.69     10584928.42
#Sta/Elev= 30
  4317.3  481.74  4355.2  479.19  4448.5  475.62  4572.3   475.9  4843.6  473.44
  4854.4  472.48 4864.22  467.64  4876.1  463.81  4884.4  462.67  4908.1  464.41
  4973.8  464.53  4984.6  462.56  4995.3  459.03  5006.4  460.77 5017.16   467.6
  5019.3  468.86  5028.1  468.87  5212.5  467.06  5219.9  465.45  5225.4  462.52
  5234.2  461.05  5255.9  465.88  5272.8  467.25  5455.2  468.21  5571.5  471.24
  5666.2  474.93    5733  478.82  5860.9  490.94  6000.1  501.14  6169.7  505.95
#Mann= 3 , 0 , 0
  4317.3     .05       0 4864.22     .07       0 5017.16     .05       0
Bank Sta=4864.22,5017.16
XS Rating Curve= 0 ,0
Exp/Cntr=0.3,0.1

Type RM Length L Ch R = 1 ,72919   ,1387,1387,1387
BEGIN DESCRIPTION:
PLUMMERS CREEK 62.0
END DESCRIPTION:
XS GIS Cut Line= 6
      3491481.79     10585627.22      3491164.95     10584945.78
      3490431.44     10584507.42      3489541.68      10584225.3
      3489559.04       10584247.      3489368.06     10584194.91
#Sta/Elev= 30
  3649.1  480.48  3688.9  477.53    3872  478.13  4074.3   474.9  4203.4  473.77
  4239.7  474.55  4261.8  473.03    4361  470.74  4472.4  469.84  4515.2  467.62
  4683.5  467.15  4733.1  465.05  4785.6  466.64  4858.2  465.85    4881  458.81
  4902.4  461.01  4945.2  461.66  4966.6  464.63  4974.7  463.57  4982.1  460.67
  4997.5  457.65  5040.5  466.06  5091.2  467.82  5258.7  471.54  5323.2  476.56
  5489.9  484.29  5651.3  495.32  5925.8  508.79  6081.4  512.79  6415.6  515.29
#Mann= 3 ,-1 , 0
  3649.1     .05       0  4515.2     .07       0  5091.2     .05       0
Bank Sta=4858.2,5040.5
XS Rating Curve= 0 ,0
Exp/Cntr=0.3,0.1

Type RM Length L Ch R = 1 ,71532   ,1463,1463,1463
BEGIN DESCRIPTION:
PLUMMERS CREEK 60.0
END DESCRIPTION:
XS GIS Cut Line= 4
       3491894.1     10584793.86      3491581.61     10584481.37
      3491403.66     10583795.61        3490770.     10583240.07
#Sta/Elev= 30
    4208  475.89  4225.1  475.32  4295.8  476.44    4416  476.09  4486.7  474.56
  4500.9  475.23  4610.6  469.41  4671.7  466.61  4747.6  465.64  4773.6  463.22
  4828.8  464.12  4904.8  463.11  4945.3  465.11  4959.6  463.48  4980.2  462.77
  4985.9  458.04  5000.7   453.7  5011.2  456.63  5052.6  459.76  5073.2  463.74
  5124.9  462.94  5217.9  465.44  5369.6   467.4  5525.2  469.29  5780.5  479.34
  5844.1  483.89    5901  486.04  6035.8  496.11    6106  503.43  6201.1  508.55
#Mann= 5 ,-1 , 0
    4208     .05       0  4610.6      .1       0  4747.6     .07       0
  5217.9     .16       0  5369.6     .05       0
Bank Sta=4959.6,5073.2
XS Rating Curve= 0 ,0
Exp/Cntr=0.3,0.1

Type RM Length L Ch R = 1 ,70069   ,1779,1779,1779
BEGIN DESCRIPTION:
PLUMMERS CREEK 58.0
END DESCRIPTION:
XS GIS Cut Line= 3
      3492263.04     10584429.28      3492141.51       10583622.
      3491273.42     10582979.61
#Sta/Elev= 30
  4648.5  474.29  4707.1  474.34  4817.8  471.57  4828.1  472.21  4891.9  469.33
  4939.4  466.92  4949.5  465.24  4955.8  462.23  4960.9  460.82  4969.7  457.23
  4979.8  455.59  4989.9  452.65  5009.9  449.89  5013.2  450.39  5030.4  460.48
  5050.6  461.12  5101.2  459.58  5131.5  459.75  5182.1  461.99  5202.3  461.55
  5242.8  463.02  5310.7  461.95  5428.6  461.32  5581.3  462.92  5743.4  463.83
  5914.6  466.17  5973.1  467.88  6158.9  475.57  6409.3  488.85  6544.8  493.24
#Mann= 6 ,-1 , 0
  4648.5      .1       0  4707.1     .16       0  4955.8     .07       0
  5182.1     .12       0  5310.7      .1       0  5581.3     .05       0
Bank Sta=4960.9,5030.4
XS Rating Curve= 0 ,0
Exp/Cntr=0.3,0.1

Type RM Length L Ch R = 1 ,68290   ,350,350,350
BEGIN DESCRIPTION:
PLUMMERS CREEK 57.0
END DESCRIPTION:
XS GIS Cut Line= 5
      3493057.31     10583847.72      3492974.84     10583292.14
      3492710.09     10583192.31      3492380.23     10583231.37
       3491451.4     10582931.89
#Sta/Elev= 30
  4270.9   469.4  4378.1  469.42    4406  468.29  4469.1  468.08  4539.8  465.72
  4614.3  464.76  4812.5  458.26    4880  457.68  4953.1  459.33  4965.3  456.28
  4974.4  451.53  4989.9  448.33  5006.5  449.49    5015  453.45  5038.6  456.25
  5081.3  459.27  5115.5  460.13  5150.5  456.05  5155.6  457.14  5173.9  456.94
  5181.1  458.31    5194  459.44  5224.3  458.64  5288.7  459.26  5480.7  461.59
  5582.3  462.67  5985.7  470.81  6151.2  476.31  6317.8  483.91  6423.6  487.33
#Mann= 6 ,-1 , 0
  4270.9     .05       0  4953.1    .035       0  5081.3      .1       0
  5181.1     .16       0  5288.7      .1       0  5480.7     .05       0
Bank Sta=4965.3,5038.6
XS Rating Curve= 0 ,0
Exp/Cntr=0.3,0.1

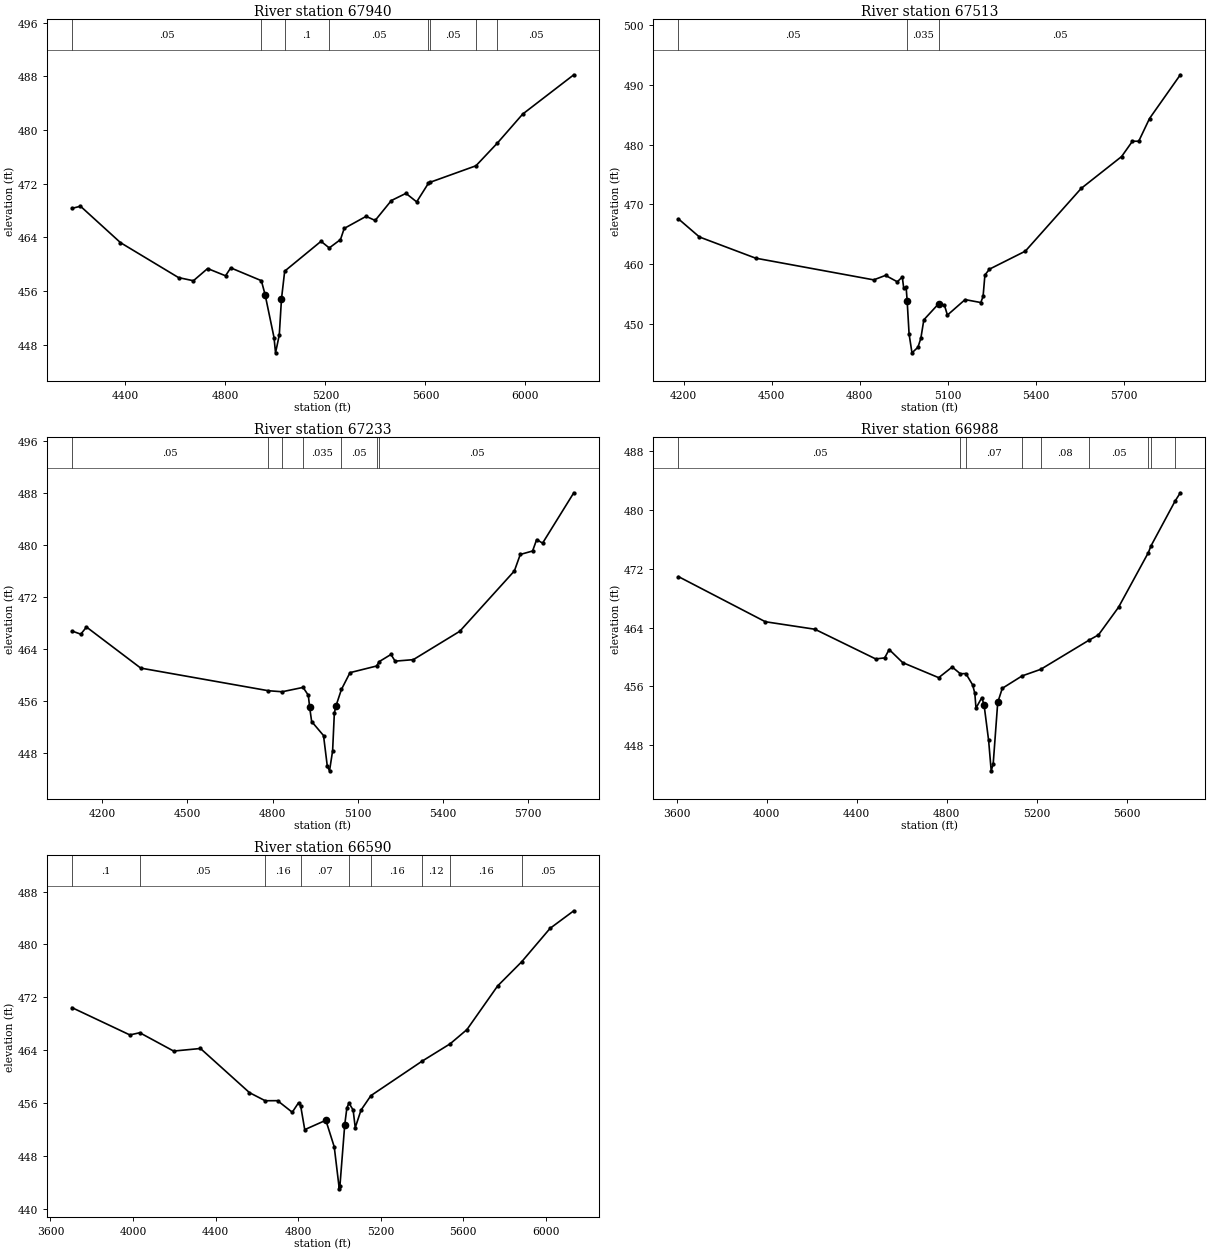
Type RM Length L Ch R = 1 ,67940   ,427,427,427
BEGIN DESCRIPTION:
PLUMMERS CREEK 56.0
END DESCRIPTION:
XS GIS Cut Line= 4
      3493074.67     10583695.81      3493083.35     10583391.96
      3492601.58     10582693.18      3492163.19     10581959.63
#Sta/Elev= 30
  4185.9  468.32  4220.1  468.64  4380.1  463.21  4612.2     458  4671.7  457.53
  4728.5  459.35  4800.2  458.27  4821.1  459.45  4943.5  457.54  4958.4  455.47
  4994.2  449.06  5000.2  446.78  5015.2  449.44    5024  454.82  5036.8  458.96
  5182.2  463.41  5215.1  462.42    5260  463.67  5274.9  465.33  5362.4  467.13
  5398.7  466.52  5463.5  469.49  5521.9  470.56  5564.7  469.29    5612  472.08
  5619.2  472.22  5801.8  474.67  5887.6  478.06  5988.8  482.38  6193.2  488.24
#Mann= 8 ,-1 , 0
  4185.9     .05       0  4943.5     .07       0  5036.8      .1       0
  5215.1     .05       0    5612      .1       0  5619.2     .05       0
  5801.8      .1       0  5887.6     .05       0
Bank Sta=4958.4,5024
XS Rating Curve= 0 ,0
Exp/Cntr=0.3,0.1

Type RM Length L Ch R = 1 ,67513   ,280,280,280
BEGIN DESCRIPTION:
PLUMMERS CREEK 55.5
END DESCRIPTION:
XS GIS Cut Line= 4
      3493278.66      10583782.6       3493217.9      10583266.1
       3493174.5     10582758.28      3492822.95     10582176.71
#Sta/Elev= 30
  4182.3  467.56  4253.7  464.54  4445.1     461  4847.3  457.37  4887.5  458.12
  4927.6  457.05  4944.6  457.85  4949.6  455.95  4957.7  456.17 4961.29  453.78
  4967.8   448.3  4977.6  445.17  4997.9   446.1  5007.9  447.62    5018  450.69
  5068.6  453.39  5088.2  453.13  5098.3  451.48  5158.5  454.07    5212  453.58
  5219.8   454.6    5226  458.18  5241.5  459.16  5363.7  462.17  5553.9  472.66
  5691.6  477.99  5728.5  480.55  5749.9  480.55  5786.7  484.35  5891.6  491.66
#Mann= 3 , 0 , 0
  4182.3     .05       0 4961.29    .035       0  5068.6     .05       0
Bank Sta=4961.29,5068.6
XS Rating Curve= 0 ,0
Exp/Cntr=0.3,0.1

Type RM Length L Ch R = 1 ,67233   ,245,245,245
BEGIN DESCRIPTION:
PLUMMERS CREEK 55.0
END DESCRIPTION:
XS GIS Cut Line= 4
      3493387.17     10583782.57      3493313.38     10583070.78
      3493413.21     10582806.03      3492936.47     10582203.59
#Sta/Elev= 30
  4093.3  466.74  4124.4  466.25  4144.5  467.35  4335.5  461.03  4784.6  457.55
  4833.3  457.39    4907  458.06  4925.5  456.85 4930.03  455.03  4937.2  452.81
    4979  450.65  4992.3  445.93  5000.1  445.22    5011   448.3  5017.1  454.12
  5022.5  455.17    5042  457.74  5072.2  460.33  5165.7  461.35  5175.5  462.04
  5216.5  463.13    5231   462.1  5295.1  462.33  5458.5  466.69  5650.9  475.98
  5671.7  478.52    5715  479.05  5729.4  480.81  5750.2  480.26  5860.1  488.01
#Mann= 7 ,-1 , 0
  4093.3     .05       0  4784.6     .16       0  4833.3     .05       0
    4907    .035       0    5042     .05       0  5165.7     .08       0
  5175.5     .05       0
Bank Sta=4930.03,5022.5
XS Rating Curve= 0 ,0
Exp/Cntr=0.3,0.1

Type RM Length L Ch R = 1 ,66988   ,398,398,398
BEGIN DESCRIPTION:
PLUMMERS CREEK 54.0
END DESCRIPTION:
XS GIS Cut Line= 4
      3493560.78     10584407.62       3493552.1     10583183.63
       3493595.5     10582905.85      3493322.77     10582234.83
#Sta/Elev= 30
  3608.7  470.94  3994.7   464.8  4214.7  463.78  4484.7  459.74  4524.7  459.88
  4544.7  461.02  4604.7  459.24  4764.7  457.19  4824.7  458.64  4860.9  457.72
  4885.3  457.75  4915.7   456.2  4925.3  455.04  4930.4  453.05  4956.2  454.47
  4966.3  453.49  4986.6  448.64    4998  444.51  5006.8  445.43    5027  453.82
  5047.3  455.74  5135.4  457.43  5217.8  458.32    5433   462.3  5474.6  463.01
  5563.7  466.77  5696.4  474.22  5707.5   475.1  5815.1  481.23  5838.2  482.35
#Mann= 9 ,-1 , 0
  3608.7     .05       0  4860.9     .16       0  4885.3     .07       0
  5135.4     .16       0  5217.8     .08       0    5433     .05       0
  5696.4     .08       0  5707.5     .05       0  5815.1      .1       0
Bank Sta=4966.3,5027
XS Rating Curve= 0 ,0
Exp/Cntr=0.3,0.1

Type RM Length L Ch R = 1 ,66590   ,1246,1246,1246
BEGIN DESCRIPTION:
PLUMMERS CREEK 53.0
END DESCRIPTION:
XS GIS Cut Line= 4
      3493799.49     10584233.93      3493764.77     10583439.71
      3493912.34     10582654.12      3493322.04     10582059.47
#Sta/Elev= 30
    3704  470.45  3984.6  466.32  4032.8  466.65  4196.8  463.88  4326.9  464.27
  4564.5  457.59  4640.6  456.37  4700.5  456.38  4771.7  454.63  4802.3  456.07
  4812.4  455.62  4832.2     452  4934.5  453.42  4975.2   449.4  4999.6  443.05
  5002.9  443.55  5026.1  452.75  5036.3  455.25  5046.5  456.03  5066.8  454.96
    5077   452.3  5104.9  454.95  5152.8  457.14  5400.8  462.35  5537.1  464.98
  5618.4  467.13  5766.9  473.72  5883.1  477.36  6021.5  482.44  6136.2  485.09
#Mann= 9 ,-1 , 0
    3704      .1       0  4032.8     .05       0  4640.6     .16       0
  4812.4     .07       0  5046.5     .12       0  5152.8     .16       0
  5400.8     .12       0  5537.1     .16       0  5883.1     .05       0
Bank Sta=4934.5,5026.1
XS Rating Curve= 0 ,0
Exp/Cntr=0.3,0.1