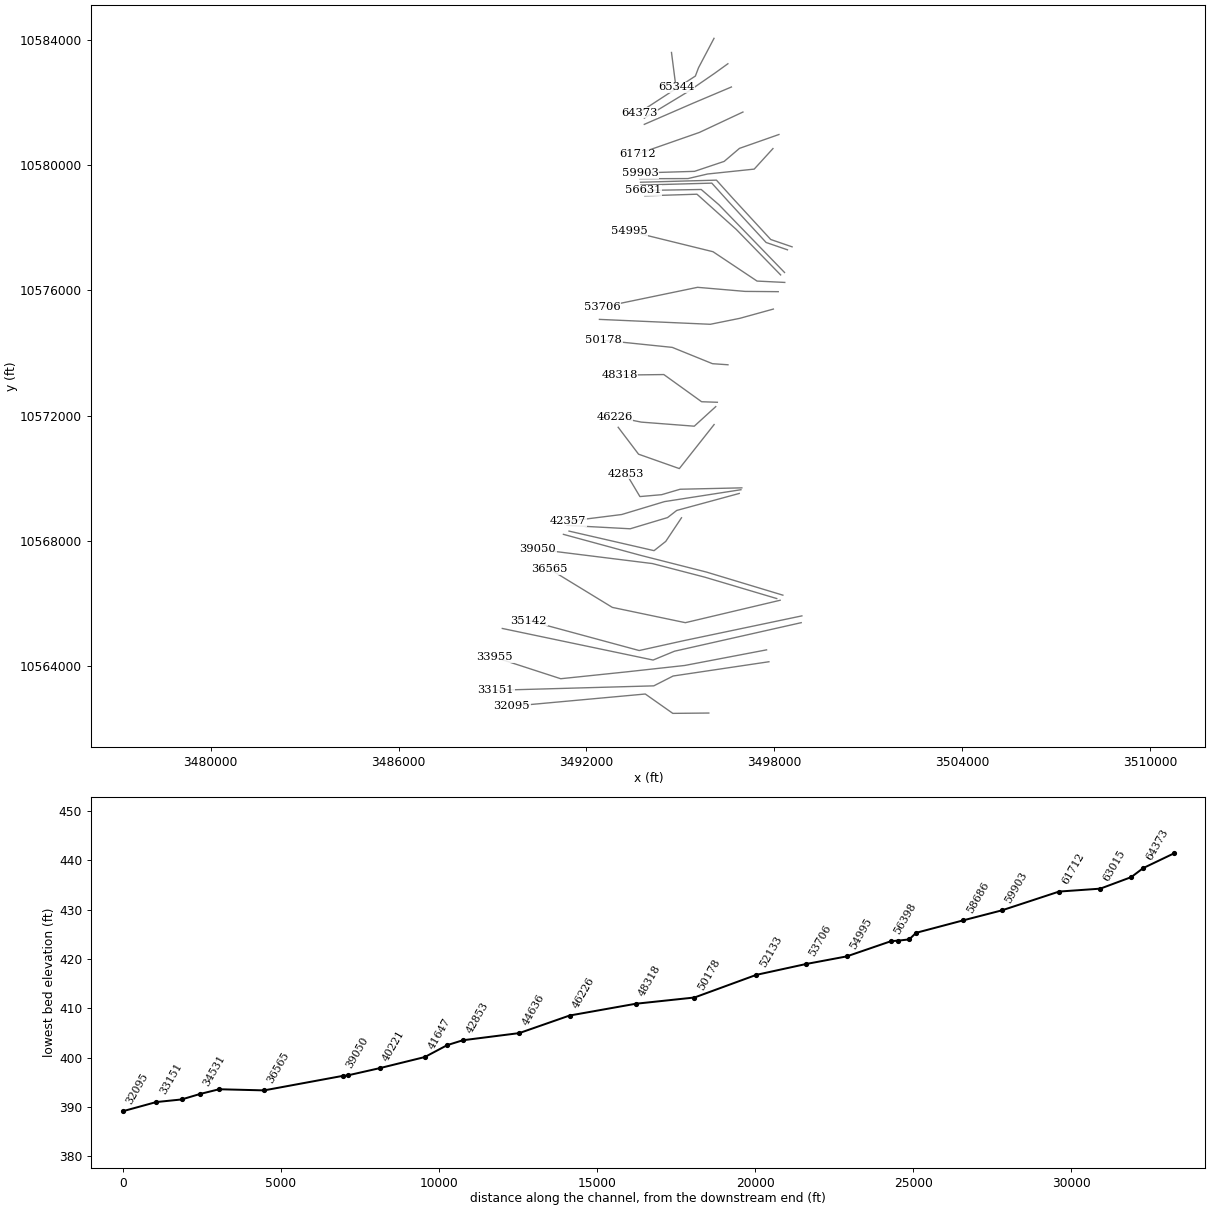
HEC-RAS study PLUMMERS CREEK.prj: PLUMMERS CREEK Base Level Engineering

--- PLUMMERS CREEK.g01 (geometry) --- (continued)

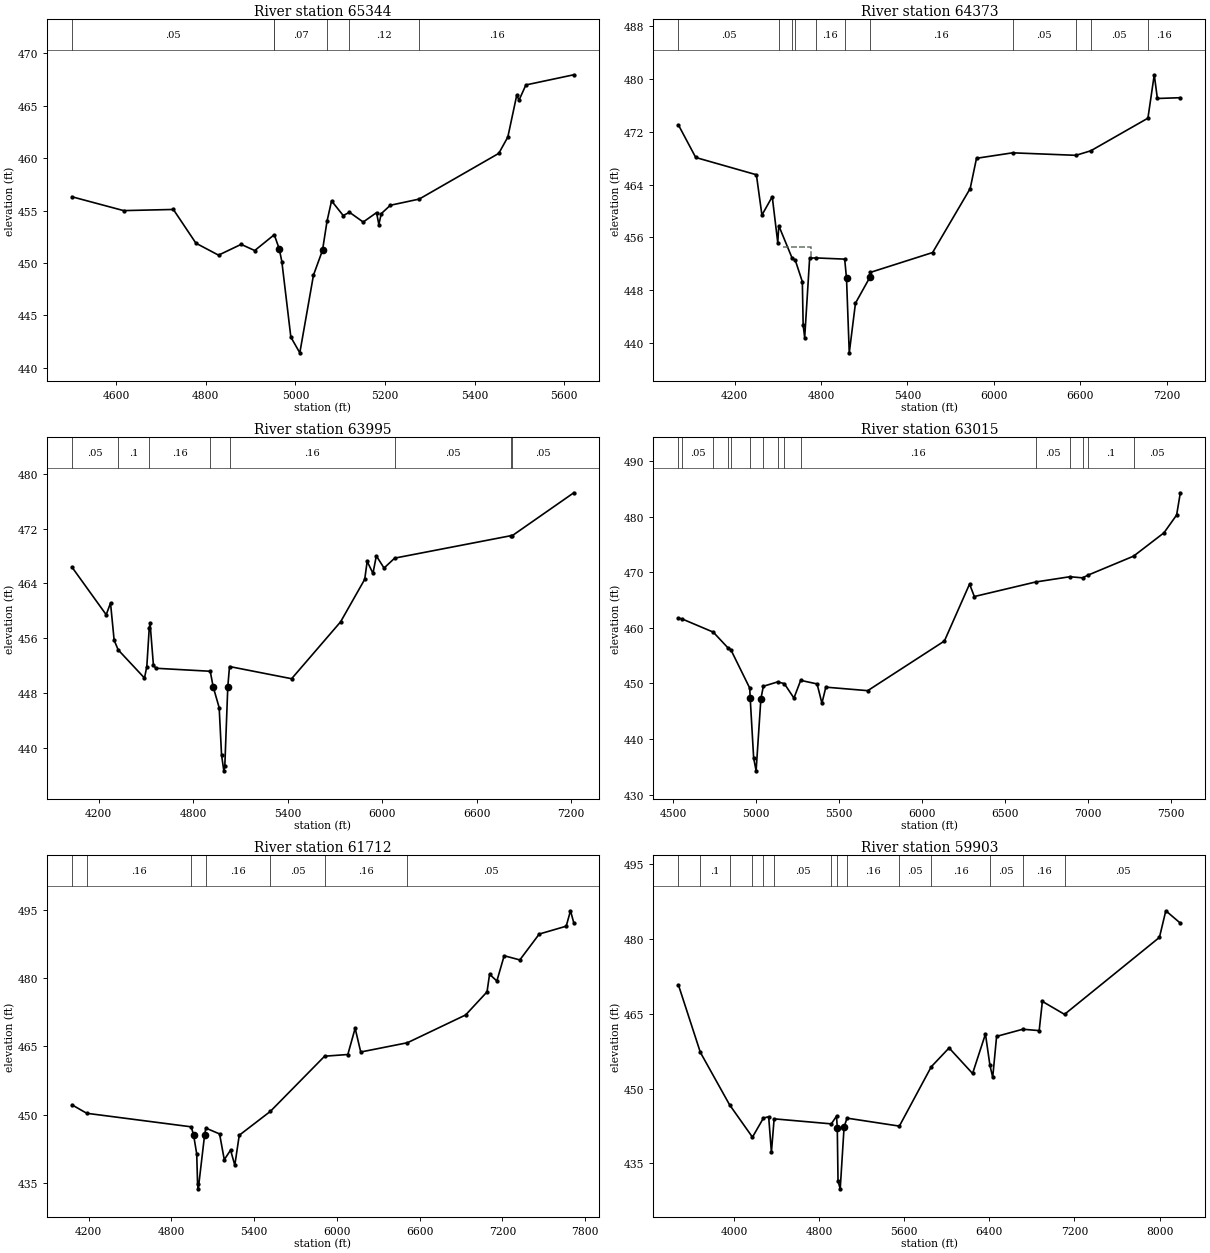
Type RM Length L Ch R = 1 ,65344   ,971,971,971
BEGIN DESCRIPTION:
PLUMMERS CREEK 52.0
END DESCRIPTION:
XS GIS Cut Line= 2
      3494719.63     10583595.97      3494862.75     10582485.76
#Sta/Elev= 30
  4501.6  456.31  4616.9  454.99  4727.8   455.1  4778.2  451.88  4828.6  450.74
    4879  451.77  4909.3  451.18  4952.9  452.69 4963.98  451.34  4969.8  450.13
  4989.9  442.92  5009.9  441.42  5040.4  448.84  5060.5   451.2  5070.6  453.98
  5080.7  455.92  5106.7  454.52  5120.7  454.83  5151.3   453.9  5181.1   454.8
  5186.2  453.66  5191.6   454.7  5211.8   455.5  5276.2  456.09  5453.7  460.45
  5473.9  462.01  5493.8     466  5498.9  465.53  5514.2  466.98    5621  467.95
#Mann= 6 ,-1 , 0
  4501.6     .05       0  4952.9     .12       0  4952.9     .07       0
  5070.6     .16       0  5120.7     .12       0  5276.2     .16       0
Bank Sta=4963.98,5060.5
XS Rating Curve= 0 ,0
Exp/Cntr=0.3,0.1

Type RM Length L Ch R = 1 ,64373   ,378,378,378
BEGIN DESCRIPTION:
PLUMMERS CREEK 51.0
END DESCRIPTION:
XS GIS Cut Line= 4
      3496078.11     10584047.64      3495583.35     10583108.52
      3495482.57     10582842.82       3493688.5     10581675.76
#Sta/Elev= 30
  3809.8  473.02  3929.6   468.1  4350.9  465.48  4389.3  459.36    4461  462.15
  4499.4  455.16  4506.5  457.74  4597.6   452.9  4621.5  452.47    4670  449.24
  4675.7  442.66  4686.4  440.74  4720.8  452.83  4766.2  452.85  4964.2  452.67
  4976.9  449.75    4996  438.44  5039.1  445.98 5138.32  449.88  5141.7  450.65
  5574.9  453.67    5836  463.39  5879.9  467.98  6130.5  468.81  6570.4  468.43
  6673.9  469.12  7070.6  474.07  7114.6  480.66  7136.3  477.06  7295.7  477.18
#Mann= 11 ,-1 , 0
  3809.8     .05       0  4506.5     .12       0  4597.6     .16       0
  4621.5     .12       0  4766.2     .16       0  4964.2     .07       0
  5141.7     .16       0  6130.5     .05       0  6570.4     .16       0
  6673.9     .05       0  7070.6     .16       0
#XS Ineff= 1 ,-1
    4534 4729.54  454.45
Permanent Ineff=
       F
Bank Sta=4976.9,5138.32
XS Rating Curve= 0 ,0
Exp/Cntr=0.3,0.1

Type RM Length L Ch R = 1 ,63995   ,980,980,980
BEGIN DESCRIPTION:
PLUMMERS CREEK 50.0
END DESCRIPTION:
XS GIS Cut Line= 4
      3496520.89     10583235.74      3496086.82     10582923.21
      3495236.13     10582337.28      3493851.55     10581499.58
#Sta/Elev= 30
  4030.8  466.38  4248.3  459.42  4275.7  461.13  4298.7  455.69  4324.3  454.29
  4491.4  450.17  4506.1  451.84  4521.7  457.53    4527  458.14  4547.8  452.12
  4562.6   451.6  4908.8  451.16 4927.52  448.88  4965.6  445.84  4980.5  438.97
  4995.1  436.61  5001.4  437.34 5020.26  448.88  5031.2  451.85  5425.5  450.07
  5736.4  458.38  5889.7   464.6  5905.2  467.22    5942  465.47  5963.4  468.02
  6012.4  466.24  6079.7  467.69  6817.9  470.97  6822.4  470.91  7216.9  477.24
#Mann= 8 ,-1 , 0
  4030.8     .05       0  4324.3      .1       0  4521.7     .16       0
  4908.8     .07       0  5031.2     .16       0  6079.7     .05       0
  6817.9      .1       0  6822.4     .05       0
#XS Ineff= 2 , 0
       0 4513.07  453.03               0
Permanent Ineff=
       T       F
Bank Sta=4927.52,5020.26
XS Rating Curve= 0 ,0
Exp/Cntr=0.3,0.1

Type RM Length L Ch R = 1 ,63015   ,1303,1303,1303
BEGIN DESCRIPTION:
PLUMMERS CREEK 49.5
END DESCRIPTION:
XS GIS Cut Line= 3
      3496633.66     10582493.51      3495431.44     10581985.71
      3493851.61     10581299.96
#Sta/Elev= 30
  4530.3  461.74  4553.5  461.57  4739.9  459.22  4831.7  456.29  4845.5  456.09
    4960  449.15 4962.88  447.33  4983.7  436.58  4998.5  434.27 5027.35  447.24
  5042.2  449.48  5128.1  450.26  5168.5  449.96  5226.7  447.36  5267.4  450.54
  5366.4   449.9  5395.5  446.43  5419.2  449.32  5671.8  448.69  6134.4  457.62
  6286.1  467.86    6315  465.62    6684  468.23  6891.2  469.18  6968.1  468.98
  6999.3  469.45  7275.4  472.88  7458.9  477.08  7535.3  480.28  7557.6  484.28
#Mann= 15 ,-1 , 0
  4530.3      .1       0  4553.5     .05       0  4739.9     .16       0
  4831.7     .05       0  4845.5     .12       0    4960     .07       0
  5042.2     .12       0  5128.1     .16       0  5168.5     .12       0
  5267.4     .16       0    6684     .05       0  6891.2      .1       0
  6968.1     .05       0  6999.3      .1       0  7275.4     .05       0
Bank Sta=4962.88,5027.35
XS Rating Curve= 0 ,0
Exp/Cntr=0.3,0.1

Type RM Length L Ch R = 1 ,61712   ,1809,1809,1809
BEGIN DESCRIPTION:
PLUMMERS CREEK 49.0
END DESCRIPTION:
XS GIS Cut Line= 3
      3497001.19     10581693.47      3495612.29     10581042.43
      3493625.74     10580348.44
#Sta/Elev= 30
  4078.6  452.16    4186   450.3  4943.7  447.32    4961  445.42  4983.2  441.36
  4989.4  434.73  4994.6  433.68  5040.5  445.57  5049.5  447.04  5148.9  445.76
    5183  440.09  5228.7   442.2  5259.3  438.88  5291.6  445.47  5516.7  450.71
  5910.5  462.86  6078.8  463.23  6131.7     469  6172.3  463.78  6510.7  465.82
  6932.7  471.93  7087.9  477.01  7106.3  480.88  7159.2   479.4  7212.2  484.96
  7325.7  484.04  7466.4  489.73    7662  491.46    7693  494.85  7716.8  492.22
#Mann= 7 ,-1 , 0
  4078.6     .05       0    4186     .16       0  4943.7     .07       0
  5049.5     .16       0  5516.7     .05       0  5910.5     .16       0
  6510.7     .05       0
Bank Sta=4961,5040.5
XS Rating Curve= 0 ,0
Exp/Cntr=0.3,0.1

Type RM Length L Ch R = 1 ,59903   ,1217,1217,1217
BEGIN DESCRIPTION:
PLUMMERS CREEK 48.0
END DESCRIPTION:
XS GIS Cut Line= 5
      3498151.87     10580975.83      3496891.42     10580533.11
      3496401.84     10580116.44      3495453.92     10579798.73
      3493715.77     10579746.69
#Sta/Elev= 30
  3478.1  470.75  3683.6  457.26  3958.2  446.74  4173.3  440.24  4276.7  444.08
  4325.8  444.34  4351.5  437.21  4377.1  443.92  4914.9  442.91  4963.5  444.46
  4970.7  442.17  4977.8  431.42  4998.4  429.87  5034.9  442.32  5062.6  444.06
  5554.3  442.46  5854.5  454.38  6021.8  458.15  6242.7  453.02  6363.6  460.94
  6406.1  454.63    6432  452.26  6468.5  460.47  6714.1   461.9  6868.7  461.63
  6898.7  467.49  7106.9  464.89  7999.2  480.34  8059.2  485.68  8195.6   483.2
#Mann= 14 ,-1 , 0
  3478.1     .05       0  3683.6      .1       0  3958.2     .05       0
  4173.3     .12       0  4276.7     .16       0  4377.1     .05       0
  4914.9     .12       0  4963.5     .07       0  5062.6     .16       0
  5554.3     .05       0  5854.5     .16       0  6406.1     .05       0
  6714.1     .16       0  7106.9     .05       0
Bank Sta=4970.7,5034.9
XS Rating Curve= 0 ,0
Exp/Cntr=0.3,0.1

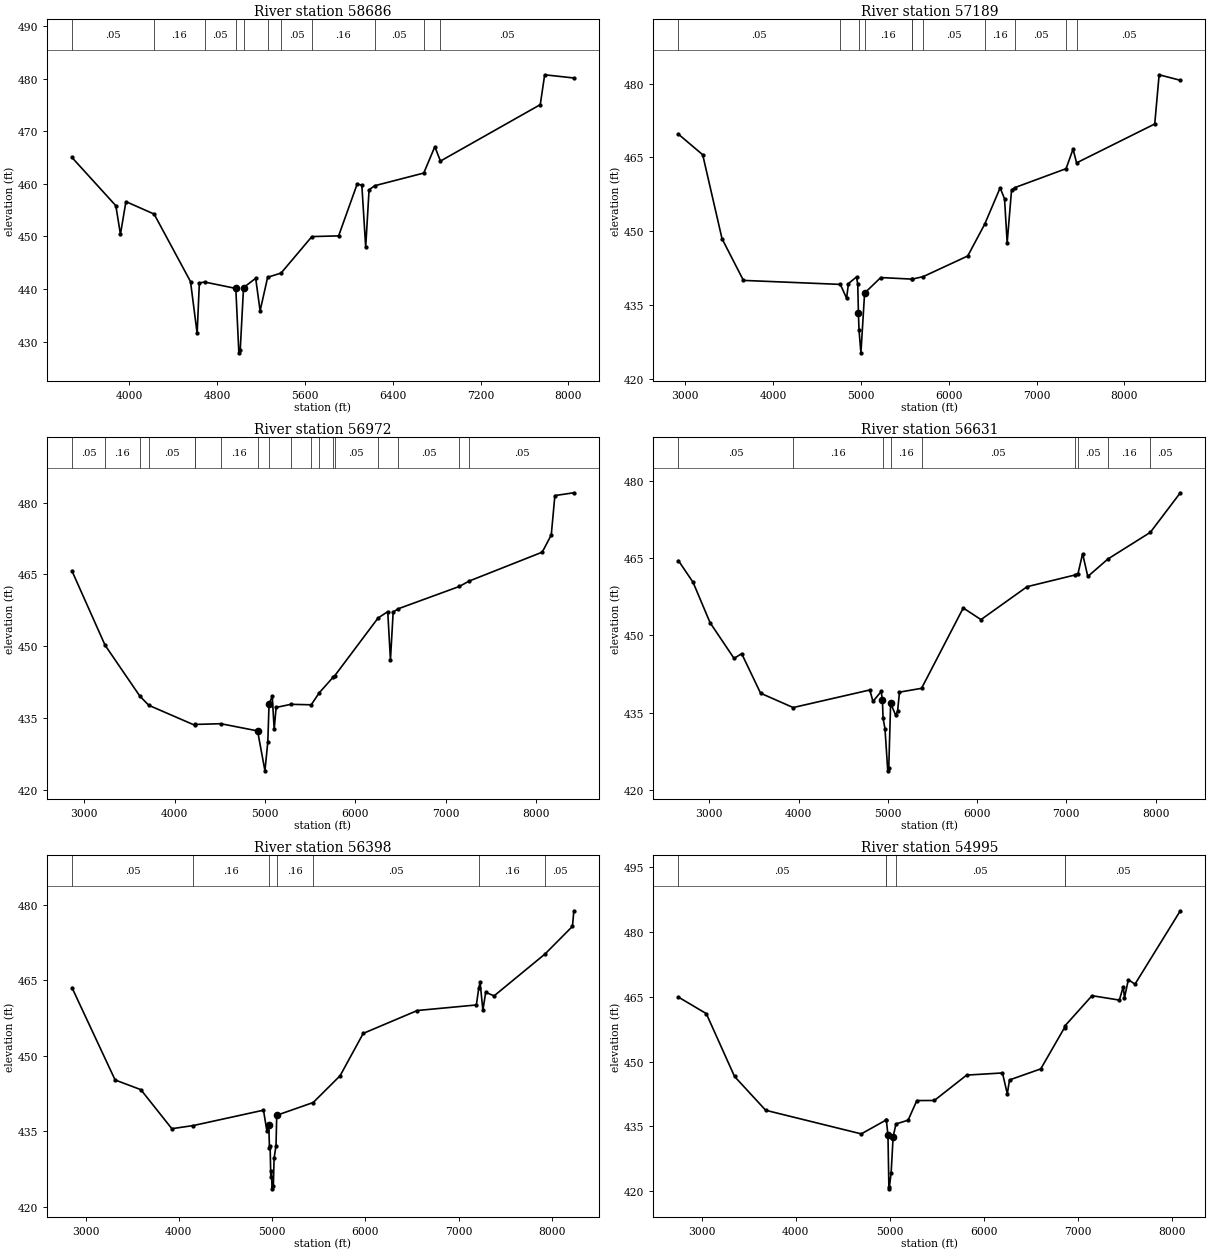
Type RM Length L Ch R = 1 ,58686   ,1497,1497,1497
BEGIN DESCRIPTION:
PLUMMERS CREEK 47.0
END DESCRIPTION:
XS GIS Cut Line= 5
      3497960.86      10580526.8      3497361.88     10579870.52
      3495872.29     10579714.27      3495247.29     10579568.43
      3493706.38     10579563.23
#Sta/Elev= 30
  3480.4  465.01  3879.9  455.83  3921.8   450.4  3971.8  456.61  4228.4  454.24
  4559.7   441.4  4620.1  431.54  4640.2  441.13  4687.1  441.32    4972   440.1
  4999.8  427.85  5012.2  428.35  5042.4  440.26    5153  442.02  5193.2  435.85
  5261.9  442.22  5384.3  443.02  5664.6  449.96    5908  450.09  6076.8  459.95
  6119.4  459.74  6154.4  447.94  6185.2  458.85  6235.9  459.63  6683.1  462.04
  6783.7  467.05    6835  464.32  7743.7  475.05  7783.7  480.73  8049.4  480.12
#Mann= 11 ,-1 , 0
  3480.4     .05       0  4228.4     .16       0  4687.1     .05       0
    4972     .07       0  5042.4     .16       0  5261.9      .1       0
  5384.3     .05       0  5664.6     .16       0  6235.9     .05       0
  6683.1     .16       0    6835     .05       0
Bank Sta=4972,5042.4
XS Rating Curve= 0 ,0
Exp/Cntr=0.3,0.1

Type RM Length L Ch R = 1 ,57189   ,217,217,217
BEGIN DESCRIPTION:
PLUMMERS CREEK 46.3
END DESCRIPTION:
XS GIS Cut Line= 5
      3498571.91     10577387.89      3497889.65     10577622.25
      3496681.32     10578934.75      3496155.28     10579518.09
       3493730.8     10579451.25
#Sta/Elev= 30
  2921.2  469.72  3197.8  465.54    3418  448.48  3661.6  440.02  4765.1  439.21
  4836.7   436.4  4857.7  439.38  4949.5  440.72  4963.7  439.24  4971.1  433.49
  4977.9  429.99  4999.8  425.31  5041.8  437.45  5225.7   440.6  5583.6  440.28
  5586.8  440.29  5709.4  440.79  6216.2  444.98  6409.4  451.43  6585.4  458.82
  6635.4  456.59  6665.4  447.68  6715.5  458.41  6751.6  458.86  7336.2  462.71
  7415.7  466.68  7456.1  463.89  8346.1  471.79  8396.1  481.78  8637.5  480.66
#Mann= 11 ,-1 , 0
  2921.2     .05       0  4765.1     .16       0  4977.9     .07       0
  5041.8     .16       0  5583.6     .05       0  5586.8     .16       0
  5709.4     .05       0  6409.4     .16       0  6751.6     .05       0
  7336.2     .16       0  7456.1     .05       0
Bank Sta=4971.1,5041.8
XS Rating Curve= 0 ,0
Exp/Cntr=0.3,0.1

Type RM Length L Ch R = 1 ,56972   ,341,341,341
BEGIN DESCRIPTION:
PLUMMERS CREEK 46.0
END DESCRIPTION:
XS GIS Cut Line= 5
      3498424.42     10577292.38      3497742.09     10577526.77
      3496533.75     10578839.27      3496007.71      10579422.6
      3493742.05      10579360.1
#Sta/Elev= 30
  2862.8  465.73    3229  450.23  3614.1   439.6  3713.1  437.67  4224.6  433.49
  4227.6  433.67  4511.1  433.82  4918.3  432.32  4999.8  423.98  5031.7  430.08
  5045.3  437.99    5081  439.54    5102  432.62  5123.6  437.22  5287.6  437.87
  5512.6  437.77    5601  440.28  5755.5  443.54  5771.3   443.8  6252.3  455.89
  6359.5  457.22  6389.5  447.13  6419.5  457.12  6473.1   457.8  7152.2  462.48
  7260.1   463.6  8070.1  469.64  8170.2  473.23  8210.2  481.46  8420.3  482.04
#Mann= 18 ,-1 , 0
  2862.8     .05       0    3229     .16       0  3614.1     .12       0
  3713.1     .05       0  4224.6     .12       0  4227.6     .05       0
  4511.1     .16       0  4918.3     .07       0  5045.3     .16       0
  5287.6     .12       0  5512.6     .16       0    5601     .12       0
  5755.5     .16       0  5771.3     .05       0  6252.3     .16       0
  6473.1     .05       0  7152.2     .16       0  7260.1     .05       0
Bank Sta=4918.3,5045.3
XS Rating Curve= 0 ,0
Exp/Cntr=0.3,0.1

Type RM Length L Ch R = 1 ,56631   ,233,233,233
BEGIN DESCRIPTION:
PLUMMERS CREEK 42.0
END DESCRIPTION:
XS GIS Cut Line= 4
      3498330.66      10576568.4      3496231.67      10578735.1
      3495669.17     10579219.48      3493805.81     10579188.25
#Sta/Elev= 30
  2654.6  464.52  2818.5  460.32  3009.4  452.47  3278.2  445.54  3363.1  446.47
  3575.3  438.79  3940.2  436.01  4798.7  439.42    4834  437.19    4926  439.13
  4940.2  437.44  4947.1  433.92  4968.5  431.94  4999.8  423.73  5010.9  424.23
    5032  436.85  5088.6  434.52  5109.7  435.26  5131.1     439  5378.4  439.74
  5845.5  455.33  6044.1  453.07  6560.7  459.46  7097.5  461.73    7131  462.01
  7182.6  465.86  7240.8  461.44  7467.7  464.85  7941.2     470  8277.2  477.68
#Mann= 9 ,-1 , 0
  2654.6     .05       0  3940.2     .16       0  4947.1     .07       0
    5032     .16       0  5378.4     .05       0  7097.5     .16       0
    7131     .05       0  7467.7     .16       0  7941.2     .05       0
Bank Sta=4940.2,5032
XS Rating Curve= 0 ,0
Exp/Cntr=0.3,0.1

Type RM Length L Ch R = 1 ,56398   ,1403,1403,1403
BEGIN DESCRIPTION:
PLUMMERS CREEK 42.1
END DESCRIPTION:
XS GIS Cut Line= 5
      3498205.61     10576490.32      3496788.96     10577943.43
      3496434.79     10578261.14      3495533.75     10579068.43
      3493867.14     10579016.35
#Sta/Elev= 30
  2853.6  463.53  3316.6  445.21  3592.5  443.29  3924.8  435.55  4154.1  436.17
  4907.6  439.22  4943.5  435.16  4964.4  436.23  4971.9  431.72  4978.6  432.11
  4986.1  425.95  4992.8  427.14  4999.8  423.62  5013.7  424.27  5021.2  429.65
  5042.1   432.2  5049.6  438.21  5440.8  440.74  5729.2  446.05  5977.4  454.45
  6557.5  458.99  7190.5  460.09  7216.7  463.51  7230.5  464.57  7260.6  459.04
  7290.6  462.61  7380.6  461.89  7928.1  470.22    8221  475.68    8236  478.77
#Mann= 7 ,-1 , 0
  2853.6     .05       0  4154.1     .16       0  4964.4     .07       0
  5049.6     .16       0  5440.8     .05       0  7216.7     .16       0
  7928.1     .05       0
Bank Sta=4964.4,5049.6
XS Rating Curve= 0 ,0
Exp/Cntr=0.3,0.1

Type RM Length L Ch R = 1 ,54995   ,1289,1289,1289
BEGIN DESCRIPTION:
PLUMMERS CREEK 41.0
END DESCRIPTION:
XS GIS Cut Line= 4
      3498338.02     10576250.76      3497452.56     10576294.16
      3496046.31     10577231.66      3493365.53     10577891.01
#Sta/Elev= 30
  2754.5  464.95  3050.8  461.13  3351.1  446.57  3682.6  438.73  4699.2  433.26
  4959.6  436.44  4965.6  436.45 4982.83  432.98  4992.6  421.03  4995.4  420.53
  5016.6  424.22  5037.7  432.55  5067.7  435.56  5196.9  436.43  5290.1  440.98
    5476     441  5819.5  446.88  6200.5  447.38    6252  442.53  6275.4  445.76
  6607.7  448.32  6860.4  457.88  6867.1  458.34  7152.7  465.28  7443.4  464.26
    7485  467.36    7498  464.78  7539.2     469  7609.5  467.94  8091.8  484.95
#Mann= 6 ,-1 , 0
  2754.5     .05       0  4959.6     .16       0  4965.6     .07       0
  5067.7     .05       0  6860.4     .08       0  6867.1     .05       0
Bank Sta=4982.83,5037.7
XS Rating Curve= 0 ,0
Exp/Cntr=0.3,0.1

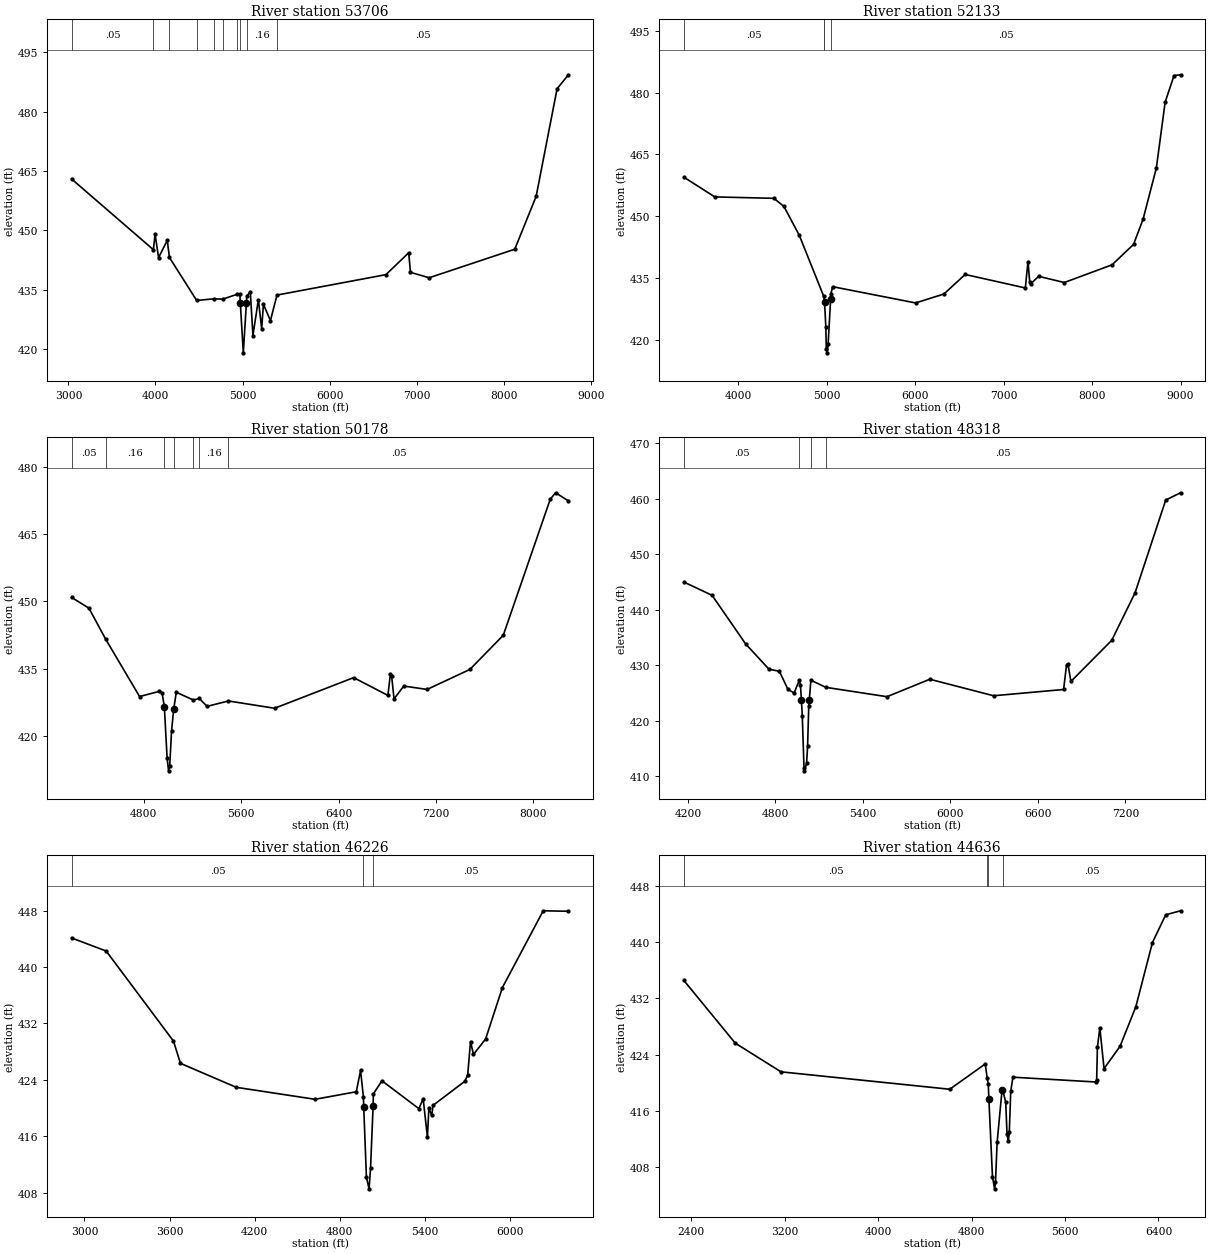
Type RM Length L Ch R = 1 ,53706   ,1573,1573,1573
BEGIN DESCRIPTION:
PLUMMERS CREEK 38.0
END DESCRIPTION:
XS GIS Cut Line= 4
      3498129.67     10575955.62      3497070.62      10575964.3
      3495551.52     10576094.51      3492496.58     10575460.96
#Sta/Elev= 30
  3037.6  462.96  3975.9  445.08  3995.2  449.02  4035.2  443.07  4135.3  447.45
  4159.9  443.12  4473.1  432.23  4672.3  432.66  4771.9  432.57  4940.3  433.82
  4968.4  433.93 4973.69  431.65  5008.3  418.98 5043.85  431.65  5048.7  433.33
  5088.8  434.44  5118.9  423.36  5181.1  432.43  5219.3  425.12  5239.4  431.27
  5319.7  427.13    5395   433.6  6646.1  438.77  6907.6  444.31    6928  439.35
  7142.5  437.98  8125.2   445.2  8370.8  458.56  8611.4  485.81  8741.3  489.35
#Mann= 10 ,-1 , 0
  3037.6     .05       0  3975.9     .16       0  4159.9     .05       0
  4473.1     .16       0  4672.3     .12       0  4771.9     .16       0
  4940.3     .12       0  4968.4     .07       0  5048.7     .16       0
    5395     .05       0
Bank Sta=4973.69,5043.85
XS Rating Curve= 0 ,0
Exp/Cntr=0.3,0.1

Type RM Length L Ch R = 1 ,52133   ,1955,1955,1955
BEGIN DESCRIPTION:
PLUMMERS CREEK 36.0
END DESCRIPTION:
XS GIS Cut Line= 4
      3497973.37     10575400.06      3496905.69     10575104.93
      3495959.51     10574913.95      3492417.84      10575070.2
#Sta/Elev= 30
  3382.3  459.48  3732.1  454.68  4400.4  454.34  4514.1  452.36  4688.1  445.33
    4963  430.58  4973.2  429.25  4987.6  423.15  4993.6  417.67  5003.5  416.78
    5014  418.93  5042.3  429.93  5044.6   431.1    5065  432.86  6003.2  428.91
  6323.5  431.08  6563.8  435.83  7244.4  432.55  7274.5  438.96  7294.5  433.92
  7304.5  433.52  7394.6  435.38  7684.9  433.87  8225.4  438.18  8468.2  443.13
  8575.7  449.23  8725.9  461.66    8826  477.72  8926.1  484.18  9000.4  484.37
#Mann= 4 ,-1 , 0
  3382.3     .05       0    4963     .16       0    4963     .07       0
  5044.6     .05       0
Bank Sta=4973.2,5042.3
XS Rating Curve= 0 ,0
Exp/Cntr=0.3,0.1

Type RM Length L Ch R = 1 ,50178   ,1860,1860,1860
BEGIN DESCRIPTION:
PLUMMERS CREEK 34.0
END DESCRIPTION:
XS GIS Cut Line= 4
      3496523.78     10573620.55      3496028.95     10573655.27
      3494744.23     10574176.11      3492556.97     10574401.78
#Sta/Elev= 30
  4207.4   450.9  4349.4   448.5  4486.8  441.57  4765.2  428.78  4926.6  429.93
  4950.1  429.64  4968.8  426.43  4991.4  415.05  5003.5  412.19    5013  413.36
  5027.8  421.03  5045.3  425.94  5066.9  429.73    5208  427.99  5255.2  428.36
  5319.9  426.58    5495  427.79  5874.5  426.16  6524.1     433  6805.6  429.03
  6825.7  433.74  6835.8  433.46  6855.9  428.26  6936.3  431.12  7127.3  430.36
  7479.2  434.83  7753.5  442.45  8139.4  472.82  8182.9  474.27  8288.6  472.47
#Mann= 7 ,-1 , 0
  4207.4     .05       0  4486.8     .16       0  4968.8     .07       0
  5045.3     .16       0    5208     .12       0  5255.2     .16       0
    5495     .05       0
#XS Ineff= 2 , 0
       0                 5066.63       0  429.51
Permanent Ineff=
       F       T
Bank Sta=4968.8,5045.3
XS Rating Curve= 0 ,0
Exp/Cntr=0.3,0.1

Type RM Length L Ch R = 1 ,48318   ,2092,2092,2092
BEGIN DESCRIPTION:
PLUMMERS CREEK 32.0
END DESCRIPTION:
XS GIS Cut Line= 4
       3496185.2     10572422.64      3495681.73       10572440.
      3494475.13     10573308.05      3493060.21     10573290.69
#Sta/Elev= 30
  4172.7  444.99  4365.9   442.6    4596  433.83  4756.2  429.26  4827.4  428.89
  4885.4  425.66  4928.1  424.96  4963.7  427.26  4971.7   426.5  4978.4  423.72
  4984.5  420.81  4996.3  411.42    4999  410.92    5014  412.25  5020.9  415.41
  5028.7  422.59 5032.73  423.78  5043.4  427.27  5145.4  425.99  5565.1   424.3
  5858.6  427.45  6295.9  424.47  6775.9   425.6  6795.9  429.99  6805.9   430.2
    6826  427.05    7106  434.48    7266  443.05    7476  459.79  7577.9   461.1
#Mann= 4 ,-1 , 0
  4172.7     .05       0  4963.7     .07       0  5043.4     .16       0
  5145.4     .05       0
Bank Sta=4978.4,5032.73
XS Rating Curve= 0 ,0
Exp/Cntr=0.3,0.1

Type RM Length L Ch R = 1 ,46226   ,1590,1590,1590
BEGIN DESCRIPTION:
PLUMMERS CREEK 31.1
END DESCRIPTION:
XS GIS Cut Line= 4
       3496133.1     10572283.73      3495447.35     10571658.75
      3493754.65     10571788.95      3492896.21     10571962.38
#Sta/Elev= 30
  2909.9  444.11    3153  442.26  3627.3  429.49  3676.6  426.33  4069.9  422.93
  4625.3  421.23  4916.1   422.3  4946.2  425.32  4966.3  421.57  4968.4  420.15
  4987.6  410.14  5006.2  408.53  5016.4  411.42 5034.54  420.23  5036.5     422
  5096.7  423.86  5357.4   419.9  5387.5  421.32  5417.6  415.84  5427.6  419.98
  5447.7  418.95  5457.7  420.38  5680.8  423.78  5701.3  424.66  5721.2  429.42
  5742.1  427.59  5827.8  429.79  5946.1  437.08  6233.8  447.97  6411.2   447.9
#Mann= 3 ,-1 , 0
  2909.9     .05       0  4966.3    .035       0  5036.5     .05       0
Bank Sta=4968.4,5034.54
XS Rating Curve= 0 ,0
Exp/Cntr=0.3,0.1

Type RM Length L Ch R = 1 ,44636   ,1783,1783,1783
BEGIN DESCRIPTION:
PLUMMERS CREEK 31.0
END DESCRIPTION:
XS GIS Cut Line= 4
      3496081.06     10571710.86      3494969.92     10570304.58
      3493667.84     10570764.65      3493016.97      10571623.8
#Sta/Elev= 30
  2338.2  434.53  2778.5  425.63  3169.6  421.57  4613.8   419.1  4917.7  422.69
  4933.6  420.73  4943.3  419.89  4948.6  417.71  4979.5  406.65  4997.6  404.97
  5005.1  405.88  5019.1  411.56  5061.5  419.03    5067  418.99  5092.6  417.26
  5103.9  412.76  5114.5  411.69  5123.5  413.03  5135.7  418.81  5154.4  420.81
  5862.8  420.13  5871.1  420.45  5877.4  425.03  5898.2  427.84  5934.2  422.03
  6070.8  425.18  6206.1  430.79  6348.2   439.9    6462  443.85  6589.3  444.42
#Mann= 4 ,-1 , 0
  2338.2     .05       0  4933.6     .16       0  4943.3     .16       0
    5067     .05       0
Bank Sta=4948.6,5061.5
XS Rating Curve= 0 ,0
Exp/Cntr=0.3,0.1

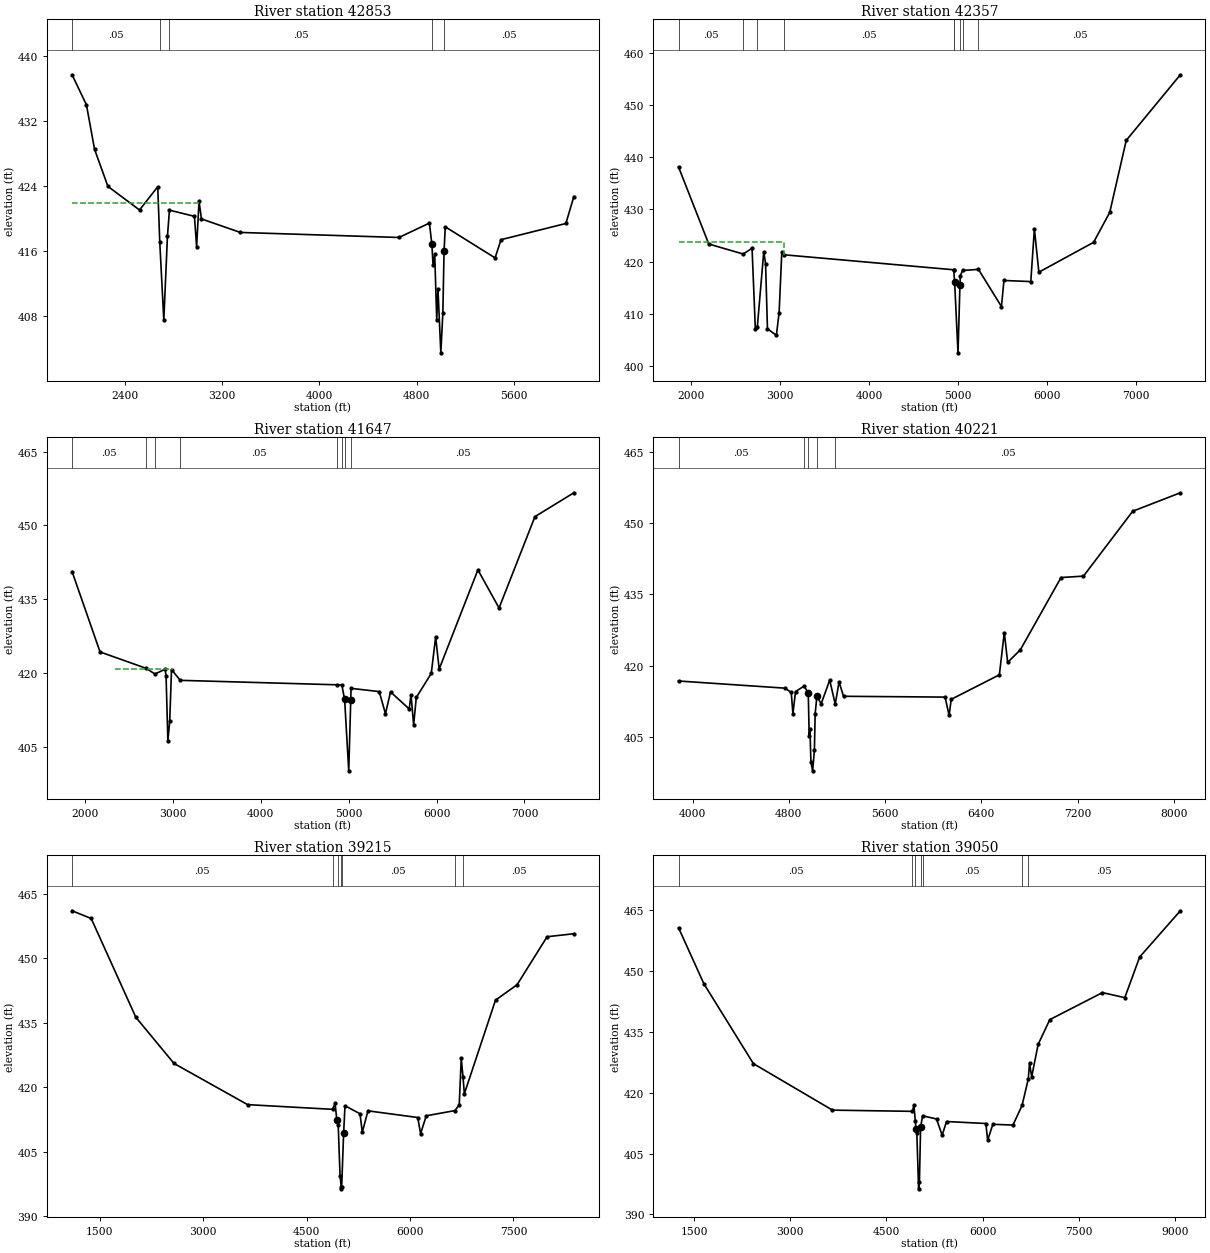
Type RM Length L Ch R = 1 ,42853   ,496,496,496
BEGIN DESCRIPTION:
PLUMMERS CREEK 30.0
END DESCRIPTION:
XS GIS Cut Line= 5
      3496967.13     10569689.27      3494995.97     10569644.86
      3494405.69     10569471.25      3493711.24     10569410.48
      3493278.09     10570138.18
#Sta/Elev= 30
  1964.1   437.7  2082.4  434.01  2149.2  428.54  2259.2  423.98  2519.3  421.08
  2669.3  423.93  2686.1  417.12  2719.3  407.54  2749.3  417.86  2765.8  421.06
  2971.5   420.3  2989.4  416.56  3009.4  422.15  3029.4  419.98  3349.5  418.32
    4655   417.7    4906  419.47  4926.1  416.84  4936.1  414.26  4949.6  415.61
  4966.2  407.55  4976.2   411.4  4999.8  403.52  5016.4  408.37  5026.4  416.02
  5036.5  419.01  5446.6  415.19  5495.3  417.43  6029.2  419.42    6095  422.73
#Mann= 5 ,-1 , 0
  1964.1     .05       0  2686.1     .16       0  2765.8     .05       0
  4926.1    .035       0  5026.4     .05       0
#XS Ineff= 2 , 0
         3011.36     422
Permanent Ineff=
       F       F
Bank Sta=4926.1,5026.4
XS Rating Curve= 0 ,0
Exp/Cntr=0.3,0.1

Type RM Length L Ch R = 1 ,42357   ,710,710,710
BEGIN DESCRIPTION:
PLUMMERS CREEK 29.2
END DESCRIPTION:
XS GIS Cut Line= 4
      3496937.98     10569629.58      3494496.57      10569249.8
      3493129.38     10568837.48      3491405.64     10568620.65
#Sta/Elev= 30
  1858.2   438.1  2197.8  423.36  2584.7  421.44  2683.9  422.55  2721.2  407.04
  2742.8  407.41  2815.4  421.87  2835.7  419.62  2857.1  407.14  2957.1  405.88
  2987.9  410.21  3017.9  421.75  3041.2   421.3    4947  418.43  4949.9  418.32
 4959.39  416.02  4997.2  402.53 5018.96  415.53    5023   417.3  5049.1  418.29
  5226.7  418.51  5485.3  411.39  5513.1  416.38  5814.7  416.17    5855  426.24
  5905.4  417.97  6520.2  423.68  6701.6  429.42  6886.8  443.19  7494.3  455.75
#Mann= 9 ,-1 , 0
  1858.2     .05       0  2584.7     .16       0  2742.8     .12       0
  3041.2     .05       0    4947     .12       0  4949.9     .07       0
    5023     .12       0  5049.1     .16       0  5226.7     .05       0
#XS Ineff= 1 ,-1
 1175.69 3039.99 423.667
Permanent Ineff=
       F
Bank Sta=4959.39,5018.96
XS Rating Curve= 0 ,0
Exp/Cntr=0.3,0.1

Type RM Length L Ch R = 1 ,41647   ,1426,1426,1426
BEGIN DESCRIPTION:
PLUMMERS CREEK 29.1
END DESCRIPTION:
XS GIS Cut Line= 5
      3496883.76     10569510.23       3494887.2     10568967.69
      3494594.23     10568739.82      3493400.65     10568381.75
      3491382.42     10568490.26
#Sta/Elev= 30
  1854.2  440.62  2172.5  424.28  2695.4  420.96  2796.8   419.8  2912.9  420.77
  2923.3  419.38    2944  406.22  2964.7  410.15  2985.4   420.7  3084.4  418.51
  4870.8   417.6    4923  417.53  4954.3  414.62  5001.1  400.11  5024.1   414.6
  5027.4  416.88  5347.6  416.22  5418.9  411.71  5476.3  416.16  5689.2  412.69
  5709.2  415.59  5739.3  409.47  5769.3  415.02  5939.6  419.91  5989.6  427.32
  6029.7   420.8  6470.3  440.97  6710.7  433.21    7119  451.79  7561.6  456.64
#Mann= 8 ,-1 , 0
  1854.2     .05       0  2695.4     .12       0  2796.8     .16       0
  3084.4     .05       0  4870.8     .12       0    4923     .05       0
  4954.3    .035       0  5027.4     .05       0
#XS Ineff= 1 ,-1
 2343.39 2988.05  420.75
Permanent Ineff=
       F
Bank Sta=4954.3,5024.1
XS Rating Curve= 0 ,0
Exp/Cntr=0.3,0.1

Type RM Length L Ch R = 1 ,40221   ,1006,1006,1006
BEGIN DESCRIPTION:
PLUMMERS CREEK 29.0
END DESCRIPTION:
XS GIS Cut Line= 4
      3495039.35     10568733.37       3494535.9     10567978.19
      3494162.63     10567683.05      3491446.33     10568307.89
#Sta/Elev= 30
  3883.7  416.78  4770.1  415.27  4820.7  414.36  4834.4  409.86  4855.9  414.55
  4927.4  415.71  4961.9  414.28  4969.7  405.19  4976.1  406.57  4984.1  399.71
  4998.3  397.86  5012.9  402.16  5019.4   409.9  5033.8  413.56  5069.1  411.98
  5140.3  416.96    5186  411.91  5218.1  416.59    5255  413.56  6098.9  413.39
  6132.7  409.53  6150.2  412.92  6550.3  418.08  6591.4  426.98  6619.2   420.7
  6724.8  423.35  7062.9  438.57  7249.6  438.87  7658.5  452.53  8054.4  456.42
#Mann= 5 ,-1 , 0
  3883.7     .05       0  4927.4     .16       0  4961.9     .07       0
  5033.8     .16       0    5186     .05       0
Bank Sta=4961.9,5033.8
XS Rating Curve= 0 ,0
Exp/Cntr=0.3,0.1

Type RM Length L Ch R = 1 ,39215   ,165,165,165
BEGIN DESCRIPTION:
PLUMMERS CREEK 28.0
END DESCRIPTION:
XS GIS Cut Line= 4
      3498277.26      10566261.6      3495835.81     10566999.46
      3493741.63     10567531.14       3491267.7     10568203.88
#Sta/Elev= 30
  1100.8  461.03  1377.8  459.24  2025.5  436.27  2579.2  425.54  3645.8  415.97
  4876.7  414.88  4913.8  416.26  4939.9  412.32  4959.5  411.18  4986.1  399.39
  5003.7   396.9  5006.4   396.4  5009.7   396.9  5037.6   409.3  5057.6  415.71
  5274.9  413.85  5308.5  409.57  5390.4  414.53    6112  412.98  6153.4  409.25
  6236.3  413.38  6649.9  414.58  6713.8  415.91  6743.2  426.74    6769   422.3
  6788.2  418.51  7239.7  440.26  7552.7  443.84  7987.7     455  8375.7  455.69
#Mann= 7 ,-1 , 0
  1100.8     .05       0  4876.7     .16       0  4959.5     .05       0
  5003.7    .035       0  5009.7     .05       0  6649.9     .16       0
    6769     .05       0
Bank Sta=4939.9,5037.6
XS Rating Curve= 0 ,0
Exp/Cntr=0.3,0.1

Type RM Length L Ch R = 1 ,39050   ,2485,2485,2485
BEGIN DESCRIPTION:
PLUMMERS CREEK 26.0
END DESCRIPTION:
XS GIS Cut Line= 4
      3498081.94     10566153.09      3495781.56      10566836.7
      3494110.55     10567270.73      3490443.02     10567726.45
#Sta/Elev= 30
  1258.7  460.71  1653.5   446.9  2425.7  427.18  3658.4  415.71  4905.5  415.41
  4927.4  416.94  4949.4  413.01  4959.8  411.15  4973.1  410.14  5000.8  396.29
  5013.7  397.86  5032.1  411.49  5062.6  414.31    5280  413.53  5368.3  409.51
  5435.9   412.9  6048.5  412.41  6077.7  408.31  6158.5  412.22  6471.7  412.02
  6613.8  416.88  6710.9   423.4  6729.6  427.24  6763.9  423.97  6864.7  431.94
  7046.1  438.04  7866.6  444.71    8215  443.46  8446.8  453.49  9080.7   464.9
#Mann= 7 ,-1 , 0
  1258.7     .05       0  4905.5     .16       0  4949.4     .07       0
  5032.1     .16       0  5062.6     .05       0  6613.8     .16       0
  6710.9     .05       0
Bank Sta=4959.8,5032.1
XS Rating Curve= 0 ,0
Exp/Cntr=0.3,0.1

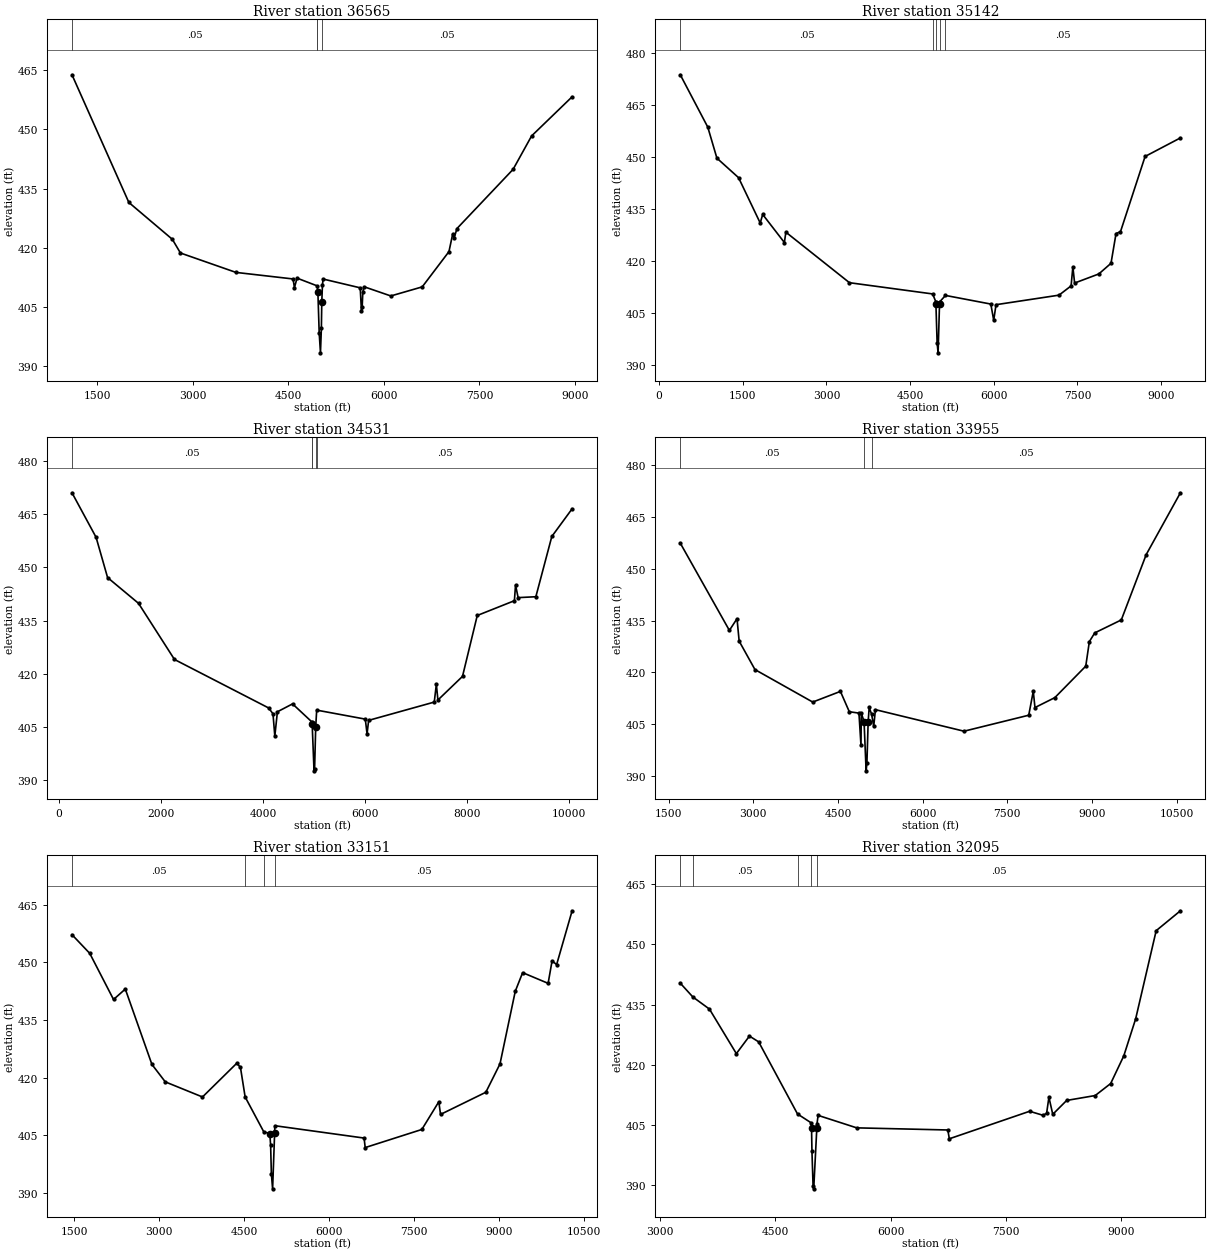
Type RM Length L Ch R = 1 ,36565   ,1423,1423,1423
BEGIN DESCRIPTION:
PLUMMERS CREEK 24.0
END DESCRIPTION:
XS GIS Cut Line= 4
      3498190.42     10566098.85      3495163.07      10565382.7
      3492830.17     10565870.99       3490823.2     10567096.86
#Sta/Elev= 30
  1106.9  463.84  1999.2  431.47  2681.4  422.13  2808.2  418.66  3679.4  413.74
    4575  412.08  4596.8  409.89  4637.7  412.29  4954.4  410.32  4964.4  408.86
    4985  398.42  5005.2  393.35  5019.4  399.63  5025.9  406.35  5036.1  410.55
  5046.3  412.06  5628.7  409.83  5648.3  403.87  5659.3  404.97  5669.6  408.75
    5690   410.1  6108.9  407.77  6601.3  410.07  7020.8  419.01  7079.4  423.48
  7102.9  422.51  7146.6  424.86  8027.2  439.87  8317.6  448.34    8953  458.26
#Mann= 4 ,-1 , 0
  1106.9     .05       0  4954.4     .16       0  4954.4    .035       0
  5036.1     .05       0
Bank Sta=4964.4,5025.9
XS Rating Curve= 0 ,0
Exp/Cntr=0.3,0.1

Type RM Length L Ch R = 1 ,35142   ,611,611,611
BEGIN DESCRIPTION:
PLUMMERS CREEK 23.0
END DESCRIPTION:
XS GIS Cut Line= 4
      3498884.83     10565599.71      3495108.81     10564807.62
      3493687.37     10564492.95      3490160.91      10565447.8
#Sta/Elev= 30
   378.7  473.79   871.9  458.69  1035.4  449.74  1423.7  444.11    1812  431.03
  1856.4   433.5  2245.4   425.4  2271.7  428.39  3412.3  413.81  4903.9  410.57
  4960.7   408.3 4962.54  407.55    4984  396.44  5001.4  393.58 5026.81  407.54
  5027.6  408.24  5133.7  410.14  5946.9  407.65  5998.7  402.97  6040.1  407.47
  7169.3  410.22  7386.1  412.89    7418  418.39  7449.1  413.71  7883.4  416.34
  8101.8  419.41  8191.9  427.99  8271.6  428.52    8713  450.23  9346.2  455.58
#Mann= 5 ,-1 , 0
   378.7     .05       0  4903.9     .16       0  4960.7     .07       0
  5027.6     .16       0  5133.7     .05       0
Bank Sta=4962.54,5026.81
XS Rating Curve= 0 ,0
Exp/Cntr=0.3,0.1

Type RM Length L Ch R = 1 ,34531   ,576,576,576
BEGIN DESCRIPTION:
PLUMMERS CREEK 22.0
END DESCRIPTION:
XS GIS Cut Line= 4
      3498863.13      10565382.7      3494815.84     10564471.25
      3494132.25     10564189.13      3489315.84     10565197.97
#Sta/Elev= 30
   255.2  471.06   727.8   458.5   953.3  447.14  1560.2  439.87  2265.3  424.03
  4110.9  410.36  4197.4  408.71  4233.4   402.4  4283.9  409.27    4581   411.5
  4959.6  406.42  4965.7  405.88  5002.6  392.61  5013.6  393.23  5035.3  404.94
  5054.5  409.74    6008   407.2  6042.6  403.03  6073.3  406.85  7360.6  412.01
  7401.5  417.05  7432.1  412.59  7914.5  419.26  8203.9  436.44  8932.4  440.61
  8954.5  445.02  9005.5  441.48  9352.9  441.73  9666.1  458.73 10064.3  466.54
#Mann= 5 ,-1 , 0
   255.2     .05       0  4959.6     .16       0  4959.6     .07       0
  5035.3     .16       0  5054.5     .05       0
Bank Sta=4965.7,5035.3
XS Rating Curve= 0 ,0
Exp/Cntr=0.3,0.1

Type RM Length L Ch R = 1 ,33955   ,804,804,804
BEGIN DESCRIPTION:
PLUMMERS CREEK 21.0
END DESCRIPTION:
XS GIS Cut Line= 5
       3497756.4     10564514.65      3495141.37     10564015.52
       3493264.2     10563809.35      3491180.86     10563592.34
      3489076.45     10564275.73
#Sta/Elev= 30
  1708.4  457.46  2578.1  432.19  2713.4  435.58  2751.2  429.08  3031.2  420.84
  4054.3  411.43  4544.7  414.52  4701.9  408.63  4872.9  408.23    4909  398.85
  4914.1  408.23  4963.4  405.79  4999.8  391.51  5013.7  393.67 5035.95  405.68
    5054  409.86  5096.2  407.96  5134.5  404.42  5164.6  409.23  6733.7  402.99
  7879.9  407.62  7960.3  414.55  7990.5  409.84  8342.4  412.72  8889.8  421.83
  8953.7  428.95  9049.6  431.47  9519.5  435.22    9961  454.16 10566.3  472.05
#Mann= 3 ,-1 , 0
  1708.4     .05       0  4963.4    .035       0  5096.2     .05       0
Bank Sta=4963.4,5035.95
XS Rating Curve= 0 ,0
Exp/Cntr=0.3,0.1

Type RM Length L Ch R = 1 ,33151   ,1056,1056,1056
BEGIN DESCRIPTION:
PLUMMERS CREEK 20.0
END DESCRIPTION:
XS GIS Cut Line= 4
      3497832.32     10564134.87      3494772.44     10563679.15
      3494153.95     10563364.48      3489108.39     10563223.42
#Sta/Elev= 30
  1462.9  457.25  1776.5  452.38  2196.9  440.35  2404.8  443.07    2875  423.42
  3111.1  418.87  3768.3  414.93  4374.9  423.74  4439.2  422.63  4521.7  414.94
  4851.5  405.83  4957.1   405.4    4972  402.38    4985  394.92    5007  390.98
 5042.46  405.43  5046.1  407.44  6622.9  404.22  6642.9  401.74  7643.3  406.46
  7943.4  413.69  7973.4  410.38  8773.7  416.16  9023.8  423.55  9293.9   442.5
  9423.9  447.35  9874.1  444.56  9944.1  450.43 10024.2  449.44   10298  463.48
#Mann= 4 ,-1 , 0
  1462.9     .05       0  4521.7     .16       0  4851.5     .05       0
  5046.1     .05       0
Bank Sta=4957.1,5042.46
XS Rating Curve= 0 ,0
Exp/Cntr=0.3,0.1

Type RM Length L Ch R = 1 ,32095   ,2317,2317,2317
BEGIN DESCRIPTION:
PLUMMERS CREEK 18.0
END DESCRIPTION:
XS GIS Cut Line= 4
      3495911.72     10562496.42      3494761.59     10562485.57
      3493882.68     10563104.06      3489618.33     10562713.43
#Sta/Elev= 30
  3263.6  440.35  3426.6  436.92  3643.2  433.89  3993.2   422.8  4163.3  427.17
  4283.3  425.73  4788.9  407.77  4970.6  405.51 4971.38  404.33  4976.7  398.54
  4991.5  389.78  4999.8  389.12 5039.89   404.2    5042  405.24  5056.8  407.42
  5559.4  404.31  6744.3  403.78  6764.4  401.59  7808.7  408.44    7983  407.44
  8029.7  407.92  8059.8  411.93    8110  407.68  8290.8  411.14  8662.3  412.36
  8863.3  415.35  9033.8  422.23  9188.4  431.46  9455.6  453.43  9770.7  458.38
#Mann= 5 ,-1 , 0
  3263.6     .16       0  3426.6     .05       0  4788.9     .16       0
  4970.6     .07       0    5042     .05       0
Bank Sta=4971.38,5039.89
XS Rating Curve= 0 ,0
Exp/Cntr=0.3,0.1