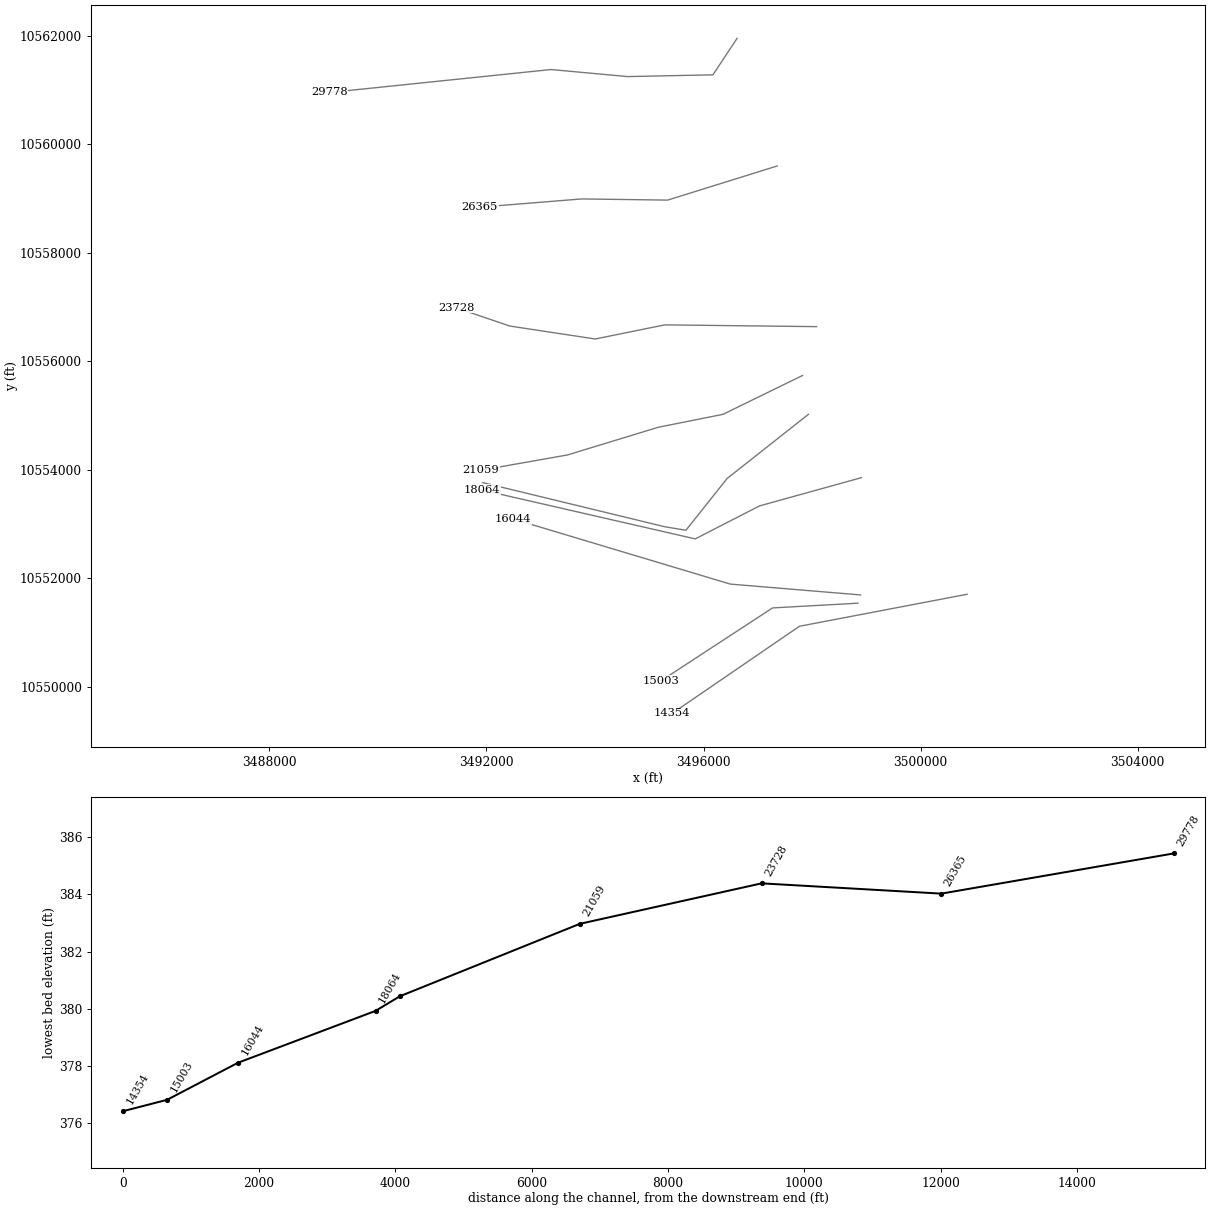
HEC-RAS study PLUMMERS CREEK.prj: PLUMMERS CREEK Base Level Engineering

--- PLUMMERS CREEK.g01 (geometry) --- (continued)

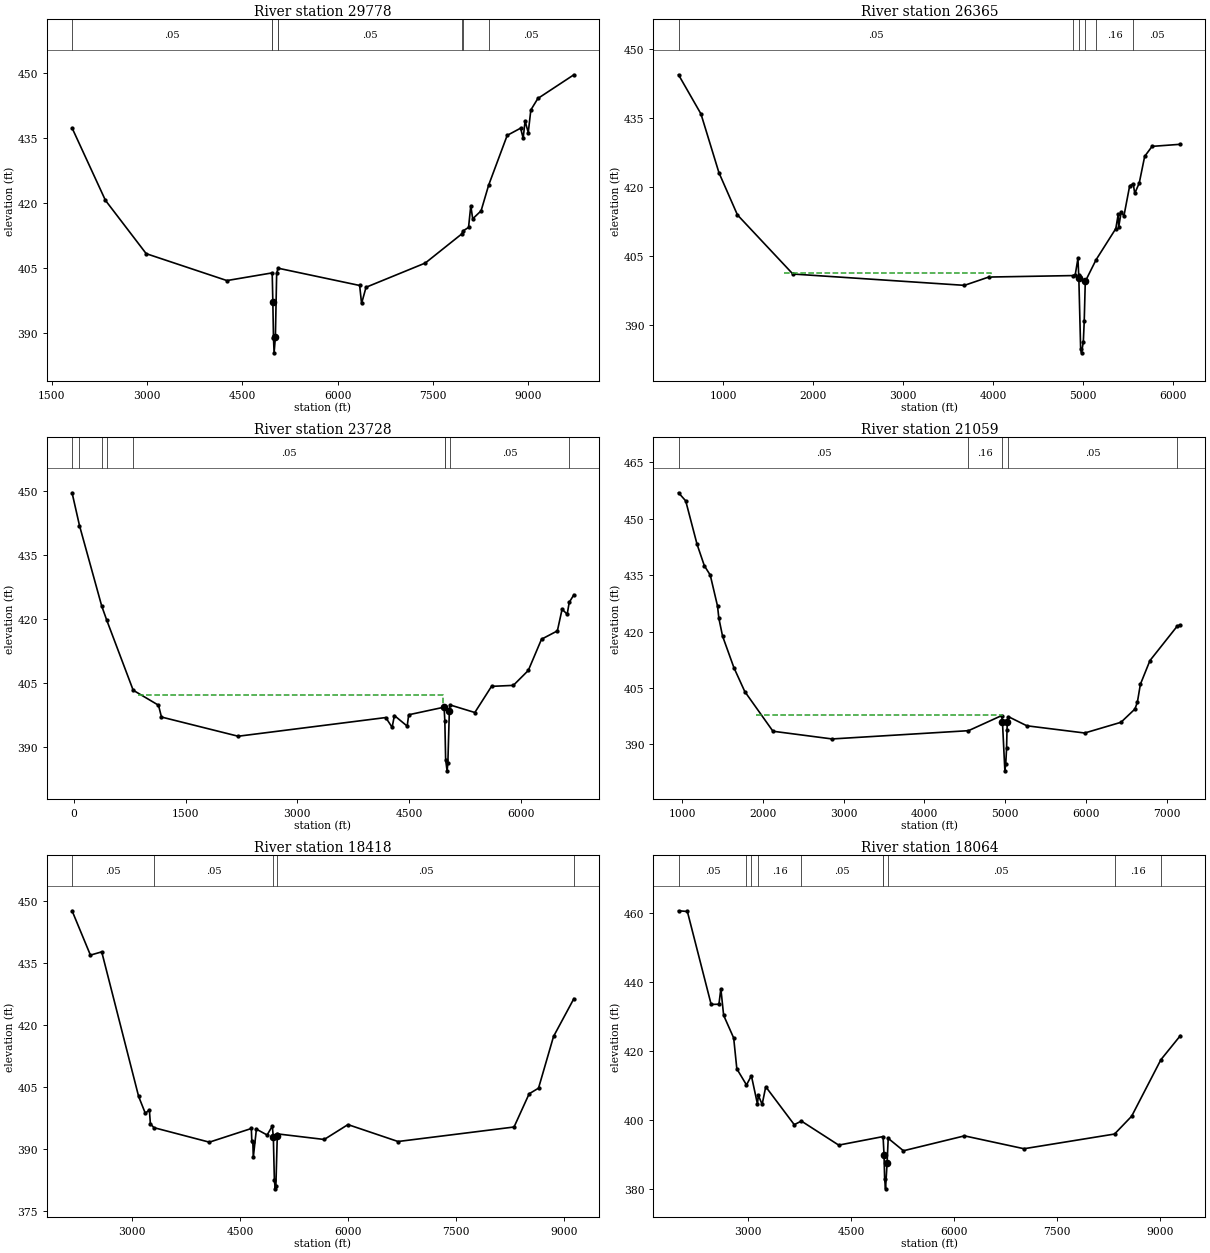
Type RM Length L Ch R = 1 ,29778   ,3413,3413,3413
BEGIN DESCRIPTION:
PLUMMERS CREEK 16.0
END DESCRIPTION:
XS GIS Cut Line= 5
      3496617.06     10561953.88      3496172.18     10561281.14
      3494598.83     10561248.59      3493188.24      10561378.8
      3489108.34     10560955.62
#Sta/Elev= 30
  1820.7  437.25  2345.6  420.58  2987.4  408.29  4257.9  402.09  4970.9  403.86
  4980.9  397.25    4991  388.97  5000.8  385.44  5021.1  389.05  5041.2  403.76
  5063.4  404.94  6347.5  400.96  6377.7  396.81  6448.1  400.55  7380.6  406.13
  7956.1  412.85  7976.6  413.55  8061.6  414.33  8096.9  419.34    8127  416.31
  8259.1  418.16  8377.7  424.06  8669.9  435.54  8881.1   437.2  8921.3   434.9
  8951.4  438.82  9001.7   436.2  9041.9  441.39  9152.5  444.04  9719.3   449.5
#Mann= 8 ,-1 , 0
  1820.7     .05       0  4970.9     .16       0  4970.9     .07       0
  5063.4     .16       0  5063.4     .05       0  7956.1     .05       0
  7976.6     .16       0  8377.7     .05       0
Bank Sta=4980.9,5021.1
XS Rating Curve= 0 ,0
Exp/Cntr=0.3,0.1

Type RM Length L Ch R = 1 ,26365   ,2637,2637,2637
BEGIN DESCRIPTION:
PLUMMERS CREEK 15.0
END DESCRIPTION:
XS GIS Cut Line= 4
       3497356.1     10559600.61      3495337.85     10558971.26
      3493753.65     10558992.96      3491876.83     10558841.08
#Sta/Elev= 30
   501.9  444.35   751.3  435.86   951.6   423.1  1157.1  413.95  1773.5  401.13
  3681.8  398.67  3951.9  400.47  4885.6  400.79  4914.2  400.94  4944.3   404.5
  4953.2  400.82  4954.3  400.37  4974.4  384.94  4984.2  384.03  5004.5  386.43
  5014.5  390.95  5026.1  399.52  5146.1  404.22  5365.7  410.98  5392.6   414.1
  5397.6  411.32  5425.9   414.6    5456  413.73  5519.8  420.25  5559.2  420.71
  5576.4  418.62  5626.5  420.88  5686.7  426.65  5769.2  428.82  6083.3  429.27
#Mann= 6 ,-1 , 0
   501.9     .05       0  4885.6     .16       0  4953.2     .07       0
  5026.1     .12       0  5146.1     .16       0  5559.2     .05       0
#XS Ineff= 1 ,-1
 1671.04 3974.88  401.37
Permanent Ineff=
       F
Bank Sta=4954.3,5026.1
XS Rating Curve= 0 ,0
Exp/Cntr=0.3,0.1

Type RM Length L Ch R = 1 ,23728   ,2669,2669,2669
BEGIN DESCRIPTION:
PLUMMERS CREEK 14.0
END DESCRIPTION:
XS GIS Cut Line= 5
      3498083.03     10556638.36       3495283.6     10556670.91
      3494003.22      10556410.5      3492429.87     10556649.21
      3491442.46     10556985.58
#Sta/Elev= 30
   -26.4  449.56    73.2  441.88   371.6  423.03   440.7  419.64   794.6  403.28
  1134.6  399.77  1174.6     397  2204.7   392.5  4187.3  396.88  4273.1  394.59
  4303.5  397.35  4475.4  394.87  4495.6  397.53    4971  399.31  4981.1  396.13
  4991.9     387  5011.2  384.39  5021.6  386.12  5041.8  398.49  5050.5  399.84
    5384  398.06  5608.2  404.19  5901.2  404.42  6102.3  407.92  6279.8  415.24
  6492.8  417.19  6556.2  422.27  6624.7  421.09  6652.1  423.88  6714.3  425.65
#Mann= 9 ,-1 , 0
   -26.4     .16       0    73.2     .05       0   371.6     .12       0
   440.7     .05       0   794.6     .05       0  4981.1     .16       0
  4981.1     .07       0  5050.5     .05       0  6652.1     .16       0
#XS Ineff= 1 ,-1
  859.97 4949.81402.2727
Permanent Ineff=
       F
Bank Sta=4971,5041.8
XS Rating Curve= 0 ,0
Exp/Cntr=0.3,0.1

Type RM Length L Ch R = 1 ,21059   ,2641,2641,2641
BEGIN DESCRIPTION:
PLUMMERS CREEK 13.0
END DESCRIPTION:
XS GIS Cut Line= 5
      3497822.65     10555737.75      3496357.82     10555021.61
      3495164.24     10554782.89      3493493.24     10554272.91
      3491898.22      10553990.8
#Sta/Elev= 30
   956.2  456.91    1045  454.76  1185.7   443.2  1275.8  437.51  1348.9  435.03
  1438.9   426.8  1455.9  423.52  1500.9  418.83  1641.6  410.43  1776.7  404.05
  2125.6   393.5  2857.7  391.45  4547.3  393.65  4958.7  397.67 4968.29  395.86
  4997.8  382.97  5008.5  384.75    5019  388.95  5024.3  393.94 5028.92     396
  5039.9  397.39  5269.9  394.95  5986.3  393.03  6435.7  395.88  6608.3   399.4
  6638.8  401.22  6676.1  405.98  6794.5  412.29  7134.3   421.5  7170.8  421.76
#Mann= 5 ,-1 , 0
   956.2     .05       0  4547.3     .16       0  4958.7     .07       0
  5039.9     .05       0  7134.3     .05       0
#XS Ineff= 1 ,-1
 1917.81 4958.24  397.73
Permanent Ineff=
       F
Bank Sta=4968.29,5028.92
XS Rating Curve= 0 ,0
Exp/Cntr=0.3,0.1

Type RM Length L Ch R = 1 ,18418   ,354,354,354
BEGIN DESCRIPTION:
PLUMMERS CREEK 12.0
END DESCRIPTION:
XS GIS Cut Line= 6
       3497931.2     10555021.63      3496433.77     10553838.88
      3495674.23     10552884.02       3495283.6     10552949.12
      3492332.21     10553665.27      3491930.76     10553762.92
#Sta/Elev= 30
  2167.4  447.52  2422.5  436.82  2579.6  437.61  3092.6  402.72  3185.6  398.65
  3241.7  399.48  3256.1  396.12  3305.8  395.19  4075.6  391.69    4659  394.99
  4665.4  392.07  4679.8  391.85  4686.2  388.01  4729.5  394.83  4878.4  393.42
  4950.5  395.56    4965  392.89  4979.3  382.49  4991.9  380.43  5000.2  381.07
 5019.58   393.1    5021  393.69  5672.3  392.34    6002  395.93  6697.8  391.85
  8310.5  395.35  8520.2  403.36  8650.7  404.72  8859.5   417.2  9141.9  426.31
#Mann= 5 ,-1 , 0
  2167.4     .05       0  3305.8     .05       0    4965     .07       0
    5021     .05       0  9141.9     .05       0
Bank Sta=4965,5019.58
XS Rating Curve= 0 ,0
Exp/Cntr=0.3,0.1

Type RM Length L Ch R = 1 ,18064   ,2020,2020,2020
BEGIN DESCRIPTION:
PLUMMERS CREEK 11.0
END DESCRIPTION:
XS GIS Cut Line= 4
      3498906.01     10553853.41      3497028.84     10553332.57
      3495846.12     10552724.94      3491918.21     10553625.53
#Sta/Elev= 30
  1985.6  460.75  2114.2  460.55  2460.8  433.52    2574  433.59  2601.9  438.09
  2642.5  430.36  2788.7  423.77  2834.6   414.8  2975.2  410.12  3046.6  412.79
  3134.7   404.6  3148.1  407.09  3203.2  404.47  3255.7   409.6  3670.9  398.57
  3774.6  399.62  4318.3  392.63  4964.3  395.11  4978.2  389.88  4986.8  382.88
  5000.1  379.92  5022.5  387.29  5039.1   394.6  5260.9  390.99  6149.8  395.32
  7016.4  391.58  8335.1  395.85  8584.3  401.03  9010.5  417.47  9293.2  424.44
#Mann= 10 ,-1 , 0
  1985.6     .05       0  2975.2     .16       0  3046.6     .12       0
  3148.1     .16       0  3774.6     .05       0  4964.3     .16       0
  4964.3     .07       0  5039.1     .05       0  8335.1     .16       0
  9010.5     .05       0
Bank Sta=4978.2,5022.5
XS Rating Curve= 0 ,0
Exp/Cntr=0.3,0.1

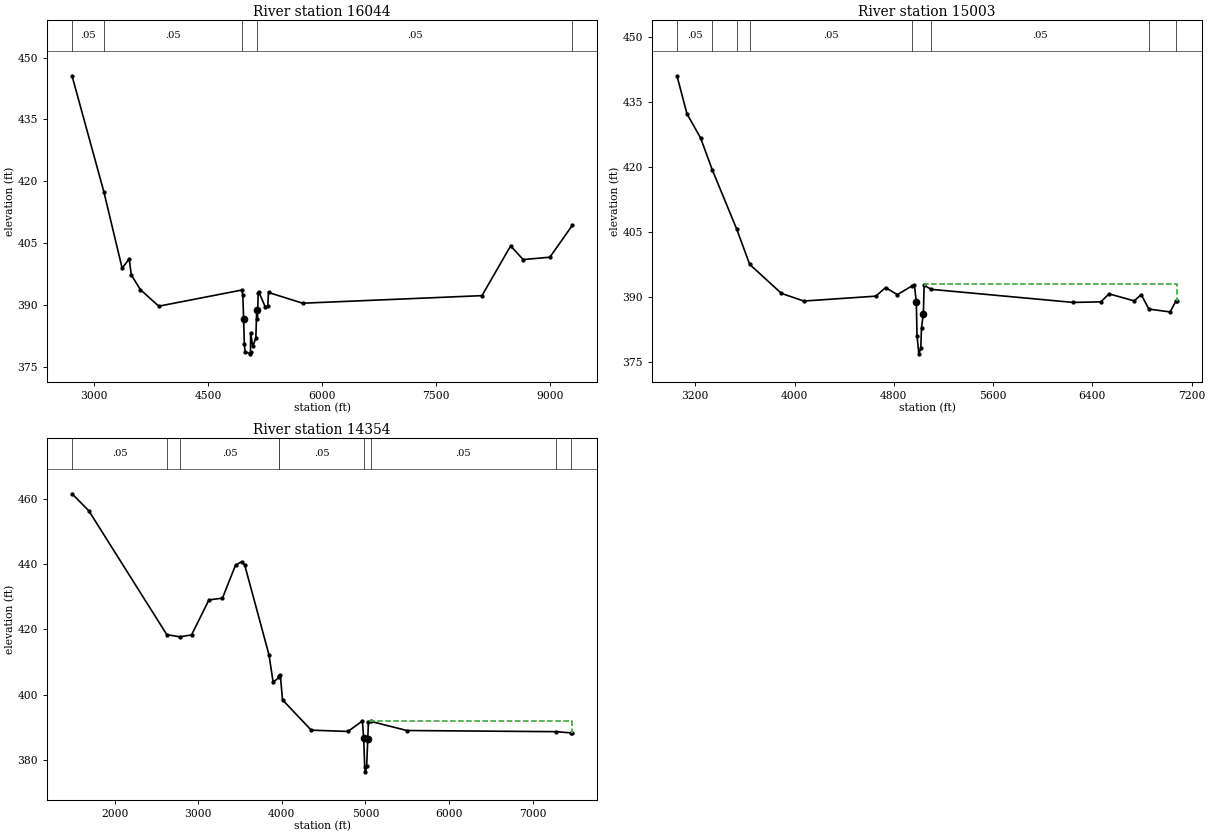
Type RM Length L Ch R = 1 ,16044   ,1041,1041,1041
BEGIN DESCRIPTION:
PLUMMERS CREEK 10.0
END DESCRIPTION:
XS GIS Cut Line= 3
      3498892.09     10551691.64      3496492.11     10551891.64
      3492492.13     10553091.63
#Sta/Elev= 30
  2711.9  445.61  3130.8  417.46  3371.7  398.88  3464.5  401.17  3492.1  397.25
  3612.5  393.67  3853.3  389.67  4946.4  393.59  4959.7  392.35  4969.7  386.59
  4979.7   380.4  4989.8  378.61  5057.2   378.1  5060.5   378.6  5062.5  383.18
  5090.1  379.89  5130.6  381.95    5142  388.65  5151.5  386.62    5162  392.81
  5169.8  393.12  5255.9  389.43  5287.2  389.75  5297.7     393  5746.6  390.39
  8106.1  392.23  8482.9   404.3  8648.2  400.99  8999.6  401.56  9296.3  409.34
#Mann= 5 ,-1 , 0
  2711.9     .05       0  3130.8     .05       0  4946.4     .07       0
    5142     .05       0  9296.3     .16       0
Bank Sta=4969.7,5142
XS Rating Curve= 0 ,0
Exp/Cntr=0.3,0.1

Type RM Length L Ch R = 1 ,15003   ,649,649,649
BEGIN DESCRIPTION:
PLUMMERS CREEK 3.0
END DESCRIPTION:
XS GIS Cut Line= 3
      3498842.12     10551539.23      3497270.94     10551452.42
      3495213.63     10550106.93
#Sta/Elev= 30
    3053   441.1  3133.1  432.33  3243.3  426.72  3337.2  419.36  3534.8  405.61
  3638.7  397.49  3894.3  390.78  4074.6  389.01  4655.2  390.14  4733.6  392.13
  4828.3  390.48  4944.8  392.48  4965.9  392.69    4981  388.88  4986.9  381.04
  5001.8   376.8  5017.2  378.04  5023.1  382.89  5038.2  386.08  5044.2  392.61
  5103.6  391.71  6244.6  388.69  6467.7  388.82  6534.1  390.67  6736.2  389.05
  6793.4  390.49  6854.8  387.15  7025.7  386.49  7074.3  389.06  7084.8  389.03
#Mann= 8 ,-1 , 0
    3053     .05       0  3337.2     .12       0  3534.8     .16       0
  3638.7     .05       0  4944.8     .07       0  5103.6     .05       0
  6854.8     .07       0  7074.3     .16       0
#XS Ineff= 2 , 0
       0                 5047.67       0  393.01
Permanent Ineff=
       F       T
Bank Sta=4981,5038.2
XS Rating Curve= 0 ,0
Exp/Cntr=0.3,0.1

Type RM Length L Ch R = 1 ,14354   ,0,0,0
BEGIN DESCRIPTION:
PLUMMERS CREEK 1.0
END DESCRIPTION:
XS GIS Cut Line= 3
      3500856.02     10551704.16      3497765.73     10551113.88
      3495421.98     10549507.98
#Sta/Elev= 30
  1489.5  461.47  1690.7  456.27  2623.8  418.37  2777.4  417.72  2919.6  418.27
    3128  429.01  3289.4  429.53  3445.7  439.62  3519.5  440.71    3555  439.75
  3845.3  412.29  3896.2  403.85  3967.7  405.31  3971.1  405.74    3982  405.95
  4008.1  398.43  4351.8  389.15  4790.8  388.76  4964.1  391.95    4979   386.7
  4991.6   377.8  4999.7   376.4  5014.9  378.21    5028  386.37  5035.9  391.65
  5065.1  391.83  5496.2  389.04  7278.4  388.69  7463.6  388.31  7476.8  388.19
#Mann= 9 ,-1 , 0
  1489.5     .05       0  2623.8     .16       0  2777.4     .05       0
  3967.7     .12       0  3971.1     .05       0    4979     .07       0
  5065.1     .05       0  7278.4     .12       0  7463.6     .05       0
#XS Ineff= 2 , 0
       0                 5055.66       0  391.81
Permanent Ineff=
       F       T
Bank Sta=4979,5028
XS Rating Curve= 0 ,0
Exp/Cntr=0.3,0.1

Chan Stop Cuts=-1
Use User Specified Reach Order=0
Composite Channel Slope=5