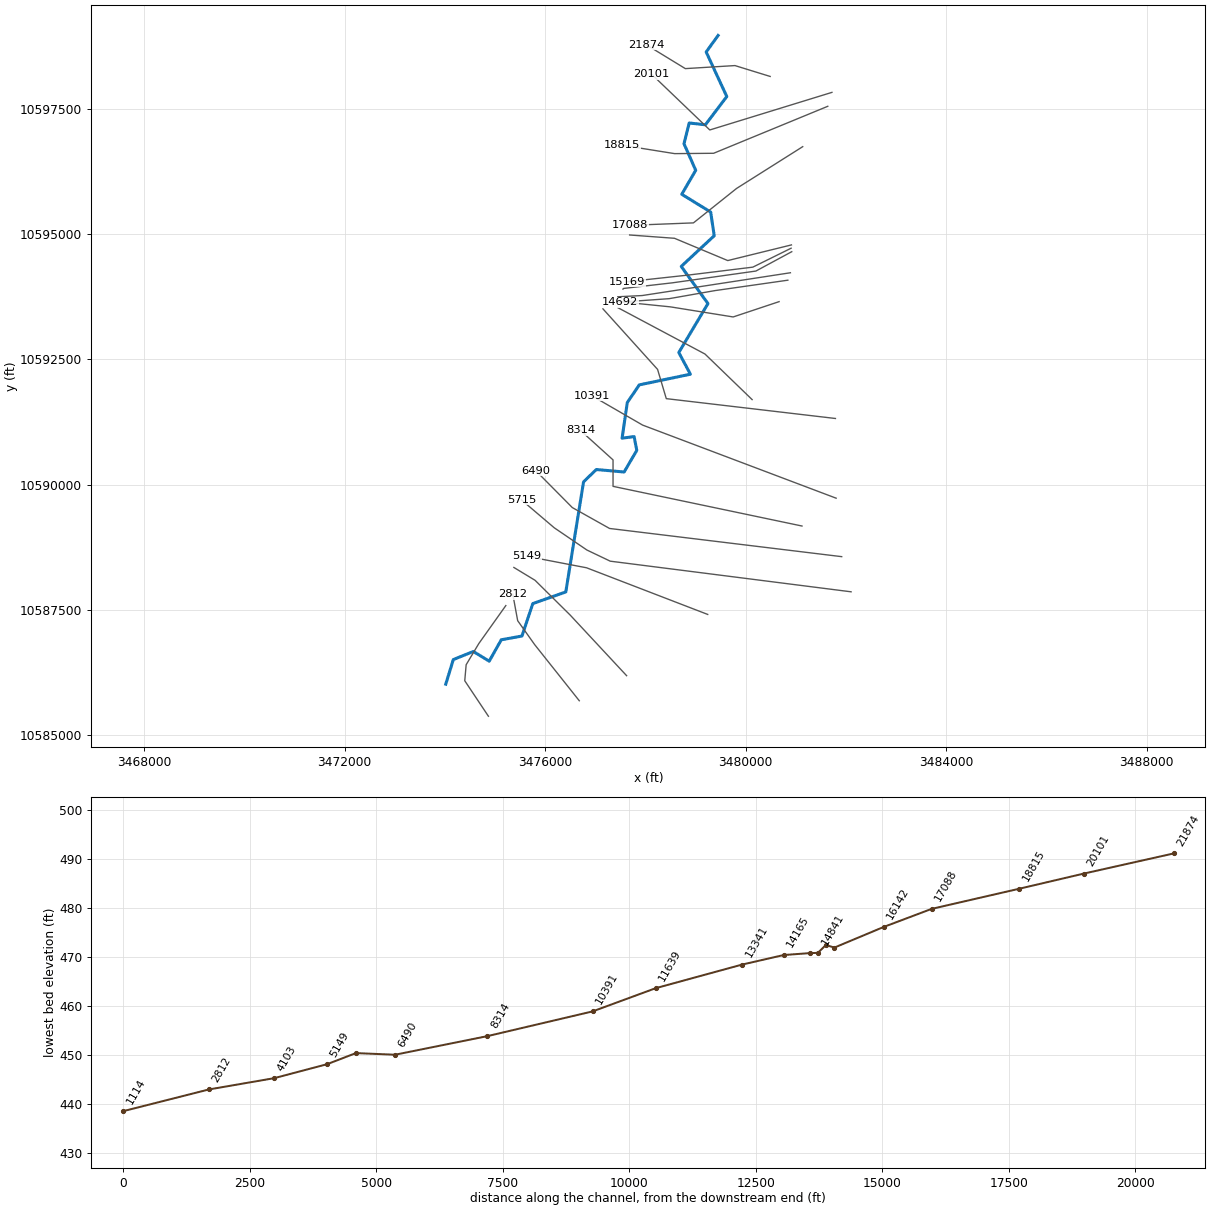
--- ROCKY CREEK.prj (project) ---

Proj Title=ROCKY CREEK Base Level Engineering
Current Plan=p01
Default Exp/Contr=0.3,0.1
English Units
Geom File=g01
Flow File=f01
Plan File=p01
BEGIN DESCRIPTION:
ROCKY CREEK
END DESCRIPTION:

--- ROCKY CREEK.p01 (plan) ---

Plan Title=Multiple Run
Short Identifier=Multiple
Geom File=g01
Flow File=f01
Subcritical Flow
K Sum by GR= 0
Std Step Tol= 0.01
Critical Tol= 0.01
Num of Std Step Trials= 20
Max Error Tol= 0.3
Flow Tol Ratio= 0.001
Split Flow NTrial= 30
Split Flow Tol= 0.02
Split Flow Ratio= 0.02
Log Output Level= 0
Friction Slope Method= 1
Unsteady Friction Slope Method= 2
Unsteady Bridges Friction Slope Method= 1
Parabolic Critical Depth
Global Vel Dist=  1 , 1 , 1
Global Log Level= 0
CheckData=True
Encroach Param= -1, 0, 0, 0
BEGIN DESCRIPTION:
Multiple Run
END DESCRIPTION:

--- ROCKY CREEK.f01 (steady flow) ---

Flow Title=Multiple
Number of Profiles=7
Profile Names=10-year,25-year,50-year,1pct_min,100-year,1pct_plu,500-year
River Rch & RM= ROCKY CREEK,Reach-1,21874
     685     878    1023     866    1171    1583    1532
River Rch & RM= ROCKY CREEK,Reach-1,14165
     773     997    1166     990    1339    1811    1763
River Rch & RM= ROCKY CREEK,Reach-1,10391
     861    1111    1300    1104    1493    2019    1966
River Rch & RM= ROCKY CREEK,Reach-1,4103
    1035    1347    1586    1355    1832    2478    2440
Boundary for River Rch & Prof#=ROCKY CREEK,Reach-1,1
Up Type=0
Dn Type=3
Dn Slope=0.005
Boundary for River Rch & Prof#=ROCKY CREEK,Reach-1,2
Up Type=0
Dn Type=3
Dn Slope=0.005
Boundary for River Rch & Prof#=ROCKY CREEK,Reach-1,3
Up Type=0
Dn Type=3
Dn Slope=0.005
Boundary for River Rch & Prof#=ROCKY CREEK,Reach-1,4
Up Type=0
Dn Type=3
Dn Slope=0.005
Boundary for River Rch & Prof#=ROCKY CREEK,Reach-1,5
Up Type=0
Dn Type=3
Dn Slope=0.005
Boundary for River Rch & Prof#=ROCKY CREEK,Reach-1,6
Up Type=0
Dn Type=3
Dn Slope=0.005
Boundary for River Rch & Prof#=ROCKY CREEK,Reach-1,7
Up Type=0
Dn Type=3
Dn Slope=0.005

--- ROCKY CREEK.g01 (geometry) ---

Geom Title=Existing Conditions

River Reach=ROCKY CREEK,Reach-1
Reach XY= 30
      3479452.11     10598961.64      3479213.60     10598632.19
      3479625.53     10597742.89      3479198.28     10597179.59
      3478875.47     10597214.93      3478771.45     10596801.22
      3479005.56     10596271.47      3478726.76     10595792.74
      3479303.78     10595438.03      3479374.72     10594965.68
      3478716.04     10594353.22      3479249.57     10593611.53
      3478667.64     10592635.60      3478899.57     10592202.59
      3477880.01     10591989.82      3477639.88     10591637.46
      3477536.23     10590926.33      3477776.52     10590957.78
      3477829.25     10590682.81      3477576.55     10590251.19
      3477021.44     10590300.71      3476767.31     10590054.65
      3476413.05     10587858.17      3475754.73     10587625.54
      3475538.16     10586977.92      3475125.97     10586903.76
      3474884.92     10586476.91      3474566.92     10586669.88
      3474168.33     10586508.24      3474017.50     10586017.04

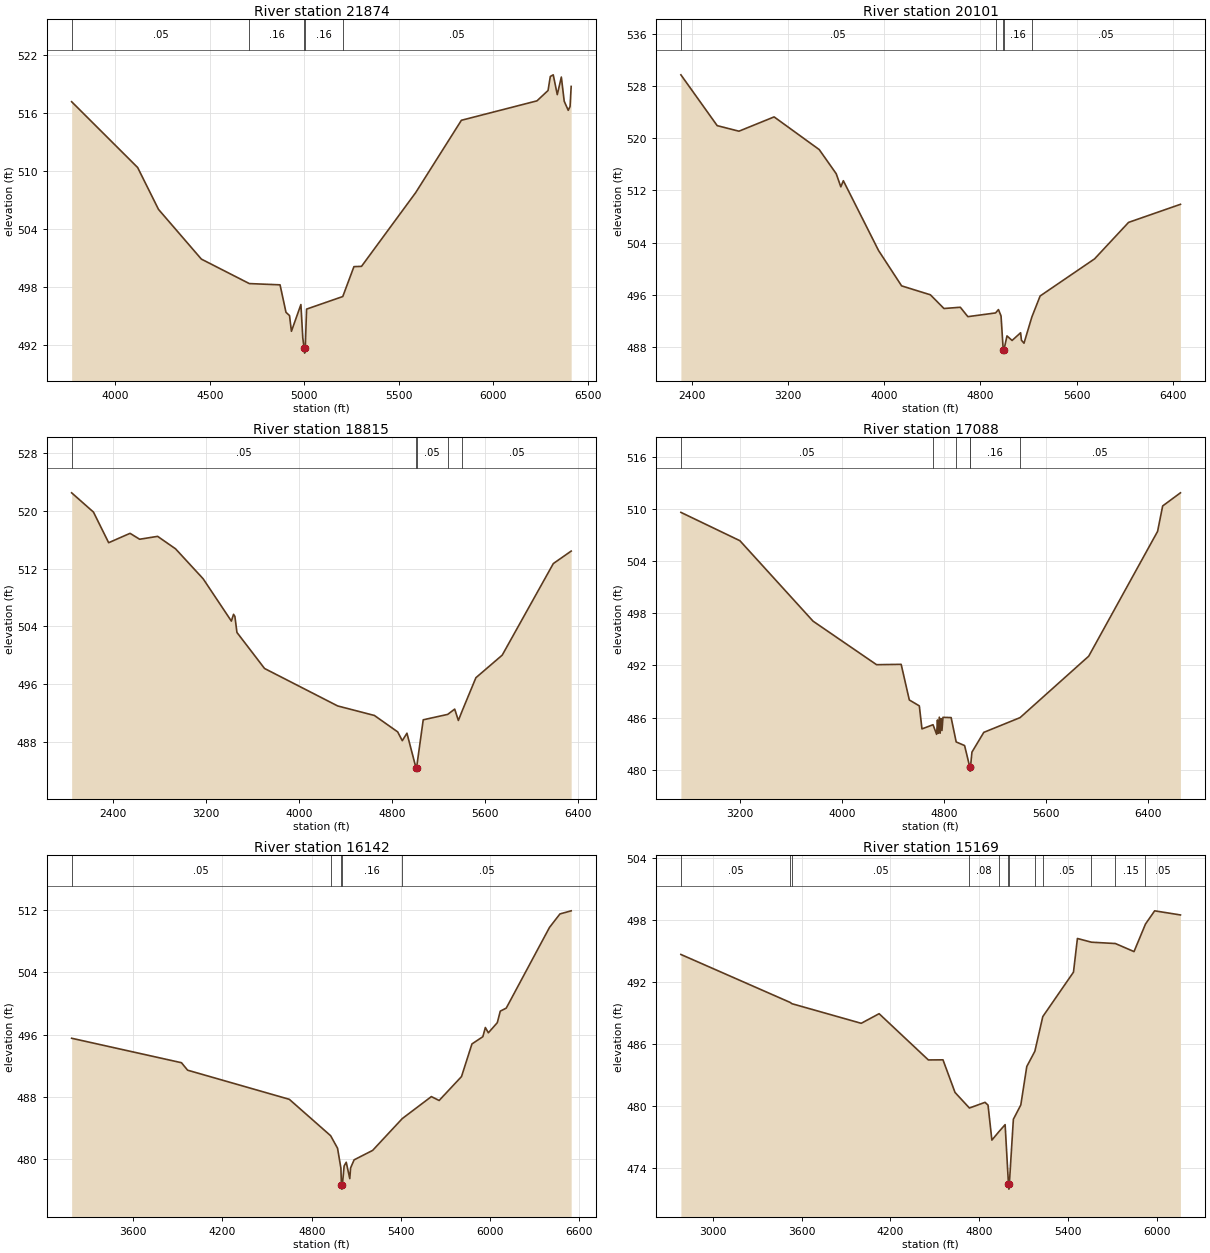
Type RM Length L Ch R = 1,21874,1773,1773,1773
BEGIN DESCRIPTION:
ROCKY CREEK 26.0
END DESCRIPTION:
XS GIS Cut Line= 4
      3480491.03     10598143.79      3479787.90     10598360.80
      3478798.32     10598300.04      3478017.74     10598777.06
#Sta/Elev= 30
  3769.0  517.17  4118.1  510.37  4228.4  506.04  4455.1  500.90  4708.8  498.37
  4871.3  498.24  4902.7  495.40  4921.4  495.06  4931.5  493.44  4981.6  496.20
  4991.6  492.76  4998.6  491.68  5001.3  491.18  5004.6  491.68  5011.6  495.73
  5203.1  497.03  5262.1  500.12  5302.2  500.15  5588.6  507.77  5830.4  515.25
  6230.2  517.26  6288.8  518.33  6300.8  519.78  6316.3  519.95  6337.6  517.90
  6359.1  519.72  6374.3  517.22  6395.6  516.28  6405.2  516.67  6411.1  518.75
#Mann=5,-1,0
  3769.0    0.05       0  4708.8    0.16       0  4998.6    0.07       0
  5004.6    0.16       0  5203.1    0.05       0
Bank Sta=4998.6,5004.6
Exp/Cntr=0.3,0.1

Type RM Length L Ch R = 1,20101,1286,1286,1286
BEGIN DESCRIPTION:
ROCKY CREEK 25.0
END DESCRIPTION:
XS GIS Cut Line= 3
      3481723.63     10597826.07      3479286.17     10597076.08
      3478127.04     10598186.62
#Sta/Elev= 30
  2308.7  529.73  2610.6  521.94  2791.6  521.09  3084.1  523.28  3459.4  518.27
  3600.7  514.57  3639.1  512.56  3660.0  513.50  3952.9  502.80  4144.7  497.38
  4384.1  496.01  4497.0  493.91  4633.0  494.10  4695.8  492.66  4926.4  493.23
  4950.5  493.75  4971.9  492.76  4990.0  487.57  4992.7  487.07  4996.0  487.57
  5021.3  489.71  5063.7  489.01  5134.5  490.19  5141.5  489.05  5162.8  488.59
  5228.0  492.60  5297.1  495.83  5750.0  501.52  6032.7  507.11  6464.2  509.88
#Mann=5,-1,0
  2308.7    0.05       0  4926.4    0.16       0  4990.0    0.07       0
  4996.0    0.16       0  5228.0    0.05       0
Bank Sta=4990,4996
Exp/Cntr=0.3,0.1

Type RM Length L Ch R = 1,18815,1727,1727,1727
BEGIN DESCRIPTION:
ROCKY CREEK 24.0
END DESCRIPTION:
XS GIS Cut Line= 4
      3481640.33     10597548.30      3479362.56     10596610.80
      3478584.78     10596603.86      3477543.09     10596770.53
#Sta/Elev= 30
  2045.7  522.50  2233.5  519.83  2364.1  515.59  2547.9  516.89  2630.6  516.07
  2785.1  516.47  2939.6  514.74  3176.8  510.59  3419.4  504.73  3438.0  505.67
  3449.6  505.39  3467.3  503.16  3704.5  498.17  4333.4  492.98  4649.3  491.66
  4849.3  489.39  4889.3  488.17  4929.3  489.20  5006.3  484.45  5009.1  483.95
  5012.3  484.45  5069.3  491.06  5279.7  491.81  5340.0  492.54  5371.5  490.97
  5406.9  492.40  5522.3  496.89  5748.8  500.02  6188.0  512.70  6341.6  514.43
#Mann=5,-1,0
  2045.7    0.05       0  5006.3   0.035       0  5012.3    0.05       0
  5279.7    0.16       0  5406.9    0.05       0
Bank Sta=5006.3,5012.3
Exp/Cntr=0.3,0.1

Type RM Length L Ch R = 1,17088,946,946,946
BEGIN DESCRIPTION:
ROCKY CREEK 22.0
END DESCRIPTION:
XS GIS Cut Line= 4
      3481140.37     10596742.77      3479820.89     10595909.41
      3478959.78     10595221.91      3477702.82     10595173.30
#Sta/Elev= 30
  2736.5  509.62  3199.5  506.36  3773.6  497.10  4272.0  492.09  4465.1  492.13
  4529.1  488.03  4607.6  487.35  4628.4  484.70  4715.3  485.18  4743.4  484.07
  4750.1  485.73  4756.5  484.19  4764.5  486.05  4770.9  484.20  4778.9  485.89
  4785.3  484.52  4793.3  486.03  4857.3  486.00  4896.9  483.20  4963.0  482.78
  5003.2  480.34  5006.0  479.84  5009.2  480.34  5020.7  482.03  5113.5  484.30
  5398.6  486.00  5937.1  493.07  6477.5  507.43  6517.5  510.36  6656.9  511.87
#Mann=6,-1,0
  2736.5    0.05       0  4715.3    0.12       0  4896.9    0.16       0
  5003.2    0.07       0  5009.2    0.16       0  5398.6    0.05       0
Bank Sta=5003.2,5009.2
Exp/Cntr=0.3,0.1

Type RM Length L Ch R = 1,16142,973,973,973
BEGIN DESCRIPTION:
ROCKY CREEK 21.0
END DESCRIPTION:
XS GIS Cut Line= 4
      3480915.62     10594782.50      3479644.82     10594470.01
      3478582.32     10594914.45      3477686.81     10594980.40
#Sta/Elev= 30
  3186.2  495.52  3924.4  492.38  3965.9  491.42  4649.6  487.68  4927.3  483.01
  4973.9  481.40  4996.4  478.84  5000.1  476.65  5002.9  476.15  5006.1  476.65
  5018.1  479.13  5032.3  479.60  5056.1  477.50  5061.6  478.87  5085.3  479.91
  5209.7  481.12  5409.2  485.21  5604.6  488.03  5656.8  487.53  5807.2  490.60
  5877.4  494.79  5950.7  495.72  5967.6  496.90  5987.7  496.22  6047.9  497.52
  6067.9  499.00  6108.0  499.39  6398.8  509.75  6469.0  511.48  6544.5  511.88
#Mann=5,-1,0
  3186.2    0.05       0  4927.3    0.16       0  5000.1    0.07       0
  5006.1    0.16       0  5409.2    0.05       0
Bank Sta=5000.1,5006.1
Exp/Cntr=0.3,0.1

Type RM Length L Ch R = 1,15169,171,171,171
BEGIN DESCRIPTION:
ROCKY CREEK 21.2
END DESCRIPTION:
XS GIS Cut Line= 4
      3480908.74     10594716.52      3480144.90     10594338.93
      3478873.19     10594182.68      3477640.56     10594048.13
#Sta/Elev= 30
  2785.5  494.68  3523.8  490.03  3535.0  489.91  4003.1  488.01  4124.0  488.94
  4456.5  484.46  4555.3  484.47  4636.6  481.31  4733.7  479.80  4839.3  480.35
  4859.5  480.08  4885.5  476.69  4932.0  477.49  4974.9  478.19  4997.4  472.44
  5000.2  471.94  5003.4  472.44  5030.6  478.71  5080.9  480.10  5121.1  483.82
  5175.7  485.30  5229.3  488.66  5436.6  492.97  5463.1  496.23  5557.8  495.87
  5719.6  495.74  5845.4  494.96  5922.8  497.63  5984.7  498.91  6158.8  498.51
#Mann=12,-1,0
  2785.5    0.05       0  3523.8    0.08       0  3535.0    0.05       0
  4733.7    0.08       0  4932.0     0.1       0  4997.4    0.07       0
  5003.4     0.1       0  5175.7    0.16       0  5229.3    0.05       0
  5557.8     0.1       0  5719.6    0.15       0  5922.8    0.05       0
Bank Sta=4997.4,5003.4
Exp/Cntr=0.3,0.1

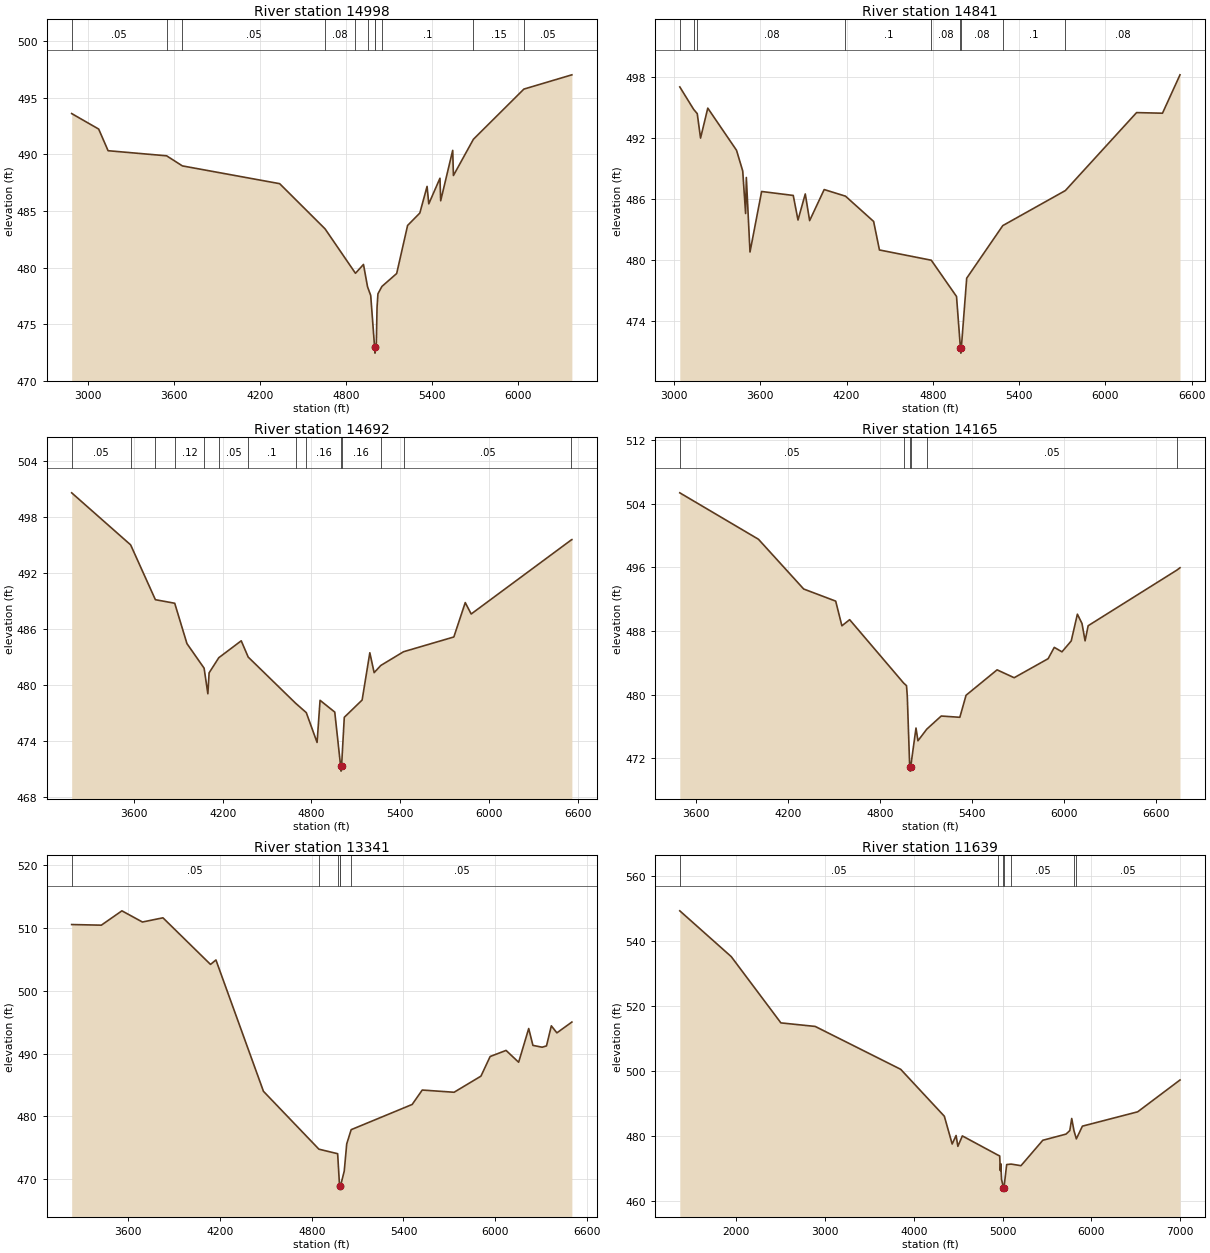
Type RM Length L Ch R = 1,14998,157,157,157
BEGIN DESCRIPTION:
ROCKY CREEK 21.1
END DESCRIPTION:
XS GIS Cut Line= 5
      3480921.76     10594647.07      3480205.66     10594260.81
      3478543.33     10594026.43      3477562.43     10593913.58
      3477553.76     10593900.58
#Sta/Elev= 30
  2883.0  493.60  3071.8  492.23  3137.5  490.32  3546.5  489.87  3656.5  488.98
  4336.5  487.41  4653.8  483.42  4866.1  479.50  4922.2  480.28  4950.4  478.31
  4972.7  477.54  5000.0  472.95  5002.7  472.45  5006.0  472.95  5011.9  473.34
  5016.9  476.50  5023.2  477.69  5051.1  478.34  5154.2  479.48  5230.4  483.72
  5316.0  484.82  5366.5  487.17  5378.5  485.63  5456.6  487.89  5461.6  485.90
  5545.6  490.35  5550.7  488.13  5690.2  491.33  6043.0  495.76  6378.4  497.02
#Mann=11,-1,0
  2883.0    0.05       0  3546.5    0.08       0  3656.5    0.05       0
  4653.8    0.08       0  4866.1    0.05       0  4950.4    0.08       0
  5000.0    0.07       0  5006.0    0.08       0  5051.1     0.1       0
  5690.2    0.15       0  6043.0    0.05       0
Bank Sta=5000,5006
Exp/Cntr=0.3,0.1

Type RM Length L Ch R = 1,14841,149,149,149
BEGIN DESCRIPTION:
ROCKY CREEK 20.0
END DESCRIPTION:
XS GIS Cut Line= 3
      3480894.84     10594226.95      3477936.49     10593772.09
      3477450.41     10593747.79
#Sta/Elev= 30
  3039.5  497.07  3135.8  494.86  3160.9  494.44  3183.9  492.03  3234.2  494.98
  3434.1  490.83  3477.3  488.79  3497.3  484.60  3502.4  488.15  3527.9  480.81
  3608.8  486.77  3828.8  486.38  3861.8  483.96  3912.4  486.53  3942.7  483.90
  4043.9  486.96  4192.2  486.31  4387.9  483.82  4428.4  481.01  4789.1  480.00
  4964.6  476.43  4991.9  471.35  4994.7  470.85  4997.9  471.35  5035.4  478.23
  5286.4  483.41  5721.8  486.86  6217.2  494.54  6397.5  494.48  6519.3  498.26
#Mann=9,-1,0
  3039.5    0.08       0  3135.8    0.05       0  3160.9    0.08       0
  4192.2     0.1       0  4789.1    0.08       0  4991.9    0.07       0
  4997.9    0.08       0  5286.4     0.1       0  5721.8    0.08       0
Bank Sta=4991.9,4997.9
Exp/Cntr=0.3,0.1

Type RM Length L Ch R = 1,14692,527,527,527
BEGIN DESCRIPTION:
ROCKY CREEK 18.2
END DESCRIPTION:
XS GIS Cut Line= 4
      3480843.69     10594078.52      3479385.35     10593870.18
      3478473.89     10593709.59      3477492.99     10593640.15
#Sta/Elev= 30
  3178.7  500.60  3577.3  495.03  3744.7  489.16  3875.4  488.78  3958.1  484.46
  4074.1  481.83  4099.5  479.09  4107.9  481.33  4173.4  482.95  4325.1  484.76
  4372.2  483.02  4692.6  478.08  4765.1  477.07  4837.9  473.88  4858.2  478.39
  4957.5  477.13  4997.4  471.31  5000.1  470.81  5003.4  471.31  5021.9  476.57
  5142.5  478.42  5194.6  483.48  5223.8  481.35  5268.7  482.12  5422.5  483.59
  5762.6  485.17  5839.8  488.85  5879.9  487.63  6556.9  495.56  6560.7  495.59
#Mann=14,-1,0
  3178.7    0.05       0  3577.3    0.08       0  3744.7    0.05       0
  3875.4    0.12       0  4074.1    0.16       0  4173.4    0.05       0
  4372.2     0.1       0  4692.6    0.05       0  4765.1    0.16       0
  4997.4    0.07       0  5003.4    0.16       0  5268.7    0.08       0
  5422.5    0.05       0  6556.9    0.08       0
Bank Sta=4997.4,5003.4
Exp/Cntr=0.3,0.1

Type RM Length L Ch R = 1,14165,824,824,824
BEGIN DESCRIPTION:
ROCKY CREEK 18.0
END DESCRIPTION:
XS GIS Cut Line= 4
      3480669.16     10593650.57      3479752.46     10593345.01
      3478498.99     10593546.40      3477475.90     10593650.44
#Sta/Elev= 30
  3492.1  505.36  4005.4  499.53  4300.6  493.28  4509.4  491.76  4549.9  488.66
  4600.5  489.43  4953.3  481.46  4971.6  481.14  4976.7  479.81  4992.5  470.91
  4995.3  470.41  4998.5  470.91  5033.5  475.82  5046.2  474.22  5103.7  475.68
  5198.1  477.33  5319.6  477.17  5360.2  479.94  5562.7  483.13  5674.1  482.14
  5895.7  484.53  5935.9  485.95  5986.1  485.39  6046.5  486.76  6086.7  490.12
  6116.8  488.95  6136.9  486.77  6157.0  488.67  6735.6  495.65  6756.3  495.95
#Mann=6,-1,0
  3492.1    0.05       0  4953.3    0.16       0  4992.5    0.07       0
  4998.5    0.16       0  5103.7    0.05       0  6735.6    0.08       0
Bank Sta=4992.5,4998.5
Exp/Cntr=0.3,0.1

Type RM Length L Ch R = 1,13341,1702,1702,1702
BEGIN DESCRIPTION:
ROCKY CREEK 18.1
END DESCRIPTION:
XS GIS Cut Line= 3
      3480130.95     10591695.69      3479189.96     10592605.42
      3477455.49     10593528.17
#Sta/Elev= 30
  3228.8  510.51  3423.0  510.41  3557.6  512.69  3691.9  510.91  3826.1  511.58
  4137.4  504.17  4172.9  504.88  4483.9  484.00  4846.8  474.80  4969.4  474.08
  4982.0  468.95  4984.8  468.45  4988.0  468.95  5012.6  471.32  5028.9  475.65
  5057.9  477.90  5457.1  481.91  5523.0  484.20  5731.4  483.85  5907.2  486.41
  5967.4  489.53  6071.6  490.50  6153.9  488.62  6219.8  493.98  6247.4  491.30
  6307.7  491.01  6336.2  491.22  6367.9  494.41  6404.2  493.29  6502.3  495.01
#Mann=6,-1,0
  3228.8    0.05       0  4846.8    0.08       0  4969.4    0.16       0
  4982.0    0.07       0  4988.0    0.16       0  5057.9    0.05       0
Bank Sta=4982,4988
Exp/Cntr=0.3,0.1

Type RM Length L Ch R = 1,11639,1248,1248,1248
BEGIN DESCRIPTION:
ROCKY CREEK 16.0
END DESCRIPTION:
XS GIS Cut Line= 4
      3481793.12     10591319.13      3478418.11     10591714.97
      3478244.50     10592298.30      3477154.20     10593506.66
#Sta/Elev= 30
  1364.2  549.32  1944.0  535.21  2503.0  514.82  2889.3  513.73  3852.2  500.53
  4344.0  486.08  4432.2  477.53  4476.4  480.15  4496.5  476.82  4546.9  480.02
  4951.0  474.07  4967.5  473.87  4974.5  469.35  4979.7  471.45  4988.4  466.62
  5009.9  464.14  5012.6  463.64  5015.9  464.14  5046.1  471.20  5095.7  471.35
  5207.5  470.86  5453.1  478.68  5714.7  480.58  5757.3  481.67  5778.9  485.39
  5804.3  481.62  5831.0  479.11  5899.2  483.03  6521.8  487.44  6998.5  497.24
#Mann=7,-1,0
  1364.2    0.05       0  4951.0    0.16       0  5009.9    0.07       0
  5015.9    0.16       0  5095.7    0.05       0  5804.3    0.16       0
  5831.0    0.05       0
Bank Sta=5009.9,5015.9
Exp/Cntr=0.3,0.1

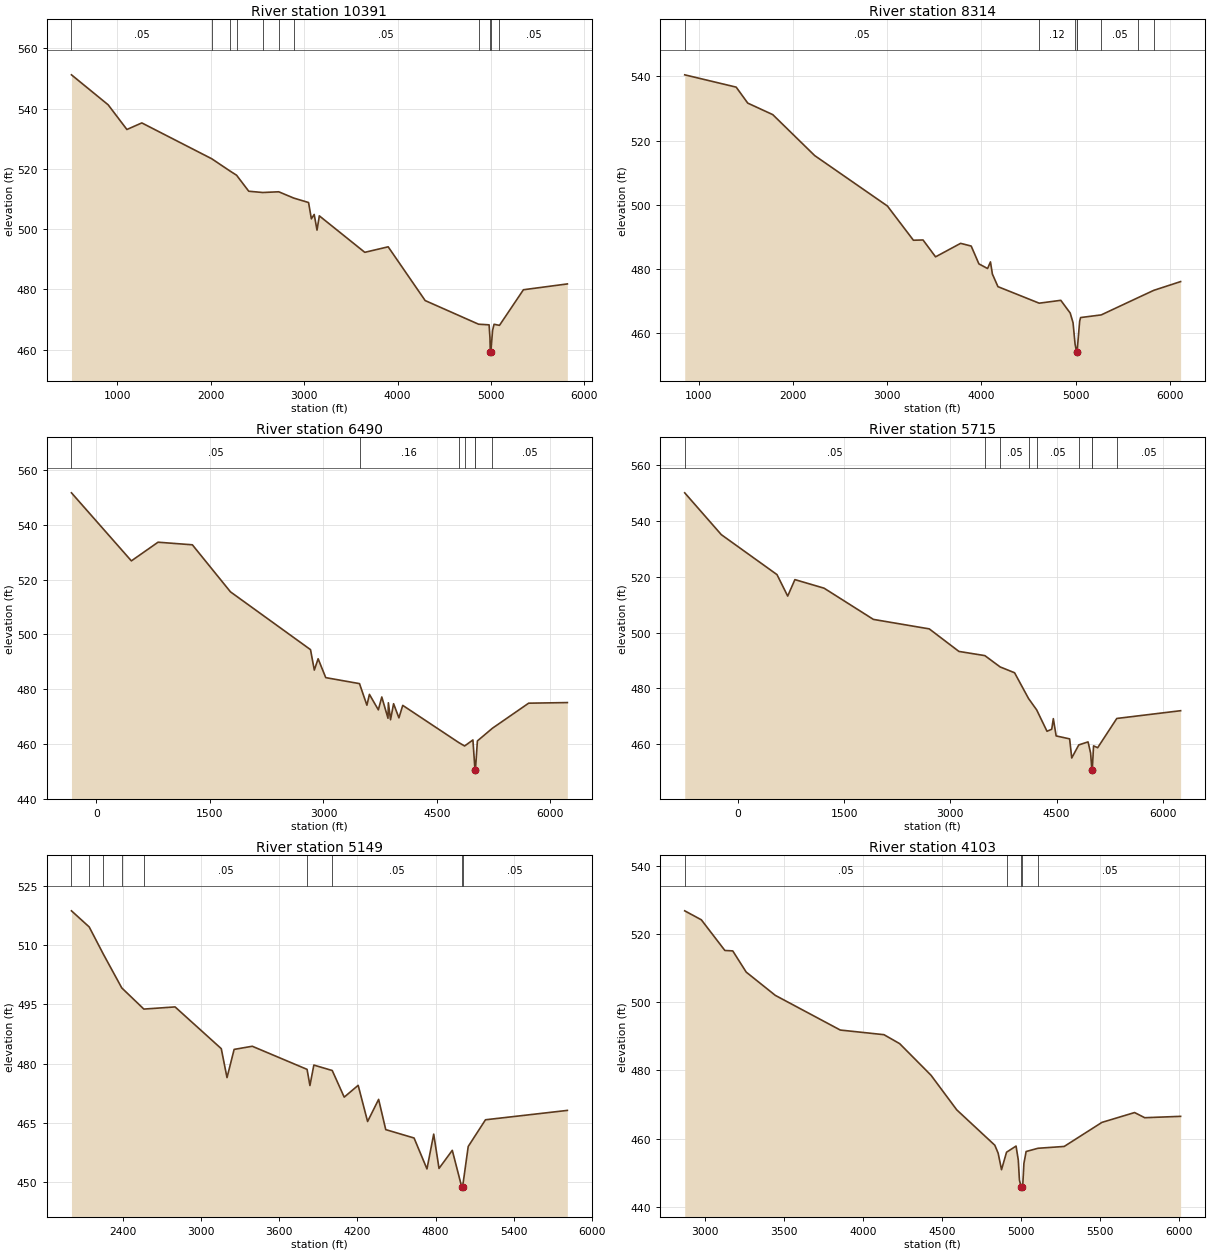
Type RM Length L Ch R = 1,10391,2077,2077,2077
BEGIN DESCRIPTION:
ROCKY CREEK 13.0
END DESCRIPTION:
XS GIS Cut Line= 3
      3481807.03     10589728.85      3477945.89     10591187.19
      3476925.04     10591777.48
#Sta/Elev= 30
   510.9  551.19   903.6  541.25  1104.2  533.06  1263.9  535.24  2012.8  523.34
  2205.8  519.32  2278.0  517.89  2408.2  512.58  2557.6  512.16  2728.8  512.40
  2891.0  510.30  3048.0  508.84  3078.2  503.43  3108.4  504.88  3138.6  499.69
  3163.4  504.42  3649.8  492.32  3900.1  494.15  4296.0  476.32  4867.4  468.48
  4980.1  468.27  4989.2  464.03  4992.9  459.39  4995.6  458.89  4998.9  459.39
  5017.4  466.45  5033.2  468.46  5091.1  468.10  5347.3  479.91  5817.5  481.84
#Mann=11,-1,0
   510.9    0.05       0  2012.8     0.1       0  2205.8    0.05       0
  2278.0     0.1       0  2557.6    0.05       0  2728.8     0.1       0
  2891.0    0.05       0  4867.4    0.16       0  4992.9    0.07       0
  4998.9    0.16       0  5091.1    0.05       0
Bank Sta=4992.9,4998.9
Exp/Cntr=0.3,0.1

Type RM Length L Ch R = 1,8314,1824,1824,1824
BEGIN DESCRIPTION:
ROCKY CREEK 10.0
END DESCRIPTION:
XS GIS Cut Line= 4
      3481126.49     10589173.29      3477355.61     10589964.97
      3477355.61     10590492.75      3476702.87     10591082.99
#Sta/Elev= 30
   852.4  540.44  1398.4  536.61  1521.1  531.64  1786.7  528.05  2231.3  515.31
  3002.7  499.62  3278.5  488.97  3380.7  489.05  3513.6  483.80  3779.2  488.00
  3891.6  487.16  3973.4  481.61  4065.3  480.17  4096.0  482.23  4116.4  478.45
  4175.4  474.52  4613.0  469.38  4842.2  470.27  4942.2  466.30  4972.2  463.28
  4993.6  456.64  5009.2  454.34  5011.9  453.84  5015.2  454.34  5042.2  463.77
  5052.2  464.91  5270.8  465.73  5657.1  471.04  5828.8  473.38  6113.3  476.10
#Mann=8,-1,0
   852.4    0.05       0  4613.0    0.12       0  4993.6    0.16       0
  5009.2    0.07       0  5015.2    0.16       0  5270.8    0.05       0
  5657.1    0.16       0  5828.8    0.05       0
Bank Sta=5009.2,5015.2
Exp/Cntr=0.3,0.1

Type RM Length L Ch R = 1,6490,775,775,775
BEGIN DESCRIPTION:
ROCKY CREEK 8.0
END DESCRIPTION:
XS GIS Cut Line= 4
      3481918.15     10588562.19      3477286.17     10589124.69
      3476543.11     10589541.36      3475814.32     10590277.09
#Sta/Elev= 30
  -329.9  551.66   461.9  526.81   814.5  533.63  1267.8  532.68  1771.5  515.50
  2829.2  494.40  2879.5  486.94  2929.9  491.07  3030.6  484.18  3476.7  481.99
  3574.6  474.11  3607.8  478.07  3725.7  472.42  3771.3  477.11  3853.1  469.35
  3858.2  475.00  3886.9  468.81  3927.2  474.65  3997.7  469.49  4048.1  474.05
  4788.6  460.47  4865.7  459.22  4975.5  461.42  5002.7  450.54  5005.5  450.04
  5008.7  450.54  5034.8  461.07  5233.8  465.71  5712.2  474.85  6223.6  475.07
#Mann=7,-1,0
  -329.9    0.05       0  3476.7    0.16       0  4788.6    0.12       0
  4865.7    0.16       0  5002.7    0.07       0  5008.7    0.16       0
  5233.8    0.05       0
Bank Sta=5002.7,5008.7
Exp/Cntr=0.3,0.1

Type RM Length L Ch R = 1,5715,566,566,566
BEGIN DESCRIPTION:
ROCKY CREEK 6.0
END DESCRIPTION:
XS GIS Cut Line= 5
      3482105.60     10587860.80      3477300.06     10588471.91
      3476834.78     10588694.14      3476182.00     10589138.58
      3475529.19     10589694.16
#Sta/Elev= 30
  -754.1  550.04  -236.9  535.06   549.8  520.75   701.0  513.06   802.6  518.96
  1215.1  515.89  1911.9  504.71  2701.4  501.31  3120.3  493.24  3486.7  491.74
  3702.4  487.69  3906.6  485.60  4103.4  476.40  4219.1  472.29  4364.9  464.64
  4431.5  465.37  4454.1  469.16  4494.0  462.98  4684.5  461.92  4714.3  455.08
  4813.8  459.76  4944.8  460.84  4980.7  456.88  4998.7  450.87  5001.4  450.37
  5004.7  450.87  5022.6  459.42  5080.8  458.76  5350.8  469.23  6252.7  472.01
#Mann=9,-1,0
  -754.1    0.05       0  3486.7    0.16       0  3702.4    0.05       0
  4103.4    0.16       0  4219.1    0.05       0  4813.8    0.16       0
  4998.7    0.07       0  5004.7    0.16       0  5350.8    0.05       0
Bank Sta=4998.7,5004.7
Exp/Cntr=0.3,0.1

Type RM Length L Ch R = 1,5149,1046,1046,1046
BEGIN DESCRIPTION:
ROCKY CREEK 4.0
END DESCRIPTION:
XS GIS Cut Line= 3
      3479244.53     10587409.40      3476827.83     10588339.97
      3475635.25     10588568.78
#Sta/Elev= 30
  2007.1  518.78  2143.2  514.69  2252.2  507.75  2393.1  499.20  2562.5  493.83
  2801.9  494.38  3156.3  483.78  3200.3  476.42  3254.9  483.59  3394.1  484.39
  3814.4  478.52  3836.4  474.42  3866.4  479.61  4007.5  478.23  4099.3  471.47
  4206.4  474.47  4278.7  465.28  4363.3  470.90  4418.0  463.22  4635.2  461.09
  4734.1  453.24  4785.9  462.08  4826.6  453.37  4928.4  457.96  5001.2  448.61
  5004.0  448.11  5007.2  448.61  5050.6  458.94  5183.0  465.72  5811.1  468.10
#Mann=9,-1,0
  2007.1    0.05       0  2143.2    0.16       0  2252.2    0.05       0
  2393.1    0.16       0  2562.5    0.05       0  3814.4    0.16       0
  4007.5    0.05       0  5001.2   0.035       0  5007.2    0.05       0
Bank Sta=5001.2,5007.2
Exp/Cntr=0.3,0.1

Type RM Length L Ch R = 1,4103,1291,1291,1291
BEGIN DESCRIPTION:
ROCKY CREEK 3.0
END DESCRIPTION:
XS GIS Cut Line= 4
      3477626.42     10586187.22      3476501.45     10587395.52
      3475800.06     10588089.97      3475377.04     10588346.55
#Sta/Elev= 30
  2874.4  526.77  2979.5  524.14  3128.0  515.16  3177.9  515.03  3262.9  508.82
  3446.6  502.01  3857.0  491.85  4133.0  490.49  4232.2  487.87  4430.1  478.62
  4592.9  468.47  4833.3  458.11  4854.5  455.78  4875.7  450.94  4907.4  456.06
  4967.6  457.87  4981.7  453.74  4988.8  447.94  4999.9  445.75  5002.7  445.25
  5005.9  445.75  5010.0  446.49  5017.1  452.76  5031.2  456.27  5106.4  457.22
  5271.6  457.75  5510.0  464.80  5716.3  467.68  5780.3  466.17  6007.1  466.57
#Mann=5,-1,0
  2874.4    0.05       0  4907.4    0.16       0  4999.9    0.07       0
  5005.9    0.16       0  5106.4    0.05       0
Bank Sta=4999.9,5005.9
Exp/Cntr=0.3,0.1

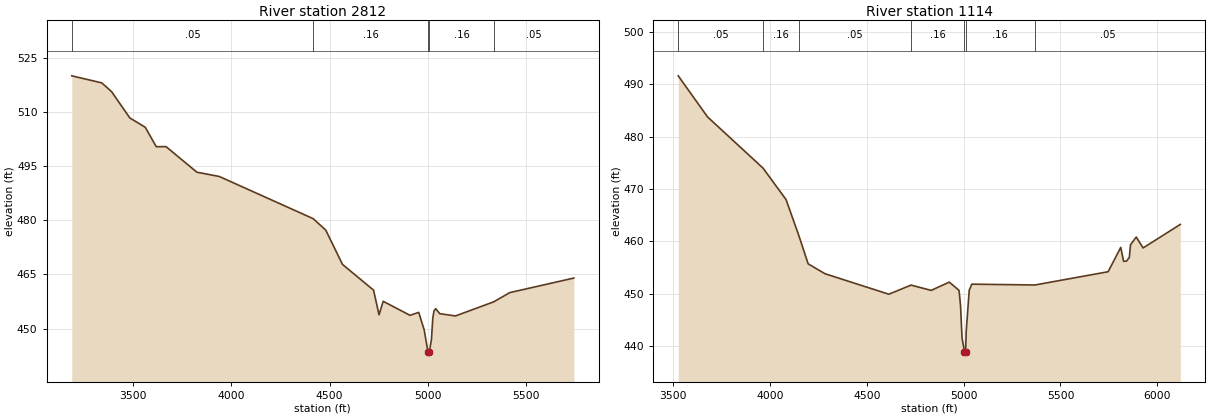
Type RM Length L Ch R = 1,2812,1698,1698,1698
BEGIN DESCRIPTION:
ROCKY CREEK 2.0
END DESCRIPTION:
XS GIS Cut Line= 4
      3476682.00     10585687.20      3475793.11     10586805.25
      3475452.83     10587284.41      3475355.61     10587812.19
#Sta/Elev= 30
  3188.9  519.95  3341.4  518.00  3391.1  515.59  3484.0  508.30  3562.5  505.72
  3618.6  500.33  3668.2  500.36  3825.2  493.28  3938.9  492.10  4416.2  480.43
  4480.4  477.25  4565.3  467.77  4723.2  460.65  4751.2  453.83  4772.3  457.56
  4908.6  453.68  4952.9  454.49  4980.8  449.64  5000.4  443.44  5003.1  442.94
  5006.4  443.44  5017.6  446.99  5024.3  452.82  5030.4  454.85  5039.0  455.52
  5059.9  454.13  5139.9  453.51  5334.2  457.41  5415.7  459.96  5741.6  463.99
#Mann=5,-1,0
  3188.9    0.05       0  4416.2    0.16       0  5000.4    0.07       0
  5006.4    0.16       0  5334.2    0.05       0
Bank Sta=5000.4,5006.4
Exp/Cntr=0.3,0.1

Type RM Length L Ch R = 1,1114,0,0,0
BEGIN DESCRIPTION:
ROCKY CREEK 1.0
END DESCRIPTION:
XS GIS Cut Line= 5
      3474869.20     10585377.74      3474396.98     10586086.06
      3474424.76     10586405.51      3474678.23     10586829.12
      3475216.44     10587586.08
#Sta/Elev= 30
  3524.9  491.59  3676.4  483.75  3963.1  473.98  4082.0  467.98  4147.2  461.21
  4196.2  455.72  4283.3  453.83  4613.1  449.92  4727.8  451.66  4832.1  450.65
  4925.4  452.23  4976.0  450.65  4983.7  447.72  4991.5  441.56  5004.0  438.99
  5006.7  438.49  5010.0  438.99  5012.9  442.79  5028.5  450.68  5042.0  451.84
  5368.0  451.68  5746.3  454.21  5811.5  458.86  5826.3  456.20  5841.1  456.24
  5855.8  456.92  5862.0  459.36  5891.5  460.83  5927.1  458.75  6119.3  463.24
#Mann=7,-1,0
  3524.9    0.05       0  3963.1    0.16       0  4147.2    0.05       0
  4727.8    0.16       0  5004.0    0.07       0  5010.0    0.16       0
  5368.0    0.05       0
Bank Sta=5004,5010
Exp/Cntr=0.3,0.1

Chan Stop Cuts=-1