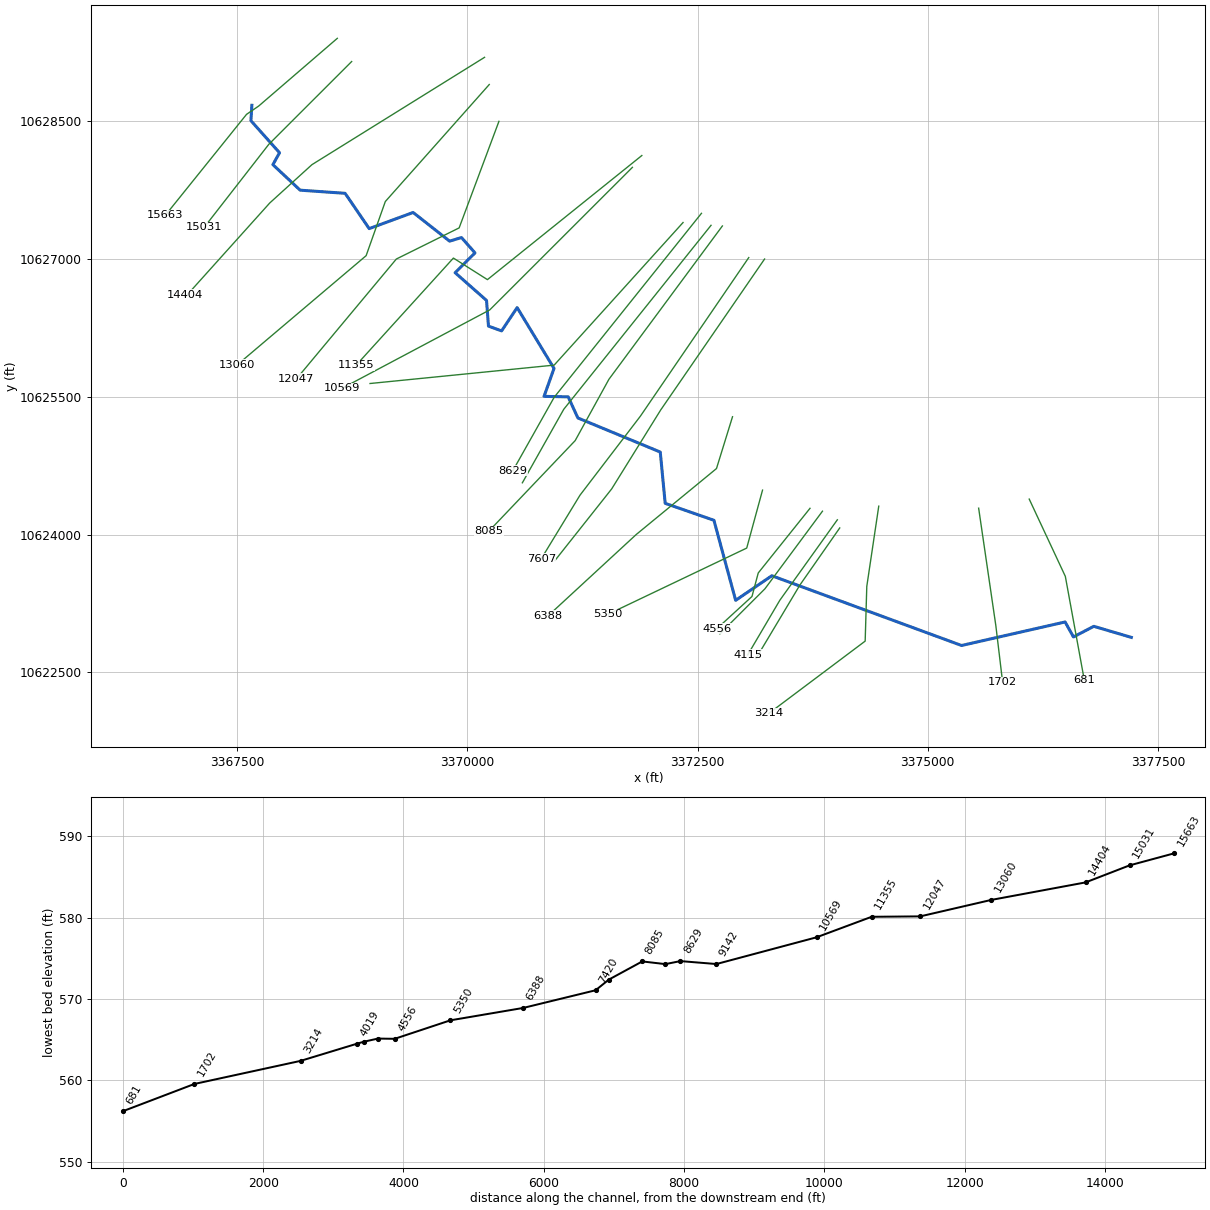
--- UNT0001 IN CHRS.prj (project) ---

Proj Title=UNT0001 IN CHRS Base Level Engineering
Current Plan=p01
Default Exp/Contr=0.3,0.1
English Units
Geom File=g01
Flow File=f01
Plan File=p01
Y Axis Title=Elevation
X Axis Title(PF)=Main Channel Distance
X Axis Title(XS)=Station
BEGIN DESCRIPTION:
UNT0001 IN CHRS
END DESCRIPTION:
DSS Export Rating Curves= 0
DSS Export Rating Curve Sorted= 0
DSS Export Volume Flow Curves= 0
DXF OffsetX= 0
DXF OffsetY= 0
DXF ScaleX= 1
DXF ScaleY= 10

--- UNT0001 IN CHRS.p01 (plan) ---

Plan Title=Multiple Run
Short Identifier=Multiple
Geom File=g01
Flow File=f01
Subcritical Flow
K Sum by GR= 0
Std Step Tol= 0.01
Critical Tol= 0.01
Num of Std Step Trials= 20
Max Error Tol= 0.3
Flow Tol Ratio= 0.001
Split Flow NTrial= 30
Split Flow Tol= 0.02
Split Flow Ratio= 0.02
Log Output Level= 0
Friction Slope Method= 1
Unsteady Friction Slope Method= 2
Unsteady Bridges Friction Slope Method= 1
Parabolic Critical Depth
Global Vel Dist=  1 , 1 , 1
Global Log Level= 0
CheckData=True
Encroach Param= -1, 0, 0, 0
BEGIN DESCRIPTION:
Multiple Run
END DESCRIPTION:

--- UNT0001 IN CHRS.f01 (steady flow) ---

Flow Title=Multiple
Number of Profiles=7
Profile Names=10-year,25-year,50-year,1pct_min,100-year,1pct_plu,500-year
River Rch & RM= UNT0001 IN CHRS,Reach-1,15663
     551     709     828     703     950    1285    1251
River Rch & RM= UNT0001 IN CHRS,Reach-1,14404
     590     759     886     751    1016    1374    1337
River Rch & RM= UNT0001 IN CHRS,Reach-1,11355
     747     970    1139     971    1314    1777    1746
River Rch & RM= UNT0001 IN CHRS,Reach-1,8629
     861    1126    1329    1138    1539    2082    2064
River Rch & RM= UNT0001 IN CHRS,Reach-1,7607
     859    1121    1321    1129    1527    2065    2040
River Rch & RM= UNT0001 IN CHRS,Reach-1,4115
     866    1129    1329    1136    1536    2077    2049
River Rch & RM= UNT0001 IN CHRS,Reach-1,3214
     966    1266    1495    1281    1733    2344    2326
Boundary for River Rch & Prof#=UNT0001 IN CHRS,Reach-1,1
Up Type=0
Dn Type=3
Dn Slope=0.005
Boundary for River Rch & Prof#=UNT0001 IN CHRS,Reach-1,2
Up Type=0
Dn Type=3
Dn Slope=0.005
Boundary for River Rch & Prof#=UNT0001 IN CHRS,Reach-1,3
Up Type=0
Dn Type=3
Dn Slope=0.005
Boundary for River Rch & Prof#=UNT0001 IN CHRS,Reach-1,4
Up Type=0
Dn Type=3
Dn Slope=0.005
Boundary for River Rch & Prof#=UNT0001 IN CHRS,Reach-1,5
Up Type=0
Dn Type=3
Dn Slope=0.005
Boundary for River Rch & Prof#=UNT0001 IN CHRS,Reach-1,6
Up Type=0
Dn Type=3
Dn Slope=0.005
Boundary for River Rch & Prof#=UNT0001 IN CHRS,Reach-1,7
Up Type=0
Dn Type=3
Dn Slope=0.005

--- UNT0001 IN CHRS.g01 (geometry) ---

Geom Title=Existing Conditions
Program Version=4.10

River Reach=UNT0001 IN CHRS ,Reach-1
Reach XY= 30
      3367658.22     10628666.06      3367648.04      10628498.6
      3367958.74      10628150.3      3367886.72     10628020.73
      3368182.67     10627743.46      3368671.16     10627709.24
      3368932.79     10627325.48      3369409.93       10627501.
      3369806.41     10627189.12      3369935.37     10627228.61
      3370082.11     10627061.64       3369866.2      10626846.3
      3370207.44     10626544.65      3370228.53     10626265.34
      3370371.28     10626213.56      3370540.06     10626466.76
      3370940.44     10625805.79      3370832.11     10625501.64
       3371094.6     10625496.65      3371199.65     10625267.16
      3372094.65     10624896.62      3372148.17     10624338.85
      3372677.55     10624154.78      3372913.73     10623284.74
      3373306.63     10623551.84      3375367.73     10622793.51
      3376492.56     10623049.32      3376583.02     10622886.41
       3376804.1     10623002.07      3377212.11     10622881.64

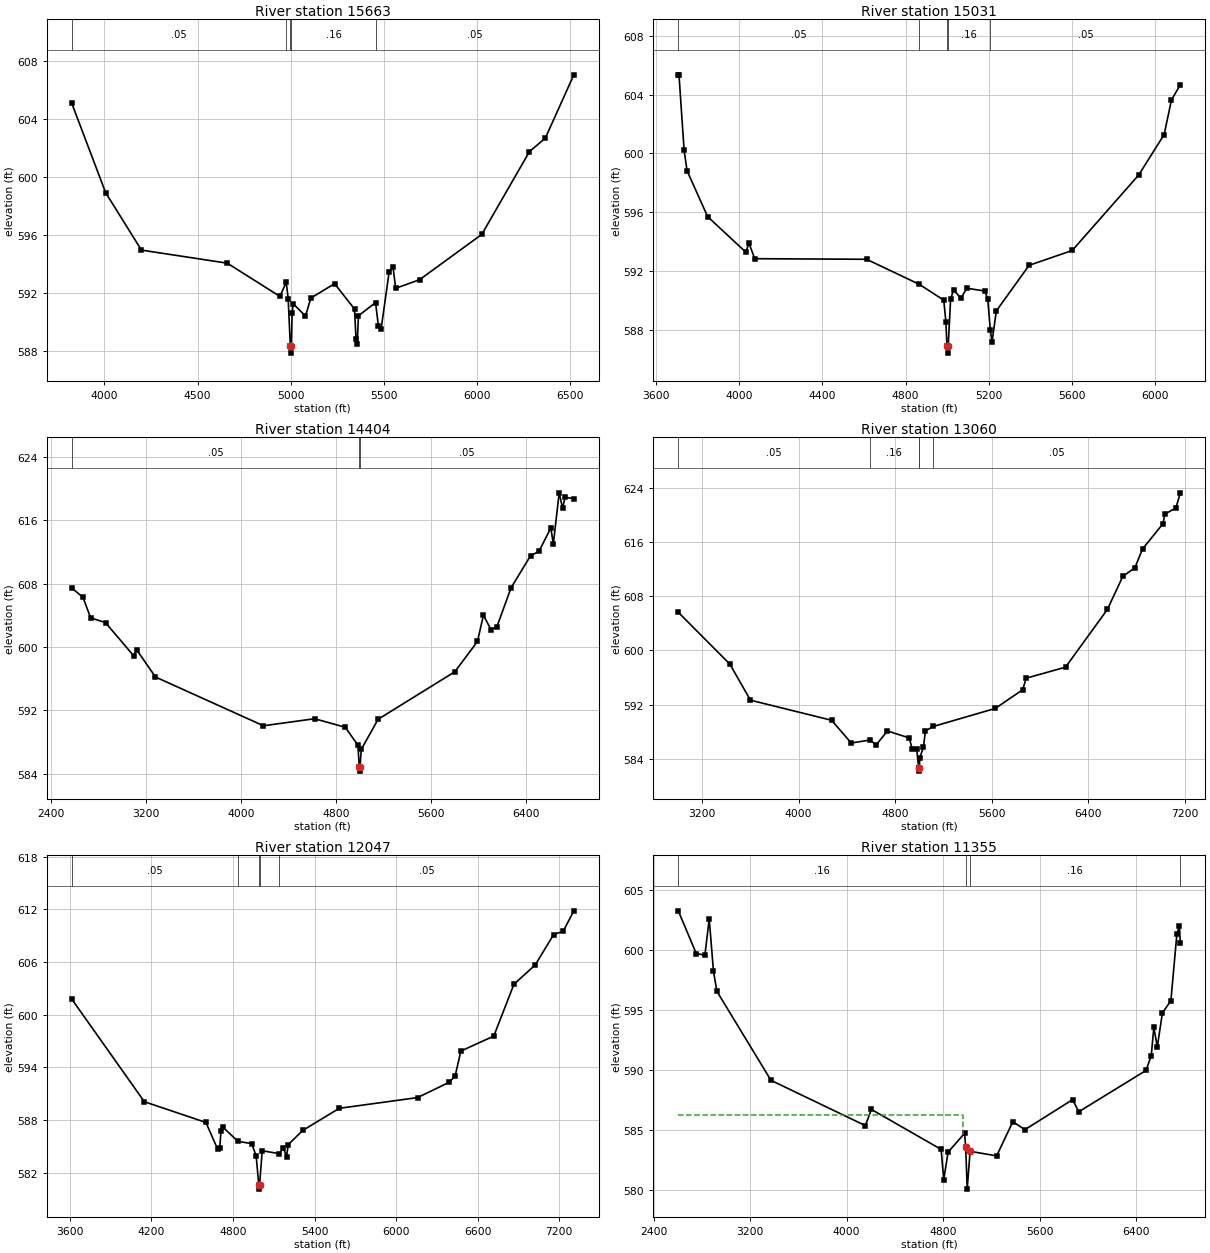
Type RM Length L Ch R = 1 ,15663   ,632,632,632
BEGIN DESCRIPTION:
UNT0001 IN CHRS 24.1
END DESCRIPTION:
XS GIS Cut Line= 4
      3368586.48     10629394.04      3367732.29     10628657.91
      3367600.34     10628567.63      3366718.42     10627470.43
#Sta/Elev= 30
  3824.9  605.06  4006.8  598.91  4198.8  594.96  4659.6  594.06  4942.6  591.77
  4976.1  592.76  4986.6  591.62  4998.2  588.37    5001  587.87  5004.2  588.37
  5007.6  590.61  5013.6  591.27  5079.3  590.42  5108.3  591.66  5235.6  592.65
  5342.8   590.9  5350.8  588.83  5357.2  588.47  5363.8  590.44  5455.7  591.35
  5470.8  589.74  5485.2   589.5  5528.4  593.44  5549.2  593.83  5563.6  592.33
  5691.6  592.92    6026  596.04    6282  601.74  6366.8  602.66  6520.1  607.02
#Mann= 5 ,-1 , 0
  3824.9     .05       0  4976.1     .16       0  4998.2     .07       0
  5004.2     .16       0  5455.7     .05       0
Bank Sta=4998.2,5004.2
XS Rating Curve= 0 ,0
Exp/Cntr=0.3,0.1

Type RM Length L Ch R = 1 ,15031   ,627,627,627
BEGIN DESCRIPTION:
UNT0001 IN CHRS 24.0
END DESCRIPTION:
XS GIS Cut Line= 3
      3368742.12     10629141.66      3367842.11     10628241.64
       3367142.1     10627341.63
#Sta/Elev= 30
  3707.3  605.35  3710.9  605.35  3735.6  600.21  3749.7  598.82  3848.7  595.69
  4032.6  593.27  4046.7   593.9    4075  592.83  4612.4  592.79  4866.3  591.08
  4983.3  590.01  4993.7  588.53  4998.8   586.9  5001.6   586.4  5004.8   586.9
  5016.3  590.07  5030.8  590.71  5066.1  590.13  5094.1  590.82  5180.1  590.63
  5194.6  590.11  5207.4  587.95  5215.4  587.17  5236.2  589.28  5393.7  592.38
  5600.9  593.39  5920.3  598.53  6042.5  601.28  6077.8  603.64  6120.3  604.67
#Mann= 5 ,-1 , 0
  3707.3     .05       0  4866.3     .16       0  4998.8     .07       0
  5004.8     .16       0  5207.4     .05       0
Bank Sta=4998.8,5004.8
XS Rating Curve= 0 ,0
Exp/Cntr=0.3,0.1

Type RM Length L Ch R = 1 ,14404   ,1344,1344,1344
BEGIN DESCRIPTION:
UNT0001 IN CHRS 22.0
END DESCRIPTION:
XS GIS Cut Line= 5
      3370186.01      10629187.6      3368310.99     10628020.91
      3367852.66     10627604.25      3366935.99     10626583.41
      3366935.99     10626604.24
#Sta/Elev= 30
  2577.7  607.46  2672.4  606.25  2736.1  603.68  2861.3  603.07  3100.5  598.84
  3123.3  599.64  3281.5   596.2  4189.2  590.04  4618.9  590.93    4877  589.85
  4983.1  587.59  4994.3  584.81    4997  584.31  5000.3  584.81  5011.5  587.06
  5152.7  590.86  5797.5  596.86  5988.1  600.69  6038.2  604.01  6101.7  602.19
    6151  602.54  6271.4   607.5  6434.4  611.52  6505.4  612.08  6604.8  615.04
  6625.7     613    6675  619.47  6703.5  617.54  6725.1   618.9  6798.3  618.73
#Mann= 3 ,-1 , 0
  2577.7     .05       0  4994.3    .035       0  5000.3     .05       0
Bank Sta=4994.3,5000.3
XS Rating Curve= 0 ,0
Exp/Cntr=0.3,0.1

Type RM Length L Ch R = 1 ,13060   ,1013,1013,1013
BEGIN DESCRIPTION:
UNT0001 IN CHRS 20.0
END DESCRIPTION:
XS GIS Cut Line= 4
      3370236.89     10628891.64      3369107.86     10627619.87
      3368899.53     10627031.33      3367498.52     10625843.85
#Sta/Elev= 30
    3003  605.65    3431  597.98  3601.6  592.65    4274  589.68  4437.1  586.32
  4593.1  586.76  4642.8  586.03  4737.4   588.1  4917.4  587.07    4943   585.4
  4979.2  585.44  4995.8  582.66  4998.5  582.16  5001.8  582.66  5004.8  584.09
  5035.7  585.76  5051.8  588.11  5118.2  588.77  5630.8  591.43  5858.3   594.2
  5886.8   595.9  6213.1  597.53  6560.2  606.07  6687.9  610.96  6787.6  612.22
  6851.3  615.01  7021.6  618.76  7035.9  620.17  7128.1  621.07  7164.5  623.31
#Mann= 5 ,-1 , 0
    3003     .05       0  4593.1     .16       0  4995.8     .07       0
  5001.8     .16       0  5118.2     .05       0
Bank Sta=4995.8,5001.8
XS Rating Curve= 0 ,0
Exp/Cntr=0.3,0.1

Type RM Length L Ch R = 1 ,12047   ,692,692,692
BEGIN DESCRIPTION:
UNT0001 IN CHRS 18.0
END DESCRIPTION:
XS GIS Cut Line= 4
      3370342.11     10628491.64      3369909.95     10627333.41
      3369227.66     10626994.87      3368142.11     10625691.65
#Sta/Elev= 30
  3613.5  601.77  4147.6  590.09  4600.6  587.73  4686.2   584.7  4702.2  584.82
  4711.2  586.78  4723.5  587.23  4835.7  585.58  4937.3  585.32  4970.1  583.92
  4989.4  580.64  4992.2  580.14  4995.4  580.64  5014.8  584.51  5139.3  584.18
  5171.1  584.82  5193.4  583.84  5206.3  585.21  5312.8  586.82  5581.7  589.34
  6157.4  590.56  6391.7  592.31  6434.7  593.06  6476.3  595.86  6718.5  597.56
  6866.9  603.47  7023.1  605.65  7158.5  609.11  7229.4   609.5  7307.5  611.82
#Mann= 5 ,-1 , 0
  3613.5     .05       0  4835.7     .16       0  4989.4     .07       0
  4995.4     .16       0  5139.3     .05       0
Bank Sta=4989.4,4995.4
XS Rating Curve= 0 ,0
Exp/Cntr=0.3,0.1

Type RM Length L Ch R = 1 ,11355   ,786,786,786
BEGIN DESCRIPTION:
UNT0001 IN CHRS 16.0
END DESCRIPTION:
XS GIS Cut Line= 4
      3371894.31     10628119.86      3370217.24     10626770.91
      3369847.45     10627005.29      3368792.11     10625841.64
#Sta/Elev= 30
    2605  603.27  2754.6  599.71    2826  599.58  2861.8   602.6    2897  598.23
  2925.7  596.56  3373.7  589.15    4156  585.38  4205.6  586.73  4783.9   583.4
  4805.1  580.89  4841.5  583.17  4977.9  584.74  4987.2  583.59  4999.9  580.09
  5023.7  583.24  5243.7  582.86  5378.2  585.71  5477.6  585.04  5874.3  587.55
  5923.6  586.53  6482.5  589.98  6525.1  591.21  6546.7  593.58  6575.1  591.93
  6617.5  594.76  6687.9  595.79    6738  601.38  6758.9     602    6766   600.6
#Mann= 4 ,-1 , 0
    2605     .16       0  4987.2     .12       0  5023.7     .16       0
    6766     .05       0
#XS Ineff= 2 , 0
       0 4968.75  586.29               0
Permanent Ineff=
       T       F
Bank Sta=4987.2,5023.7
XS Rating Curve= 0 ,0
Exp/Cntr=0.3,0.1

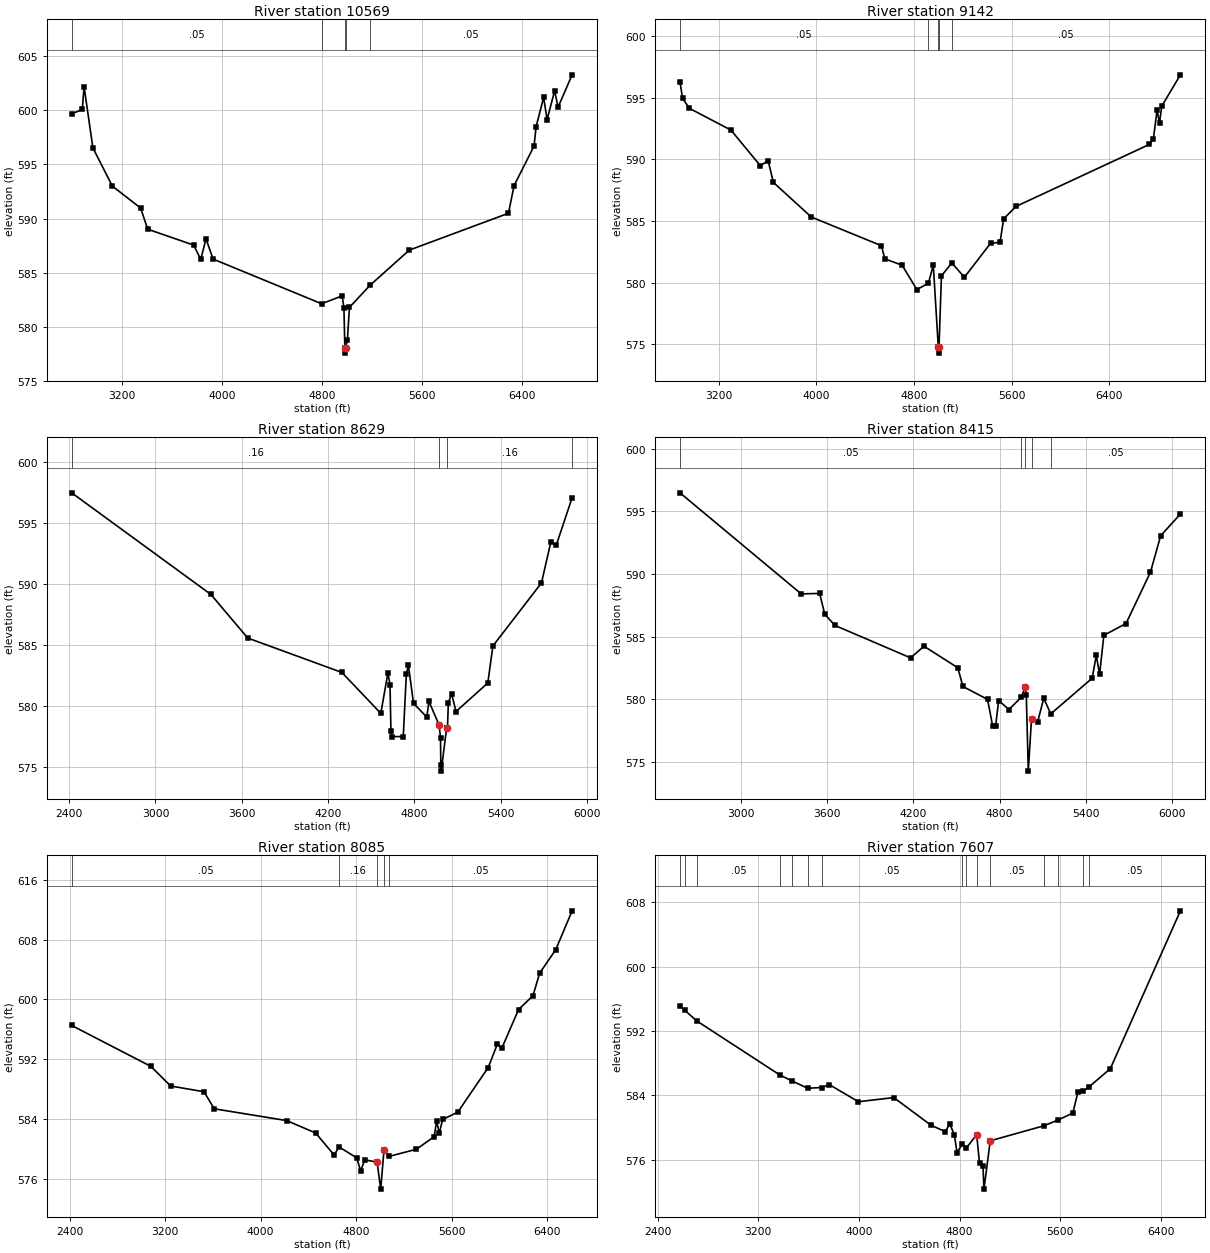
Type RM Length L Ch R = 1 ,10569   ,1427,1427,1427
BEGIN DESCRIPTION:
UNT0001 IN CHRS 15.0
END DESCRIPTION:
XS GIS Cut Line= 3
      3371792.14     10627991.67      3370242.11     10626441.64
      3368642.14     10625591.66
#Sta/Elev= 30
  2797.3  599.67  2882.2  600.08  2896.3  602.19    2967  596.53  3122.6     593
  3348.9  590.97  3405.5  589.02  3773.2  587.55  3829.7  586.23  3872.1  588.13
  3928.7  586.26  4797.3  582.13  4961.1  582.86  4975.2  581.78  4982.8  578.07
  4985.6  577.57  4988.8  578.07  5003.2   578.8  5019.5   581.8  5187.1  583.87
  5498.9  587.09  6291.6  590.49  6336.9  593.05  6496.6   596.7  6512.9  598.49
  6573.2  601.19  6600.8  599.14  6661.1  601.81  6688.7  600.29  6801.1  603.28
#Mann= 5 ,-1 , 0
  2797.3     .05       0  4797.3     .16       0  4982.8     .07       0
  4988.8     .16       0  5187.1     .05       0
Bank Sta=4982.8,4988.8
XS Rating Curve= 0 ,0
Exp/Cntr=0.3,0.1

Type RM Length L Ch R = 1 ,9142    ,513,513,513
BEGIN DESCRIPTION:
UNT0001 IN CHRS 13.0
END DESCRIPTION:
XS GIS Cut Line= 3
      3372342.09     10627391.62      3370942.11     10625841.64
      3368942.12     10625641.64
#Sta/Elev= 30
  2884.3  596.29  2905.6  594.94  2962.4  594.13    3302  592.37    3543  589.48
  3606.5   589.9  3649.1  588.13  3960.7  585.32  4533.9     583  4562.3  581.93
  4703.6  581.42  4824.6  579.44  4919.1  579.96  4959.1  581.42  5000.1  574.79
  5002.8  574.29  5006.1  574.79  5025.7  580.55  5110.6   581.6  5214.1  580.44
  5427.7  583.19  5505.6  583.28  5535.7  585.18  5636.2  586.18  6729.2  591.21
  6761.8  591.67    6792  593.99  6812.1  592.94  6829.6   594.3  6982.9  596.85
#Mann= 5 ,-1 , 0
  2884.3     .05       0  4919.1     .16       0  5000.1     .07       0
  5006.1     .16       0  5110.6     .05       0
Bank Sta=5000.1,5006.1
XS Rating Curve= 0 ,0
Exp/Cntr=0.3,0.1

Type RM Length L Ch R = 1 ,8629    ,214,214,214
BEGIN DESCRIPTION:
UNT0001 IN CHRS 12.0
END DESCRIPTION:
XS GIS Cut Line= 3
      3372542.13     10627491.68      3370942.11     10625491.64
      3370492.09     10624691.62
#Sta/Elev= 30
  2417.5  597.44  3385.2  589.12  3641.3  585.55  4296.1  582.73  4566.6  579.38
  4616.2  582.71  4630.6  581.69    4637  577.94    4645  577.48  4722.7  577.48
  4744.3  582.63  4758.7  583.31  4793.9   580.2  4886.7  579.07  4901.2  580.36
  4971.6  578.43  4981.7  577.39  4983.8  575.15  4986.5  574.65  5024.4  578.19
  5030.1  578.15  5036.2  580.26  5059.1  580.98  5089.4  579.53  5310.6  581.87
  5345.9   584.9  5683.5  590.06  5748.5   593.4  5786.1  593.14  5896.7  597.04
#Mann= 4 ,-1 , 0
  2417.5     .16       0  4971.6     .07       0  5024.4     .16       0
  5896.7     .05       0
#XS Ineff= 1 ,-1
 4190.22  4760.9  582.06
Permanent Ineff=
       F
Bank Sta=4971.6,5024.4
XS Rating Curve= 0 ,0
Exp/Cntr=0.3,0.1

Type RM Length L Ch R = 1 ,8415    ,330,330,330
BEGIN DESCRIPTION:
UNT0001 IN CHRS 12.1
END DESCRIPTION:
XS GIS Cut Line= 3
      3372646.29     10627361.46      3371046.27     10625361.43
      3370596.69     10624562.18
#Sta/Elev= 30
  2577.8  596.47  3420.6  588.41  3548.7  588.45  3583.9   586.8  3654.4   585.9
    4181  583.31  4273.9  584.24  4509.2  582.52  4544.4  581.03  4715.7     580
  4750.9   577.9  4771.7  577.88    4793  579.91  4864.5  579.19  4948.9  580.16
  4978.2  580.99  4985.1  580.33  4998.8  574.28  5021.4  578.47    5063  578.17
  5106.3  580.08  5155.4  578.85  5443.1  581.69  5471.6  583.51  5494.5  581.99
  5524.1  585.11  5678.1  586.05  5847.9  590.14    5919  593.05  6056.1  594.78
#Mann= 5 ,-1 , 0
  2577.8     .05       0  4948.9     .16       0  4978.2     .07       0
  5021.4     .16       0  5155.4     .05       0
Bank Sta=4978.2,5021.4
XS Rating Curve= 0 ,0
Exp/Cntr=0.3,0.1

Type RM Length L Ch R = 1 ,8085    ,478,478,478
BEGIN DESCRIPTION:
UNT0001 IN CHRS 11.0
END DESCRIPTION:
XS GIS Cut Line= 4
      3372769.31     10627354.24      3371537.28     10625688.12
      3371170.36     10625020.91      3370232.92     10624036.59
#Sta/Elev= 30
  2416.9  596.51    3081  591.03    3246  588.41  3525.7  587.64  3611.3  585.36
  4218.8  583.78  4460.9  582.12  4615.1  579.19  4657.8  580.25  4805.5  578.79
  4837.7  577.06  4873.1  578.53  4975.8  578.22    5006  574.61  5033.8  579.88
  5074.7  578.98  5305.2  579.95    5454  581.63    5475  583.74  5496.4  582.08
  5524.8  583.93  5651.8  584.91  5906.6  590.88  5984.3  594.05  6019.8  593.43
    6161  598.64  6281.5  600.49  6338.1  603.52  6472.4  606.65  6609.8  611.85
#Mann= 5 ,-1 , 0
  2416.9     .05       0  4657.8     .16       0  4975.8     .07       0
  5033.8     .16       0  5074.7     .05       0
Bank Sta=4975.8,5033.8
XS Rating Curve= 0 ,0
Exp/Cntr=0.3,0.1

Type RM Length L Ch R = 1 ,7607    ,187,187,187
BEGIN DESCRIPTION:
UNT0001 IN CHRS 10.0
END DESCRIPTION:
XS GIS Cut Line= 4
      3373055.75     10627010.46       3371878.7     10625286.54
      3371222.45     10624427.16      3370801.24     10623735.55
#Sta/Elev= 30
  2577.3  595.07  2615.9  594.56  2710.5  593.25  3373.1  586.52  3470.6  585.78
  3592.7  584.89  3704.5  584.98  3765.8  585.33  3996.1  583.22  4277.3  583.73
  4573.3   580.3  4686.8   579.5  4722.1  580.49    4759  579.09  4780.3  576.89
  4820.1  577.94    4851  577.42  4936.2  579.13    4959  575.57  4986.1   575.3
  4994.1  572.37  5044.2  578.37  5470.3  580.23  5583.9  580.95  5700.9  581.82
  5742.2  584.47  5785.2  584.54  5831.6  585.09  5998.4  587.31  6555.8  606.91
#Mann= 15 ,-1 , 0
  2577.3     .05       0  2615.9      .1       0  2710.5     .05       0
  3373.1      .1       0  3470.6     .05       0  3592.7      .1       0
  3704.5     .05       0  4820.1     .16       0    4851     .05       0
  4936.2     .07       0  5044.2     .05       0  5470.3      .1       0
  5583.9     .05       0  5785.2      .1       0  5831.6     .05       0
Bank Sta=4936.2,5044.2
XS Rating Curve= 0 ,0
Exp/Cntr=0.3,0.1

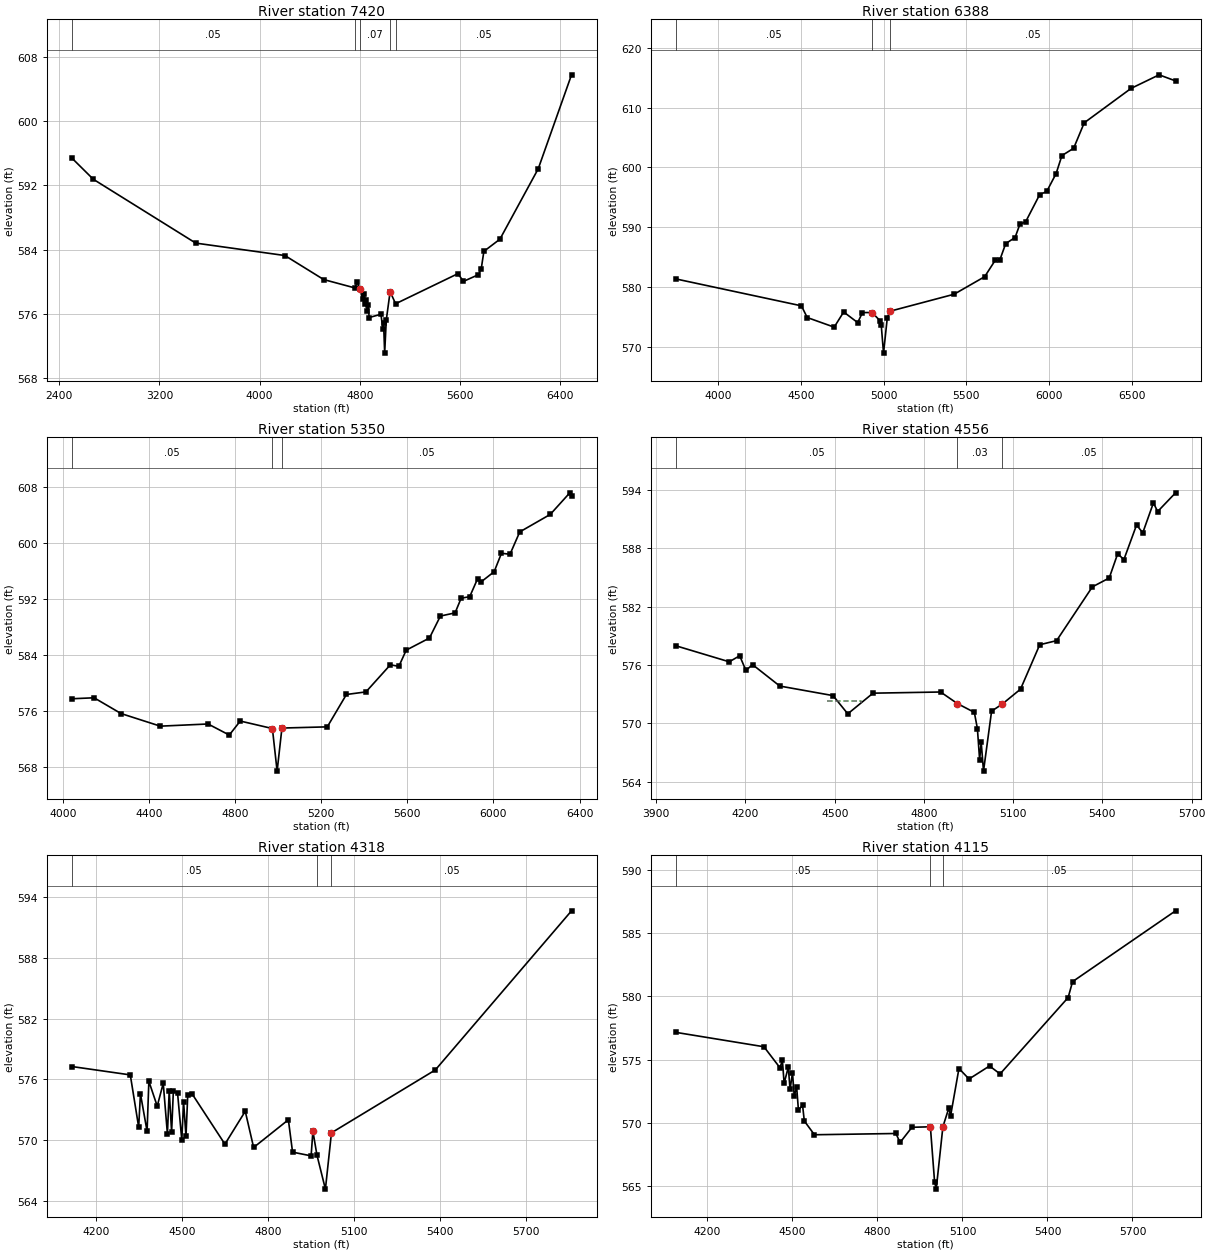
Type RM Length L Ch R = 1 ,7420    ,1032,1032,1032
BEGIN DESCRIPTION:
UNT0001 IN CHRS 9.0
END DESCRIPTION:
XS GIS Cut Line= 4
      3373227.66     10626994.87      3372099.85     10625354.88
       3371566.2     10624494.87      3370951.62     10623718.84
#Sta/Elev= 30
  2498.5  595.44  2671.1  592.77  3489.6   584.8  4201.5  583.25  4511.7  580.25
  4759.7  579.21  4779.8  579.92    4801  579.08  4822.3  577.87  4831.8   578.5
  4837.6  577.14    4853   577.7  4858.9  576.28  4868.4  577.03  4874.3  575.51
  4968.8  575.92  4984.1  574.09    4990  574.78  4998.5  571.07  5011.3  575.19
    5042  578.74  5085.9  577.23    5584  580.99  5627.3  580.02  5747.5  580.86
    5770  581.61  5790.8  583.77    5919  585.29  6225.1  594.08  6490.9   605.8
#Mann= 5 ,-1 , 0
  2498.5     .05       0  4759.7     .16       0    4801     .07       0
    5042     .16       0  5085.9     .05       0
Bank Sta=4801,5042
XS Rating Curve= 0 ,0
Exp/Cntr=0.3,0.1

Type RM Length L Ch R = 1 ,6388    ,1038,1038,1038
BEGIN DESCRIPTION:
UNT0001 IN CHRS 8.0
END DESCRIPTION:
XS GIS Cut Line= 4
      3372879.56     10625280.46      3372705.36     10624716.99
      3371833.56     10624000.08      3370876.77     10623116.89
#Sta/Elev= 30
  3743.1  581.33  4502.8  576.82  4537.9  574.86  4700.8  573.25  4758.2  575.79
  4842.9  574.01  4871.6  575.69 4929.67   575.7  4978.5  574.31  4984.9  573.68
    4999   568.9  5021.5  574.74  5035.8   575.9  5425.4  578.76  5610.3   581.7
  5673.8  584.44  5702.1  584.52  5737.3  587.24    5794  588.26  5822.4  590.44
  5858.1  590.91  5942.6  595.44  5985.1  595.97  6041.8  598.96    6077  601.98
  6147.8   603.2  6211.9  607.47  6494.9  613.23  6664.4   615.5  6763.7  614.48
#Mann= 3 , 0 , 0
  3743.1     .05       0 4929.67     .03       0  5035.8     .05       0
Bank Sta=4929.67,5035.8
XS Rating Curve= 0 ,0
Exp/Cntr=0.3,0.1

Type RM Length L Ch R = 1 ,5350    ,794,794,794
BEGIN DESCRIPTION:
UNT0001 IN CHRS 7.0
END DESCRIPTION:
XS GIS Cut Line= 3
       3373205.7     10624482.85      3373033.82     10623852.61
      3371528.58     10623133.85
#Sta/Elev= 30
  4041.5  577.71  4145.7  577.85  4270.8   575.6  4453.2   573.8    4675  574.11
  4773.5  572.53  4824.4  574.53  4973.7  573.46  4995.6  567.38    5018  573.53
  5228.6   573.7  5317.4  578.32  5408.1  578.69  5521.5  582.56    5561  582.34
  5595.1  584.65    5703  586.38  5753.9  589.52    5822  589.97  5850.2  592.06
  5890.1  592.29  5926.7  594.85    5941  594.35  6003.5  595.85  6037.5  598.48
  6077.1  598.34  6122.4  601.53  6264.1  604.03  6354.8  607.11  6362.8  606.61
#Mann= 3 , 0 , 0
  4041.5     .05       0  4973.7     .03       0    5018     .05       0
Bank Sta=4973.7,5018
XS Rating Curve= 0 ,0
Exp/Cntr=0.3,0.1

Type RM Length L Ch R = 1 ,4556    ,238,238,238
BEGIN DESCRIPTION:
UNT0001 IN CHRS 7.1
END DESCRIPTION:
XS GIS Cut Line= 4
      3373721.35     10624284.94      3373158.82     10623581.78
      3373091.11     10623326.57       3372710.9     10622977.61
#Sta/Elev= 30
  3965.3  577.98  4145.3  576.33  4180.5  576.95  4201.3  575.44  4223.7  576.04
  4315.3  573.84  4494.3  572.86  4543.9  570.99  4628.7  573.11    4856  573.23
    4912  572.05  4969.4  571.14  4979.7  569.47  4987.2  566.25  4992.4   568.1
  5000.2  565.11  5027.4  571.27  5062.4  571.97  5124.6  573.52  5189.2  578.08
  5245.9   578.5  5366.2  584.02  5422.9  584.93  5451.3  587.42  5472.2  586.82
  5514.8  590.37  5535.7  589.57  5571.5  592.64  5585.7  591.75  5645.9  593.67
#Mann= 3 , 0 , 0
  3965.3     .05       0    4912     .03       0  5062.4     .05       0
#XS Ineff= 1 ,-1
 4473.27 4588.12  572.29
Permanent Ineff=
       F
Bank Sta=4912,5062.4
XS Rating Curve= 0 ,0
Exp/Cntr=0.3,0.1

Type RM Length L Ch R = 1 ,4318    ,203,203,203
BEGIN DESCRIPTION:
UNT0001 IN CHRS 6.0
END DESCRIPTION:
XS GIS Cut Line= 3
      3373856.71     10624253.63      3373231.74      10623409.9
      3372742.12     10622920.29
#Sta/Elev= 30
  4114.8  577.27  4319.2  576.44  4348.4  571.27  4354.6  574.57  4377.7  570.86
  4383.9  575.81  4413.1  573.35    4434  575.61  4448.6  570.59  4454.8  574.87
  4463.2  570.81  4469.4  574.89  4484.1   574.6  4498.7  569.99  4504.9  573.78
  4513.3  570.36  4519.5  574.49  4534.2  574.58    4649  569.59  4719.9  572.84
  4749.1  569.26  4870.2     572  4884.8   568.8  4949.5  568.43  4955.7  570.87
  4969.7  568.52  4999.3  565.14  5020.4  570.71  5382.5  576.93  5857.2  592.67
#Mann= 3 ,-1 , 0
  4114.8     .05       0  4969.7    .035       0  5020.4     .05       0
#XS Ineff= 1 ,-1
 4286.66 4570.67  572.89
Permanent Ineff=
       F
Bank Sta=4955.7,5020.4
XS Rating Curve= 0 ,0
Exp/Cntr=0.3,0.1

Type RM Length L Ch R = 1 ,4115    ,96,96,96
BEGIN DESCRIPTION:
UNT0001 IN CHRS 5.0
END DESCRIPTION:
XS GIS Cut Line= 3
      3374018.19      10624159.9      3373393.19      10623284.9
      3373044.23     10622691.14
#Sta/Elev= 30
    4088  577.15  4399.4  576.01  4455.9  574.35  4464.5  574.93  4470.7  573.12
  4485.4   574.4  4491.6  572.64  4500.2  573.95  4506.3  572.12  4514.9  572.82
  4521.1  571.01  4535.8  571.37  4541.9  570.14  4577.6  569.05  4865.1  569.15
  4879.9  568.44  4921.7  569.64  4986.8  569.68  5001.6  565.33  5007.4  564.75
    5031  569.69  5051.9  571.16  5058.1  570.54  5087.6  574.29  5123.2  573.46
  5195.6  574.49  5232.7  573.86  5472.9   579.9  5488.6  581.16    5852  586.76
#Mann= 3 , 0 , 0
    4088     .05       0  4986.8     .04       0    5031     .05       0
Bank Sta=4986.8,5031
XS Rating Curve= 0 ,0
Exp/Cntr=0.3,0.1

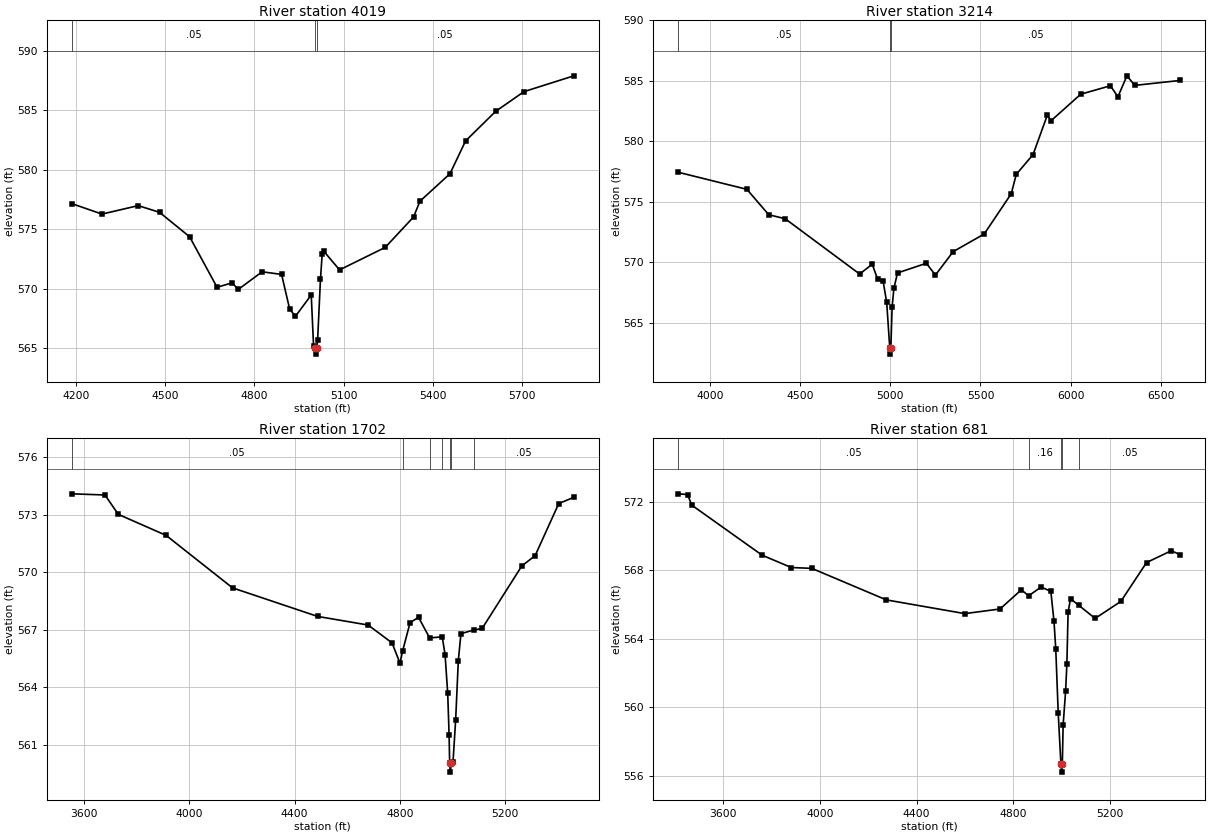
Type RM Length L Ch R = 1 ,4019    ,805,805,805
BEGIN DESCRIPTION:
UNT0001 IN CHRS 4.0
END DESCRIPTION:
XS GIS Cut Line= 3
      3374044.25     10624071.38      3373611.94     10623451.57
      3373132.77     10622649.48
#Sta/Elev= 30
  4185.1  577.16  4286.7  576.28  4408.8  576.99  4480.4  576.43  4581.6  574.38
  4674.1  570.13  4724.7   570.5  4745.6  569.95  4825.9  571.43  4891.3  571.21
  4918.3  568.32  4937.7  567.68  4991.2  569.48  4998.9  565.23  5003.7  565.01
  5006.5  564.51  5009.7  565.01  5012.6  565.67  5022.2  570.81  5028.1  572.95
    5034  573.14  5086.5  571.59  5240.2  573.48  5335.6  576.04    5357  577.36
  5458.1  579.67  5510.7  582.43  5611.8  584.91  5707.2  586.57  5875.1   587.9
#Mann= 3 ,-1 , 0
  4185.1     .05       0  5003.7     .04       0  5009.7     .05       0
Bank Sta=5003.7,5009.7
XS Rating Curve= 0 ,0
Exp/Cntr=0.3,0.1

Type RM Length L Ch R = 1 ,3214    ,1512,1512,1512
BEGIN DESCRIPTION:
UNT0001 IN CHRS 3.0
END DESCRIPTION:
XS GIS Cut Line= 4
      3374468.11     10624308.26      3374338.15     10623436.25
      3374320.54     10622841.23      3373274.52     10622055.63
#Sta/Elev= 30
  3823.6  577.43  4204.4  576.02  4325.7  573.92  4416.7  573.59  4829.9  569.02
  4899.9  569.83    4930  568.57    4960  568.43    4980  566.67    4997   562.9
  4999.7   562.4    5003   562.9    5010  566.29    5020  567.85    5040  569.11
  5200.1  569.91  5250.1  568.93  5348.6  570.87    5521  572.33    5671  575.66
  5698.8  577.26  5791.8  578.89    5871  582.15  5891.8  581.69  6056.3  583.88
  6220.9  584.58  6262.6  583.67  6312.6   585.4  6356.3  584.61  6608.7  585.02
#Mann= 3 ,-1 , 0
  3823.6     .05       0    4997     .03       0    5003     .05       0
Bank Sta=4997,5003
XS Rating Curve= 0 ,0
Exp/Cntr=0.3,0.1

Type RM Length L Ch R = 1 ,1702    ,1021,1021,1021
BEGIN DESCRIPTION:
UNT0001 IN CHRS 1.0
END DESCRIPTION:
XS GIS Cut Line= 3
      3375553.18     10624286.54      3375739.81      10623010.5
      3375813.45     10622395.41
#Sta/Elev= 30
  3552.9   574.1  3679.1  574.04  3729.7  573.03  3911.6  571.93  4164.2  569.19
  4487.6   567.7  4679.7  567.25  4770.6  566.32  4800.9  565.26  4811.4  565.92
  4839.4  567.38  4871.6  567.65  4913.5  566.58  4961.6  566.63  4972.3  565.71
  4982.4  563.68  4987.7  561.49  4989.7  560.07  4992.5  559.57  4995.7  560.07
  5002.5  560.08  5012.6   562.3  5022.7  565.39  5032.7   566.8  5081.2  566.99
  5113.3  567.07  5264.4  570.34  5314.7  570.87  5404.5  573.59    5462  573.92
#Mann= 7 ,-1 , 0
  3552.9     .05       0  4811.4     .16       0  4913.5     .05       0
  4961.6     .16       0  4989.7     .07       0  4995.7     .16       0
  5081.2     .05       0
Bank Sta=4989.7,4995.7
XS Rating Curve= 0 ,0
Exp/Cntr=0.3,0.1

Type RM Length L Ch R = 1 ,681     ,0,0,0
BEGIN DESCRIPTION:
UNT0001 IN CHRS 1.0b
END DESCRIPTION:
XS GIS Cut Line= 3
      3376102.54     10624385.27      3376494.89     10623545.01
      3376701.41     10622415.07
#Sta/Elev= 30
  3414.8  572.46  3453.3  572.42  3470.7   571.8  3761.5  568.88  3882.3  568.16
  3967.2  568.11  4275.3  566.27  4599.7  565.47  4745.4  565.74  4833.5  566.86
  4863.5  566.51  4915.3  567.02  4955.5  566.77  4968.5  565.02  4975.8  563.41
    4986  559.66    4997  556.72  4999.8  556.22    5003  556.72  5006.3  558.97
  5016.5  560.94  5021.7  562.51  5026.8  565.55  5036.8  566.34  5070.4  565.96
  5138.5  565.19  5244.8  566.18  5351.2  568.45  5453.6  569.14  5490.8   568.9
#Mann= 5 ,-1 , 0
  3414.8     .05       0  4863.5     .16       0    4997     .07       0
    5003     .16       0  5070.4     .05       0
Bank Sta=4997,5003
XS Rating Curve= 0 ,0
Exp/Cntr=0.3,0.1

Chan Stop Cuts=-1
Use User Specified Reach Order=0
Composite Channel Slope=5