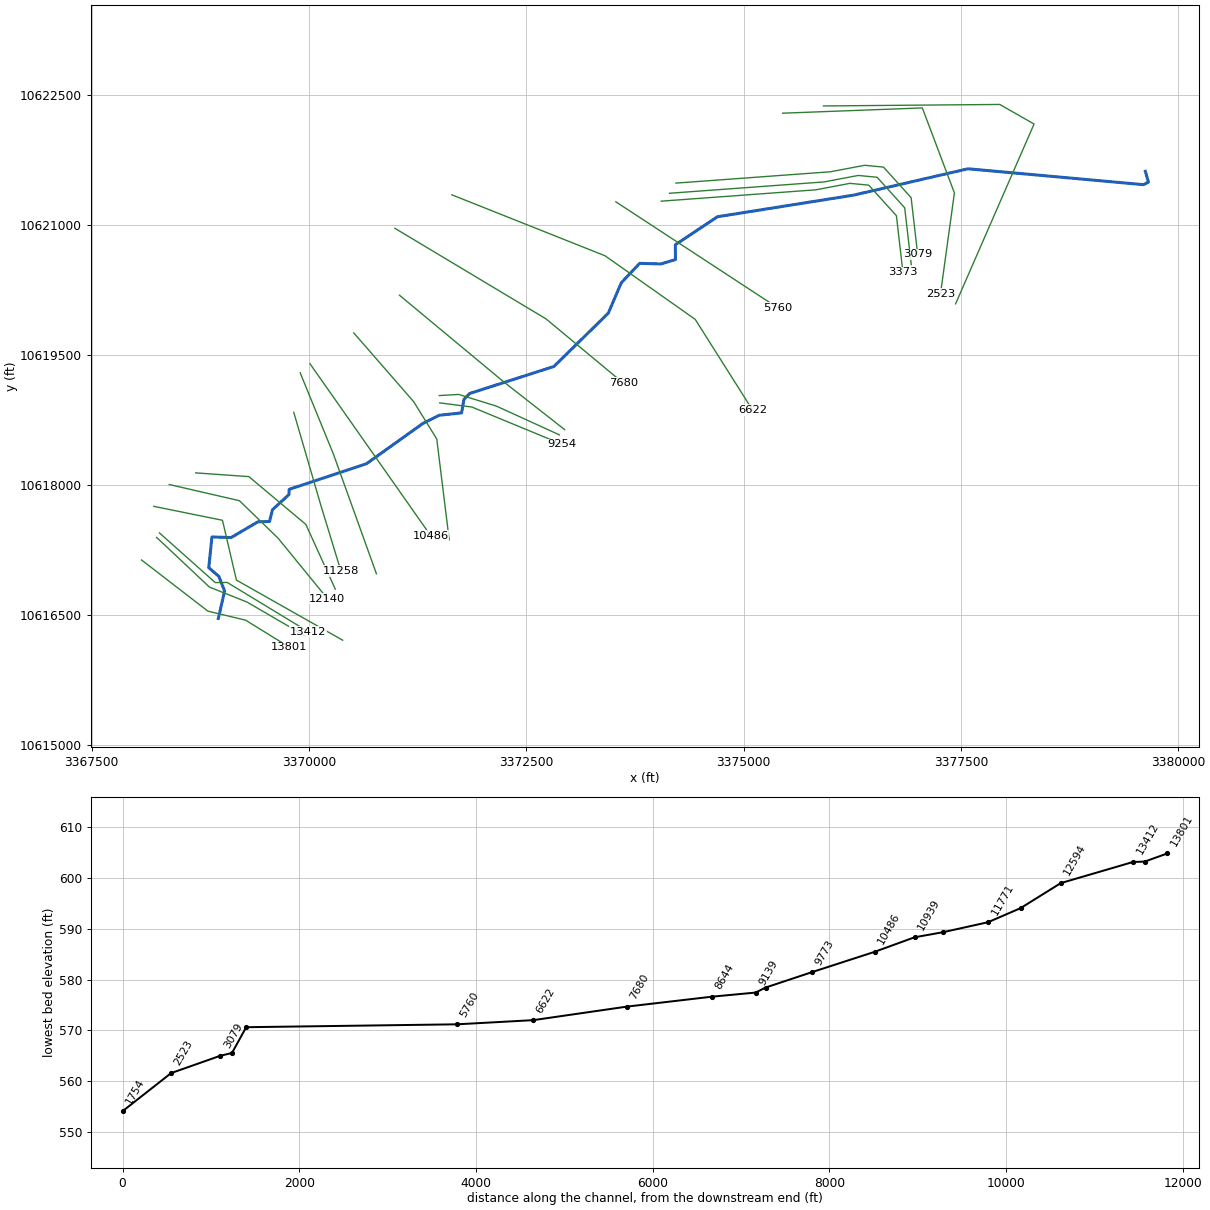
--- UNT0004 IN CHRS.prj (project) ---

Proj Title=UNT0004 IN CHRS Base Level Engineering
Current Plan=p01
Default Exp/Contr=0.3,0.1
English Units
Geom File=g01
Flow File=f01
Plan File=p01
Y Axis Title=Elevation
X Axis Title(PF)=Main Channel Distance
X Axis Title(XS)=Station
BEGIN DESCRIPTION:
UNT0004 IN CHRS
END DESCRIPTION:
DSS Export Rating Curves= 0
DSS Export Rating Curve Sorted= 0
DSS Export Volume Flow Curves= 0
DXF OffsetX= 0
DXF OffsetY= 0
DXF ScaleX= 1
DXF ScaleY= 10

--- UNT0004 IN CHRS.p01 (plan) ---

Plan Title=Multiple Run
Short Identifier=Multiple
Geom File=g01
Flow File=f01
Subcritical Flow
K Sum by GR= 0
Std Step Tol= 0.01
Critical Tol= 0.01
Num of Std Step Trials= 20
Max Error Tol= 0.3
Flow Tol Ratio= 0.001
Split Flow NTrial= 30
Split Flow Tol= 0.02
Split Flow Ratio= 0.02
Log Output Level= 0
Friction Slope Method= 1
Unsteady Friction Slope Method= 2
Unsteady Bridges Friction Slope Method= 1
Parabolic Critical Depth
Global Vel Dist=  1 , 1 , 1
Global Log Level= 0
CheckData=True
Encroach Param= -1, 0, 0, 0
BEGIN DESCRIPTION:
Multiple Run
END DESCRIPTION:

--- UNT0004 IN CHRS.f01 (steady flow) ---

Flow Title=Multiple
Number of Profiles=7
Profile Names=10-year,25-year,50-year,1pct_min,100-year,1pct_plu,500-year
River Rch & RM= UNT0004 IN CHRS,Reach-1,13801
     266     329     373     309     418     565     522
River Rch & RM= UNT0004 IN CHRS,Reach-1,9254
     451     578     674     572     774    1047    1018
River Rch & RM= UNT0004 IN CHRS,Reach-1,8644
     563     724     846     718     971    1313    1278
River Rch & RM= UNT0004 IN CHRS,Reach-1,5760
     722     941    1109     949    1284    1737    1720
Boundary for River Rch & Prof#=UNT0004 IN CHRS,Reach-1,1
Up Type=0
Dn Type=3
Dn Slope=0.005
Boundary for River Rch & Prof#=UNT0004 IN CHRS,Reach-1,2
Up Type=0
Dn Type=3
Dn Slope=0.005
Boundary for River Rch & Prof#=UNT0004 IN CHRS,Reach-1,3
Up Type=0
Dn Type=3
Dn Slope=0.005
Boundary for River Rch & Prof#=UNT0004 IN CHRS,Reach-1,4
Up Type=0
Dn Type=3
Dn Slope=0.005
Boundary for River Rch & Prof#=UNT0004 IN CHRS,Reach-1,5
Up Type=0
Dn Type=3
Dn Slope=0.005
Boundary for River Rch & Prof#=UNT0004 IN CHRS,Reach-1,6
Up Type=0
Dn Type=3
Dn Slope=0.005
Boundary for River Rch & Prof#=UNT0004 IN CHRS,Reach-1,7
Up Type=0
Dn Type=3
Dn Slope=0.005

--- UNT0004 IN CHRS.g01 (geometry) ---

Geom Title=Existing Conditions
Program Version=4.10

River Reach=UNT0004 IN CHRS ,Reach-1
Reach XY= 30
      3368958.18     10616463.51      3369030.33     10616779.12
      3368963.92     10616948.39      3368848.03     10617048.65
      3368884.69     10617403.01      3369105.01      10617396.2
      3369413.72     10617577.92      3369547.59     10617581.78
      3369581.55     10617717.99      3369770.65     10617892.19
      3369772.71     10617952.41      3370662.23     10618247.61
      3371314.68     10618714.93      3371499.41     10618806.91
      3371756.18     10618834.51      3371783.86     10618990.81
      3371848.76     10619058.08      3372818.63     10619369.79
      3373444.41     10619985.39      3373593.35     10620334.69
      3373804.61     10620559.49      3374049.73     10620552.72
      3374216.97      10620603.5      3374215.35     10620773.69
      3374699.35     10621096.91      3376268.43     10621346.85
      3377582.29     10621650.41      3379600.62      10621467.2
      3379657.67      10621497.3      3379622.11     10621621.64

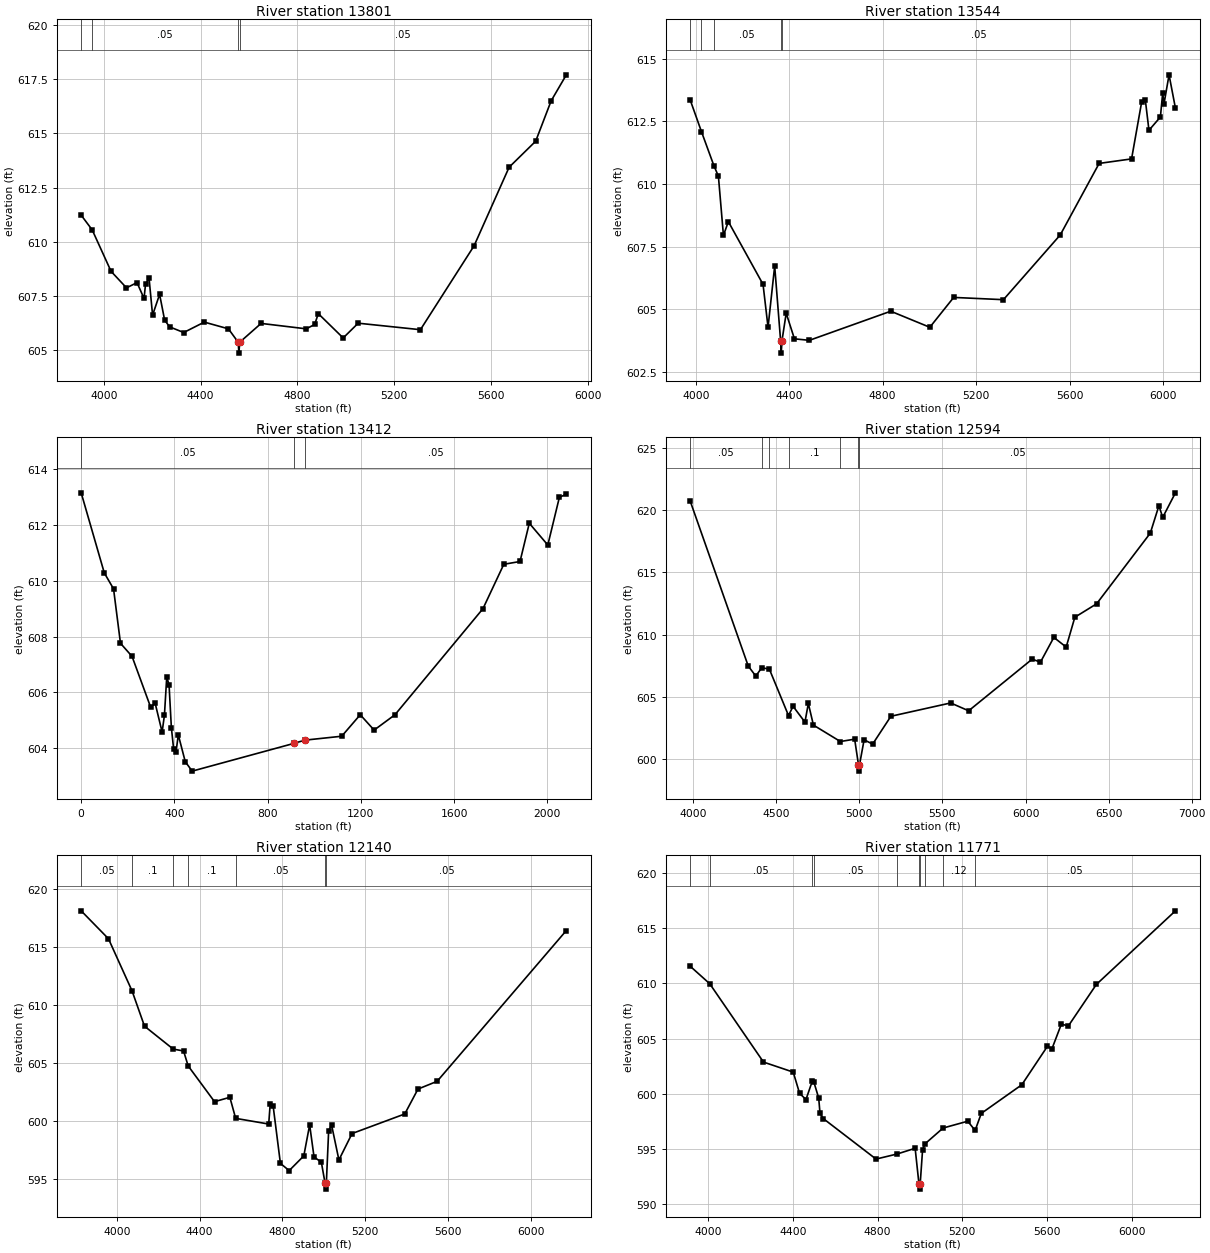
Type RM Length L Ch R = 1 ,13801   ,257,257,257
BEGIN DESCRIPTION:
UNT0004 IN CHRS 16.1
END DESCRIPTION:
XS GIS Cut Line= 4
       3368074.4     10617137.57      3368838.33     10616547.26
      3369272.35      10616443.1      3369775.79     10616130.62
#Sta/Elev= 30
  3906.9  611.23  3952.5  610.55  4030.4  608.64  4094.1  607.88  4137.6  608.12
  4166.6  607.39  4172.9  608.06  4187.4  608.32  4201.9  606.62  4230.9  607.58
  4251.7  606.39  4272.5  606.08  4330.5  605.82  4415.6   606.3  4515.2  605.99
  4555.7  605.37  4558.5  604.87  4561.7  605.37  4650.2  606.24  4836.7  605.99
  4871.5  606.19  4886.5  606.69  4989.3  605.57  5051.3  606.25  5308.4  605.95
  5530.2  609.82  5674.8  613.44  5784.6  614.64  5848.4   616.5  5911.2   617.7
#Mann= 4 ,-1 , 0
  3906.9     .08       0  3952.5     .05       0  4555.7    .035       0
  4561.7     .05       0
Bank Sta=4555.7,4561.7
XS Rating Curve= 0 ,0
Exp/Cntr=0.3,0.1

Type RM Length L Ch R = 1 ,13544   ,132,132,132
BEGIN DESCRIPTION:
UNT0004 IN CHRS 16.2
END DESCRIPTION:
XS GIS Cut Line= 4
      3368248.07     10617397.94      3368855.69     10616825.04
      3369289.71     10616651.43      3369957.64     10616261.08
#Sta/Elev= 30
  3976.8  613.34  4024.5  612.09  4077.9  610.73  4097.2  610.31  4118.7  607.95
  4139.7   608.5  4288.2     606  4309.6  604.29    4338  606.73  4363.3  603.76
    4366  603.26  4369.3  603.76  4387.3  604.85  4422.5  603.83  4486.4  603.77
  4834.7  604.93  5001.9  604.29    5104  605.48  5316.9  605.39  5560.1  607.97
  5726.5  610.82  5865.3     611  5908.3  613.26    5924  613.36  5939.7  612.14
  5988.7  612.67  5998.4  613.62  6004.2   613.2  6025.7  614.35    6053  613.02
#Mann= 5 ,-1 , 0
  3976.8     .05       0  4024.5     .08       0  4077.9     .05       0
  4363.3    .035       0  4369.3     .05       0
Bank Sta=4363.3,4369.3
XS Rating Curve= 0 ,0
Exp/Cntr=0.3,0.1

Type RM Length L Ch R = 1 ,13412   ,818,818,818
XS GIS Cut Line= 4
     3368280.393    10617449.808     3368922.754    10616876.891
    3369059.9077    10616878.627     3369992.199    10616310.919
#Sta/Elev= 30
       0  613.15   99.23  610.28  138.92  609.71  168.69  607.76  218.31  607.29
  297.69  605.48  317.54  605.61  347.31  604.58  357.23  605.18  367.15  606.55
  377.07  606.28     387  604.74  396.92  603.96  406.84  603.86  416.77  604.48
  446.54  603.52   476.3  603.18  911.42  604.17  959.79  604.29 1117.98  604.43
 1197.48   605.2 1257.09  604.65 1346.52   605.2 1724.11     609 1813.54  610.59
  1883.1  610.69 1922.85  612.06 2002.34  611.28 2052.02  612.99 2081.83   613.1
#Mann= 3 , 0 , 0
       0     .05       0  911.42    .035       0  959.79     .05       0
#XS Ineff= 2 , 0
       0  880.36  603.98               0
Permanent Ineff=
       T       F
Bank Sta=911.42,959.79
XS Rating Curve= 0 ,0
Exp/Cntr=0.3,0.1

Type RM Length L Ch R = 1 ,12594   ,454,454,454
BEGIN DESCRIPTION:
UNT0004 IN CHRS 16.0
END DESCRIPTION:
XS GIS Cut Line= 4
      3368215.75     10617756.22      3369005.65     10617595.64
      3369166.24     10616905.54      3370388.68     10616211.95
#Sta/Elev= 30
  3982.3  620.71  4331.1  607.47  4376.6  606.66  4412.5  607.33  4458.3  607.22
  4573.5  603.49  4601.1  604.23  4672.5  602.96  4692.9  604.46  4723.5  602.72
  4885.8   601.4  4971.7  601.59  4994.8  599.52  4997.6  599.02  5000.8  599.52
  5028.6  601.54  5079.9  601.19  5189.8  603.43  5549.6   604.5  5657.8  603.87
    6040  608.02    6090  607.78  6170.5  609.77  6244.8  608.99    6297  611.39
    6428  612.47  6751.1  618.15  6802.9  620.35  6825.9  619.42  6902.4  621.39
#Mann= 7 ,-1 , 0
  3982.3     .05       0  4412.5      .1       0  4458.3     .05       0
  4573.5      .1       0  4885.8     .05       0  4994.8    .035       0
  5000.8     .05       0
Bank Sta=4994.8,5000.8
XS Rating Curve= 0 ,0
Exp/Cntr=0.3,0.1

Type RM Length L Ch R = 1 ,12140   ,369,369,369
BEGIN DESCRIPTION:
UNT0004 IN CHRS 15.0
END DESCRIPTION:
XS GIS Cut Line= 4
      3368393.64     10618007.97      3369200.96     10617821.33
      3369643.89     10617390.57      3370212.27     10616692.84
#Sta/Elev= 30
  3826.9  618.13  3958.8  615.72  4072.9  611.22  4133.2  608.17  4272.1  606.19
  4322.1  606.03  4344.3  604.74  4471.9  601.65    4546  602.03    4574  600.21
  4733.9  599.72  4740.9  601.41    4755  601.32  4790.5  596.32  4832.9   595.7
  4903.6  596.97  4931.9  599.65  4953.1  596.88  4988.5  596.42  5006.6   594.6
  5009.4   594.1  5012.6   594.6  5023.8  599.15  5037.9  599.64  5073.4  596.62
    5137   598.9  5391.9  600.59  5455.8  602.74  5548.5  603.41  6173.3  616.43
#Mann= 7 ,-1 , 0
  3826.9     .05       0  4072.9      .1       0  4272.1     .05       0
  4344.3      .1       0    4574     .05       0  5006.6    .035       0
  5012.6     .05       0
Bank Sta=5006.6,5012.6
XS Rating Curve= 0 ,0
Exp/Cntr=0.3,0.1

Type RM Length L Ch R = 1 ,11771   ,513,513,513
BEGIN DESCRIPTION:
UNT0004 IN CHRS 14.0
END DESCRIPTION:
XS GIS Cut Line= 4
       3368697.5     10618142.51      3369309.47     10618099.11
      3369964.85      10617547.9       3370303.4     10616801.35
#Sta/Elev= 30
  3916.1  611.56  4007.8  609.98  4261.6  602.86  4401.9  601.95    4432  600.02
  4462.1  599.46  4492.8  601.18  4499.8  601.02  4522.2  599.59  4528.4  598.19
  4544.3  597.72  4792.7  594.05  4892.1  594.51  4977.3  595.03  4995.2  591.82
    4998  591.32  5001.2  591.82  5012.5  594.91  5024.8  595.45  5109.2  596.87
  5225.6  597.49  5260.3  596.65  5289.5   598.2  5480.7   600.8  5601.5  604.29
  5623.4  604.09  5667.4  606.31  5700.3  606.14  5832.4  609.91  6205.7   616.6
#Mann= 10 ,-1 , 0
  3916.1      .1       0  4007.8     .05       0  4492.8     .08       0
  4499.8     .05       0  4892.1     .12       0  4995.2     .07       0
  5001.2     .12       0  5024.8     .16       0  5109.2     .12       0
  5260.3     .05       0
Bank Sta=4995.2,5001.2
XS Rating Curve= 0 ,0
Exp/Cntr=0.3,0.1

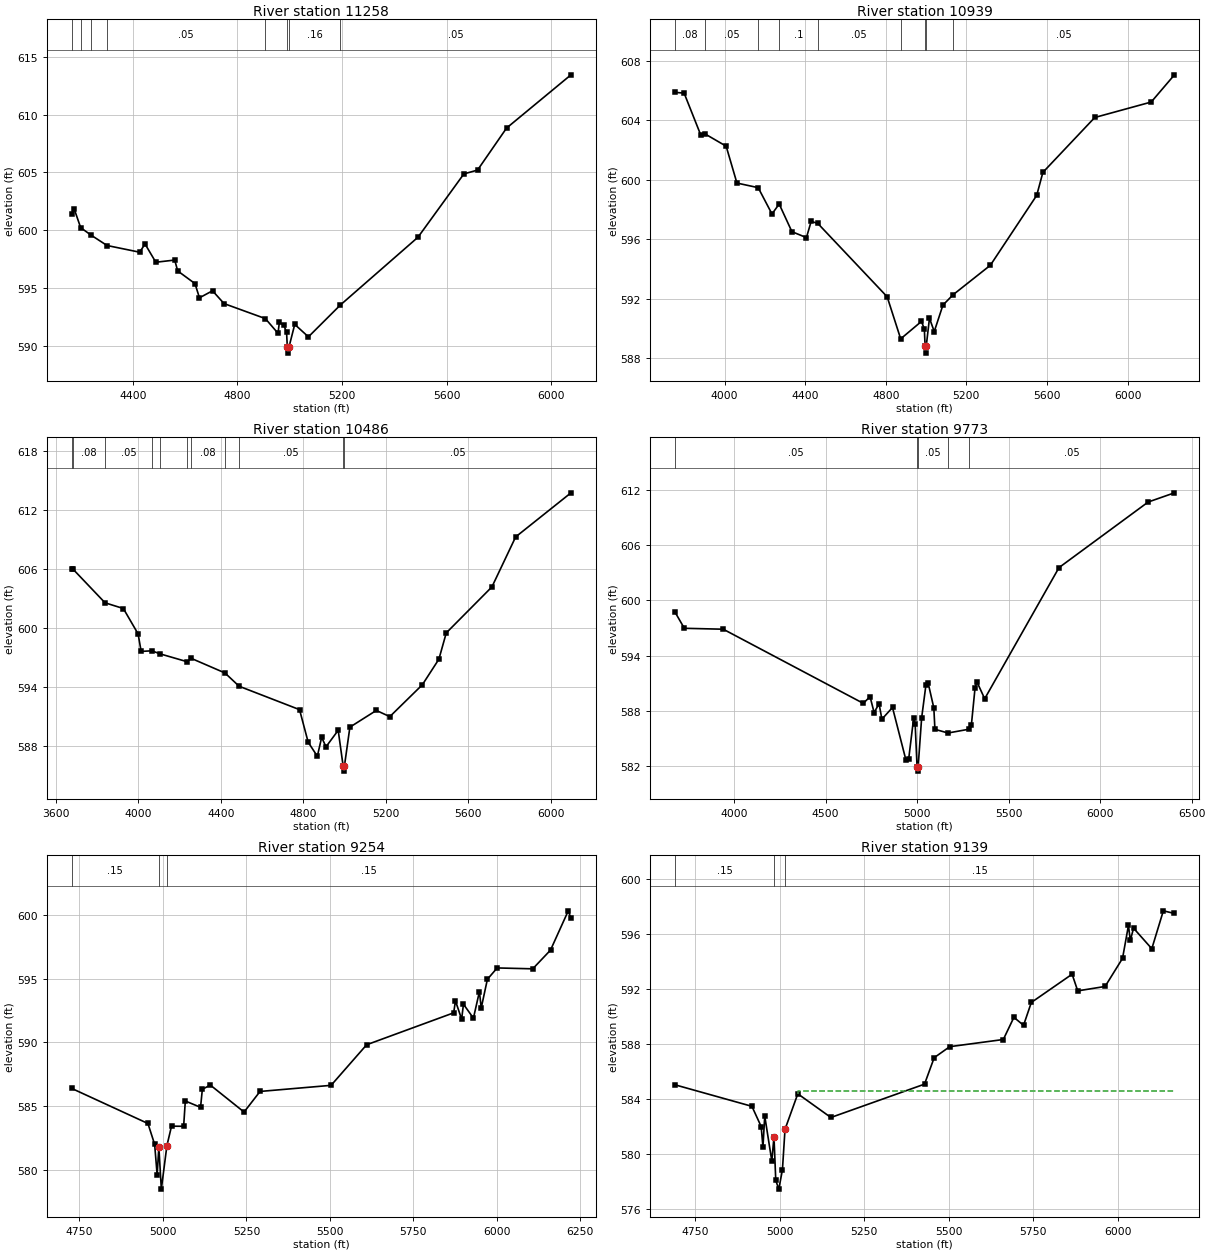
Type RM Length L Ch R = 1 ,11258   ,319,319,319
BEGIN DESCRIPTION:
UNT0004 IN CHRS 13.0
END DESCRIPTION:
XS GIS Cut Line= 3
      3369825.97     10618841.29      3370138.46     10617764.91
       3370368.5     10617009.69
#Sta/Elev= 30
  4165.5  601.42  4175.5  601.81    4200  600.21  4238.4  599.58  4300.9  598.66
  4425.7  598.08  4446.3  598.79  4487.6  597.21  4559.9   597.4  4571.2  596.46
  4637.4  595.36  4654.5  594.13  4704.5  594.74  4748.5  593.63  4906.6  592.33
    4955  591.06  4960.2     592  4977.3  591.75  4987.8  591.14  4990.7  589.84
  4993.5  589.34  4996.7  589.84    5019  591.83  5071.3  590.75  5193.7  593.51
  5490.6  599.38  5666.1  604.86  5718.3  605.19  5829.4  608.83  6075.8  613.44
#Mann= 8 ,-1 , 0
  4165.5     .08       0    4200     .05       0  4238.4     .08       0
  4300.9     .05       0  4906.6     .16       0  4990.7     .07       0
  4996.7     .16       0  5193.7     .05       0
Bank Sta=4990.7,4996.7
XS Rating Curve= 0 ,0
Exp/Cntr=0.3,0.1

Type RM Length L Ch R = 1 ,10939   ,453,453,453
BEGIN DESCRIPTION:
UNT0004 IN CHRS 12.0
END DESCRIPTION:
XS GIS Cut Line= 3
      3369899.75     10619297.02      3370281.69     10618359.53
      3370776.48     10616979.34
#Sta/Elev= 30
  3754.4  605.89  3799.2  605.84  3882.1  603.01  3903.7  603.09  4007.8  602.27
  4061.3  599.79  4166.8  599.48  4235.3  597.71    4271  598.38  4334.2  596.52
  4406.3  596.12  4429.7  597.21  4462.3  597.08    4807  592.14  4874.1  589.31
  4976.9  590.48  4991.5  589.99  4995.2  588.85  4997.9  588.35  5001.2  588.85
    5017   590.7  5040.7   589.8  5083.8  591.58  5133.6  592.27  5319.2  594.26
  5549.2  598.96    5580  600.51  5837.4   604.2  6117.6  605.24  6232.9  607.07
#Mann= 9 ,-1 , 0
  3754.4     .08       0  3903.7     .05       0  4166.8     .08       0
    4271      .1       0  4462.3     .05       0  4874.1     .16       0
  4995.2     .07       0  5001.2     .16       0  5133.6     .05       0
Bank Sta=4995.2,5001.2
XS Rating Curve= 0 ,0
Exp/Cntr=0.3,0.1

Type RM Length L Ch R = 1 ,10486   ,713,713,713
BEGIN DESCRIPTION:
UNT0004 IN CHRS 11.0
END DESCRIPTION:
XS GIS Cut Line= 2
      3370012.62     10619401.15       3371401.5     10617417.67
#Sta/Elev= 30
  3676.9  606.04  3682.7  606.03    3839  602.59  3927.7  602.01  3999.2  599.43
    4014  597.65  4065.8  597.71  4107.4  597.39  4237.3   596.6  4256.1  596.95
  4420.3  595.46    4489  594.11  4782.1  591.73  4823.9  588.42  4868.4  586.99
  4889.3  588.92  4910.3  587.95  4969.5  589.63  4993.6  585.98  4996.3  585.48
  4999.6  585.98  5026.2  589.95  5154.4  591.65  5219.8  591.02  5377.6  594.26
  5457.8  596.86  5493.5  599.53    5715  604.21  5830.1  609.29  6098.3  613.77
#Mann= 11 ,-1 , 0
  3676.9      .1       0  3682.7     .08       0    3839     .05       0
  4065.8      .1       0  4107.4     .05       0  4237.3      .1       0
  4256.1     .08       0  4420.3      .1       0    4489     .05       0
  4993.6    .035       0  4999.6     .05       0
Bank Sta=4993.6,4999.6
XS Rating Curve= 0 ,0
Exp/Cntr=0.3,0.1

Type RM Length L Ch R = 1 ,9773    ,519,519,519
BEGIN DESCRIPTION:
UNT0004 IN CHRS 9.0
END DESCRIPTION:
XS GIS Cut Line= 4
      3370516.05     10619757.12      3371206.17     10618962.83
      3371470.93     10618533.14      3371614.16     10617369.96
#Sta/Elev= 30
  3677.1  598.71  3727.6  596.97  3940.3  596.87  4705.6  588.82  4742.5  589.55
  4764.7  587.82  4791.8  588.78  4807.2   587.1  4865.2  588.37  4938.5  582.67
  4953.9  582.82  4981.1  587.26  4989.1  586.55  4999.4  581.96  5002.1  581.46
  5005.4  581.96  5024.4  587.23  5047.9  590.82  5060.3     591  5091.1  588.32
    5097     586  5168.6   585.6  5285.6  586.02    5296  586.42  5316.1  590.45
  5326.2  591.17    5369  589.32  5775.1  603.56  6262.3  610.68    6406  611.68
#Mann= 5 ,-1 , 0
  3677.1     .05       0  4999.4    .035       0  5005.4     .05       0
  5168.6     .16       0  5285.6     .05       0
Bank Sta=4999.4,5005.4
XS Rating Curve= 0 ,0
Exp/Cntr=0.3,0.1

Type RM Length L Ch R = 1 ,9254    ,115,115,115
BEGIN DESCRIPTION:
UNT0004 IN CHRS 10.0
END DESCRIPTION:
XS GIS Cut Line= 3
      3371505.61     10618949.81      3371874.57     10618902.06
      3372911.87     10618472.39
#Sta/Elev= 30
  4726.9  586.38  4955.3  583.62  4975.4  581.98  4982.9  579.58    4988  581.78
  4995.4  578.46 5012.12  581.88  5025.9  583.41  5062.2   583.4  5067.2  585.39
  5112.8  584.89  5118.2  586.31  5142.1  586.64  5243.1  584.52  5290.9  586.14
  5503.6  586.62    5610  589.81  5870.5  592.32  5875.9  593.26  5894.4  591.82
  5899.8     593  5929.7   591.9  5947.6  593.99    5953   592.7  5971.5  594.96
  6000.8  595.85  6107.2  595.78  6160.4  597.25  6213.6  600.34  6221.7  599.74
#Mann= 3 , 0 , 0
  4726.9     .15       0    4988     .12       0 5012.12     .15       0
#XS Ineff= 2 , 0
       0                 5187.21       0  585.67
Permanent Ineff=
       F       T
Bank Sta=4988,5012.12
XS Rating Curve= 0 ,0
Exp/Cntr=0.3,0.1

Type RM Length L Ch R = 1 ,9139    ,495,495,495
BEGIN DESCRIPTION:
UNT0004 IN CHRS 9.1
END DESCRIPTION:
XS GIS Cut Line= 4
      3371499.49     10619034.21        3371723.     10619047.23
      3372157.03     10618912.69       3372881.9     10618580.64
#Sta/Elev= 30
  4691.3  585.03  4918.3  583.47  4945.7     582  4950.9  580.51  4956.2  582.77
  4977.1   579.5  4983.5  581.26  4988.8  578.09  4997.8  577.46  5008.5  578.87
  5016.1   581.8  5053.9  584.38  5151.7  582.66  5428.4  585.08  5456.9     587
  5502.9   587.8  5661.2  588.32  5692.5  589.93    5721  589.35    5744  591.01
  5864.5  593.06  5881.1  591.85    5962  592.17  6013.5  594.21    6031   596.6
  6036.5  595.51  6046.1   596.4    6100  594.91  6134.1  597.66  6166.9  597.47
#Mann= 3 ,-1 , 0
  4691.3     .15       0  4983.5     .12       0  5016.1     .15       0
#XS Ineff= 2 , 0
       0                 5053.64       0  584.58
Permanent Ineff=
       F       T
Bank Sta=4983.5,5016.1
XS Rating Curve= 0 ,0
Exp/Cntr=0.3,0.1

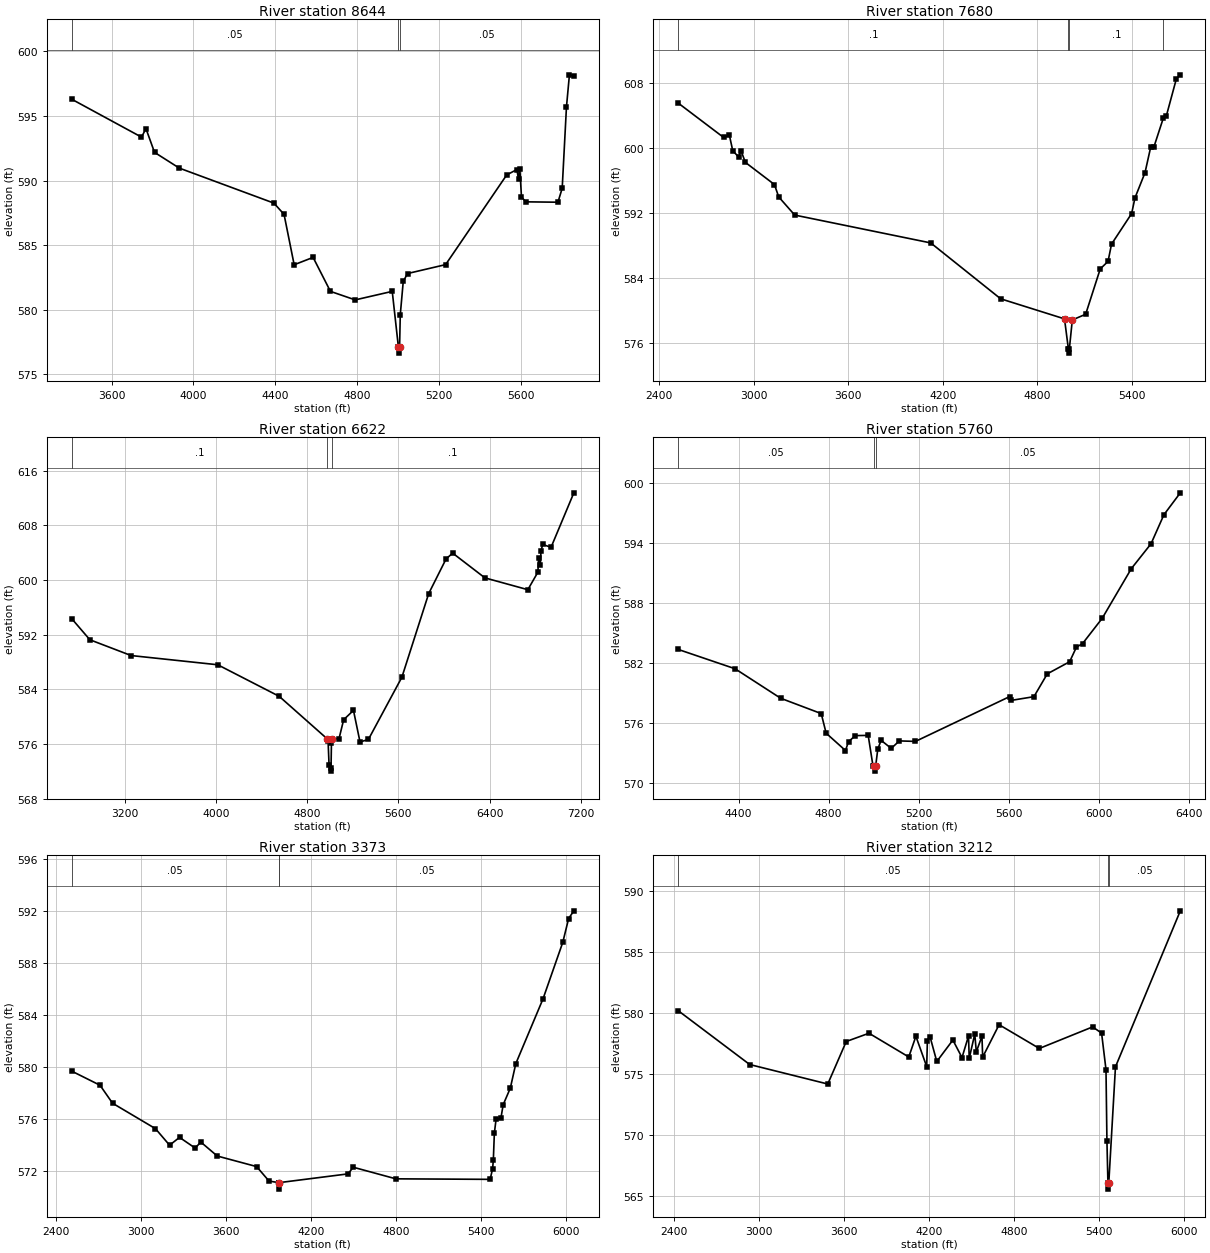
Type RM Length L Ch R = 1 ,8644    ,964,964,964
BEGIN DESCRIPTION:
UNT0004 IN CHRS 8.0
END DESCRIPTION:
XS GIS Cut Line= 3
      3371042.13     10620191.62      3372242.11     10619191.64
      3372942.07     10618641.67
#Sta/Elev= 30
  3405.5   596.3  3745.9  593.37    3768  594.02  3809.6  592.19  3930.7  590.97
  4392.8  588.26  4442.3  587.39  4491.7  583.49  4584.2  584.06  4668.8  581.43
  4789.8  580.77  4970.7  581.43  5000.6  577.15  5003.4  576.65  5006.6  577.15
    5010  579.63  5024.5   582.2  5045.3  582.81  5231.4   583.5  5529.7  590.44
  5579.4  590.86  5587.5  590.12  5593.9  590.92  5601.9  588.74  5622.8  588.36
    5780  588.33  5800.8  589.41  5821.6   595.7  5836.1  598.19  5857.7  598.09
#Mann= 3 ,-1 , 0
  3405.5     .05       0  5000.6     .03       0  5006.6     .05       0
Bank Sta=5000.6,5006.6
XS Rating Curve= 0 ,0
Exp/Cntr=0.3,0.1

Type RM Length L Ch R = 1 ,7680    ,1058,1058,1058
BEGIN DESCRIPTION:
UNT0004 IN CHRS 5.0
END DESCRIPTION:
XS GIS Cut Line= 3
      3370989.15      10620963.7      3372726.88      10619919.6
      3373614.99     10619179.87
#Sta/Elev= 30
  2522.7  605.57  2810.1  601.33    2847   601.6  2868.4  599.68  2905.3  598.92
  2920.8  599.69  2948.1  598.25  3132.6  595.51  3159.8  593.98  3261.1  591.74
  4123.6   588.3  4566.7   581.4  4971.6  578.92  4996.3  575.19    4999  574.69
  5002.3  575.19  5021.1  578.79  5105.7  579.49  5198.1  585.09  5247.6  586.02
  5269.7  588.15  5397.3  591.93  5418.1  593.85  5481.9  596.97  5518.3  600.16
  5539.2   600.2  5598.4  603.74  5617.3  603.99  5681.1  608.59  5705.8  609.06
#Mann= 4 ,-1 , 0
  2522.7      .1       0  4996.3     .05       0  5002.3      .1       0
  5598.4      .1       0
Bank Sta=4971.6,5021.1
XS Rating Curve= 0 ,0
Exp/Cntr=0.3,0.1

Type RM Length L Ch R = 1 ,6622    ,862,862,862
BEGIN DESCRIPTION:
UNT0004 IN CHRS 4.0
END DESCRIPTION:
XS GIS Cut Line= 4
      3371644.59     10621349.96      3373406.69     10620646.85
      3374444.02     10619913.35      3375103.72     10618867.38
#Sta/Elev= 30
  2734.8  594.34  2893.6  591.26  3255.4  588.95  4015.4   587.6  4554.4  582.98
  4977.1  576.73  4983.2  576.44  4991.9  572.88  5005.8  572.03  5009.1  572.53
  5012.8   576.2  5018.9  576.78  5078.1  576.71  5119.9  579.56    5206  580.92
  5263.3   576.3  5336.6  576.66  5630.7  585.78  5865.8  598.02  6018.8  603.11
  6076.4  603.94  6358.9  600.32  6735.5  598.59  6823.8  601.16  6829.7  603.22
    6845  602.27  6850.9  604.28  6866.2  605.21  6939.1  604.79  7139.1  612.77
#Mann= 3 , 0 , 0
  2734.8      .1       0  4977.1    .033       0  5018.9      .1       0
Bank Sta=4977.1,5018.9
XS Rating Curve= 0 ,0
Exp/Cntr=0.3,0.1

Type RM Length L Ch R = 1 ,5760    ,2387,2387,2387
BEGIN DESCRIPTION:
UNT0004 IN CHRS 3.0
END DESCRIPTION:
XS GIS Cut Line= 3
        3373531.     10621269.51      3375388.67     10620049.87
       3375397.2     10620049.87
#Sta/Elev= 30
  4131.7  583.37  4384.2  581.44    4587  578.49    4767  576.96  4788.9     575
  4874.7  573.27  4888.3  574.15  4918.5  574.76  4975.7  574.78  4996.8  571.76
  5002.9  571.71  5005.7  571.21  5008.9  571.71  5018.3   573.4    5033  574.29
  5078.1  573.48    5114  574.23  5185.7  574.18  5604.4  578.66  5611.6  578.28
  5712.1  578.65  5771.4  580.93  5870.7  582.14  5900.9   583.6    5928  583.95
  6015.4  586.48    6145  591.45  6232.4  593.93  6289.6  596.83  6362.5  599.02
#Mann= 3 ,-1 , 0
  4131.7     .05       0  5002.9    .033       0  5008.9     .05       0
Bank Sta=5002.9,5008.9
XS Rating Curve= 0 ,0
Exp/Cntr=0.3,0.1

Type RM Length L Ch R = 1 ,3373    ,161,161,161
BEGIN DESCRIPTION:
UNT0004 IN CHRS 2.2
END DESCRIPTION:
XS GIS Cut Line= 6
      3374053.21     10621276.87      3375829.79     10621407.65
      3376223.89      10621482.3       3376440.9     10621461.47
      3376758.61     10621109.04      3376833.85     10620455.04
#Sta/Elev= 30
  2510.5  579.69  2709.9  578.61  2798.4  577.23  3101.1  575.28    3201  574.01
  3271.2  574.61  3381.4  573.79  3421.5  574.25  3537.5  573.18  3815.2  572.37
  3902.9  571.26  3970.1  571.14  3972.9  570.64  3976.1  571.14  4460.7  571.81
  4497.4  572.32  4798.5  571.43  5463.8  571.39  5481.3  572.21  5486.5   572.9
  5493.6  574.94  5505.6  575.99  5539.7  576.08    5556  577.12  5606.3  578.39
  5645.1  580.27  5837.2  585.24  5976.5  589.57  6017.9   591.4  6054.7  591.99
#Mann= 3 ,-1 , 0
  2510.5     .05       0  3970.1    .033       0  3976.1     .05       0
Bank Sta=3970.1,3976.1
XS Rating Curve= 0 ,0
Exp/Cntr=0.3,0.1

Type RM Length L Ch R = 1 ,3212    ,133,133,133
BEGIN DESCRIPTION:
UNT0004 IN CHRS 2.0
END DESCRIPTION:
XS GIS Cut Line= 6
       3374148.7     10621368.01      3375925.28      10621498.8
      3376319.37     10621573.45      3376536.39     10621552.62
       3376854.1     10621200.19      3376929.38     10620545.68
#Sta/Elev= 30
  2430.5  580.21  2935.1  575.79  3486.3  574.19  3616.6  577.68  3777.2  578.36
  4058.1  576.41  4108.4  578.11  4184.6  575.62  4189.6  577.76  4207.8  578.09
  4255.9  576.04  4369.5   577.8    4434  576.36  4479.8  578.13  4484.9   576.3
    4524  578.29    4535  576.84  4574.8  578.11  4579.9   576.4  4695.8  579.06
  4979.9  577.11  5356.3  578.88  5419.4  578.37  5450.5  575.37  5457.1  569.51
  5464.2  566.06  5466.9  565.56  5470.2  566.06  5517.4   575.6  5975.2  588.41
#Mann= 3 ,-1 , 0
  2430.5     .05       0  5464.2     .03       0  5470.2     .05       0
Bank Sta=5464.2,5470.2
XS Rating Curve= 0 ,0
Exp/Cntr=0.3,0.1

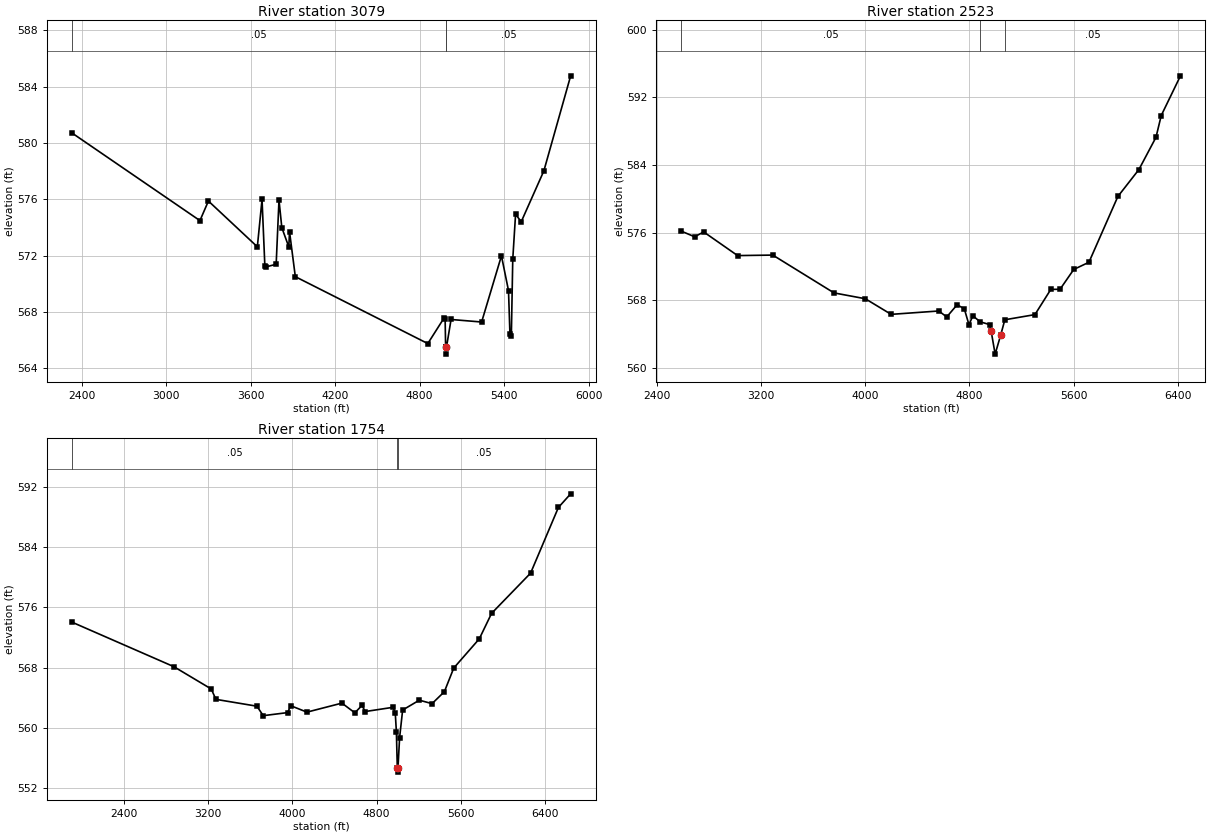
Type RM Length L Ch R = 1 ,3079    ,556,556,556
BEGIN DESCRIPTION:
UNT0004 IN CHRS 2.01
END DESCRIPTION:
XS GIS Cut Line= 6
      3374222.47      10621485.2      3375999.06     10621615.98
      3376393.16     10621690.64      3376610.17      10621669.8
      3376927.88     10621317.37      3377003.25     10620661.88
#Sta/Elev= 30
  2327.4  580.73  3239.1  574.49  3299.3  575.88    3647  572.63  3680.3  575.99
  3700.4  571.27  3710.5  571.21  3780.7  571.39  3800.8  575.95  3820.9  573.99
  3870.6  572.62  3875.6  573.71  3916.8  570.51    4858  565.76  4975.1   567.6
  4981.1  567.53  4984.8  565.51  4987.5  565.01  4990.8  565.51  5023.4  567.47
  5240.5  567.29  5381.3  571.99  5431.5  569.52  5441.6  566.45  5451.6   566.3
  5461.7  571.75  5481.7  574.94  5521.9  574.41  5682.6  578.02  5873.1  584.77
#Mann= 3 ,-1 , 0
  2327.4     .05       0  4984.8     .03       0  4990.8     .05       0
Bank Sta=4984.8,4990.8
XS Rating Curve= 0 ,0
Exp/Cntr=0.3,0.1

Type RM Length L Ch R = 1 ,2523    ,550,550,550
BEGIN DESCRIPTION:
UNT0004 IN CHRS 1.0
END DESCRIPTION:
XS GIS Cut Line= 4
      3375450.92     10622291.82      3377056.87     10622352.58
      3377425.79     10621371.68      3377265.38     10620205.44
#Sta/Elev= 30
  2588.8  576.16  2690.1   575.5  2760.1  576.07  3020.3  573.27  3290.5  573.33
  3760.8  568.85    4001  568.16  4199.4  566.31  4565.7  566.71  4626.1     566
  4706.1  567.45  4761.3  566.96  4796.8  565.09  4827.2  566.14  4882.2  565.43
  4955.5   565.1  4967.5  564.31  4997.9   561.6  5040.9  563.87  5072.4  565.67
  5303.5  566.28  5425.6  569.27  5496.3  569.28  5601.7  571.63  5718.3  572.48
  5940.4  580.27  6101.9  583.46  6233.1  587.28  6273.5  589.86  6421.1  594.56
#Mann= 3 ,-1 , 0
  2588.8     .05       0  4882.2     .03       0  5072.4     .05       0
Bank Sta=4967.5,5040.9
XS Rating Curve= 0 ,0
Exp/Cntr=0.3,0.1

Type RM Length L Ch R = 1 ,1754    ,0,0,0
BEGIN DESCRIPTION:
UNT0004 IN CHRS 1.0
END DESCRIPTION:
XS GIS Cut Line= 4
      3375920.47     10622375.27      3377947.35     10622392.63
      3378342.32     10622166.93      3377439.55      10620092.3
#Sta/Elev= 30
  1900.5  574.06  2872.2  568.12    3228  565.15  3272.2  563.77  3662.2  562.86
  3722.2   561.6  3954.9  562.01  3982.3  562.93  4137.8  562.07  4470.3  563.27
  4592.9  561.98  4660.8  562.96  4692.1  562.15  4955.2  562.71  4977.2     562
  4987.9  559.49    4997  554.59  4999.8  554.09    5003  554.59  5018.6  558.67
  5047.5  562.35  5206.1  563.66  5327.1   563.2  5444.3  564.79  5533.2  567.93
  5776.2  571.82  5893.1  575.21  6263.9  580.56  6528.4   589.3  6644.9  591.11
#Mann= 3 ,-1 , 0
  1900.5     .05       0    4997     .03       0    5003     .05       0
Bank Sta=4997,5003
XS Rating Curve= 0 ,0
Exp/Cntr=0.3,0.1

Chan Stop Cuts=-1
Use User Specified Reach Order=0
Composite Channel Slope=5