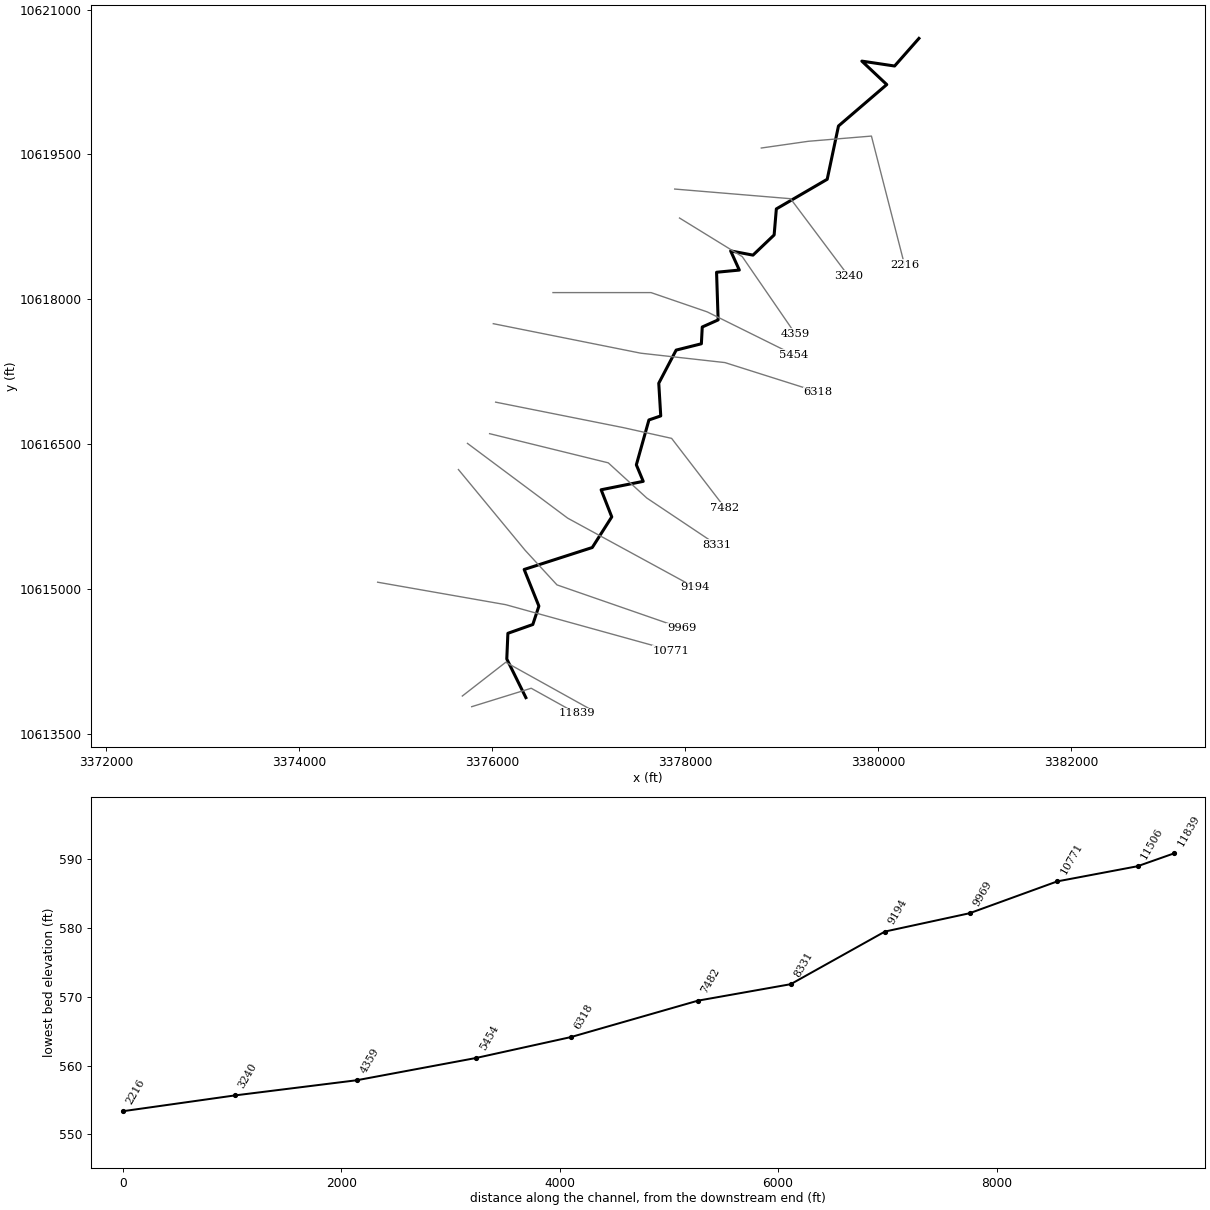
--- UNT0005 IN CHRS.prj (project) ---

Proj Title=UNT0005 IN CHRS Base Level Engineering
Current Plan=p01
Default Exp/Contr=0.3,0.1
English Units
Geom File=g01
Flow File=f01
Plan File=p01
BEGIN DESCRIPTION:
UNT0005 IN CHRS
END DESCRIPTION:

--- UNT0005 IN CHRS.p01 (plan) ---

Plan Title=Multiple Run
Short Identifier=Multiple
Geom File=g01
Flow File=f01
Subcritical Flow
K Sum by GR= 0
Std Step Tol= 0.01
Critical Tol= 0.01
Num of Std Step Trials= 20
Max Error Tol= 0.3
Flow Tol Ratio= 0.001
Split Flow NTrial= 30
Split Flow Tol= 0.02
Split Flow Ratio= 0.02
Log Output Level= 0
Friction Slope Method= 1
Unsteady Friction Slope Method= 2
Unsteady Bridges Friction Slope Method= 1
Parabolic Critical Depth
Global Vel Dist=  1 , 1 , 1
Global Log Level= 0
CheckData=True
Encroach Param= -1, 0, 0, 0
BEGIN DESCRIPTION:
Multiple Run
END DESCRIPTION:

--- UNT0005 IN CHRS.f01 (steady flow) ---

Flow Title=Multiple
Number of Profiles=7
Profile Names=10-year,25-year,50-year,1pct_min,100-year,1pct_plu,500-year
River Rch & RM= UNT0005 IN CHRS,Reach-1,11839
     357     449     516     432     584     789     746
River Rch & RM= UNT0005 IN CHRS,Reach-1,10771
     566     727     848     720     973    1316    1279
River Rch & RM= UNT0005 IN CHRS,Reach-1,3240
     604     778     909     772    1044    1412    1376
Boundary for River Rch & Prof#=UNT0005 IN CHRS,Reach-1,1
Up Type=0
Dn Type=3
Dn Slope=0.005
Boundary for River Rch & Prof#=UNT0005 IN CHRS,Reach-1,2
Up Type=0
Dn Type=3
Dn Slope=0.005
Boundary for River Rch & Prof#=UNT0005 IN CHRS,Reach-1,3
Up Type=0
Dn Type=3
Dn Slope=0.005
Boundary for River Rch & Prof#=UNT0005 IN CHRS,Reach-1,4
Up Type=0
Dn Type=3
Dn Slope=0.005
Boundary for River Rch & Prof#=UNT0005 IN CHRS,Reach-1,5
Up Type=0
Dn Type=3
Dn Slope=0.005
Boundary for River Rch & Prof#=UNT0005 IN CHRS,Reach-1,6
Up Type=0
Dn Type=3
Dn Slope=0.005
Boundary for River Rch & Prof#=UNT0005 IN CHRS,Reach-1,7
Up Type=0
Dn Type=3
Dn Slope=0.005

--- UNT0005 IN CHRS.g01 (geometry) ---

Geom Title=Existing Conditions

River Reach=UNT0005 IN CHRS,Reach-1
Reach XY= 30
      3376350.52     10613875.10      3376152.74     10614275.30
      3376164.24     10614541.12      3376422.25     10614632.20
      3376485.30     10614822.80      3376332.75     10615202.10
      3377038.33     10615429.59      3377240.09     10615746.74
      3377130.07     10616027.54      3377566.11     10616114.68
      3377494.81     10616285.71      3377625.04     10616750.49
      3377747.50     10616792.26      3377727.01     10617130.78
      3377907.15     10617473.90      3378168.37     10617539.33
      3378177.54     10617713.17      3378342.02     10617786.56
      3378325.78     10618280.00      3378561.53     10618302.60
      3378471.63     10618501.21      3378702.90     10618457.30
      3378922.18     10618666.25      3378944.98     10618935.88
      3379471.86     10619242.86      3379588.61     10619794.51
      3380088.70     10620223.59      3379830.62     10620466.40
      3380169.85     10620415.71      3380422.11     10620701.64

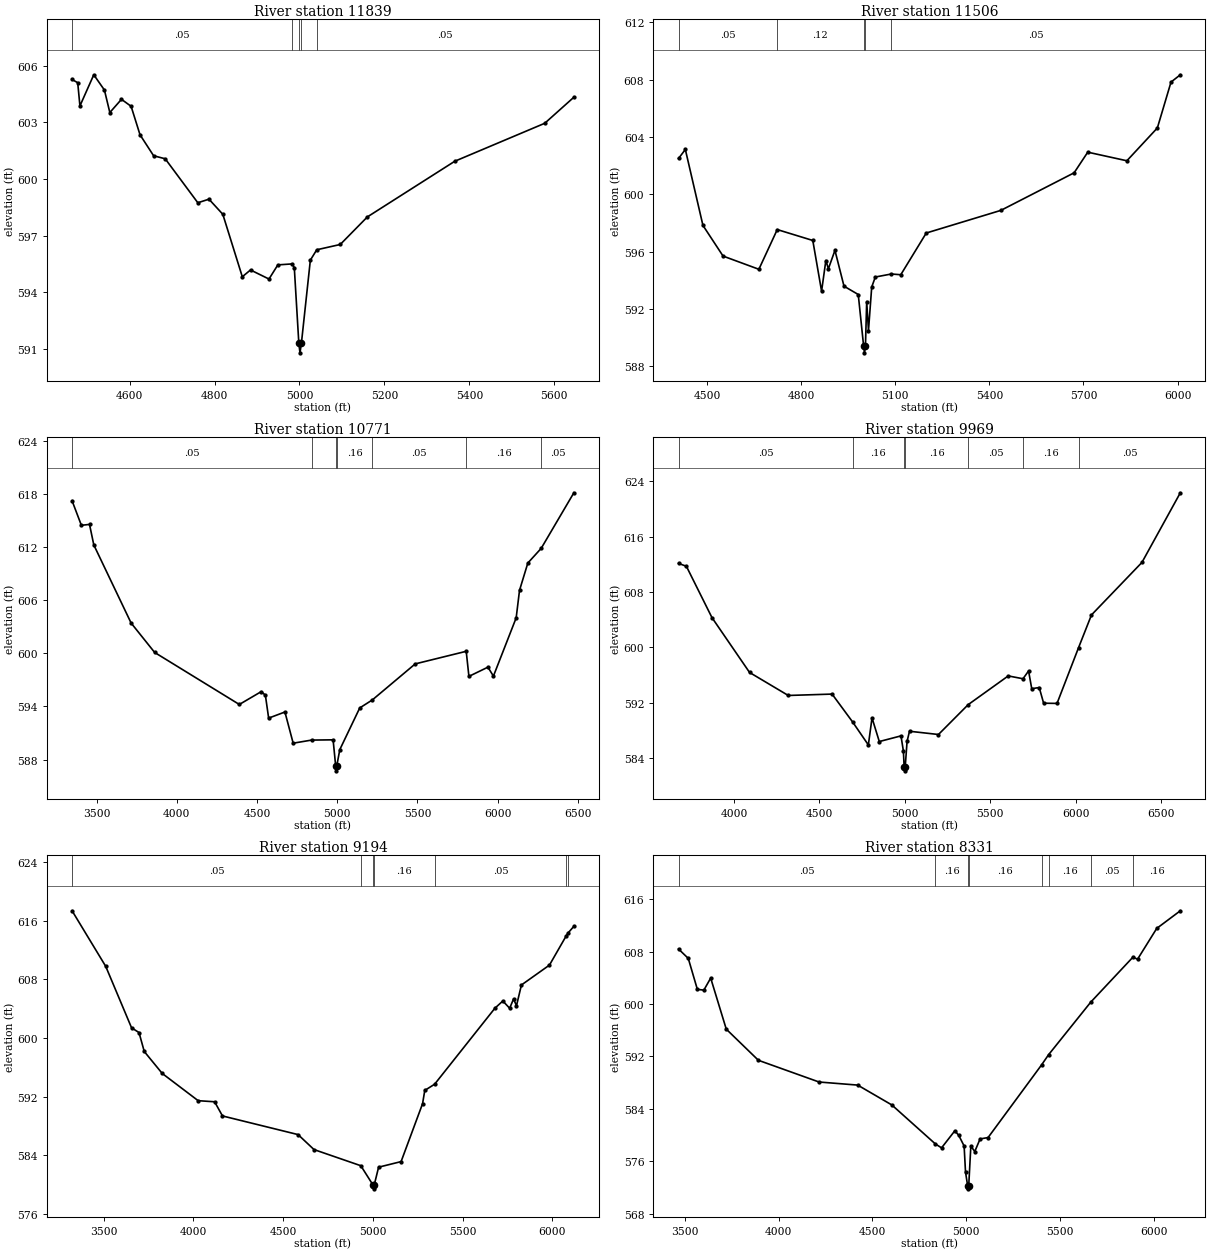
Type RM Length L Ch R = 1,11839,333,333,333
BEGIN DESCRIPTION:
UNT0005 IN CHRS 19.1
END DESCRIPTION:
XS GIS Cut Line= 3
      3375789.30     10613781.21      3376405.60     10613972.18
      3376874.32     10613711.78
#Sta/Elev= 30
  4464.6  605.27  4477.9  605.10  4483.1  603.87  4515.7  605.52  4540.8  604.71
  4553.5  603.52  4580.9  604.22  4603.6  603.85  4624.6  602.34  4656.6  601.23
  4683.9  601.07  4760.7  598.74  4786.9  598.93  4819.5  598.13  4865.4  594.82
  4884.7  595.18  4928.2  594.70  4949.1  595.45  4982.4  595.50  4987.8  595.31
  4998.5  591.29  5001.2  590.79  5004.5  591.29  5025.6  595.70  5040.7  596.25
  5096.0  596.53  5159.8  597.99  5365.7  600.94  5577.4  602.95  5646.0  604.33
#Mann=5,-1,0
  4464.6    0.05       0  4982.4    0.12       0  4998.5    0.07       0
  5004.5    0.12       0  5040.7    0.05       0
Bank Sta=4998.5,5004.5
Exp/Cntr=0.3,0.1

Type RM Length L Ch R = 1,11506,735,735,735
BEGIN DESCRIPTION:
UNT0005 IN CHRS 19.0
END DESCRIPTION:
XS GIS Cut Line= 3
      3375692.13     10613891.66      3376142.11     10614241.64
      3377042.09     10613741.65
#Sta/Elev= 30
  4409.3  602.49  4431.0  603.12  4487.1  597.82  4551.3  595.68  4665.4  594.76
  4724.0  597.53  4837.3  596.77  4865.3  593.23  4878.9  595.37  4887.1  594.80
  4907.9  596.08  4936.8  593.58  4982.2  593.00  4999.2  589.43  5002.0  588.93
  5005.2  589.43  5009.1  592.51  5014.8  590.48  5025.1  593.52  5036.6  594.22
  5087.5  594.43  5117.8  594.38  5199.0  597.29  5436.9  598.87  5670.3  601.49
  5713.8  602.93  5838.5  602.33  5935.7  604.62  5979.2  607.82  6008.9  608.33
#Mann=5,-1,0
  4409.3    0.05       0  4724.0    0.12       0  4999.2    0.07       0
  5005.2    0.12       0  5087.5    0.05       0
Bank Sta=4999.2,5005.2
Exp/Cntr=0.3,0.1

Type RM Length L Ch R = 1,10771,802,802,802
BEGIN DESCRIPTION:
UNT0005 IN CHRS 18.0
END DESCRIPTION:
XS GIS Cut Line= 3
      3374814.98     10615070.33      3376141.40     10614837.68
      3377858.67     10614362.40
#Sta/Elev= 30
  3346.8  617.21  3404.8  614.44  3455.6  614.54  3482.4  612.22  3714.9  603.41
  3861.7  600.09  4389.6  594.22  4526.2  595.67  4552.0  595.27  4572.4  592.68
  4673.9  593.37  4725.3  589.85  4839.9  590.20  4974.3  590.23  4990.6  587.23
  4993.3  586.73  4996.6  587.23  5015.9  589.12  5140.4  593.83  5218.7  594.73
  5486.3  598.80  5804.2  600.22  5821.0  597.39  5939.5  598.43  5973.8  597.42
  6115.7  604.00  6136.5  607.10  6188.3  610.18  6271.7  611.84  6475.3  618.11
#Mann=7,-1,0
  3346.8    0.05       0  4839.9    0.16       0  4990.6    0.07       0
  4996.6    0.16       0  5218.7    0.05       0  5804.2    0.16       0
  6271.7    0.05       0
Bank Sta=4990.6,4996.6
Exp/Cntr=0.3,0.1

Type RM Length L Ch R = 1,9969,775,775,775
BEGIN DESCRIPTION:
UNT0005 IN CHRS 17.0
END DESCRIPTION:
XS GIS Cut Line= 4
      3375651.85     10616236.95      3376342.07     10615401.68
      3376672.65     10615042.54      3377964.31     10614594.63
#Sta/Elev= 30
  3674.6  612.14  3720.6  611.72  3870.4  604.29  4090.6  596.35  4317.2  593.02
  4573.9  593.22  4693.7  589.20  4786.3  585.86  4807.8  589.77  4850.4  586.35
  4977.4  587.17  4991.6  584.97  4995.9  582.61  4998.7  582.11  5001.9  582.61
  5013.1  586.38  5027.3  587.84  5196.9  587.37  5371.3  591.70  5605.6  595.85
  5692.0  595.44  5724.7  596.57  5743.2  594.00  5787.0  594.17  5812.8  591.90
  5891.3  591.87  6017.7  599.96  6093.1  604.68  6388.6  612.28  6613.4  622.36
#Mann=7,-1,0
  3674.6    0.05       0  4693.7    0.16       0  4995.9    0.07       0
  5001.9    0.16       0  5371.3    0.05       0  5692.0    0.16       0
  6017.7    0.05       0
Bank Sta=4995.9,5001.9
Exp/Cntr=0.3,0.1

Type RM Length L Ch R = 1,9194,863,863,863
BEGIN DESCRIPTION:
UNT0005 IN CHRS 15.0
END DESCRIPTION:
XS GIS Cut Line= 3
      3375745.59     10616507.80      3376783.76     10615733.52
      3378101.52     10615015.68
#Sta/Elev= 30
  3324.5  617.33  3512.0  609.76  3655.9  601.39  3697.5  600.74  3726.7  598.16
  3826.8  595.17  4027.0  591.46  4118.7  591.31  4162.5  589.38  4583.6  586.84
  4672.4  584.80  4933.2  582.60  5001.7  579.95  5004.5  579.45  5007.7  579.95
  5032.3  582.40  5157.6  583.16  5277.3  591.05  5289.6  592.86  5344.3  593.70
  5680.8  604.07  5724.5  605.04  5762.5  604.05  5784.3  605.32  5800.5  604.39
  5828.0  607.22  5984.2  609.93  6077.8  613.92  6087.8  614.30  6120.2  615.21
#Mann=7,-1,0
  3324.5    0.05       0  4933.2    0.16       0  5001.7    0.07       0
  5007.7    0.16       0  5344.3    0.05       0  6077.8    0.16       0
  6087.8    0.05       0
Bank Sta=5001.7,5007.7
Exp/Cntr=0.3,0.1

Type RM Length L Ch R = 1,8331,849,849,849
BEGIN DESCRIPTION:
UNT0005 IN CHRS 13.0
END DESCRIPTION:
XS GIS Cut Line= 4
      3375974.69     10616608.53      3377203.90     10616306.43
      3377603.21     10615941.85      3378325.39     10615459.24
#Sta/Elev= 30
  3466.1  608.38  3518.0  606.95  3566.4  602.23  3601.1  602.11  3637.5  603.95
  3720.6  596.16  3891.9  591.41  4215.2  588.10  4421.1  587.63  4603.3  584.60
  4835.6  578.65  4868.3  578.06  4939.3  580.67  4960.2  579.95  4988.6  578.34
  4996.0  574.37  5007.2  572.31  5010.0  571.81  5013.2  572.31  5024.4  578.34
  5045.4  577.50  5073.7  579.42  5116.3  579.63  5401.8  590.72  5438.5  592.25
  5663.7  600.28  5888.3  607.13  5913.3  606.83  6015.4  611.52  6141.2  614.21
#Mann=8,-1,0
  3466.1    0.05       0  4835.6    0.16       0  5007.2    0.07       0
  5013.2    0.16       0  5401.8    0.05       0  5438.5    0.16       0
  5663.7    0.05       0  5888.3    0.16       0
Bank Sta=5007.2,5013.2
Exp/Cntr=0.3,0.1

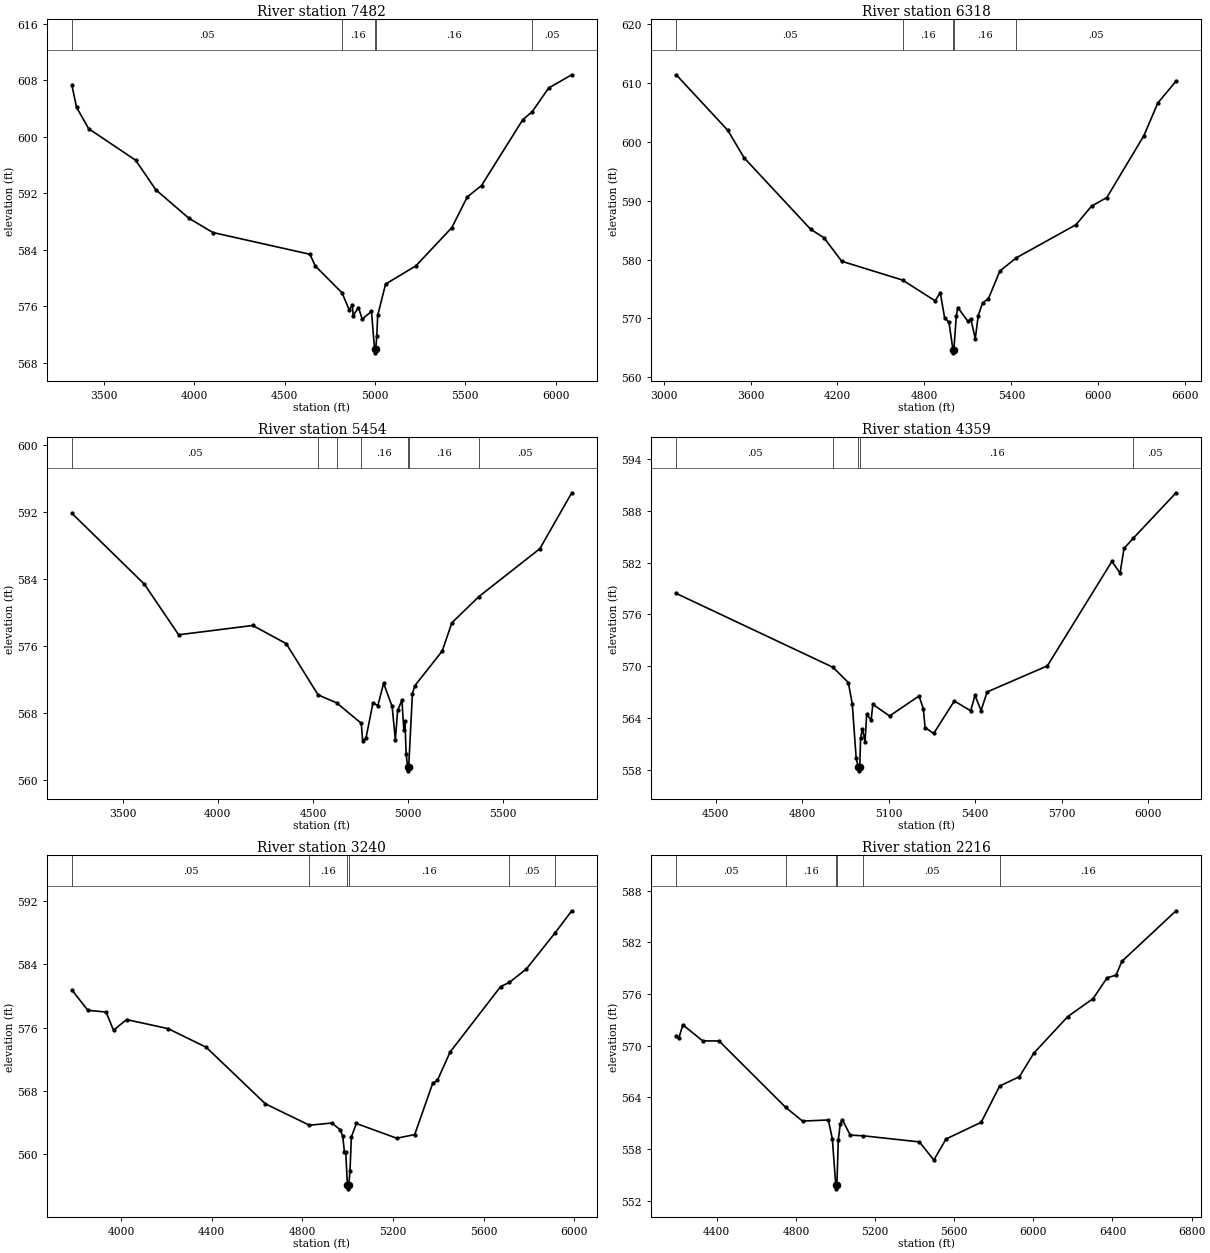
Type RM Length L Ch R = 1,7482,1164,1164,1164
BEGIN DESCRIPTION:
UNT0005 IN CHRS 11.0
END DESCRIPTION:
XS GIS Cut Line= 4
      3376037.28     10616934.90      3377360.15     10616671.02
      3377860.15     10616559.90      3378412.21     10615841.19
#Sta/Elev= 30
  3322.1  607.24  3347.4  604.15  3414.6  601.12  3674.9  596.66  3785.9  592.50
  3969.4  588.46  4102.0  586.44  4639.8  583.36  4669.5  581.70  4817.4  577.91
  4857.4  575.49  4874.2  576.21  4879.3  574.69  4908.6  575.83  4929.1  574.18
  4980.4  575.28  4997.8  569.92  5000.6  569.42  5003.8  569.92  5009.9  571.80
  5015.0  574.73  5058.6  579.15  5226.3  581.72  5425.7  587.14  5510.9  591.47
  5589.7  593.08  5818.1  602.39  5870.5  603.53  5961.4  606.88  6089.5  608.75
#Mann=5,-1,0
  3322.1    0.05       0  4817.4    0.16       0  4997.8    0.07       0
  5003.8    0.16       0  5870.5    0.05       0
Bank Sta=4997.8,5003.8
Exp/Cntr=0.3,0.1

Type RM Length L Ch R = 1,6318,864,864,864
BEGIN DESCRIPTION:
UNT0005 IN CHRS 10.0
END DESCRIPTION:
XS GIS Cut Line= 4
      3376012.97     10617747.40      3377540.71     10617441.85
      3378412.23     10617344.63      3379377.31     10617039.14
#Sta/Elev= 30
  3087.8  611.44  3443.7  601.98  3556.0  597.31  4014.9  585.15  4106.5  583.72
  4229.1  579.71  4649.1  576.51  4873.4  572.98  4908.8  574.37  4939.0  570.08
  4969.2  569.31  4996.4  564.63  4999.1  564.13  5002.4  564.63  5019.5  570.34
  5029.6  571.84  5100.0  569.48  5120.1  569.84  5150.3  566.54  5170.4  570.42
  5200.6  572.64  5240.9  573.35  5320.2  578.06  5432.8  580.29  5845.0  585.93
  5952.6  589.10  6057.5  590.55  6312.9  601.06  6409.8  606.66  6535.0  610.35
#Mann=5,-1,0
  3087.8    0.05       0  4649.1    0.16       0  4996.4    0.07       0
  5002.4    0.16       0  5432.8    0.05       0
Bank Sta=4996.4,5002.4
Exp/Cntr=0.3,0.1

Type RM Length L Ch R = 1,5454,1095,1095,1095
BEGIN DESCRIPTION:
UNT0005 IN CHRS 8.0
END DESCRIPTION:
XS GIS Cut Line= 4
      3376631.25     10618069.40      3377646.92     10618069.40
      3378228.52     10617869.75      3379122.64     10617427.03
#Sta/Elev= 30
  3233.0  591.84  3613.9  583.39  3793.9  577.35  4183.9  578.46  4359.9  576.29
  4527.2  570.18  4624.2  569.23  4754.3  566.79  4761.6  564.73  4779.1  565.01
  4815.7  569.21  4841.6  568.90  4871.9  571.56  4916.7  568.79  4933.6  564.82
  4945.7  568.32  4968.0  569.53  4978.4  565.93  4984.0  567.00  4990.3  563.16
  4997.8  561.61  5000.6  561.11  5003.8  561.61  5023.3  570.29  5035.0  571.24
  5180.0  575.41  5230.7  578.78  5372.9  581.91  5693.3  587.62  5861.3  594.30
#Mann=7,-1,0
  3233.0    0.05       0  4527.2    0.16       0  4624.2    0.05       0
  4754.3    0.16       0  4997.8    0.07       0  5003.8    0.16       0
  5372.9    0.05       0
Bank Sta=4997.8,5003.8
Exp/Cntr=0.3,0.1

Type RM Length L Ch R = 1,4359,1119,1119,1119
BEGIN DESCRIPTION:
UNT0005 IN CHRS 6.0
END DESCRIPTION:
XS GIS Cut Line= 3
      3377942.11     10618841.64      3378592.11     10618441.64
      3379142.09     10617641.67
#Sta/Elev= 30
  4362.9  578.44  4907.0  569.87  4959.9  568.11  4973.5  565.67  4987.0  559.41
  4993.6  558.37  4996.3  557.87  4999.6  558.37  5002.5  561.67  5008.7  562.74
  5017.9  561.26  5023.7  564.45  5039.1  563.74  5045.0  565.58  5103.0  564.23
  5205.3  566.55  5220.2  565.07  5226.2  562.89  5256.0  562.20  5327.7  565.97
  5384.5  564.83  5399.4  566.62  5420.4  564.86  5441.6  567.02  5650.4  570.04
  5874.4  582.15  5902.8  580.80  5916.3  583.65  5948.9  584.85  6096.9  590.11
#Mann=5,-1,0
  4362.9    0.05       0  4907.0    0.16       0  4993.6    0.07       0
  4999.6    0.16       0  5948.9    0.05       0
Bank Sta=4993.6,4999.6
Exp/Cntr=0.3,0.1

Type RM Length L Ch R = 1,3240,1024,1024,1024
BEGIN DESCRIPTION:
UNT0005 IN CHRS 4.0
END DESCRIPTION:
XS GIS Cut Line= 3
      3377892.06     10619141.65      3379092.11     10619041.64
      3379692.11     10618241.64
#Sta/Elev= 30
  3784.0  580.72  3854.3  578.17  3934.6  577.95  3967.2  575.66  4024.9  577.00
  4208.0  575.86  4376.1  573.51  4637.0  566.38  4831.3  563.68  4930.5  563.96
  4968.1  563.07  4978.2  562.26  4985.7  560.30  4991.3  560.30  4998.7  556.16
  5001.5  555.66  5004.7  556.16  5010.1  557.87  5016.3  562.20  5038.2  563.90
  5216.3  562.04  5295.5  562.50  5374.7  568.95  5395.5  569.33  5451.7  572.91
  5674.7  581.17  5712.9  581.68  5788.2  583.39  5913.7  587.90  5988.2  590.72
#Mann=6,-1,0
  3784.0    0.05       0  4831.3    0.16       0  4998.7    0.07       0
  5004.7    0.16       0  5712.9    0.05       0  5913.7    0.16       0
Bank Sta=4998.7,5004.7
Exp/Cntr=0.3,0.1

Type RM Length L Ch R = 1,2216,0,0,0
BEGIN DESCRIPTION:
UNT0005 IN CHRS 1.0
END DESCRIPTION:
XS GIS Cut Line= 4
      3378789.22     10619566.50      3379276.82     10619636.29
      3379929.96     10619690.21      3380273.13     10618355.86
#Sta/Elev= 30
  4195.4  571.11  4208.4  570.85  4228.6  572.42  4329.6  570.55  4411.8  570.55
  4749.0  562.82  4833.7  561.24  4964.2  561.37  4984.3  559.16  5001.3  553.87
  5004.1  553.37  5007.3  553.87  5014.4  559.04  5024.4  560.90  5034.4  561.42
  5074.6  559.61  5141.1  559.53  5424.5  558.82  5497.2  556.71  5558.7  559.16
  5736.4  561.10  5829.8  565.31  5929.7  566.40  6002.7  569.14  6174.0  573.38
  6302.1  575.47  6372.5  577.88  6418.4  578.20  6446.7  579.78  6721.1  585.67
#Mann=6,-1,0
  4195.4    0.05       0  4749.0    0.16       0  5001.3    0.07       0
  5007.3    0.16       0  5141.1    0.05       0  5829.8    0.16       0
Bank Sta=5001.3,5007.3
Exp/Cntr=0.3,0.1

Chan Stop Cuts=-1