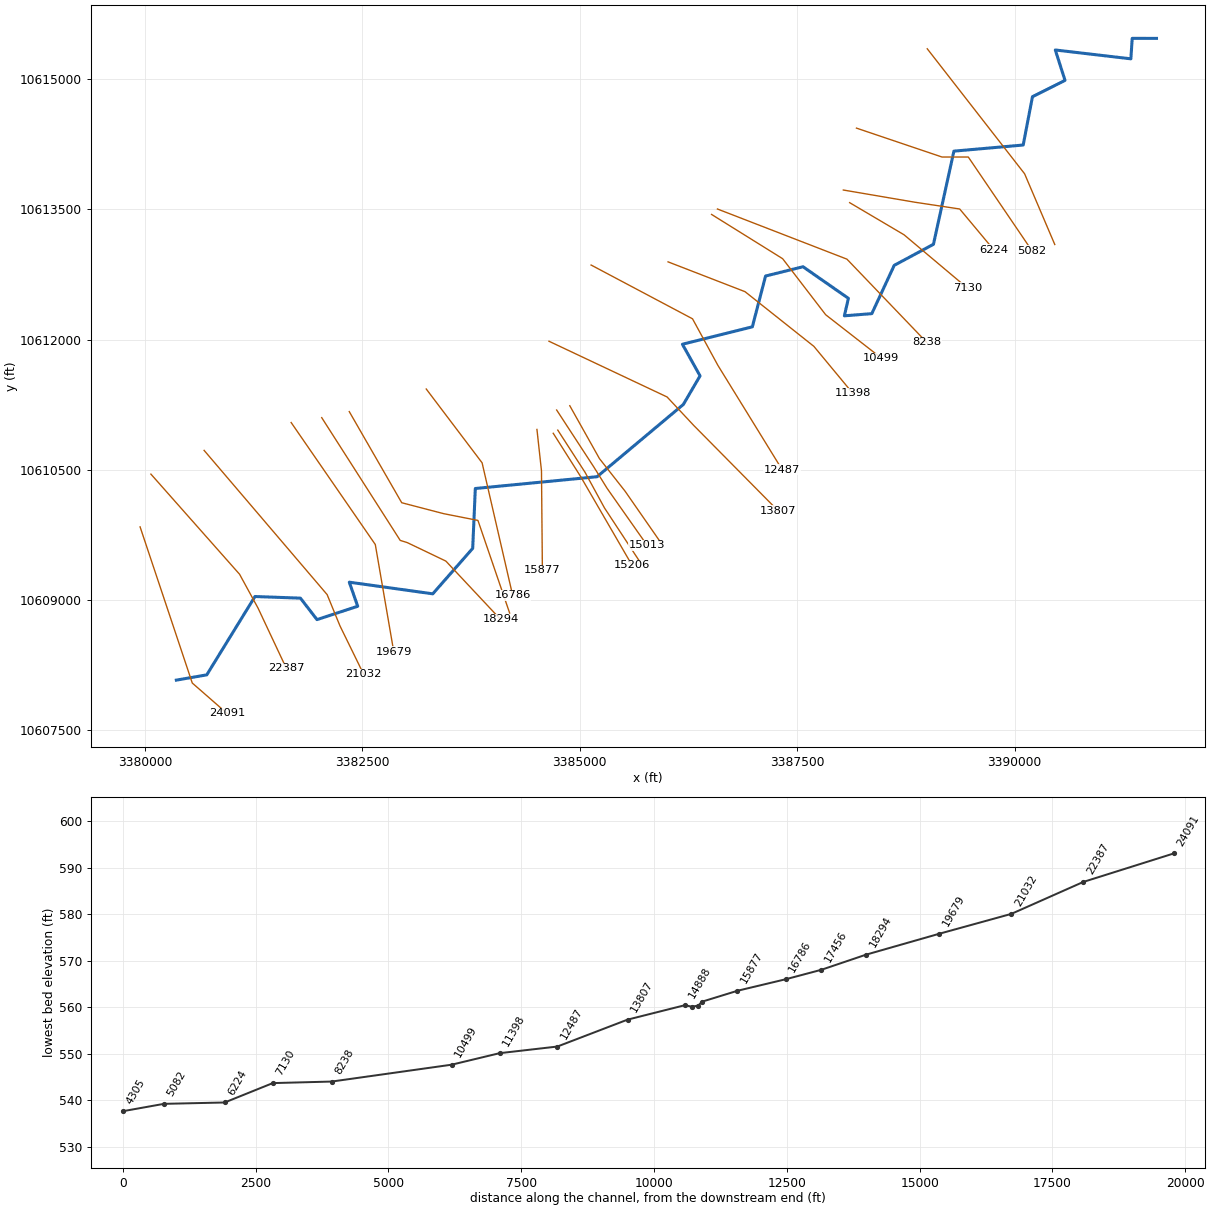
--- UNT0008 IN CHRS.prj (project) ---

Proj Title=UNT0008 IN CHRS Base Level Engineering
Current Plan=p01
Default Exp/Contr=0.3,0.1
English Units
Geom File=g01
Flow File=f01
Plan File=p01
BEGIN DESCRIPTION:
UNT0008 IN CHRS
END DESCRIPTION:

--- UNT0008 IN CHRS.p01 (plan) ---

Plan Title=Multiple Run
Short Identifier=Multiple
Geom File=g01
Flow File=f01
Subcritical Flow
K Sum by GR= 0
Std Step Tol= 0.01
Critical Tol= 0.01
Num of Std Step Trials= 20
Max Error Tol= 0.3
Flow Tol Ratio= 0.001
Split Flow NTrial= 30
Split Flow Tol= 0.02
Split Flow Ratio= 0.02
Log Output Level= 0
Friction Slope Method= 1
Unsteady Friction Slope Method= 2
Unsteady Bridges Friction Slope Method= 1
Parabolic Critical Depth
Global Vel Dist=  1 , 1 , 1
Global Log Level= 0
CheckData=True
Encroach Param= -1, 0, 0, 0
BEGIN DESCRIPTION:
Multiple Run
END DESCRIPTION:

--- UNT0008 IN CHRS.f01 (steady flow) ---

Flow Title=Multiple
Number of Profiles=7
Profile Names=10-year,25-year,50-year,1pct_min,100-year,1pct_plu,500-year
River Rch & RM= UNT0008 IN CHRS,Reach-1,24091
     392     494     570     478     647     874     831
River Rch & RM= UNT0008 IN CHRS,Reach-1,22387
     466     593     688     580     785    1062    1020
River Rch & RM= UNT0008 IN CHRS,Reach-1,21032
     487     621     720     608     823    1112    1071
River Rch & RM= UNT0008 IN CHRS,Reach-1,19679
     490     623     722     609     823    1113    1068
River Rch & RM= UNT0008 IN CHRS,Reach-1,15877
     622     802     938     798    1079    1459    1424
River Rch & RM= UNT0008 IN CHRS,Reach-1,15013
     642     828     968     822    1112    1504    1466
River Rch & RM= UNT0008 IN CHRS,Reach-1,12487
     780    1013    1190    1015    1372    1856    1822
River Rch & RM= UNT0008 IN CHRS,Reach-1,7130
     819    1064    1249    1065    1440    1947    1911
Boundary for River Rch & Prof#=UNT0008 IN CHRS,Reach-1,1
Up Type=0
Dn Type=3
Dn Slope=0.005
Boundary for River Rch & Prof#=UNT0008 IN CHRS,Reach-1,2
Up Type=0
Dn Type=3
Dn Slope=0.005
Boundary for River Rch & Prof#=UNT0008 IN CHRS,Reach-1,3
Up Type=0
Dn Type=3
Dn Slope=0.005
Boundary for River Rch & Prof#=UNT0008 IN CHRS,Reach-1,4
Up Type=0
Dn Type=3
Dn Slope=0.005
Boundary for River Rch & Prof#=UNT0008 IN CHRS,Reach-1,5
Up Type=0
Dn Type=3
Dn Slope=0.005
Boundary for River Rch & Prof#=UNT0008 IN CHRS,Reach-1,6
Up Type=0
Dn Type=3
Dn Slope=0.005
Boundary for River Rch & Prof#=UNT0008 IN CHRS,Reach-1,7
Up Type=0
Dn Type=3
Dn Slope=0.005

--- UNT0008 IN CHRS.g01 (geometry) ---

Geom Title=Existing Conditions
Program Version=4.10

River Reach=UNT0008 IN CHRS ,Reach-1
Reach XY= 30
      3380358.89     10608074.86      3380708.75     10608135.51
      3381263.36     10609038.63      3381786.34     10609019.75
      3381976.76     10608772.52      3382445.11     10608926.21
      3382348.17     10609203.84      3383308.43     10609069.54
      3383767.52     10609593.51      3383797.72     10610283.68
      3385198.35      10610419.5      3386190.18     10611252.34
       3386382.4     10611581.69      3386179.57     10611946.38
      3386983.81     10612146.88       3387135.9     10612732.49
      3387566.59     10612839.66      3388088.43     10612475.74
       3388042.4     10612274.04      3388358.01     10612299.08
      3388615.77     10612855.75      3389066.74     10613098.29
      3389302.04     10614171.97      3390099.02     10614242.57
      3390205.62     10614799.48      3390580.16     10614987.52
      3390468.27     10615338.07      3391337.51     10615236.12
      3391352.65     10615472.32      3391632.11     10615471.64

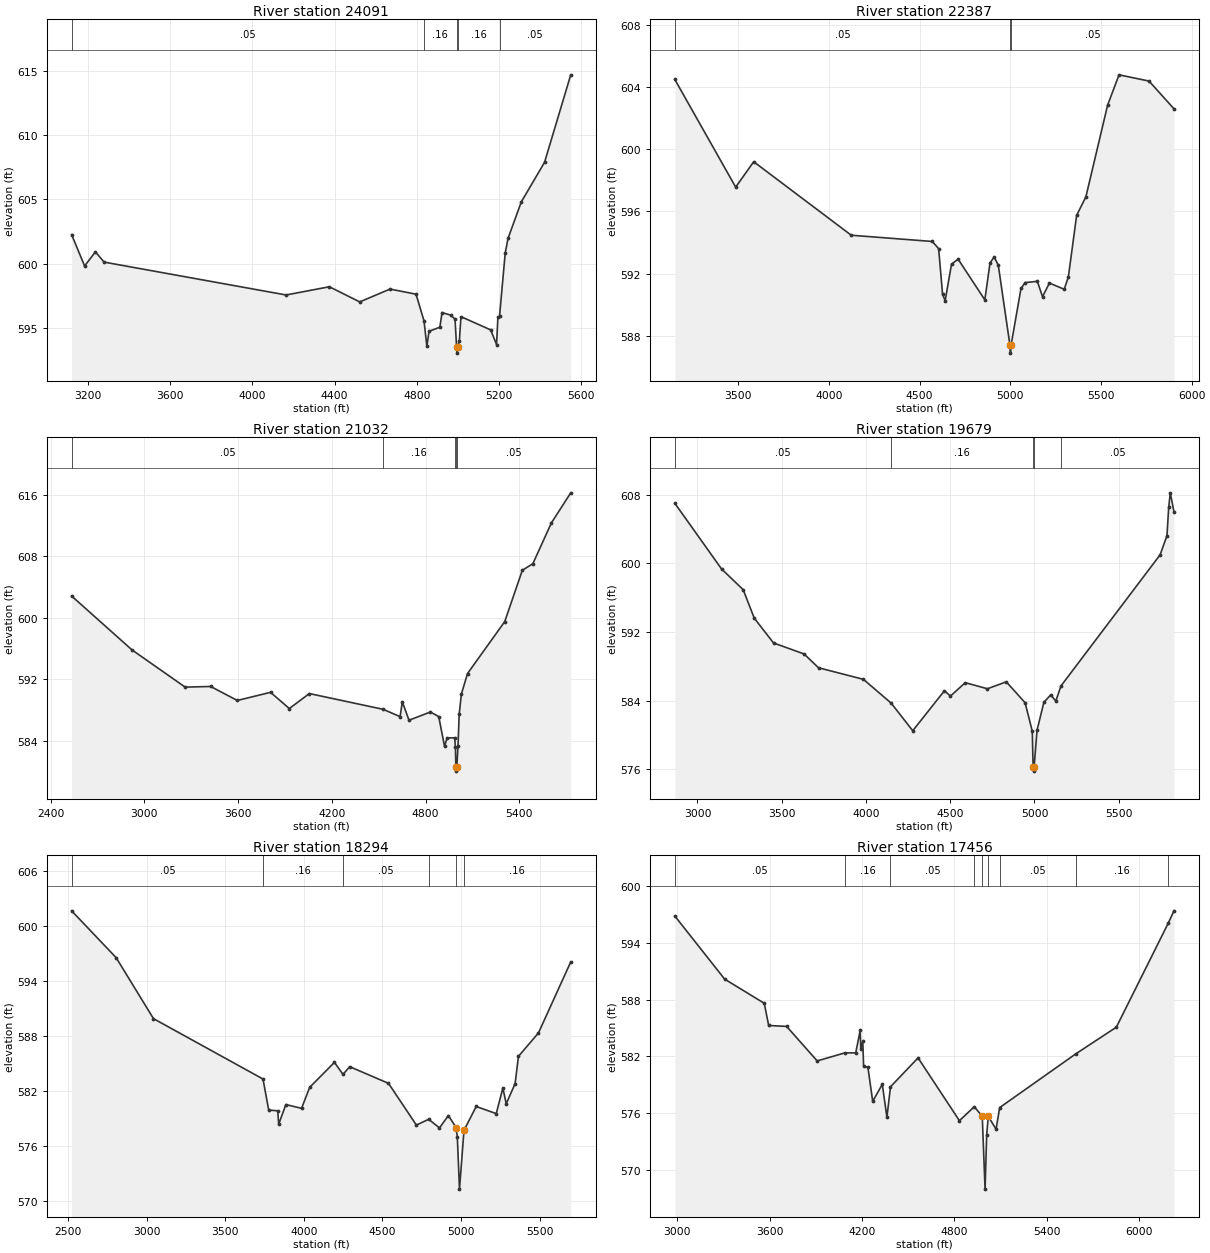
Type RM Length L Ch R = 1 ,24091   ,1704,1704,1704
BEGIN DESCRIPTION:
UNT0008 IN CHRS 29.0
END DESCRIPTION:
XS GIS Cut Line= 3
      3379942.11     10609841.62      3380542.11     10608041.64
      3380942.07     10607691.67
#Sta/Elev= 30
  3120.1  602.26  3183.3  599.82    3236  600.92  3278.2  600.12  4163.6  597.56
  4374.4   598.2    4522  597.02  4669.6  598.02  4796.1  597.62  4834.9  595.54
  4848.8  593.56  4859.3  594.73    4912  595.05  4922.6  596.19  4964.7  595.99
  4985.8  595.68  4993.4  593.53  4996.1  593.03  4999.4  593.53  5006.9     594
  5014.8  595.87  5159.3  594.84  5187.8   593.7  5194.5  595.82  5202.3  595.89
    5230  600.82  5243.8  601.97  5308.3  604.81  5421.3  607.89  5548.9  614.71
#Mann= 5 ,-1 , 0
  3120.1     .05       0  4834.9     .16       0  4993.4     .07       0
  4999.4     .16       0  5202.3     .05       0
Bank Sta=4993.4,4999.4
XS Rating Curve= 0 ,0
Exp/Cntr=0.3,0.1

Type RM Length L Ch R = 1 ,22387   ,1355,1355,1355
BEGIN DESCRIPTION:
UNT0008 IN CHRS 27.0
END DESCRIPTION:
XS GIS Cut Line= 4
      3380066.44     10610449.54      3381086.39     10609295.03
      3381299.07     10608904.41      3381624.57     10608209.99
#Sta/Elev= 30
  3150.3  604.47  3485.7  597.56  3585.2  599.19  4123.1  594.47  4569.8  594.07
  4604.9  593.61  4626.7  590.67  4640.9  590.27  4676.1  592.62  4712.5  592.93
  4859.7  590.32  4888.2  592.69    4911  593.07  4933.8  592.55  4998.2   587.4
    5001   586.9  5004.2   587.4    5059  591.05  5081.8  591.43  5149.3  591.51
  5177.7  590.52  5215.9   591.4  5297.3     591  5320.2  591.79  5365.8  595.74
    5417  596.94  5536.6  602.82  5599.6  604.77  5764.9  604.37  5902.5  602.59
#Mann= 3 ,-1 , 0
  3150.3     .05       0  4998.2     .03       0  5004.2     .05       0
Bank Sta=4998.2,5004.2
XS Rating Curve= 0 ,0
Exp/Cntr=0.3,0.1

Type RM Length L Ch R = 1 ,21032   ,1353,1353,1353
BEGIN DESCRIPTION:
UNT0008 IN CHRS 26.0
END DESCRIPTION:
XS GIS Cut Line= 4
      3380678.44     10610722.95      3382093.34     10609060.66
      3382240.91     10608700.41      3382514.34     10608140.53
#Sta/Elev= 30
  2534.5  602.81  2920.9   595.8  3261.3  590.96  3424.9  591.04  3595.2  589.22
  3808.2  590.28  3928.2  588.17  4056.4  590.12  4528.7  588.07  4637.3  587.12
  4651.6  589.04  4694.4  586.65  4831.4  587.72  4884.7  587.12  4921.7  583.26
  4938.1  584.34  4986.8  584.37  4991.5  583.19  4994.3  580.53  4997.1  580.03
  5000.3  580.53  5008.1  583.28  5015.5   587.4  5029.7  590.05  5068.9  592.72
  5307.2  599.48  5419.8  606.15  5487.4  607.02  5606.1  612.32  5729.8  616.23
#Mann= 5 ,-1 , 0
  2534.5     .05       0  4528.7     .16       0  4986.8     .05       0
  4994.3    .035       0  5000.3     .05       0
Bank Sta=4994.3,5000.3
XS Rating Curve= 0 ,0
Exp/Cntr=0.3,0.1

Type RM Length L Ch R = 1 ,19679   ,1385,1385,1385
BEGIN DESCRIPTION:
UNT0008 IN CHRS 24.0
END DESCRIPTION:
XS GIS Cut Line= 3
      3381679.49     10611044.08      3382647.38     10609637.82
      3382860.05     10608400.82
#Sta/Elev= 30
  2865.6  606.99  3142.7  599.34  3271.2  596.92  3336.8  593.61  3451.3  590.71
  3632.4  589.43  3718.3  587.82  3984.8  586.47  4149.4   583.7  4277.6  580.48
  4465.7  585.14  4501.5  584.52  4589.2  586.08  4721.1  585.37  4832.7  586.18
  4944.3  583.75  4987.1  580.42    4992  576.27  4994.8  575.77    4998  576.27
  5015.3  580.54  5055.9  583.79  5096.5  584.66  5126.9  583.94  5157.6  585.71
  5745.9  600.99  5786.5  603.22  5796.6   606.5  5806.1  608.21  5827.9     606
#Mann= 5 ,-1 , 0
  2865.6     .05       0  4149.4     .16       0    4992     .07       0
    4998     .16       0  5157.6     .05       0
Bank Sta=4992,4998
XS Rating Curve= 0 ,0
Exp/Cntr=0.3,0.1

Type RM Length L Ch R = 1 ,18294   ,838,838,838
BEGIN DESCRIPTION:
UNT0008 IN CHRS 23.0
END DESCRIPTION:
XS GIS Cut Line= 5
      3382031.06      10611100.5      3382933.84     10609685.56
       3383016.3     10609659.52      3383459.01     10609446.85
      3384086.54     10608776.04
#Sta/Elev= 30
  2523.5  601.66  2806.8  596.54  3044.1  589.88  3740.8  583.28    3777  579.89
  3834.5  579.81  3840.5  578.34  3886.1  580.49    3986  580.08  4037.6  582.37
    4195   585.1  4249.7  583.79  4292.2  584.63  4538.9  582.81  4716.4  578.25
  4794.7  578.88  4863.3  577.94  4919.9  579.29  4969.3  577.97  4976.6  576.97
  4990.5  571.25  5019.1  577.67  5096.8  580.28  5224.3   579.5  5266.3   582.3
  5287.8  580.57  5344.4  582.79  5365.4  585.76  5492.9  588.32  5698.1  596.08
#Mann= 6 ,-1 , 0
  2523.5     .05       0  3740.8     .16       0  4249.7     .05       0
  4794.7     .16       0  4969.3     .07       0  5019.1     .16       0
Bank Sta=4969.3,5019.1
XS Rating Curve= 0 ,0
Exp/Cntr=0.3,0.1

Type RM Length L Ch R = 1 ,17456   ,670,670,670
BEGIN DESCRIPTION:
UNT0008 IN CHRS 22.0
END DESCRIPTION:
XS GIS Cut Line= 5
      3382347.91     10611169.92       3382951.2     10610119.59
      3383432.97     10609993.72      3383827.93      10609915.6
      3384192.53     10608847.84
#Sta/Elev= 30
  2985.3  596.81  3308.5  590.16  3565.8  587.61  3594.5  585.27    3711  585.17
  3909.5  581.53  4089.2  582.38  4159.6  582.38  4188.4  584.74  4192.5   582.8
  4205.4  583.58  4210.6     581  4238.8  580.84  4269.8  577.27    4332  579.06
  4362.1  575.59  4385.2   578.8  4564.3  581.85  4832.6  575.23  4929.1   576.7
  4980.9   575.7  4999.2  568.01  5009.6  573.69  5019.8  575.68  5070.8  574.33
    5094  576.61  5586.7  582.26  5851.5  585.09  6189.3  596.09  6225.4  597.36
#Mann= 9 ,-1 , 0
  2985.3     .05       0  4089.2     .16       0  4385.2     .05       0
  4929.1     .16       0  4980.9     .07       0  5019.8     .16       0
    5094     .05       0  5586.7     .16       0  6189.3     .05       0
Bank Sta=4980.9,5019.8
XS Rating Curve= 0 ,0
Exp/Cntr=0.3,0.1

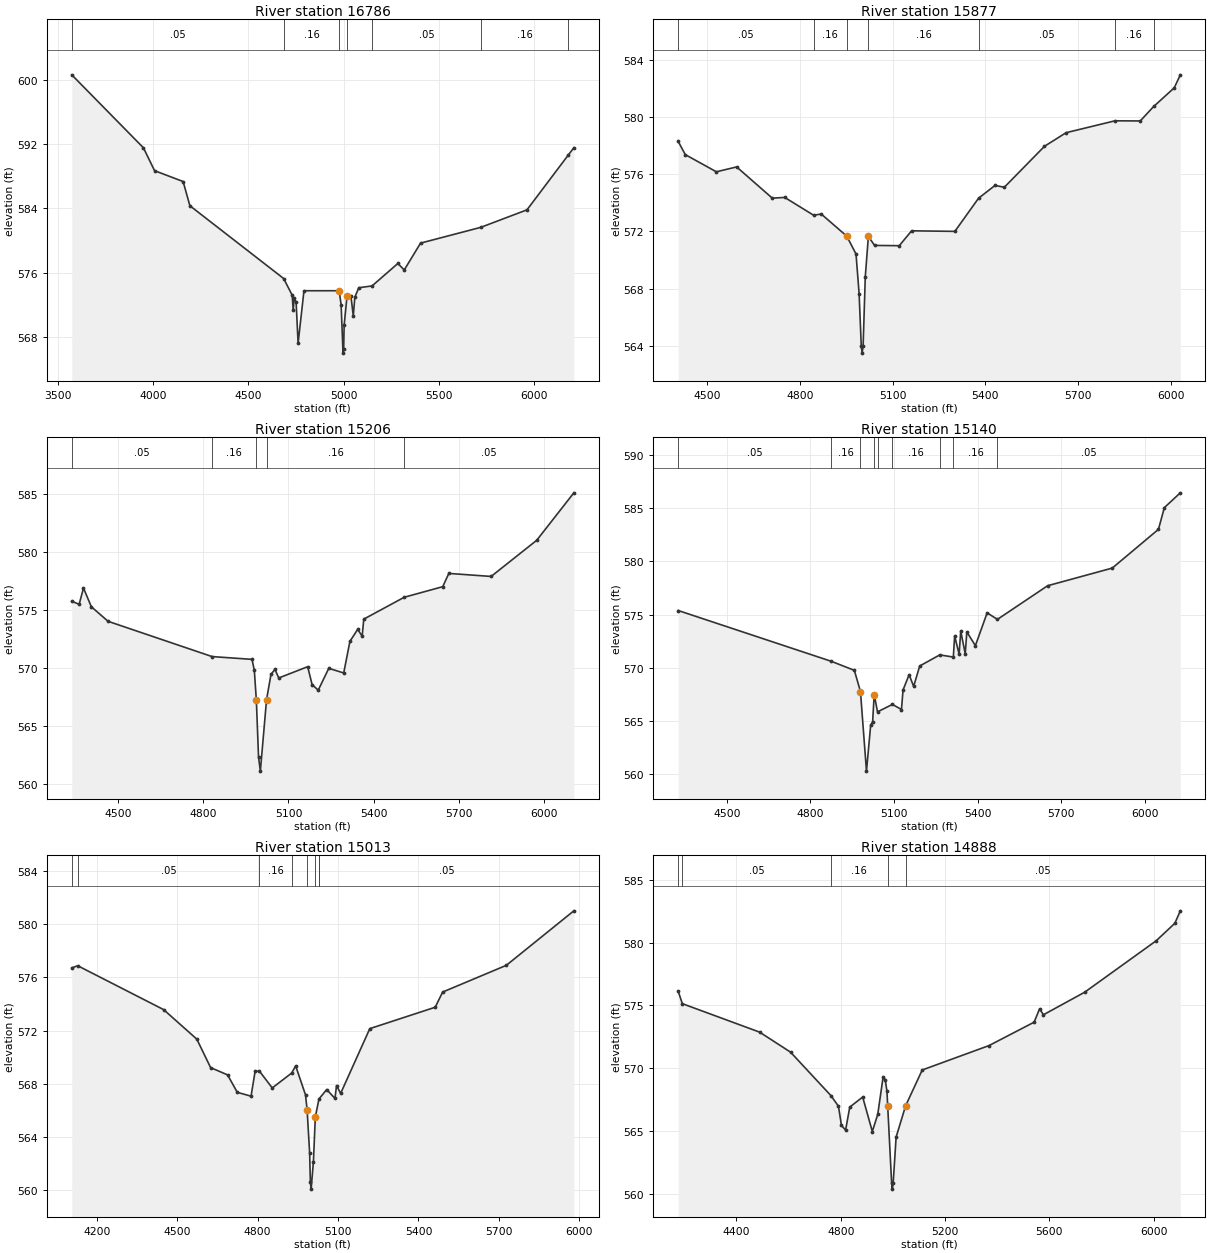
Type RM Length L Ch R = 1 ,16786   ,909,909,909
BEGIN DESCRIPTION:
UNT0008 IN CHRS 21.0
END DESCRIPTION:
XS GIS Cut Line= 3
      3383233.32     10611430.34      3383875.68     10610579.66
      3384227.18     10609052.15
#Sta/Elev= 30
  3573.4  600.59  3949.4  591.51  4007.6  588.67  4157.5  587.32  4192.9  584.31
  4684.6  575.26  4729.7  573.18  4734.9  571.31    4740  572.86  4750.2  572.29
  4760.5   567.2  4791.3  573.74    4976  573.74  4986.2  571.98  4996.2  565.98
  4999.5  566.48    5002  569.43    5017  573.04  5037.5  573.09    5050   570.6
    5058  572.92  5078.6  574.11  5148.6  574.34  5283.8  577.13  5317.2  576.32
  5402.8  579.66  5718.4  581.62    5961   583.8  6176.5  590.58  6206.8  591.52
#Mann= 7 ,-1 , 0
  3573.4     .05       0  4684.6     .16       0    4976     .07       0
    5017     .16       0  5148.6     .05       0  5718.4     .16       0
  6176.5     .05       0
Bank Sta=4976,5017
XS Rating Curve= 0 ,0
Exp/Cntr=0.3,0.1

Type RM Length L Ch R = 1 ,15877   ,671,671,671
BEGIN DESCRIPTION:
UNT0008 IN CHRS 20.0
END DESCRIPTION:
XS GIS Cut Line= 3
      3384506.53     10610964.34      3384558.62     10610487.74
      3384569.03     10609341.92
#Sta/Elev= 30
  4405.6  578.28  4428.4  577.36    4529  576.16  4594.7   576.5  4710.1  574.32
  4750.3  574.37  4843.7  573.13  4868.6  573.21  4951.1  571.67  4981.1  570.42
  4991.1  567.66  4998.1     564  5000.9   563.5  5004.1     564  5011.1  568.83
  5021.1  571.65  5041.1  571.02  5121.1     571  5161.1  572.04  5301.1     572
  5377.6  574.31  5431.2  575.21  5461.2  575.08  5591.2  577.94  5661.2  578.89
  5819.5  579.72  5901.2  579.71  5944.7  580.72  6011.2  582.02  6030.9  582.93
#Mann= 7 ,-1 , 0
  4405.6     .05       0  4843.7     .16       0  4951.1     .07       0
  5021.1     .16       0  5377.6     .05       0  5819.5     .16       0
  5944.7     .05       0
Bank Sta=4951.1,5021.1
XS Rating Curve= 0 ,0
Exp/Cntr=0.3,0.1

Type RM Length L Ch R = 1 ,15206   ,66,66,66
BEGIN DESCRIPTION:
UNT0008 IN CHRS 19.0
END DESCRIPTION:
XS GIS Cut Line= 3
      3384694.03     10610920.03      3385006.53     10610425.24
       3385600.3     10609399.17
#Sta/Elev= 30
  4335.7  575.74  4361.8  575.49    4377  576.88  4404.8  575.27  4463.9  574.02
  4830.5  570.99  4971.3  570.75  4979.5  569.82 4986.69  567.24  4994.4  562.34
  5000.8  561.14  5022.6  567.28  5038.3  569.46  5052.2  569.89  5065.7  569.15
  5167.7  570.12  5183.3  568.58  5204.9   568.1  5242.1  569.98  5294.8  569.58
  5316.7   572.3  5344.1  573.33  5359.8  572.74  5365.6  574.21  5508.2  576.09
    5644     577  5665.5  578.14  5814.7  577.88  5975.5  580.99  6106.4  585.07
#Mann= 5 ,-1 , 0
  4335.7     .05       0  4830.5     .16       0 4986.69     .07       0
  5022.6     .16       0  5508.2     .05       0
Bank Sta=4986.69,5022.6
XS Rating Curve= 0 ,0
Exp/Cntr=0.3,0.1

Type RM Length L Ch R = 1 ,15140   ,127,127,127
BEGIN DESCRIPTION:
UNT0008 IN CHRS 18.0
END DESCRIPTION:
XS GIS Cut Line= 4
      3384746.11     10610956.51      3385058.62     10610472.12
      3385282.58     10610060.66      3385697.73     10609427.55
#Sta/Elev= 30
  4325.5  575.39  4874.7  570.62  4957.6  569.77  4979.5  567.78  5001.1   560.3
  5016.3  564.64  5023.2  564.94  5028.9   567.5  5040.7  565.87  5094.3  566.57
  5126.7  566.09  5132.4  567.93  5154.2  569.36  5170.4  568.26  5192.2  570.18
  5264.1  571.22  5312.8  571.02  5317.6     573  5333.7  571.28  5339.4  573.46
  5355.6  571.32  5361.3  573.38    5392  572.09  5434.2  575.17  5471.2  574.56
  5651.2  577.72  5883.4  579.38  6049.1  583.02  6070.2  585.06  6127.5  586.45
#Mann= 9 ,-1 , 0
  4325.5     .05       0  4874.7     .16       0  4979.5     .07       0
  5028.9     .16       0  5040.7     .05       0  5094.3     .16       0
  5264.1     .05       0  5312.8     .16       0  5471.2     .05       0
Bank Sta=4979.5,5028.9
XS Rating Curve= 0 ,0
Exp/Cntr=0.3,0.1

Type RM Length L Ch R = 1 ,15013   ,125,125,125
BEGIN DESCRIPTION:
UNT0008 IN CHRS 17.0
END DESCRIPTION:
XS GIS Cut Line= 4
      3384733.12     10611188.23      3385165.39      10610524.2
      3385313.83     10610284.62      3385772.16     10609630.97
#Sta/Elev= 30
    4107  576.72  4129.3  576.88  4449.6  573.58  4573.4  571.36  4624.8  569.22
  4688.1  568.67  4724.3  567.36  4775.6  567.07  4790.8  568.94  4806.6  568.96
  4854.7  567.69  4927.2  568.81    4942  569.35  4978.7  567.17  4984.7  566.05
  4994.1  562.81  4996.9  560.58  4999.7  560.08  5008.2  562.13  5015.3   565.5
  5028.9  566.86  5057.8  567.57  5088.6   566.9  5094.5  567.87  5109.8  567.28
  5218.5  572.15  5462.6  573.76  5490.1   574.9  5727.6  576.91  5979.5  581.01
#Mann= 8 ,-1 , 0
    4107     .16       0  4129.3     .05       0  4806.6     .16       0
  4927.2     .05       0  4984.7     .04       0  5015.3     .05       0
  5028.9     .16       0  5028.9     .05       0
Bank Sta=4984.7,5015.3
XS Rating Curve= 0 ,0
Exp/Cntr=0.3,0.1

Type RM Length L Ch R = 1 ,14888   ,1081,1081,1081
BEGIN DESCRIPTION:
UNT0008 IN CHRS 16.0
END DESCRIPTION:
XS GIS Cut Line= 4
      3384884.15     10611237.72      3385225.28     10610628.37
      3385519.55     10610253.37      3385947.08     10609636.69
#Sta/Elev= 30
  4176.7  576.12  4192.4  575.14  4488.6  572.88  4607.3  571.29  4762.4  567.83
  4791.1  566.99  4802.6  565.47  4818.5  565.09  4834.5  566.92    4884  567.72
    4921  564.98  4941.8  566.34  4962.6  569.34  4970.7  569.06  4977.1  568.18
 4979.85  567.04    4995   560.9  4997.7   560.4    5001   560.9  5012.3  564.54
  5048.8  567.03  5112.4  569.87  5368.5  571.81  5541.5  573.67  5562.4  574.73
  5577.3  574.26  5735.3  576.05  6009.6  580.14  6081.2  581.53  6102.1  582.52
#Mann= 5 ,-1 , 0
  4176.7     .16       0  4192.4     .05       0  4762.4     .16       0
 4979.85     .07       0  5048.8     .05       0
Bank Sta=4979.85,5048.8
XS Rating Curve= 0 ,0
Exp/Cntr=0.3,0.1

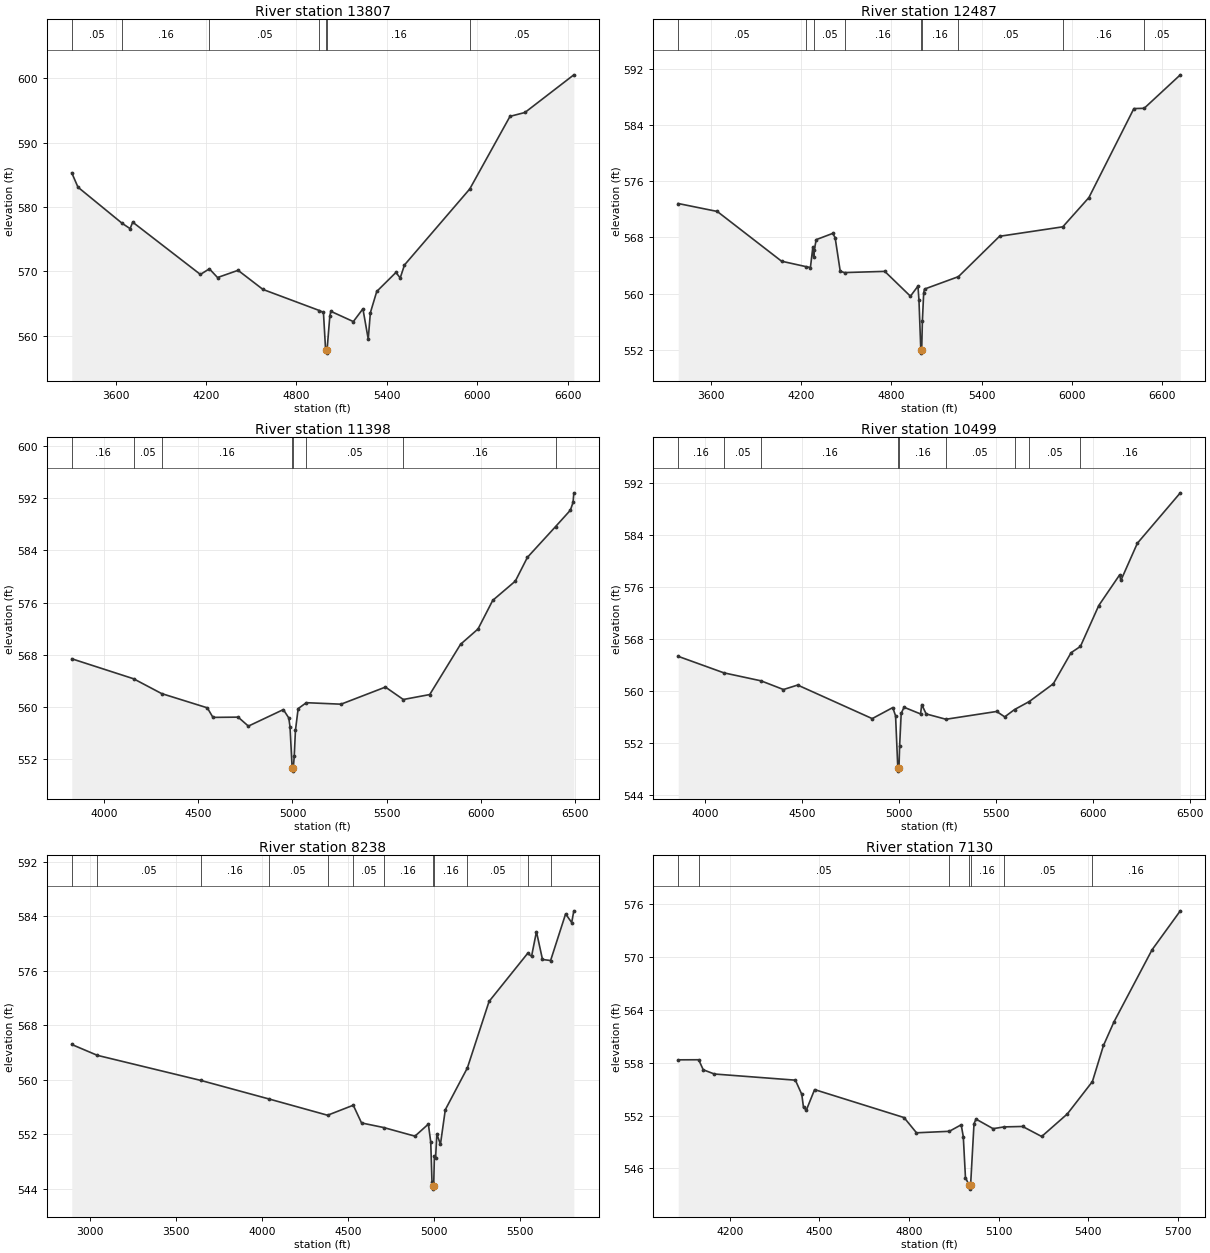
Type RM Length L Ch R = 1 ,13807   ,1320,1320,1320
BEGIN DESCRIPTION:
UNT0008 IN CHRS 14.0
END DESCRIPTION:
XS GIS Cut Line= 4
      3384644.86     10611980.93      3386003.35     10611338.58
      3386311.51     10611008.72      3387278.24     10610028.98
#Sta/Elev= 30
  3309.4  585.29  3350.6  583.06  3643.6  577.45  3696.4  576.62  3713.6  577.63
  4162.6  569.51  4222.2  570.38  4276.4  569.03  4412.5  570.15  4577.8  567.18
  4951.5  563.91  4978.9   563.6    4993  557.86  4996.9  557.79  4999.6  557.29
  5002.9  557.79  5021.4   563.1  5028.2  563.78  5177.2  562.19  5240.7  564.17
    5276  559.47  5290.1  563.56  5332.5  566.87  5459.8  569.82  5488.1  568.96
  5516.4  570.98  5949.6  582.79  6216.4  594.06  6315.4  594.66  6639.9  600.51
#Mann= 7 ,-1 , 0
  3309.4     .05       0  3643.6     .16       0  4222.2     .05       0
  4951.5     .16       0  4996.9     .07       0  5002.9     .16       0
  5949.6     .05       0
Bank Sta=4996.9,5002.9
XS Rating Curve= 0 ,0
Exp/Cntr=0.3,0.1

Type RM Length L Ch R = 1 ,12487   ,1089,1089,1089
BEGIN DESCRIPTION:
UNT0008 IN CHRS 13.0
END DESCRIPTION:
XS GIS Cut Line= 4
       3385129.2     10612859.42      3386295.89     10612239.62
      3386587.55     10611703.16      3387327.14     10610500.03
#Sta/Elev= 30
  3379.9  572.83  3639.8   571.7  4068.1  564.61  4232.1  563.83  4260.3  563.71
  4276.6  566.65  4282.2  565.22  4286.8  566.27  4298.6  567.68  4408.5  568.57
  4424.8  567.98  4458.9  563.17  4487.5  562.99  4755.6  563.16  4926.4  559.62
  4976.6  561.06  4983.3  559.03  4995.5  552.01  4998.2  551.51  5001.5  552.01
    5006  556.07  5014.7   560.1  5020.3  560.64  5246.1  562.41  5519.8  568.16
  5941.3  569.51  6115.1  573.68  6414.6  586.36  6483.2   586.4  6723.9  591.17
#Mann= 9 ,-1 , 0
  3379.9     .05       0  4232.1     .16       0  4286.8     .05       0
  4487.5     .16       0  4995.5     .07       0  5001.5     .16       0
  5246.1     .05       0  5941.3     .16       0  6483.2     .05       0
Bank Sta=4995.5,5001.5
XS Rating Curve= 0 ,0
Exp/Cntr=0.3,0.1

Type RM Length L Ch R = 1 ,11398   ,899,899,899
BEGIN DESCRIPTION:
UNT0008 IN CHRS 11.0
END DESCRIPTION:
XS GIS Cut Line= 4
      3386014.67     10612895.86      3386900.05     10612552.12
      3387691.72     10611921.91      3388138.35      10611381.8
#Sta/Elev= 30
  3829.5  567.35  4157.1  564.28  4306.1     562  4548.3  559.81  4578.2  558.34
  4711.6  558.38  4766.1     557  4951.5  559.54  4980.4  558.25  4986.8  556.91
  4998.2  550.58  5000.9  550.08  5004.2  550.58  5009.2  552.33  5015.6  556.33
    5030  559.69  5073.4   560.6  5257.4  560.37  5492.9     563  5587.6  561.09
  5727.7  561.85  5891.3  569.58  5983.8  571.93  6061.9  576.33  6181.7  579.29
  6245.7  582.94  6394.8  587.66  6473.6  590.19  6487.9   591.4    6492  592.86
#Mann= 8 ,-1 , 0
  3829.5     .16       0  4157.1     .05       0  4306.1     .16       0
  4998.2     .07       0  5004.2     .16       0  5073.4     .05       0
  5587.6     .16       0  6394.8     .05       0
Bank Sta=4998.2,5004.2
XS Rating Curve= 0 ,0
Exp/Cntr=0.3,0.1

Type RM Length L Ch R = 1 ,10499   ,2261,2261,2261
BEGIN DESCRIPTION:
UNT0008 IN CHRS 8.0
END DESCRIPTION:
XS GIS Cut Line= 4
      3386514.65     10613442.74      3387332.34     10612932.33
      3387827.14      10612286.5      3388467.33     10611786.84
#Sta/Elev= 30
    3863  565.29  4098.4  562.75  4289.9  561.52  4405.7  560.18  4478.9  560.87
  4863.5   555.7  4969.5   557.4    4984  556.12  4995.5  548.11  4998.3  547.61
  5001.5  548.11  5004.8  551.42    5013  556.51  5027.6  557.45  5112.8  556.42
    5119  557.86  5141.8  556.42  5243.8   555.6  5505.3   556.8    5547  555.97
  5597.8   557.1  5673.6  558.33  5797.7  561.07  5889.1  565.85  5937.4  566.82
    6032  573.12  6139.6  577.84    6146  576.98    6231  582.71  6452.6  590.48
#Mann= 9 ,-1 , 0
    3863     .16       0  4098.4     .05       0  4289.9     .16       0
  4995.5     .07       0  5001.5     .16       0  5243.8     .05       0
  5597.8     .16       0  5673.6     .05       0  5937.4     .16       0
Bank Sta=4995.5,5001.5
XS Rating Curve= 0 ,0
Exp/Cntr=0.3,0.1

Type RM Length L Ch R = 1 ,8238    ,1108,1108,1108
BEGIN DESCRIPTION:
UNT0008 IN CHRS 9.0
END DESCRIPTION:
XS GIS Cut Line= 3
      3386582.32     10613505.25      3388071.93     10612927.12
      3388987.83     10611969.59
#Sta/Elev= 30
  2892.7   565.2  3041.4  563.61  3645.1  559.92  4038.9  557.22    4382  554.82
  4531.5  556.29  4579.6  553.69  4707.8  553.02  4890.6  551.75  4968.6  553.52
  4982.5  550.89  4989.7  545.07  4993.6  544.48  4996.3  543.98  4999.6  544.48
  5003.8  548.85  5010.7  548.55    5018  552.06    5039  550.56  5067.3  555.63
  5195.7  561.76  5322.1  571.52    5546  578.55  5569.6  578.16  5597.9  581.75
  5633.1  577.67  5680.3  577.52  5767.7  584.36    5803  583.09  5815.6  584.81
#Mann= 12 ,-1 , 0
  2892.7     .16       0  3041.4     .05       0  3645.1     .16       0
  4038.9     .05       0    4382     .16       0  4531.5     .05       0
  4707.8     .16       0  4993.6     .07       0  4999.6     .16       0
  5195.7     .05       0    5546     .16       0  5680.3     .05       0
Bank Sta=4993.6,4999.6
XS Rating Curve= 0 ,0
Exp/Cntr=0.3,0.1

Type RM Length L Ch R = 1 ,7130    ,906,906,906
BEGIN DESCRIPTION:
UNT0008 IN CHRS 7.0
END DESCRIPTION:
XS GIS Cut Line= 3
      3388103.16     10613578.17      3388728.18     10613208.37
      3389457.24     10612593.88
#Sta/Elev= 30
  4027.9  558.34  4096.2  558.35  4111.6  557.21  4148.7  556.73  4419.8  556.03
  4441.2  554.42    4447  552.93  4456.6  552.64  4484.1  554.96  4783.4  551.78
    4825  550.05  4934.9  550.22  4974.5  550.96  4981.6  549.61  4988.8  544.97
  5000.1  544.15  5002.9  543.65  5006.1  544.15  5017.4  551.08    5024  551.61
  5081.2  550.52  5118.1  550.72    5180  550.77  5243.8  549.63  5329.5  552.19
  5413.5  555.87  5450.5  559.97  5485.6  562.65    5613  570.84  5707.6  575.27
#Mann= 7 ,-1 , 0
  4027.9     .16       0  4096.2     .05       0  4934.9     .16       0
  5000.1     .07       0  5006.1     .16       0  5118.1     .05       0
  5413.5     .16       0
Bank Sta=5000.1,5006.1
XS Rating Curve= 0 ,0
Exp/Cntr=0.3,0.1

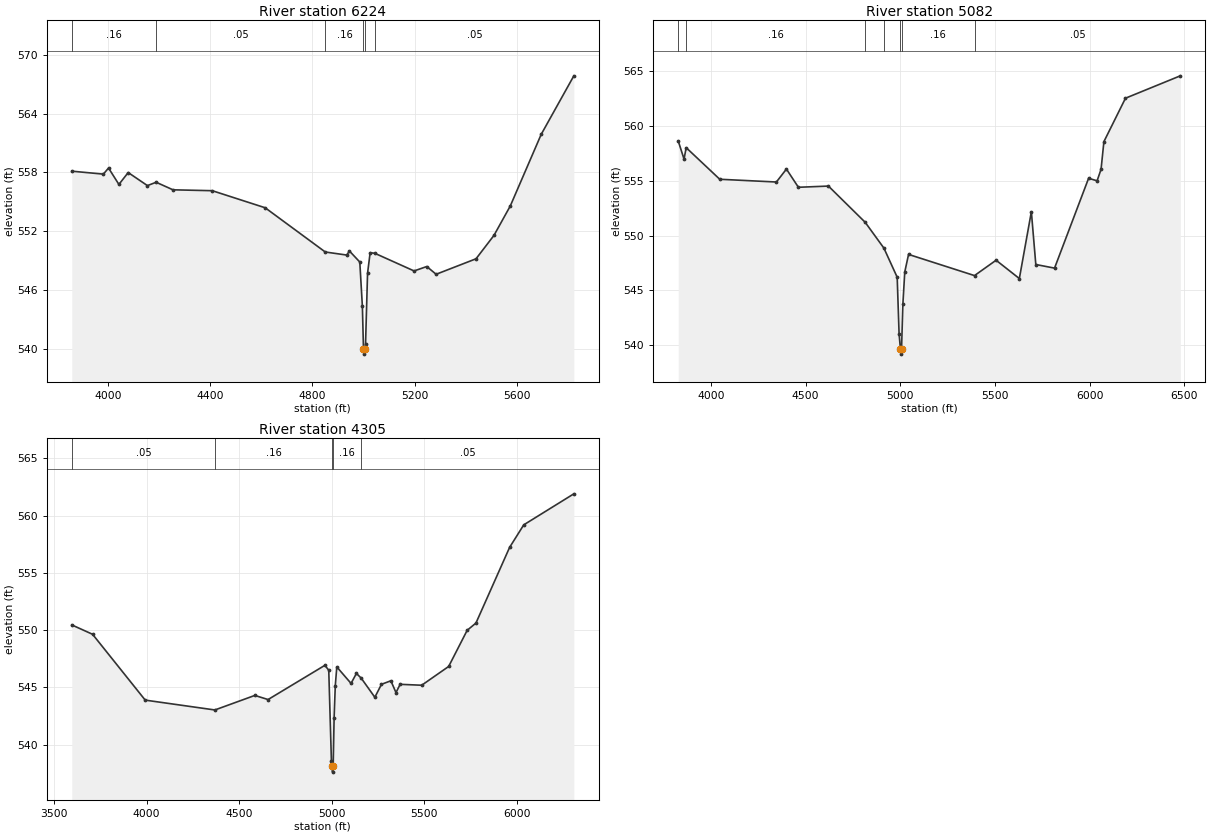
Type RM Length L Ch R = 1 ,6224    ,1142,1142,1142
BEGIN DESCRIPTION:
UNT0008 IN CHRS 6.0
END DESCRIPTION:
XS GIS Cut Line= 4
       3388030.3     10613723.99      3388853.18     10613583.37
       3389368.8     10613505.25      3389758.22     10613037.95
#Sta/Elev= 30
  3858.7  558.13  3982.3  557.83  4002.6  558.45  4043.1  556.78  4079.5  557.99
  4154.7  556.66  4188.9     557  4254.8  556.23  4408.4  556.14  4615.5   554.4
  4850.7  549.89  4934.4  549.58  4945.3  549.99  4985.7  548.87  4995.8  544.37
  5000.2  539.98  5002.9  539.48  5006.2  539.98  5008.2  540.48  5016.1  547.72
  5026.2  549.82  5044.5  549.76  5198.1  547.96  5247.9  548.41  5284.4  547.62
  5440.6   549.2  5510.9  551.59  5574.7  554.59  5695.7  561.89  5823.3  567.85
#Mann= 6 ,-1 , 0
  3858.7     .16       0  4188.9     .05       0  4850.7     .16       0
  5000.2     .07       0  5006.2     .16       0  5044.5     .05       0
Bank Sta=5000.2,5006.2
XS Rating Curve= 0 ,0
Exp/Cntr=0.3,0.1

Type RM Length L Ch R = 1 ,5082    ,777,777,777
BEGIN DESCRIPTION:
UNT0008 IN CHRS 4.0
END DESCRIPTION:
XS GIS Cut Line= 4
      3388181.31     10614437.54      3389165.68      10614104.2
      3389467.76      10614104.2      3390202.11     10613020.91
#Sta/Elev= 30
  3827.8  558.62  3858.4  556.97  3869.8  558.01    4047  555.13    4346  554.88
  4398.8  556.06  4462.1   554.4  4620.5  554.51  4814.5  551.21  4913.5  548.85
  4983.5   546.2  4993.5  541.04  5000.5  539.69  5003.3  539.19  5006.5  539.69
  5013.5  543.74  5023.5  546.68  5043.5  548.28  5391.6  546.35  5505.5  547.75
  5628.3  546.08  5691.7  552.17  5715.2  547.36  5814.1  547.03  5993.8  555.22
  6038.7  554.99  6059.6  556.04  6074.6  558.56  6188.5  562.52  6477.9  564.56
#Mann= 7 ,-1 , 0
  3827.8     .05       0  3869.8     .16       0  4814.5     .05       0
  4913.5     .16       0  5000.5     .07       0  5006.5     .16       0
  5391.6     .05       0
Bank Sta=5000.5,5006.5
XS Rating Curve= 0 ,0
Exp/Cntr=0.3,0.1

Type RM Length L Ch R = 1 ,4305    ,0,0,0
BEGIN DESCRIPTION:
UNT0008 IN CHRS 1.0
END DESCRIPTION:
XS GIS Cut Line= 3
      3388995.52     10615352.05      3390115.33     10613911.06
      3390462.23     10613095.85
#Sta/Elev= 30
  3596.1  550.46  3708.5  549.64  3992.7  543.89  4368.7  543.03  4584.5   544.3
    4656  543.94  4962.8  546.93  4983.7   546.5  4998.1  538.53  5001.5   538.1
  5004.2   537.6  5007.5   538.1  5012.6  542.36  5018.9  545.14  5027.1  546.79
    5104  545.35    5133  546.22  5158.9  545.81  5232.5  544.14  5268.3  545.27
    5319  545.58  5346.6  544.55  5369.2  545.27  5485.6  545.19  5631.1  546.83
  5731.1  549.99  5778.4  550.62  5960.1  557.23  6036.5   559.2    6307  561.91
#Mann= 5 ,-1 , 0
  3596.1     .05       0  4368.7     .16       0  5001.5     .07       0
  5007.5     .16       0  5158.9     .05       0
Bank Sta=5001.5,5007.5
XS Rating Curve= 0 ,0
Exp/Cntr=0.3,0.1

Chan Stop Cuts=-1
Use User Specified Reach Order=0
Composite Channel Slope=5