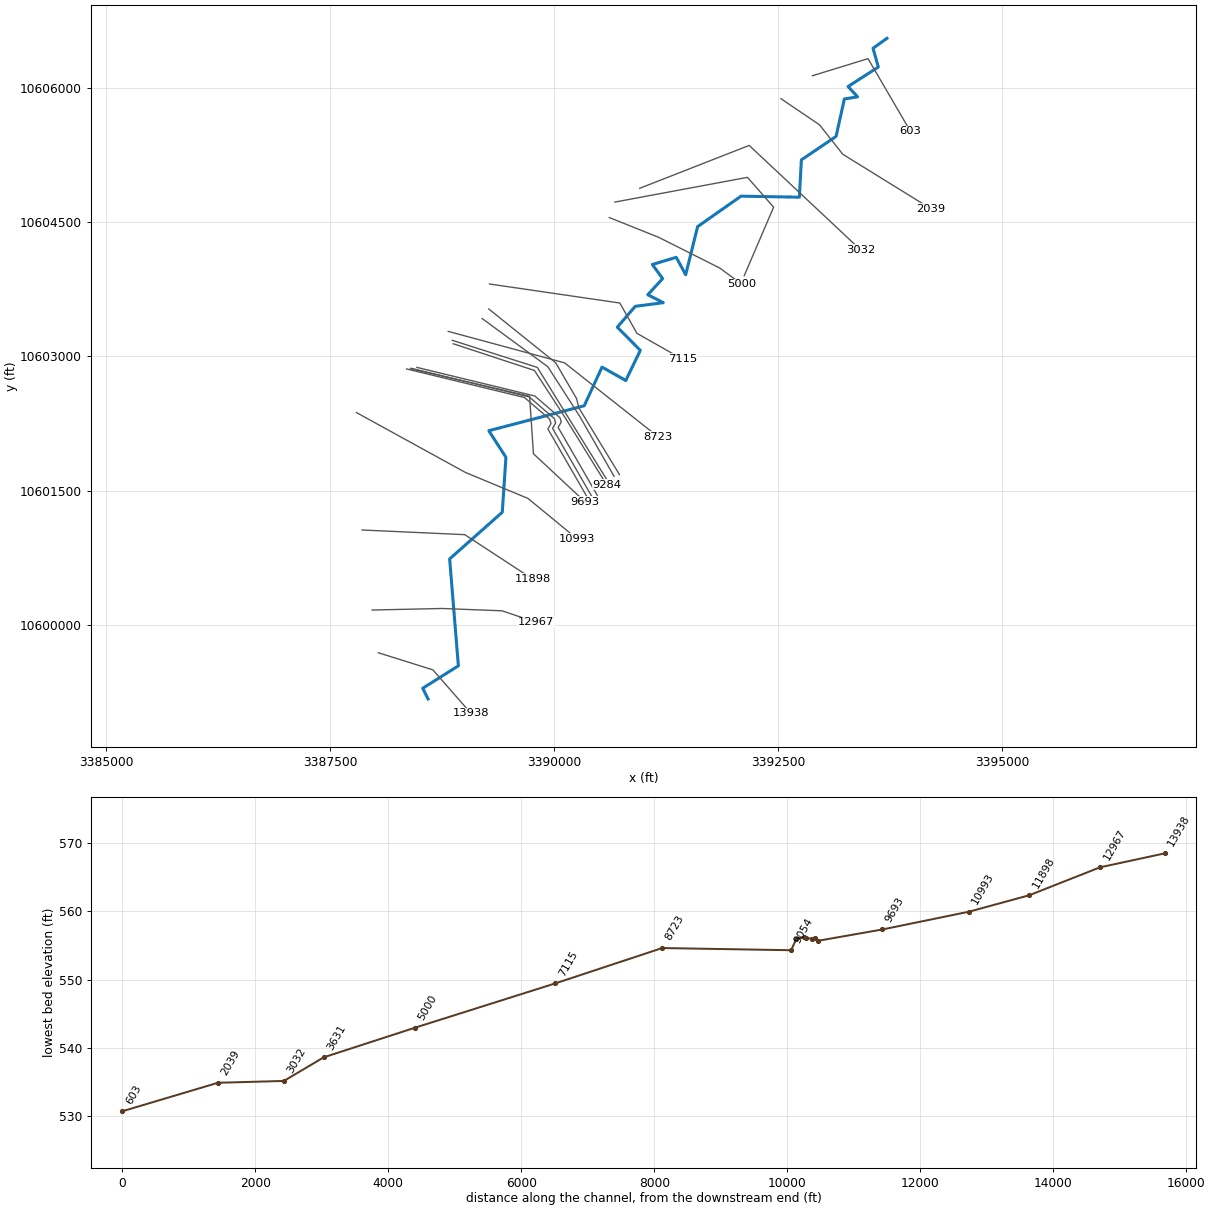
--- UNT0011 IN CHRS.prj (project) ---

Proj Title=UNT0011 IN CHRS Base Level Engineering
Current Plan=p01
Default Exp/Contr=0.3,0.1
English Units
Geom File=g01
Flow File=f01
Plan File=p01
Y Axis Title=Elevation
X Axis Title(PF)=Main Channel Distance
X Axis Title(XS)=Station
BEGIN DESCRIPTION:
UNT0011 IN CHRS
END DESCRIPTION:
DSS Export Rating Curves= 0
DSS Export Rating Curve Sorted= 0
DSS Export Volume Flow Curves= 0
DXF OffsetX= 0
DXF OffsetY= 0
DXF ScaleX= 1
DXF ScaleY= 10

--- UNT0011 IN CHRS.p01 (plan) ---

Plan Title=Multiple Run
Short Identifier=Multiple
Geom File=g01
Flow File=f01
Subcritical Flow
K Sum by GR= 0
Std Step Tol= 0.01
Critical Tol= 0.01
Num of Std Step Trials= 20
Max Error Tol= 0.3
Flow Tol Ratio= 0.001
Split Flow NTrial= 30
Split Flow Tol= 0.02
Split Flow Ratio= 0.02
Log Output Level= 0
Friction Slope Method= 1
Unsteady Friction Slope Method= 2
Unsteady Bridges Friction Slope Method= 1
Parabolic Critical Depth
Global Vel Dist=  1 , 1 , 1
Global Log Level= 0
CheckData=True
Encroach Param= -1, 0, 0, 0
BEGIN DESCRIPTION:
Multiple Run
END DESCRIPTION:

--- UNT0011 IN CHRS.f01 (steady flow) ---

Flow Title=Multiple
Number of Profiles=7
Profile Names=10-year,25-year,50-year,1pct_min,100-year,1pct_plu,500-year
River Rch & RM= UNT0011 IN CHRS,Reach-1,13938
     420     531     612     513     694     938     891
River Rch & RM= UNT0011 IN CHRS,Reach-1,9693
     463     584     674     565     764    1033     981
River Rch & RM= UNT0011 IN CHRS,Reach-1,3032
     728     942    1103     938    1269    1716    1678
Boundary for River Rch & Prof#=UNT0011 IN CHRS,Reach-1,1
Up Type=0
Dn Type=3
Dn Slope=0.005
Boundary for River Rch & Prof#=UNT0011 IN CHRS,Reach-1,2
Up Type=0
Dn Type=3
Dn Slope=0.005
Boundary for River Rch & Prof#=UNT0011 IN CHRS,Reach-1,3
Up Type=0
Dn Type=3
Dn Slope=0.005
Boundary for River Rch & Prof#=UNT0011 IN CHRS,Reach-1,4
Up Type=0
Dn Type=3
Dn Slope=0.005
Boundary for River Rch & Prof#=UNT0011 IN CHRS,Reach-1,5
Up Type=0
Dn Type=3
Dn Slope=0.005
Boundary for River Rch & Prof#=UNT0011 IN CHRS,Reach-1,6
Up Type=0
Dn Type=3
Dn Slope=0.005
Boundary for River Rch & Prof#=UNT0011 IN CHRS,Reach-1,7
Up Type=0
Dn Type=3
Dn Slope=0.005

--- UNT0011 IN CHRS.g01 (geometry) ---

Geom Title=Existing Conditions
Program Version=4.10

River Reach=UNT0011 IN CHRS ,Reach-1
Reach XY= 30
      3388592.11     10599171.64      3388532.71     10599290.91
      3388930.73     10599541.55      3388833.35     10600735.86
      3389420.43     10601257.18      3389461.31     10601871.34
      3389270.12     10602168.24      3390334.54     10602446.65
      3390533.41     10602878.78      3390798.53     10602728.71
      3390960.32     10603065.91      3390703.83     10603324.86
      3390903.88     10603557.77      3391216.92     10603598.66
      3391043.85     10603687.32       3391209.7     10603867.32
      3391095.05     10604025.22      3391361.45      10604105.2
      3391466.59     10603910.27      3391599.72     10604447.91
      3392083.55     10604788.42      3392734.98       10604777.
      3392757.32     10605193.59      3393144.55     10605456.11
      3393237.16     10605874.17      3393384.56     10605897.98
       3393278.3     10606013.33        3393616.     10606230.79
      3393556.65     10606440.45      3393712.11     10606551.64

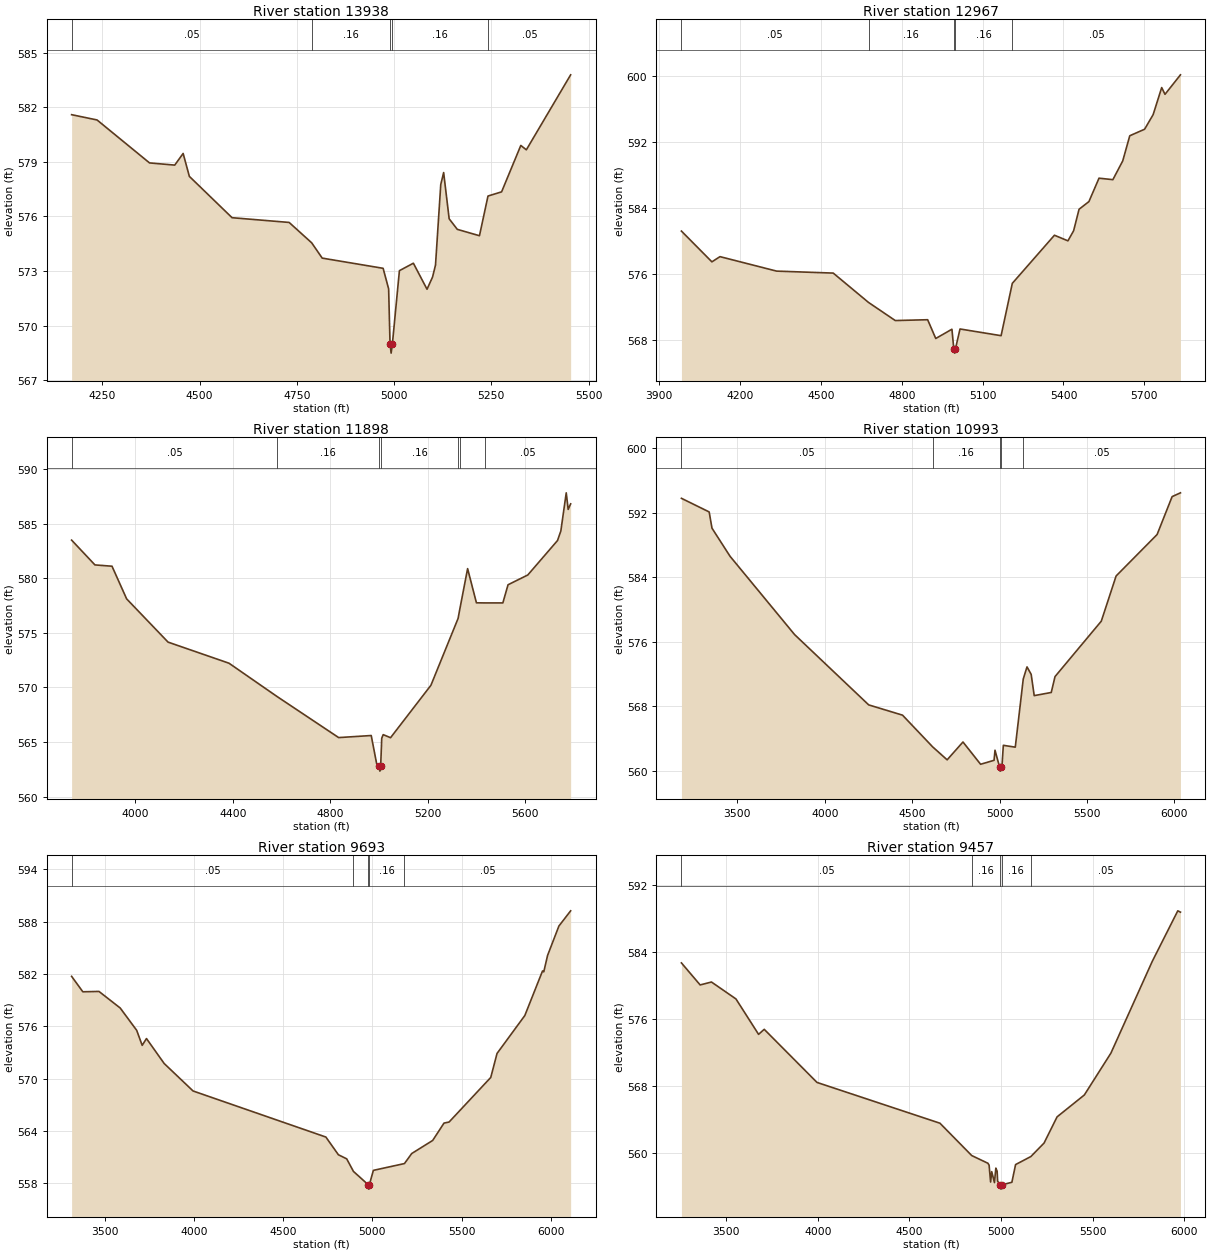
Type RM Length L Ch R = 1 ,13938   ,971,971,971
BEGIN DESCRIPTION:
UNT0011 IN CHRS 13.1
END DESCRIPTION:
XS GIS Cut Line= 3
      3388038.61     10599687.48      3388646.25     10599496.51
      3389071.61     10599010.38
#Sta/Elev= 30
  4171.1  581.59  4236.5   581.3  4371.4  578.94  4436.2  578.82  4457.8  579.46
  4473.8   578.2  4583.6  575.93  4730.3  575.67  4788.3  574.55  4815.3  573.71
  4971.9  573.15  4986.1  572.02  4989.7  568.99  4992.5  568.49  4995.7  568.99
  5013.8  573.02  5049.7  573.43  5084.8     572    5099  572.67  5106.6  573.33
  5120.1  577.75  5127.5  578.41  5141.7  575.87  5162.6  575.29  5219.6  574.94
  5241.5  577.12  5276.5  577.35  5325.9   579.9  5340.1  579.66    5454  583.78
#Mann= 5 ,-1 , 0
  4171.1     .05       0  4788.3     .16       0  4989.7     .07       0
  4995.7     .16       0  5241.5     .05       0
Bank Sta=4989.7,4995.7
XS Rating Curve= 0 ,0
Exp/Cntr=0.3,0.1

Type RM Length L Ch R = 1 ,12967   ,1069,1069,1069
BEGIN DESCRIPTION:
UNT0011 IN CHRS 13.2
END DESCRIPTION:
XS GIS Cut Line= 4
      3387969.15     10600164.91      3388750.41     10600182.28
      3389418.81     10600156.23      3389798.02     10600026.96
#Sta/Elev= 30
    3983  581.21    4096  577.49    4126  578.12    4336  576.37  4546.1  576.13
    4677  572.58  4776.2  570.39  4896.3  570.49  4926.3  568.22  4986.3  569.34
  4993.3  566.95  4996.1  566.45  4999.3  566.95  5016.3  569.37  5168.7  568.56
  5210.3  574.89  5366.6  580.71  5416.6  580.03  5437.7  581.25  5457.9  583.85
  5494.5  584.78  5531.9  587.61  5583.3  587.43  5619.9   589.7    5646  592.74
    5701  593.53  5732.7   595.3  5764.4  598.57  5776.6  597.75    5834  600.11
#Mann= 5 ,-1 , 0
    3983     .05       0    4677     .16       0  4993.3     .07       0
  4999.3     .16       0  5210.3     .05       0
Bank Sta=4993.3,4999.3
XS Rating Curve= 0 ,0
Exp/Cntr=0.3,0.1

Type RM Length L Ch R = 1 ,11898   ,905,905,905
BEGIN DESCRIPTION:
UNT0011 IN CHRS 13.0
END DESCRIPTION:
XS GIS Cut Line= 3
      3387856.36     10601059.01      3389002.15     10601006.93
      3389757.24     10600512.21
#Sta/Elev= 30
  3737.7  583.49  3833.5  581.22  3903.6   581.1  3963.7  578.11  4133.9  574.15
  4384.1  572.22  4582.2  569.16  4834.6  565.41  4968.3   565.6  4990.5  563.03
  5001.2  562.84  5003.9  562.34  5007.2  562.84  5011.5  565.35  5017.5  565.68
  5047.7   565.4  5213.5   570.2  5325.1  576.32  5332.7  577.23  5364.2  580.88
  5400.4  577.75  5436.4  577.74  5508.9  577.74  5530.2   579.4  5611.5   580.3
  5733.4  583.45  5747.1  584.32  5769.3  587.82  5777.3   586.3  5787.4  586.81
#Mann= 7 ,-1 , 0
  3737.7     .05       0  4582.2     .16       0  5001.2     .07       0
  5007.2     .16       0  5325.1     .05       0  5332.7     .16       0
  5436.4     .05       0
Bank Sta=5001.2,5007.2
XS Rating Curve= 0 ,0
Exp/Cntr=0.3,0.1

Type RM Length L Ch R = 1 ,10993   ,1300,1300,1300
BEGIN DESCRIPTION:
UNT0011 IN CHRS 11.0
END DESCRIPTION:
XS GIS Cut Line= 5
      3387793.57     10602370.65      3389008.84     10601702.25
      3389707.63     10601411.45      3390250.16      10600964.4
      3390258.01     10600960.47
#Sta/Elev= 30
  3179.7  593.76  3338.4  592.07  3354.5  590.06  3457.7  586.58  3827.1  576.87
  4251.4  568.15  4444.8  566.88  4617.6  562.94  4700.2  561.34  4790.8  563.55
  4891.6  560.79  4968.6  561.28    4974  562.53  5000.4  560.44  5003.2  559.94
  5006.4  560.44  5014.3  560.67  5021.7  563.14  5090.1  562.91  5135.7  571.36
  5157.2  572.86    5181  571.94  5198.4   569.3  5295.9  569.69  5317.5  571.66
  5582.3  578.53    5667  584.13  5901.6  589.27  5987.6  593.97  6035.3  594.44
#Mann= 5 ,-1 , 0
  3179.7     .05       0  4617.6     .16       0  5000.4     .07       0
  5006.4     .16       0  5135.7     .05       0
Bank Sta=5000.4,5006.4
XS Rating Curve= 0 ,0
Exp/Cntr=0.3,0.1

Type RM Length L Ch R = 1 ,9693    ,970,970,970
BEGIN DESCRIPTION:
UNT0011 IN CHRS 9.0
END DESCRIPTION:
XS GIS Cut Line= 4
      3388396.86      10602861.1      3389724.99     10602552.94
      3389768.39     10601910.58      3390345.68     10601372.36
#Sta/Elev= 30
  3315.1  581.73    3378  579.96  3468.5     580  3587.4   578.1  3679.8  575.54
  3710.6  573.82  3734.6   574.6  3833.8  571.74  3995.7  568.59  4739.9  563.31
  4810.1  561.28  4856.7  560.81  4894.5  559.37  4977.5  557.84  4980.2  557.34
  4983.5  557.84  5006.1  559.49  5180.3  560.27    5221  561.42  5338.5  562.92
    5402  564.91  5430.4  565.03  5663.9  570.14  5699.1  572.89  5854.9  577.24
  5954.1  582.35  5960.9  582.24  5982.4  584.13  6045.9   587.5  6111.6  589.24
#Mann= 5 ,-1 , 0
  3315.1     .05       0  4894.5     .16       0  4977.5     .07       0
  4983.5     .16       0  5180.3     .05       0
Bank Sta=4977.5,4983.5
XS Rating Curve= 0 ,0
Exp/Cntr=0.3,0.1

Type RM Length L Ch R = 1 ,9457    ,48,48,48
BEGIN DESCRIPTION:
UNT0011 IN CHRS 9.2
END DESCRIPTION:
XS GIS Cut Line= 6
       3388352.8     10602858.31      3389668.74     10602538.87
      3389949.99     10602295.82      3389963.88     10602247.21
      3389929.15     10602188.18      3390366.63      10601427.8
#Sta/Elev= 30
  3255.1  582.69  3357.3  580.06    3419  580.41  3552.8  578.39  3676.3  574.16
  3707.2  574.76  3995.3  568.42  4666.6  563.55    4840  559.69  4928.4  558.77
    4935  558.54  4943.2  556.53  4949.3  557.77  4964.1  556.46  4971.8  558.19
  4978.9  557.81  4981.4  556.63    4997  556.18  4999.8  555.68    5003  556.18
  5059.4   556.5  5079.5  558.61  5162.9  559.57    5235  561.18  5306.2  564.31
  5454.9  566.92  5600.1  571.92  5825.7  582.87  5965.2  588.91  5979.8  588.75
#Mann= 5 ,-1 , 0
  3255.1     .05       0    4840     .16       0    4997     .07       0
    5003     .16       0  5162.9     .05       0
Bank Sta=4997,5003
XS Rating Curve= 0 ,0
Exp/Cntr=0.3,0.1

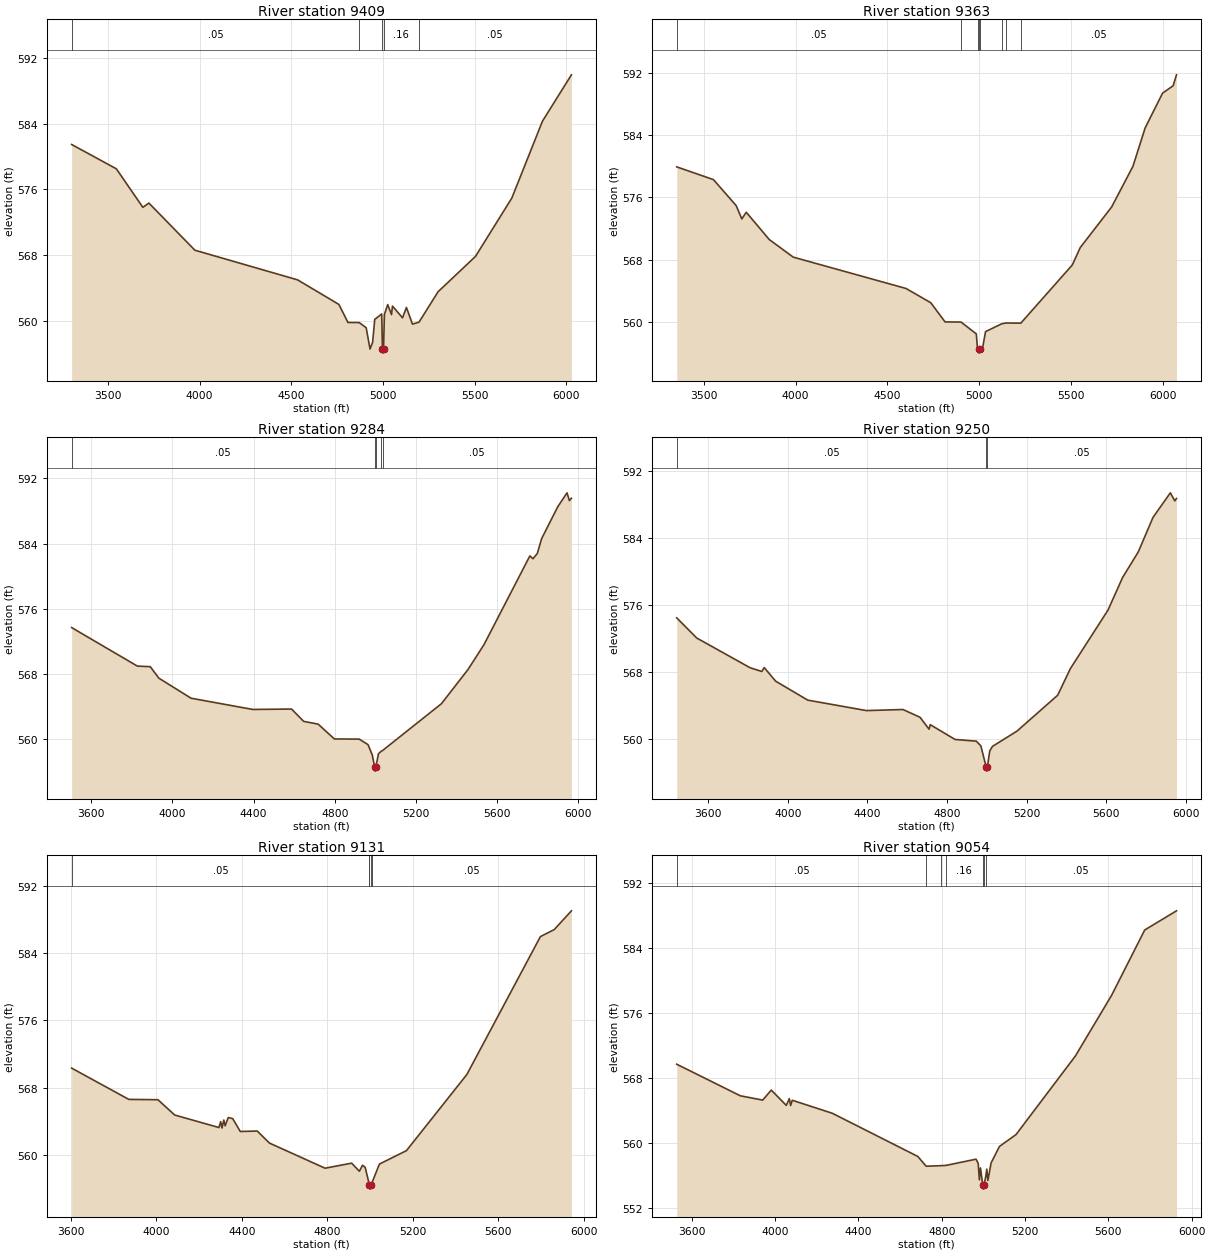
Type RM Length L Ch R = 1 ,9409    ,46,46,46
BEGIN DESCRIPTION:
UNT0011 IN CHRS 9.1
END DESCRIPTION:
XS GIS Cut Line= 6
      3388404.83     10602865.27      3389720.82     10602545.82
      3390002.07     10602302.76      3390015.96     10602254.15
      3389981.24     10602195.12      3390418.74     10601434.71
#Sta/Elev= 30
  3302.6  581.49  3546.4  578.52  3690.8  573.82  3723.8  574.34  3974.4  568.59
  4534.6  564.97  4759.8  561.97  4809.1  559.77  4870.6  559.76  4908.5  559.13
  4929.4  556.53  4943.6  557.36  4955.1  560.15    4993  560.81    4997  556.53
  4999.8  556.03    5003  556.53  5007.8  560.74  5025.9  561.95  5046.5  560.74
  5051.7  561.77  5106.6  560.34  5127.9   561.6  5160.9  559.57  5196.6  559.81
  5300.3  563.52  5504.4  567.83  5702.7  574.96  5869.5  584.33  6027.4  589.99
#Mann= 5 ,-1 , 0
  3302.6     .05       0  4870.6     .16       0    4997     .07       0
    5003     .16       0  5196.6     .05       0
Bank Sta=4997,5003
XS Rating Curve= 0 ,0
Exp/Cntr=0.3,0.1

Type RM Length L Ch R = 1 ,9363    ,79,79,79
BEGIN DESCRIPTION:
UNT0011 IN CHRS 9.0
END DESCRIPTION:
XS GIS Cut Line= 6
      3388467.31     10602875.69      3389783.32     10602556.23
      3390064.57     10602313.18      3390078.46     10602264.57
      3390043.74     10602205.54      3390480.78     10601445.92
#Sta/Elev= 30
    3352  579.93  3552.4  578.29  3675.9  574.96  3706.8  573.25    3731   574.1
  3856.3   570.6  3986.8  568.34  4602.1  564.31  4736.9  562.48  4814.6  560.02
  4901.7     560  4984.9  558.48  4991.6  556.51  4995.4  556.51    4997  556.51
  4999.8  556.01    5003  556.51  5020.3  556.83  5035.1  558.77    5123  559.77
  5147.1  559.88  5227.4  559.86  5508.4  567.34  5551.5  569.57  5722.5  574.78
  5838.6     580  5905.1  584.93  6000.1   589.4  6057.8  590.35  6075.9  591.75
#Mann= 8 ,-1 , 0
    3352     .05       0  4901.7     .16       0  4995.4     .05       0
    4997    .035       0    5003     .05       0    5123     .05       0
  5147.1     .16       0  5227.4     .05       0
Bank Sta=4997,5003
XS Rating Curve= 0 ,0
Exp/Cntr=0.3,0.1

Type RM Length L Ch R = 1 ,9284    ,34,34,34
BEGIN DESCRIPTION:
UNT0011 IN CHRS 8.2
END DESCRIPTION:
XS GIS Cut Line= 4
      3388873.63     10603139.56      3389779.85     10602840.96
      3390120.13     10602316.65      3390585.38     10601563.22
#Sta/Elev= 30
  3502.7  573.68  3826.9  568.95  3890.4  568.88  3932.8  567.47  4091.6  565.01
  4396.1  563.63  4587.2  563.68  4646.8  562.17  4718.3  561.83  4798.3  560.01
    4921  559.99  4964.4  559.31  4985.5  558.03    4997  556.56  4999.8  556.06
    5003  556.56  5015.8  558.19  5028.6  558.49  5036.1  558.59  5326.1  564.33
  5457.4  568.53  5536.6   571.6  5762.5  582.48  5777.8  582.13  5799.1  582.77
  5820.4  584.59  5899.6  588.49  5945.7  590.22  5957.5  589.27  5967.4  589.55
#Mann= 5 ,-1 , 0
  3502.7     .05       0    4997    .035       0    5003     .05       0
  5028.6     .16       0  5036.1     .05       0
Bank Sta=4997,5003
XS Rating Curve= 0 ,0
Exp/Cntr=0.3,0.1

Type RM Length L Ch R = 1 ,9250    ,119,119,119
BEGIN DESCRIPTION:
UNT0011 IN CHRS 8.1
END DESCRIPTION:
XS GIS Cut Line= 3
      3388863.22     10603177.75       3389811.1     10602875.68
      3390608.89     10601585.33
#Sta/Elev= 30
  3441.7   574.5  3542.2  572.09  3810.4  568.54  3869.5  568.09  3881.3  568.56
  3939.2  566.93  4100.3  564.67  4395.4  563.42  4578.8  563.55  4664.7  562.62
    4710   561.2  4715.9  561.74    4841  559.97  4947.5  559.77  4970.4   559.2
    4997  556.69  4999.8  556.19    5003  556.69    5015   558.6  5029.1  559.15
  5152.1  560.97  5356.6  565.26  5420.4  568.44  5609.5  575.43  5682.8  579.32
    5762  582.39  5835.3  586.48  5922.7  589.43  5945.3  588.47  5953.6  588.76
#Mann= 3 ,-1 , 0
  3441.7     .05       0    4997     .04       0    5003     .05       0
Bank Sta=4997,5003
XS Rating Curve= 0 ,0
Exp/Cntr=0.3,0.1

Type RM Length L Ch R = 1 ,9131    ,77,77,77
BEGIN DESCRIPTION:
UNT0011 IN CHRS 8.3
END DESCRIPTION:
XS GIS Cut Line= 4
      3389196.53      10603420.8      3389929.15     10602882.62
      3390283.32     10602330.54      3390667.92     10601658.36
#Sta/Elev= 30
  3602.9  570.31  3870.4  566.59  4006.9  566.55  4085.2  564.73  4292.3  563.24
  4300.5  563.94  4306.7  563.19  4315.1  564.13  4321.3  563.45    4336  564.43
  4356.8   564.3  4392.3  562.77  4471.8  562.82  4528.8  561.39  4789.1   558.4
  4913.4     559  4949.7  558.04  4964.6  558.75  4976.8  558.51  4996.8  556.41
    4997  556.41  4999.8  555.91    5003  556.41  5009.7  556.73  5043.5  558.89
  5170.1  560.49  5453.1  569.56  5797.1  585.96  5861.9   586.8  5942.3  589.03
#Mann= 5 ,-1 , 0
  3602.9     .05       0  4996.8     .16       0    4997     .07       0
    5003     .16       0  5009.7     .05       0
Bank Sta=4997,5003
XS Rating Curve= 0 ,0
Exp/Cntr=0.3,0.1

Type RM Length L Ch R = 1 ,9054    ,1939,1939,1939
BEGIN DESCRIPTION:
UNT0011 IN CHRS 8.0
END DESCRIPTION:
XS GIS Cut Line= 5
      3389269.45     10603528.44      3390015.96     10602927.76
       3390248.6     10602528.46      3390276.38     10602420.82
      3390727.46     10601678.26
#Sta/Elev= 30
    3527  569.69  3832.5   565.8  3939.7  565.27  3981.3   566.5  4053.3  564.62
  4067.7  565.45  4074.1  564.61    4082  565.25    4274  563.65  4684.7  558.33
  4725.2  557.12  4796.4  557.19  4819.6  557.22  4964.7  557.99    4975  557.46
  4980.8  555.44  4985.9  556.91    4997   554.8  4999.8   554.3    5003   554.8
  5011.4  555.88  5016.3  556.76  5021.4  555.36    5037  557.53  5077.1  559.56
  5156.6  561.02  5441.4  570.69  5615.9  578.19  5774.8  586.23  5927.3  588.59
#Mann= 7 ,-1 , 0
    3527     .05       0  4725.2     .16       0  4796.4     .05       0
  4819.6     .16       0    4997     .07       0    5003     .16       0
  5011.4     .05       0
Bank Sta=4997,5003
XS Rating Curve= 0 ,0
Exp/Cntr=0.3,0.1

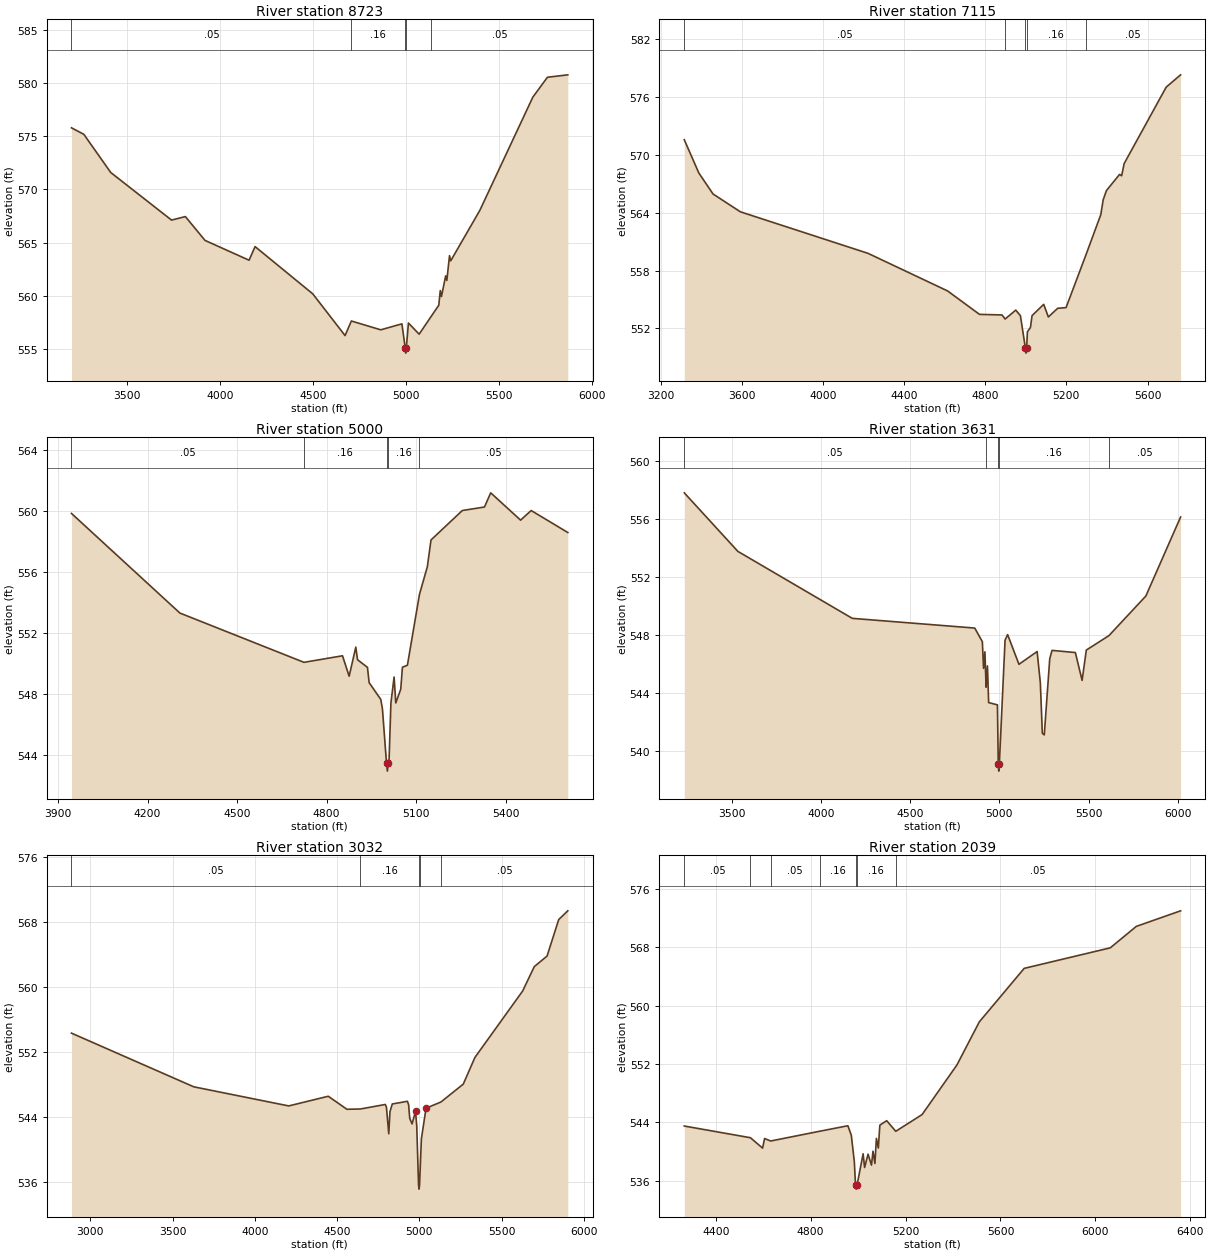
Type RM Length L Ch R = 1 ,8723    ,1608,1608,1608
BEGIN DESCRIPTION:
UNT0011 IN CHRS 8.0
END DESCRIPTION:
XS GIS Cut Line= 3
      3388817.85     10603277.78      3390115.61     10602926.21
      3391157.18     10602101.63
#Sta/Elev= 30
  3199.3  575.79  3265.9  575.18  3410.9  571.59  3738.2  567.12  3812.7  567.45
  3918.6  565.21  4155.7  563.35    4188  564.63  4498.8  560.19  4672.7  556.27
  4706.6  557.64    4865  556.81  4978.8  557.37  4996.6  555.12  4999.3  554.62
  5002.6  555.12    5014  557.45  5071.7   556.4  5137.2  558.09  5177.5  559.12
  5185.5   560.5  5191.9  559.94  5214.4  561.88  5220.8  561.45  5235.2  563.78
  5241.6  563.29  5398.7  568.04  5683.9  578.67  5762.5  580.54  5872.3  580.77
#Mann= 5 ,-1 , 0
  3199.3     .05       0  4706.6     .16       0  4996.6     .07       0
  5002.6     .16       0  5137.2     .05       0
Bank Sta=4996.6,5002.6
XS Rating Curve= 0 ,0
Exp/Cntr=0.3,0.1

Type RM Length L Ch R = 1 ,7115    ,2115,2115,2115
BEGIN DESCRIPTION:
UNT0011 IN CHRS 6.0
END DESCRIPTION:
XS GIS Cut Line= 5
       3389277.9     10603807.29      3390731.93     10603594.61
       3390922.9     10603256.07      3391426.38     10602969.61
      3391435.02     10602969.61
#Sta/Elev= 30
    3317  571.58  3388.7  568.13  3458.7  565.95  3593.5   564.1  4222.7  559.79
  4614.9  555.89    4772  553.46    4883   553.4  4898.4  552.98  4950.6   553.9
  4973.6  553.33  4998.4  549.94  5001.2  549.44  5004.4  549.94  5008.1  551.65
  5023.1   552.1    5031  553.33  5088.4   554.5  5111.4  553.19  5157.3  554.09
  5198.6  554.16  5296.4  559.62  5369.9  563.81  5381.7  565.35  5397.5   566.3
  5462.4  567.98  5472.5  567.84  5484.9   569.1    5692  577.03  5763.1  578.31
#Mann= 5 ,-1 , 0
    3317     .05       0  4898.4     .16       0  4998.4     .07       0
  5004.4     .16       0  5296.4     .05       0
Bank Sta=4998.4,5004.4
XS Rating Curve= 0 ,0
Exp/Cntr=0.3,0.1

Type RM Length L Ch R = 1 ,5000    ,1369,1369,1369
BEGIN DESCRIPTION:
UNT0011 IN CHRS 5.0
END DESCRIPTION:
XS GIS Cut Line= 4
      3390614.77     10604549.46      3391165.96     10604328.12
      3391847.38     10603985.23      3392094.78     10603802.94
#Sta/Elev= 30
  3944.8  559.82  4308.3  553.29  4724.3  550.06  4853.5  550.49  4875.8  549.15
  4898.1  551.06  4903.9  550.23  4937.2  549.73  4942.8  548.73  4981.8  547.63
  4987.4  547.01  5001.1  543.43  5003.9  542.93  5007.1  543.43  5009.7  543.71
  5015.8  547.39  5026.5   549.1  5032.1   547.4  5048.8   548.3  5054.4  549.74
  5071.1  549.87  5111.6  554.52    5138  556.33  5150.2  558.08  5255.2  560.01
  5329.5  560.24  5350.4  561.17  5450.6  559.38  5486.1  560.01  5608.9  558.57
#Mann= 5 ,-1 , 0
  3944.8     .05       0  4724.3     .16       0  5001.1     .07       0
  5007.1     .16       0  5111.6     .05       0
Bank Sta=5001.1,5007.1
XS Rating Curve= 0 ,0
Exp/Cntr=0.3,0.1

Type RM Length L Ch R = 1 ,3631    ,599,599,599
BEGIN DESCRIPTION:
UNT0011 IN CHRS 4.0
END DESCRIPTION:
XS GIS Cut Line= 4
      3390676.93     10604722.57      3392156.11     10604998.62
      3392447.78     10604665.28      3392119.67     10603899.68
#Sta/Elev= 30
  3234.5   557.8  3534.8  553.76  4175.7  549.14  4861.8  548.47  4904.5  547.53
  4911.2  545.69  4918.8  546.83  4922.7  545.39  4925.4  544.39    4933  545.86
  4939.7  543.33    4989  543.17  4993.6   539.1  4996.4   538.6  4999.6   539.1
  5031.7  547.63    5046  548.02  5109.5  545.97  5211.3  546.85  5229.4  544.68
  5240.5  541.21  5251.4   541.1    5282  546.35  5294.9  546.93  5425.5  546.78
  5463.3  544.86  5486.9  546.95  5613.8  547.95  5820.5  550.68  6015.1  556.13
#Mann= 5 ,-1 , 0
  3234.5     .05       0  4922.7     .16       0  4993.6     .07       0
  4999.6     .16       0  5613.8     .05       0
Bank Sta=4993.6,4999.6
XS Rating Curve= 0 ,0
Exp/Cntr=0.3,0.1

Type RM Length L Ch R = 1 ,3032    ,993,993,993
BEGIN DESCRIPTION:
UNT0011 IN CHRS 3.0
END DESCRIPTION:
XS GIS Cut Line= 3
      3390953.03     10604876.12      3392175.22     10605355.28
      3393417.66     10604189.19
#Sta/Elev= 30
  2885.8  554.32  3629.1  547.72  4206.2  545.37  4446.5  546.56  4559.8  544.96
  4640.8  544.99  4793.3  545.55  4800.1  545.22  4814.3  541.95  4821.6  544.67
  4835.8  545.61  4927.6  545.94  4934.9  545.52  4941.8  543.84  4955.9  543.16
  4976.9  544.71  4984.3  542.91  4995.4  535.64  4998.2  535.14  5001.4  535.64
  5012.6  541.33  5040.9  545.09    5131  545.85  5267.1  548.05  5337.9  551.33
    5628   559.5  5698.8   562.5  5776.5   563.8  5847.3  568.29  5902.5  569.36
#Mann= 5 ,-1 , 0
  2885.8     .05       0  4640.8     .16       0  4995.4     .07       0
  5001.4     .16       0    5131     .05       0
Bank Sta=4976.9,5040.9
XS Rating Curve= 0 ,0
Exp/Cntr=0.3,0.1

Type RM Length L Ch R = 1 ,2039    ,1436,1436,1436
BEGIN DESCRIPTION:
UNT0011 IN CHRS 2.0
END DESCRIPTION:
XS GIS Cut Line= 4
      3392528.77     10605877.62      3392958.49      10605586.8
      3393218.91     10605256.94      3394198.44     10604650.15
#Sta/Elev= 30
  4267.6  543.51  4546.2  541.91  4597.6  540.49    4606   541.8  4631.8  541.46
  4838.9   542.8    4957  543.55  4971.4  542.26  4984.2  538.63  4989.3  535.37
    4992  534.87  4995.3  535.37  5021.2  539.71  5027.5  537.83    5042  539.66
  5056.4  538.16  5062.8  540.06  5070.9  538.39  5077.2  541.82  5085.3   540.5
  5091.7  543.63  5120.5  544.24  5158.8  542.79  5269.7  545.08  5416.3  551.86
  5510.8  557.77  5699.9   565.1  6062.6  567.91  6172.5  570.85    6359  572.98
#Mann= 7 ,-1 , 0
  4267.6     .05       0  4546.2     .16       0  4631.8     .05       0
  4838.9     .16       0  4989.3     .07       0  4995.3     .16       0
  5158.8     .05       0
Bank Sta=4989.3,4995.3
XS Rating Curve= 0 ,0
Exp/Cntr=0.3,0.1

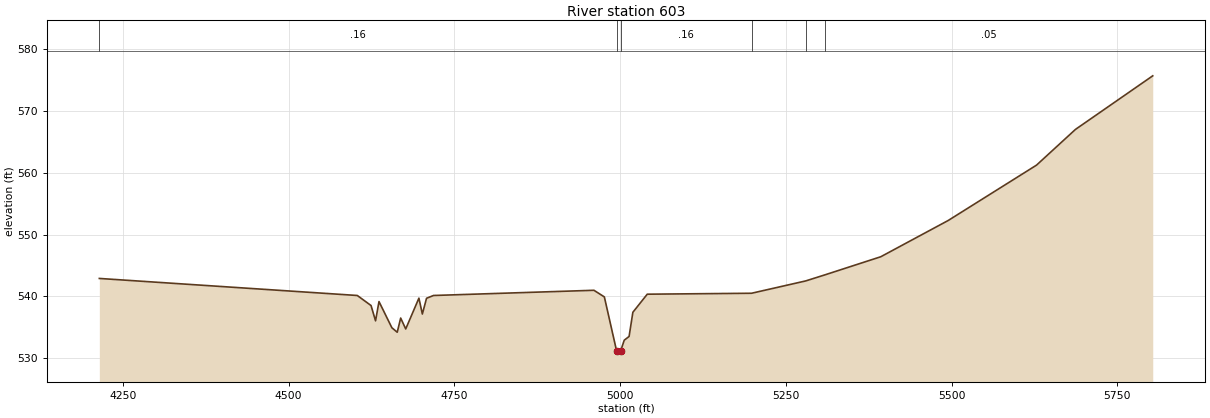
Type RM Length L Ch R = 1 ,603     ,0,0,0
BEGIN DESCRIPTION:
UNT0011 IN CHRS 1.0
END DESCRIPTION:
XS GIS Cut Line= 3
       3392880.4     10606133.68      3393501.03     10606324.64
      3393974.12     10605513.01
#Sta/Elev= 30
  4214.6  542.91  4603.7  540.16  4624.4  538.54  4631.2  536.07  4636.4  539.18
  4655.8  534.96  4663.9  534.23  4669.1  536.52  4676.7  534.76  4696.6  539.73
  4701.8  537.17  4708.1  539.71  4718.6  540.16  4960.6     541  4976.3  539.93
  4994.8   531.2  4997.6   530.7  5000.8   531.2  5006.3  532.95  5013.6  533.55
  5019.3  537.45    5041  540.37  5198.3  540.52    5280  542.51  5309.3   543.5
  5393.2  546.41  5494.9  552.26  5628.1  561.19  5686.8  566.95  5803.4   575.6
#Mann= 6 ,-1 , 0
  4214.6     .16       0  4994.8     .07       0  5000.8     .16       0
  5198.3     .05       0    5280     .16       0  5309.3     .05       0
Bank Sta=4994.8,5000.8
XS Rating Curve= 0 ,0
Exp/Cntr=0.3,0.1

Chan Stop Cuts=-1
Use User Specified Reach Order=0
Composite Channel Slope=5