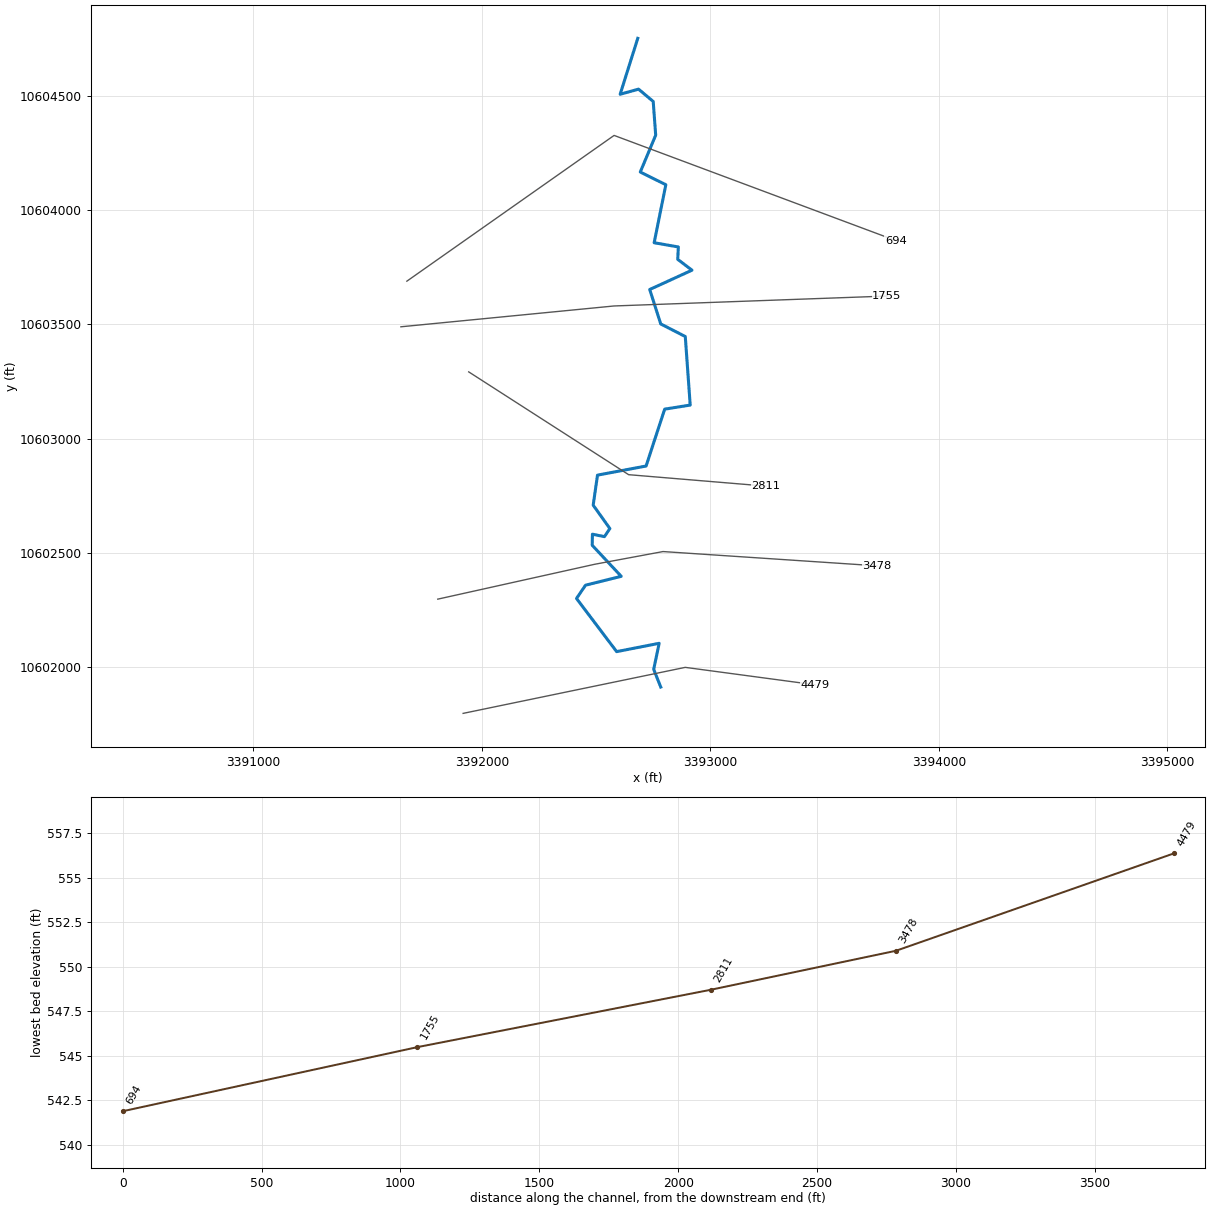
--- UNT0012 IN CHRS.prj (project) ---

Proj Title=UNT0012 IN CHRS Base Level Engineering
Current Plan=p01
Default Exp/Contr=0.3,0.1
English Units
Geom File=g01
Flow File=f01
Plan File=p01
BEGIN DESCRIPTION:
UNT0012 IN CHRS
END DESCRIPTION:

--- UNT0012 IN CHRS.p01 (plan) ---

Plan Title=Multiple Run
Short Identifier=Multiple
Geom File=g01
Flow File=f01
Subcritical Flow
K Sum by GR= 0
Std Step Tol= 0.01
Critical Tol= 0.01
Num of Std Step Trials= 20
Max Error Tol= 0.3
Flow Tol Ratio= 0.001
Split Flow NTrial= 30
Split Flow Tol= 0.02
Split Flow Ratio= 0.02
Log Output Level= 0
Friction Slope Method= 1
Unsteady Friction Slope Method= 2
Unsteady Bridges Friction Slope Method= 1
Parabolic Critical Depth
Global Vel Dist=  1 , 1 , 1
Global Log Level= 0
CheckData=True
Encroach Param= -1, 0, 0, 0
BEGIN DESCRIPTION:
Multiple Run
END DESCRIPTION:

--- UNT0012 IN CHRS.f01 (steady flow) ---

Flow Title=Multiple
Number of Profiles=7
Profile Names=10-year,25-year,50-year,1pct_min,100-year,1pct_plu,500-year
River Rch & RM= UNT0012 IN CHRS,Reach-1,4479
     395     497     571     478     647     874     827
Boundary for River Rch & Prof#=UNT0012 IN CHRS,Reach-1,1
Up Type=0
Dn Type=3
Dn Slope=0.005
Boundary for River Rch & Prof#=UNT0012 IN CHRS,Reach-1,2
Up Type=0
Dn Type=3
Dn Slope=0.005
Boundary for River Rch & Prof#=UNT0012 IN CHRS,Reach-1,3
Up Type=0
Dn Type=3
Dn Slope=0.005
Boundary for River Rch & Prof#=UNT0012 IN CHRS,Reach-1,4
Up Type=0
Dn Type=3
Dn Slope=0.005
Boundary for River Rch & Prof#=UNT0012 IN CHRS,Reach-1,5
Up Type=0
Dn Type=3
Dn Slope=0.005
Boundary for River Rch & Prof#=UNT0012 IN CHRS,Reach-1,6
Up Type=0
Dn Type=3
Dn Slope=0.005
Boundary for River Rch & Prof#=UNT0012 IN CHRS,Reach-1,7
Up Type=0
Dn Type=3
Dn Slope=0.005

--- UNT0012 IN CHRS.g01 (geometry) ---

Geom Title=Existing Conditions

River Reach=UNT0012 IN CHRS,Reach-1
Reach XY= 30
      3392782.68     10601911.92      3392751.86     10601989.73
      3392775.77     10602103.46      3392589.59     10602067.09
      3392413.91     10602299.80      3392453.45     10602357.84
      3392609.77     10602396.69      3392482.65     10602532.61
      3392483.69     10602581.14      3392536.28     10602570.31
      3392559.94     10602605.79      3392486.96     10602708.13
      3392505.91     10602839.68      3392718.54     10602879.51
      3392799.93     10603128.50      3392911.68     10603146.32
      3392890.03     10603446.39      3392782.59     10603501.55
      3392734.40     10603652.25      3392919.44     10603736.68
      3392857.08     10603784.21      3392859.77     10603838.40
      3392753.88     10603856.94      3392805.00     10604110.85
      3392693.10     10604166.35      3392760.51     10604327.59
      3392749.77     10604475.25      3392685.53     10604529.17
      3392605.01     10604506.88      3392682.11     10604751.64

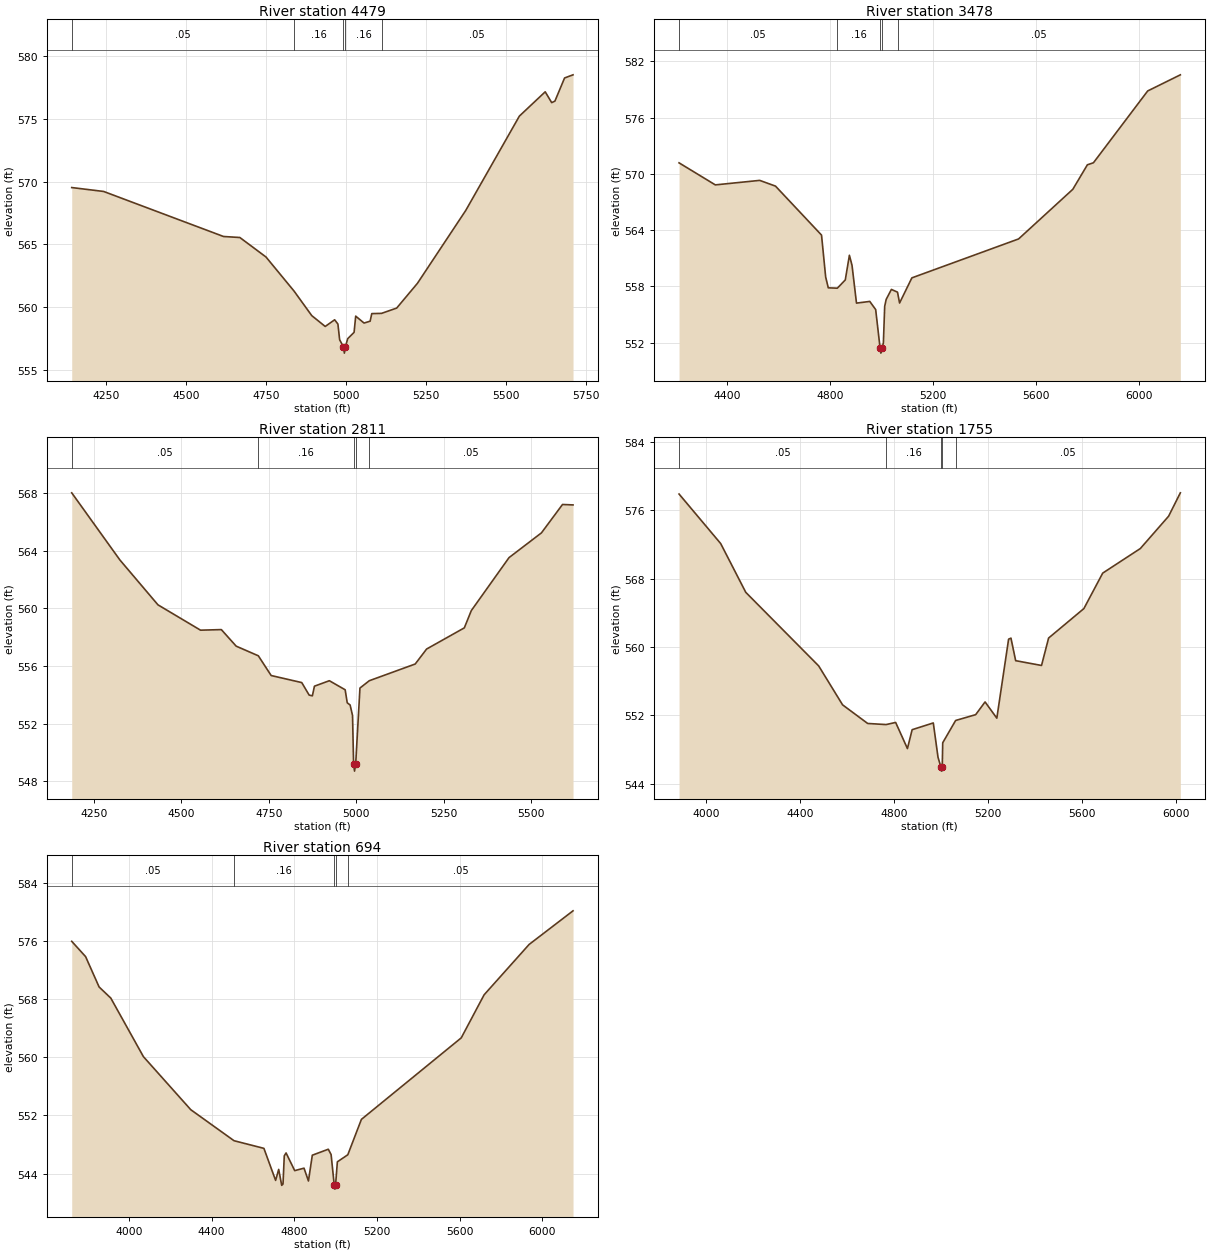
Type RM Length L Ch R = 1,4479,1001,1001,1001
BEGIN DESCRIPTION:
UNT0012 IN CHRS 4.1
END DESCRIPTION:
XS GIS Cut Line= 3
      3391917.68     10601796.79      3392889.93     10601998.18
      3393458.25     10601921.94
#Sta/Elev= 30
  4143.1  569.52  4242.8  569.21  4617.4  565.63  4668.4  565.55  4750.1  564.00
  4837.8  561.29  4893.1  559.34  4935.1  558.48  4964.6  559.01  4974.8  558.67
  4980.2  557.42  4992.2  556.86  4995.0  556.36  4998.2  556.86  5005.4  557.51
  5025.3  558.01  5030.4  559.30  5056.5  558.75  5075.5  558.90  5080.6  559.50
  5111.1  559.52  5158.4  559.94  5223.3  561.91  5374.2  567.70  5541.8  575.20
  5622.5  577.13  5642.7  576.27  5652.8  576.39  5683.0  578.23  5709.4  578.48
#Mann=5,-1,0
  4143.1    0.05       0  4837.8    0.16       0  4992.2    0.07       0
  4998.2    0.16       0  5111.1    0.05       0
Bank Sta=4992.2,4998.2
Exp/Cntr=0.3,0.1

Type RM Length L Ch R = 1,3478,667,667,667
BEGIN DESCRIPTION:
UNT0012 IN CHRS 4.2
END DESCRIPTION:
XS GIS Cut Line= 4
      3391806.59     10602296.79      3392494.09     10602449.57
      3392792.70     10602505.12      3393728.62     10602442.73
#Sta/Elev= 30
  4214.2  571.17  4355.0  568.82  4527.2  569.30  4588.6  568.69  4767.3  563.47
  4783.3  559.01  4793.5  557.85  4828.6  557.81  4859.5  558.69  4875.5  561.32
  4885.7  560.24  4903.0  556.22  4954.6  556.40  4977.5  555.53  4994.8  551.39
  4997.6  550.89  5000.8  551.39  5007.4  551.96  5012.5  555.88  5018.2  556.61
  5038.5  557.68  5062.2  557.39  5070.3  556.23  5118.0  558.91  5532.3  563.06
  5742.8  568.35  5799.3  570.96  5822.9  571.18  6033.4  578.83  6160.2  580.55
#Mann=5,-1,0
  4214.2    0.05       0  4828.6    0.16       0  4994.8    0.07       0
  5000.8    0.16       0  5062.2    0.05       0
Bank Sta=4994.8,5000.8
Exp/Cntr=0.3,0.1

Type RM Length L Ch R = 1,2811,1056,1056,1056
BEGIN DESCRIPTION:
UNT0012 IN CHRS 4.0
END DESCRIPTION:
XS GIS Cut Line= 3
      3391942.12     10603291.63      3392642.11     10602841.64
      3393242.08     10602791.64
#Sta/Elev= 30
  4186.2  568.03  4323.9  563.37  4432.9  560.25  4554.7  558.49  4614.2  558.53
  4656.7  557.38  4720.1  556.71  4756.8  555.34  4844.3  554.85  4865.5  553.98
  4874.7  553.93  4880.6  554.60  4923.2  554.98  4968.5  554.35  4974.4  553.45
  4982.7  553.29  4989.6  552.56  4992.6  549.20  4995.3  548.70  4998.6  549.20
  5010.8  554.47  5037.6  554.98  5168.9  556.14  5201.5  557.18  5309.4  558.65
  5329.4  559.85  5437.3  563.53  5530.1  565.25  5590.3  567.22  5620.4  567.19
#Mann=5,-1,0
  4186.2    0.05       0  4720.1    0.16       0  4992.6    0.07       0
  4998.6    0.16       0  5037.6    0.05       0
Bank Sta=4992.6,4998.6
Exp/Cntr=0.3,0.1

Type RM Length L Ch R = 1,1755,1061,1061,1061
BEGIN DESCRIPTION:
UNT0012 IN CHRS 2.0
END DESCRIPTION:
XS GIS Cut Line= 3
      3391645.30     10603488.99      3392578.50     10603580.14
      3393772.07     10603623.54
#Sta/Elev= 30
  3886.7  577.92  4063.8  572.12  4170.5  566.41  4480.5  557.80  4582.2  553.24
  4688.9  551.06  4767.3  550.93  4807.9  551.18  4858.0  548.12  4878.0  550.33
  4968.0  551.12  4988.1  547.10  5000.1  545.98  5002.9  545.48  5006.1  545.98
  5008.1  548.80  5063.0  551.41  5148.2  552.09  5188.2  553.58  5238.2  551.68
  5288.3  560.93  5298.3  561.05  5318.3  558.41  5428.3  557.85  5458.4  561.06
  5608.5  564.51  5688.5  568.66  5848.6  571.54  5968.7  575.32  6018.7  578.06
#Mann=5,-1,0
  3886.7    0.05       0  4767.3    0.16       0  5000.1    0.07       0
  5006.1    0.16       0  5063.0    0.05       0
Bank Sta=5000.1,5006.1
Exp/Cntr=0.3,0.1

Type RM Length L Ch R = 1,694,0,0,0
BEGIN DESCRIPTION:
UNT0012 IN CHRS 1.0
END DESCRIPTION:
XS GIS Cut Line= 3
      3391671.41     10603688.67      3392578.50     10604326.67
      3393811.05     10603866.63
#Sta/Elev= 30
  3723.5  575.92  3790.6  573.82  3855.9  569.65  3912.5  568.12  4070.2  560.08
  4299.3  552.79  4508.5  548.53  4653.0  547.48  4709.6  543.08  4724.5  544.59
  4739.1  542.40  4745.4  542.57  4751.5  546.45  4760.2  546.85  4802.0  544.42
  4847.0  544.76  4868.4  543.00  4887.1  546.54  4964.4  547.36  4978.0  546.63
  4993.4  542.38  4996.2  541.88  4999.4  542.38  5008.3  545.63  5058.8  546.60
  5124.5  551.46  5607.5  562.66  5718.0  568.57  5935.7  575.49  6148.1  580.11
#Mann=5,-1,0
  3723.5    0.05       0  4508.5    0.16       0  4993.4    0.07       0
  4999.4    0.16       0  5058.8    0.05       0
Bank Sta=4993.4,4999.4
Exp/Cntr=0.3,0.1

Chan Stop Cuts=-1