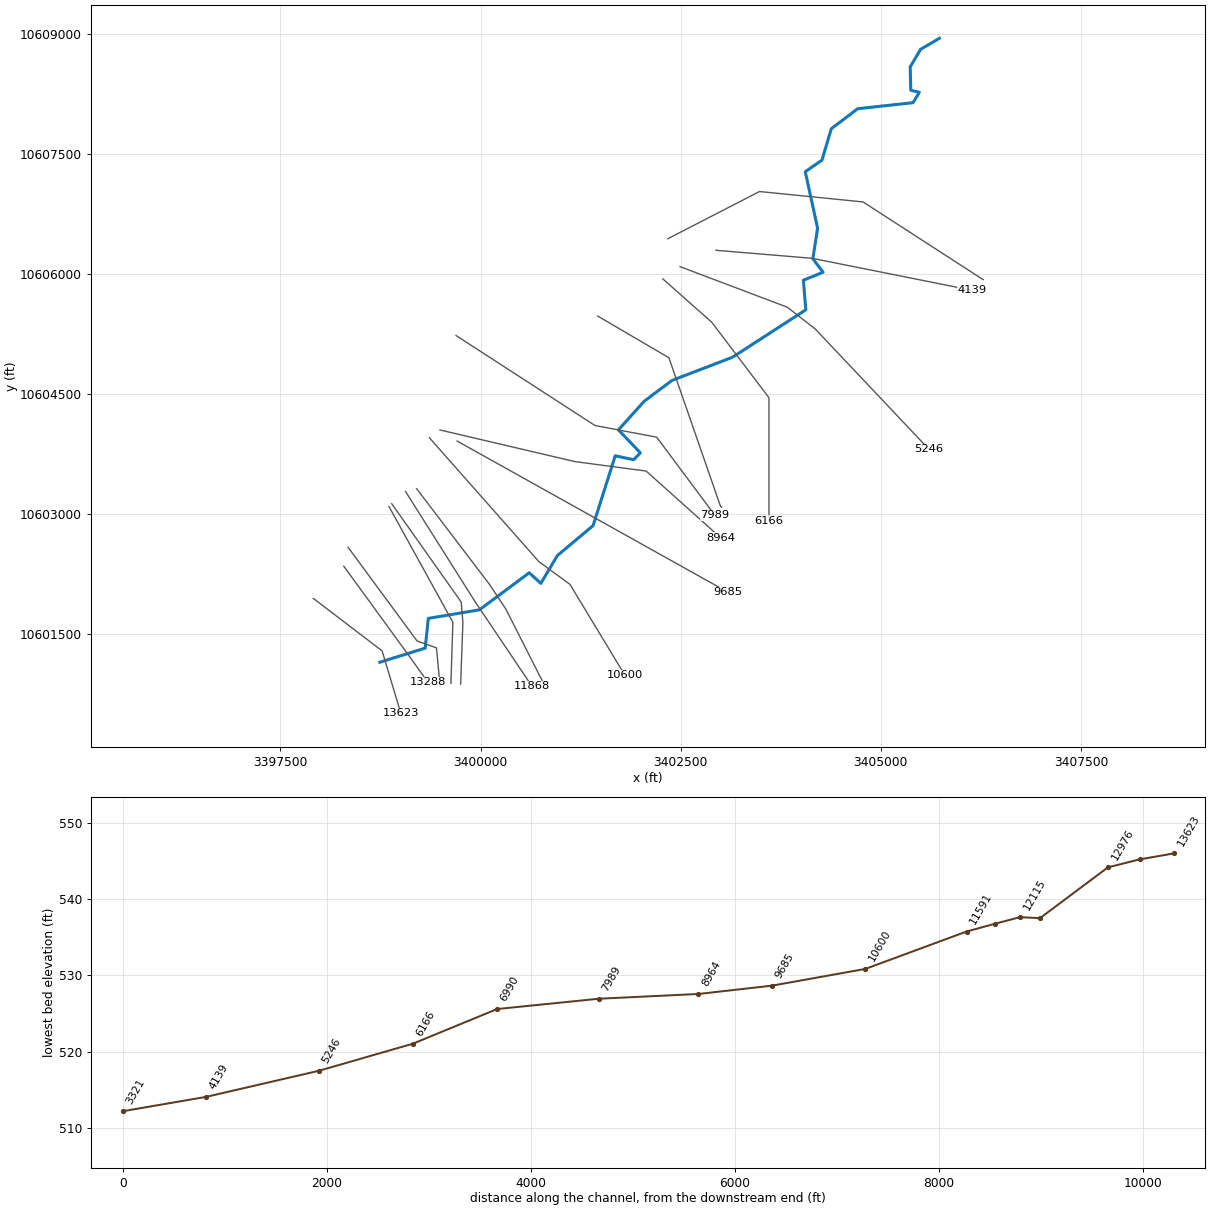
--- UNT0013 IN CHRS.prj (project) ---

Proj Title=UNT0013 IN CHRS Base Level Engineering
Current Plan=p01
Default Exp/Contr=0.3,0.1
English Units
Geom File=g01
Flow File=f01
Plan File=p01
Y Axis Title=Elevation
X Axis Title(PF)=Main Channel Distance
X Axis Title(XS)=Station
BEGIN DESCRIPTION:
UNT0013 IN CHRS
END DESCRIPTION:
DSS Export Rating Curves= 0
DSS Export Rating Curve Sorted= 0
DSS Export Volume Flow Curves= 0
DXF OffsetX= 0
DXF OffsetY= 0
DXF ScaleX= 1
DXF ScaleY= 10

--- UNT0013 IN CHRS.p01 (plan) ---

Plan Title=Multiple Run
Short Identifier=Multiple
Geom File=g01
Flow File=f01
Subcritical Flow
K Sum by GR= 0
Std Step Tol= 0.01
Critical Tol= 0.01
Num of Std Step Trials= 20
Max Error Tol= 0.3
Flow Tol Ratio= 0.001
Split Flow NTrial= 30
Split Flow Tol= 0.02
Split Flow Ratio= 0.02
Log Output Level= 0
Friction Slope Method= 1
Unsteady Friction Slope Method= 2
Unsteady Bridges Friction Slope Method= 1
Parabolic Critical Depth
Global Vel Dist=  1 , 1 , 1
Global Log Level= 0
CheckData=True
Encroach Param= -1, 0, 0, 0
BEGIN DESCRIPTION:
Multiple Run
END DESCRIPTION:

--- UNT0013 IN CHRS.f01 (steady flow) ---

Flow Title=Multiple
Number of Profiles=7
Profile Names=10-year,25-year,50-year,1pct_min,100-year,1pct_plu,500-year
River Rch & RM= UNT0013 IN CHRS,Reach-1,13623
     451     573     664     560     757    1024     984
River Rch & RM= UNT0013 IN CHRS,Reach-1,11868
     567     724     842     711     962    1301    1254
River Rch & RM= UNT0013 IN CHRS,Reach-1,4139
     740     959    1126     959    1297    1755    1722
Boundary for River Rch & Prof#=UNT0013 IN CHRS,Reach-1,1
Up Type=0
Dn Type=3
Dn Slope=0.005
Boundary for River Rch & Prof#=UNT0013 IN CHRS,Reach-1,2
Up Type=0
Dn Type=3
Dn Slope=0.005
Boundary for River Rch & Prof#=UNT0013 IN CHRS,Reach-1,3
Up Type=0
Dn Type=3
Dn Slope=0.005
Boundary for River Rch & Prof#=UNT0013 IN CHRS,Reach-1,4
Up Type=0
Dn Type=3
Dn Slope=0.005
Boundary for River Rch & Prof#=UNT0013 IN CHRS,Reach-1,5
Up Type=0
Dn Type=3
Dn Slope=0.005
Boundary for River Rch & Prof#=UNT0013 IN CHRS,Reach-1,6
Up Type=0
Dn Type=3
Dn Slope=0.005
Boundary for River Rch & Prof#=UNT0013 IN CHRS,Reach-1,7
Up Type=0
Dn Type=3
Dn Slope=0.005

--- UNT0013 IN CHRS.g01 (geometry) ---

Geom Title=Existing Conditions
Program Version=4.10

River Reach=UNT0013 IN CHRS ,Reach-1
Reach XY= 30
      3398742.11     10601141.64       3399308.9     10601317.88
      3399347.56     10601689.69      3399984.95     10601796.18
      3400608.57     10602259.78      3400753.23     10602127.24
      3400960.99     10602476.14      3401406.23     10602849.36
      3401682.64     10603721.97      3401914.01     10603673.82
      3401996.74     10603759.28      3401723.05     10604046.64
      3402043.13     10604402.89      3402392.19     10604664.98
      3403147.39     10604954.04      3404064.06     10605547.79
      3404033.68     10605917.58      3404279.52     10606017.33
      3404151.71     10606186.53       3404211.3     10606567.97
      3404057.28     10607274.22      3404266.23     10607419.45
      3404382.32     10607811.67      3404712.11     10608061.64
      3405403.28     10608137.18      3405481.95     10608266.81
      3405375.39      10608292.8      3405368.39      10608584.5
      3405497.44     10608803.25      3405732.11     10608941.64

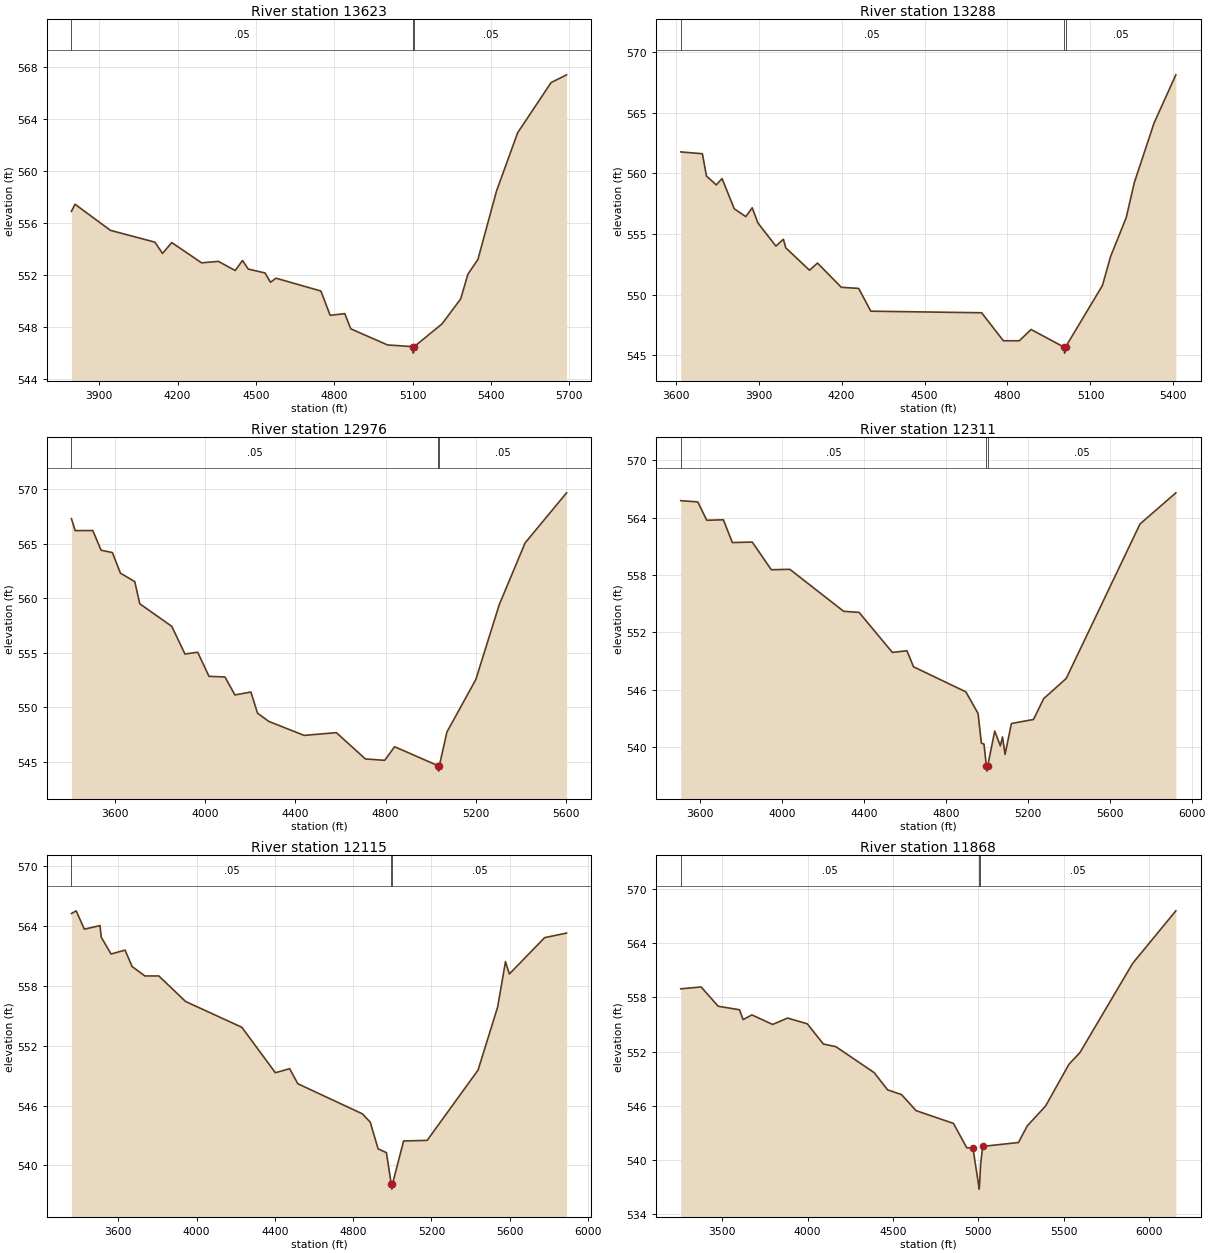
Type RM Length L Ch R = 1 ,13623   ,335,335,335
BEGIN DESCRIPTION:
UNT0013 IN CHRS 23.1
END DESCRIPTION:
XS GIS Cut Line= 3
      3397911.19     10601939.62      3398770.55     10601283.39
      3399004.92     10600502.15
#Sta/Elev= 30
  3793.2  556.87  3806.9  557.42  3942.7  555.41  4113.2   554.5  4142.2  553.63
  4177.6  554.47  4291.9  552.91  4356.3  553.02  4420.7  552.32  4448.6  553.09
  4470.6  552.43    4535  552.13  4555.8  551.41  4576.6  551.73    4749  550.74
  4784.4  548.87  4840.6     549  4863.3  547.83  5004.2  546.59  5100.4  546.46
  5103.2  545.96  5106.4  546.46    5213  548.21  5284.4  550.13  5312.2  552.04
  5350.5  553.17  5421.8  558.44  5502.7  562.92  5630.7  566.78  5690.1  567.38
#Mann= 3 ,-1 , 0
  3793.2     .05       0  5100.4     .03       0  5106.4     .05       0
Bank Sta=5100.4,5106.4
XS Rating Curve= 0 ,0
Exp/Cntr=0.3,0.1

Type RM Length L Ch R = 1 ,13288   ,312,312,312
BEGIN DESCRIPTION:
UNT0013 IN CHRS 23.0
END DESCRIPTION:
XS GIS Cut Line= 3
      3398292.11     10602341.64      3399092.11     10601241.64
      3399342.13     10600891.61
#Sta/Elev= 30
  3618.5  561.78  3696.9  561.63  3711.6  559.79  3747.2  559.06    3768  559.58
  3812.1  557.09  3853.8  556.44    3877  557.17  3897.9  555.91  3962.8  554.01
  3989.8  554.58  3998.3  553.87  4084.1  552.02  4113.1  552.61  4199.3  550.61
  4261.9  550.52  4305.9  548.64  4706.6  548.51  4785.1   546.2  4842.6   546.2
  4885.5  547.13  5003.9  545.68  5006.7  545.18  5009.9  545.68  5143.3  550.76
  5172.8  553.15  5229.3  556.36  5258.8  559.26  5330.1  564.17  5408.8  568.14
#Mann= 3 ,-1 , 0
  3618.5     .05       0  5003.9     .03       0  5009.9     .05       0
Bank Sta=5003.9,5009.9
XS Rating Curve= 0 ,0
Exp/Cntr=0.3,0.1

Type RM Length L Ch R = 1 ,12976   ,665,665,665
BEGIN DESCRIPTION:
UNT0013 IN CHRS 22.0
END DESCRIPTION:
XS GIS Cut Line= 4
      3398345.54     10602577.95      3399206.64     10601407.83
      3399449.69     10601321.03      3399494.83     10600838.43
#Sta/Elev= 30
  3406.8   567.3  3423.6   566.2  3501.5  566.21  3538.5   564.4  3588.5  564.19
  3624.1   562.3  3687.8  561.52  3709.8  559.49  3851.7  557.42  3910.3  554.88
  3966.7  555.04  4016.8  552.83  4087.8  552.77  4131.7  551.12  4202.7  551.39
    4232  549.45  4282.2  548.69  4438.8  547.41  4581.7  547.66  4710.3  545.25
    4796  545.12  4839.9  546.37  5032.3  544.63  5035.1  544.13  5038.3  544.63
  5071.9  547.72  5199.9  552.53  5303.8   559.4  5418.4  565.07  5602.4  569.67
#Mann= 3 ,-1 , 0
  3406.8     .05       0  5032.3     .03       0  5038.3     .05       0
Bank Sta=5032.3,5038.3
XS Rating Curve= 0 ,0
Exp/Cntr=0.3,0.1

Type RM Length L Ch R = 1 ,12311   ,196,196,196
BEGIN DESCRIPTION:
UNT0013 IN CHRS 21.0
END DESCRIPTION:
XS GIS Cut Line= 4
      3398855.92     10603088.43      3399484.41      10601949.5
      3399654.55     10601640.47      3399630.25     10600876.66
#Sta/Elev= 30
  3505.1  565.77  3588.7  565.64  3632.3  563.72  3713.6  563.77  3757.2  561.39
  3854.6  561.44  3947.4  558.55  4038.2  558.59  4300.9   554.2    4376  554.09
  4538.8   549.9  4609.8  550.08  4641.9   548.4  4897.5  545.78  4957.1  543.52
  4973.2  540.42  4986.1  540.32  4997.7  537.99  5000.4  537.49  5003.7  537.99
  5038.5  541.68    5066  540.13  5076.4  541.06  5088.9  539.24    5120  542.47
  5227.6  542.89  5277.6  545.07  5387.6  547.18  5747.8  563.33  5922.9  566.59
#Mann= 3 ,-1 , 0
  3505.1     .05       0  4997.7     .03       0  5003.7     .05       0
Bank Sta=4997.7,5003.7
XS Rating Curve= 0 ,0
Exp/Cntr=0.3,0.1

Type RM Length L Ch R = 1 ,12115   ,247,247,247
BEGIN DESCRIPTION:
UNT0013 IN CHRS 20.0
END DESCRIPTION:
XS GIS Cut Line= 4
      3398890.68     10603123.09      3399758.72     10601893.94
      3399779.55     10601640.47      3399751.78     10600869.66
#Sta/Elev= 30
    3360  565.26  3384.3  565.53  3426.1  563.69  3506.2  564.05  3512.3  562.89
  3562.8   561.2  3634.2  561.59  3669.9  559.95  3735.2     559  3806.6     559
  3943.2  556.44    4231  553.85  4402.4  549.29  4475.1   549.7    4517  548.19
  4846.9  545.17  4887.1  544.34  4927.3  541.66  4969.8  541.28  4994.5  538.12
  4997.3  537.62  5000.5  538.12  5057.7  542.45    5178  542.51  5438.1  549.56
  5538.2  555.88  5578.2  560.43  5598.2   559.2  5778.3  562.84  5890.4   563.3
#Mann= 3 ,-1 , 0
    3360     .05       0  4994.5     .03       0  5000.5     .05       0
Bank Sta=4994.5,5000.5
XS Rating Curve= 0 ,0
Exp/Cntr=0.3,0.1

Type RM Length L Ch R = 1 ,11868   ,277,277,277
BEGIN DESCRIPTION:
UNT0013 IN CHRS 19.0
END DESCRIPTION:
XS GIS Cut Line= 3
      3399062.54     10603276.75       3399930.6     10601900.89
      3400642.39     10600841.88
#Sta/Elev= 30
  3255.7  558.96  3375.4  559.17  3475.4  557.03  3600.2  556.64  3621.4  555.55
  3673.1  556.07  3794.4  555.01  3882.6  555.72  3997.9  555.08  4092.1  552.84
    4165  552.55  4389.8  549.67  4468.7  547.76  4550.6  547.23  4635.8  545.45
  4854.6  544.04  4932.9  541.33  4968.9  541.32  5001.9  537.25  5004.7  536.75
  5007.9  537.25  5013.9  539.52  5026.2  541.49  5235.9  541.92  5286.9  543.75
  5394.9  545.97  5532.2  550.61  5595.9  551.88  5905.8   561.8  6158.5  567.61
#Mann= 3 ,-1 , 0
  3255.7     .05       0  5001.9     .03       0  5007.9     .05       0
Bank Sta=4968.9,5026.2
XS Rating Curve= 0 ,0
Exp/Cntr=0.3,0.1

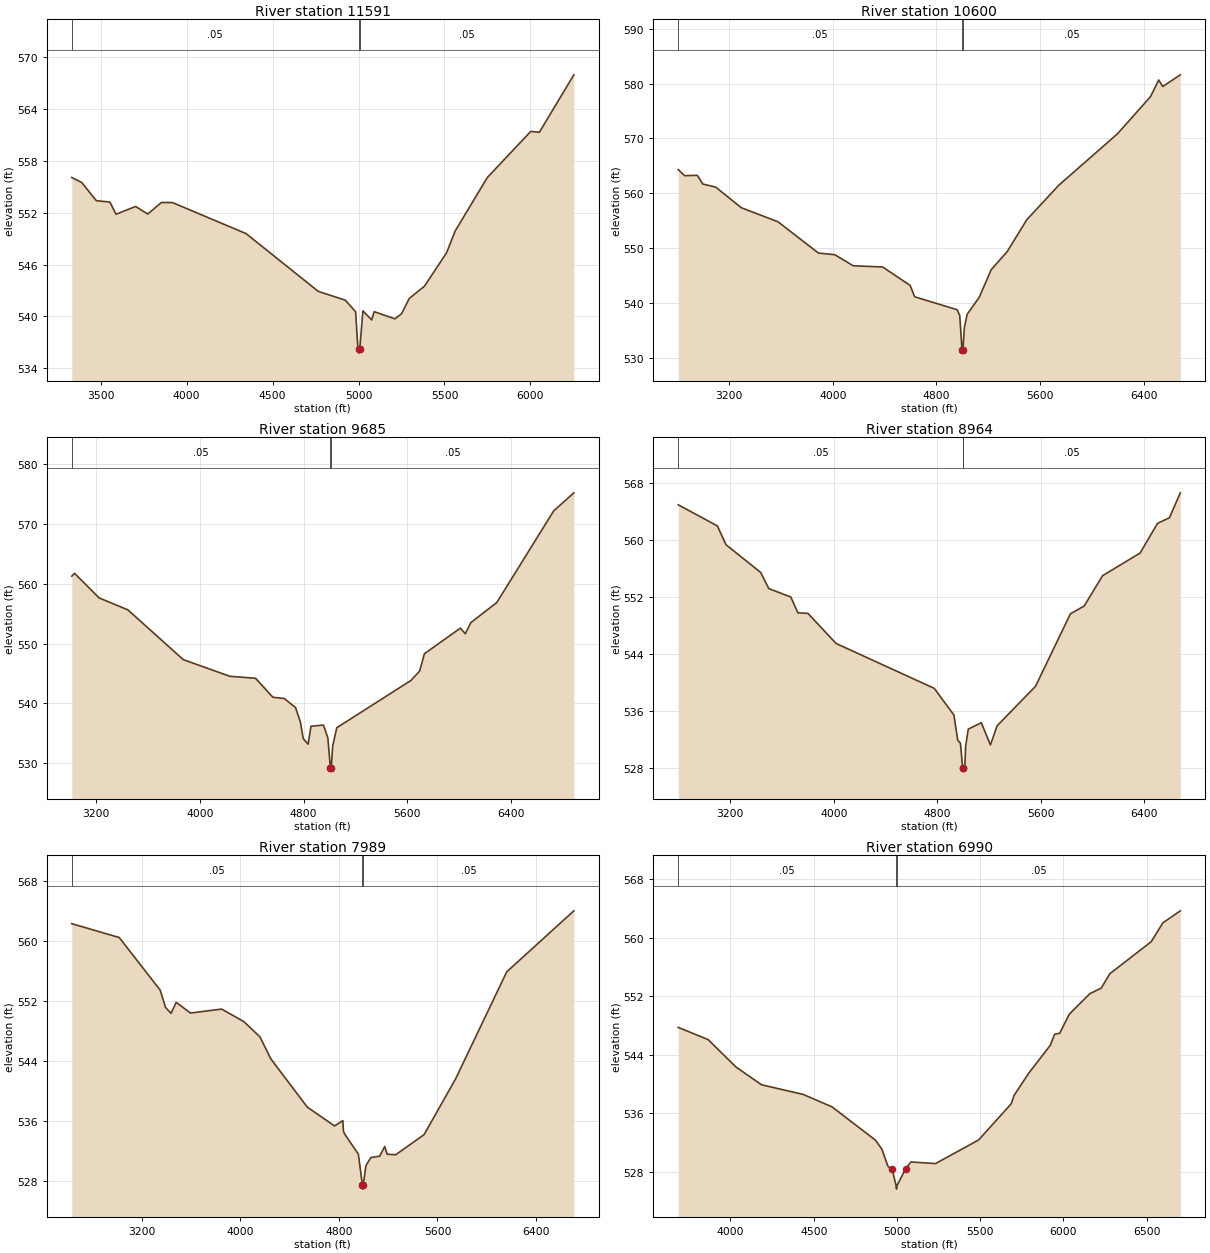
Type RM Length L Ch R = 1 ,11591   ,991,991,991
BEGIN DESCRIPTION:
UNT0013 IN CHRS 18.0
END DESCRIPTION:
XS GIS Cut Line= 4
      3399201.41     10603311.51      3400112.89     10602113.56
      3400316.88      10601805.4      3400789.98     10600872.22
#Sta/Elev= 30
  3331.7  556.07  3389.4   555.5  3474.6  553.39  3553.6  553.23    3589  551.82
  3703.3  552.72    3774  551.84    3853  553.18  3917.5  553.17  4345.8  549.58
  4765.8  542.89  4923.2  541.87  4983.2  540.53  4995.4  536.63  5001.4  536.24
  5004.2  535.74  5007.4  536.24  5025.5  540.63  5076.6  539.58  5091.1  540.54
  5211.7  539.71  5250.6   540.3  5295.2  542.07  5384.2   543.5  5512.3  547.36
  5562.4  549.88  5748.9  556.06  6002.2  561.41  6052.3  561.31  6252.8  567.96
#Mann= 3 ,-1 , 0
  3331.7     .05       0  5001.4     .03       0  5007.4     .05       0
Bank Sta=5001.4,5007.4
XS Rating Curve= 0 ,0
Exp/Cntr=0.3,0.1

Type RM Length L Ch R = 1 ,10600   ,915,915,915
BEGIN DESCRIPTION:
UNT0013 IN CHRS 17.0
END DESCRIPTION:
XS GIS Cut Line= 4
      3399360.55     10603948.42      3400728.63     10602399.79
      3401117.52     10602115.07      3401804.88      10600976.4
#Sta/Elev= 30
  2805.1  564.32  2853.9   563.2  2952.6  563.27  2995.3  561.68  3094.4  561.12
  3293.1  557.35  3575.8   554.8  3887.8   549.1    4015  548.79  4157.2  546.77
  4383.9  546.56  4596.4   543.2  4631.5  541.12  4958.9  538.77  4979.7  537.72
  4997.6  531.35  5000.4  530.85  5003.6  531.35  5015.3   535.5  5036.9  537.93
  5130.3  541.03  5222.8  546.07  5345.7  549.34  5497.6  555.17  5744.2  561.45
  6198.3  570.84  6452.6  577.59  6516.7  580.64  6547.7  579.46  6683.5  581.59
#Mann= 3 ,-1 , 0
  2805.1     .05       0  4997.6     .03       0  5003.6     .05       0
Bank Sta=4997.6,5003.6
XS Rating Curve= 0 ,0
Exp/Cntr=0.3,0.1

Type RM Length L Ch R = 1 ,9685    ,721,721,721
BEGIN DESCRIPTION:
UNT0013 IN CHRS 15.0
END DESCRIPTION:
XS GIS Cut Line= 2
      3399707.81     10603906.73      3403088.45     10602018.56
#Sta/Elev= 30
  3012.2  561.28  3033.6  561.76  3223.3  557.64  3444.8  555.65  3872.1  547.32
  4231.2  544.53  4429.6   544.2  4563.4  541.02  4651.2  540.81    4738   539.3
  4775.7  536.86  4797.4   534.1  4835.1  533.17  4856.8  536.17  4952.9  536.37
  4987.2  534.23  5007.1  529.16  5009.9  528.66  5013.1  529.16  5024.7  532.88
  5055.9  535.92  5628.6  543.84  5695.3  545.41  5731.7   548.3  6009.4  552.59
  6047.1  551.65  6090.5  553.52  6290.4  556.88  6729.1  572.21  6884.4  575.23
#Mann= 3 ,-1 , 0
  3012.2     .05       0  5007.1     .03       0  5013.1     .05       0
Bank Sta=5007.1,5013.1
XS Rating Curve= 0 ,0
Exp/Cntr=0.3,0.1

Type RM Length L Ch R = 1 ,8964    ,975,975,975
BEGIN DESCRIPTION:
UNT0013 IN CHRS 13.0
END DESCRIPTION:
XS GIS Cut Line= 4
      3399492.55     10604045.61      3401180.02     10603649.79
      3402068.91     10603531.73      3402998.26     10602699.47
#Sta/Elev= 30
  2799.3     565  3101.6  562.03  3168.6  559.38  3435.7   555.5  3498.9  553.22
  3668.7  552.04  3723.3  549.82  3801.1  549.74  4018.4  545.51  4776.8   539.2
  4928.1  535.46  4958.4  531.88  4978.5  531.51  4995.7  528.07  4998.5  527.57
  5001.7  528.07    5013  528.41  5018.9  531.06  5039.1  533.47  5139.9  534.38
  5210.6  531.25    5261  533.92  5558.9   539.5  5828.1  549.68  5934.2  550.77
  6076.3  555.03  6366.4  558.22    6501  562.39  6592.9  563.18  6676.8  566.68
#Mann= 3 ,-1 , 0
  2799.3     .05       0  4995.7     .03       0  5001.7     .05       0
Bank Sta=4995.7,5001.7
XS Rating Curve= 0 ,0
Exp/Cntr=0.3,0.1

Type RM Length L Ch R = 1 ,7989    ,999,999,999
BEGIN DESCRIPTION:
UNT0013 IN CHRS 11.0
END DESCRIPTION:
XS GIS Cut Line= 4
      3399693.87      10605226.2      3401430.02     10604101.18
      3402200.85     10603955.34      3402929.82     10602976.44
#Sta/Elev= 30
  2632.8  562.32  3018.1  560.47  3350.4  553.46  3393.3  551.17  3438.1  550.37
  3480.3  551.84  3595.9  550.41  3848.9  550.94  4030.2  549.26  4160.1  547.23
  4247.8  544.31  4543.8  537.88  4764.8  535.37  4832.2  536.08  4837.3  534.67
  4846.2  534.31  4958.1  531.61  4991.4  527.45  4994.1  526.95  4997.4  527.45
  5019.2  530.07  5059.9  531.16  5131.2  531.34  5171.9  532.63  5192.2   531.6
  5261.2  531.53  5491.3  534.21    5747  541.63    6162   555.9  6706.6  564.03
#Mann= 3 ,-1 , 0
  2632.8     .05       0  4991.4     .03       0  4997.4     .05       0
Bank Sta=4991.4,4997.4
XS Rating Curve= 0 ,0
Exp/Cntr=0.3,0.1

Type RM Length L Ch R = 1 ,6990    ,824,824,824
BEGIN DESCRIPTION:
UNT0013 IN CHRS 9.0
END DESCRIPTION:
XS GIS Cut Line= 4
      3401464.72     10605469.24      3402353.63      10604948.4
      3402999.46     10603087.29      3403013.38     10603080.33
#Sta/Elev= 30
  3686.1  547.75    3866  546.07    4032  542.34  4186.5  539.89  4436.4  538.57
  4610.3  536.86  4871.7  532.29  4909.4  531.06  4945.8  528.72  4971.6   528.3
  4994.5   526.1  4997.2   525.6  5000.5   526.1  5051.6  528.36  5083.4  529.32
  5231.6   529.1  5490.2  532.33  5686.7   537.3  5702.8  538.41  5790.9  541.46
  5920.7  545.29  5946.6  546.81  5977.7  546.95  6034.7  549.55  6159.2  552.38
  6226.7  553.12  6278.4  555.09  6527.4  559.49  6597.1  562.06  6701.9  563.71
#Mann= 3 ,-1 , 0
  3686.1     .05       0  4994.5     .03       0  5000.5     .05       0
Bank Sta=4971.6,5051.6
XS Rating Curve= 0 ,0
Exp/Cntr=0.3,0.1

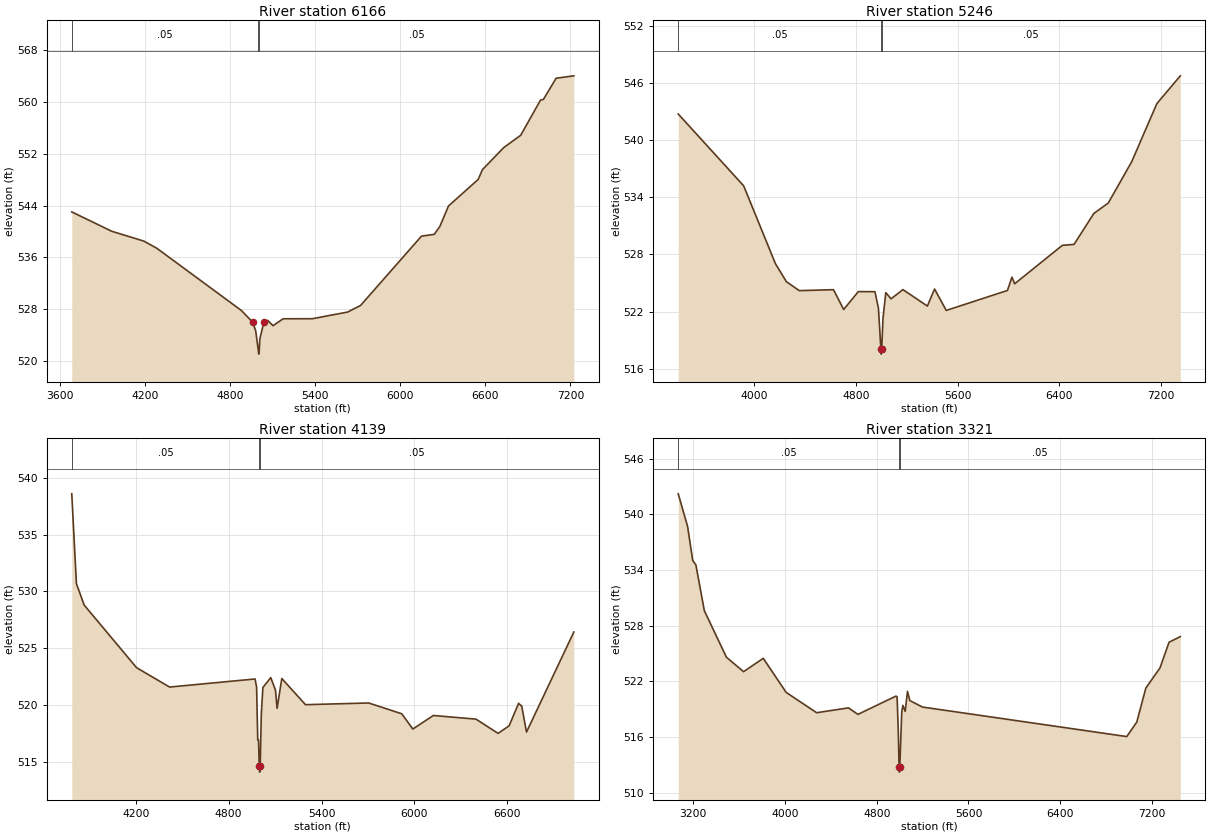
Type RM Length L Ch R = 1 ,6166    ,920,920,920
BEGIN DESCRIPTION:
UNT0013 IN CHRS 6.0
END DESCRIPTION:
XS GIS Cut Line= 4
      3402277.22     10605934.52      3402888.35     10605392.84
      3403603.63      10604448.4      3403603.63     10602906.77
#Sta/Elev= 30
  3680.7  543.04  3962.6  540.05  4189.2  538.53  4281.2  537.42  4878.8  527.79
  4957.9  525.98  4978.7  524.66  4997.6  521.57  5000.4  521.07  5003.6  521.57
  5007.8  523.41  5036.9  526.06    5064  526.27    5101  525.46  5172.2  526.53
  5378.2  526.54  5627.8  527.57  5718.8  528.59  6148.8   539.3  6238.8  539.57
  6278.8  540.82  6338.8  543.94  6548.8  548.06  6578.8  549.57  6728.8  552.97
  6848.8  554.88  6988.8  560.32  7008.8  560.41  7098.8  563.69  7223.7  564.06
#Mann= 3 ,-1 , 0
  3680.7     .05       0  4997.6     .03       0  5003.6     .05       0
Bank Sta=4957.9,5036.9
XS Rating Curve= 0 ,0
Exp/Cntr=0.3,0.1

Type RM Length L Ch R = 1 ,5246    ,1107,1107,1107
BEGIN DESCRIPTION:
UNT0013 IN CHRS 4.0
END DESCRIPTION:
XS GIS Cut Line= 4
      3402492.54     10606087.28      3403832.79     10605580.34
      3404180.02     10605309.51       3405603.6     10603802.59
#Sta/Elev= 30
  3403.5  542.76  3917.8  535.21    4168  527.02  4253.2  525.15  4354.6   524.2
    4624   524.3  4703.8  522.22  4819.1   524.1  4949.7  524.09    4977  522.37
  4996.6  518.03  4999.3  517.53  5002.6  518.03  5013.1  521.31  5034.8  523.99
  5076.5  523.34  5169.6  524.31  5361.6  522.58  5418.2  524.37  5510.1  522.12
  5991.1  524.22  6026.7  525.62  6047.7  524.92  6422.7  528.96  6514.6  529.06
  6670.3  532.31  6783.6  533.41  6967.3  537.73  7165.5  543.85  7349.8  546.77
#Mann= 3 ,-1 , 0
  3403.5     .05       0  4996.6     .03       0  5002.6     .05       0
Bank Sta=4996.6,5002.6
XS Rating Curve= 0 ,0
Exp/Cntr=0.3,0.1

Type RM Length L Ch R = 1 ,4139    ,818,818,818
BEGIN DESCRIPTION:
UNT0013 IN CHRS 3.0
END DESCRIPTION:
XS GIS Cut Line= 3
      3402942.15     10606291.64      3404142.11     10606191.64
      3406142.08     10605791.65
#Sta/Elev= 30
  3786.5  538.58  3816.6  530.68  3866.7   528.8  4205.4  523.29  4418.6  521.59
  4970.5   522.3  4980.6   521.6  4988.1  516.94  4993.2  516.94  4997.8  514.61
  5000.6  514.11  5003.8  514.61    5011  519.19  5021.2  521.55  5072.2  522.42
  5102.8  521.31    5113  519.72  5143.6  522.34  5296.6  520.04  5704.5  520.19
  5918.6  519.24    5990   517.9  6122.6  519.09  6397.9  518.77  6540.7  517.52
  6612.1  518.18  6673.3  520.16  6693.7   519.9  6724.3  517.63  7030.2  526.43
#Mann= 3 ,-1 , 0
  3786.5     .05       0  4997.8     .03       0  5003.8     .05       0
Bank Sta=4997.8,5003.8
XS Rating Curve= 0 ,0
Exp/Cntr=0.3,0.1

Type RM Length L Ch R = 1 ,3321    ,0,0,0
BEGIN DESCRIPTION:
UNT0013 IN CHRS 1.0
END DESCRIPTION:
XS GIS Cut Line= 4
      3402339.73     10606436.24      3403485.57     10607026.53
      3404778.98     10606896.32      3406280.74     10605924.08
#Sta/Elev= 30
  3069.2  542.21  3150.6  538.71  3195.5  535.03  3223.3  534.55  3296.9  529.62
  3489.3  524.61  3638.9  523.05  3810.6  524.49  4010.1  520.82  4276.1  518.63
  4553.7  519.15  4636.1  518.45  4967.8  520.42  4977.8  520.33  4987.9  516.65
  4994.9  512.73  4997.7  512.23  5000.9  512.73    5018  518.71  5028.1  519.42
  5048.2  518.77  5068.3  520.93  5088.4  519.94  5198.9  519.24  6980.3  516.06
  7067.5  517.62  7146.5  521.28    7270  523.46  7348.9  526.22  7447.1  526.83
#Mann= 3 ,-1 , 0
  3069.2     .05       0  4994.9     .03       0  5000.9     .05       0
Bank Sta=4994.9,5000.9
XS Rating Curve= 0 ,0
Exp/Cntr=0.3,0.1

Chan Stop Cuts=-1
Use User Specified Reach Order=0
Composite Channel Slope=5