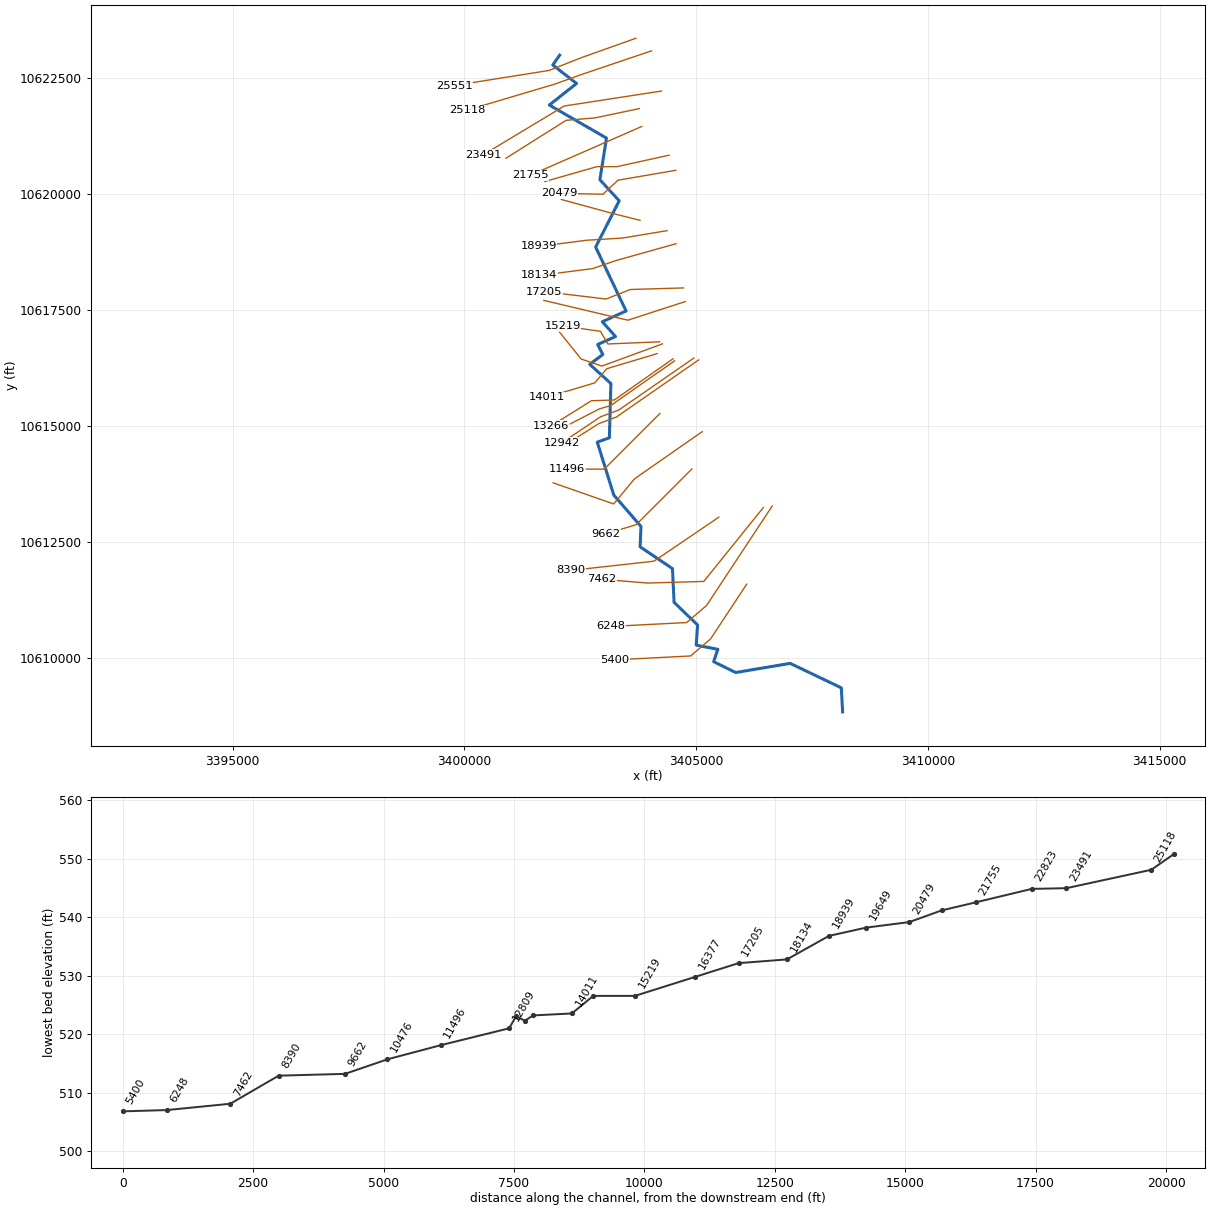
--- UNT0014 IN CHRS.prj (project) ---

Proj Title=UNT0014 IN CHRS Base Level Engineering
Current Plan=p01
Default Exp/Contr=0.3,0.1
English Units
Geom File=g01
Flow File=f01
Plan File=p01
Y Axis Title=Elevation
X Axis Title(PF)=Main Channel Distance
X Axis Title(XS)=Station
BEGIN DESCRIPTION:
UNT0014 IN CHRS
END DESCRIPTION:
DSS Export Rating Curves= 0
DSS Export Rating Curve Sorted= 0
DSS Export Volume Flow Curves= 0
DXF OffsetX= 0
DXF OffsetY= 0
DXF ScaleX= 1
DXF ScaleY= 10

--- UNT0014 IN CHRS.p01 (plan) ---

Plan Title=Multiple Run
Short Identifier=Multiple
Geom File=g01
Flow File=f01
Subcritical Flow
K Sum by GR= 0
Std Step Tol= 0.01
Critical Tol= 0.01
Num of Std Step Trials= 20
Max Error Tol= 0.3
Flow Tol Ratio= 0.001
Split Flow NTrial= 30
Split Flow Tol= 0.02
Split Flow Ratio= 0.02
Log Output Level= 0
Friction Slope Method= 1
Unsteady Friction Slope Method= 2
Unsteady Bridges Friction Slope Method= 1
Parabolic Critical Depth
Global Vel Dist=  1 , 1 , 1
Global Log Level= 0
CheckData=True
Encroach Param= -1, 0, 0, 0
BEGIN DESCRIPTION:
Multiple Run
END DESCRIPTION:

--- UNT0014 IN CHRS.f01 (steady flow) ---

Flow Title=Multiple
Number of Profiles=7
Profile Names=10-year,25-year,50-year,1pct_min,100-year,1pct_plu,500-year
River Rch & RM= UNT0014 IN CHRS,Reach-1,25551
     352     438     501     417     564     762     712
River Rch & RM= UNT0014 IN CHRS,Reach-1,23491
     543     692     802     675     914    1235    1184
River Rch & RM= UNT0014 IN CHRS,Reach-1,21097
     720     925    1079     913    1235    1670    1617
River Rch & RM= UNT0014 IN CHRS,Reach-1,12942
     837    1078    1260    1067    1444    1952    1894
Boundary for River Rch & Prof#=UNT0014 IN CHRS,Reach-1,1
Up Type=0
Dn Type=3
Dn Slope=0.005
Boundary for River Rch & Prof#=UNT0014 IN CHRS,Reach-1,2
Up Type=0
Dn Type=3
Dn Slope=0.005
Boundary for River Rch & Prof#=UNT0014 IN CHRS,Reach-1,3
Up Type=0
Dn Type=3
Dn Slope=0.005
Boundary for River Rch & Prof#=UNT0014 IN CHRS,Reach-1,4
Up Type=0
Dn Type=3
Dn Slope=0.005
Boundary for River Rch & Prof#=UNT0014 IN CHRS,Reach-1,5
Up Type=0
Dn Type=3
Dn Slope=0.005
Boundary for River Rch & Prof#=UNT0014 IN CHRS,Reach-1,6
Up Type=0
Dn Type=3
Dn Slope=0.005
Boundary for River Rch & Prof#=UNT0014 IN CHRS,Reach-1,7
Up Type=0
Dn Type=3
Dn Slope=0.005

--- UNT0014 IN CHRS.g01 (geometry) ---

Geom Title=Existing Conditions
Program Version=4.10

River Reach=UNT0014 IN CHRS ,Reach-1
Reach XY= 30
      3402056.14     10623003.24      3401908.35     10622790.35
      3402421.69     10622392.64      3401833.34     10621927.61
       3403067.2     10621214.67      3402924.45     10620316.79
      3403341.15     10619862.72      3402833.17     10618864.95
      3403489.71     10617487.08      3402977.19     10617254.09
      3403262.07     10616936.21      3402877.03       10616764.
      3402988.27     10616548.83       3402705.8      10616336.7
      3403161.68     10615921.74      3403129.38     10614752.27
      3402868.09     10614658.06      3403224.05     10613517.89
      3403811.02     10612840.68      3403792.38     10612401.84
      3404490.44     10611930.77      3404525.12     10611202.94
      3405031.78     10610716.52      3405002.92     10610282.47
      3405469.75     10610190.17      3405378.14     10609924.66
      3405854.88     10609690.61      3407030.17     10609887.78
      3408133.15     10609361.07      3408162.11     10608841.64

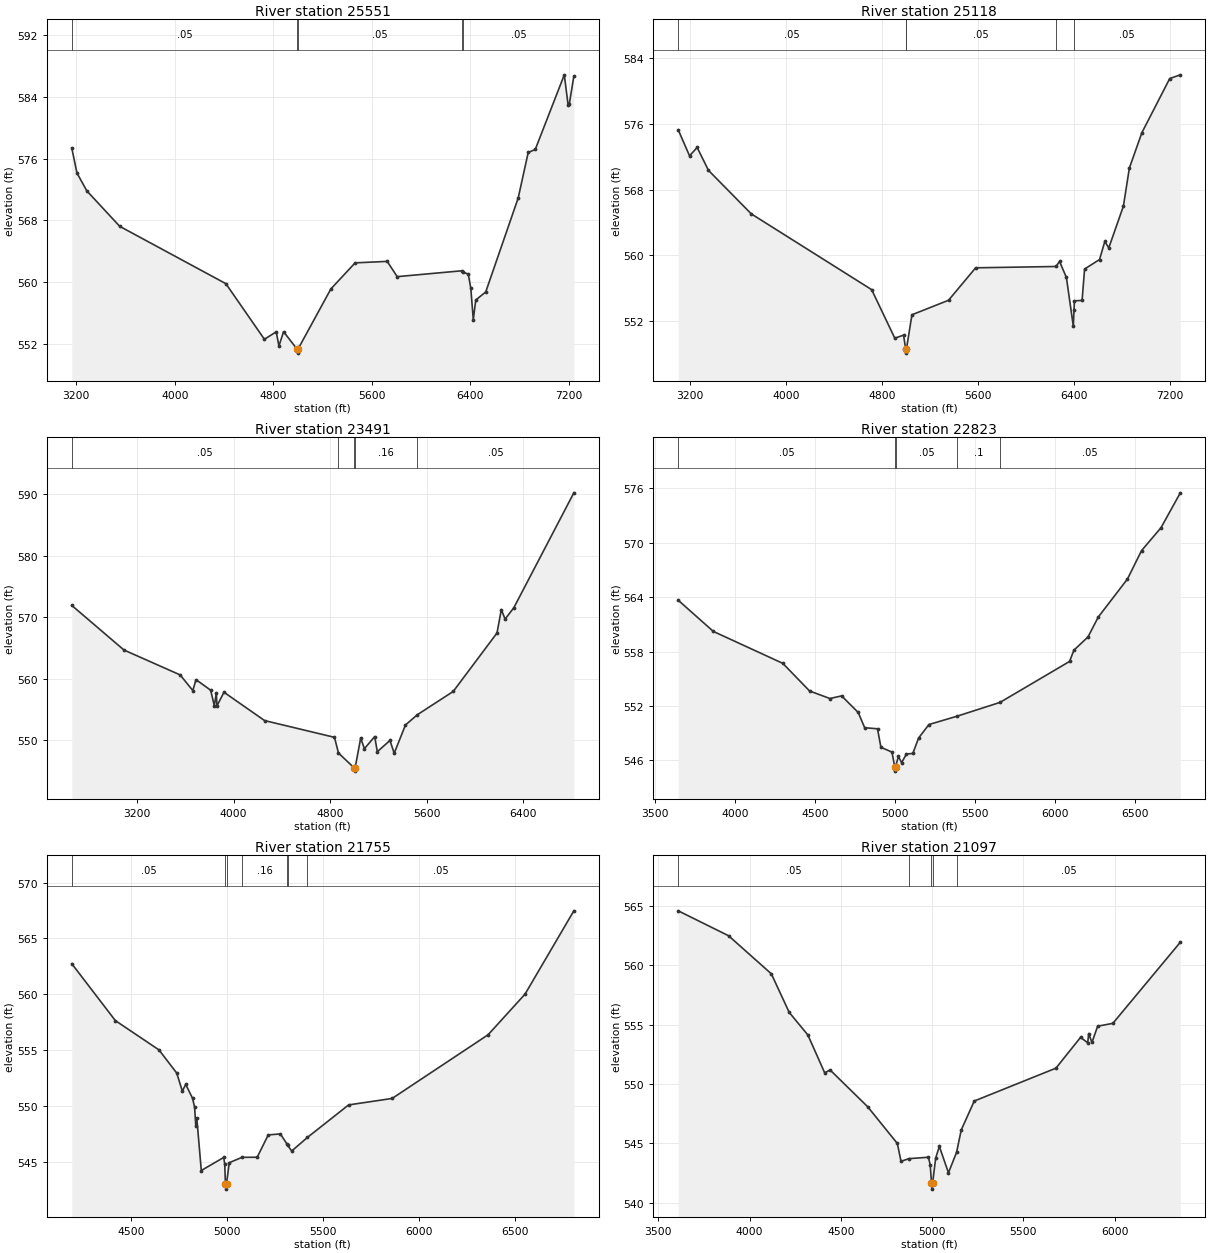
Type RM Length L Ch R = 1 ,25551   ,433,433,433
BEGIN DESCRIPTION:
UNT0014 IN CHRS 39.1
END DESCRIPTION:
XS GIS Cut Line= 4
      3403701.98     10623367.59      3402540.95     10622955.26
       3401824.8     10622673.14      3399775.55     10622347.87
#Sta/Elev= 30
    3163  577.39  3205.3  574.14  3285.1  571.83  3552.2  567.23  4414.3  559.79
    4727  552.58  4823.1  553.54  4845.2   551.7  4882.6  553.56  4993.3  551.28
  4996.1  550.78  4999.3  551.28  5266.9  559.11  5463.8  562.49  5724.4  562.68
  5805.4   560.7  6329.1  561.46  6341.2  561.28  6382.5  561.03  6402.8  559.22
  6423.2  555.13  6443.3  557.67  6524.3  558.72  6787.6  570.89  6869.2  576.81
  6926.4   577.2  7162.2  586.88  7192.6  583.03  7202.7  583.08  7239.7   586.7
#Mann= 5 ,-1 , 0
    3163     .05       0  4993.3     .03       0  4999.3     .05       0
  6329.1     .16       0  6341.2     .05       0
Bank Sta=4993.3,4999.3
XS Rating Curve= 0 ,0
Exp/Cntr=0.3,0.1

Type RM Length L Ch R = 1 ,25118   ,1627,1627,1627
BEGIN DESCRIPTION:
UNT0014 IN CHRS 39.2
END DESCRIPTION:
XS GIS Cut Line= 4
      3404038.36     10623096.33      3402497.55     10622575.49
      3401955.01     10622380.18      3400057.78     10621816.43
#Sta/Elev= 30
  3101.5  575.28    3196  572.11  3258.9  573.14  3353.2  570.35  3709.8  565.05
  4712.6  555.82  4905.4  549.91  4978.2  550.28  4996.5  548.59  4999.2  548.09
  5002.5  548.59  5048.3  552.76  5353.3  554.53  5578.8  558.48  6247.6  558.64
  6277.8  559.25  6335.1   557.3  6392.6  551.36  6398.4  553.36  6401.6  554.46
  6465.6  554.51  6486.4  558.33  6611.2  559.49  6654.8  561.69    6688  560.91
  6809.8  565.99  6859.3  570.62  6964.1  574.95  7195.8  581.53  7283.8  581.98
#Mann= 5 ,-1 , 0
  3101.5     .05       0  4996.5    .035       0  5002.5     .05       0
  6247.6     .16       0  6398.4     .05       0
Bank Sta=4996.5,5002.5
XS Rating Curve= 0 ,0
Exp/Cntr=0.3,0.1

Type RM Length L Ch R = 1 ,23491   ,668,668,668
BEGIN DESCRIPTION:
UNT0014 IN CHRS 39.0
END DESCRIPTION:
XS GIS Cut Line= 4
      3404249.46     10622229.17      3402152.25     10621906.26
      3401832.81     10621711.81      3400406.37     10620854.56
#Sta/Elev= 30
  2658.8  571.92  3091.2  564.66  3556.6  560.61    3662  558.06  3688.1  559.84
  3809.6  558.12  3839.9  555.59  3856.7   557.7  3861.7  555.56  3919.9  557.79
  4256.2  553.18  4835.6  550.45  4868.5   547.9  5000.3  545.45  5003.1  544.95
  5006.3  545.45  5052.6  550.32  5083.6  548.61  5168.9  550.57  5190.5  548.11
  5295.2  549.94  5330.5  547.86  5423.8  552.46  5523.1  554.14  5819.7  557.92
  6182.2  567.43    6218  571.24  6249.1  569.69  6322.2  571.56  6818.9  590.24
#Mann= 5 ,-1 , 0
  2658.8     .05       0  4868.5     .16       0  5000.3     .07       0
  5006.3     .16       0  5523.1     .05       0
Bank Sta=5000.3,5006.3
XS Rating Curve= 0 ,0
Exp/Cntr=0.3,0.1

Type RM Length L Ch R = 1 ,22823   ,1068,1068,1068
BEGIN DESCRIPTION:
UNT0014 IN CHRS 37.0
END DESCRIPTION:
XS GIS Cut Line= 4
      3403775.21     10621850.99       3402819.5     10621650.47
       3402197.1     10621598.39      3400897.65      10620780.7
#Sta/Elev= 30
  3644.7  563.67  3864.1  560.23  4297.8  556.71  4465.3  553.66  4592.1  552.83
  4665.4  553.12  4769.1  551.29  4809.3  549.61  4889.5  549.49  4910.8  547.45
  4979.9  546.92  4996.9  545.32  4999.7  544.82  5002.9  545.32    5020  546.45
  5040.1  545.75  5070.2  546.71  5110.3  546.77  5146.1  548.47  5210.7  549.96
  5388.5  550.89  5654.6   552.4  6089.3  556.92  6116.4  558.16  6204.7  559.63
  6268.3  561.81  6450.8  566.01  6539.1  569.15  6660.4  571.67  6781.1  575.52
#Mann= 5 ,-1 , 0
  3644.7     .05       0  4996.9    .035       0  5002.9     .05       0
  5388.5      .1       0  5654.6     .05       0
Bank Sta=4996.9,5002.9
XS Rating Curve= 0 ,0
Exp/Cntr=0.3,0.1

Type RM Length L Ch R = 1 ,21755   ,658,658,658
BEGIN DESCRIPTION:
UNT0014 IN CHRS 35.0
END DESCRIPTION:
XS GIS Cut Line= 3
      3403829.08     10621466.12      3403029.08     10621116.12
      3401429.67     10620416.38
#Sta/Elev= 30
  4188.9  562.74  4416.2  557.64    4644  555.01  4736.6  552.93  4765.5  551.32
  4783.4  551.92  4818.7  550.68  4829.6  549.88  4835.7  548.21  4841.1   548.9
  4864.5   544.2  4981.5  545.37  4986.9  544.77  4990.3  543.03  4993.1  542.53
  4996.3  543.03  5010.3   544.9  5077.1  545.38  5156.1  545.39  5213.8  547.39
  5277.1  547.48  5312.3  546.55  5314.9  546.45  5336.2  545.95  5418.5  547.17
  5633.2  550.08  5860.1  550.66  6360.7  556.37  6553.2  560.01  6807.9  567.48
#Mann= 7 ,-1 , 0
  4188.9     .05       0  4990.3    .035       0  4996.3     .05       0
  5077.1     .16       0  5312.3     .05       0  5314.9      .1       0
  5418.5     .05       0
Bank Sta=4990.3,4996.3
XS Rating Curve= 0 ,0
Exp/Cntr=0.3,0.1

Type RM Length L Ch R = 1 ,21097   ,618,618,618
BEGIN DESCRIPTION:
UNT0014 IN CHRS 34.0
END DESCRIPTION:
XS GIS Cut Line= 4
      3404415.88     10620845.79      3403288.25     10620598.39
      3402858.56     10620598.39       3401736.6      10620278.2
#Sta/Elev= 30
  3608.8  564.61  3884.4  562.51  4118.8   559.3  4216.7  556.05  4319.1  554.14
  4411.2  550.95  4440.8  551.19  4646.7  548.09  4809.4  544.99  4829.4  543.48
    4872  543.71  4979.4  543.83  4989.4   543.2  4996.4  541.64  4999.1  541.14
  5002.4  541.64  5019.4  543.76  5039.4  544.74  5089.4  542.52  5133.8  544.24
  5159.4  546.13  5230.7  548.57  5678.1  551.34  5813.2  553.94  5852.4  553.48
  5857.6  554.26  5875.6  553.51  5906.8  554.88    5990  555.12  6359.7  561.96
#Mann= 5 ,-1 , 0
  3608.8     .05       0    4872     .16       0  4996.4     .07       0
  5002.4     .16       0  5133.8     .05       0
Bank Sta=4996.4,5002.4
XS Rating Curve= 0 ,0
Exp/Cntr=0.3,0.1

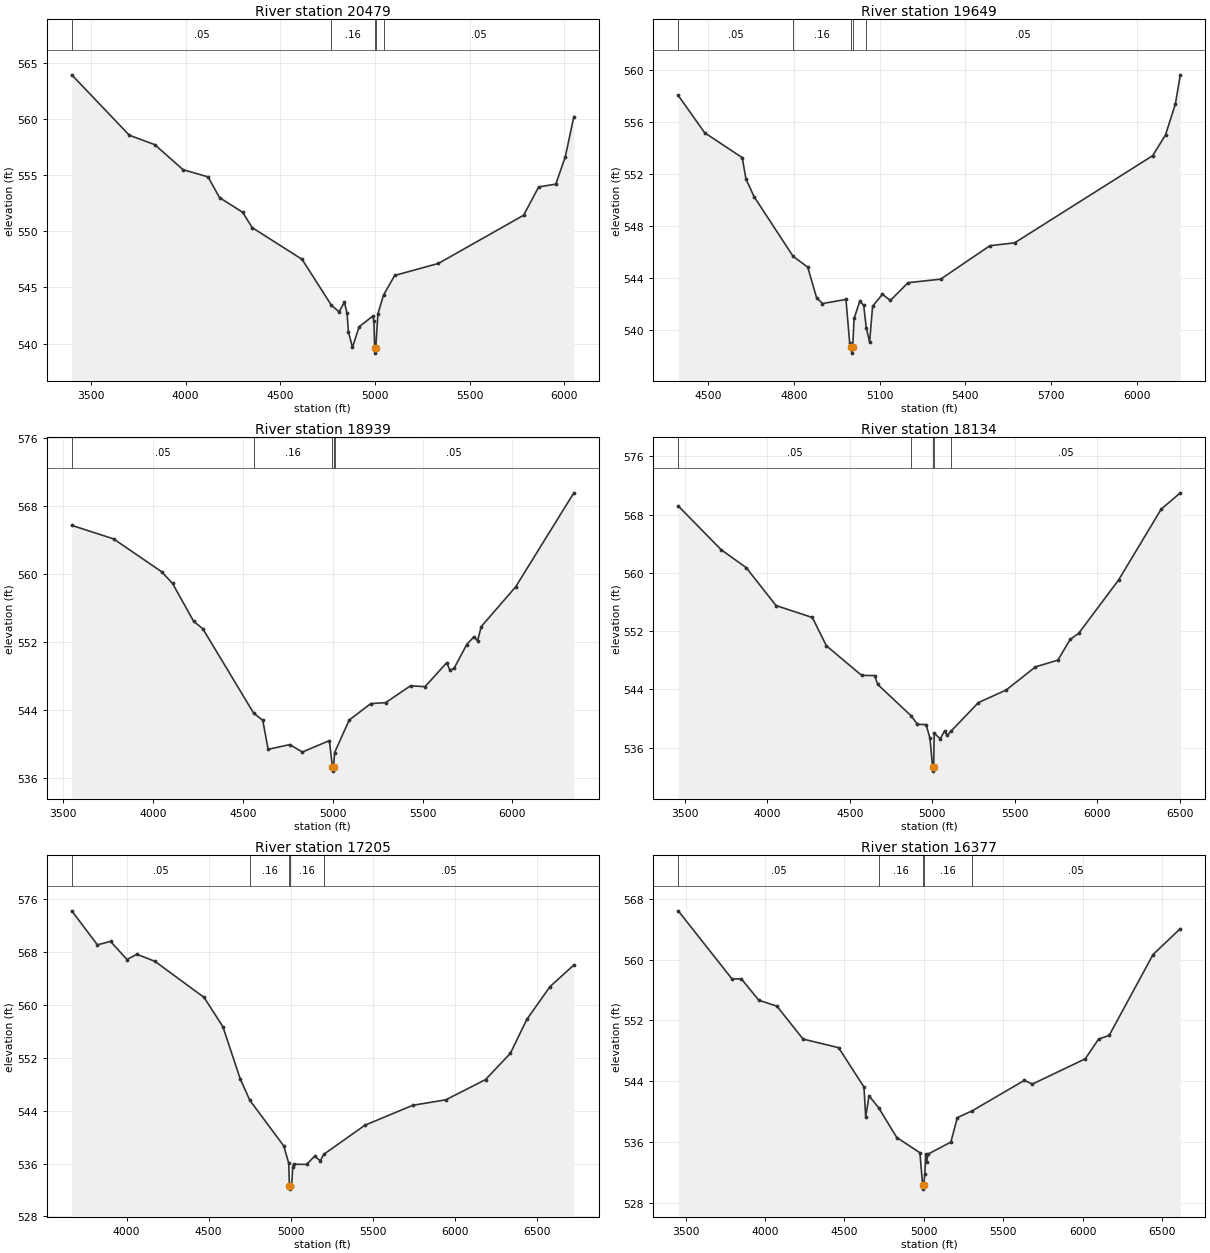
Type RM Length L Ch R = 1 ,20479   ,830,830,830
BEGIN DESCRIPTION:
UNT0014 IN CHRS 32.0
END DESCRIPTION:
XS GIS Cut Line= 4
      3404561.73     10620520.27      3403314.29     10620306.72
      3402991.37     10620004.64      3402046.62     10620022.85
#Sta/Elev= 30
  3398.3  563.94  3702.3  558.56  3836.9  557.72  3986.4  555.49  4118.2  554.85
  4179.1     553  4300.9   551.7  4351.6  550.33  4615.4   547.5  4769.8  543.42
  4810.5  542.83  4838.8  543.69    4853  542.68  4859.9  541.07  4881.3  539.66
  4916.5   541.5  4987.4  542.43  4994.7  542.03  4998.5  539.65  5001.3  539.15
  5004.5  539.65  5015.7  542.64  5045.6  544.33  5104.6  546.07  5335.4  547.14
  5785.5  551.43  5865.5  553.96  5955.5   554.2  6005.5  556.62    6051  560.21
#Mann= 5 ,-1 , 0
  3398.3     .05       0  4769.8     .16       0  4998.5     .07       0
  5004.5     .16       0  5045.6     .05       0
Bank Sta=4998.5,5004.5
XS Rating Curve= 0 ,0
Exp/Cntr=0.3,0.1

Type RM Length L Ch R = 1 ,19649   ,710,710,710
BEGIN DESCRIPTION:
UNT0014 IN CHRS 31.0
END DESCRIPTION:
XS GIS Cut Line= 3
      3403792.11     10619441.64      3403192.11     10619591.64
      3402092.15     10619891.63
#Sta/Elev= 30
  4394.1  558.06  4486.9  555.18  4618.3  553.27  4631.2  551.63  4659.5  550.27
  4796.5  545.66  4847.6  544.83  4878.6  542.48  4899.2  542.02  4981.6  542.34
  4994.5  539.01  4999.3   538.7    5002   538.2  5005.3   538.7    5010  540.87
  5029.8  542.19  5043.7  541.89  5052.6  540.17  5064.4  539.04  5074.8  541.81
  5109.3  542.74    5137  542.26  5199.1  543.63  5313.2   543.9  5485.9  546.48
  5572.3   546.7    6056  553.42  6100.9  555.02  6135.5  557.41  6152.7  559.65
#Mann= 5 ,-1 , 0
  4394.1     .05       0  4796.5     .16       0  4999.3     .07       0
  5005.3     .16       0  5052.6     .05       0
Bank Sta=4999.3,5005.3
XS Rating Curve= 0 ,0
Exp/Cntr=0.3,0.1

Type RM Length L Ch R = 1 ,18939   ,805,805,805
BEGIN DESCRIPTION:
UNT0014 IN CHRS 29.0
END DESCRIPTION:
XS GIS Cut Line= 4
      3404371.53     10619218.17      3403413.25     10619059.32
      3402642.41     10619012.45      3401600.76     10618879.64
#Sta/Elev= 30
  3547.8  565.72  3780.4  564.13  4047.7  560.26  4108.6  558.88  4225.5  554.44
    4277  553.55  4559.8  543.62  4610.5  542.77  4640.5  539.36  4760.7  539.91
  4830.9  539.04  4981.2  540.38  4998.2  537.29  5000.9  536.79  5004.2  537.29
  5010.4  538.98  5091.4   542.8  5211.6  544.74  5294.1  544.85  5432.9  546.84
  5513.5  546.73  5634.5  549.56  5651.6  548.67  5674.8  548.88  5745.4  551.69
  5785.7  552.61  5805.9  552.13    5826   553.8  6017.6  558.48  6341.5  569.55
#Mann= 5 ,-1 , 0
  3547.8     .05       0  4559.8     .16       0  4998.2     .07       0
  5004.2     .16       0  5010.4     .05       0
Bank Sta=4998.2,5004.2
XS Rating Curve= 0 ,0
Exp/Cntr=0.3,0.1

Type RM Length L Ch R = 1 ,18134   ,929,929,929
BEGIN DESCRIPTION:
UNT0014 IN CHRS 27.0
END DESCRIPTION:
XS GIS Cut Line= 4
      3404566.88     10618936.93        3403257.     10618569.74
      3402767.41     10618400.47       3401611.2     10618252.04
#Sta/Elev= 30
    3459  569.19  3718.9  563.18  3870.9  560.72  4051.8  555.51    4272  553.87
  4357.1  549.99  4570.8  545.92  4649.4  545.89  4668.7  544.67  4872.2  540.34
  4909.2   539.2  4962.1  539.16  4985.2  537.28  5001.4  533.27  5004.2  532.77
  5007.4  533.27  5011.1  537.98  5047.6  537.21  5073.4  538.26  5089.1  537.68
  5114.7  538.31  5279.5  542.19  5447.3  543.91    5625  547.09  5760.6  548.01
  5835.2  550.85  5887.2   551.7  6129.1  559.03  6387.3  568.75  6503.1  570.99
#Mann= 5 ,-1 , 0
    3459     .05       0  4872.2     .16       0  5001.4     .07       0
  5007.4     .16       0  5114.7     .05       0
Bank Sta=5001.4,5007.4
XS Rating Curve= 0 ,0
Exp/Cntr=0.3,0.1

Type RM Length L Ch R = 1 ,17205   ,828,828,828
BEGIN DESCRIPTION:
UNT0014 IN CHRS 26.0
END DESCRIPTION:
XS GIS Cut Line= 4
      3404728.36      10617983.8      3403582.52     10617949.95
      3403056.47     10617744.22      3401717.96     10617905.67
#Sta/Elev= 30
  3665.9  574.25  3822.2   569.1  3902.3  569.62  4002.3  566.88  4062.3  567.68
  4172.4  566.61  4472.5  561.14  4586.6  556.72  4692.6   548.8  4750.6  545.59
  4958.1  538.65    4988  536.05  4992.2  532.63    4995  532.13  4998.2  532.63
    5006  532.67  5012.4  535.48  5017.8   535.9  5096.6  535.87  5145.5  537.11
  5180.7  536.42    5201  537.39    5452   541.8  5744.1  544.82  5945.5  545.65
  6187.3  548.71  6338.4  552.68  6439.1  557.83  6580.1  562.78  6725.3  566.05
#Mann= 5 ,-1 , 0
  3665.9     .05       0  4750.6     .16       0  4992.2     .07       0
  4998.2     .16       0    5201     .05       0
Bank Sta=4992.2,4998.2
XS Rating Curve= 0 ,0
Exp/Cntr=0.3,0.1

Type RM Length L Ch R = 1 ,16377   ,1158,1158,1158
BEGIN DESCRIPTION:
UNT0014 IN CHRS 24.0
END DESCRIPTION:
XS GIS Cut Line= 4
      3404764.81     10617689.53      3403530.43     10617288.49
      3403108.56     10617384.84      3401716.18     10617715.37
#Sta/Elev= 30
    3453  566.42  3792.3  557.44  3850.4  557.47  3960.5  554.65  4074.1  553.88
  4239.1  549.54  4462.8  548.41  4622.6  543.23  4633.5  539.28  4654.5  542.07
  4715.4  540.49  4829.3  536.58  4974.8  534.58  4992.4  530.29  4995.1  529.79
  4998.4  530.29  5005.6  531.74  5011.4  534.35  5016.5  533.31  5026.1   534.4
  5169.7  535.98  5210.8  539.21  5302.7  540.08  5632.2   544.1  5683.6  543.62
  6015.8  546.94  6100.2  549.54  6166.7  550.02    6443  560.67  6614.7  564.07
#Mann= 5 ,-1 , 0
    3453     .05       0  4715.4     .16       0  4992.4     .07       0
  4998.4     .16       0  5302.7     .05       0
Bank Sta=4992.4,4998.4
XS Rating Curve= 0 ,0
Exp/Cntr=0.3,0.1

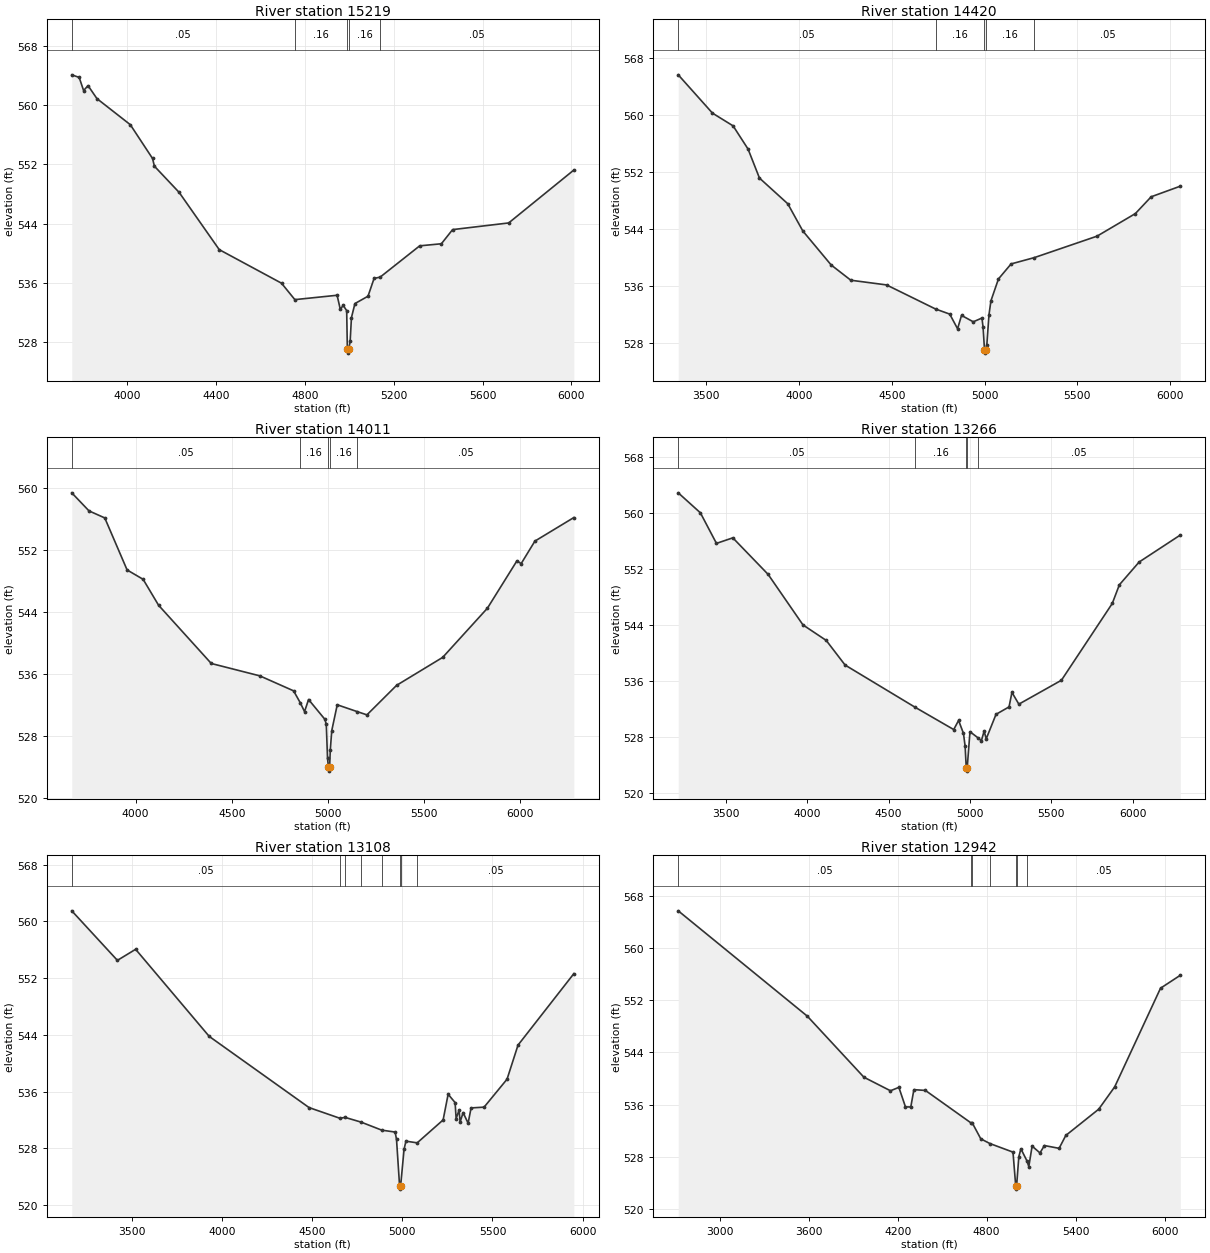
Type RM Length L Ch R = 1 ,15219   ,799,799,799
BEGIN DESCRIPTION:
UNT0014 IN CHRS 22.0
END DESCRIPTION:
XS GIS Cut Line= 4
      3404215.35     10616822.35      3403095.54     10616775.47
      3402936.68     10617048.91      3402121.63     10617163.48
#Sta/Elev= 30
  3750.5  564.09  3783.8  563.74  3803.8  561.97  3823.8  562.63  3863.8  560.88
    4014  557.36  4114.1   552.8  4122.5  551.76  4234.2  548.21  4414.3   540.5
  4694.6  535.97  4754.7  533.75  4944.9  534.34  4959.4  532.43  4972.2  532.98
    4988  532.27  4991.1  527.03  4993.8  526.53  4997.1  527.03  5003.7  528.15
  5009.5  531.33  5025.2  533.22    5084  534.21  5111.3  536.61  5138.8  536.79
  5316.7  541.01  5414.3  541.29  5464.8   543.2  5717.3   544.1  6010.6  551.24
#Mann= 5 ,-1 , 0
  3750.5     .05       0  4754.7     .16       0  4991.1     .07       0
  4997.1     .16       0  5138.8     .05       0
Bank Sta=4991.1,4997.1
XS Rating Curve= 0 ,0
Exp/Cntr=0.3,0.1

Type RM Length L Ch R = 1 ,14420   ,409,409,409
BEGIN DESCRIPTION:
UNT0014 IN CHRS 21.0
END DESCRIPTION:
XS GIS Cut Line= 4
      3404275.18     10616778.06      3402967.93     10616298.91
      3402522.62     10616449.95      3401993.97      10617103.6
#Sta/Elev= 30
  3350.7  565.62    3535  560.24  3646.1  558.45  3726.7  555.19    3788  551.12
  3940.5  547.51  4021.4  543.69  4174.1  538.91  4279.9  536.77  4472.3  536.11
  4735.9  532.73  4812.5  532.01  4854.7  529.95  4875.9  531.83  4939.2  530.93
  4985.9  531.46    4992  530.17  4999.6  527.03  5002.3  526.53  5005.6  527.03
    5012  527.63  5023.7   531.9  5034.3  533.88  5074.8  536.95  5142.9  539.06
  5268.3  539.95  5605.7  542.96  5811.9  546.13    5897  548.49  6053.9  549.98
#Mann= 5 ,-1 , 0
  3350.7     .05       0  4735.9     .16       0  4999.6     .07       0
  5005.6     .16       0  5268.3     .05       0
Bank Sta=4999.6,5005.6
XS Rating Curve= 0 ,0
Exp/Cntr=0.3,0.1

Type RM Length L Ch R = 1 ,14011   ,745,745,745
BEGIN DESCRIPTION:
UNT0014 IN CHRS 20.0
END DESCRIPTION:
XS GIS Cut Line= 4
      3404158.04     10616567.14       3403072.1     10616241.62
      3402814.29     10615936.93      3401777.83     10615627.03
#Sta/Elev= 30
  3667.2  559.44  3756.9  557.11  3839.1   556.2  3955.3  549.49  4038.8  548.28
  4119.4  544.93  4393.7  537.42  4646.8  535.82  4822.3  533.89  4856.9  532.36
  4879.4  531.21  4900.3  532.77  4984.8  530.23  4992.6  529.58  4999.1  525.18
  5003.9  524.03  5006.6  523.53  5009.9  524.03  5013.4  526.24  5021.2  528.77
  5049.7  532.09  5154.7   531.2  5204.3  530.79  5358.8   534.6  5598.9  538.21
  5831.6  544.55  5985.1  550.65  6007.5  550.31    6079  553.21  6281.8  556.25
#Mann= 5 ,-1 , 0
  3667.2     .05       0  4856.9     .16       0  5003.9     .07       0
  5009.9     .16       0  5154.7     .05       0
Bank Sta=5003.9,5009.9
XS Rating Curve= 0 ,0
Exp/Cntr=0.3,0.1

Type RM Length L Ch R = 1 ,13266   ,158,158,158
BEGIN DESCRIPTION:
UNT0014 IN CHRS 20.1
END DESCRIPTION:
XS GIS Cut Line= 6
      3404504.42     10616457.78      3403236.16     10615567.14
      3402741.37     10615551.51      3401915.85     10615035.89
      3401928.87     10615028.07      3401876.98      10615015.1
#Sta/Elev= 30
  3206.3  562.88  3342.5  560.03  3441.3  555.67    3542  556.46    3759  551.25
  3973.4  544.04  4116.3  541.83  4232.2  538.32  4661.3  532.32  4900.2  529.12
  4930.2  530.42  4960.2  528.57  4970.2  526.77  4977.2  523.69    4980  523.19
  4983.2  523.69  5000.2  528.81  5049.5  527.94  5070.3  527.52  5086.9  528.88
  5100.3  527.81  5160.3  531.29  5240.4  532.35  5258.2  534.42  5300.7  532.74
  5562.5  536.15  5875.1   547.1  5918.7  549.76  6040.2  553.01  6293.5  556.86
#Mann= 5 ,-1 , 0
  3206.3     .05       0  4661.3     .16       0  4977.2     .07       0
  4983.2     .16       0  5049.5     .05       0
Bank Sta=4977.2,4983.2
XS Rating Curve= 0 ,0
Exp/Cntr=0.3,0.1

Type RM Length L Ch R = 1 ,13108   ,166,166,166
BEGIN DESCRIPTION:
UNT0014 IN CHRS 19.0
END DESCRIPTION:
XS GIS Cut Line= 4
      3404535.61     10616410.87      3403160.64     10615449.95
      3402905.43     10615371.82      3402158.29     10614986.54
#Sta/Elev= 30
  3166.4  561.48  3419.5   554.5  3520.6  556.06  3928.8  543.79  4482.6  533.76
  4654.1  532.25    4682  532.38  4771.5  531.71  4885.8  530.58  4960.1  530.31
  4967.8  529.27  4984.7  522.77  4987.4  522.27  4990.7  522.77  5009.7   527.9
  5020.1  529.03  5082.5  528.79  5226.3  532.02  5254.1  535.64  5292.8  534.46
  5298.4   532.2  5314.9  533.42  5320.6  531.73  5337.1  533.05  5364.9  531.56
  5381.4  533.71  5453.5  533.82  5580.9  537.76  5641.7  542.56  5951.4  552.63
#Mann= 8 ,-1 , 0
  3166.4     .05       0  4654.1     .16       0    4682     .05       0
  4771.5     .16       0  4885.8     .05       0  4984.7     .07       0
  4990.7     .05       0  5082.5     .05       0
Bank Sta=4984.7,4990.7
XS Rating Curve= 0 ,0
Exp/Cntr=0.3,0.1

Type RM Length L Ch R = 1 ,12942   ,133,133,133
BEGIN DESCRIPTION:
UNT0014 IN CHRS 18.0
END DESCRIPTION:
XS GIS Cut Line= 4
      3404953.21     10616472.54      3403334.25     10615352.73
      3402939.29     10615205.16      3402110.27     10614649.59
#Sta/Elev= 30
  2718.6  565.66  3589.8  549.54  3971.7   540.2  4150.7  538.13  4207.5  538.65
    4252  535.66  4287.9  535.65  4308.9   538.3  4386.6  538.18  4697.4  533.16
  4701.6  533.26  4760.2  530.78  4821.1  530.06  4977.6  528.74    4996  523.58
  4998.7  523.08    5002  523.58  5016.9  528.03    5031  529.25  5070.7  527.45
  5084.4  526.53  5106.6  529.66  5159.7  528.62  5189.6  529.75  5288.8  529.32
  5333.8  531.29    5556  535.31    5664  538.73  5973.2  553.82  6106.7   555.8
#Mann= 7 ,-1 , 0
  2718.6     .05       0  4697.4     .16       0  4701.6     .05       0
  4821.1     .16       0    4996     .07       0    5002     .16       0
  5070.7     .05       0
Bank Sta=4996,5002
XS Rating Curve= 0 ,0
Exp/Cntr=0.3,0.1

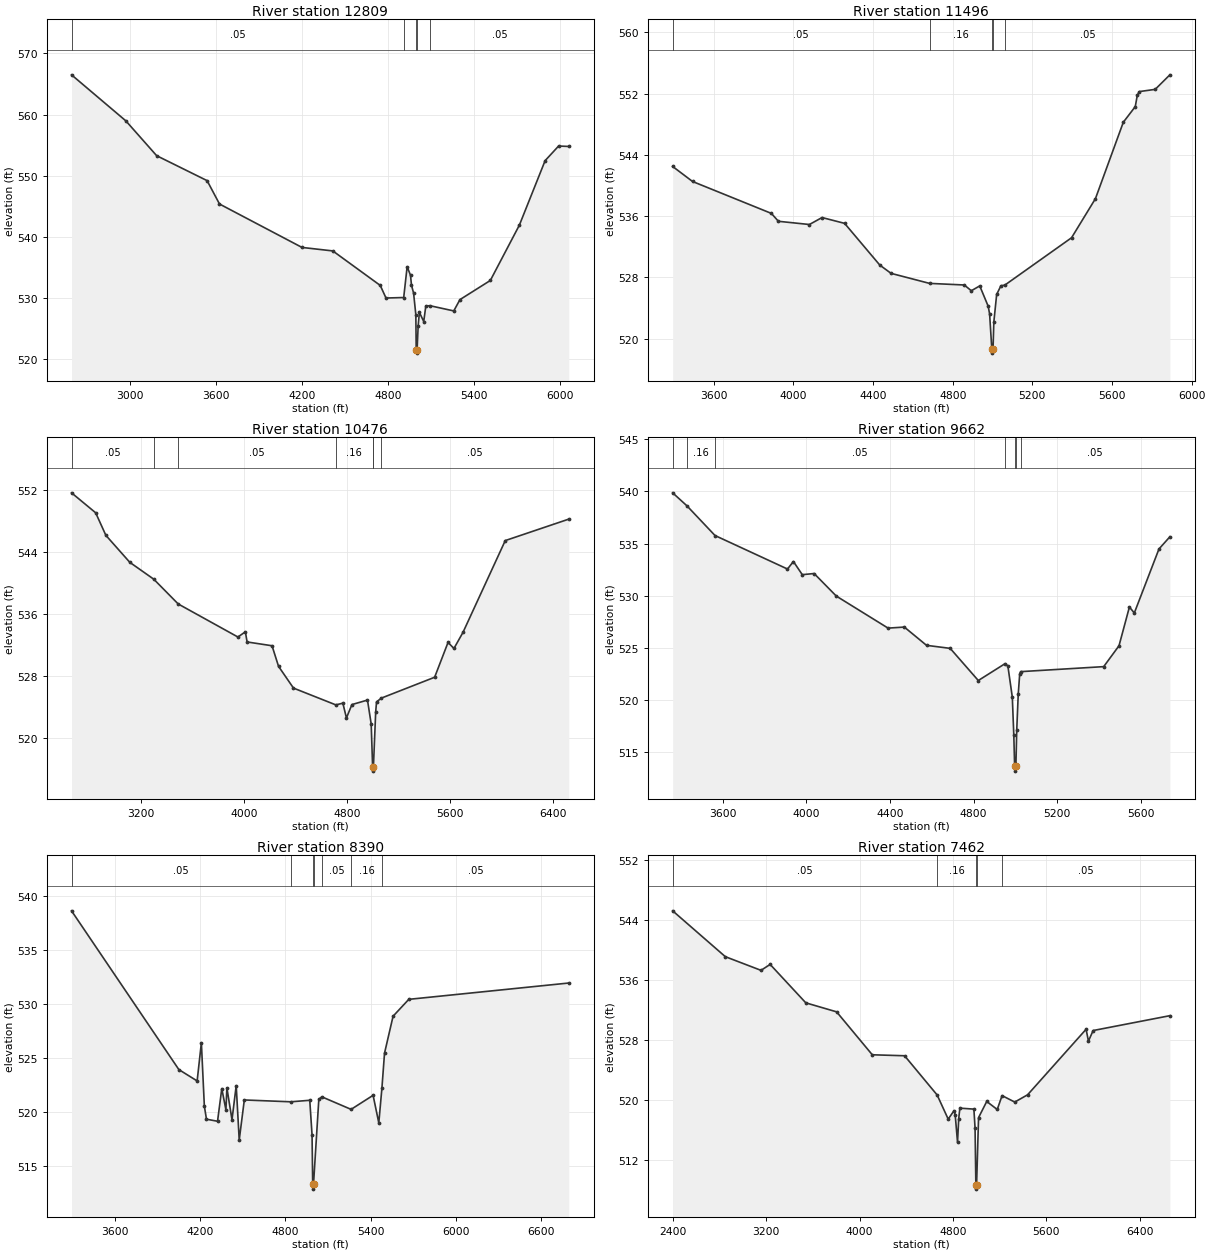
Type RM Length L Ch R = 1 ,12809   ,1313,1313,1313
BEGIN DESCRIPTION:
UNT0014 IN CHRS 17.0
END DESCRIPTION:
XS GIS Cut Line= 4
      3405057.37     10616433.48      3403282.17     10615200.82
      3402900.22     10615057.59      3402141.33     10614576.23
#Sta/Elev= 30
  2590.7  566.49  2969.7  558.96  3184.4  553.27  3536.3  549.19  3622.7  545.37
  4198.1  538.27  4412.9   537.7  4743.8  532.06    4784     530  4907.4  530.08
  4931.4  535.12  4954.9  533.72  4961.7   532.1  4976.3  530.81    4992  527.28
  4994.6  521.49  4997.4  520.99  5000.6  521.49  5008.3  525.46  5016.9  527.65
  5047.1  526.16  5061.7   528.7  5090.9  528.74  5256.6  527.89  5299.7  529.74
  5511.6  532.87  5714.2  541.92  5893.7  552.46  5987.8  554.85  6058.5  554.78
#Mann= 5 ,-1 , 0
  2590.7     .05       0  4907.4     .16       0  4994.6     .07       0
  5000.6     .16       0  5090.9     .05       0
Bank Sta=4994.6,5000.6
XS Rating Curve= 0 ,0
Exp/Cntr=0.3,0.1

Type RM Length L Ch R = 1 ,11496   ,1020,1020,1020
BEGIN DESCRIPTION:
UNT0014 IN CHRS 16.0
END DESCRIPTION:
XS GIS Cut Line= 3
      3404218.34     10615276.56      3403018.32     10614076.54
      3402218.31     10614076.54
#Sta/Elev= 30
  3393.5  542.48  3493.3  540.52  3889.3  536.35  3924.6  535.32  4080.2   534.9
  4143.8  535.81    4257  535.05  4433.8   529.6  4490.3  528.52  4683.5  527.21
    4858     527  4893.4  526.25  4935.8  526.88  4978.2  524.22  4985.3  523.21
  4996.4   518.6  4999.2   518.1  5002.4   518.6  5006.5  522.16  5020.7  525.77
  5041.9  526.89    5062  526.99  5396.8  533.17  5516.8  538.28  5656.8  548.26
  5716.8   550.3  5726.8  551.75  5736.8  552.26  5816.8  552.55  5890.6  554.45
#Mann= 5 ,-1 , 0
  3393.5     .05       0  4683.5     .16       0  4996.4     .07       0
  5002.4     .16       0    5062     .05       0
Bank Sta=4996.4,5002.4
XS Rating Curve= 0 ,0
Exp/Cntr=0.3,0.1

Type RM Length L Ch R = 1 ,10476   ,814,814,814
BEGIN DESCRIPTION:
UNT0014 IN CHRS 14.0
END DESCRIPTION:
XS GIS Cut Line= 4
       3405131.1     10614883.96      3403672.79     10613868.35
       3403221.4     10613325.82      3401916.02     10613781.18
#Sta/Elev= 30
  2659.4  551.65  2847.1  549.07  2926.3  546.16  3112.4  542.67  3298.7  540.49
  3488.6  537.29  3952.8  533.02  4010.8  533.69  4024.3  532.38  4218.1  531.89
  4268.7  529.23  4384.8  526.42    4714  524.25  4768.8  524.47  4796.5  522.56
  4839.1  524.29  4960.2  524.87  4988.9  521.79  5000.2  516.19  5002.9  515.69
  5006.2  516.19    5024  523.35  5030.6  524.64  5068.8  525.13  5482.2  527.82
  5586.4  532.32  5632.3  531.54  5702.9  533.63  6031.2  545.48  6524.8  548.25
#Mann= 7 ,-1 , 0
  2659.4     .05       0  3298.7     .16       0  3488.6     .05       0
    4714     .16       0  5000.2     .07       0  5006.2     .16       0
  5068.8     .05       0
Bank Sta=5000.2,5006.2
XS Rating Curve= 0 ,0
Exp/Cntr=0.3,0.1

Type RM Length L Ch R = 1 ,9662    ,1272,1272,1272
BEGIN DESCRIPTION:
UNT0014 IN CHRS 12.0
END DESCRIPTION:
XS GIS Cut Line= 3
      3404909.63     10614080.52      3403709.64     10612880.53
      3403059.65     10612680.53
#Sta/Elev= 30
  3361.4  539.86  3429.4  538.62  3563.9  535.77  3910.4  532.56  3938.7  533.28
  3981.1  532.02  4037.7  532.13  4143.7  529.97  4391.2   526.9    4469     527
  4575.1  525.25  4688.2  524.96  4822.6  521.88  4950.9   523.5    4964  523.27
  4985.2  520.29  4992.3  516.67  4996.3   513.7  4999.1   513.2  5002.3   513.7
  5006.4  517.13  5013.5  520.56  5020.6  522.52  5025.1  522.73  5422.1  523.21
  5495.3  525.21    5545  528.92  5568.5  528.35  5686.3  534.48  5738.5  535.65
#Mann= 7 ,-1 , 0
  3361.4     .05       0  3429.4     .16       0  3563.9     .05       0
  4950.9     .16       0  4996.3     .07       0  5002.3     .16       0
  5025.1     .05       0
Bank Sta=4996.3,5002.3
XS Rating Curve= 0 ,0
Exp/Cntr=0.3,0.1

Type RM Length L Ch R = 1 ,8390    ,928,928,928
BEGIN DESCRIPTION:
UNT0014 IN CHRS 10.0
END DESCRIPTION:
XS GIS Cut Line= 3
      3405492.14     10613041.67      3404092.11     10612091.64
      3402292.12     10611891.64
#Sta/Elev= 30
  3293.1  538.64  4049.3  523.95  4178.1   522.9  4207.9  526.44  4228.9  520.56
  4243.9  519.36  4321.8  519.17  4351.7  522.19  4380.8  520.23  4387.6  522.27
  4423.6  519.31  4453.3  522.47  4474.5  517.43  4510.4  521.14  4837.8  520.97
  4971.5  521.11  4987.6  517.91  4992.1  513.39  4994.9  512.89  4998.1  513.39
  5035.3   521.2  5056.6  521.43  5262.7  520.27  5417.7  521.57  5457.9  519.02
  5479.9  522.25  5498.2  525.47  5558.5  528.89  5669.2  530.45  6796.1  531.96
#Mann= 7 ,-1 , 0
  3293.1     .05       0  4837.8     .16       0  4992.1     .07       0
  4998.1     .16       0  5056.6     .05       0  5262.7     .16       0
  5479.9     .05       0
Bank Sta=4992.1,4998.1
XS Rating Curve= 0 ,0
Exp/Cntr=0.3,0.1

Type RM Length L Ch R = 1 ,7462    ,1214,1214,1214
BEGIN DESCRIPTION:
UNT0014 IN CHRS 8.0
END DESCRIPTION:
XS GIS Cut Line= 4
      3406450.58      10613247.7      3405165.85     10611654.81
      3403950.57     10611620.09      3402956.88     10611702.53
#Sta/Elev= 30
  2398.7  545.17    2850  539.06  3155.5  537.24  3233.8  538.03  3539.3  532.91
  3803.2  531.71  4108.7  525.99  4385.4  525.86  4664.5  520.63    4759  517.42
    4809  518.54    4819  517.98    4839  514.33    4849  517.46    4859  518.88
  4979.1  518.75  4989.1  516.25  4996.1  508.59  4998.8  508.09  5002.1  508.59
  5019.1  517.62  5089.1  519.77  5179.2   518.7  5220.5  520.55  5329.2  519.69
  5439.3  520.66  5940.3  529.39  5960.4  527.81  6000.5  529.22    6658   531.2
#Mann= 5 ,-1 , 0
  2398.7     .05       0  4664.5     .16       0  4996.1     .07       0
  5002.1     .16       0  5220.5     .05       0
Bank Sta=4996.1,5002.1
XS Rating Curve= 0 ,0
Exp/Cntr=0.3,0.1

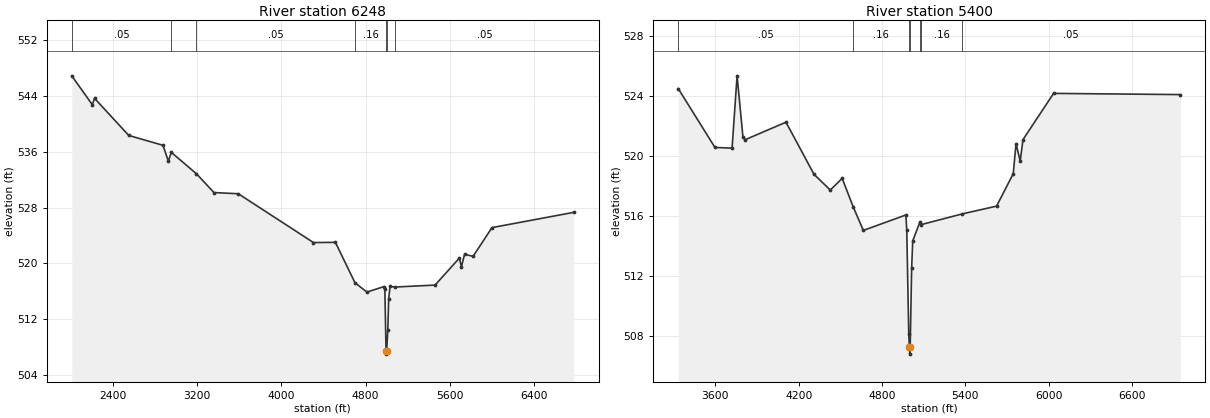
Type RM Length L Ch R = 1 ,6248    ,848,848,848
BEGIN DESCRIPTION:
UNT0014 IN CHRS 1.0
END DESCRIPTION:
XS GIS Cut Line= 4
      3406642.99     10613282.13      3405226.32     10611136.29
      3404795.77     10610768.24      3403165.42     10610684.98
#Sta/Elev= 30
  2008.6  546.87  2203.8  542.74  2224.9  543.65    2550  538.33  2875.1  536.92
  2926.3  534.65  2954.5  535.91  3193.4  532.84  3359.8  530.15  3590.9  529.98
    4305  522.99  4513.6  523.02  4699.8  517.22  4812.9   515.9  4976.5  516.69
  4983.1  516.37  4994.4  507.51  4997.1  507.01  5000.4  507.51  5011.6  510.52
  5019.3  514.93  5032.7   516.7  5080.3  516.62  5460.4   516.9  5690.7  520.76
  5710.7  519.54  5740.8  521.32  5820.9  521.01  6001.1  525.13  6778.8  527.32
#Mann= 7 ,-1 , 0
  2008.6     .05       0  2954.5     .16       0  3193.4     .05       0
  4699.8     .16       0  4994.4     .07       0  5000.4     .16       0
  5080.3     .05       0
Bank Sta=4994.4,5000.4
XS Rating Curve= 0 ,0
Exp/Cntr=0.3,0.1

Type RM Length L Ch R = 1 ,5400    ,0,0,0
BEGIN DESCRIPTION:
UNT0014 IN CHRS 1.0b
END DESCRIPTION:
XS GIS Cut Line= 4
      3406092.88      10611596.9      3405313.13     10610415.81
      3404882.57     10610047.75       3403250.6     10609964.42
#Sta/Elev= 30
  3332.5  524.48  3596.8  520.56  3720.2  520.51  3756.3  525.33  3798.4  521.27
  3813.5  521.07  4108.5  522.24  4310.2  518.77  4427.6  517.72  4513.1   518.5
  4592.2  516.61  4665.4  515.03  4971.8  516.06  4978.3  515.06  4992.6  508.16
    4997  507.29  4999.8  506.79    5003  507.29  5013.5  512.54  5021.2  514.33
  5072.9  515.59  5078.6  515.41  5377.1  516.13  5625.1  516.65  5745.2  518.81
  5765.3  520.81  5795.3  519.65  5815.3  521.08  6035.6  524.16  6948.3  524.08
#Mann= 7 ,-1 , 0
  3332.5     .05       0  4592.2     .16       0    4997     .07       0
    5003     .16       0  5072.9     .12       0  5078.6     .16       0
  5377.1     .05       0
Bank Sta=4997,5003
XS Rating Curve= 0 ,0
Exp/Cntr=0.3,0.1

Chan Stop Cuts=-1
Use User Specified Reach Order=0
Composite Channel Slope=5