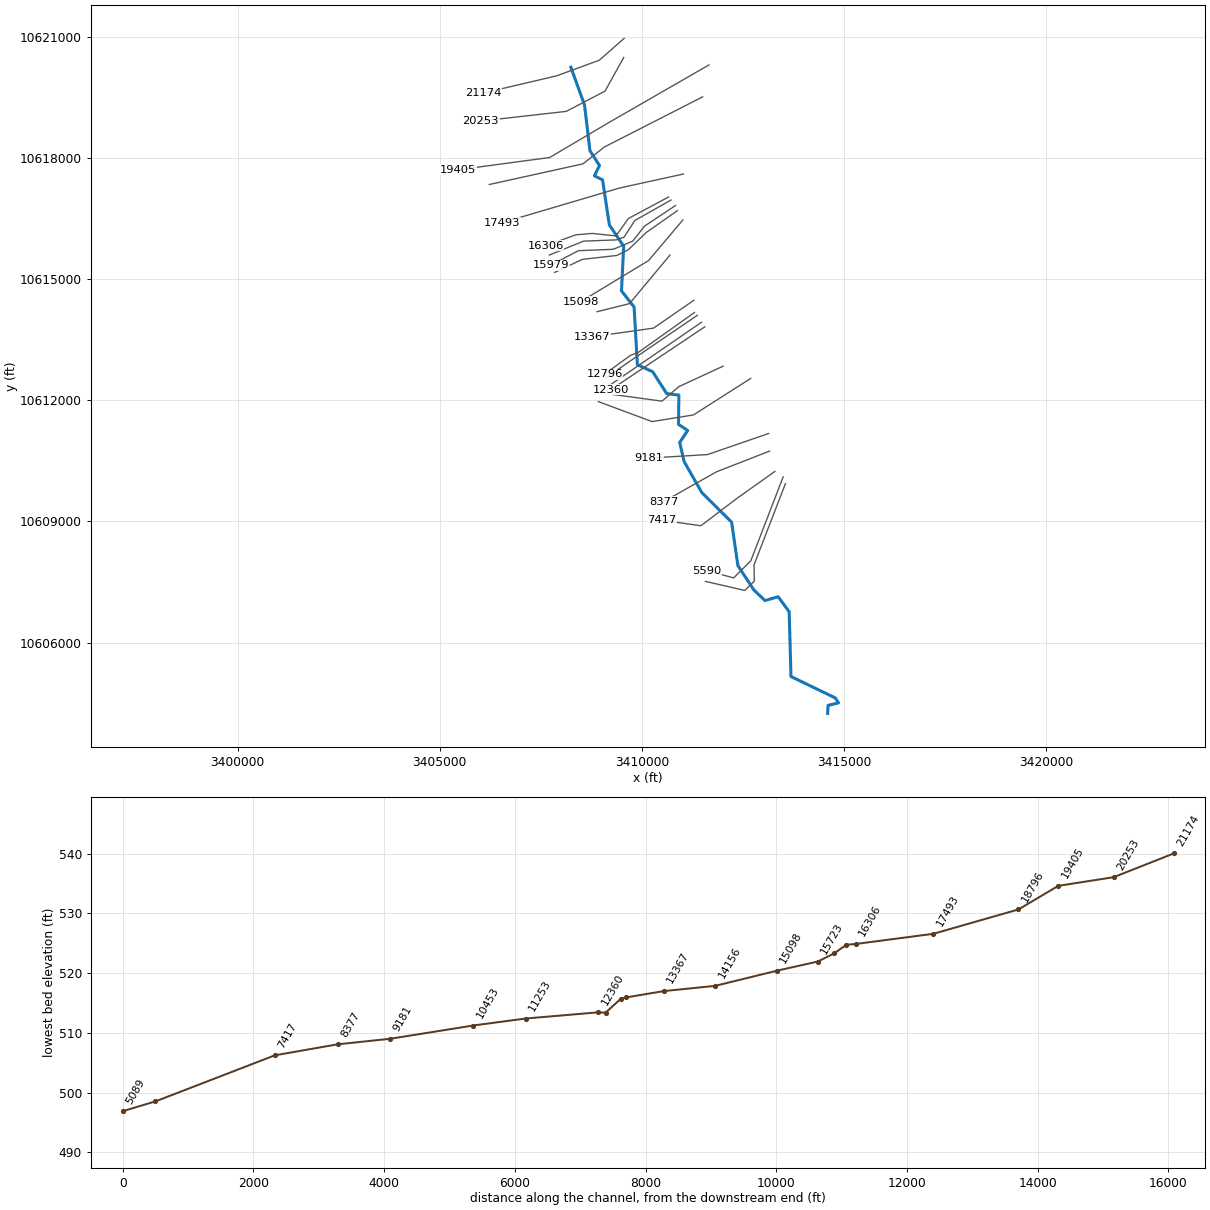
--- UNT0016 IN CHRS.prj (project) ---

Proj Title=UNT0016 IN CHRS Base Level Engineering
Current Plan=p01
Default Exp/Contr=0.3,0.1
English Units
Geom File=g01
Flow File=f01
Plan File=p01
BEGIN DESCRIPTION:
UNT0016 IN CHRS
END DESCRIPTION:

--- UNT0016 IN CHRS.p01 (plan) ---

Plan Title=Multiple Run
Short Identifier=Multiple
Geom File=g01
Flow File=f01
Subcritical Flow
K Sum by GR= 0
Std Step Tol= 0.01
Critical Tol= 0.01
Num of Std Step Trials= 20
Max Error Tol= 0.3
Flow Tol Ratio= 0.001
Split Flow NTrial= 30
Split Flow Tol= 0.02
Split Flow Ratio= 0.02
Log Output Level= 0
Friction Slope Method= 1
Unsteady Friction Slope Method= 2
Unsteady Bridges Friction Slope Method= 1
Parabolic Critical Depth
Global Vel Dist=  1 , 1 , 1
Global Log Level= 0
CheckData=True
Encroach Param= -1, 0, 0, 0
BEGIN DESCRIPTION:
Multiple Run
END DESCRIPTION:

--- UNT0016 IN CHRS.f01 (steady flow) ---

Flow Title=Multiple
Number of Profiles=7
Profile Names=10-year,25-year,50-year,1pct_min,100-year,1pct_plu,500-year
River Rch & RM= UNT0016 IN CHRS,Reach-1,21174
     321     395     448     369     499     675     620
River Rch & RM= UNT0016 IN CHRS,Reach-1,19405
     394     490     558     463     626     847     786
River Rch & RM= UNT0016 IN CHRS,Reach-1,15979
     629     802     930     784    1060    1433    1373
River Rch & RM= UNT0016 IN CHRS,Reach-1,13367
     666     848     983     827    1119    1513    1447
River Rch & RM= UNT0016 IN CHRS,Reach-1,7417
     767     983    1144     965    1305    1765    1697
Boundary for River Rch & Prof#=UNT0016 IN CHRS,Reach-1,1
Up Type=0
Dn Type=3
Dn Slope=0.005
Boundary for River Rch & Prof#=UNT0016 IN CHRS,Reach-1,2
Up Type=0
Dn Type=3
Dn Slope=0.005
Boundary for River Rch & Prof#=UNT0016 IN CHRS,Reach-1,3
Up Type=0
Dn Type=3
Dn Slope=0.005
Boundary for River Rch & Prof#=UNT0016 IN CHRS,Reach-1,4
Up Type=0
Dn Type=3
Dn Slope=0.005
Boundary for River Rch & Prof#=UNT0016 IN CHRS,Reach-1,5
Up Type=0
Dn Type=3
Dn Slope=0.005
Boundary for River Rch & Prof#=UNT0016 IN CHRS,Reach-1,6
Up Type=0
Dn Type=3
Dn Slope=0.005
Boundary for River Rch & Prof#=UNT0016 IN CHRS,Reach-1,7
Up Type=0
Dn Type=3
Dn Slope=0.005

--- UNT0016 IN CHRS.g01 (geometry) ---

Geom Title=Existing Conditions

River Reach=UNT0016 IN CHRS,Reach-1
Reach XY= 30
      3408242.11     10620241.64      3408579.89     10619305.91
      3408714.57     10618172.80      3408949.50     10617809.88
      3408825.12     10617553.00      3409025.51     10617454.60
      3409194.29     10616337.44      3409548.76     10615809.84
      3409493.69     10614706.98      3409805.35     10614307.93
      3409886.98     10612878.91      3410263.46     10612706.28
      3410613.52     10612164.14      3410912.44     10612127.12
      3410904.72     10611402.62      3411131.13     10611251.32
      3410933.65     10610955.74      3411043.35     10610480.94
      3411482.18     10609711.61      3412216.70     10608983.98
      3412372.96     10607907.19      3412765.62     10607308.25
      3413041.56     10607043.00      3413368.49     10607137.46
      3413640.59     10606765.81      3413685.13     10605162.90
      3414778.75     10604634.84      3414862.11     10604511.64
      3414602.76     10604450.93      3414592.11     10604251.64

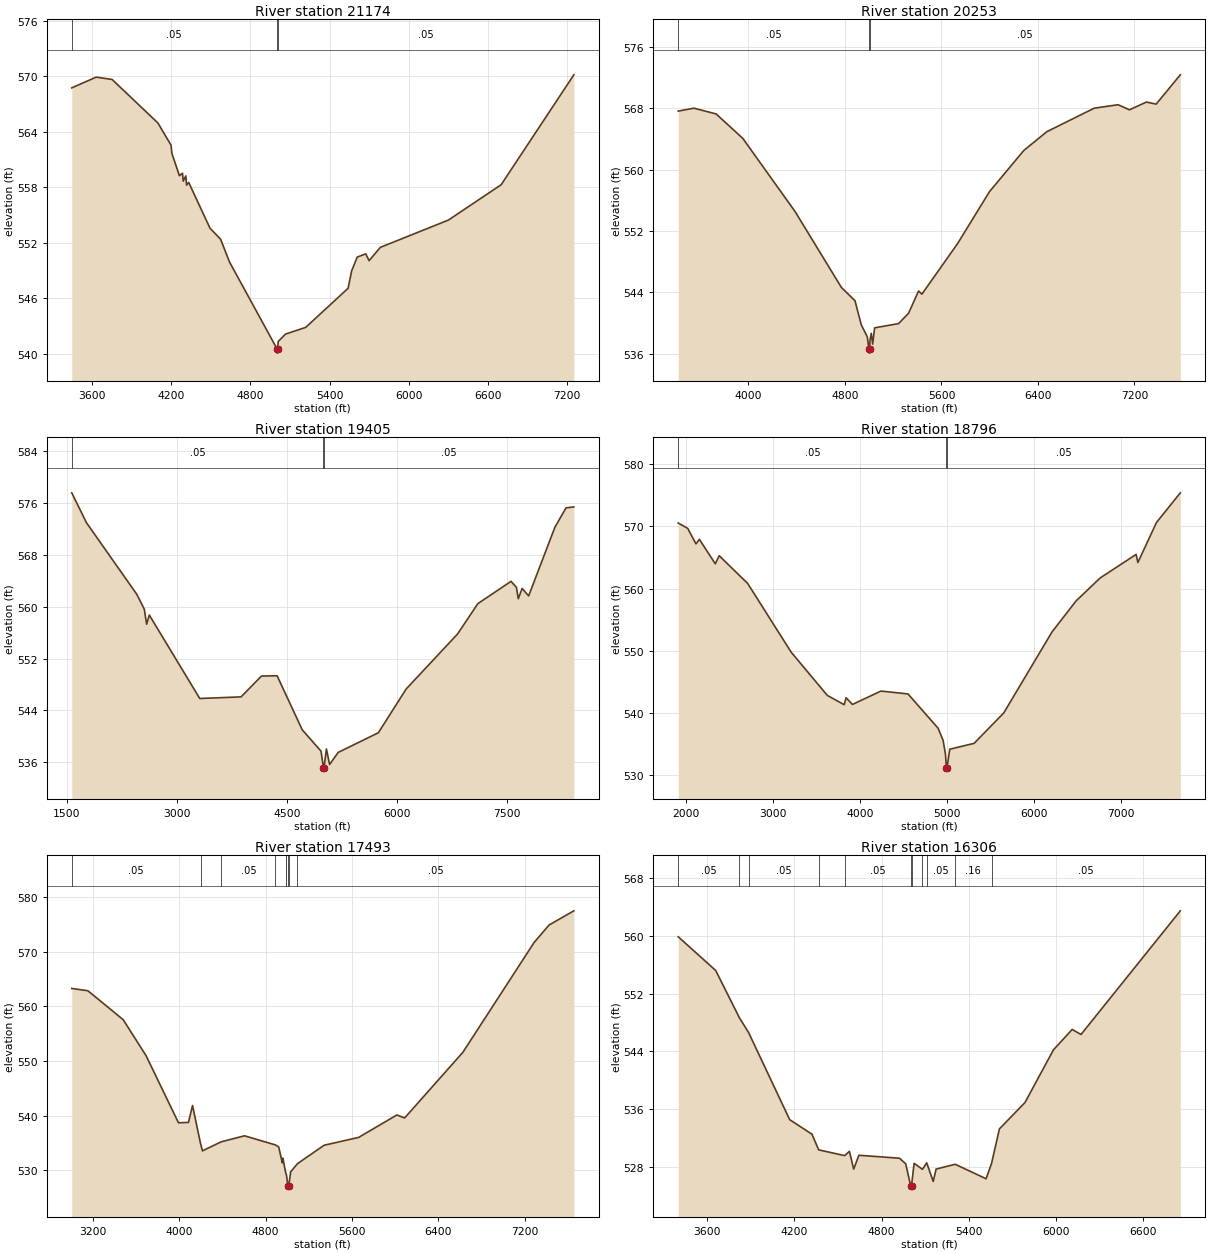
Type RM Length L Ch R = 1,21174,921,921,921
BEGIN DESCRIPTION:
UNT0016 IN CHRS 32.0
END DESCRIPTION:
XS GIS Cut Line= 4
      3409559.89     10620955.58      3408945.32     10620413.92
      3407893.24     10620028.50      3406076.28     10619601.60
#Sta/Elev= 30
  3445.4  568.72  3630.5  569.88  3751.0  569.63  4098.2  564.93  4197.8  562.53
  4204.4  561.64  4261.4  559.23  4284.9  559.49  4290.2  558.64  4310.1  559.21
  4315.4  558.21  4331.9  558.50  4493.1  553.56  4574.0  552.35  4640.8  549.91
  4999.9  540.55  5002.6  540.05  5005.9  540.55  5010.4  541.31  5066.1  542.11
  5218.6  542.83  5540.3  547.06  5567.0  548.94  5609.4  550.43  5673.8  550.78
  5699.4  550.04  5784.2  551.48  6300.5  554.43  6700.4  558.25  7251.5  570.13
#Mann=3,-1,0
  3445.4    0.05       0  4999.9    0.03       0  5005.9    0.05       0
Bank Sta=4999.9,5005.9
Exp/Cntr=0.3,0.1

Type RM Length L Ch R = 1,20253,848,848,848
BEGIN DESCRIPTION:
UNT0016 IN CHRS 32.2
END DESCRIPTION:
XS GIS Cut Line= 4
      3409549.50     10620481.66      3409085.94     10619648.30
      3408127.61     10619148.30      3406013.08     10618908.72
#Sta/Elev= 30
  3417.6  567.63  3547.6  568.01  3731.7  567.26  3953.6  564.06  4386.8  554.52
  4770.3  544.64  4883.1  542.90  4935.4  539.75  4985.2  538.19  4998.6  536.57
  5001.4  536.07  5004.6  536.57  5007.3  537.75  5018.1  538.65  5029.7  537.25
  5045.8  539.37  5244.6  539.92  5327.3  541.27  5410.0  544.17  5437.8  543.76
  5733.9  550.36  5997.9  557.12  6282.9  562.50  6474.1  564.95  6866.6  568.01
  7064.3  568.46  7159.0  567.80  7299.4  568.81  7379.9  568.54  7580.2  572.36
#Mann=3,-1,0
  3417.6    0.05       0  4998.6    0.03       0  5004.6    0.05       0
Bank Sta=4998.6,5004.6
Exp/Cntr=0.3,0.1

Type RM Length L Ch R = 1,19405,609,609,609
BEGIN DESCRIPTION:
UNT0016 IN CHRS 32.1
END DESCRIPTION:
XS GIS Cut Line= 4
      3411658.01     10620297.97      3409201.44     10618883.05
      3407717.06     10618006.31      3405451.42     10617702.49
#Sta/Elev= 30
  1565.2  577.61  1765.3  573.00  2452.1  561.93  2554.2  559.63  2585.7  557.31
  2622.2  558.73  3309.9  545.84  3873.1  546.09  4151.9  549.31  4364.7  549.35
  4707.4  541.00  4963.0  537.71  4997.0  535.12  4999.8  534.62  5003.0  535.12
  5037.1  538.04  5080.0  535.65  5197.1  537.51  5745.3  540.55  6123.7  547.30
  6825.3  555.81  7101.2  560.49  7553.9  563.94  7626.9  563.01  7652.6  561.25
  7704.9  562.84  7793.8  561.69  8152.5  572.31  8303.5  575.29  8410.0  575.43
#Mann=3,-1,0
  1565.2    0.05       0  4997.0    0.04       0  5003.0    0.05       0
Bank Sta=4997,5003
Exp/Cntr=0.3,0.1

Type RM Length L Ch R = 1,18796,1303,1303,1303
BEGIN DESCRIPTION:
UNT0016 IN CHRS 31.0
END DESCRIPTION:
XS GIS Cut Line= 4
      3411501.78     10619508.05      3409071.23     10618266.73
      3408541.72     10617850.06      3406225.57     10617338.26
#Sta/Elev= 30
  1912.5  570.52  2022.2  569.65  2116.7  567.17  2155.5  567.90  2338.9  563.97
  2383.7  565.27  2711.0  560.82  3210.9  549.79  3627.5  542.83  3821.0  541.34
  3843.5  542.45  3916.4  541.38  4244.1  543.53  4555.2  543.07  4901.0  537.57
  4958.7  535.62  4986.0  533.43  4997.4  531.17  5000.2  530.67  5003.4  531.17
  5035.7  534.19  5315.5  535.13  5657.0  540.02  6211.5  553.02  6488.8  558.01
  6766.1  561.70  7179.0  565.48  7199.5  564.18  7413.2  570.60  7687.5  575.37
#Mann=3,-1,0
  1912.5    0.05       0  4997.4   0.035       0  5003.4    0.05       0
Bank Sta=4997.4,5003.4
Exp/Cntr=0.3,0.1

Type RM Length L Ch R = 1,17493,1187,1187,1187
BEGIN DESCRIPTION:
UNT0016 IN CHRS 28.0
END DESCRIPTION:
XS GIS Cut Line= 3
      3411024.39     10617598.34      3409444.50     10617251.11
      3406536.81     10616391.82
#Sta/Elev= 30
  3004.6  563.28  3153.8  562.86  3480.7  557.57  3692.9  550.98  3992.9  538.72
  4085.5  538.79  4123.0  541.88  4196.8  534.94  4215.1  533.59  4388.6  535.24
  4604.2  536.34  4890.6  534.67  4921.1  534.29  4954.3  531.40  4959.6  532.27
  4985.1  529.63  4992.6  529.18  5007.5  527.09  5010.3  526.59  5013.5  527.09
  5031.4  529.74  5094.5  531.24  5341.3  534.61  5661.7  536.05  6015.4  540.15
  6087.2  539.60  6626.8  551.61  7286.6  571.69  7425.0  574.88  7654.2  577.47
#Mann=9,-1,0
  3004.6    0.05       0  4196.8    0.16       0  4388.6    0.05       0
  4890.6    0.16       0  4985.1    0.05       0  4992.6    0.16       0
  5007.5    0.07       0  5013.5    0.16       0  5094.5    0.05       0
Bank Sta=5007.5,5013.5
Exp/Cntr=0.3,0.1

Type RM Length L Ch R = 1,16306,145,145,145
BEGIN DESCRIPTION:
UNT0016 IN CHRS 27.0
END DESCRIPTION:
XS GIS Cut Line= 6
      3410660.14     10617030.87      3409663.62     10616496.15
      3409358.06     10616065.59      3408774.73     10616128.09
      3408361.54     10616093.37      3407618.48     10615819.07
#Sta/Elev= 30
  3400.8  559.91  3658.7  555.23  3821.8  548.67  3885.9  546.58  4167.9  534.53
  4321.3  532.51  4367.3  530.34  4546.4  529.54  4578.9  530.13  4608.4  527.68
  4644.1  529.59  4923.4  529.18  4966.3  528.41  5000.2  525.39  5002.9  524.89
  5006.2  525.39  5024.2  528.47  5081.4  527.64  5110.9  528.54  5155.6  525.96
  5175.6  527.67  5306.9  528.34  5519.3  526.33  5556.9  528.44  5611.3  533.25
  5786.9  536.90  5983.3  544.22  6112.0  547.05  6172.8  546.35  6856.2  563.51
#Mann=11,-1,0
  3400.8    0.05       0  3821.8     0.1       0  3885.9    0.05       0
  4367.3    0.16       0  4546.4    0.05       0  5000.2   0.035       0
  5006.2    0.05       0  5081.4    0.16       0  5110.9    0.05       0
  5306.9    0.16       0  5556.9    0.05       0
Bank Sta=5000.2,5006.2
Exp/Cntr=0.3,0.1

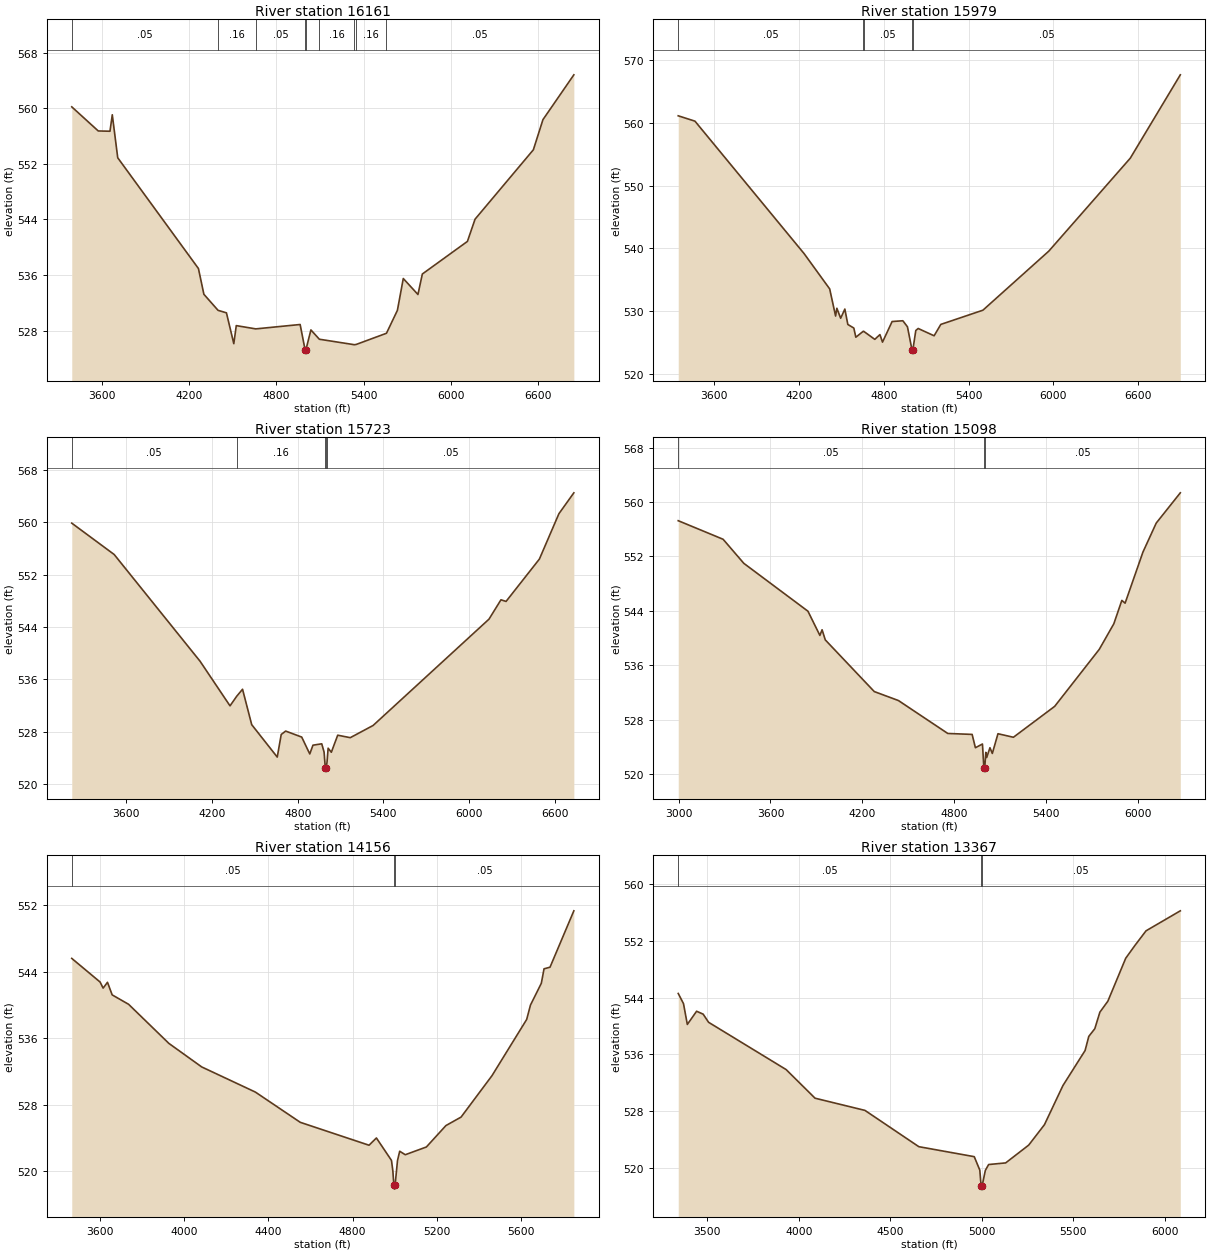
Type RM Length L Ch R = 1,16161,182,182,182
BEGIN DESCRIPTION:
UNT0016 IN CHRS 26.0
END DESCRIPTION:
XS GIS Cut Line= 6
      3410719.15     10616954.47      3409823.34     10616447.54
      3409555.98     10616034.34      3409368.48     10615968.37
      3408555.98     10615937.12      3407708.78     10615593.38
#Sta/Elev= 30
  3391.2  560.21  3573.5  556.74  3654.3  556.70  3670.2  559.07  3707.7  552.88
  4263.3  536.94  4300.9  533.23  4398.4  530.92  4456.2  530.56  4506.9  526.12
  4523.9  528.72  4658.0  528.25  4963.6  528.88  4997.6  525.26  5000.4  524.76
  5003.6  525.26  5037.8  528.10  5095.9  526.76  5337.5  525.97  5349.8  526.01
  5558.1  527.62  5633.4  530.92  5673.8  535.50  5774.8  533.20  5805.1  536.15
  6115.4  540.84  6168.0  544.04  6569.5  554.03  6635.5  558.37  6848.2  564.82
#Mann=9,-1,0
  3391.2    0.05       0  4398.4    0.16       0  4658.0    0.05       0
  4997.6   0.035       0  5003.6    0.05       0  5095.9    0.16       0
  5337.5    0.05       0  5349.8    0.16       0  5558.1    0.05       0
Bank Sta=4997.6,5003.6
Exp/Cntr=0.3,0.1

Type RM Length L Ch R = 1,15979,256,256,256
BEGIN DESCRIPTION:
UNT0016 IN CHRS 25.0
END DESCRIPTION:
XS GIS Cut Line= 6
      3410830.29     10616819.07      3410062.93     10616308.65
      3409771.26     10615937.12      3409292.09     10615735.73
      3408427.51     10615701.01      3407750.41     10615343.36
#Sta/Elev= 30
  3345.1  561.09  3463.4  560.24  4235.9  539.16  4416.7  533.55  4458.6  529.23
  4467.5  530.47  4494.5  528.88  4524.1  530.34  4545.1  527.89  4587.6  527.32
  4601.8  525.86  4654.0  526.80  4656.2  526.82  4735.9  525.52  4772.3  526.28
  4790.6  525.08  4858.6  528.36  4934.6  528.48  4967.1  527.52  4999.3  523.83
  5002.1  523.33  5005.3  523.83  5026.1  526.93  5043.0  527.25  5155.7  526.09
  5203.2  527.90  5501.0  530.16  5967.3  539.56  6543.9  554.35  6897.8  567.61
#Mann=5,-1,0
  3345.1    0.05       0  4654.0    0.16       0  4656.2    0.05       0
  4999.3    0.04       0  5005.3    0.05       0
Bank Sta=4999.3,5005.3
Exp/Cntr=0.3,0.1

Type RM Length L Ch R = 1,15723,625,625,625
BEGIN DESCRIPTION:
UNT0016 IN CHRS 24.0
END DESCRIPTION:
XS GIS Cut Line= 6
      3410875.39     10616690.57      3410108.06     10616152.40
      3409663.62     10615725.32      3409378.90     10615582.96
      3408524.73     10615485.73      3407840.72     10615162.82
#Sta/Elev= 30
  3218.3  559.89  3515.3  555.09  4116.7  538.75  4326.1  531.93  4373.4  533.41
  4413.8  534.47  4478.0  529.05  4656.8  524.09  4684.6  527.55  4715.6  528.07
  4828.1  527.15  4884.4  524.57  4906.8  525.91  4968.3  526.12  4984.6  524.86
  4993.2  522.44  4996.0  521.94  4999.2  522.44  5005.2  523.32  5013.0  525.45
  5035.4  524.83  5080.1  527.44  5168.0  527.06  5328.0  528.93  6139.2  545.20
  6222.9  548.16  6258.6  547.91  6491.9  554.39  6628.5  561.33  6733.1  564.53
#Mann=5,-1,0
  3218.3    0.05       0  4373.4    0.16       0  4993.2    0.07       0
  4999.2    0.16       0  5005.2    0.05       0
Bank Sta=4993.2,4999.2
Exp/Cntr=0.3,0.1

Type RM Length L Ch R = 1,15098,942,942,942
BEGIN DESCRIPTION:
UNT0016 IN CHRS 23.0
END DESCRIPTION:
XS GIS Cut Line= 3
      3411013.78     10616463.18      3410163.06     10615456.20
      3408487.70     10614440.56
#Sta/Elev= 30
  2998.0  557.24  3290.9  554.51  3426.1  550.97  3844.7  543.93  3922.7  540.37
  3937.0  541.20  3957.9  539.71  4277.7  532.11  4435.6  530.79  4757.5  525.95
  4916.5  525.81  4937.8  523.85  4983.9  524.40  4993.0  520.91  4995.7  520.41
  4999.0  520.91  5005.6  523.17  5011.5  522.41  5032.8  523.85  5048.3  523.01
  5085.1  525.91  5186.0  525.39  5455.5  529.94  5746.4  538.32  5841.4  542.08
  5893.7  545.52  5915.0  545.11  6031.4  552.62  6118.2  556.89  6275.4  561.34
#Mann=3,-1,0
  2998.0    0.05       0  4993.0   0.035       0  4999.0    0.05       0
Bank Sta=4993,4999
Exp/Cntr=0.3,0.1

Type RM Length L Ch R = 1,14156,789,789,789
BEGIN DESCRIPTION:
UNT0016 IN CHRS 21.0
END DESCRIPTION:
XS GIS Cut Line= 3
      3410692.08     10615591.62      3409692.11     10614391.64
      3408892.14     10614191.65
#Sta/Elev= 30
  3465.0  545.58  3599.7  542.74  3614.0  542.01  3634.8  542.71  3657.0  541.20
  3735.1  540.07  3926.4  535.38  4082.6  532.55  4337.8  529.53  4551.2  525.90
  4878.0  523.15  4913.1  524.02  4984.7  521.33  4991.2  520.08  4996.0  518.38
  4998.8  517.88  5002.0  518.38  5013.3  521.30  5023.8  522.43  5050.2  522.01
  5150.7  522.94  5243.5  525.51  5315.6  526.53  5462.5  531.50  5627.4  538.25
  5645.5  539.98  5697.0  542.59  5709.9  544.33  5738.3  544.52  5851.6  551.29
#Mann=3,-1,0
  3465.0    0.05       0  4996.0   0.035       0  5002.0    0.05       0
Bank Sta=4996,5002
Exp/Cntr=0.3,0.1

Type RM Length L Ch R = 1,13367,571,571,571
BEGIN DESCRIPTION:
UNT0016 IN CHRS 20.1
END DESCRIPTION:
XS GIS Cut Line= 3
      3411281.78     10614472.31      3410287.02     10613784.84
      3408766.63     10613571.36
#Sta/Elev= 30
  3341.2  544.61  3370.0  543.17  3390.9  540.24  3441.6  542.10  3477.4  541.69
  3507.2  540.54  3931.0  533.87  4089.1  529.83  4361.9  528.11  4656.3  522.99
  4959.3  521.58  4989.6  519.69  4996.7  517.50  4999.4  517.00  5002.7  517.50
  5019.9  519.64  5037.9  520.47  5131.0  520.70  5256.9  523.21  5343.0  526.09
  5444.0  531.61  5565.2  536.56  5585.4  538.55  5618.4  539.64  5646.0  541.97
  5689.7  543.52  5787.3  549.58  5837.8  551.39  5898.4  553.45  6085.7  556.27
#Mann=3,-1,0
  3341.2    0.05       0  4996.7   0.035       0  5002.7    0.05       0
Bank Sta=4996.7,5002.7
Exp/Cntr=0.3,0.1

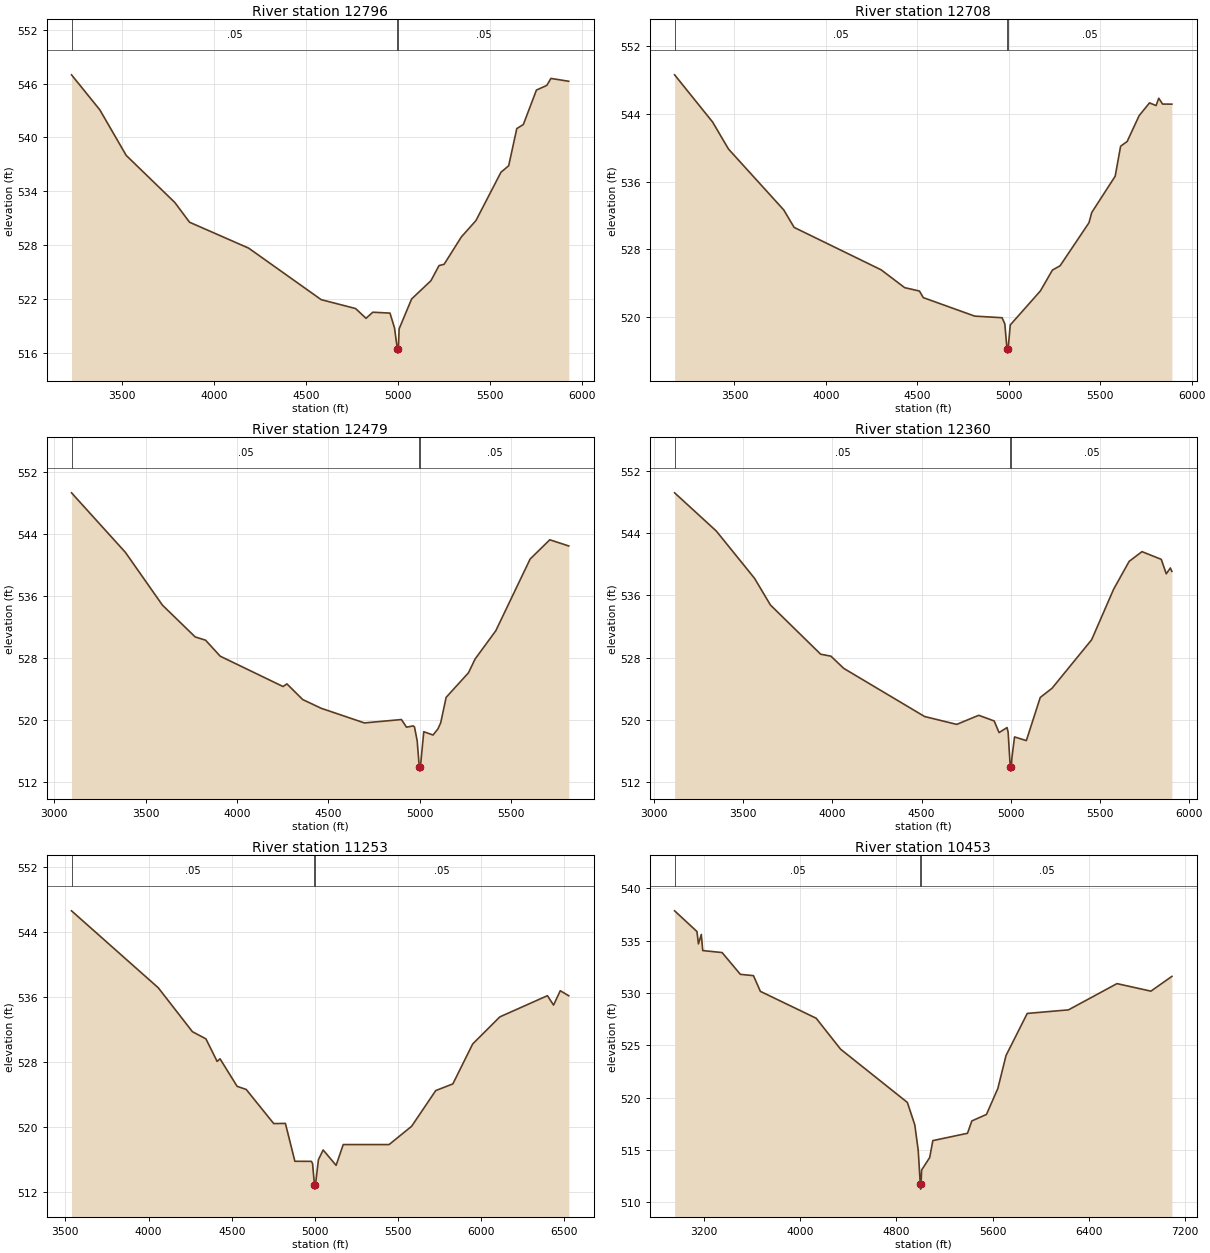
Type RM Length L Ch R = 1,12796,88,88,88
BEGIN DESCRIPTION:
UNT0016 IN CHRS 20.0
END DESCRIPTION:
XS GIS Cut Line= 4
      3411297.47     10614170.28      3409912.02     10613185.88
      3409719.31     10613112.96      3409073.49     10612644.22
#Sta/Elev= 30
  3225.7  546.97  3379.5  543.07  3523.0  537.99  3787.4  532.74  3867.4  530.54
  4189.1  527.65  4583.2  521.91  4770.2  520.92  4827.0  519.83  4863.8  520.51
  4957.2  520.41  4981.8  518.76  4997.0  516.45  4999.8  515.95  5003.0  516.45
  5006.6  518.64  5074.9  521.99  5179.8  524.02  5223.9  525.71  5251.4  525.85
  5345.2  528.90  5424.4  530.72  5560.3  536.10  5602.6  536.84  5646.7  540.98
  5682.3  541.43  5753.4  545.27  5809.8  545.79  5832.2  546.57  5929.3  546.25
#Mann=3,-1,0
  3225.7    0.05       0  4997.0   0.035       0  5003.0    0.05       0
Bank Sta=4997,5003
Exp/Cntr=0.3,0.1

Type RM Length L Ch R = 1,12708,229,229,229
BEGIN DESCRIPTION:
UNT0016 IN CHRS 19.0
END DESCRIPTION:
XS GIS Cut Line= 3
      3411370.37     10614102.56      3409604.73     10612899.42
      3409126.71     10612566.89
#Sta/Elev= 30
  3172.9  548.63  3380.7  543.04  3467.4  539.85  3769.6  532.64  3826.5  530.57
  4302.2  525.55  4430.9  523.44  4511.6  523.04  4532.6  522.26  4813.8  520.07
  4963.5  519.88  4978.5  519.15  4990.4  516.19  4993.1  515.69  4996.4  516.19
  5008.3  519.03  5172.9  523.05  5238.7  525.52  5280.7  526.03  5438.8  531.13
  5453.6  532.33  5581.9  536.63  5611.6  540.18  5647.4  540.74  5712.9  543.80
  5769.6  545.31  5805.4  544.99  5820.2  545.86  5841.1  545.17  5891.8  545.16
#Mann=3,-1,0
  3172.9    0.05       0  4990.4   0.035       0  4996.4    0.05       0
Bank Sta=4990.4,4996.4
Exp/Cntr=0.3,0.1

Type RM Length L Ch R = 1,12479,119,119,119
BEGIN DESCRIPTION:
UNT0016 IN CHRS 16.0
END DESCRIPTION:
XS GIS Cut Line= 2
      3411474.51     10613930.66      3409229.72     10612389.00
#Sta/Elev= 30
  3094.2  549.32  3389.1  541.64  3592.2  534.82  3771.5  530.72  3828.3  530.30
  3908.8  528.23  4252.6  524.32  4273.8  524.66  4360.1  522.64  4461.7  521.51
  4698.4  519.62  4900.8  520.06  4928.9  519.07  4965.3  519.24  4972.5  519.10
  4987.4  517.29  4998.7  513.90  5001.5  513.40  5004.7  513.90  5023.3  518.49
  5074.1  518.06  5101.1  518.86  5116.0  519.64  5145.8  522.92  5268.3  526.10
  5304.1  527.86  5417.8  531.52  5605.9  540.78  5713.5  543.26  5817.4  542.46
#Mann=3,-1,0
  3094.2    0.05       0  4998.7    0.03       0  5004.7    0.05       0
Bank Sta=4998.7,5004.7
Exp/Cntr=0.3,0.1

Type RM Length L Ch R = 1,12360,1107,1107,1107
BEGIN DESCRIPTION:
UNT0016 IN CHRS 16.1
END DESCRIPTION:
XS GIS Cut Line= 2
      3411552.64     10613816.09      3409236.01     10612264.72
#Sta/Elev= 30
  3115.5  549.17  3349.5  544.26  3563.8  538.19  3652.7  534.77  3934.5  528.45
  3991.9  528.20  4064.0  526.63  4517.3  520.45  4697.4  519.44  4820.5  520.61
  4907.5  519.88  4934.6  518.39  4979.6  519.03  4985.6  518.43  4997.6  513.94
  5000.4  513.44  5003.6  513.94  5006.6  515.13  5021.6  517.83  5087.7  517.36
  5165.7  522.90  5231.8  524.08  5453.9  530.31  5577.0  536.79  5664.1  540.37
  5736.1  541.62  5844.2  540.63  5872.2  538.77  5895.2  539.52  5903.6  539.08
#Mann=3,-1,0
  3115.5    0.05       0  4997.6    0.03       0  5003.6    0.05       0
Bank Sta=4997.6,5003.6
Exp/Cntr=0.3,0.1

Type RM Length L Ch R = 1,11253,800,800,800
BEGIN DESCRIPTION:
UNT0016 IN CHRS 20.2
END DESCRIPTION:
XS GIS Cut Line= 4
      3412005.78     10612842.14      3410912.02     10612336.92
      3410495.35     10611977.54      3409271.39     10612144.21
#Sta/Elev= 30
  3536.8  546.58  4058.6  537.13  4263.8  531.74  4345.0  530.86  4412.5  528.09
  4429.9  528.41  4532.7  525.03  4587.3  524.65  4752.7  520.46  4823.0  520.48
  4880.0  515.83  4979.2  515.82  4986.4  515.55  4997.7  512.91  5000.4  512.41
  5003.7  512.91  5021.5  516.02  5050.0  517.22  5127.9  515.33  5170.7  517.88
  5446.5  517.88  5582.2  520.13  5727.0  524.51  5830.0  525.33  5949.1  530.23
  6112.6  533.56  6398.6  536.16  6435.6  535.01  6476.0  536.77  6527.1  536.15
#Mann=3,-1,0
  3536.8    0.05       0  4997.7    0.03       0  5003.7    0.05       0
Bank Sta=4997.7,5003.7
Exp/Cntr=0.3,0.1

Type RM Length L Ch R = 1,10453,1272,1272,1272
BEGIN DESCRIPTION:
UNT0016 IN CHRS 13.0
END DESCRIPTION:
XS GIS Cut Line= 4
      3412689.08     10612539.52      3411274.17     10611636.75
      3410249.87     10611471.82      3408921.72     10611966.62
#Sta/Elev= 30
  2957.1  537.85  3142.9  535.87  3155.2  534.69  3178.9  535.59  3191.1  534.05
  3351.9  533.86  3503.4  531.78  3612.5  531.65  3670.0  530.15  4133.8  527.58
  4336.8  524.62  4891.8  519.53  4953.7  517.38  4982.0  514.95  4999.2  511.74
  5002.0  511.24  5005.2  511.74  5010.4  513.07  5077.3  514.26  5103.5  515.88
  5391.6  516.58  5427.6  517.76  5549.2  518.38  5644.0  520.87  5711.7  524.01
  5888.3  528.04  6230.9  528.38  6634.2  530.89  6916.1  530.17  7090.3  531.58
#Mann=3,-1,0
  2957.1    0.05       0  4999.2   0.035       0  5005.2    0.05       0
Bank Sta=4999.2,5005.2
Exp/Cntr=0.3,0.1

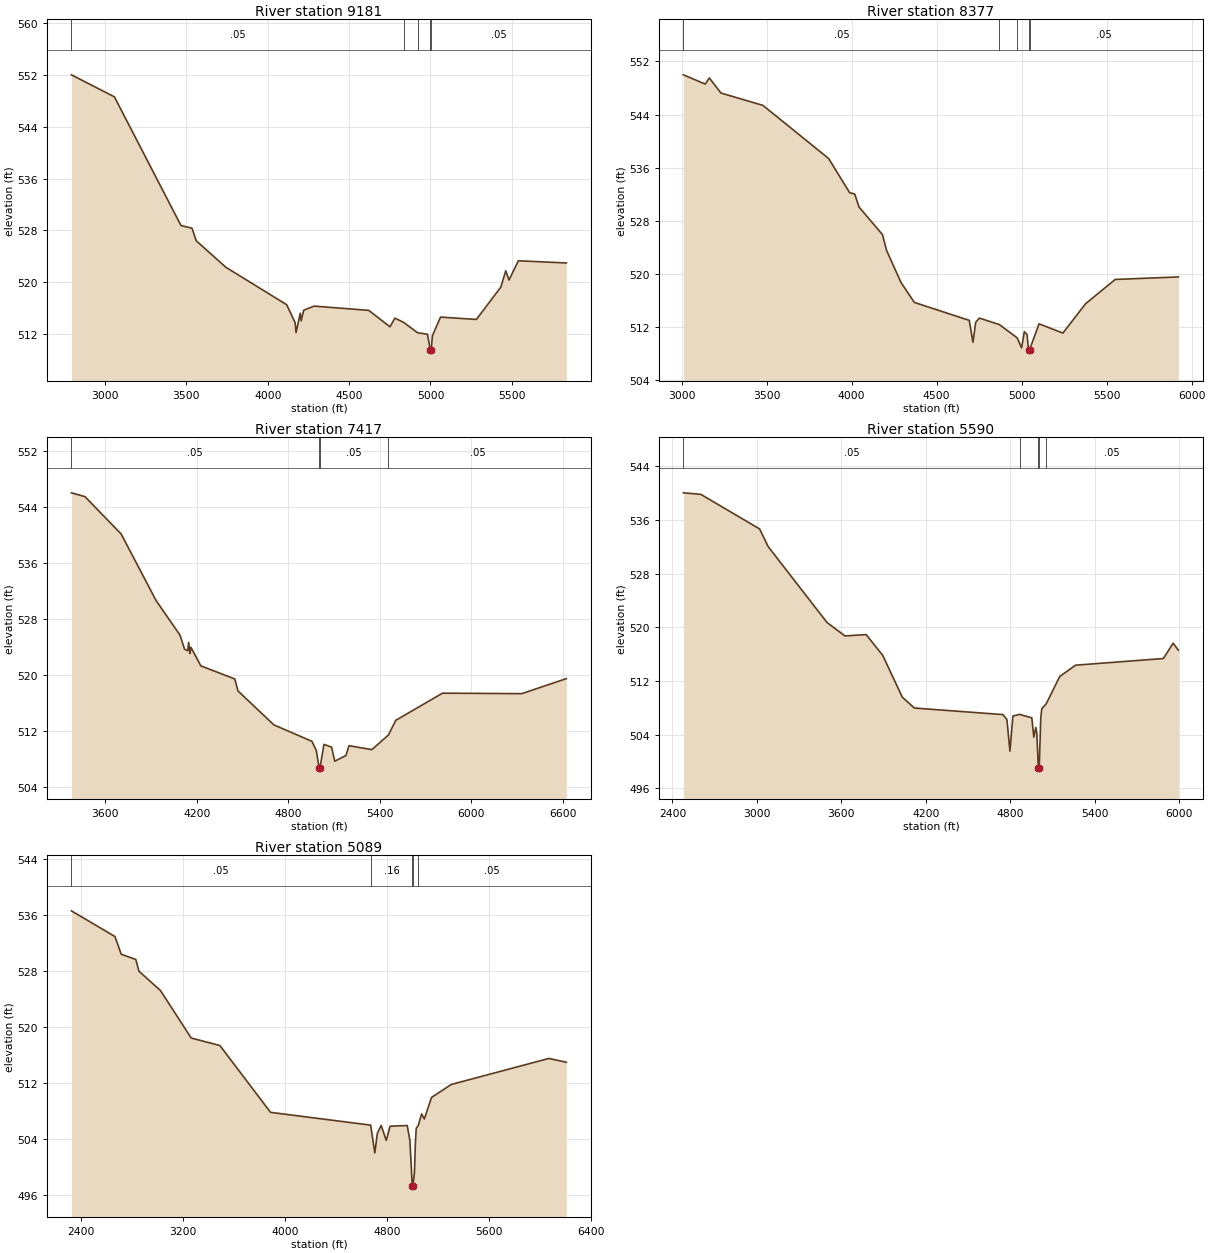
Type RM Length L Ch R = 1,9181,804,804,804
BEGIN DESCRIPTION:
UNT0016 IN CHRS 11.0
END DESCRIPTION:
XS GIS Cut Line= 3
      3413131.80     10611176.68      3411621.39     10610655.85
      3410180.39     10610569.04
#Sta/Elev= 30
  2793.6  552.05  3057.7  548.65  3466.8  528.75  3534.5  528.34  3560.4  526.40
  3742.3  522.30  4116.8  516.50  4168.4  513.72  4173.9  512.19  4199.8  515.20
  4205.1  514.02  4221.3  515.66  4284.8  516.29  4621.0  515.63  4751.2  513.09
  4781.3  514.43  4835.1  513.77  4921.8  512.16  4981.6  511.95  4998.7  509.52
  5001.4  509.02  5004.7  509.52  5011.7  511.69  5061.8  514.59  5282.2  514.23
  5432.5  519.24  5462.5  521.75  5482.5  520.32  5539.9  523.30  5834.9  522.96
#Mann=5,-1,0
  2793.6    0.05       0  4835.1    0.16       0  4921.8    0.05       0
  4998.7   0.035       0  5004.7    0.05       0
Bank Sta=4998.7,5004.7
Exp/Cntr=0.3,0.1

Type RM Length L Ch R = 1,8377,960,960,960
BEGIN DESCRIPTION:
UNT0016 IN CHRS 8.0
END DESCRIPTION:
XS GIS Cut Line= 3
      3413157.87     10610742.67      3411847.09     10610230.50
      3410536.72     10609492.88
#Sta/Elev= 30
  3010.8  549.98  3138.9  548.59  3163.3  549.51  3231.7  547.24  3478.6  545.38
  3865.2  537.38  3988.8  532.23  4018.7  532.04  4043.2  530.10  4181.6  525.93
  4206.1  523.53  4290.3  518.74  4369.1  515.72  4692.2  513.02  4713.9  509.71
  4729.8  512.72  4751.5  513.36  4868.3  512.40  4973.6  510.40  5000.0  508.89
  5016.0  511.31  5031.9  510.90  5040.5  508.59  5043.2  508.09  5046.5  508.59
  5102.6  512.50  5242.9  511.11  5376.3  515.53  5550.7  519.18  5921.8  519.56
#Mann=5,-1,0
  3010.8    0.05       0  4868.3     0.1       0  4973.6    0.05       0
  5040.5   0.035       0  5046.5    0.05       0
Bank Sta=5040.5,5046.5
Exp/Cntr=0.3,0.1

Type RM Length L Ch R = 1,7417,1827,1827,1827
BEGIN DESCRIPTION:
UNT0016 IN CHRS 7.0
END DESCRIPTION:
XS GIS Cut Line= 4
      3413288.04     10610239.17      3412359.24     10609579.46
      3411456.46     10608893.70      3410492.97     10609032.58
#Sta/Elev= 30
  3377.0  546.02  3465.9  545.48  3703.2  540.14  3932.0  530.64  4089.5  525.68
  4119.0  523.68  4139.9  523.45  4146.0  524.65  4154.7  523.06  4160.8  523.95
  4226.0  521.29  4448.7  519.42  4469.6  517.71  4705.0  512.86  4954.6  510.51
  4983.7  509.17  5001.5  506.75  5004.3  506.25  5007.5  506.75  5033.6  510.07
  5083.5  509.68  5104.3  507.67  5177.1  508.47  5197.9  509.89  5347.6  509.32
  5456.0  511.40  5504.7  513.51  5810.9  517.39  6331.3  517.32  6623.4  519.47
#Mann=4,-1,0
  3377.0    0.05       0  5001.5   0.035       0  5007.5    0.05       0
  5456.0    0.05       0
Bank Sta=5001.5,5007.5
Exp/Cntr=0.3,0.1

Type RM Length L Ch R = 1,5590,501,501,501
BEGIN DESCRIPTION:
UNT0016 IN CHRS 1.0
END DESCRIPTION:
XS GIS Cut Line= 4
      3413491.36     10610103.51      3412692.76     10608028.88
      3412267.41     10607603.54      3411598.98     10607785.84
#Sta/Elev= 30
  2477.8  540.04  2602.0  539.81  3019.7  534.65  3079.9  532.03  3497.8  520.72
  3626.0  518.70  3776.4  518.90  3894.2  515.81  4033.5  509.57  4119.2  507.95
  4748.8  506.97  4777.1  506.22  4798.3  501.52  4819.5  506.75  4866.4  507.00
  4953.9  506.49  4968.0  503.61  4982.2  505.05  4989.2  504.28  5000.4  499.04
  5003.1  498.54  5006.4  499.04  5017.5  506.46  5024.6  507.84  5056.6  508.60
  5151.9  512.64  5265.0  514.34  5888.9  515.33  5958.0  517.62  5995.2  516.58
#Mann=5,-1,0
  2477.8    0.05       0  4866.4    0.16       0  5000.4    0.07       0
  5006.4    0.16       0  5056.6    0.05       0
Bank Sta=5000.4,5006.4
Exp/Cntr=0.3,0.1

Type RM Length L Ch R = 1,5089,0,0,0
BEGIN DESCRIPTION:
UNT0016 IN CHRS 1.1
END DESCRIPTION:
XS GIS Cut Line= 5
      3413548.84     10609939.42      3412772.79     10607928.99
      3412778.00     10607522.74      3412543.62     10607293.58
      3411571.58     10607517.10
#Sta/Elev= 30
  2322.1  536.59  2664.1  532.92  2713.3  530.40  2827.8  529.65  2852.4  527.98
  3021.5  525.22  3263.0  518.44  3488.0  517.38  3886.0  507.84  4672.1  506.02
  4704.5  502.06  4724.5  504.85  4754.5  505.98  4794.5  503.84  4824.5  505.87
  4959.1  505.96  4980.2  503.80  4998.5  497.39  5001.3  496.89  5004.5  497.39
  5015.7  499.26  5022.7  503.25  5029.8  505.55  5045.6  505.97  5072.3  507.62
  5093.4  506.90  5150.0  509.97  5305.1  511.82  6071.1  515.53  6208.6  514.99
#Mann=5,-1,0
  2322.1    0.05       0  4672.1    0.16       0  4998.5    0.07       0
  5004.5    0.16       0  5045.6    0.05       0
Bank Sta=4998.5,5004.5
Exp/Cntr=0.3,0.1

Chan Stop Cuts=-1