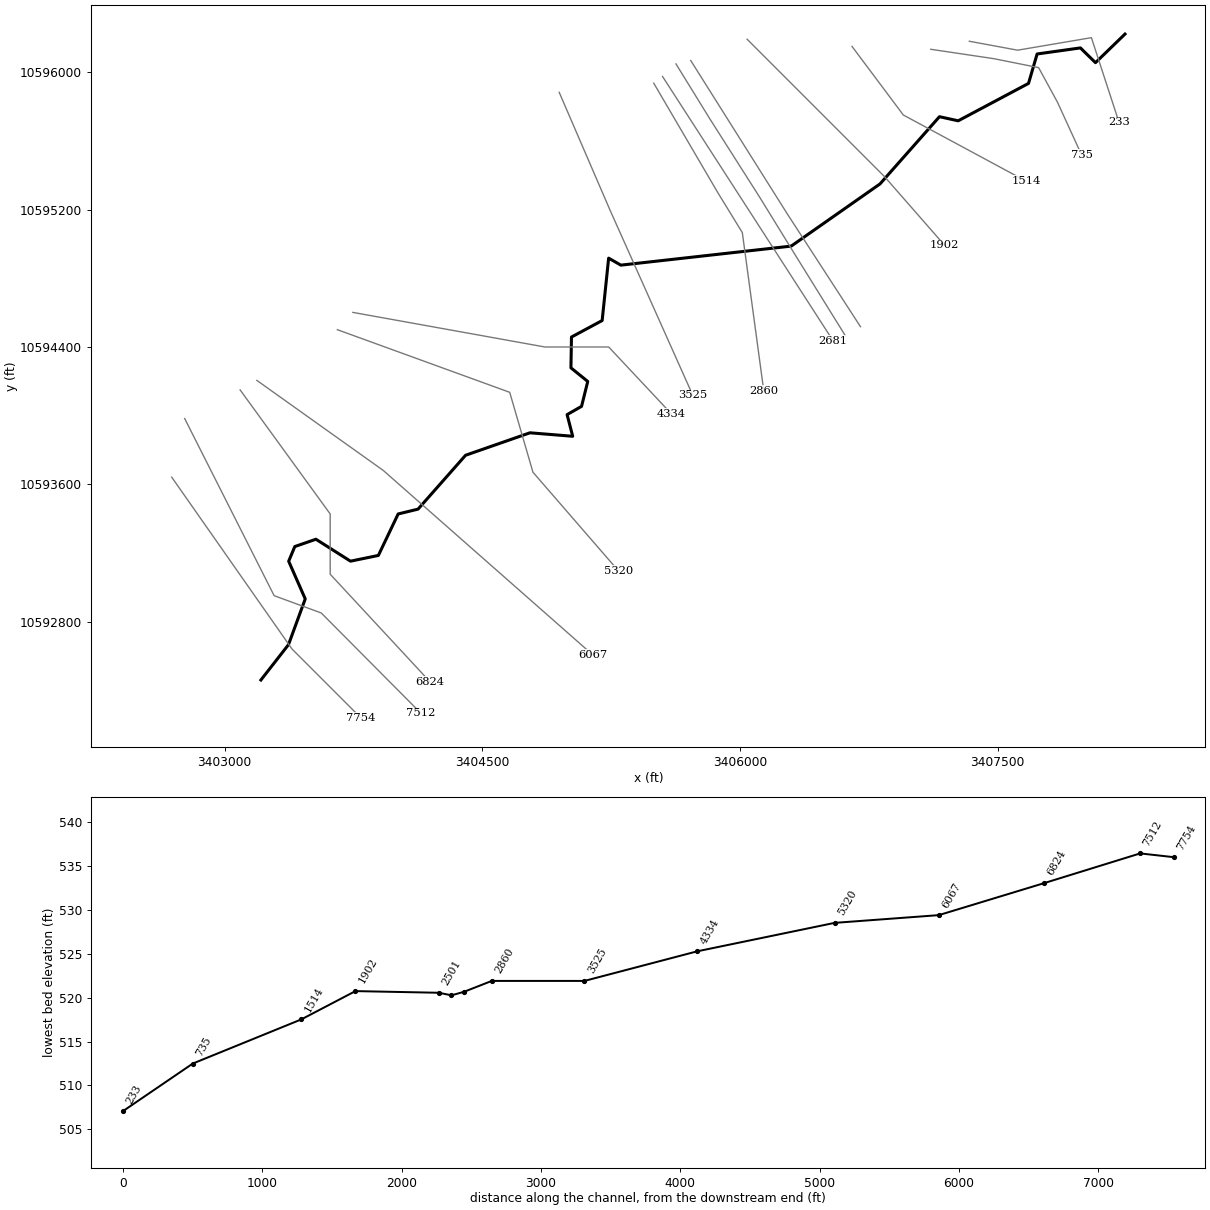
--- UNT0019 IN CHRS.prj (project) ---

Proj Title=UNT0019 IN CHRS Base Level Engineering
Current Plan=p01
Default Exp/Contr=0.3,0.1
English Units
Geom File=g01
Flow File=f01
Plan File=p01
Y Axis Title=Elevation
X Axis Title(PF)=Main Channel Distance
X Axis Title(XS)=Station
BEGIN DESCRIPTION:
UNT0019 IN CHRS
END DESCRIPTION:
DSS Export Rating Curves= 0
DSS Export Rating Curve Sorted= 0
DSS Export Volume Flow Curves= 0
DXF OffsetX= 0
DXF OffsetY= 0
DXF ScaleX= 1
DXF ScaleY= 10

--- UNT0019 IN CHRS.p01 (plan) ---

Plan Title=Multiple Run
Short Identifier=Multiple
Geom File=g01
Flow File=f01
Subcritical Flow
K Sum by GR= 0
Std Step Tol= 0.01
Critical Tol= 0.01
Num of Std Step Trials= 20
Max Error Tol= 0.3
Flow Tol Ratio= 0.001
Split Flow NTrial= 30
Split Flow Tol= 0.02
Split Flow Ratio= 0.02
Log Output Level= 0
Friction Slope Method= 1
Unsteady Friction Slope Method= 2
Unsteady Bridges Friction Slope Method= 1
Parabolic Critical Depth
Global Vel Dist=  1 , 1 , 1
Global Log Level= 0
CheckData=True
Encroach Param= -1, 0, 0, 0
BEGIN DESCRIPTION:
Multiple Run
END DESCRIPTION:

--- UNT0019 IN CHRS.f01 (steady flow) ---

Flow Title=Multiple
Number of Profiles=7
Profile Names=10-year,25-year,50-year,1pct_min,100-year,1pct_plu,500-year
River Rch & RM= UNT0019 IN CHRS,Reach-1,7754
     449     568     656     552     746    1009     963
River Rch & RM= UNT0019 IN CHRS,Reach-1,5320
     549     702     816     689     932    1261    1216
River Rch & RM= UNT0019 IN CHRS,Reach-1,233
    1273    1688    2011    1737    2349    3177    3203
Boundary for River Rch & Prof#=UNT0019 IN CHRS,Reach-1,1
Up Type=0
Dn Type=3
Dn Slope=0.005
Boundary for River Rch & Prof#=UNT0019 IN CHRS,Reach-1,2
Up Type=0
Dn Type=3
Dn Slope=0.005
Boundary for River Rch & Prof#=UNT0019 IN CHRS,Reach-1,3
Up Type=0
Dn Type=3
Dn Slope=0.005
Boundary for River Rch & Prof#=UNT0019 IN CHRS,Reach-1,4
Up Type=0
Dn Type=3
Dn Slope=0.005
Boundary for River Rch & Prof#=UNT0019 IN CHRS,Reach-1,5
Up Type=0
Dn Type=3
Dn Slope=0.005
Boundary for River Rch & Prof#=UNT0019 IN CHRS,Reach-1,6
Up Type=0
Dn Type=3
Dn Slope=0.005
Boundary for River Rch & Prof#=UNT0019 IN CHRS,Reach-1,7
Up Type=0
Dn Type=3
Dn Slope=0.005

--- UNT0019 IN CHRS.g01 (geometry) ---

Geom Title=Existing Conditions
Program Version=4.10

River Reach=UNT0019 IN CHRS ,Reach-1
Reach XY= 30
      3403211.32     10592460.86      3403371.95     10592666.65
      3403469.43     10592932.99      3403373.03     10593152.31
      3403408.59     10593237.75      3403531.58     10593280.44
       3403732.9     10593152.69      3403895.18      10593186.1
      3404010.39     10593427.55      3404126.25     10593455.77
      3404403.02     10593769.32      3404777.87     10593900.13
      3405026.64     10593879.87        3404994.     10594005.97
      3405078.21     10594054.08      3405114.23     10594199.08
      3405016.37     10594278.31      3405019.48     10594457.62
      3405198.15     10594553.75      3405235.89       10594917.
      3405307.02     10594876.25      3406298.82     10594987.08
      3406815.75     10595349.06      3407161.95     10595740.55
      3407270.94     10595716.61      3407680.47     10595934.36
      3407730.57     10596105.69      3407982.62     10596141.02
      3408070.34     10596055.04      3408242.11     10596221.64

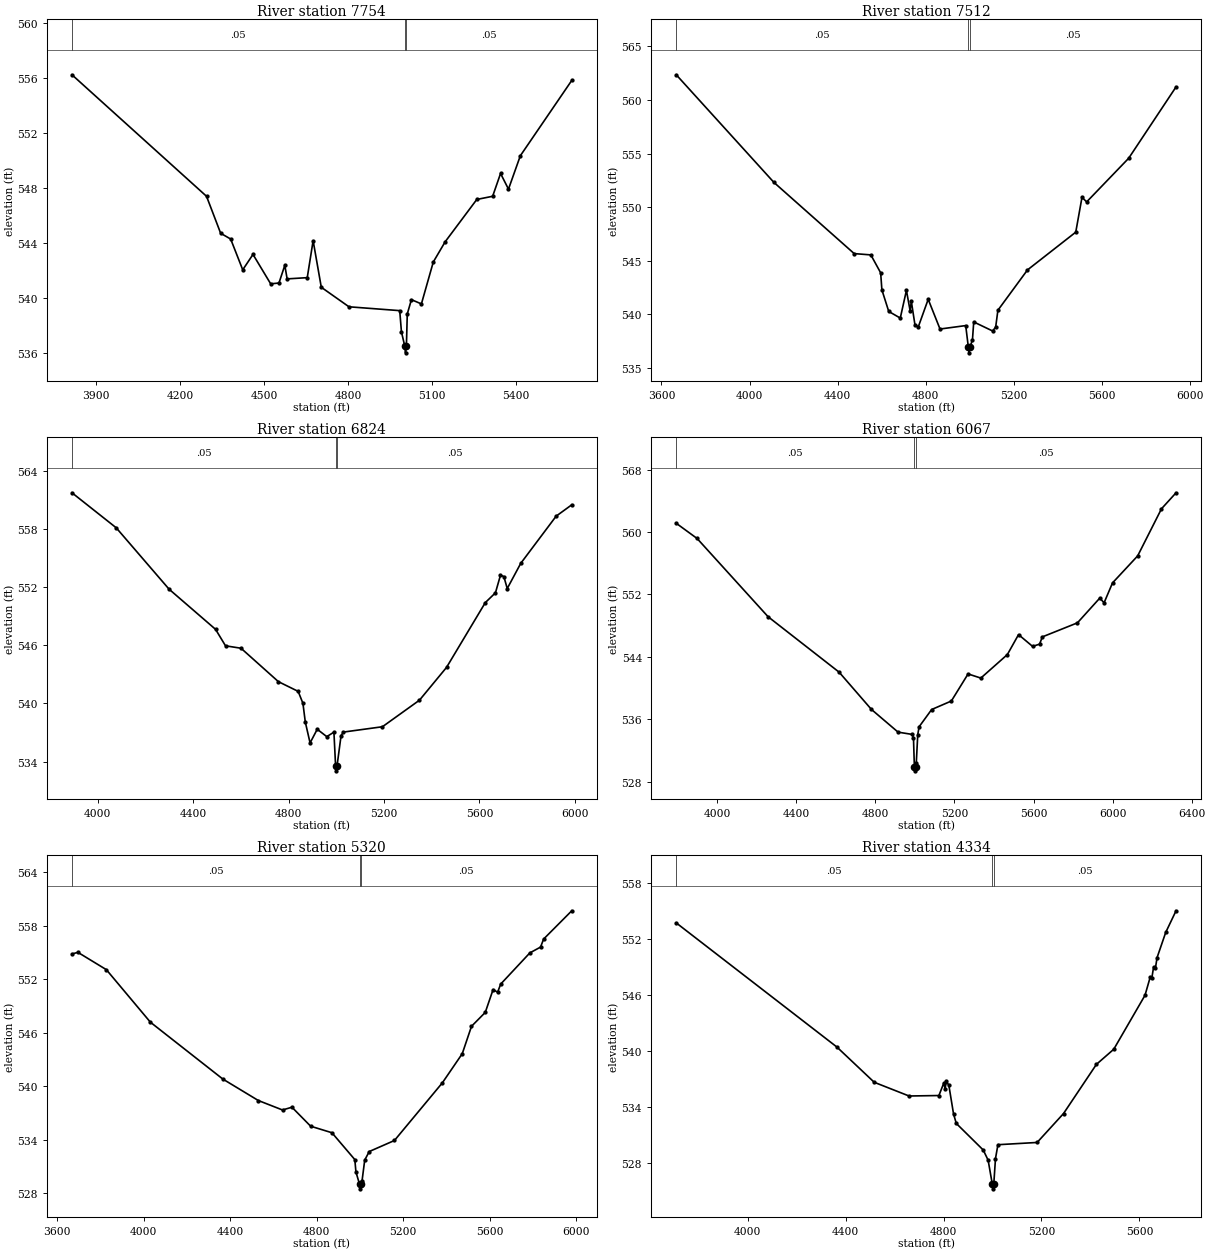
Type RM Length L Ch R = 1 ,7754    ,242,242,242
BEGIN DESCRIPTION:
UNT0019 IN CHRS 16.0
END DESCRIPTION:
XS GIS Cut Line= 3
       3402692.1     10593641.65      3403392.11     10592641.64
      3403792.07     10592241.68
#Sta/Elev= 30
  3812.8  556.22  4293.7  547.38  4344.2  544.69    4380  544.27  4423.1  542.03
  4459.8  543.15    4523  541.01  4552.6  541.07  4573.5  542.36  4581.8  541.37
  4653.7  541.46  4674.7  544.15  4703.9  540.76  4802.8  539.34  4984.2  539.06
  4990.3  537.52  5002.1  536.49  5004.9  535.99  5008.1  536.49  5011.2  538.82
    5026  539.86  5061.7  539.55  5104.2   542.6  5146.6  544.07  5259.7  547.15
  5316.3  547.38  5344.6  549.04  5372.9   547.9  5415.3  550.33  5599.1  555.81
#Mann= 3 ,-1 , 0
  3812.8     .05       0  5002.1     .03       0  5008.1     .05       0
Bank Sta=5002.1,5008.1
XS Rating Curve= 0 ,0
Exp/Cntr=0.3,0.1

Type RM Length L Ch R = 1 ,7512    ,688,688,688
BEGIN DESCRIPTION:
UNT0019 IN CHRS 15.0
END DESCRIPTION:
XS GIS Cut Line= 4
      3402767.46      10593983.1       3403288.3     10592951.84
       3403562.6     10592851.15      3404142.44     10592267.83
#Sta/Elev= 30
    3667  562.34  4110.5  552.31  4475.2  545.67  4550.8  545.55  4595.4  543.88
    4601  542.29  4632.1  540.28  4684.5  539.66  4712.4  542.24  4729.1  540.36
  4734.7  541.22  4751.4     539  4766.5  538.85  4811.3  541.41    4865  538.64
  4981.7  538.96  4993.8  536.92  4996.6  536.42  4999.8  536.92  5012.2   537.6
  5018.1   539.3  5103.6  538.46  5117.7  538.81  5127.9  540.39  5262.3  544.15
  5481.5  547.67  5509.8  550.92    5531  550.49  5721.9  554.56    5937  561.21
#Mann= 3 ,-1 , 0
    3667     .05       0  4993.8     .03       0  4999.8     .05       0
Bank Sta=4993.8,4999.8
XS Rating Curve= 0 ,0
Exp/Cntr=0.3,0.1

Type RM Length L Ch R = 1 ,6824    ,757,757,757
BEGIN DESCRIPTION:
UNT0019 IN CHRS 13.0
END DESCRIPTION:
XS GIS Cut Line= 4
      3403090.38     10594149.76      3403614.68     10593427.54
      3403614.68     10593076.84      3404194.53     10592451.86
#Sta/Elev= 30
  3891.7  561.73  4077.1  558.12    4299  551.78  4493.8  547.64  4535.5  545.94
  4600.5  545.69  4757.4  542.24  4840.1  541.24  4860.1  540.01  4870.1  538.07
  4890.1  535.92  4920.1  537.33  4960.1  536.57  4990.1  537.03  4997.1  533.54
  4999.8  533.04  5003.1  533.54  5020.1  536.68  5030.1  537.04  5193.5  537.59
  5348.8  540.33  5462.2  543.71  5624.9   550.4  5667.4  551.41  5688.4  553.22
  5702.6  553.09  5716.8  551.85  5773.5  554.45    5922  559.32  5987.4  560.49
#Mann= 3 ,-1 , 0
  3891.7     .05       0  4997.1     .03       0  5003.1     .05       0
Bank Sta=4997.1,5003.1
XS Rating Curve= 0 ,0
Exp/Cntr=0.3,0.1

Type RM Length L Ch R = 1 ,6067    ,747,747,747
BEGIN DESCRIPTION:
UNT0019 IN CHRS 12.0
END DESCRIPTION:
XS GIS Cut Line= 3
      3403187.62      10594205.3      3403923.71     10593681.01
      3405142.42     10592608.12
#Sta/Elev= 30
  3793.4  561.12  3898.9  559.17  4257.9  549.14  4616.9  542.04  4780.5  537.26
  4915.2  534.35  4986.3  534.06    4993  533.64  4997.6  529.89  5000.3  529.39
  5003.6  529.89  5007.2  530.39  5014.7  534.04  5021.5  535.04    5085  537.25
  5184.6  538.34  5269.1  541.81  5333.6  541.28  5467.7  544.29  5524.3  546.85
  5595.4  545.34  5630.6  545.63  5644.8  546.56  5822.2  548.36  5935.1  551.53
  5956.9  550.93  5999.6  553.48  6126.7  556.94  6247.2  562.98  6320.8  565.03
#Mann= 3 ,-1 , 0
  3793.4     .05       0  4997.6     .03       0  5003.6     .05       0
Bank Sta=4997.6,5003.6
XS Rating Curve= 0 ,0
Exp/Cntr=0.3,0.1

Type RM Length L Ch R = 1 ,5320    ,986,986,986
BEGIN DESCRIPTION:
UNT0019 IN CHRS 10.0
END DESCRIPTION:
XS GIS Cut Line= 4
      3403656.39     10594500.44      3404659.82     10594135.87
      3404795.24     10593670.59      3405291.75      10593097.7
#Sta/Elev= 30
  3668.9  554.84  3696.3  555.02  3827.8  553.08  4031.4  547.19  4366.6  540.81
  4530.4  538.41  4642.1  537.35  4685.7  537.66  4772.2  535.53  4870.5   534.8
  4976.3  531.79  4981.5  530.41  4998.3  529.01    5001  528.51  5004.3  529.01
  5009.8  529.41  5022.1  531.73  5042.9  532.69  5159.5  533.93  5380.9  540.39
    5473  543.66  5515.7  546.73  5579.4  548.29  5615.5  550.85  5636.4  550.55
  5650.6  551.46  5785.5  554.96  5834.9  555.61  5849.1  556.51  5979.2  559.68
#Mann= 3 ,-1 , 0
  3668.9     .05       0  4998.3     .03       0  5004.3     .05       0
Bank Sta=4998.3,5004.3
XS Rating Curve= 0 ,0
Exp/Cntr=0.3,0.1

Type RM Length L Ch R = 1 ,4334    ,809,809,809
BEGIN DESCRIPTION:
UNT0019 IN CHRS 9.0
END DESCRIPTION:
XS GIS Cut Line= 4
      3403746.65     10594601.14      3404864.68     10594399.76
      3405236.21     10594399.76      3405600.78     10594010.88
#Sta/Elev= 30
  3708.8  553.77  4364.6  540.47  4517.1  536.69  4659.3  535.22  4781.2  535.27
  4801.2  536.61  4806.3  535.99  4811.7  536.81  4821.9  536.35    4841  533.29
  4852.2  532.28  4962.2  529.43  4982.2  528.34  4999.2  525.77    5002  525.27
  5005.2  525.77  5012.2  528.52  5022.2     530  5182.2  530.24    5290  533.34
  5424.3  538.61  5495.1  540.23  5622.6  546.01  5643.6  547.93  5650.9  547.91
  5657.8  549.06  5665.1   548.9  5671.9  550.05  5707.2  552.75  5749.4  555.07
#Mann= 3 ,-1 , 0
  3708.8     .05       0  4999.2     .03       0  5005.2     .05       0
Bank Sta=4999.2,5005.2
XS Rating Curve= 0 ,0
Exp/Cntr=0.3,0.1

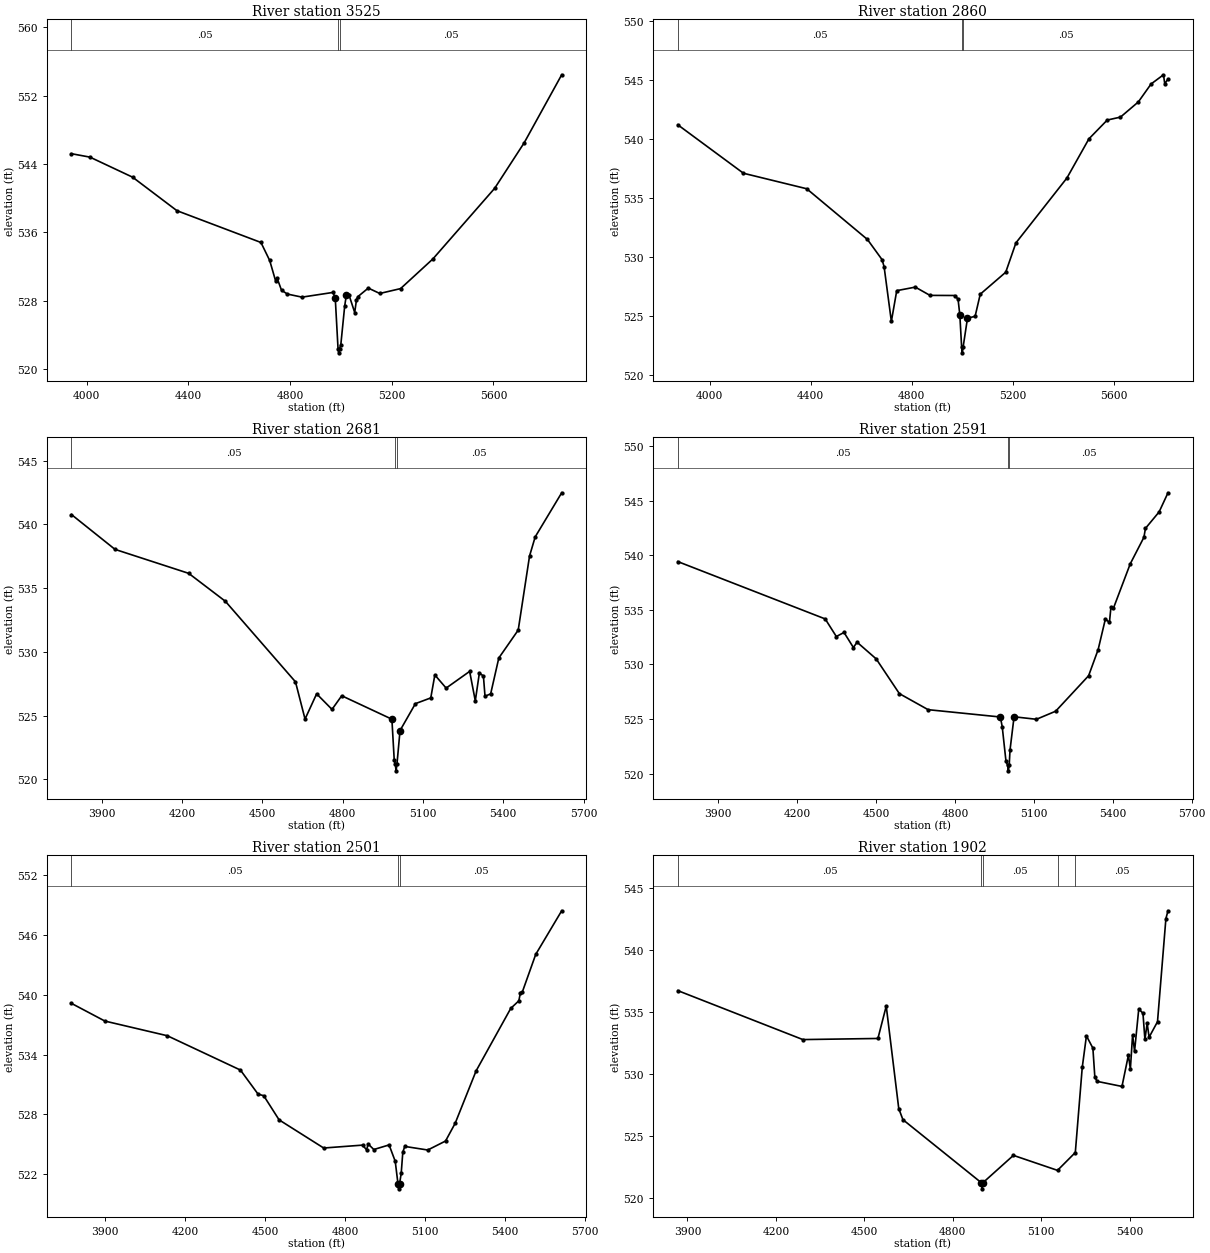
Type RM Length L Ch R = 1 ,3525    ,665,665,665
BEGIN DESCRIPTION:
UNT0019 IN CHRS 7.0
END DESCRIPTION:
XS GIS Cut Line= 3
        3404948.     10595882.43      3405243.16     10595198.37
      3405725.78     10594118.53
#Sta/Elev= 30
  3940.4  545.21    4013  544.81  4180.9  542.46  4355.1  538.54  4685.4  534.82
  4719.9  532.71  4743.1  530.32  4748.6  530.68  4766.3  529.23  4789.5  528.78
  4846.9  528.42  4968.4  528.97  4977.6  528.36  4988.6   522.4  4991.3   521.9
  4994.6   522.4  4999.5  522.83  5014.8  527.38  5021.4  528.67  5032.3  528.62
  5054.2  526.62  5061.2  528.13  5066.7  528.48  5107.6  529.48  5152.8  528.85
  5234.6  529.42  5361.6  532.89  5604.6  541.16  5720.7  546.49  5868.2  554.45
#Mann= 3 ,-1 , 0
  3940.4     .05       0  4988.6     .03       0  4994.6     .05       0
Bank Sta=4977.6,5021.4
XS Rating Curve= 0 ,0
Exp/Cntr=0.3,0.1

Type RM Length L Ch R = 1 ,2860    ,199,199,199
BEGIN DESCRIPTION:
UNT0019 IN CHRS 6.0
END DESCRIPTION:
XS GIS Cut Line= 4
      3405498.54     10595935.62      3405873.56     10595294.98
      3406014.18     10595065.81        3406139.     10594145.24
#Sta/Elev= 30
    3874  541.19  4133.9  537.09  4384.2  535.78  4624.6  531.49  4682.6  529.78
  4690.6  529.18  4719.3  524.56  4740.6  527.16  4814.1  527.46  4872.1  526.76
  4970.1  526.75  4983.3  526.44  4990.3   525.1  4997.4   522.4  5000.2   521.9
  5003.4   522.4  5020.6  524.83  5050.8  524.99  5071.1  526.86    5172  528.72
  5212.3   531.2  5414.2  536.69  5501.2     540  5573.7  541.59  5626.1  541.84
  5696.7  543.12  5747.2  544.64  5796.3  545.42  5801.4  544.66  5814.2  545.06
#Mann= 3 ,-1 , 0
    3874     .05       0  4997.4     .03       0  5003.4     .05       0
Bank Sta=4990.3,5020.6
XS Rating Curve= 0 ,0
Exp/Cntr=0.3,0.1

Type RM Length L Ch R = 1 ,2681    ,90,90,90
BEGIN DESCRIPTION:
UNT0019 IN CHRS 6.1
END DESCRIPTION:
XS GIS Cut Line= 2
      3405549.81     10595974.57      3406542.49     10594436.13
#Sta/Elev= 30
  3787.5  540.76  3950.1  538.03  4225.3  536.15  4362.2  533.96  4624.1  527.64
  4659.8  524.72  4703.1   526.7  4760.5  525.48  4796.8  526.55  4984.2  524.71
    4993  521.48    4997  521.16  4999.8  520.66    5003  521.16  5014.6  523.82
    5072  525.93  5129.4  526.38  5144.6  528.18  5186.8  527.15  5274.6  528.46
  5295.7  526.15  5310.9  528.33    5326   528.1    5332  526.51  5353.1   526.7
  5383.5  529.51    5456   531.7  5498.3  537.51  5519.4  539.01  5618.4  542.47
#Mann= 3 ,-1 , 0
  3787.5     .05       0    4997     .03       0    5003     .05       0
Bank Sta=4984.2,5014.6
XS Rating Curve= 0 ,0
Exp/Cntr=0.3,0.1

Type RM Length L Ch R = 1 ,2591    ,90,90,90
BEGIN DESCRIPTION:
UNT0019 IN CHRS 5.0
END DESCRIPTION:
XS GIS Cut Line= 5
      3405627.93     10596047.86      3405826.04     10595726.48
       3406114.4     10595273.03      3406319.11     10594940.65
       3406613.6     10594465.95
#Sta/Elev= 30
  3746.1  539.42  4306.6  534.17  4348.9  532.56  4378.2  532.93  4413.8  531.55
  4427.7  532.04  4500.5  530.51  4588.6  527.33  4697.9  525.86  4972.6  525.19
  4979.7   524.3  4993.9  521.15  5000.2  520.76    5003  520.26  5006.2  520.76
  5009.3  522.16  5024.7  525.21  5109.7  524.98  5182.9  525.72  5308.2  528.97
  5344.4  531.36  5371.9  534.16  5387.3  533.85  5393.2  535.27  5402.7  535.16
  5466.4  539.21  5518.4  541.64  5524.3  542.46  5576.3  543.97    5610  545.72
#Mann= 3 ,-1 , 0
  3746.1     .05       0  5000.2     .04       0  5006.2     .05       0
Bank Sta=4972.6,5024.7
XS Rating Curve= 0 ,0
Exp/Cntr=0.3,0.1

Type RM Length L Ch R = 1 ,2501    ,599,599,599
BEGIN DESCRIPTION:
UNT0019 IN CHRS 5.1
END DESCRIPTION:
XS GIS Cut Line= 3
      3405713.76      10596067.7      3406275.09     10595176.18
      3406702.13     10594517.99
#Sta/Elev= 30
  3774.4  539.13  3899.7  537.36  4133.7  535.89  4407.9  532.45    4474  530.04
  4495.2  529.88  4552.9  527.46  4720.1  524.64  4865.7  524.93  4880.9  524.46
  4886.9  525.04    4908  524.49  4965.3  524.95  4988.3  523.31  4998.6  521.05
  5001.3  520.55  5004.6  521.05  5010.8  522.12  5016.7  524.22    5024   524.8
  5110.3  524.44  5176.9  525.34  5213.1  527.12  5291.6  532.37  5421.5  538.63
  5451.8  539.39  5457.7   540.2  5465.1  540.29  5515.1  544.04  5612.5  548.41
#Mann= 3 ,-1 , 0
  3774.4     .05       0  4998.6     .03       0  5004.6     .05       0
Bank Sta=4998.6,5004.6
XS Rating Curve= 0 ,0
Exp/Cntr=0.3,0.1

Type RM Length L Ch R = 1 ,1902    ,388,388,388
BEGIN DESCRIPTION:
UNT0019 IN CHRS 4.0
END DESCRIPTION:
XS GIS Cut Line= 3
      3406042.08     10596191.66      3406842.11     10595391.64
       3407192.1     10594991.65
#Sta/Elev= 30
  3867.1  536.73  4291.4  532.78    4546  532.87  4574.2  535.48  4616.7  527.21
  4630.8  526.32  4896.5  521.24  4899.3  520.74  4902.5  521.24  5005.6  523.44
  5155.2  522.23  5215.6  523.67  5239.1  530.53  5253.3  533.08  5275.2  532.09
  5281.8  529.77  5289.4  529.41  5373.9     529  5395.7  531.52  5402.4  530.41
  5409.9  533.16  5416.6  531.84  5430.8  535.25  5445.1   534.9  5451.7  532.79
  5459.3  534.09  5465.9  532.97  5494.4  534.22  5522.9  542.54    5530  543.17
#Mann= 5 ,-1 , 0
  3867.1     .05       0  4896.5     .03       0  4902.5     .05       0
  5155.2     .16       0  5215.6     .05       0
Bank Sta=4896.5,4902.5
XS Rating Curve= 0 ,0
Exp/Cntr=0.3,0.1

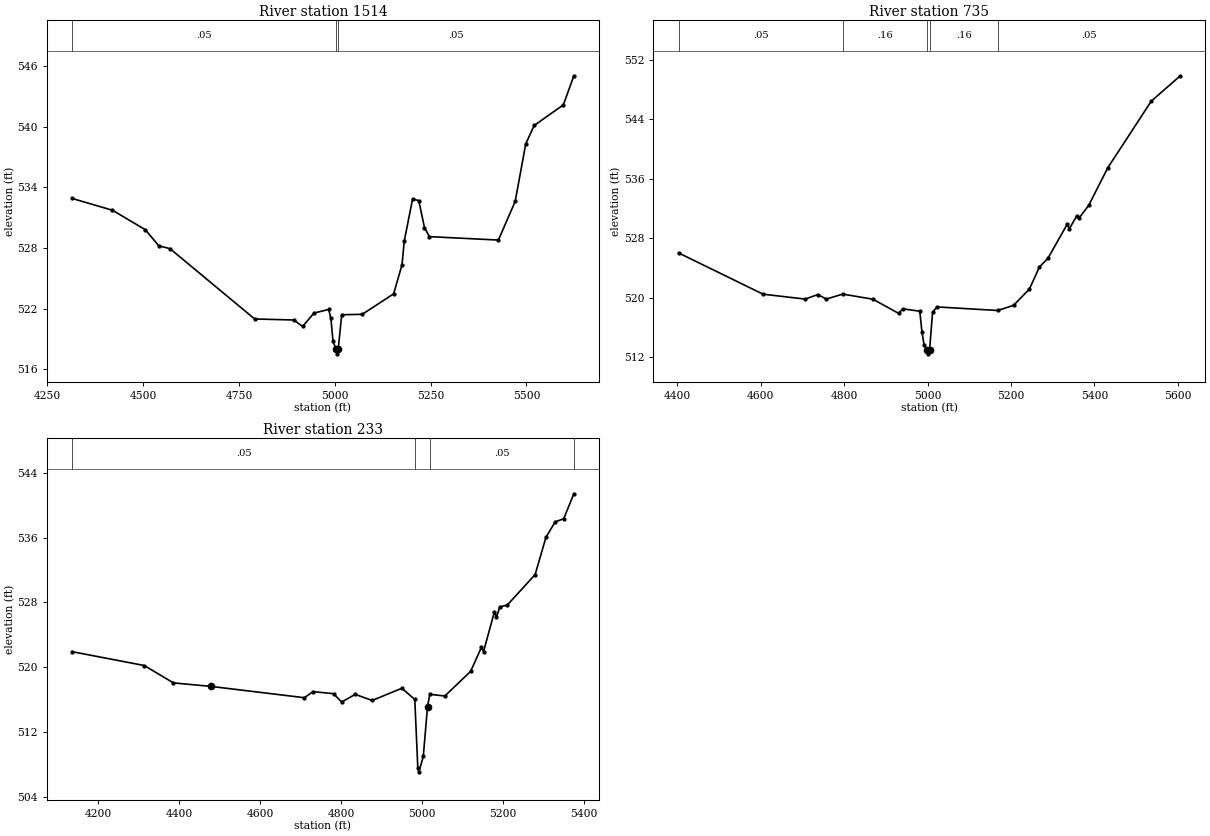
Type RM Length L Ch R = 1 ,1514    ,779,779,779
BEGIN DESCRIPTION:
UNT0019 IN CHRS 2.0
END DESCRIPTION:
XS GIS Cut Line= 3
       3406652.9     10596149.73      3406951.49     10595750.45
      3407665.28     10595365.84
#Sta/Elev= 30
  4314.2   532.9  4419.7  531.73  4505.1  529.81  4540.6  528.21  4569.7  527.93
  4790.7  520.97    4893  520.87  4915.7  520.23  4945.7  521.56  4983.8  521.91
  4989.5  521.04  4995.2  518.75  5002.7  518.02  5005.5  517.52  5008.7  518.02
  5017.9  521.39  5071.4  521.43  5153.3  523.46  5175.2  526.34  5180.9  528.65
  5202.8  532.86    5219  532.68  5233.8  530.01  5246.6  529.12  5426.7  528.78
  5470.5  532.61  5498.1  538.31    5520  540.12  5596.2  542.16  5623.6  545.04
#Mann= 3 ,-1 , 0
  4314.2     .05       0  5002.7     .03       0  5008.7     .05       0
Bank Sta=5002.7,5008.7
XS Rating Curve= 0 ,0
Exp/Cntr=0.3,0.1

Type RM Length L Ch R = 1 ,735     ,502,502,502
BEGIN DESCRIPTION:
UNT0019 IN CHRS 1.9
END DESCRIPTION:
XS GIS Cut Line= 5
      3407111.71     10596132.99      3407478.91      10596078.3
      3407739.33     10596026.22       3407848.7     10595825.69
      3407989.34     10595518.38
#Sta/Elev= 30
  4402.8  526.04  4605.4   520.5  4706.5  519.84  4736.8  520.45  4757.1  519.84
  4796.5  520.51  4869.1  519.82  4930.3  517.93  4940.5  518.53  4981.3  518.21
  4986.4  515.46  4991.5  513.71  4998.7  512.99  5001.4  512.49  5004.7  512.99
  5011.9  518.04  5022.1  518.79  5168.1  518.31    5206     519    5244  521.17
    5268  524.14  5288.6  525.32  5334.6  529.87  5340.1   529.3  5357.6     531
  5363.1  530.71  5386.2  532.41  5432.2  537.48  5536.4  546.42    5606  549.82
#Mann= 5 ,-1 , 0
  4402.8     .05       0  4796.5     .16       0  4998.7     .07       0
  5004.7     .16       0  5168.1     .05       0
Bank Sta=4998.7,5004.7
XS Rating Curve= 0 ,0
Exp/Cntr=0.3,0.1

Type RM Length L Ch R = 1 ,233     ,0,0,0
BEGIN DESCRIPTION:
UNT0019 IN CHRS 1.0
END DESCRIPTION:
XS GIS Cut Line= 4
      3407335.72     10596179.85      3407616.93     10596127.78
      3408046.62     10596200.69      3408207.46      10595707.8
#Sta/Elev= 30
  4134.9  521.91  4313.2   520.2  4385.5  518.05  4477.9  517.62    4709  516.22
  4730.4  516.97  4781.1  516.72  4801.4  515.69  4834.7  516.63  4876.8  515.88
  4950.1  517.39    4982     516  4989.5  507.56  4992.2  507.06    5003  508.96
  5013.5  515.12  5019.1  516.64  5056.3  516.43  5120.1  519.48  5146.7  522.44
    5152  521.93  5178.6   526.8  5183.9   526.2  5192.3  527.45  5210.5  527.66
  5279.5  531.44  5306.2  536.04  5329.1  537.95  5350.1  538.34  5375.2  541.42
#Mann= 4 ,-1 , 0
  4134.9     .05       0    4982    .035       0  5019.1     .05       0
  5375.2     .05       0
Bank Sta=4477.9,5013.5
XS Rating Curve= 0 ,0
Exp/Cntr=0.3,0.1

Chan Stop Cuts=-1
Use User Specified Reach Order=0
Composite Channel Slope=5