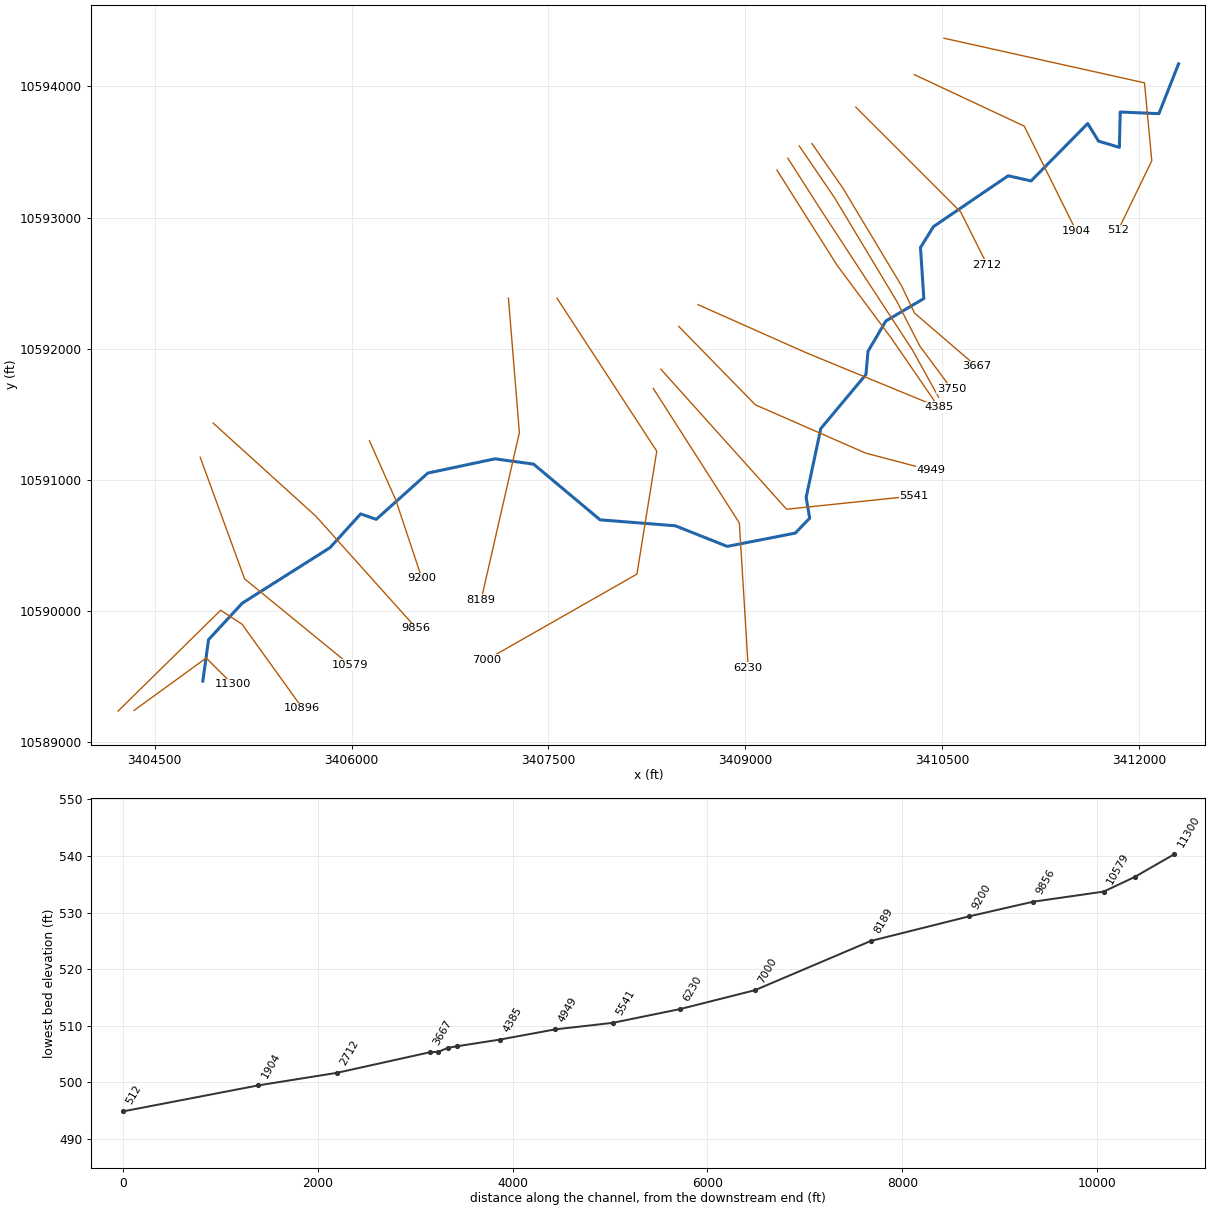
--- UNT0020 IN CHRS.prj (project) ---

Proj Title=UNT0020 IN CHRS Base Level Engineering
Current Plan=p01
Default Exp/Contr=0.3,0.1
English Units
Geom File=g01
Flow File=f01
Plan File=p01
Y Axis Title=Elevation
X Axis Title(PF)=Main Channel Distance
X Axis Title(XS)=Station
BEGIN DESCRIPTION:
UNT0020 IN CHRS
END DESCRIPTION:
DSS Export Rating Curves= 0
DSS Export Rating Curve Sorted= 0
DSS Export Volume Flow Curves= 0
DXF OffsetX= 0
DXF OffsetY= 0
DXF ScaleX= 1
DXF ScaleY= 10

--- UNT0020 IN CHRS.p01 (plan) ---

Plan Title=Multiple Run
Short Identifier=Multiple
Geom File=g01
Flow File=f01
Subcritical Flow
K Sum by GR= 0
Std Step Tol= 0.01
Critical Tol= 0.01
Num of Std Step Trials= 20
Max Error Tol= 0.3
Flow Tol Ratio= 0.001
Split Flow NTrial= 30
Split Flow Tol= 0.02
Split Flow Ratio= 0.02
Log Output Level= 0
Friction Slope Method= 1
Unsteady Friction Slope Method= 2
Unsteady Bridges Friction Slope Method= 1
Parabolic Critical Depth
Global Vel Dist=  1 , 1 , 1
Global Log Level= 0
CheckData=True
Encroach Param= -1, 0, 0, 0
BEGIN DESCRIPTION:
Multiple Run
END DESCRIPTION:

--- UNT0020 IN CHRS.f01 (steady flow) ---

Flow Title=Multiple
Program Version=4.10
Number of Profiles= 7
Profile Names=10-year,25-year,50-year,1pct_min,100-year,1pct_plu,500-year
River Rch & RM=UNT0020 IN CHRS,Reach-1         ,11300
     373     468     538     450     609     824     779
River Rch & RM=UNT0020 IN CHRS,Reach-1         ,8189
     603     779     912     776    1050    1419    1389
River Rch & RM=UNT0020 IN CHRS,Reach-1         ,6230
     715     927    1088     928    1254    1697    1666
Boundary for River Rch & Prof#=UNT0020 IN CHRS,Reach-1         , 1
Up Type= 0
Dn Type= 3
Dn Slope=0.005
Boundary for River Rch & Prof#=UNT0020 IN CHRS,Reach-1         , 2
Up Type= 0
Dn Type= 3
Dn Slope=0.005
Boundary for River Rch & Prof#=UNT0020 IN CHRS,Reach-1         , 3
Up Type= 0
Dn Type= 3
Dn Slope=0.005
Boundary for River Rch & Prof#=UNT0020 IN CHRS,Reach-1         , 4
Up Type= 0
Dn Type= 3
Dn Slope=0.005
Boundary for River Rch & Prof#=UNT0020 IN CHRS,Reach-1         , 5
Up Type= 0
Dn Type= 3
Dn Slope=0.005
Boundary for River Rch & Prof#=UNT0020 IN CHRS,Reach-1         , 6
Up Type= 0
Dn Type= 3
Dn Slope=0.005
Boundary for River Rch & Prof#=UNT0020 IN CHRS,Reach-1         , 7
Up Type= 0
Dn Type= 3
Dn Slope=0.005
DSS Import GetInterval= 0
DSS Import GetPeak= 0
DSS Import FillOption= 0

--- UNT0020 IN CHRS.g01 (geometry) ---

Geom Title=Existing Conditions
Program Version=4.10

River Reach=UNT0020 IN CHRS ,Reach-1
Reach XY= 30
      3404866.42     10589465.96      3404909.85     10589781.43
      3405166.48     10590059.35       3405835.3     10590482.67
      3406068.95     10590740.12      3406187.91     10590698.88
      3406581.26     10591051.61      3407092.47     10591160.09
      3407386.54     10591119.78      3407893.61     10590694.99
      3408466.51     10590649.76       3408862.4     10590492.47
      3409381.18     10590593.88      3409490.71     10590707.43
      3409464.01     10590865.92      3409575.35     10591390.43
      3409919.71     10591802.65      3409935.48     10591980.02
       3410071.5     10592211.05      3410360.97     10592382.17
      3410335.23     10592771.25      3410434.59     10592930.77
      3411003.62     10593318.23      3411178.23     10593278.95
      3411609.83      10593716.5      3411692.12     10593582.29
      3411851.07     10593534.79      3411857.47     10593804.39
      3412152.11     10593791.64      3412302.11     10594171.64

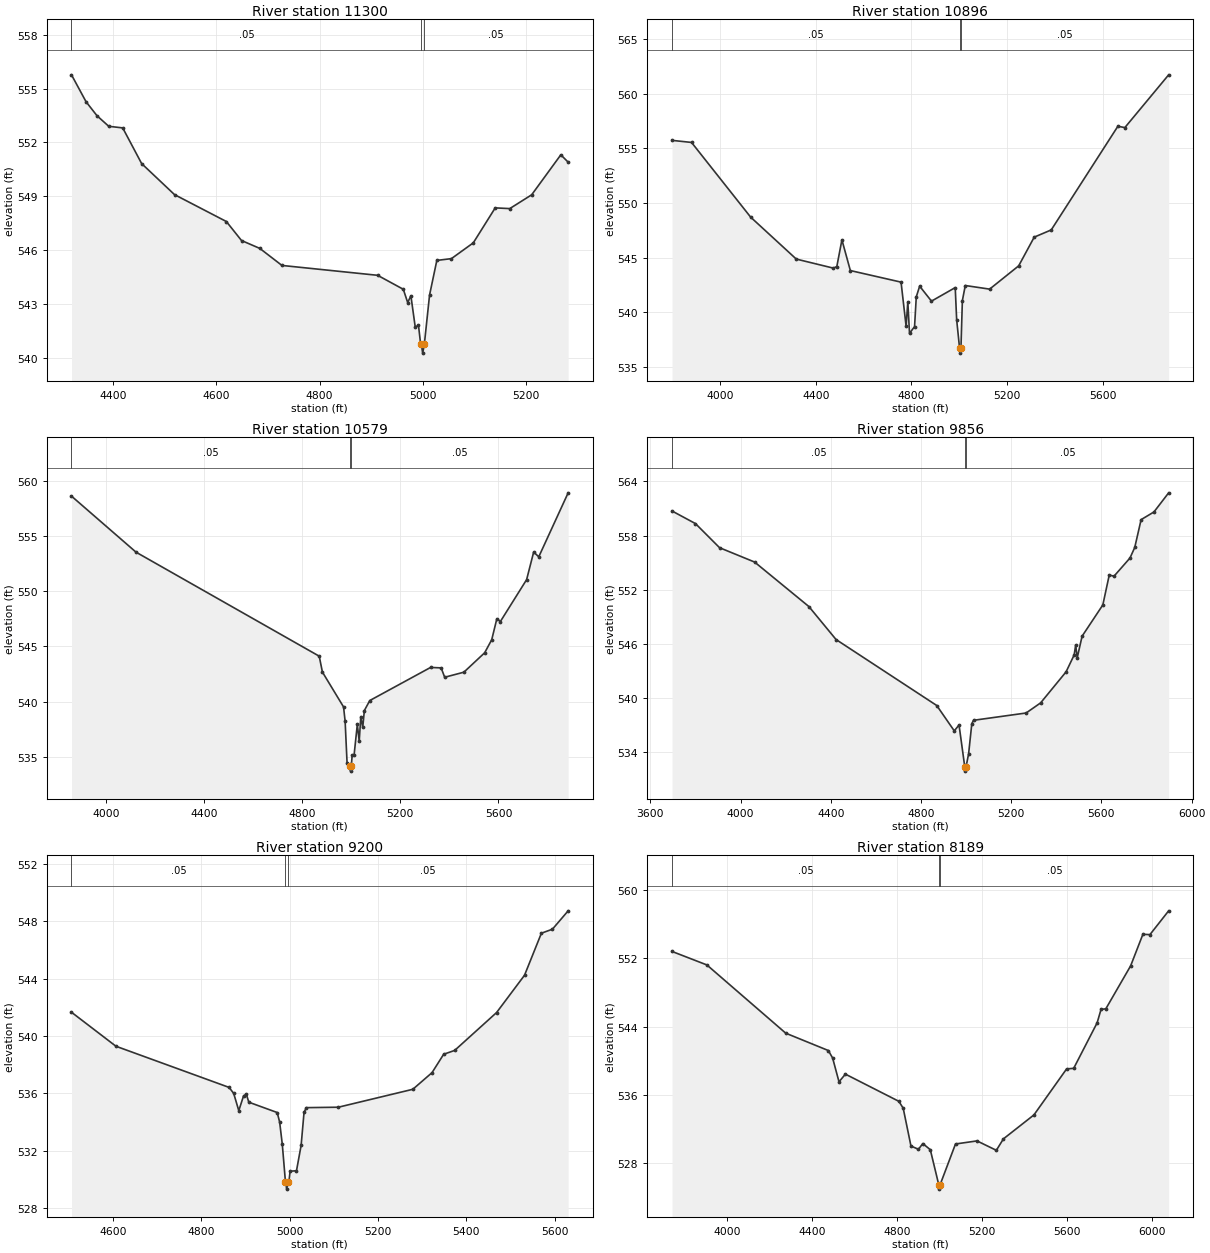
Type RM Length L Ch R = 1 ,11300   ,404,404,404
BEGIN DESCRIPTION:
UNT0020 IN CHRS 10.1
END DESCRIPTION:
XS GIS Cut Line= 3
      3404342.13     10589241.66      3404892.11     10589641.64
      3405092.12     10589441.63
#Sta/Elev= 30
  4318.9  555.77  4347.1  554.27  4368.3  553.49  4391.1   552.9  4418.2  552.81
  4454.9  550.82  4518.6  549.09  4619.1  547.59  4648.5  546.53    4684  546.09
  4726.9  545.14  4912.4  544.59  4962.2  543.81  4970.7  543.07  4976.9  543.45
  4985.4  541.69  4991.6  541.81  4995.8  540.75    4997  540.75  4999.8  540.25
    5003  540.75  5013.1  543.49  5027.2  545.42  5055.5  545.52  5097.9   546.4
  5140.4  548.35  5168.6  548.31  5211.1  549.08  5267.6  551.31  5281.8   550.9
#Mann= 3 ,-1 , 0
  4318.9     .05       0    4997    .035       0    5003     .05       0
Bank Sta=4997,5003
XS Rating Curve= 0 ,0
Exp/Cntr=0.3,0.1

Type RM Length L Ch R = 1 ,10896   ,317,317,317
BEGIN DESCRIPTION:
UNT0020 IN CHRS 9.0
END DESCRIPTION:
XS GIS Cut Line= 4
      3404220.82     10589237.31       3405002.1     10590005.57
      3405164.86     10589899.24      3405624.92     10589259.05
#Sta/Elev= 30
  3797.8  555.74  3879.6  555.55    4127  548.71    4318  544.87  4473.5  544.04
  4487.6  544.19  4508.9  546.63  4544.2  543.82  4756.4  542.76  4777.6  538.71
  4784.7  540.97  4791.8  538.07  4812.9  538.69  4820.1  541.41  4834.2  542.39
  4883.7  541.02  4983.1  542.26  4989.1  539.31  5001.1  536.76  5003.9  536.26
  5007.1  536.76    5013  541.07  5025.2  542.45  5127.1  542.12  5248.6  544.25
  5313.7  546.88  5384.9  547.54  5663.8  557.03    5693  556.91  5876.3  561.74
#Mann= 3 ,-1 , 0
  3797.8     .05       0  5001.1     .03       0  5007.1     .05       0
Bank Sta=5001.1,5007.1
XS Rating Curve= 0 ,0
Exp/Cntr=0.3,0.1

Type RM Length L Ch R = 1 ,10579   ,723,723,723
BEGIN DESCRIPTION:
UNT0020 IN CHRS 8.0
END DESCRIPTION:
XS GIS Cut Line= 3
      3404846.27     10591171.83      3405184.82     10590244.72
      3405986.88     10589588.49
#Sta/Elev= 30
  3860.7  558.62  4123.6  553.54  4869.9  544.11  4882.9  542.67    4969  539.51
  4975.4  538.22  4983.3  534.45  4994.7  534.19  4997.4  533.69  5000.7  534.19
  5004.1  535.13    5012  535.16  5025.1  537.92  5032.8  536.41  5039.3  538.63
  5047.2  537.65  5053.7  539.18  5075.9  540.09  5323.6  543.09  5366.6  543.05
    5381   542.2  5459.2  542.66  5543.9  544.42  5572.6   545.6  5593.6  547.51
  5607.8  547.25  5714.8  551.05  5743.5  553.55  5764.3  553.12    5884  558.92
#Mann= 3 ,-1 , 0
  3860.7     .05       0  4994.7     .03       0  5000.7     .05       0
Bank Sta=4994.7,5000.7
XS Rating Curve= 0 ,0
Exp/Cntr=0.3,0.1

Type RM Length L Ch R = 1 ,9856    ,656,656,656
BEGIN DESCRIPTION:
UNT0020 IN CHRS 7.0
END DESCRIPTION:
XS GIS Cut Line= 3
       3404945.2     10591432.26      3405726.49     10590723.89
      3406492.13     10589869.71
#Sta/Elev= 30
  3696.3  560.73  3800.4  559.33  3907.2  556.66  4062.6  555.07  4303.2  550.14
  4423.5  546.49  4869.9  539.18  4947.6  536.37  4968.8  537.02    4994  532.41
  4996.7  531.91    5000  532.41  5011.2  533.83  5025.4  537.17  5032.9  537.54
  5266.1  538.35  5330.4  539.47  5443.3  542.91  5479.1  544.78  5485.9  545.88
  5492.6  544.46  5514.3  546.86  5606.2  550.32  5634.7  553.64  5655.6   553.5
  5726.6  555.52  5747.7  556.69  5775.9  559.77  5832.8  560.62    5898  562.74
#Mann= 3 ,-1 , 0
  3696.3     .05       0    4994     .03       0    5000     .05       0
Bank Sta=4994,5000
XS Rating Curve= 0 ,0
Exp/Cntr=0.3,0.1

Type RM Length L Ch R = 1 ,9200    ,1011,1011,1011
BEGIN DESCRIPTION:
UNT0020 IN CHRS 5.0
END DESCRIPTION:
XS GIS Cut Line= 3
      3406135.86     10591297.87      3406335.86     10590847.89
      3406535.86     10590247.87
#Sta/Elev= 30
  4505.9  541.66  4606.6  539.29  4862.9  536.42  4873.3     536  4884.8   534.8
  4895.7  535.84  4902.1  535.93  4907.5  535.39  4971.8  534.67  4977.3  534.01
  4983.3  532.47  4990.5  529.83  4993.3  529.33  4996.5  529.83  4998.3  529.83
    5001  530.58  5015.5  530.61    5026  532.38  5032.6  534.68  5037.9  535.01
  5110.3  535.04    5279  536.29  5322.5  537.45  5348.8  538.73  5373.8     539
  5468.7  541.64    5532  544.24  5570.2  547.17  5595.2  547.45  5630.8  548.73
#Mann= 3 ,-1 , 0
  4505.9     .05       0  4990.5     .03       0  4996.5     .05       0
Bank Sta=4990.5,4996.5
XS Rating Curve= 0 ,0
Exp/Cntr=0.3,0.1

Type RM Length L Ch R = 1 ,8189    ,1189,1189,1189
BEGIN DESCRIPTION:
UNT0020 IN CHRS 3.0
END DESCRIPTION:
XS GIS Cut Line= 3
      3407195.24     10592385.37      3407278.57     10591359.31
      3406986.91     10590083.26
#Sta/Elev= 30
  3739.9  552.78  3904.2   551.2  4275.4  543.22    4476  541.19  4496.1  540.32
  4526.2  537.53  4556.3  538.43    4808  535.25  4828.5  534.44    4865  530.02
  4900.3  529.64  4920.8  530.31  4956.1  529.59    4996  525.48  4998.8  524.98
    5002  525.48  5074.7  530.26    5176  530.62    5267  529.52  5300.4  530.86
    5444  533.66  5597.8  539.04  5631.2  539.11  5741.5  544.43    5760     546
  5782.5  546.07  5899.2  551.09  5956.9  554.78  5990.2  554.75  6078.3  557.53
#Mann= 3 ,-1 , 0
  3739.9     .05       0    4996     .03       0    5002     .05       0
Bank Sta=4996,5002
XS Rating Curve= 0 ,0
Exp/Cntr=0.3,0.1

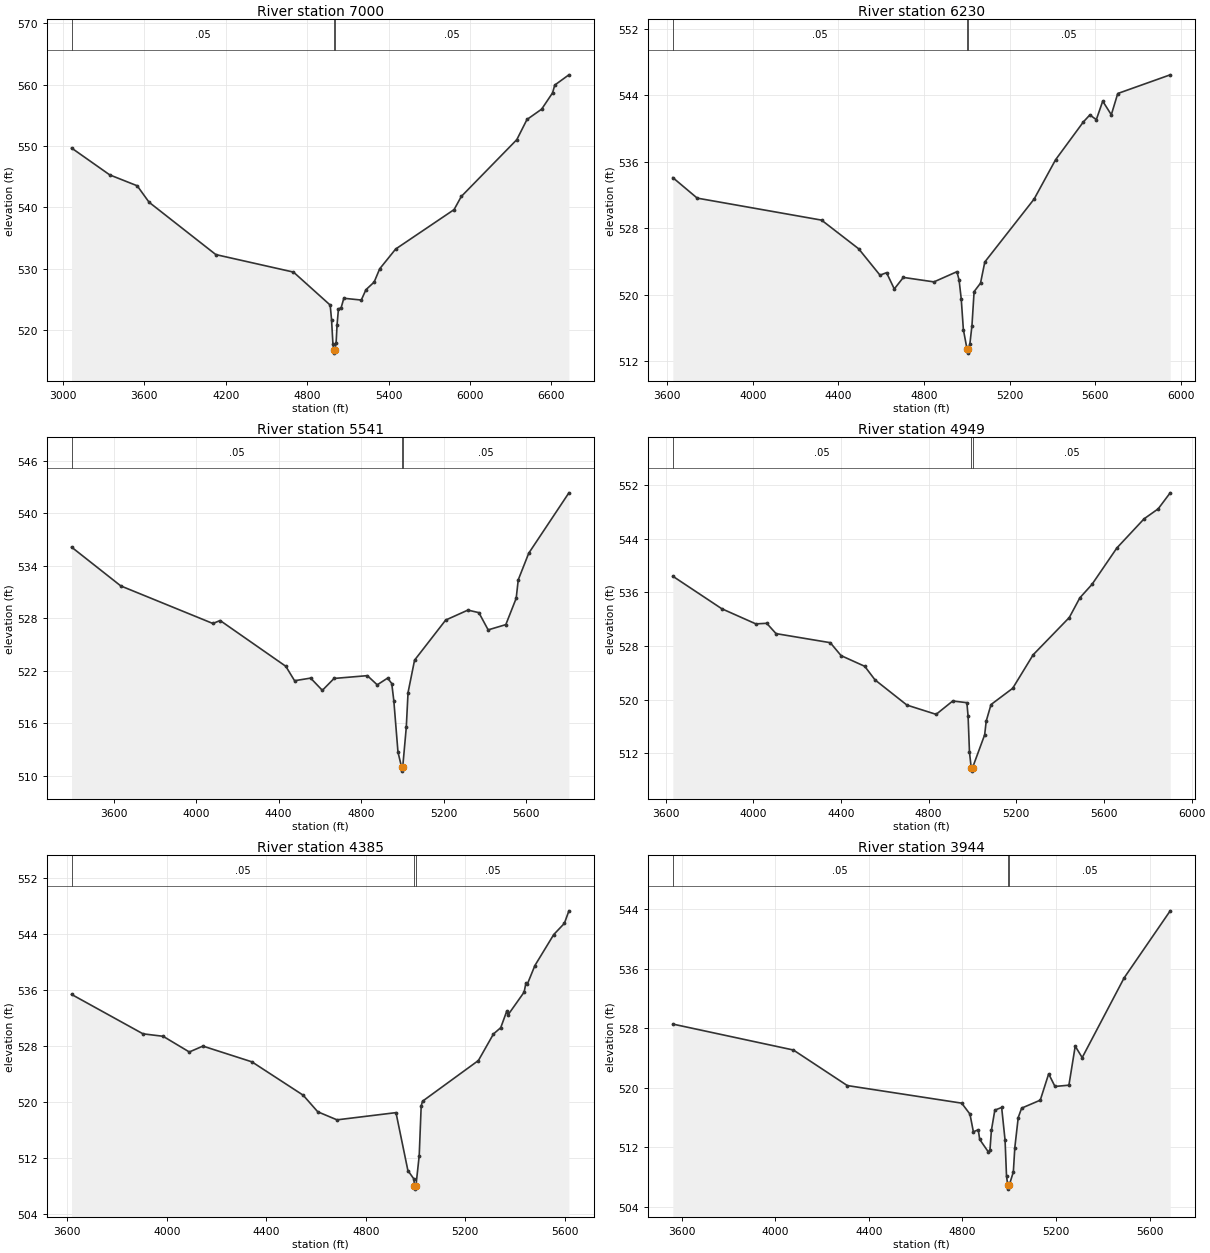
Type RM Length L Ch R = 1 ,7000    ,770,770,770
BEGIN DESCRIPTION:
UNT0020 IN CHRS 1.1
END DESCRIPTION:
XS GIS Cut Line= 4
      3407565.01     10592385.38      3408325.45     10591218.68
      3408174.41     10590281.18      3407024.84     10589625.78
#Sta/Elev= 30
  3063.7  549.68  3345.5   545.3  3547.6  543.53  3635.2  540.85  4127.1  532.33
  4699.4  529.48  4969.9  524.11    4980  521.72  4990.2  517.73  4997.3  516.79
  5000.1  516.29  5003.3  516.79  5013.6  517.93  5020.6  520.91  5030.7  523.46
  5050.9   523.7  5070.4  525.22  5199.1  524.93  5233.3  526.61    5294  527.86
  5334.6  530.01  5452.2  533.23  5882.9  539.65  5936.2  541.79  6345.3  551.04
  6420.2  554.32  6528.2     556  6608.9  558.66  6624.7  559.92  6729.2  561.59
#Mann= 3 ,-1 , 0
  3063.7     .05       0  4997.3     .03       0  5003.3     .05       0
Bank Sta=4997.3,5003.3
XS Rating Curve= 0 ,0
Exp/Cntr=0.3,0.1

Type RM Length L Ch R = 1 ,6230    ,689,689,689
BEGIN DESCRIPTION:
UNT0020 IN CHRS 12.0
END DESCRIPTION:
XS GIS Cut Line= 3
      3408298.61     10591697.16      3408954.87     10590671.11
      3409022.58     10589566.95
#Sta/Elev= 30
  3626.4  534.09  3740.3  531.62  4321.4  528.97  4494.7  525.52  4594.5  522.34
    4625  522.64  4661.3  520.68  4703.6  522.07  4846.6  521.53    4954  522.76
  4964.1  521.75  4974.1  519.48  4984.1  515.78  5001.1  513.45  5003.9  512.95
  5007.1  513.45  5014.2  513.99  5024.2  516.27  5034.2  520.36  5064.2  521.38
  5084.3  523.93  5314.7  531.51  5414.9  536.24  5545.2  540.81  5575.2  541.64
  5605.3  541.07  5635.3   543.3  5675.4  541.66  5705.5  544.22  5950.6  546.47
#Mann= 3 ,-1 , 0
  3626.4     .05       0  5001.1     .03       0  5007.1     .05       0
Bank Sta=5001.1,5007.1
XS Rating Curve= 0 ,0
Exp/Cntr=0.3,0.1

Type RM Length L Ch R = 1 ,5541    ,592,592,592
BEGIN DESCRIPTION:
UNT0020 IN CHRS 11.0
END DESCRIPTION:
XS GIS Cut Line= 3
      3408356.62     10591843.53      3409314.97      10590775.8
      3410286.33     10590877.36
#Sta/Elev= 30
  3396.1  536.13  3635.1  531.69  4081.4   527.4  4116.5  527.74  4434.9  522.51
  4477.5  520.86  4555.3  521.16  4612.1  519.76  4668.9  521.12  4830.3  521.44
  4878.2  520.39  4928.5  521.16  4948.6  520.54  4958.7  518.56  4978.8   512.7
  4995.9  511.03  4998.6  510.53  5001.9  511.03    5019  515.52  5027.6  519.51
  5059.2  523.21    5210  527.79  5317.7  528.93  5370.9  528.64    5416  526.67
  5501.6  527.27  5551.9  530.28  5561.9  532.39  5612.7  535.43  5807.5  542.33
#Mann= 3 ,-1 , 0
  3396.1     .05       0  4995.9    .035       0  5001.9     .05       0
Bank Sta=4995.9,5001.9
XS Rating Curve= 0 ,0
Exp/Cntr=0.3,0.1

Type RM Length L Ch R = 1 ,4949    ,564,564,564
BEGIN DESCRIPTION:
UNT0020 IN CHRS 10.0
END DESCRIPTION:
XS GIS Cut Line= 4
      3408493.77     10592169.05      3409077.13     10591571.81
       3409917.4     10591203.75      3410417.28     10591071.84
#Sta/Elev= 30
  3632.9  538.41  3856.1  533.57  4011.7  531.31  4061.3   531.4  4103.8  529.86
  4351.2  528.51  4400.6  526.58  4508.5  524.99  4555.2  522.97    4701  519.21
  4834.2  517.83  4909.9  519.82  4974.5  519.57    4980  517.54  4986.3  512.21
  4994.2  509.87    4997  509.37  5000.2  509.87  5055.6  514.78  5062.7  516.83
  5084.6  519.29  5183.4  521.71  5276.9  526.71  5441.7  532.26  5489.8  535.19
  5545.1  537.19  5658.9  542.63    5783  546.97  5847.1  548.45  5902.1  550.84
#Mann= 3 ,-1 , 0
  3632.9     .05       0  4994.2     .03       0  5000.2     .05       0
Bank Sta=4994.2,5000.2
XS Rating Curve= 0 ,0
Exp/Cntr=0.3,0.1

Type RM Length L Ch R = 1 ,4385    ,441,441,441
BEGIN DESCRIPTION:
UNT0020 IN CHRS 8.1
END DESCRIPTION:
XS GIS Cut Line= 3
      3408639.61      10592335.7      3409459.07     10591971.11
       3410478.5     10591551.55
#Sta/Elev= 30
  3617.1  535.38  3904.4  529.75  3985.1   529.4  4090.5  527.16  4145.2     528
  4342.2  525.75  4548.2  520.99  4606.9  518.62  4684.2  517.47  4921.3   518.5
  4969.2  510.23  4993.1  509.04  4995.6  508.08  4998.4  507.58  5001.6  508.08
  5014.7  512.37  5022.6  519.46    5028  520.13  5252.6  525.94  5313.1  529.73
  5342.4  530.63  5366.4  532.97  5371.8  532.46  5436.5  535.71  5443.6  537.02
    5449  536.82  5479.7   539.5  5555.6  543.93  5598.1  545.52  5616.4  547.31
#Mann= 3 ,-1 , 0
  3617.1     .05       0  4995.6     .03       0  5001.6     .05       0
Bank Sta=4995.6,5001.6
XS Rating Curve= 0 ,0
Exp/Cntr=0.3,0.1

Type RM Length L Ch R = 1 ,3944    ,98,98,98
BEGIN DESCRIPTION:
UNT0020 IN CHRS 6.0
END DESCRIPTION:
XS GIS Cut Line= 4
      3409241.19     10593361.76      3409699.55     10592636.02
      3410112.74     10592080.47      3410439.12     10591604.79
#Sta/Elev= 30
  3560.9  528.55  4076.6  525.07  4307.2   520.3  4796.5  517.94  4831.9  516.47
  4846.5   514.1  4867.4  514.36  4873.6  513.07  4910.8  511.38  4917.4  511.62
  4923.7   514.3  4938.3     517  4967.5  517.36  4982.1  512.97  4988.3  508.15
  4993.7   506.9  4996.5   506.4  4999.7   506.9  5017.5  508.71  5023.8  511.97
  5038.4  516.01    5053  517.27  5132.7  518.34  5168.6  521.87  5195.6  520.18
  5255.2  520.35  5282.2  525.59    5312  524.05  5491.4  534.75  5688.5  543.75
#Mann= 3 ,-1 , 0
  3560.9     .05       0  4993.7     .03       0  4999.7     .05       0
Bank Sta=4993.7,4999.7
XS Rating Curve= 0 ,0
Exp/Cntr=0.3,0.1

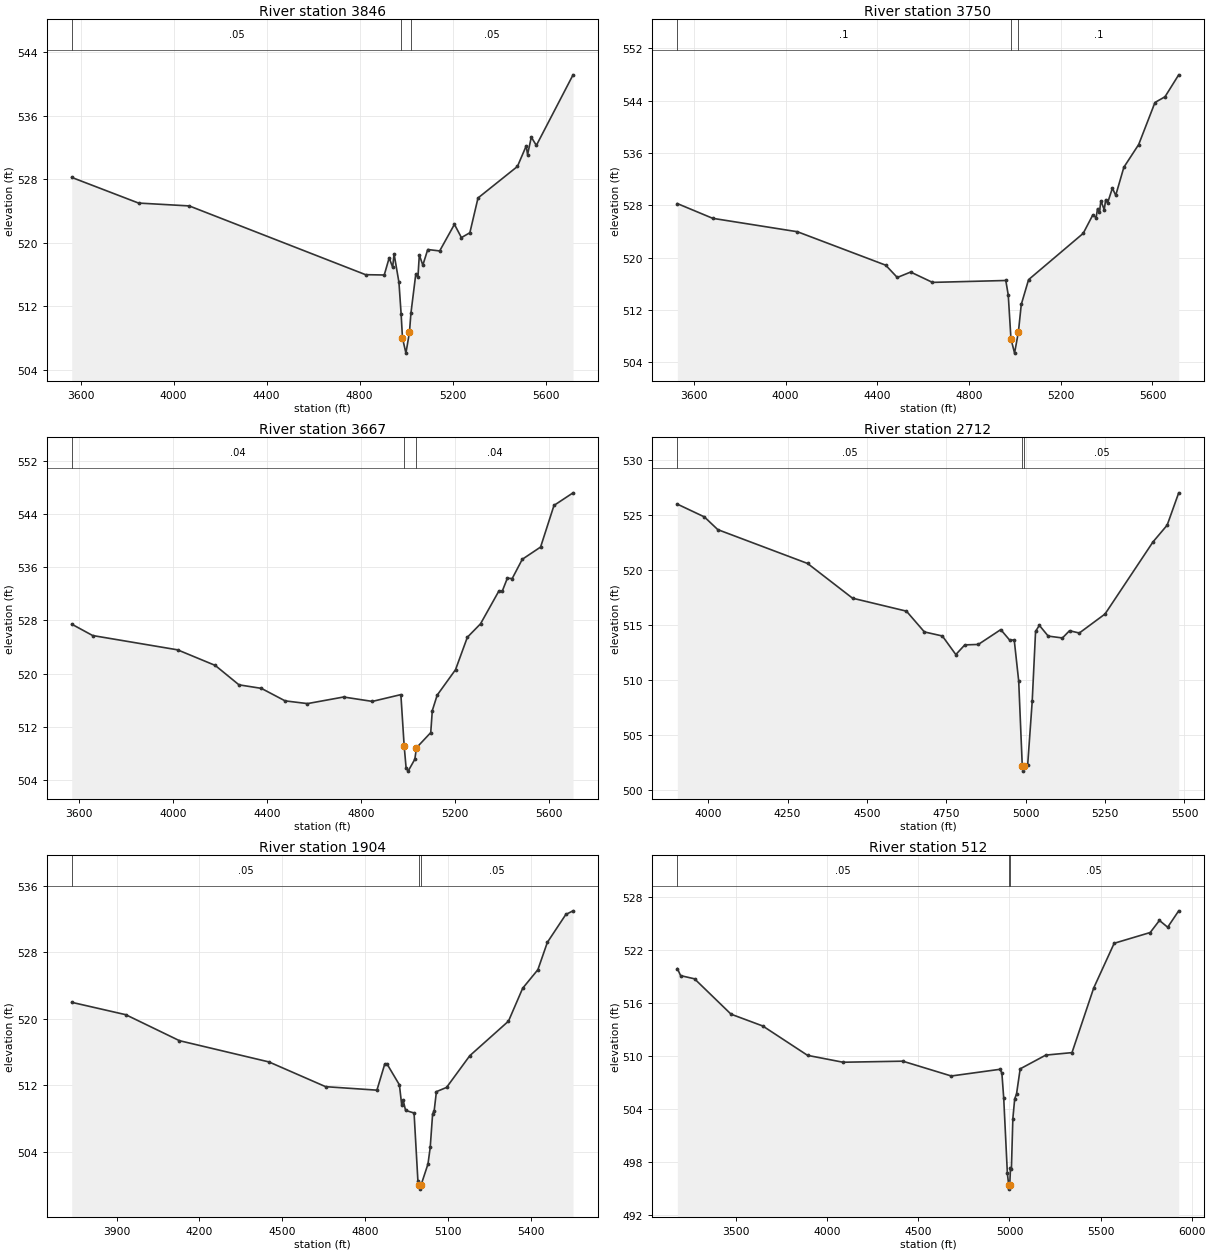
Type RM Length L Ch R = 1 ,3846    ,96,96,96
BEGIN DESCRIPTION:
UNT0020 IN CHRS 6.3
END DESCRIPTION:
XS GIS Cut Line= 5
      3409324.55       10593452.      3409557.19     10593087.41
      3410178.72     10592136.02      3410275.94     10591986.72
      3410473.84      10591629.1
#Sta/Elev= 30
  3561.8  528.23  3849.1     525  4067.1  524.64  4825.4  515.98  4905.7  515.94
  4926.8  518.09  4941.9  516.92  4947.9   518.6  4968.9  515.01  4978.1  511.09
  4984.1     508  4998.9   506.1  5014.2  508.75  5020.3   511.1  5041.3  516.06
  5050.5  515.66  5056.5  518.46  5071.6  517.18  5092.7  519.15    5144  518.97
  5207.5  522.32  5237.5  520.65  5273.8  521.26  5308.9  525.64  5478.4  529.61
  5516.2   532.2    5522  531.09    5538   533.3  5559.8  532.26  5717.6  541.15
#Mann= 3 ,-1 , 0
  3561.8     .05       0  4978.1     .03       0  5020.3     .05       0
Bank Sta=4984.1,5014.2
XS Rating Curve= 0 ,0
Exp/Cntr=0.3,0.1

Type RM Length L Ch R = 1 ,3750    ,83,83,83
BEGIN DESCRIPTION:
UNT0020 IN CHRS 6.1
END DESCRIPTION:
XS GIS Cut Line= 5
      3409411.36     10593545.74      3409678.72     10593153.38
      3410154.41     10592361.72      3410331.49     10592017.97
      3410570.51     10591695.81
#Sta/Elev= 30
  3528.1  528.26  3682.3  526.01  4051.6  523.96  4436.6  518.85  4487.1  516.97
  4545.4   517.8  4640.6  516.22  4960.3  516.51    4971  514.29  4982.8   507.6
  4998.5  505.41  5015.3  508.65  5027.8  512.85  5059.7  516.64  5297.8  523.71
  5339.5  526.51  5354.2  526.12  5360.4  527.49  5368.8  526.97    5375   528.7
  5389.6  527.32  5395.8  528.86  5404.2  528.36  5425.1  530.62  5439.7  529.53
  5475.2  533.82  5539.8  537.29  5610.8  543.71  5654.6  544.59  5714.3  547.94
#Mann= 3 , 0 , 0
  3528.1      .1       0  4982.8     .08       0  5015.3      .1       0
Bank Sta=4982.8,5015.3
XS Rating Curve= 0 ,0
Exp/Cntr=0.3,0.1

Type RM Length L Ch R = 1 ,3667    ,955,955,955
BEGIN DESCRIPTION:
UNT0020 IN CHRS 6.2
END DESCRIPTION:
XS GIS Cut Line= 5
      3409508.58      10593563.1      3409744.69     10593222.83
       3410192.6      10592476.3      3410289.83     10592271.44
      3410761.18     10591865.93
#Sta/Elev= 30
  3567.8  527.44  3656.9  525.73  4018.3  523.58  4178.4  521.24  4279.5  518.32
  4374.7  517.79  4475.8  515.91    4571   515.5  4724.6  516.49    4847  515.83
  4968.4  516.85  4982.3  509.19  4990.5  505.89  4999.3  505.35  5027.8  507.14
  5034.8  508.86  5095.5  511.14  5102.1  514.44  5122.9  516.77    5201   520.6
  5251.3  525.47  5307.3  527.49  5385.7  532.44  5399.4  532.36  5421.4  534.34
  5442.2   534.3    5485  537.19  5562.9  539.03    5620  545.29  5701.1  547.18
#Mann= 3 , 0 , 0
  3567.8     .04       0  4982.3     .03       0  5034.8     .04       0
Bank Sta=4982.3,5034.8
XS Rating Curve= 0 ,0
Exp/Cntr=0.3,0.1

Type RM Length L Ch R = 1 ,2712    ,808,808,808
BEGIN DESCRIPTION:
UNT0020 IN CHRS 5.1
END DESCRIPTION:
XS GIS Cut Line= 3
      3409842.09     10593841.66      3410642.11     10593041.64
       3410842.1     10592641.65
#Sta/Elev= 30
  3903.2  526.01  3988.1  524.85  4030.5  523.69  4313.3  520.61  4454.8  517.45
  4624.5  516.27    4681  514.38  4737.6  514.01    4780  512.32  4808.3   513.2
  4850.8  513.24  4921.5  514.59  4949.7  513.63  4963.9  513.65    4978   509.9
  4989.2  502.21  4991.9  501.71  4995.2  502.21  5006.3   502.3  5020.5  508.06
  5031.1  514.43    5043  514.98  5070.9     514  5115.7  513.83    5138  514.49
  5168.8  514.28  5249.8  516.01  5400.8  522.57  5445.5   524.1  5481.8  527.04
#Mann= 3 ,-1 , 0
  3903.2     .05       0  4989.2     .03       0  4995.2     .05       0
Bank Sta=4989.2,4995.2
XS Rating Curve= 0 ,0
Exp/Cntr=0.3,0.1

Type RM Length L Ch R = 1 ,1904    ,1392,1392,1392
BEGIN DESCRIPTION:
UNT0020 IN CHRS 2.0
END DESCRIPTION:
XS GIS Cut Line= 3
      3410288.89     10594089.19      3411125.74     10593696.81
      3411521.57      10592898.2
#Sta/Elev= 30
  3737.7  521.99  3933.3   520.5  4127.8  517.37    4452  514.81  4657.2  511.83
    4843  511.41    4871  514.52  4879.8  514.55  4924.4  512.05  4932.6  509.66
  4938.2  510.17  4946.8  508.97  4977.5  508.66  4991.4  500.48  4996.9  499.99
  4999.7  499.49  5002.9  499.99  5027.9  502.52    5036  504.52  5044.7  508.56
  5050.3  508.92  5058.4  511.23  5095.2  511.74  5179.3  515.56  5319.4  519.72
  5370.9  523.69  5425.9  525.92  5460.2  529.21  5527.1  532.57  5553.3  533.01
#Mann= 3 ,-1 , 0
  3737.7     .05       0  4996.9     .03       0  5002.9     .05       0
Bank Sta=4996.9,5002.9
XS Rating Curve= 0 ,0
Exp/Cntr=0.3,0.1

Type RM Length L Ch R = 1 ,512     ,0,0,0
BEGIN DESCRIPTION:
UNT0020 IN CHRS 1.0
END DESCRIPTION:
XS GIS Cut Line= 4
      3410514.62     10594366.95       3412042.4     10594026.67
      3412097.96     10593432.92      3411841.01     10592901.66
#Sta/Elev= 30
  3177.3   519.9  3195.2   519.1  3271.4  518.74  3471.8  514.73    3646  513.39
  3891.9  510.06  4086.5  509.28  4414.4   509.4  4680.7  507.72  4948.4  508.48
  4958.5  508.04  4968.5  505.23  4988.6  496.69  4995.7  495.39  4998.4  494.89
  5001.7  495.39  5005.7  497.26  5010.7  497.15  5018.7  502.89  5028.8  505.13
  5038.8  505.67  5058.9  508.53  5199.5  510.09  5343.3  510.37  5462.5   517.7
  5574.8  522.77  5772.6  523.99  5823.3  525.36  5868.5  524.59    5929  526.45
#Mann= 3 ,-1 , 0
  3177.3     .05       0  4995.7    .035       0  5001.7     .05       0
Bank Sta=4995.7,5001.7
XS Rating Curve= 0 ,0
Exp/Cntr=0.3,0.1

Chan Stop Cuts=-1
Use User Specified Reach Order=0
Composite Channel Slope=5