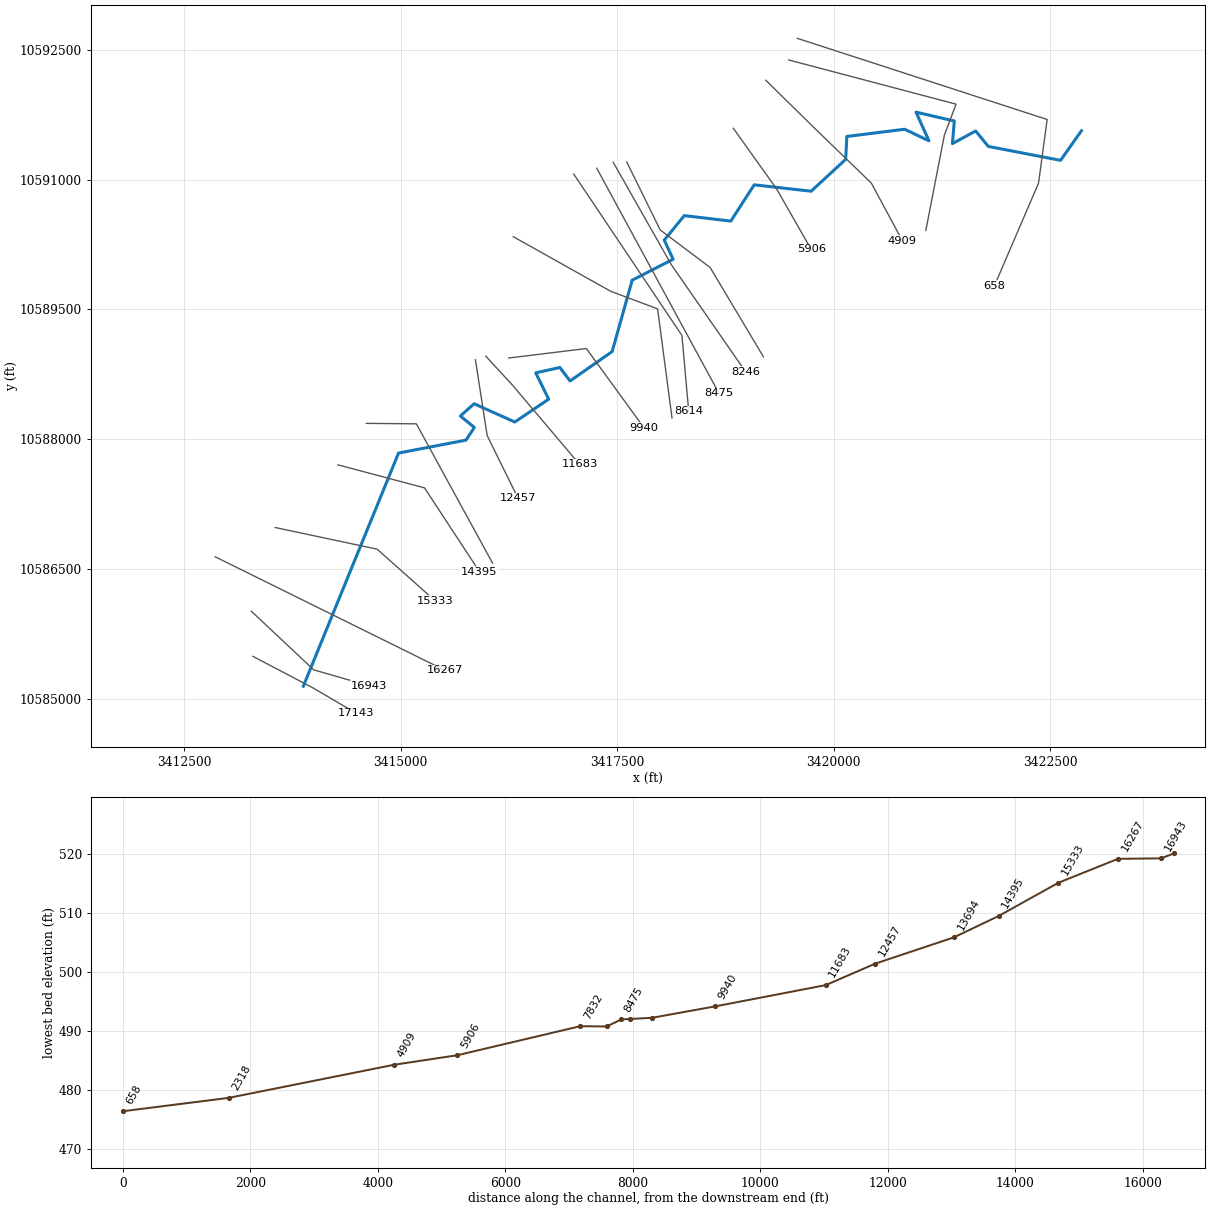
--- UNT0021 IN CHRS.prj (project) ---

Proj Title=UNT0021 IN CHRS Base Level Engineering
Current Plan=p01
Default Exp/Contr=0.3,0.1
English Units
Geom File=g01
Flow File=f01
Plan File=p01
Y Axis Title=Elevation
X Axis Title(PF)=Main Channel Distance
X Axis Title(XS)=Station
BEGIN DESCRIPTION:
UNT0021 IN CHRS
END DESCRIPTION:
DSS Export Rating Curves= 0
DSS Export Rating Curve Sorted= 0
DSS Export Volume Flow Curves= 0
DXF OffsetX= 0
DXF OffsetY= 0
DXF ScaleX= 1
DXF ScaleY= 10

--- UNT0021 IN CHRS.p01 (plan) ---

Plan Title=Multiple Run
Short Identifier=Multiple
Geom File=g01
Flow File=f01
Subcritical Flow
K Sum by GR= 0
Std Step Tol= 0.01
Critical Tol= 0.01
Num of Std Step Trials= 20
Max Error Tol= 0.3
Flow Tol Ratio= 0.001
Split Flow NTrial= 30
Split Flow Tol= 0.02
Split Flow Ratio= 0.02
Log Output Level= 0
Friction Slope Method= 1
Unsteady Friction Slope Method= 2
Unsteady Bridges Friction Slope Method= 1
Parabolic Critical Depth
Global Vel Dist=  1 , 1 , 1
Global Log Level= 0
CheckData=True
Encroach Param= -1, 0, 0, 0
BEGIN DESCRIPTION:
Multiple Run
END DESCRIPTION:

--- UNT0021 IN CHRS.f01 (steady flow) ---

Flow Title=Multiple
Number of Profiles=7
Profile Names=10-year,25-year,50-year,1pct_min,100-year,1pct_plu,500-year
River Rch & RM= UNT0021 IN CHRS,Reach-1,17143
     427     541     625     527     712     963     922
River Rch & RM= UNT0021 IN CHRS,Reach-1,15333
     671     868    1017     866    1171    1584    1552
River Rch & RM= UNT0021 IN CHRS,Reach-1,8954
     751     973    1142     973    1316    1779    1745
River Rch & RM= UNT0021 IN CHRS,Reach-1,2318
     791    1026    1205    1027    1389    1879    1845
Boundary for River Rch & Prof#=UNT0021 IN CHRS,Reach-1,1
Up Type=0
Dn Type=3
Dn Slope=0.005
Boundary for River Rch & Prof#=UNT0021 IN CHRS,Reach-1,2
Up Type=0
Dn Type=3
Dn Slope=0.005
Boundary for River Rch & Prof#=UNT0021 IN CHRS,Reach-1,3
Up Type=0
Dn Type=3
Dn Slope=0.005
Boundary for River Rch & Prof#=UNT0021 IN CHRS,Reach-1,4
Up Type=0
Dn Type=3
Dn Slope=0.005
Boundary for River Rch & Prof#=UNT0021 IN CHRS,Reach-1,5
Up Type=0
Dn Type=3
Dn Slope=0.005
Boundary for River Rch & Prof#=UNT0021 IN CHRS,Reach-1,6
Up Type=0
Dn Type=3
Dn Slope=0.005
Boundary for River Rch & Prof#=UNT0021 IN CHRS,Reach-1,7
Up Type=0
Dn Type=3
Dn Slope=0.005

--- UNT0021 IN CHRS.g01 (geometry) ---

Geom Title=Existing Conditions
Program Version=4.10

River Reach=UNT0021 IN CHRS ,Reach-1
Reach XY= 30
      3413874.76     10585146.53      3414974.73     10587839.94
      3415754.28     10587989.65      3415850.45     10588135.56
      3415689.61     10588268.07      3415847.59     10588409.69
      3416318.42     10588198.79      3416709.19     10588462.95
       3416559.5     10588766.64      3416837.68     10588828.97
      3416956.48     10588673.09      3417442.47     10589012.64
      3417673.79     10589837.03      3418146.74       10590079.
      3418044.64     10590300.17      3418275.62     10590583.13
      3418812.96     10590519.67      3419083.22      10590938.7
      3419740.92     10590864.81      3420139.72      10591232.4
      3420153.65     10591497.45      3420821.36     10591580.78
      3421102.09     10591446.72      3420952.71     10591778.23
      3421394.99     10591675.95      3421373.13     10591414.77
      3421641.53     10591560.88      3421787.36     10591382.46
      3422622.38      10591221.5      3422863.31     10591562.68

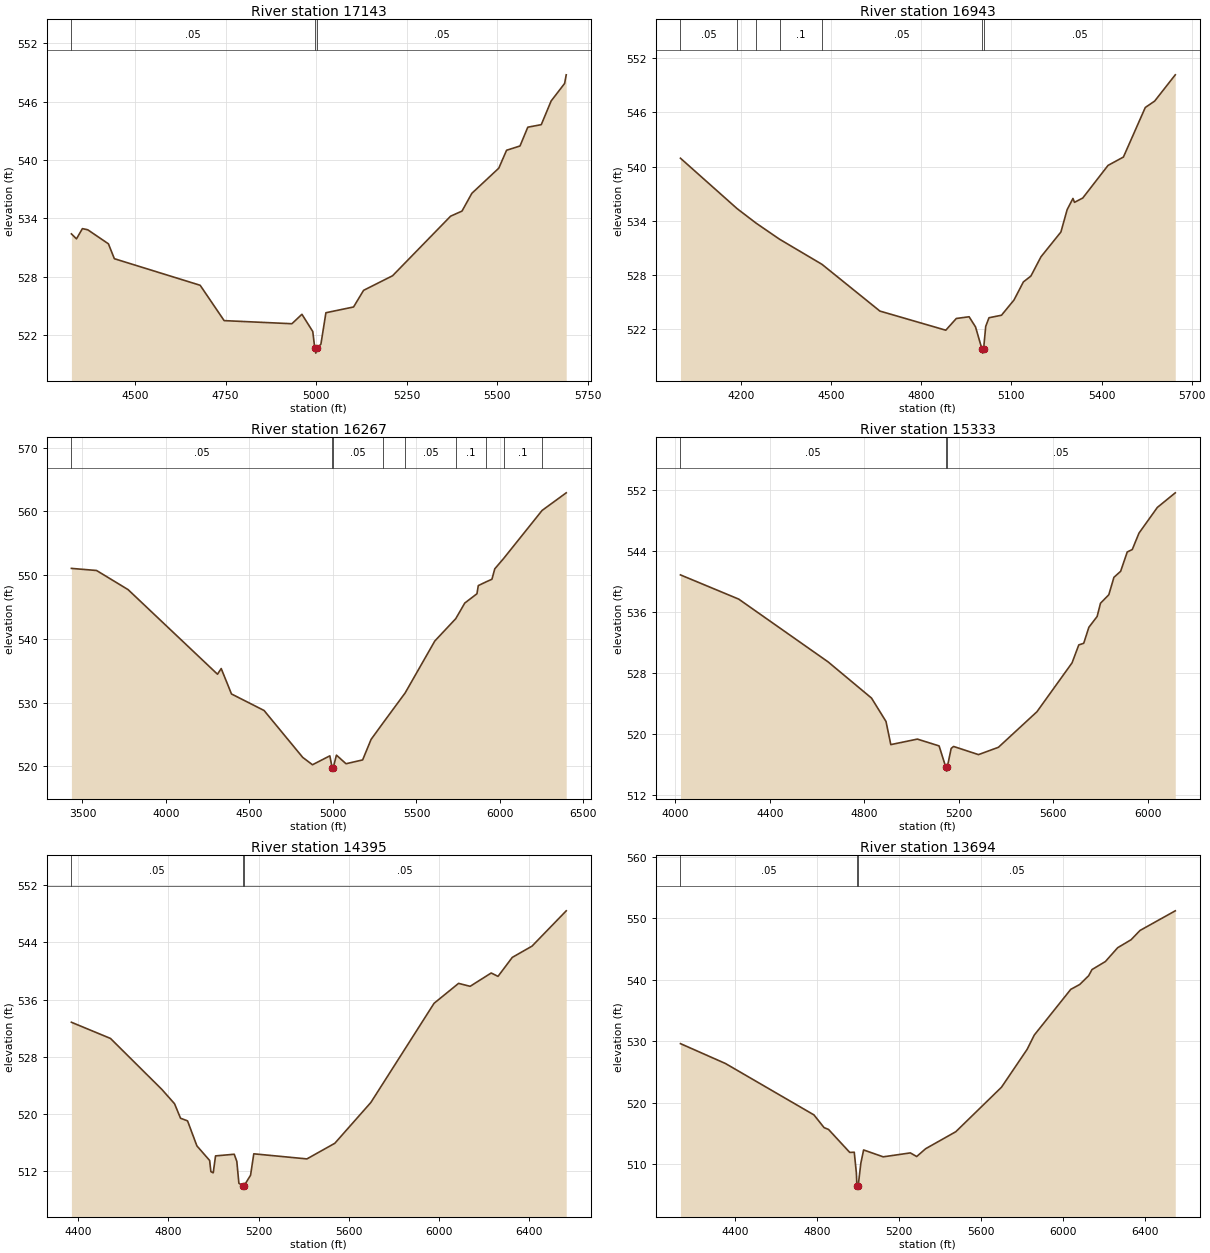
Type RM Length L Ch R = 1 ,17143   ,200,200,200
BEGIN DESCRIPTION:
UNT0021 IN CHRS 24.1
END DESCRIPTION:
XS GIS Cut Line= 3
      3413292.12     10585491.79      3413986.55     10585127.21
      3414488.54     10584832.94
#Sta/Elev= 30
  4324.3  532.41  4338.3   531.9  4354.7  532.95  4369.5  532.83  4426.5  531.39
  4442.9  529.86  4679.8  527.13    4746   523.5  4933.1  523.18  4960.8  524.15
  4990.7  522.38  4996.3  520.66    4999  520.16  5002.3  520.66  5013.2  521.08
    5027  524.31  5103.3   524.9    5131  526.61  5211.1  528.11  5371.3  534.23
  5402.7  534.75    5430  536.58  5504.3  539.16  5525.8     541  5562.9  541.44
  5584.4  543.37  5621.6  543.63  5648.8  546.06    5686  547.86  5690.5  548.75
#Mann= 3 ,-1 , 0
  4324.3     .05       0  4996.3    .035       0  5002.3     .05       0
Bank Sta=4996.3,5002.3
XS Rating Curve= 0 ,0
Exp/Cntr=0.3,0.1

Type RM Length L Ch R = 1 ,16943   ,676,676,676
BEGIN DESCRIPTION:
UNT0021 IN CHRS 24.0
END DESCRIPTION:
XS GIS Cut Line= 3
      3413274.77      10586012.6      3413995.23     10585335.54
        3414628.     10585153.51
#Sta/Elev= 30
  3998.4  540.92  4187.4  535.32  4250.4  533.72  4328.4  531.94  4469.5  529.16
  4662.3  523.98  4881.6  521.86  4916.7  523.16  4959.2  523.35  4980.7  522.22
  5001.6  519.82  5004.4  519.32  5007.6  519.82  5014.5  522.28  5025.4  523.24
  5067.1  523.52  5108.7  525.21  5139.9  527.21  5164.9  527.86  5198.6     530
  5264.8  532.74  5285.6  535.22  5304.9  536.46  5310.1  536.03  5337.6  536.51
  5421.6  540.12  5472.9  541.05  5545.7  546.54  5576.9  547.25  5645.5  550.16
#Mann= 7 ,-1 , 0
  3998.4     .05       0  4187.4      .1       0  4250.4     .05       0
  4328.4      .1       0  4469.5     .05       0  5001.6    .035       0
  5007.6     .05       0
Bank Sta=5001.6,5007.6
XS Rating Curve= 0 ,0
Exp/Cntr=0.3,0.1

Type RM Length L Ch R = 1 ,16267   ,934,934,934
BEGIN DESCRIPTION:
UNT0021 IN CHRS 22.0
END DESCRIPTION:
XS GIS Cut Line= 2
      3412857.93     10586641.32      3415514.16     10585328.83
#Sta/Elev= 30
  3433.9  551.06  3584.5  550.73  3773.2  547.73  4308.6  534.45  4330.9  535.34
  4392.4  531.35  4587.4  528.76  4818.8   521.4  4877.4  520.24  4981.4  521.64
  4995.3  519.74  4998.1  519.24  5001.3  519.74  5020.8  521.75  5078.2   520.4
  5177.8     521  5228.3  524.22  5298.2  526.74  5432.2  531.51  5609.8  539.66
  5735.3  543.17  5789.3  545.62  5862.2  547.08  5870.2  548.36  5916.5  548.94
    5952  549.36  5968.9  550.99  6021.4   552.6  6252.4  560.16  6396.7  562.92
#Mann= 9 ,-1 , 0
  3433.9     .05       0  4995.3    .035       0  5001.3     .05       0
  5298.2      .1       0  5432.2     .05       0  5735.3      .1       0
  5916.5     .05       0  6021.4      .1       0  6252.4     .05       0
Bank Sta=4995.3,5001.3
XS Rating Curve= 0 ,0
Exp/Cntr=0.3,0.1

Type RM Length L Ch R = 1 ,15333   ,938,938,938
BEGIN DESCRIPTION:
UNT0021 IN CHRS 21.0
END DESCRIPTION:
XS GIS Cut Line= 3
      3413550.65     10586979.88      3414727.68     10586729.89
      3415394.03     10586136.42
#Sta/Elev= 30
  4021.9  540.86  4268.7  537.69    4647  529.48    4831  524.74  4892.4  521.68
  4912.8  518.65  5025.3  519.37  5117.3  518.48  5145.8  515.68  5148.5  515.18
  5151.8  515.68  5168.4  518.15  5178.6  518.41  5284.1  517.34  5368.6   518.3
  5531.6  522.95  5680.4  529.35  5708.9   531.7  5729.8  531.91  5751.5     534
  5786.6  535.42  5800.8  537.15    5836  538.26  5857.7  540.54  5886.1  541.33
  5914.1  543.86  5935.4  544.18  5963.9  546.33  6041.6  549.69  6117.5   551.6
#Mann= 3 ,-1 , 0
  4021.9     .05       0  5145.8    .035       0  5151.8     .05       0
Bank Sta=5145.8,5151.8
XS Rating Curve= 0 ,0
Exp/Cntr=0.3,0.1

Type RM Length L Ch R = 1 ,14395   ,701,701,701
BEGIN DESCRIPTION:
UNT0021 IN CHRS 18.0
END DESCRIPTION:
XS GIS Cut Line= 3
      3414274.58     10587703.84      3415274.56     10587438.22
      3415909.98     10586469.47
#Sta/Elev= 30
  4370.1  532.83  4543.4  530.57  4771.1  523.45  4827.3  521.45  4853.8  519.43
  4884.9  519.06  4926.3  515.57  4982.8  513.53  4988.3  511.97  4998.7  511.81
    5009  514.17  5091.8   514.4  5103.3   513.4  5112.5  510.34  5130.1  510.03
  5132.9  509.53  5136.1  510.03  5164.2  511.47  5178.5  514.46    5414  513.75
  5537.6  515.93  5697.4  521.63  5977.6  535.48  6086.2  538.26  6137.4  537.85
  6230.8  539.71    6261  539.24  6324.3  541.89  6411.7  543.46  6563.3  548.39
#Mann= 3 ,-1 , 0
  4370.1     .05       0  5130.1    .035       0  5136.1     .05       0
Bank Sta=5130.1,5136.1
XS Rating Curve= 0 ,0
Exp/Cntr=0.3,0.1

Type RM Length L Ch R = 1 ,13694   ,1237,1237,1237
BEGIN DESCRIPTION:
UNT0021 IN CHRS 16.0
END DESCRIPTION:
XS GIS Cut Line= 3
      3414602.63     10588183.01      3415180.81      10588177.8
      3416060.99     10586568.47
#Sta/Elev= 30
    4135   529.6  4354.5  526.36  4785.9  517.99  4835.2  515.92    4857  515.62
  4960.4  511.88  4982.4  511.91  4992.7  508.53  4995.4   506.4  4998.1   505.9
  5001.4   506.4  5014.5  510.12    5028  512.28  5123.6  511.16  5255.9   511.8
  5286.7  511.21  5330.3  512.48  5477.4  515.25  5700.3   522.5  5825.5  528.68
    5860  530.99    6038  538.44  6081.6  539.23  6125.2  540.66  6141.4  541.66
  6206.8  542.97  6266.6  545.22    6332  546.52  6375.6  548.03  6547.5  551.23
#Mann= 3 ,-1 , 0
    4135     .05       0  4995.4    .035       0  5001.4     .05       0
Bank Sta=4995.4,5001.4
XS Rating Curve= 0 ,0
Exp/Cntr=0.3,0.1

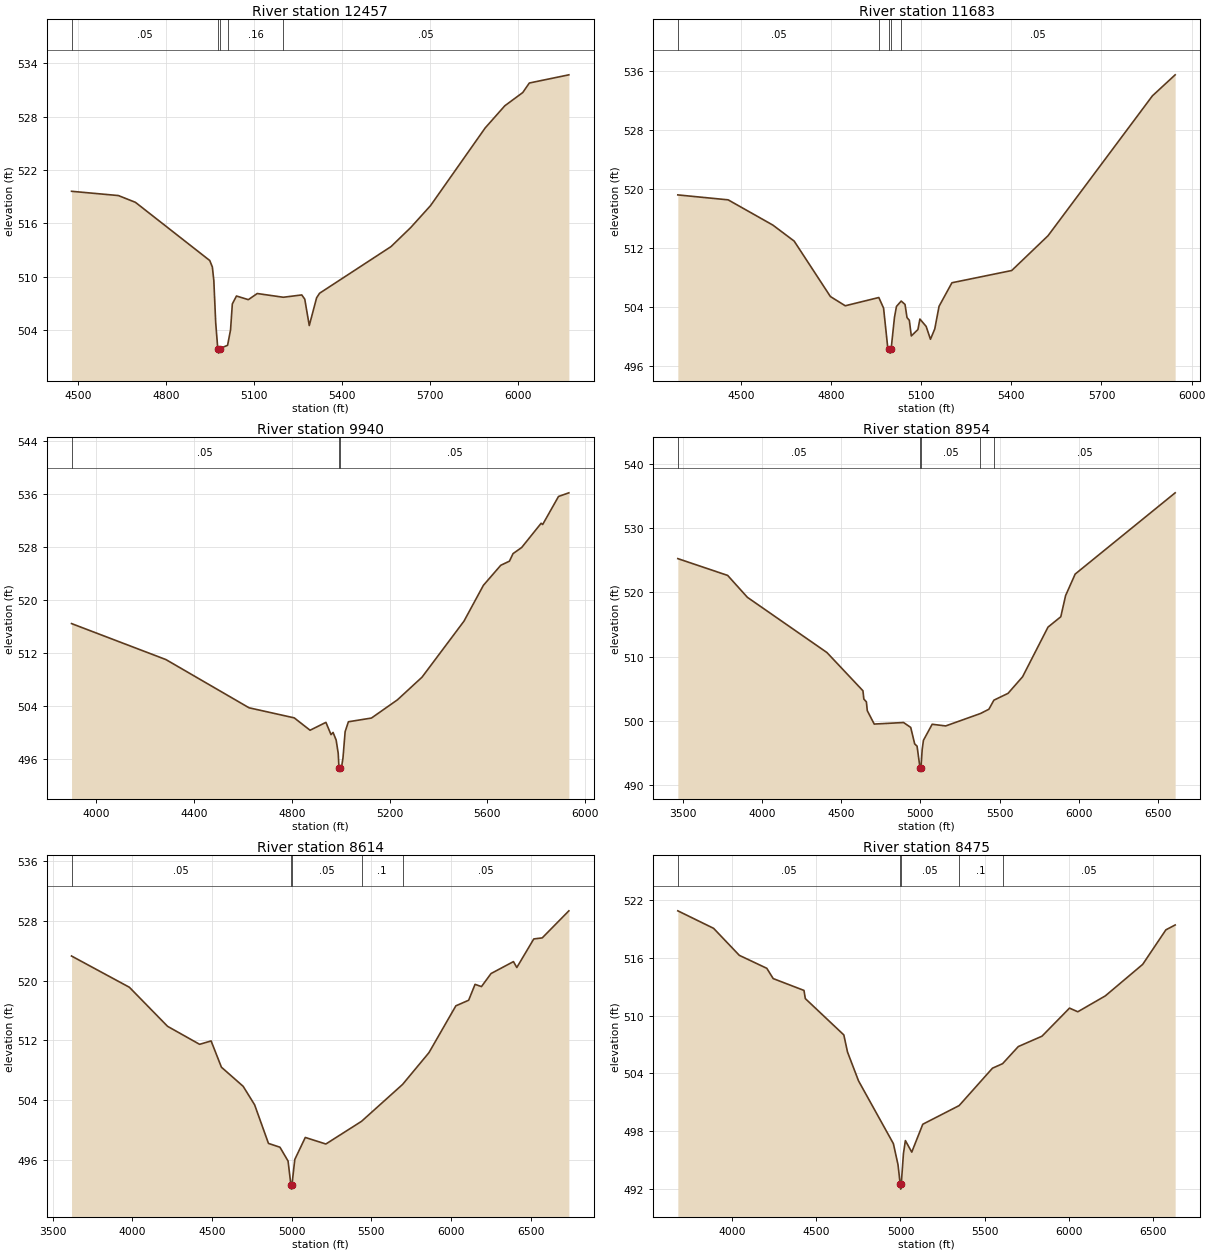
Type RM Length L Ch R = 1 ,12457   ,774,774,774
BEGIN DESCRIPTION:
UNT0021 IN CHRS 15.0
END DESCRIPTION:
XS GIS Cut Line= 3
      3415863.11     10588917.34      3415998.52     10588042.39
      3416356.66     10587315.72
#Sta/Elev= 30
  4478.3  519.61  4638.1  519.13  4696.1  518.37  4949.5  511.83  4958.4   511.1
  4963.4  509.59  4969.8  504.83  4976.9  501.92  4979.6  501.42  4982.9  501.92
  5010.3   502.3  5020.4  504.03  5026.5  506.95  5040.6  507.84  5081.1  507.43
  5111.4  508.12  5200.3   507.7  5263.2  507.96  5273.4  507.49  5288.8  504.52
  5313.8  507.64  5323.9  508.15  5567.4  513.39  5634.8  515.54  5702.2     518
  5888.5  526.73  5955.4  529.22  6016.6  530.71    6039  531.78  6173.8   532.7
#Mann= 5 ,-1 , 0
  4478.3     .05       0  4976.9    .035       0  4982.9     .05       0
  5010.3     .16       0  5200.3     .05       0
Bank Sta=4976.9,4982.9
XS Rating Curve= 0 ,0
Exp/Cntr=0.3,0.1

Type RM Length L Ch R = 1 ,11683   ,1743,1743,1743
BEGIN DESCRIPTION:
UNT0021 IN CHRS 13.0
END DESCRIPTION:
XS GIS Cut Line= 3
      3415982.88     10588959.07      3416290.18     10588625.72
       3417066.2     10587709.08
#Sta/Elev= 30
  4290.8  519.23  4458.3  518.56  4606.9  515.14  4677.8  512.97  4798.4  505.45
  4847.8   504.2  4959.4  505.32  4975.2  503.89  4989.5  498.38  4994.2  498.28
    4997  497.78  5000.2  498.28  5011.5  502.63  5018.1  504.11  5033.8  504.84
  5046.6  504.38  5053.2   502.6  5060.9  502.23  5067.5  500.11  5089.5  500.98
  5096.1   502.4  5116.9   501.4  5131.2  499.66  5145.5  501.06  5159.8  504.13
  5202.6  507.32  5401.5  508.98  5522.4   513.7  5869.5  532.66  5945.2  535.51
#Mann= 5 ,-1 , 0
  4290.8     .05       0  4959.4     .16       0  4994.2     .07       0
  5000.2     .16       0  5033.8     .05       0
Bank Sta=4994.2,5000.2
XS Rating Curve= 0 ,0
Exp/Cntr=0.3,0.1

Type RM Length L Ch R = 1 ,9940    ,986,986,986
BEGIN DESCRIPTION:
UNT0021 IN CHRS 12.0
END DESCRIPTION:
XS GIS Cut Line= 3
      3416248.52     10588938.22      3417144.35     10589047.59
      3417810.99     10588130.96
#Sta/Elev= 30
  3898.1  516.45  4284.5  511.01  4624.9  503.72  4809.7   502.2  4874.6  500.33
  4939.5  501.52  4960.4  499.66  4968.7     500  4981.3  498.85  4989.8  496.84
  4992.9  494.65  4995.7  494.15  4998.9  494.65  5004.4     495  5009.3  496.14
  5018.1  500.11  5031.5  501.61  5125.8  502.17  5232.4  504.93  5332.9  508.35
  5504.5  516.81  5584.1  522.23  5655.2  525.26  5690.7  525.88  5705.4  527.02
  5740.9  527.95  5820.5  531.61  5826.7  531.42  5891.6  535.66    5934  536.21
#Mann= 3 ,-1 , 0
  3898.1     .05       0  4992.9    .035       0  4998.9     .05       0
Bank Sta=4992.9,4998.9
XS Rating Curve= 0 ,0
Exp/Cntr=0.3,0.1

Type RM Length L Ch R = 1 ,8954    ,340,340,340
BEGIN DESCRIPTION:
UNT0021 IN CHRS 11.1
END DESCRIPTION:
XS GIS Cut Line= 4
      3416300.61     10590339.25       3417425.6     10589709.05
      3417967.27     10589505.93      3418133.86     10588246.07
#Sta/Elev= 30
  3469.1  525.23  3783.7  522.62  3908.1  519.22  4410.3  510.64  4637.5   504.7
  4643.2  503.41  4659.2  502.98  4664.9  501.61  4708.7  499.53  4893.7  499.77
    4939  499.01    4964  496.45  4979.1  496.09  4997.5  492.72  5000.2  492.22
  5003.5  492.72  5011.2  495.55  5019.1     497  5074.3   499.5  5159.8  499.24
  5379.1  501.17  5432.2  501.83  5463.8  503.24  5553.2   504.3    5645  506.88
  5805.4  514.59  5886.1   516.2  5916.4  519.49  5976.9  522.83  6607.9  535.45
#Mann= 5 ,-1 , 0
  3469.1     .05       0  4997.5    .035       0  5003.5     .05       0
  5379.1      .1       0  5463.8     .05       0
Bank Sta=4997.5,5003.5
XS Rating Curve= 0 ,0
Exp/Cntr=0.3,0.1

Type RM Length L Ch R = 1 ,8614    ,139,139,139
BEGIN DESCRIPTION:
UNT0021 IN CHRS 11.0
END DESCRIPTION:
XS GIS Cut Line= 3
      3416998.52      10591063.2      3418248.52     10589198.64
      3418326.51      10588325.1
#Sta/Elev= 30
  3618.4  523.29  3981.5   519.1  4221.3  513.86  4422.4  511.45  4494.5   511.9
  4559.3  508.38  4695.6  505.82  4767.6  503.34  4854.6  498.16  4926.7  497.65
  4977.7  495.79  4995.7  492.53  4998.5  492.03  5001.7  492.53  5019.7     496
  5085.7  498.96  5214.8  498.08  5438.6  501.12  5696.4  506.07  5861.9  510.33
  6030.8  516.61  6111.2  517.36  6151.3  519.49  6191.5  519.19  6251.7  520.94
  6392.3  522.54  6413.5  521.75  6519.9  525.58    6573  525.72  6740.2  529.35
#Mann= 5 ,-1 , 0
  3618.4     .05       0  4995.7     .03       0  5001.7     .05       0
  5438.6      .1       0  5696.4     .05       0
Bank Sta=4995.7,5001.7
XS Rating Curve= 0 ,0
Exp/Cntr=0.3,0.1

Type RM Length L Ch R = 1 ,8475    ,229,229,229
BEGIN DESCRIPTION:
UNT0021 IN CHRS 10.0
END DESCRIPTION:
XS GIS Cut Line= 2
      3417264.15      10591130.9      3418675.61     10588531.94
#Sta/Elev= 30
  3676.2  520.89  3888.9  519.07  4041.9  516.26  4205.4  514.91  4243.4  513.84
  4426.4  512.61  4434.4  511.76  4663.4  507.98  4685.3   506.2  4750.9   503.2
  4958.1  496.67  4985.6  494.48  4998.8  492.44  5001.5  491.94  5004.8  492.44
  5017.9  495.64  5029.5  496.99  5067.3  495.79  5132.9  498.69  5349.1  500.63
  5547.3  504.52  5607.5  504.99  5700.9  506.77  5841.9  507.85  6005.4  510.77
  6054.8  510.39  6218.2  512.04  6440.6  515.32  6578.4  518.91  6633.7  519.42
#Mann= 5 ,-1 , 0
  3676.2     .05       0  4998.8     .03       0  5004.8     .05       0
  5349.1      .1       0  5607.5     .05       0
Bank Sta=4998.8,5004.8
XS Rating Curve= 0 ,0
Exp/Cntr=0.3,0.1

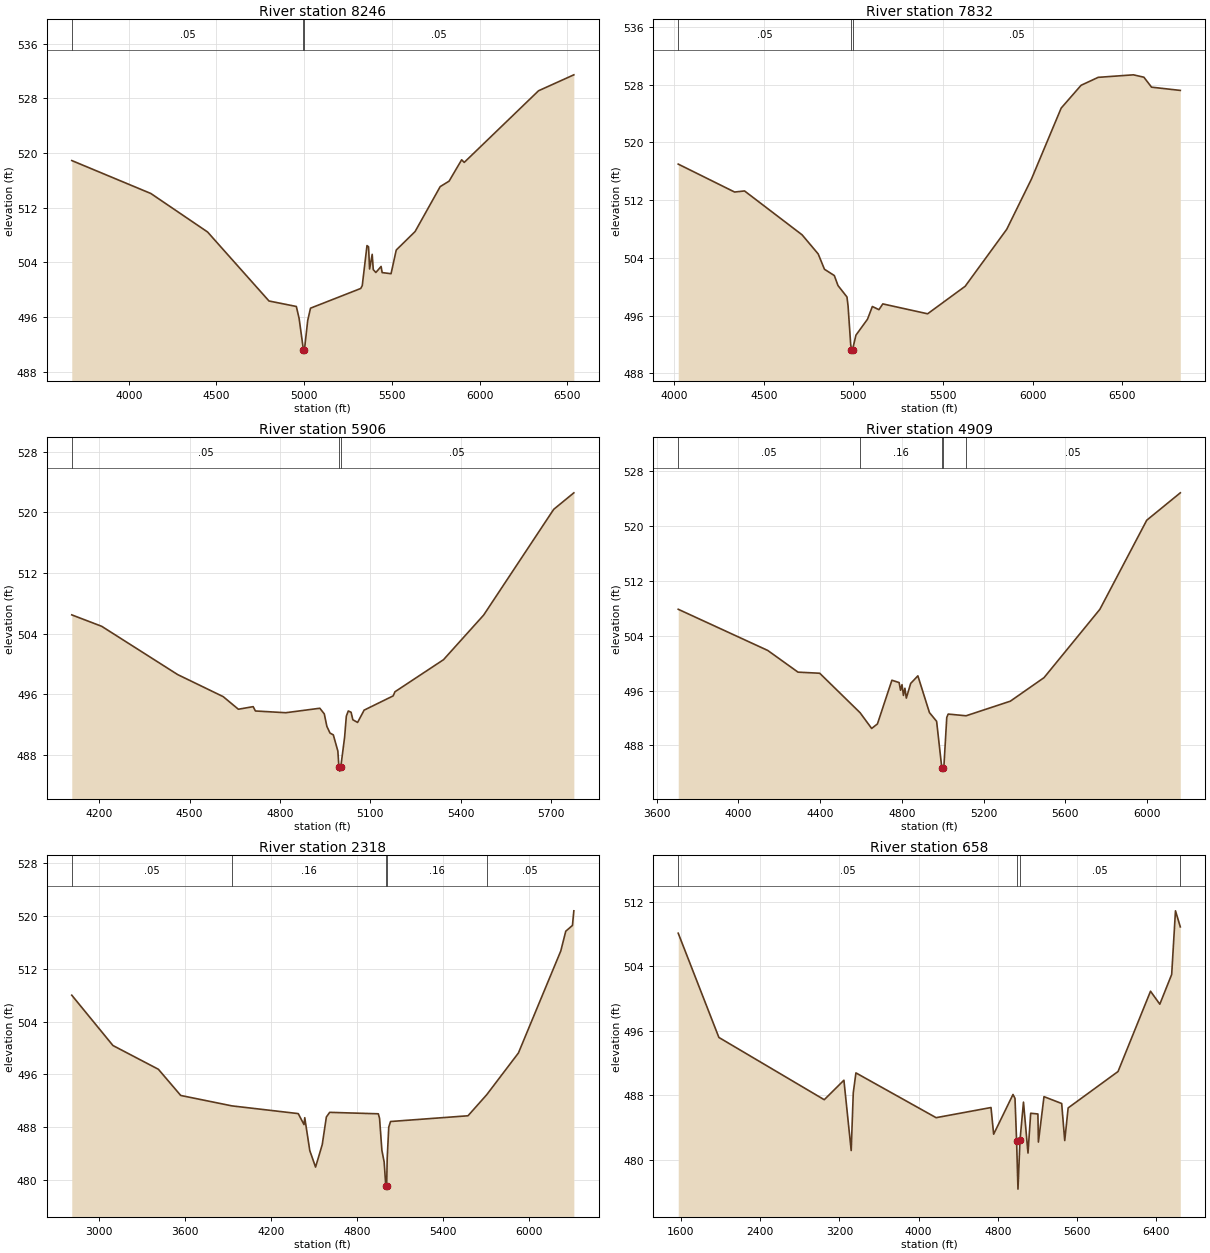
Type RM Length L Ch R = 1 ,8246    ,414,414,414
BEGIN DESCRIPTION:
UNT0021 IN CHRS 9.0
END DESCRIPTION:
XS GIS Cut Line= 3
      3417454.44     10591199.24      3418127.18     10590014.36
      3418982.21     10588781.72
#Sta/Elev= 30
  3674.9   518.9  4126.1  514.08  4449.1  508.46  4799.5  498.37  4955.3  497.57
  4971.2  495.82  4995.6  491.25  4998.3  490.75  5001.6  491.25  5020.2  495.53
  5036.1  497.32  5322.4   500.2  5331.2  500.62  5358.2  506.47    5367  506.29
  5373.1  503.05  5387.9  505.19    5394  502.95  5408.9  502.54  5438.6  503.42
  5444.7  502.52  5495.3  502.36    5525  505.82  5632.4  508.52  5775.6  515.09
  5826.3  515.89  5897.9  519.01  5912.7  518.63  6336.3   529.1  6537.6  531.43
#Mann= 3 ,-1 , 0
  3674.9     .05       0  4995.6     .04       0  5001.6     .05       0
Bank Sta=4995.6,5001.6
XS Rating Curve= 0 ,0
Exp/Cntr=0.3,0.1

Type RM Length L Ch R = 1 ,7832    ,1926,1926,1926
BEGIN DESCRIPTION:
UNT0021 IN CHRS 8.0
END DESCRIPTION:
XS GIS Cut Line= 4
       3417610.7     10591203.58      3417996.97     10590418.01
      3418574.23     10589983.98      3419190.55     10588950.99
#Sta/Elev= 30
  4023.1  516.99  4337.5  513.12    4393  513.27    4714  507.19  4803.9  504.54
  4838.7  502.42  4893.7  501.55  4914.3  500.16  4964.3  498.58  4970.5   497.3
  4985.1  491.98  4989.5   491.3  4992.3   490.8  4995.5   491.3  5014.3  493.29
  5078.8   495.5  5105.9  497.26  5142.6  496.82  5164.2  497.62  5414.1  496.25
  5623.5  500.06  5855.5  507.96  5993.7  514.94  6159.1  524.75  6270.1  527.91
  6365.4  529.01    6562  529.36  6620.4  529.03  6663.2  527.65  6823.6   527.2
#Mann= 3 ,-1 , 0
  4023.1     .05       0  4989.5     .03       0  4995.5     .05       0
Bank Sta=4989.5,4995.5
XS Rating Curve= 0 ,0
Exp/Cntr=0.3,0.1

Type RM Length L Ch R = 1 ,5906    ,997,997,997
BEGIN DESCRIPTION:
UNT0021 IN CHRS 5.0
END DESCRIPTION:
XS GIS Cut Line= 3
      3418842.12     10591591.62      3419342.11     10590891.64
      3419742.09     10590191.67
#Sta/Elev= 30
  4108.9  506.47  4208.4  504.96  4460.3   498.6  4611.5  495.69  4661.9  494.03
    4711  494.37  4718.4   493.8  4819.2  493.57  4932.2  494.16    4947  493.42
  4955.6  491.77    4966  490.89    4977  490.65  4992.1  488.51  4995.6  486.37
  4998.4  485.87  5001.6  486.37  5014.5  490.35  5020.2  493.13  5026.7   493.8
    5036  493.63  5041.8  492.64  5057.6  492.29  5079.2  493.91  5175.7  495.79
  5181.5  496.33  5342.7  500.56  5475.9  506.44  5708.4  520.38  5775.3  522.56
#Mann= 3 ,-1 , 0
  4108.9     .05       0  4995.6    .035       0  5001.6     .05       0
Bank Sta=4995.6,5001.6
XS Rating Curve= 0 ,0
Exp/Cntr=0.3,0.1

Type RM Length L Ch R = 1 ,4909    ,2591,2591,2591
BEGIN DESCRIPTION:
UNT0021 IN CHRS 3.0
END DESCRIPTION:
XS GIS Cut Line= 4
      3419217.27     10592146.55       3419800.6     10591573.64
      3420436.02     10590959.05       3420795.4     10590292.38
#Sta/Elev= 30
  3704.9  507.87  4143.2  501.86  4291.6  498.69  4397.8  498.53  4595.5  492.77
  4652.2  490.47  4680.5  491.13  4751.3  497.51  4786.7  497.17  4793.7  496.05
  4800.9  496.86  4807.8  495.29    4815  496.34    4822   494.9  4843.3  497.04
  4878.6  498.15  4935.2  492.79  4970.4  491.51  4995.7  484.74  4998.5  484.24
  5001.7  484.74  5005.9  484.84  5020.1  492.08    5027  492.57  5114.7  492.32
  5331.3  494.45  5496.6  497.89  5769.9  507.86  5999.5  520.87  6163.9  524.87
#Mann= 5 ,-1 , 0
  3704.9     .05       0  4595.5     .16       0  4995.7     .07       0
  5001.7     .16       0  5114.7     .05       0
Bank Sta=4995.7,5001.7
XS Rating Curve= 0 ,0
Exp/Cntr=0.3,0.1

Type RM Length L Ch R = 1 ,2318    ,1660,1660,1660
BEGIN DESCRIPTION:
UNT0021 IN CHRS 2.0
END DESCRIPTION:
XS GIS Cut Line= 4
      3419482.86     10592380.94      3421415.18     10591870.51
      3421279.77     10591511.14      3421066.21     10590412.13
#Sta/Elev= 30
  2811.4  508.02  3098.7  500.39  3415.6  496.79  3571.5  492.82  3928.5  491.24
  4391.2  490.07  4431.4   488.4  4436.6  489.45  4471.7  484.46    4512  481.96
  4558.6  485.37  4587.3  489.55  4610.3  490.26  4949.7  490.04  4958.4  489.35
  4974.6   484.5  4990.5  482.73  5001.8  479.12  5004.5  478.62  5007.8  479.12
  5011.8  483.32  5022.5  488.02    5035  488.87  5575.3  489.74  5705.8  492.93
    5927  499.26  6222.4  514.72  6257.3  517.72  6303.9   518.6  6313.6  520.81
#Mann= 5 ,-1 , 0
  2811.4     .05       0  3928.5     .16       0  5001.8     .07       0
  5007.8     .16       0  5705.8     .05       0
Bank Sta=5001.8,5007.8
XS Rating Curve= 0 ,0
Exp/Cntr=0.3,0.1

Type RM Length L Ch R = 1 ,658     ,0,0,0
BEGIN DESCRIPTION:
UNT0021 IN CHRS 1.0
END DESCRIPTION:
XS GIS Cut Line= 4
      3419581.86     10592630.92      3422467.27     10591693.43
      3422368.31     10590959.05      3421857.91     10589771.59
#Sta/Elev= 30
  1573.6  508.12  1983.9  495.18  3047.4  487.45  3245.7  489.87  3319.3  481.14
  3340.3  488.32    3367  490.78  4176.3  485.22  4730.4  486.48    4757  483.17
  4952.4   488.1  4972.5  487.62 4988.54  482.38  5002.6  476.35    5023  482.41
  5058.1  487.15  5103.7  480.83  5130.9  485.77  5203.7  485.68  5208.7  482.19
  5265.2  487.83  5443.6  486.98  5474.5  482.38  5508.9  486.43  6012.5  490.95
  6340.4  500.92  6434.1  499.31  6553.9     503  6592.2   510.9    6641  508.91
#Mann= 4 ,-1 , 0
  1573.6     .05       0 4988.54     .03       0    5023     .05       0
    6641     .05       0
Bank Sta=4988.54,5023
XS Rating Curve= 0 ,0
Exp/Cntr=0.3,0.1

Chan Stop Cuts=-1
Use User Specified Reach Order=0
Composite Channel Slope=5