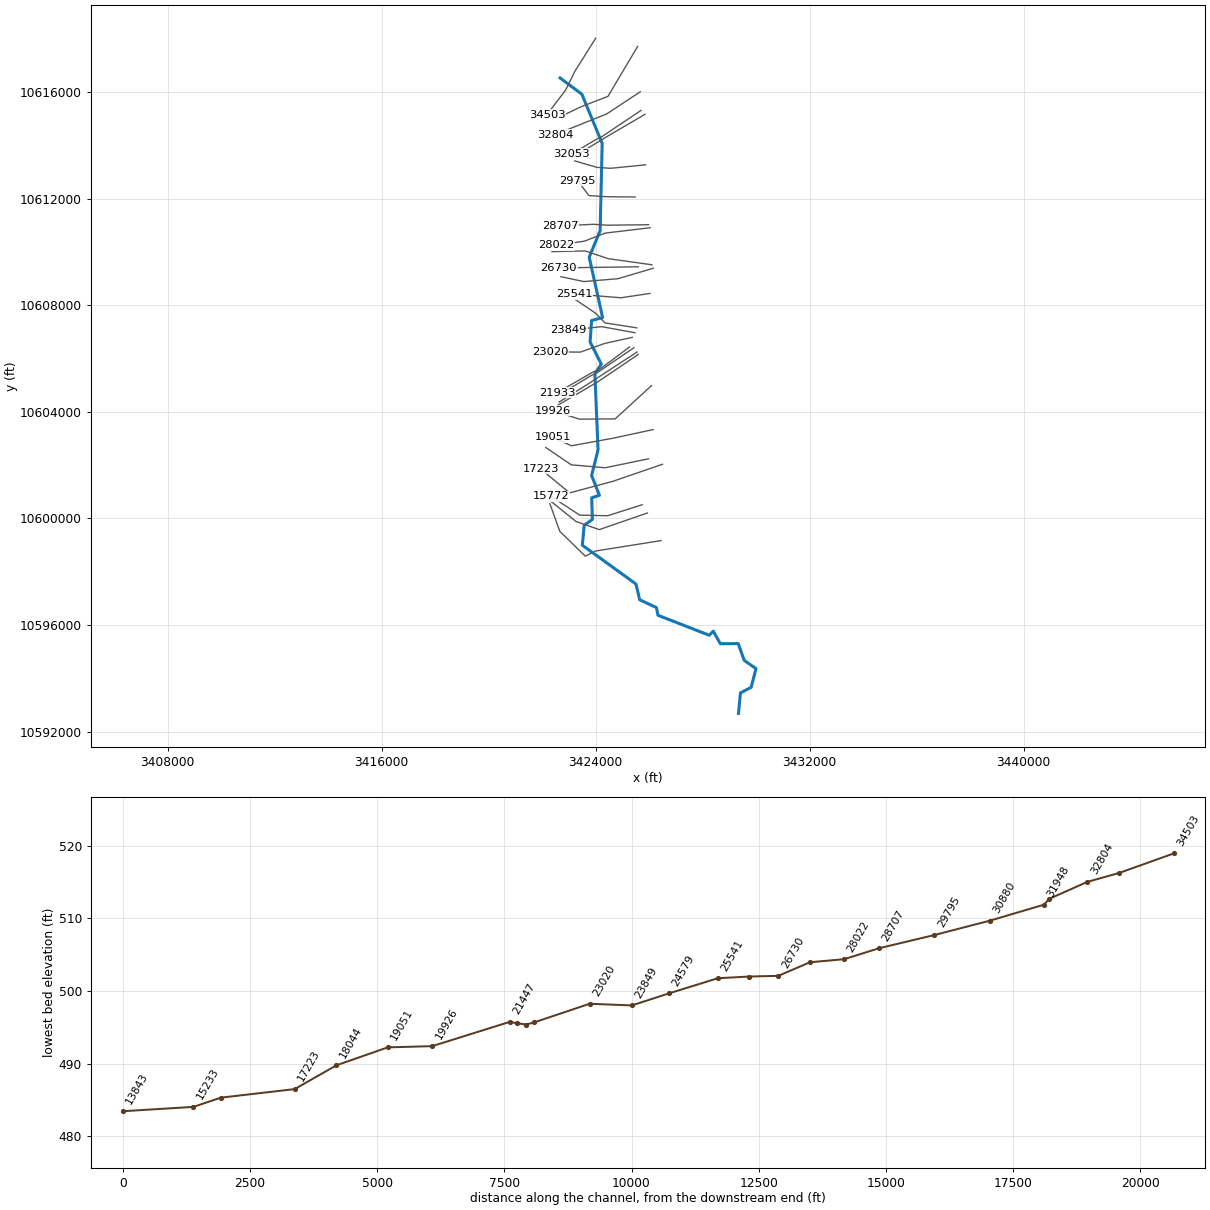
--- UNT0022 IN CHRS.prj (project) ---

Proj Title=UNT0022 IN CHRS Base Level Engineering
Current Plan=p01
Default Exp/Contr=0.3,0.1
English Units
Geom File=g01
Flow File=f01
Plan File=p01
Y Axis Title=Elevation
X Axis Title(PF)=Main Channel Distance
X Axis Title(XS)=Station
BEGIN DESCRIPTION:
UNT0022 IN CHRS
END DESCRIPTION:
DSS Export Rating Curves= 0
DSS Export Rating Curve Sorted= 0
DSS Export Volume Flow Curves= 0
DXF OffsetX= 0
DXF OffsetY= 0
DXF ScaleX= 1
DXF ScaleY= 10

--- UNT0022 IN CHRS.p01 (plan) ---

Plan Title=Multiple Run
Short Identifier=Multiple
Geom File=g01
Flow File=f01
Subcritical Flow
K Sum by GR= 0
Std Step Tol= 0.01
Critical Tol= 0.01
Num of Std Step Trials= 20
Max Error Tol= 0.3
Flow Tol Ratio= 0.001
Split Flow NTrial= 30
Split Flow Tol= 0.02
Split Flow Ratio= 0.02
Log Output Level= 0
Friction Slope Method= 1
Unsteady Friction Slope Method= 2
Unsteady Bridges Friction Slope Method= 1
Parabolic Critical Depth
Global Vel Dist=  1 , 1 , 1
Global Log Level= 0
CheckData=True
Encroach Param= -1, 0, 0, 0
BEGIN DESCRIPTION:
Multiple Run
END DESCRIPTION:

--- UNT0022 IN CHRS.f01 (steady flow) ---

Flow Title=Multiple
Number of Profiles=7
Profile Names=10-year,25-year,50-year,1pct_min,100-year,1pct_plu,500-year
River Rch & RM= UNT0022 IN CHRS,Reach-1,34503
     402     505     581     486     657     889     839
River Rch & RM= UNT0022 IN CHRS,Reach-1,33425
     547     696     807     680     919    1243    1191
River Rch & RM= UNT0022 IN CHRS,Reach-1,29795
     683     878    1024     867    1173    1587    1538
River Rch & RM= UNT0022 IN CHRS,Reach-1,28022
     865    1122    1317    1122    1517    2052    2010
River Rch & RM= UNT0022 IN CHRS,Reach-1,23020
     876    1135    1331    1133    1532    2071    2026
River Rch & RM= UNT0022 IN CHRS,Reach-1,19926
     991    1287    1513    1288    1742    2356    2309
River Rch & RM= UNT0022 IN CHRS,Reach-1,13843
    1047    1359    1595    1357    1835    2481    2426
Boundary for River Rch & Prof#=UNT0022 IN CHRS,Reach-1,1
Up Type=0
Dn Type=3
Dn Slope=0.005
Boundary for River Rch & Prof#=UNT0022 IN CHRS,Reach-1,2
Up Type=0
Dn Type=3
Dn Slope=0.005
Boundary for River Rch & Prof#=UNT0022 IN CHRS,Reach-1,3
Up Type=0
Dn Type=3
Dn Slope=0.005
Boundary for River Rch & Prof#=UNT0022 IN CHRS,Reach-1,4
Up Type=0
Dn Type=3
Dn Slope=0.005
Boundary for River Rch & Prof#=UNT0022 IN CHRS,Reach-1,5
Up Type=0
Dn Type=3
Dn Slope=0.005
Boundary for River Rch & Prof#=UNT0022 IN CHRS,Reach-1,6
Up Type=0
Dn Type=3
Dn Slope=0.005
Boundary for River Rch & Prof#=UNT0022 IN CHRS,Reach-1,7
Up Type=0
Dn Type=3
Dn Slope=0.005

--- UNT0022 IN CHRS.g01 (geometry) ---

Geom Title=Existing Conditions
Program Version=4.10

River Reach=UNT0022 IN CHRS ,Reach-1
Reach XY= 30
      3422674.01     10616530.39      3423486.53     10615923.91
      3424246.27     10614075.23      3424170.31     10610801.76
      3423761.72     10609805.41       3424262.6     10607538.78
       3423849.8     10607428.12      3423796.56     10606623.28
      3424213.23     10605791.04      3423974.51     10605436.22
      3424092.25     10602581.93      3423852.22     10601611.48
      3424142.53     10600866.35      3423854.56     10600774.45
      3423881.17     10599961.53      3423573.61      10599740.5
      3423505.52      10598992.7      3425508.22      10597538.9
      3425650.05     10596945.04      3426274.13     10596654.11
      3426332.56     10596364.01      3428249.21     10595614.05
      3428400.05     10595768.88      3428663.19     10595294.86
      3429332.11     10595301.64      3429557.02     10594669.43
      3429995.91     10594362.49      3429816.33     10593658.69
      3429415.35     10593450.79      3429342.11     10592681.64

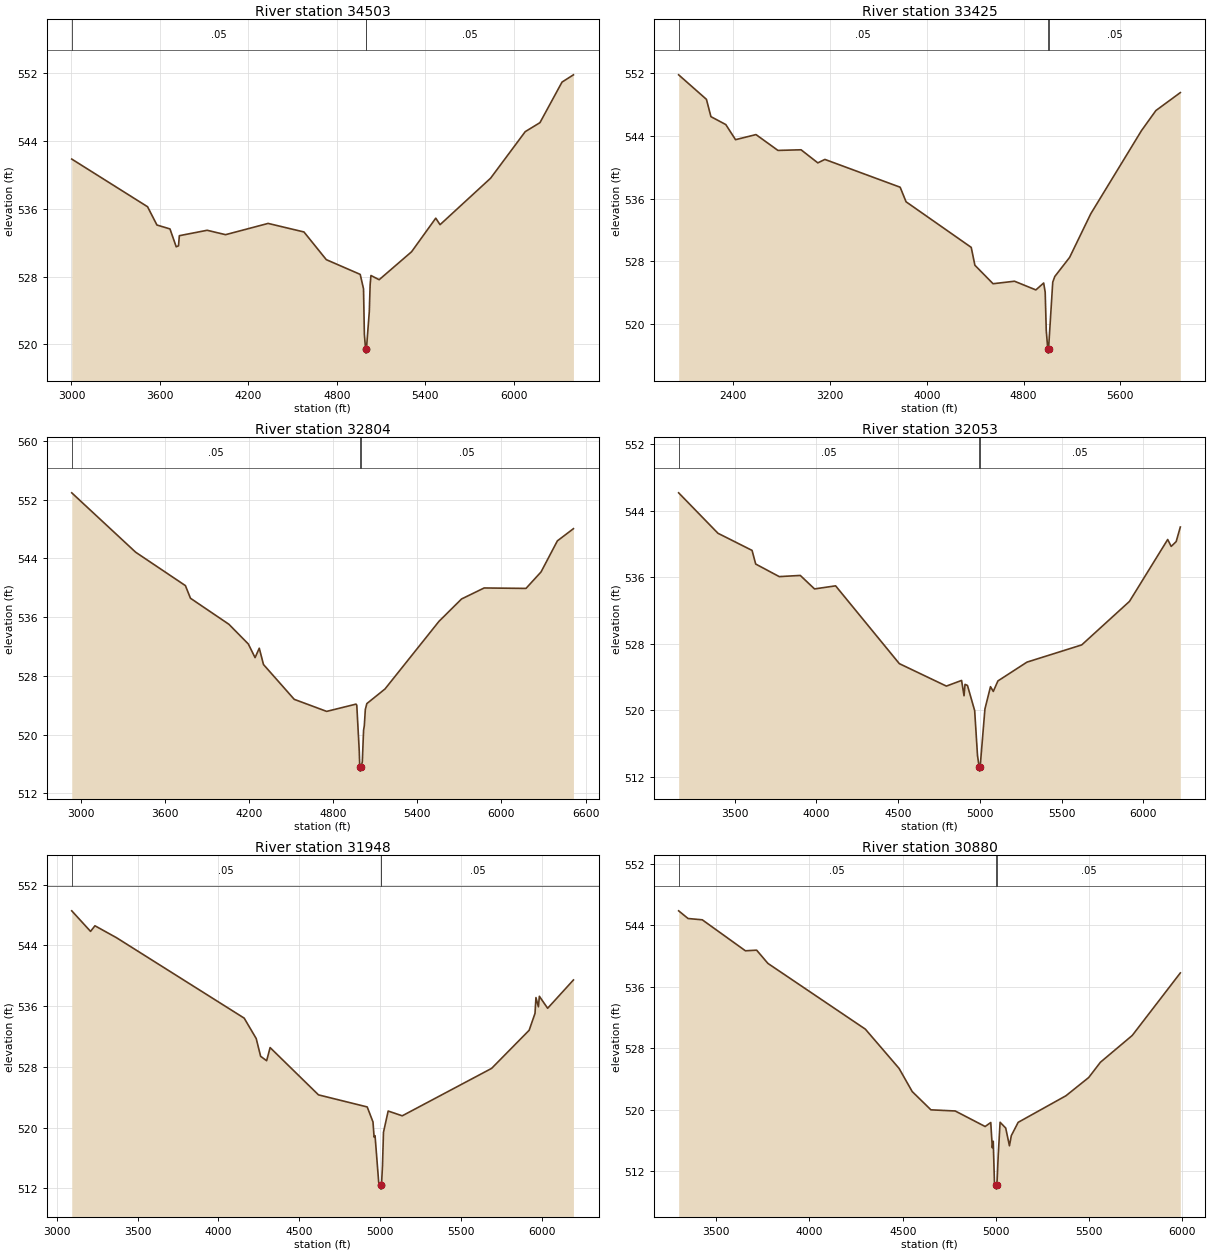
Type RM Length L Ch R = 1 ,34503   ,1078,1078,1078
BEGIN DESCRIPTION:
UNT0022 IN CHRS 47.0
END DESCRIPTION:
XS GIS Cut Line= 4
      3424001.89     10618019.76      3423229.34     10616787.16
      3422873.44     10616066.67      3422179.51     10615155.89
#Sta/Elev= 30
  3002.2  541.88  3516.5  536.25  3580.1  534.09  3668.5  533.63  3710.9  531.52
  3726.3  531.63  3732.2  532.83  3920.7  533.47  4045.6  532.95  4334.4  534.28
  4577.5  533.27    4729     530    4959  528.26  4981.5  526.56  4987.3  521.19
  4995.3  519.46  4998.1  518.96  5001.3  519.46  5020.7  523.86  5026.4  527.03
  5031.9  528.13  5087.6  527.63  5307.4  530.93  5471.6   534.9  5500.7  534.13
  5843.6  539.62  6078.6  545.12  6178.4  546.18    6328  550.97  6405.5  551.83
#Mann= 3 ,-1 , 0
  3002.2     .05       0  4995.3    .035       0  5001.3     .05       0
Bank Sta=4995.3,5001.3
XS Rating Curve= 0 ,0
Exp/Cntr=0.3,0.1

Type RM Length L Ch R = 1 ,33425   ,621,621,621
BEGIN DESCRIPTION:
UNT0022 IN CHRS 45.0
END DESCRIPTION:
XS GIS Cut Line= 4
       3425573.1     10617715.99      3424461.98     10615840.98
       3423472.4     10615459.03      3422656.79     10615068.58
#Sta/Elev= 30
  1950.8  551.79  2180.4  548.66  2217.5  546.45  2340.3  545.44  2420.8  543.51
  2589.8  544.16  2771.1  542.14  2962.1  542.22  3100.5  540.55    3159  540.99
  3780.8  537.44  3829.6  535.58  4367.9  529.76  4398.2  527.48  4548.2  525.12
  4725.3  525.44  4901.9  524.33  4966.3  525.21  4978.9  524.04  4987.7  519.14
  5000.5  516.76  5003.3  516.26  5006.5  516.76  5041.3  525.32  5058.1  526.04
  5180.6  528.48  5355.4  534.05  5774.5  544.67  5893.4  547.23  6095.3  549.52
#Mann= 3 ,-1 , 0
  1950.8     .05       0  5000.5    .035       0  5006.5     .05       0
Bank Sta=5000.5,5006.5
XS Rating Curve= 0 ,0
Exp/Cntr=0.3,0.1

Type RM Length L Ch R = 1 ,32804   ,751,751,751
BEGIN DESCRIPTION:
UNT0022 IN CHRS 45.1
END DESCRIPTION:
XS GIS Cut Line= 3
      3425671.85     10616014.59       3424413.2     10615181.28
      3422495.93     10614409.17
#Sta/Elev= 30
  2936.9  552.92  3392.3  544.84  3747.2  540.29  3783.3  538.57  4057.1  535.03
  4195.5  532.35  4243.8  530.49  4273.7  531.77  4303.8  529.55    4523  524.81
  4754.1  523.17  4963.5  524.16  4968.9  524.01  4986.6  517.74  4990.1  515.54
  4992.9  515.04  4996.1  515.54  5008.2  516.27  5017.3  520.61  5022.7  521.23
  5029.7  523.43  5040.5  524.23  5169.9  526.22  5554.5  535.42  5715.6  538.47
  5876.8  539.97    6175  539.91  6282.4  542.15  6398.8  546.38  6513.3  548.04
#Mann= 3 ,-1 , 0
  2936.9     .05       0  4990.1     .03       0  4996.1     .05       0
Bank Sta=4990.1,4996.1
XS Rating Curve= 0 ,0
Exp/Cntr=0.3,0.1

Type RM Length L Ch R = 1 ,32053   ,105,105,105
BEGIN DESCRIPTION:
UNT0022 IN CHRS 43.0
END DESCRIPTION:
XS GIS Cut Line= 4
      3425694.66     10615312.25      3424221.14     10614320.28
      3424032.34      10614231.3      3423100.25     10613677.36
#Sta/Elev= 30
  3157.7  546.15  3398.2  541.29  3606.8  539.23  3629.1  537.59  3773.1  536.08
    3902  536.22    3989   534.6    4118  534.97  4507.8  525.62  4795.7  522.92
  4888.7   523.6  4903.7  521.76  4909.7  523.13  4924.7     523  4968.8  519.97
  4986.1  514.58  4996.3   513.2    4999   512.7  5002.3   513.2  5031.6  520.18
  5065.6  522.85  5082.7  522.28    5111  523.54  5288.6   525.8  5623.7  527.87
  5915.9   533.1  6149.7  540.54  6171.1  539.71  6201.6  540.29    6227  542.04
#Mann= 3 ,-1 , 0
  3157.7     .05       0  4996.3    .035       0  5002.3     .05       0
Bank Sta=4996.3,5002.3
XS Rating Curve= 0 ,0
Exp/Cntr=0.3,0.1

Type RM Length L Ch R = 1 ,31948   ,1068,1068,1068
BEGIN DESCRIPTION:
UNT0022 IN CHRS 41.0
END DESCRIPTION:
XS GIS Cut Line= 4
      3425845.67     10615166.39      3424408.21     10614322.67
        3423653.     10613859.12      3423195.86     10613557.83
#Sta/Elev= 30
  3093.2  548.56  3209.4  545.85  3236.6  546.59  3369.6  545.02  4158.9  534.42
  4233.2  531.73  4260.5  529.39  4297.6  528.81  4319.1  530.54    4618  524.31
  4919.1  522.72  4954.9  520.74  4961.7  518.75  4967.6  518.93  4990.1   512.8
  5001.3  512.39    5004  511.89  5007.3  512.39  5013.5  514.94  5019.7  519.38
  5048.7  522.18  5135.7  521.55    5688   527.8  5919.9  532.82  5956.1  535.04
    5962  537.13  5977.1  535.92  5983.1   537.3  6034.3  535.72  6193.6  539.45
#Mann= 3 ,-1 , 0
  3093.2     .05       0  5001.3     .04       0  5007.3     .05       0
Bank Sta=5001.3,5007.3
XS Rating Curve= 0 ,0
Exp/Cntr=0.3,0.1

Type RM Length L Ch R = 1 ,30880   ,1085,1085,1085
BEGIN DESCRIPTION:
UNT0022 IN CHRS 39.0
END DESCRIPTION:
XS GIS Cut Line= 4
      3425868.28     10613271.54      3424557.47     10613141.32
      3424053.99     10613176.05      3423220.65      10613419.1
#Sta/Elev= 30
  3298.7   545.9  3349.2   544.9  3425.5  544.73  3656.7   540.7  3716.9  540.78
  3777.2  539.06  4299.8   530.5  4480.7  525.39    4551  522.38  4651.4     520
  4781.7  519.85  4942.1  517.83  4972.2  518.35  4980.6  515.06  4985.6  515.91
  4992.2  510.41  4999.2  510.18    5002  509.68  5005.2  510.18  5012.3   514.1
  5022.3  518.38  5052.4  517.63  5072.4  515.32  5082.4  516.64  5119.1  518.37
  5375.3  521.83  5497.6  524.21  5560.1  526.19  5730.9  529.68  5988.7  537.82
#Mann= 3 ,-1 , 0
  3298.7     .05       0  4999.2    .035       0  5005.2     .05       0
Bank Sta=4999.2,5005.2
XS Rating Curve= 0 ,0
Exp/Cntr=0.3,0.1

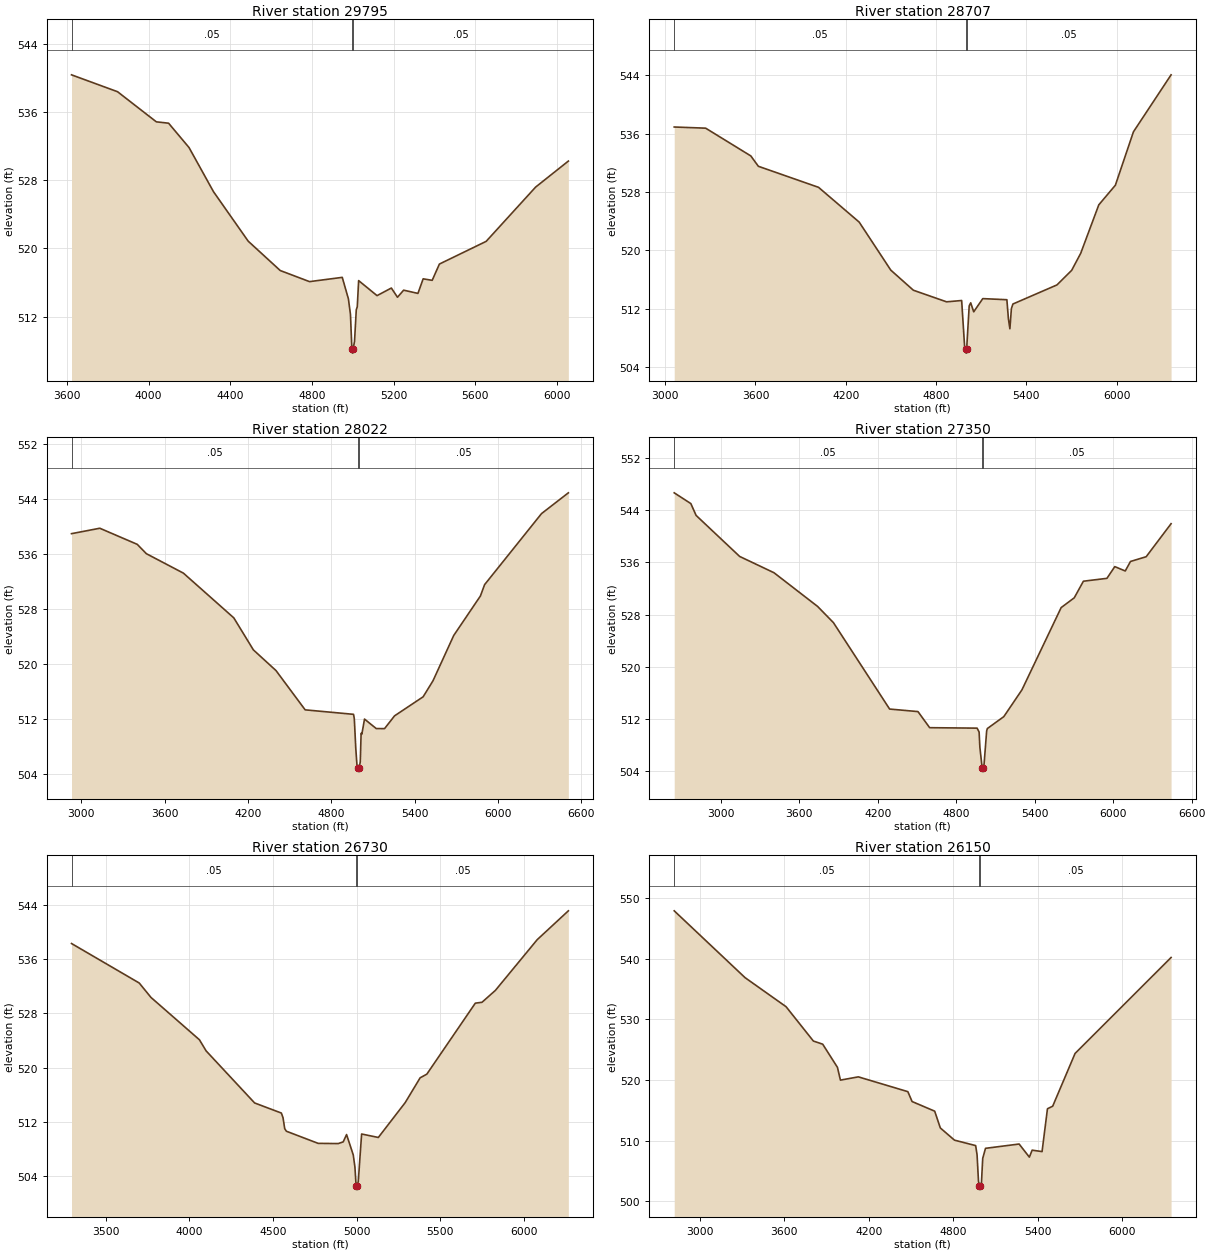
Type RM Length L Ch R = 1 ,29795   ,1088,1088,1088
BEGIN DESCRIPTION:
UNT0022 IN CHRS 36.0
END DESCRIPTION:
XS GIS Cut Line= 4
      3425477.61     10612064.93       3424453.3     10612073.61
      3423750.17     10612117.02      3423325.98     10612679.73
#Sta/Elev= 30
  3622.9  540.33  3848.4  538.35  4038.4  534.82  4098.4  534.66  4198.4  531.81
  4318.4  526.63  4488.4  520.83  4645.3  517.39  4788.7  516.09    4949  516.59
  4979.1  514.07  4989.1  512.26  4996.1  508.21  4998.9  507.71  5002.1  508.21
  5009.1  509.09  5017.6  512.78  5022.6  513.16  5029.2  516.21  5119.3  514.45
  5189.5  515.34  5219.5  514.26  5249.6  515.09  5319.7  514.71  5345.2  516.42
  5389.4  516.24  5424.8  518.15  5653.8  520.81    5896  527.17  6056.4  530.22
#Mann= 3 ,-1 , 0
  3622.9     .05       0  4996.1    .035       0  5002.1     .05       0
Bank Sta=4996.1,5002.1
XS Rating Curve= 0 ,0
Exp/Cntr=0.3,0.1

Type RM Length L Ch R = 1 ,28707   ,685,685,685
BEGIN DESCRIPTION:
UNT0022 IN CHRS 35.0
END DESCRIPTION:
XS GIS Cut Line= 4
      3425981.03     10611023.27      3424427.26     10611005.91
      3423923.78     10611040.63      3422682.36     10610978.79
#Sta/Elev= 30
  3060.3  536.92  3269.2  536.76  3569.3  532.95  3619.3  531.53  4019.3  528.64
  4289.3  523.87  4499.3  517.28  4649.4  514.52  4869.9  512.93  4970.2  513.11
  4990.2  506.69  4997.2  506.39    5000  505.89  5003.2  506.39  5020.3  512.38
  5030.3  512.79  5050.4  511.56  5110.5  513.37  5270.7  513.22  5280.7  510.63
  5290.7  509.23  5300.7     512  5310.8  512.63  5603.5  515.25  5701.2  517.25
  5761.3  519.59  5881.5  526.24  5991.6  528.93  6111.7  536.26  6361.8  544.08
#Mann= 3 ,-1 , 0
  3060.3     .05       0  4997.2    .035       0  5003.2     .05       0
Bank Sta=4997.2,5003.2
XS Rating Curve= 0 ,0
Exp/Cntr=0.3,0.1

Type RM Length L Ch R = 1 ,28022   ,672,672,672
BEGIN DESCRIPTION:
UNT0022 IN CHRS 34.0
END DESCRIPTION:
XS GIS Cut Line= 4
       3426041.8     10610910.42      3424366.49     10610710.77
      3423585.24     10610406.95      3422545.33     10610259.63
#Sta/Elev= 30
  2930.4  538.91  3133.9   539.7  3403.4  537.36  3469.1     536  3735.8  533.17
  4098.3  526.67  4239.3  522.01  4402.2     519  4611.9  513.29  4960.1  512.64
  4965.6     512  4976.3  507.66  4984.7  505.29  4994.8  504.88  4997.6  504.38
  5000.8  504.88  5008.5  505.73  5014.6  509.88  5019.9  509.75  5039.1  511.95
  5123.4  510.57  5183.2  510.56  5255.3  512.42    5461  515.19    5532  517.52
  5681.2  524.11  5873.1  529.85  5903.4   531.5    6313  541.83  6506.1  544.85
#Mann= 3 ,-1 , 0
  2930.4     .05       0  4994.8     .03       0  5000.8     .05       0
Bank Sta=4994.8,5000.8
XS Rating Curve= 0 ,0
Exp/Cntr=0.3,0.1

Type RM Length L Ch R = 1 ,27350   ,620,620,620
BEGIN DESCRIPTION:
UNT0022 IN CHRS 32.0
END DESCRIPTION:
XS GIS Cut Line= 4
      3426107.84     10609519.79      3424475.87     10609748.96
      3423607.81     10610040.63      3422371.66     10610012.85
#Sta/Elev= 30
  2642.5  546.69  2769.5  545.04  2809.9  543.22  3143.1  536.92  3405.7  534.42
  3738.9  529.25  3860.1  526.76  4289.9  513.49  4506.8   513.1  4596.1  510.63
  4959.1  510.56  4974.4  509.96  4980.2  507.64  4997.7  504.46  5000.4  503.96
  5003.7  504.46  5011.8   504.9  5032.2  510.14  5037.5   510.5  5163.5  512.33
    5302  516.44    5602  529.07  5702.1  530.57  5772.1  533.12  5952.1  533.56
  6012.1  535.36  6092.2  534.69  6132.2  536.15  6252.2  536.88  6442.7  541.95
#Mann= 3 ,-1 , 0
  2642.5     .05       0  4997.7     .03       0  5003.7     .05       0
Bank Sta=4997.7,5003.7
XS Rating Curve= 0 ,0
Exp/Cntr=0.3,0.1

Type RM Length L Ch R = 1 ,26730   ,580,580,580
BEGIN DESCRIPTION:
UNT0022 IN CHRS 31.0
END DESCRIPTION:
XS GIS Cut Line= 2
      3425597.26     10609445.71      3422625.57     10609402.33
#Sta/Elev= 30
  3294.7  538.32  3699.9  532.49  3769.9  530.37  4059.9  524.12  4099.9  522.48
    4390   514.8    4550  513.31    4560  512.62    4570  511.01    4580  510.63
    4770  508.84    4890  508.81    4920  509.06    4940  510.14    4980  507.14
    4990  505.35    4997  502.59  4999.8  502.09    5003  502.59    5010   503.2
    5030  510.22    5130  509.71  5290.7  514.85  5380.1  518.51  5420.1  519.05
  5710.1  529.52  5750.1  529.65  5830.1   531.4  6080.1  538.88  6266.7  543.14
#Mann= 3 ,-1 , 0
  3294.7     .05       0    4997    .035       0    5003     .05       0
Bank Sta=4997,5003
XS Rating Curve= 0 ,0
Exp/Cntr=0.3,0.1

Type RM Length L Ch R = 1 ,26150   ,609,609,609
BEGIN DESCRIPTION:
UNT0022 IN CHRS 30.0
END DESCRIPTION:
XS GIS Cut Line= 4
      3426153.79     10609388.71      3424840.89     10608998.09
       3423560.5     10608889.59      3422705.23     10609073.63
#Sta/Elev= 30
  2818.3   547.9  3321.3  536.88    3613  532.08  3806.7  526.42  3873.1   525.9
  3977.8  522.08    3999  519.97  4126.2  520.51  4477.9  518.07    4508  516.44
  4668.6  514.85  4708.7  512.08  4809.1  510.07  4959.6  509.17  4969.6  507.66
  4979.7   503.3  4986.7  502.49  4989.5  501.99  4992.7  502.49  4999.8   502.6
  5009.8  507.06  5029.5  508.72  5268.4  509.43    5341  507.27    5361  508.42
  5431.3  508.18  5469.7  515.25  5506.9  515.67  5665.8  524.37  6347.9   540.2
#Mann= 3 ,-1 , 0
  2818.3     .05       0  4986.7    .035       0  4992.7     .05       0
Bank Sta=4986.7,4992.7
XS Rating Curve= 0 ,0
Exp/Cntr=0.3,0.1

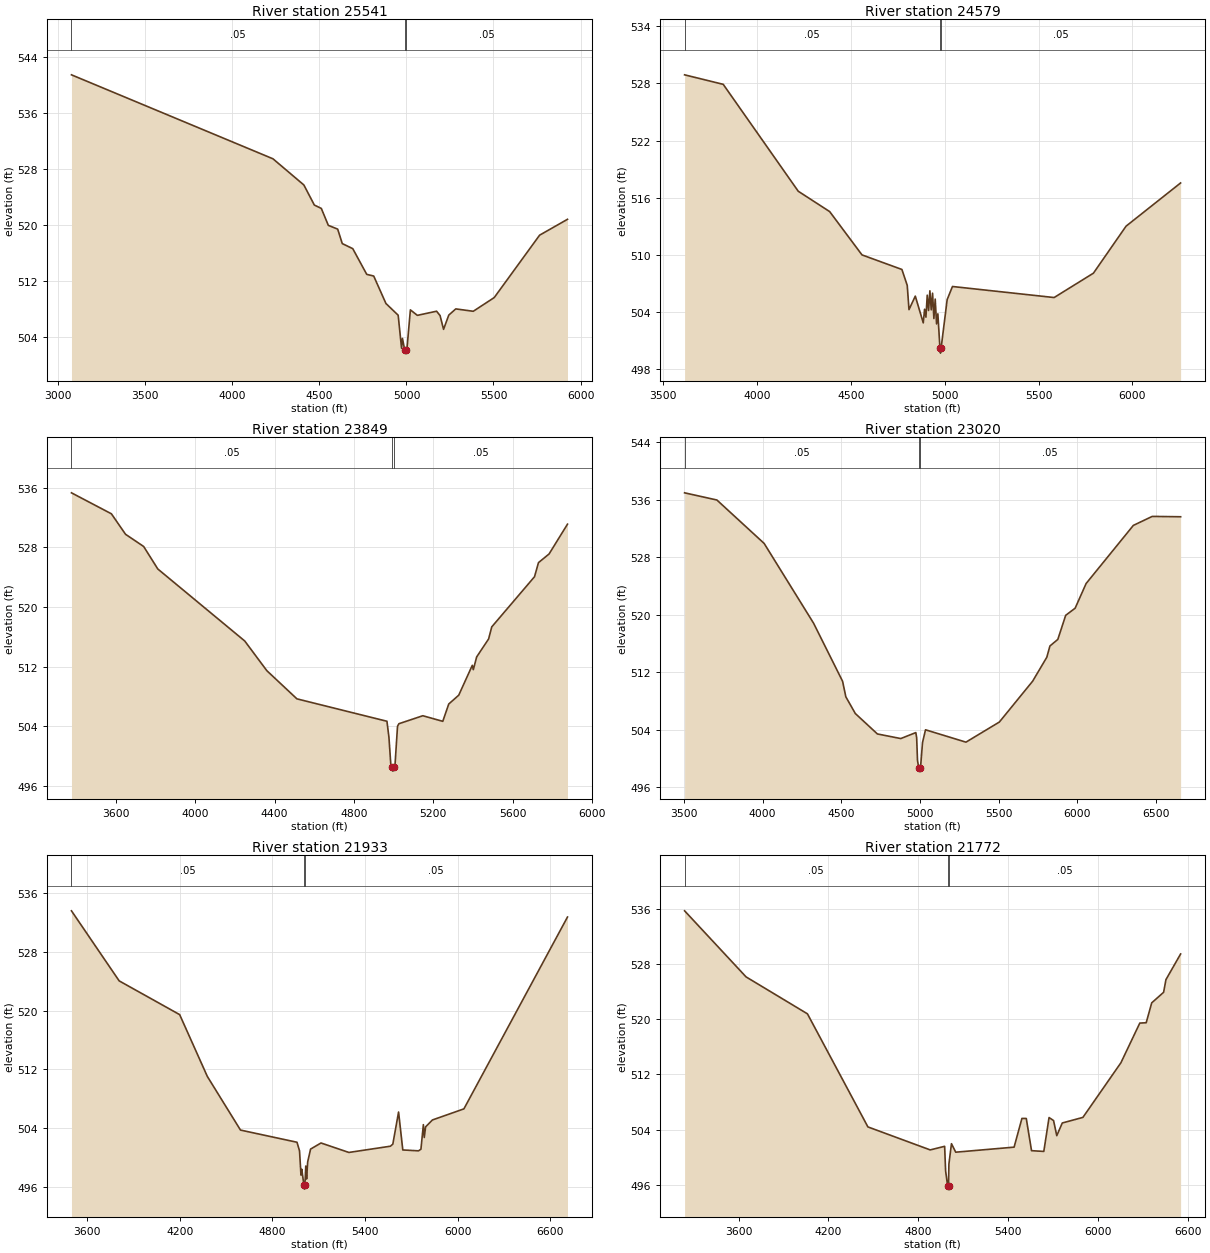
Type RM Length L Ch R = 1 ,25541   ,962,962,962
BEGIN DESCRIPTION:
UNT0022 IN CHRS 28.0
END DESCRIPTION:
XS GIS Cut Line= 3
       3426034.5     10608444.71      3424949.39     10608281.95
      3423202.43     10608423.01
#Sta/Elev= 30
  3075.2   541.4  4232.9  529.44  4410.5  525.71  4470.7  522.85  4510.8  522.37
    4551  519.96  4604.8  519.42  4631.2  517.36  4691.4  516.64  4771.7  512.98
  4811.8  512.74    4882  508.83  4952.3  507.16  4971.8  502.46  4976.8  503.86
  4989.4  502.26  4992.1  501.76  4995.4  502.26  5002.4  502.27  5022.5  507.92
  5062.6  507.14    5173  507.73    5193  507.11  5213.1  505.15  5243.2  507.18
  5283.3  508.06  5383.7  507.72  5504.1  509.67  5764.9  518.56  5925.1  520.82
#Mann= 3 ,-1 , 0
  3075.2     .05       0  4989.4    .035       0  4995.4     .05       0
Bank Sta=4989.4,4995.4
XS Rating Curve= 0 ,0
Exp/Cntr=0.3,0.1

Type RM Length L Ch R = 1 ,24579   ,730,730,730
BEGIN DESCRIPTION:
UNT0022 IN CHRS 26.0
END DESCRIPTION:
XS GIS Cut Line= 4
      3425535.37     10607153.47       3424352.6     10607337.94
      3423994.53     10607706.86      3423224.15     10608227.68
#Sta/Elev= 30
  3615.5  528.91  3821.2  527.91  4220.6  516.68    4388  514.54  4560.1  509.99
  4772.6  508.46    4801  506.79  4810.3  504.24  4843.9  505.66  4886.3  502.85
  4893.3  504.28  4900.5  503.45  4907.5  505.76  4914.6  504.15  4921.6  506.22
  4928.8  504.22  4935.8  505.97  4942.9   503.3  4949.9  505.35  4957.1  502.74
  4964.1   503.8  4975.2  500.17  4977.9  499.67  4981.2  500.17  5013.5  505.29
  5041.8  506.67  5583.1  505.51  5792.4  508.07  5966.2  513.01  6256.6  517.55
#Mann= 3 ,-1 , 0
  3615.5     .05       0  4975.2     .03       0  4981.2     .05       0
Bank Sta=4975.2,4981.2
XS Rating Curve= 0 ,0
Exp/Cntr=0.3,0.1

Type RM Length L Ch R = 1 ,23849   ,829,829,829
BEGIN DESCRIPTION:
UNT0022 IN CHRS 25.0
END DESCRIPTION:
XS GIS Cut Line= 3
      3425470.19     10606969.02      3424233.25     10607196.88
      3422996.73     10607066.72
#Sta/Elev= 30
    3376  535.29  3577.4  532.48  3648.6  529.74  3740.1   528.1  3811.3  525.09
  4249.8  515.44    4361  511.47  4512.9  507.69  4966.7  504.69  4976.8  502.55
  4986.8  498.67  4993.9  498.51  4996.6  498.01  4999.9  498.51  5006.9  498.62
  5020.1  504.02  5027.1  504.36  5147.7  505.43  5248.3  504.68  5278.4     507
  5328.7  508.18  5397.1  512.18  5402.2   511.6  5419.2  513.31  5479.5  515.72
  5495.2  517.33  5710.8  524.05  5730.9  525.94  5784.3   527.1  5877.1  531.09
#Mann= 3 ,-1 , 0
    3376     .05       0  4993.9    .035       0  4999.9     .05       0
Bank Sta=4993.9,4999.9
XS Rating Curve= 0 ,0
Exp/Cntr=0.3,0.1

Type RM Length L Ch R = 1 ,23020   ,1087,1087,1087
BEGIN DESCRIPTION:
UNT0022 IN CHRS 22.0
END DESCRIPTION:
XS GIS Cut Line= 4
      3425372.53     10606795.39      3424341.75     10606567.54
       3423430.3     10606242.02      3422301.85     10606252.87
#Sta/Elev= 30
    3504  536.95  3709.3  535.95  4009.6  529.91  4323.8  518.81  4508.1  510.73
  4528.6  508.58  4588.9  506.25  4729.2  503.41  4877.8  502.77  4973.3   503.6
  4978.7   502.9    4984  499.73  4991.7  498.74  4994.4  498.24  4997.7  498.74
  5004.1  498.95  5015.9  502.21  5034.9  503.99    5292  502.27  5504.3  505.07
  5715.7  510.75  5805.7  514.08  5825.7  515.65  5875.7  516.56  5925.7  519.91
  5985.7   520.9  6055.7  524.34  6355.7  532.42  6475.7  533.67    6656  533.62
#Mann= 3 ,-1 , 0
    3504     .05       0  4991.7     .03       0  4997.7     .05       0
Bank Sta=4991.7,4997.7
XS Rating Curve= 0 ,0
Exp/Cntr=0.3,0.1

Type RM Length L Ch R = 1 ,21933   ,161,161,161
BEGIN DESCRIPTION:
UNT0022 IN CHRS 20.1
END DESCRIPTION:
XS GIS Cut Line= 4
       3425271.3     10606434.08      3424121.12      10605574.7
      3423921.47     10605505.25       3422567.3     10604719.66
#Sta/Elev= 30
  3499.4  533.62  3808.4  524.07  4200.2  519.47  4379.5  511.04  4594.2  503.73
  4960.1  502.07  4976.5   500.9    4986  497.59  4991.2  498.39  5005.2  496.18
    5008  495.68  5011.2  496.18  5017.1  498.83  5022.3  497.06  5029.4   499.4
  5048.2  501.14  5115.7  501.97  5296.1  500.68    5565  501.53  5580.8  501.81
  5618.1  506.19  5645.4  501.02  5747.2   500.9  5762.9  501.12  5778.7  504.47
  5784.5  502.72  5793.2  504.17  5837.5  505.11  6041.2  506.62  6712.1  532.77
#Mann= 3 ,-1 , 0
  3499.4     .05       0  5005.2     .03       0  5011.2     .05       0
Bank Sta=5005.2,5011.2
XS Rating Curve= 0 ,0
Exp/Cntr=0.3,0.1

Type RM Length L Ch R = 1 ,21772   ,187,187,187
BEGIN DESCRIPTION:
UNT0022 IN CHRS 20.0
END DESCRIPTION:
XS GIS Cut Line= 4
      3425436.19       10606408.        3424043.     10605457.51
      3423821.64     10605353.34      3422641.06     10604637.18
#Sta/Elev= 30
  3239.8  535.69  3650.3  526.12  4060.1  520.77  4463.9  504.39  4879.8  501.06
  4976.2  501.58  4982.6  498.02    4996  495.88  4998.7  495.38    5002  495.88
  5004.7  499.02  5021.8  501.96  5050.1  500.73  5439.9  501.46  5492.2  505.62
  5521.3  505.61  5556.4  500.95  5638.3  500.84  5673.4  505.75  5703.5  505.31
  5724.9  503.12  5761.7  504.96  5899.4  505.77  6153.3  513.69  6279.3  519.43
    6322  519.48  6358.8  522.36  6438.3  523.89  6453.8  525.72  6551.8  529.44
#Mann= 3 ,-1 , 0
  3239.8     .05       0    4996    .035       0    5002     .05       0
Bank Sta=4996,5002
XS Rating Curve= 0 ,0
Exp/Cntr=0.3,0.1

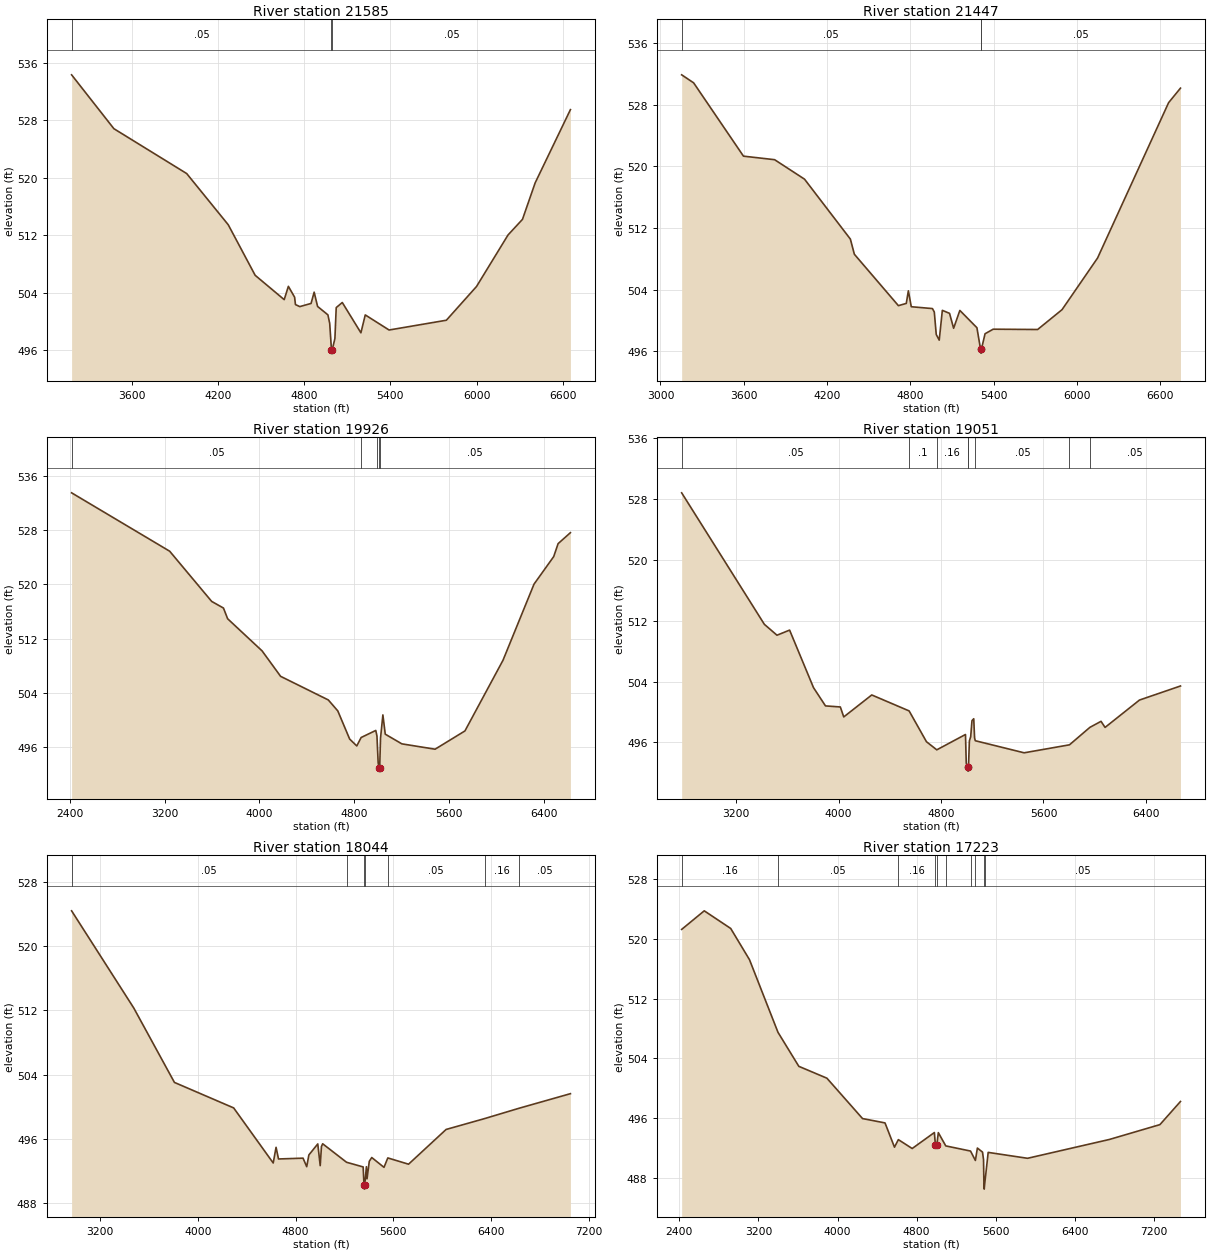
Type RM Length L Ch R = 1 ,21585   ,138,138,138
BEGIN DESCRIPTION:
UNT0022 IN CHRS 17.0
END DESCRIPTION:
XS GIS Cut Line= 3
      3425553.42     10606247.45      3423678.41     10605019.14
      3422636.92     10604368.21
#Sta/Elev= 30
  3182.4  534.33  3476.4  526.83  3982.9  520.58  4271.9  513.45  4459.2  506.41
  4661.2  503.02  4690.3  504.87  4733.6  503.36  4739.5  502.33  4769.7  502.05
  4848.1  502.49  4869.6  504.06  4893.4  502.07  4965.2   500.9  4977.7  499.71
  4989.8  496.07  4992.6  495.57  4995.8  496.07  5013.9   497.6    5023  501.91
  5065.2  502.62  5194.8   498.4    5225  500.89  5390.8  498.79  5789.1  500.15
    5999  504.85  6218.3  512.03  6318.6   514.2    6407  519.29  6652.1  529.48
#Mann= 3 ,-1 , 0
  3182.4     .05       0  4989.8     .04       0  4995.8     .05       0
Bank Sta=4989.8,4995.8
XS Rating Curve= 0 ,0
Exp/Cntr=0.3,0.1

Type RM Length L Ch R = 1 ,21447   ,1521,1521,1521
BEGIN DESCRIPTION:
UNT0022 IN CHRS 17.1
END DESCRIPTION:
XS GIS Cut Line= 3
      3425596.79     10606156.28      3424099.42     10605136.33
      3422562.96     10604233.55
#Sta/Elev= 30
    3153  531.91  3239.2  530.87  3598.4  521.34  3822.7  520.88  4038.2  518.35
  4368.6  510.56  4397.3  508.59  4714.5  501.91  4771.4   502.2  4786.3  503.84
  4807.3  501.77  4959.8  501.53  4973.2  501.08  4987.2  498.16  5008.7  497.43
  5031.2   501.3    5083  500.91  5112.4  498.97  5157.3  501.29  5280.3  499.04
  5306.6  496.24  5309.3  495.74  5312.6  496.24  5338.9  498.26  5397.5  498.85
  5717.8  498.81  5893.6  501.39  6149.5   508.1  6661.3  528.29  6746.8  530.18
#Mann= 3 ,-1 , 0
    3153     .05       0  5306.6    .035       0  5312.6     .05       0
Bank Sta=5306.6,5312.6
XS Rating Curve= 0 ,0
Exp/Cntr=0.3,0.1

Type RM Length L Ch R = 1 ,19926   ,875,875,875
BEGIN DESCRIPTION:
UNT0022 IN CHRS 16.0
END DESCRIPTION:
XS GIS Cut Line= 4
      3426088.71     10604983.33      3424732.38     10603735.51
      3423397.74     10603724.66      3422421.18     10604039.33
#Sta/Elev= 30
  2416.8  533.53  3243.4   524.9  3597.3  517.48  3696.6   516.5  3731.7  514.92
  4022.1  510.17  4178.1  506.41  4580.1  502.92  4660.1   501.3  4760.1  497.14
  4820.1  496.12  4856.9  497.37  4980.1  498.41  4990.1   497.6  4994.6  495.84
  5000.1  493.68  5007.1   492.9  5009.9   492.4  5013.1   492.9  5020.1  497.25
  5040.1  500.71  5060.1  497.86  5200.1  496.43  5480.1  495.64  5731.6  498.34
  6052.2  508.78  6313.9  520.04  6479.5   524.1  6516.8  526.02  6620.5  527.64
#Mann= 5 ,-1 , 0
  2416.8     .05       0  4856.9     .16       0  4994.6     .05       0
  5007.1    .035       0  5013.1     .05       0
Bank Sta=5007.1,5013.1
XS Rating Curve= 0 ,0
Exp/Cntr=0.3,0.1

Type RM Length L Ch R = 1 ,19051   ,1007,1007,1007
BEGIN DESCRIPTION:
UNT0022 IN CHRS 13.0
END DESCRIPTION:
XS GIS Cut Line= 4
       3426153.8     10603334.03      3424645.57     10603008.51
      3423093.92     10602726.39      3422388.66      10603051.9
#Sta/Elev= 30
  2773.7  528.84  3419.9  511.54  3518.4  510.11    3617  510.78  3803.8  503.21
  3897.3  500.81  4013.3  500.67    4040  499.36  4258.8  502.25  4550.7  500.15
  4686.1   496.1  4766.7  495.03    4991  497.05    4997  493.27  5008.3  492.73
  5011.1  492.23  5014.3  492.73  5021.5   496.2  5031.7  496.76  5041.8  498.87
  5055.4  499.12  5062.1  496.59  5067.4  496.23  5449.3  494.64  5803.4  495.69
    5963  497.99  6049.9  498.78  6081.4  497.98  6350.3  501.58  6670.5  503.43
#Mann= 8 ,-1 , 0
  2773.7     .05       0  4550.7      .1       0  4766.7     .16       0
  5008.3     .07       0  5014.3     .16       0  5067.4     .05       0
  5803.4     .16       0    5963     .05       0
Bank Sta=5008.3,5014.3
XS Rating Curve= 0 ,0
Exp/Cntr=0.3,0.1

Type RM Length L Ch R = 1 ,18044   ,821,821,821
BEGIN DESCRIPTION:
UNT0022 IN CHRS 12.0
END DESCRIPTION:
XS GIS Cut Line= 4
      3425980.22     10602238.11      3424363.46     10601901.74
      3423093.92     10602010.25      3422139.09     10602661.27
#Sta/Elev= 30
  2968.1  524.37  3476.9  512.28  3809.4  503.03    4294  499.86  4617.6  493.01
  4640.9  494.96    4661  493.51  4861.7  493.61  4891.8  492.55  4909.4  494.01
  4982.2  495.38  5002.2  492.68  5012.3  495.06  5022.3   495.4  5217.7   493.1
  5353.5  492.52  5360.5  490.26  5363.3  489.76  5366.5  490.26  5380.1  492.55
  5385.1  491.04  5403.7  493.22  5423.8  493.69  5524.1  492.47  5555.2  493.64
  5724.9  492.86  6032.1  497.18  6346.8  498.53  6629.5  499.82  7049.3  501.63
#Mann= 7 ,-1 , 0
  2968.1     .05       0  5217.7     .16       0  5360.5    .035       0
  5366.5     .16       0  5555.2     .05       0  6346.8     .16       0
  6629.5     .05       0
Bank Sta=5360.5,5366.5
XS Rating Curve= 0 ,0
Exp/Cntr=0.3,0.1

Type RM Length L Ch R = 1 ,17223   ,1451,1451,1451
BEGIN DESCRIPTION:
UNT0022 IN CHRS 11.0
END DESCRIPTION:
XS GIS Cut Line= 4
      3426501.01     10602031.94      3424645.57     10601391.76
      3423028.82     10600957.73      3421944.75      10601857.5
#Sta/Elev= 30
  2423.2  521.27  2651.8  523.76  2919.2   521.4  3109.2  517.22  3397.4  507.49
  3608.3  502.93  3892.5  501.34  4252.9  495.93  4480.2  495.35  4575.9   492.1
  4615.2  493.11    4755  491.92  4979.4  494.06  4990.1  492.37 5003.96  492.37
  5019.4  494.05  5094.7  492.27  5345.2  491.58  5394.3  490.32  5414.6  491.98
  5466.4  491.44  5476.7  490.43  5480.8  486.98  5483.5  486.48  5486.8  486.98
  5523.8   491.4    5922  490.61  6749.1  493.13  7260.9  495.12  7468.8  498.22
#Mann= 10 ,-1 , 0
  2423.2     .16       0  3397.4     .05       0  4615.2     .16       0
  4990.1     .05       0 5003.96     .16       0  5094.7     .05       0
  5345.2     .16       0  5394.3     .05       0  5480.8     .07       0
  5486.8     .05       0
#XS Ineff= 2 , 0
       0 4979.45  493.98    5020       0  493.91
Permanent Ineff=
       T       T
Bank Sta=4990.1,5003.96
XS Rating Curve= 0 ,0
Exp/Cntr=0.3,0.1

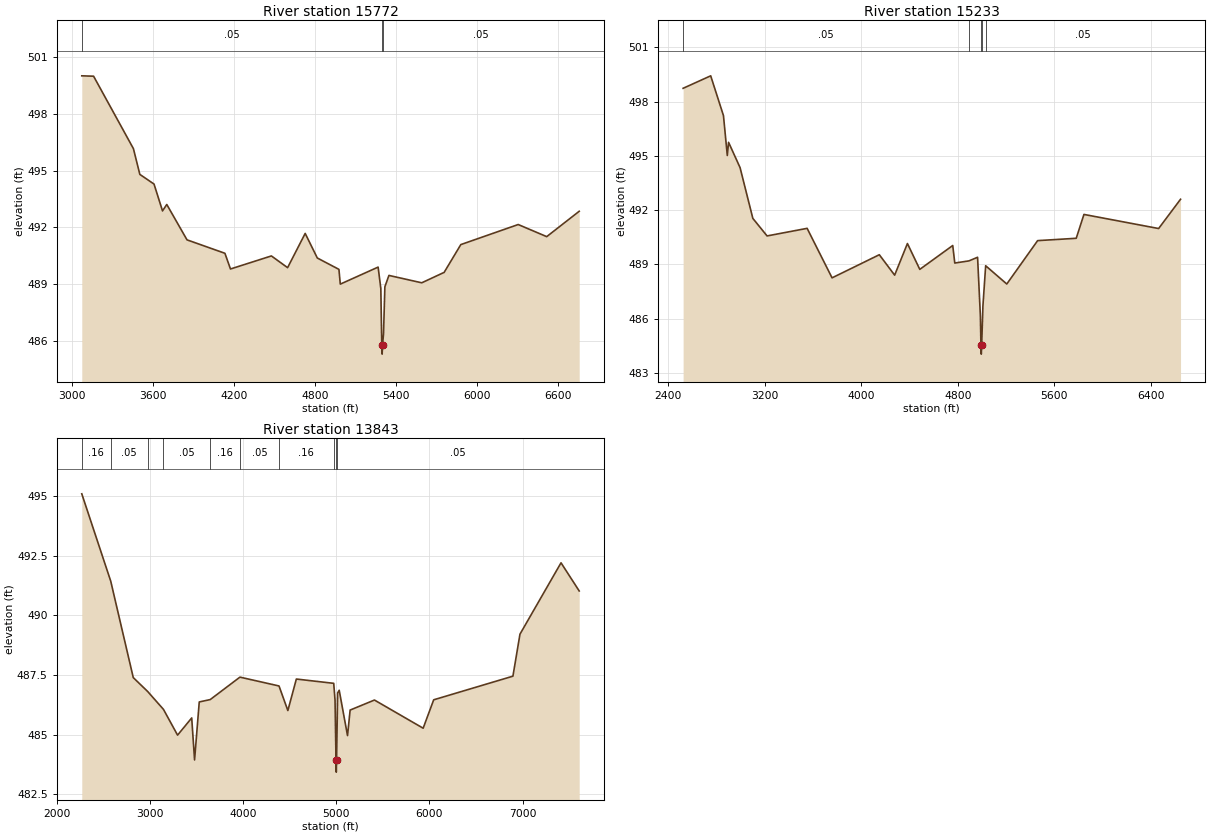
Type RM Length L Ch R = 1 ,15772   ,539,539,539
BEGIN DESCRIPTION:
UNT0022 IN CHRS 9.0
END DESCRIPTION:
XS GIS Cut Line= 4
       3425741.5     10600512.85      3424450.26     10600100.52
      3423408.59     10600122.23       3422334.4     10600827.51
#Sta/Elev= 30
  3075.3  500.01  3162.7  499.99  3457.6  496.16  3505.1   494.8    3610  494.29
    3673  492.87  3704.5  493.21  3854.3  491.34  4134.9  490.63  4176.1   489.8
  4478.9  490.49    4599  489.87  4729.2  491.68    4819  490.38    4979  489.78
    4989     489  5269.1   489.9  5289.1  488.77  5296.1   485.8  5298.9   485.3
  5302.1   485.8  5309.1  486.38  5319.1  488.86  5349.1  489.46  5592.1  489.07
  5757.8  489.62  5881.4  491.09  6306.2  492.15  6517.2  491.51  6757.7  492.85
#Mann= 3 ,-1 , 0
  3075.3     .05       0  5296.1    .035       0  5302.1     .05       0
Bank Sta=5296.1,5302.1
XS Rating Curve= 0 ,0
Exp/Cntr=0.3,0.1

Type RM Length L Ch R = 1 ,15233   ,1390,1390,1390
BEGIN DESCRIPTION:
UNT0022 IN CHRS 9.2
END DESCRIPTION:
XS GIS Cut Line= 4
      3425937.88     10600203.26      3424135.81     10599578.27
      3423266.02     10599885.56      3422261.72     10600697.32
#Sta/Elev= 30
  2523.7  498.74  2752.1  499.43  2857.9  497.23  2889.7  495.02  2900.3  495.75
  2995.5  494.35  3101.4  491.54  3219.2  490.57  3551.1  490.99  3757.6  488.25
  4149.2  489.53  4276.2   488.4  4382.1  490.15  4484.5  488.72  4757.5  490.04
  4774.4  489.07  4892.2  489.19  4963.3  489.39  4986.5  486.15  4991.2  484.53
  4993.9  484.03  4997.2  484.53  5007.7  486.71  5030.3  488.92  5205.3  487.91
  5460.8  490.31  5780.6  490.44  5844.6  491.76  6463.4  490.98  6644.9   492.6
#Mann= 5 ,-1 , 0
  2523.7     .05       0  4892.2     .16       0  4991.2     .07       0
  4997.2     .16       0  5030.3     .05       0
Bank Sta=4991.2,4997.2
XS Rating Curve= 0 ,0
Exp/Cntr=0.3,0.1

Type RM Length L Ch R = 1 ,13843   ,0,0,0
BEGIN DESCRIPTION:
UNT0022 IN CHRS 9.1
END DESCRIPTION:
XS GIS Cut Line= 5
      3426448.29      10599166.8      3424000.39     10598776.18
      3423614.98     10598583.47      3422661.85     10599515.77
      3422292.06     10600552.23
#Sta/Elev= 30
  2265.4  495.09  2576.4  491.43  2818.5  487.39  2972.7  486.81  3142.7  486.06
  3294.4  484.98  3446.3   485.7    3477  483.94  3527.3  486.37  3645.3  486.47
  3964.2  487.41    4384  487.04  4479.2  486.01  4570.4  487.33  4971.8  487.15
    4986  486.44  4996.5  483.93  4999.2  483.43  5002.5  483.93  5013.9  486.75
  5030.7  486.86  5120.1  484.96  5148.1  486.03  5409.3  486.45  5932.6  485.27
  6045.8  486.46  6896.9  487.45  6972.7  489.21  7413.6   492.2  7608.9  491.02
#Mann= 10 ,-1 , 0
  2265.4     .16       0  2576.4     .05       0  2972.7     .16       0
  3142.7     .05       0  3645.3     .16       0  3964.2     .05       0
    4384     .16       0  4971.8     .05       0  4996.5    .035       0
  5002.5     .05       0
Bank Sta=4996.5,5002.5
XS Rating Curve= 0 ,0
Exp/Cntr=0.3,0.1

Chan Stop Cuts=-1
Use User Specified Reach Order=0
Composite Channel Slope=5