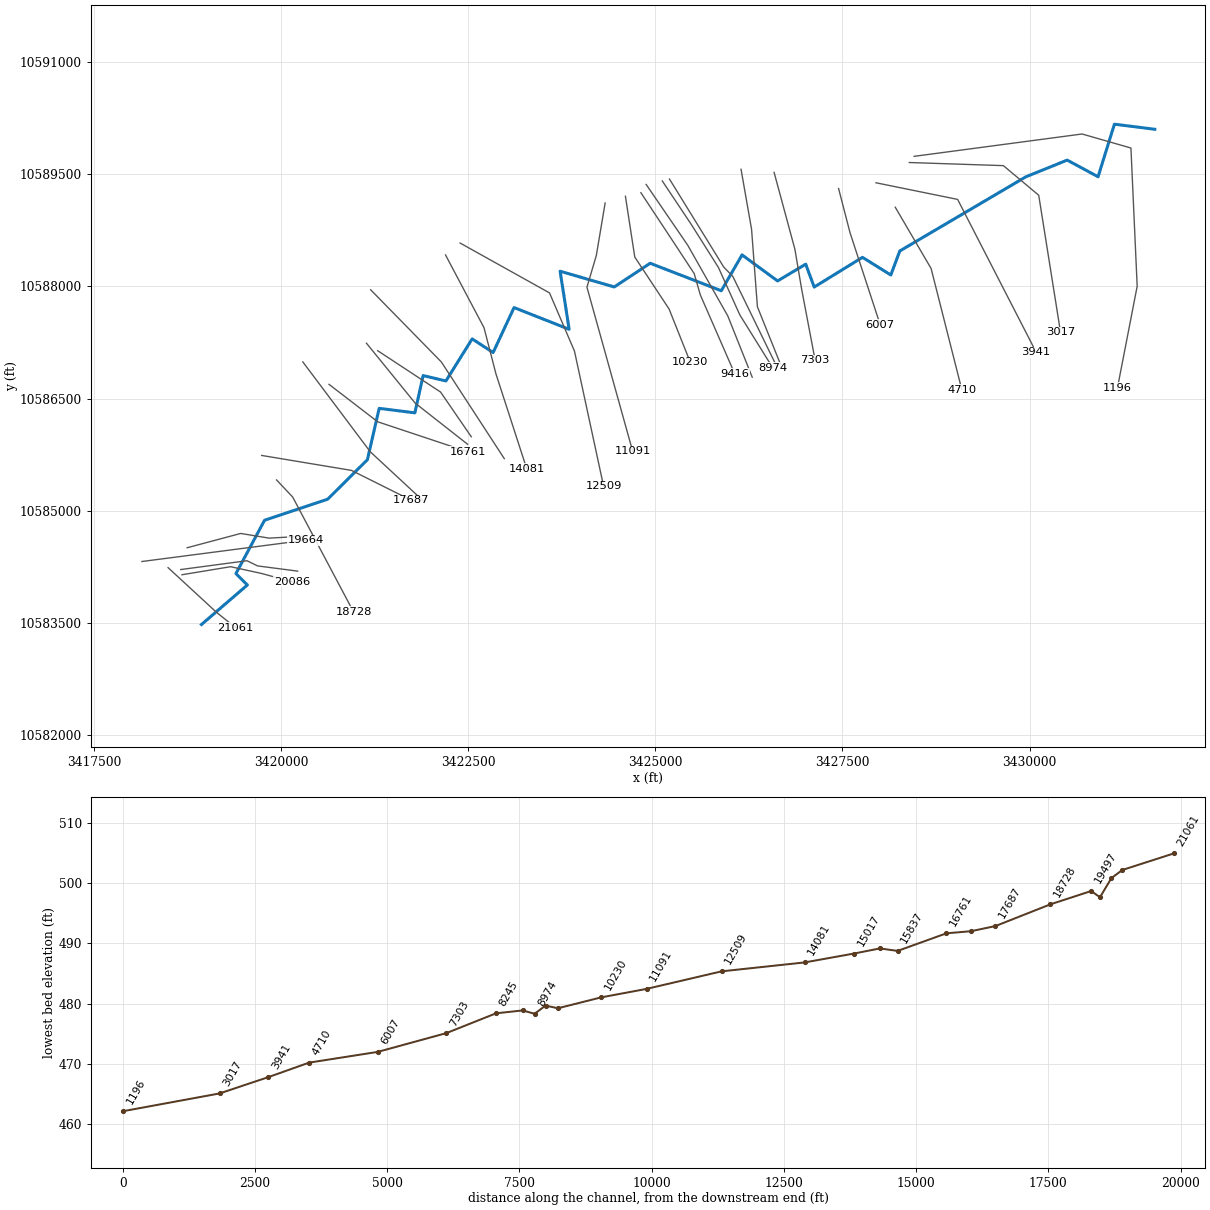
--- UNT0024 IN CHRS.prj (project) ---

Proj Title=UNT0024 IN CHRS Base Level Engineering
Current Plan=p01
Default Exp/Contr=0.3,0.1
English Units
Geom File=g01
Flow File=f01
Plan File=p01
Y Axis Title=Elevation
X Axis Title(PF)=Main Channel Distance
X Axis Title(XS)=Station
BEGIN DESCRIPTION:
UNT0024 IN CHRS
END DESCRIPTION:
DSS Export Rating Curves= 0
DSS Export Rating Curve Sorted= 0
DSS Export Volume Flow Curves= 0
DXF OffsetX= 0
DXF OffsetY= 0
DXF ScaleX= 1
DXF ScaleY= 10

--- UNT0024 IN CHRS.p01 (plan) ---

Plan Title=Multiple Run
Short Identifier=Multiple
Geom File=g01
Flow File=f01
Subcritical Flow
K Sum by GR= 0
Std Step Tol= 0.01
Critical Tol= 0.01
Num of Std Step Trials= 20
Max Error Tol= 0.3
Flow Tol Ratio= 0.001
Split Flow NTrial= 30
Split Flow Tol= 0.02
Split Flow Ratio= 0.02
Log Output Level= 0
Friction Slope Method= 1
Unsteady Friction Slope Method= 2
Unsteady Bridges Friction Slope Method= 1
Parabolic Critical Depth
Global Vel Dist=  1 , 1 , 1
Global Log Level= 0
CheckData=True
Encroach Param= -1, 0, 0, 0
BEGIN DESCRIPTION:
Multiple Run
END DESCRIPTION:

--- UNT0024 IN CHRS.f01 (steady flow) ---

Flow Title=Multiple
Number of Profiles=7
Profile Names=10-year,25-year,50-year,1pct_min,100-year,1pct_plu,500-year
River Rch & RM= UNT0024 IN CHRS,Reach-1,21061
     422     534     617     519     702     949     906
River Rch & RM= UNT0024 IN CHRS,Reach-1,19664
     646     836     980     836    1131    1530    1503
River Rch & RM= UNT0024 IN CHRS,Reach-1,16761
     771    1002    1178    1005    1360    1839    1810
River Rch & RM= UNT0024 IN CHRS,Reach-1,11091
     832    1077    1264    1076    1455    1967    1925
River Rch & RM= UNT0024 IN CHRS,Reach-1,3017
     912    1184    1390    1184    1602    2166    2124
Boundary for River Rch & Prof#=UNT0024 IN CHRS,Reach-1,1
Up Type=0
Dn Type=3
Dn Slope=0.005
Boundary for River Rch & Prof#=UNT0024 IN CHRS,Reach-1,2
Up Type=0
Dn Type=3
Dn Slope=0.005
Boundary for River Rch & Prof#=UNT0024 IN CHRS,Reach-1,3
Up Type=0
Dn Type=3
Dn Slope=0.005
Boundary for River Rch & Prof#=UNT0024 IN CHRS,Reach-1,4
Up Type=0
Dn Type=3
Dn Slope=0.005
Boundary for River Rch & Prof#=UNT0024 IN CHRS,Reach-1,5
Up Type=0
Dn Type=3
Dn Slope=0.005
Boundary for River Rch & Prof#=UNT0024 IN CHRS,Reach-1,6
Up Type=0
Dn Type=3
Dn Slope=0.005
Boundary for River Rch & Prof#=UNT0024 IN CHRS,Reach-1,7
Up Type=0
Dn Type=3
Dn Slope=0.005

--- UNT0024 IN CHRS.g01 (geometry) ---

Geom Title=Existing Conditions
Program Version=4.10

River Reach=UNT0024 IN CHRS ,Reach-1
Reach XY= 30
      3418937.91     10583481.34      3419551.08     10584010.14
      3419398.22     10584162.49      3419780.73     10584874.88
      3420624.72     10585157.36      3421154.58     10585684.87
       3421311.8     10586371.19      3421788.72      10586311.2
      3421898.79     10586809.09      3422203.46      10586737.5
      3422553.74     10587299.43      3422833.99     10587117.53
      3423113.57     10587718.12      3423849.49     10587427.72
       3423728.7     10588204.15      3424451.98     10587993.96
      3424931.57      10588310.4      3425881.88     10587943.04
      3426158.94     10588422.34      3426633.43     10588074.27
       3427009.6     10588298.34      3427122.56     10587992.38
       3427767.7      10588389.8      3428146.22     10588153.56
      3428266.05     10588474.48       3429949.6     10589465.91
      3430502.22     10589689.48       3430914.7     10589466.79
      3431132.91     10590169.38      3431672.11     10590101.64

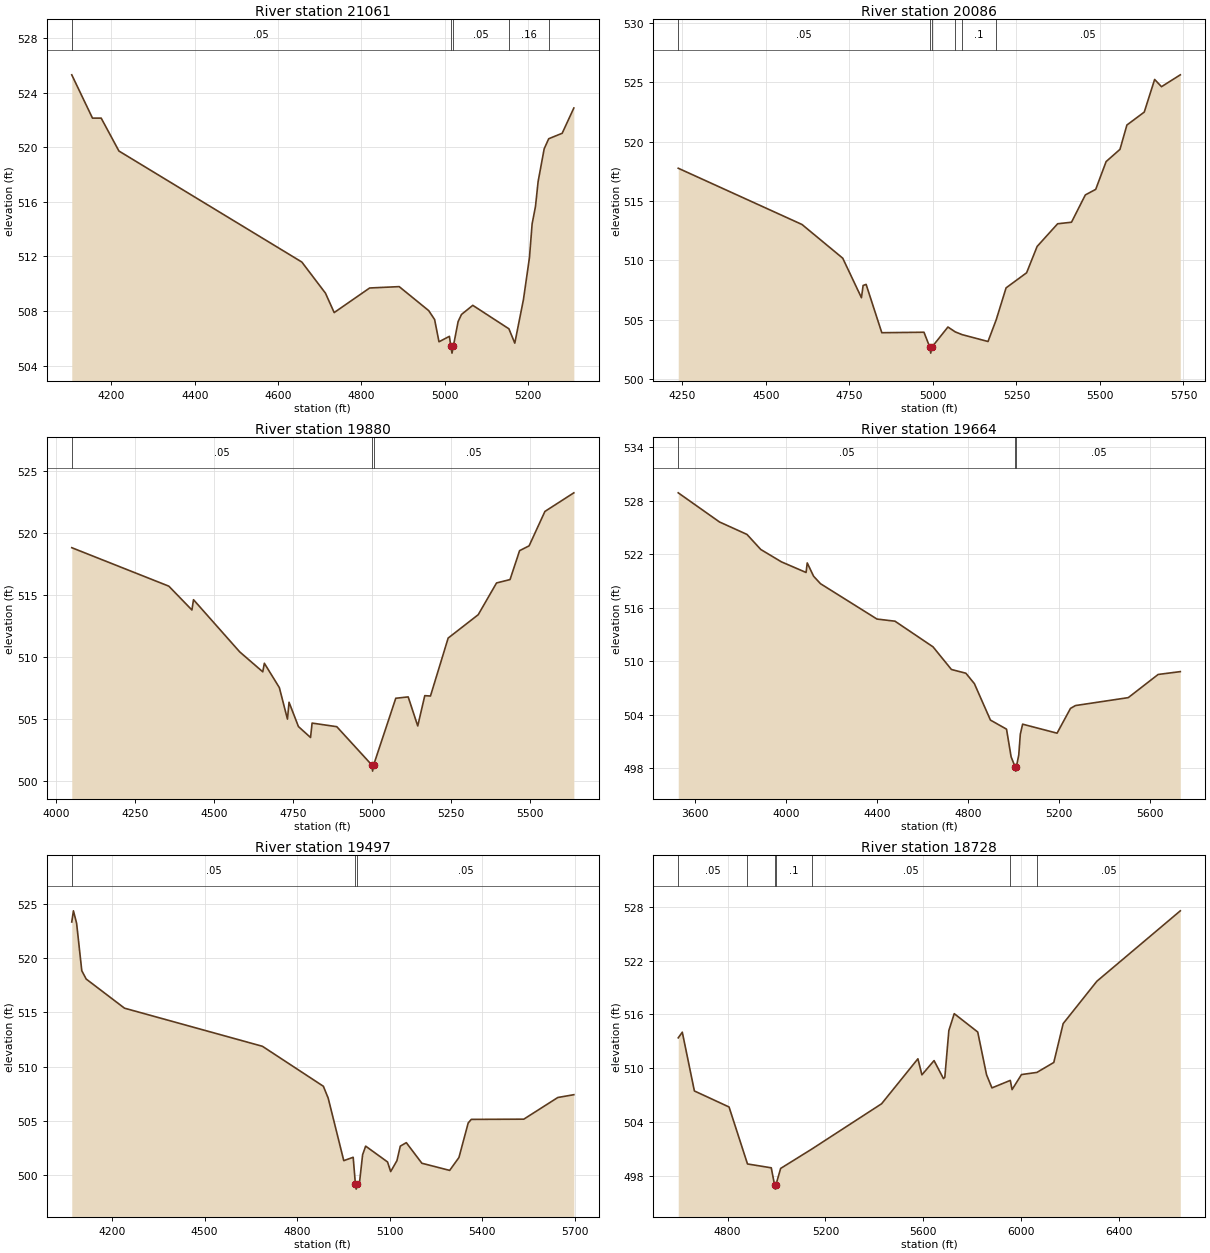
Type RM Length L Ch R = 1 ,21061   ,975,975,975
BEGIN DESCRIPTION:
UNT0024 IN CHRS 37.0
END DESCRIPTION:
XS GIS Cut Line= 3
      3418492.07     10584241.67      3419142.11     10583641.64
      3419392.11     10583441.64
#Sta/Elev= 30
    4105   525.3  4154.7  522.13  4175.6  522.13  4218.2  519.72  4657.1  511.59
  4713.8  509.31  4734.7  507.89  4819.8  509.69  4890.7  509.79  4961.6  508.03
  4975.7  507.38  4986.2  505.75  5011.2  506.15  5014.6  505.42  5017.4  504.92
  5020.6  505.42  5032.1  507.23  5040.1  507.75  5067.3  508.42    5154   506.7
  5168.1  505.65  5188.9  508.85  5203.3  511.92  5209.7  514.39  5217.7  515.65
  5224.1  517.49  5238.6  519.88  5249.5  520.62  5281.8  521.02  5309.8  522.87
#Mann= 5 ,-1 , 0
    4105     .05       0  5014.6    .035       0  5020.6     .05       0
    5154     .16       0  5249.5      .1       0
Bank Sta=5014.6,5020.6
XS Rating Curve= 0 ,0
Exp/Cntr=0.3,0.1

Type RM Length L Ch R = 1 ,20086   ,206,206,206
BEGIN DESCRIPTION:
UNT0024 IN CHRS 36.0
END DESCRIPTION:
XS GIS Cut Line= 4
      3418677.43     10584146.81      3419326.78     10584254.46
      3419739.97     10584164.18       3420146.2     10584053.08
#Sta/Elev= 30
  4238.2  517.75  4608.5  513.01  4730.4  510.17  4786.4  506.84  4791.4  507.87
  4800.4  507.96  4847.3  503.89  4973.5  503.93    4991  502.67  4993.7  502.17
    4997  502.67  5045.2  504.37  5067.1  503.96  5087.4  503.73  5165.1  503.15
  5189.5  504.97  5219.2  507.67  5280.6  508.94  5312.1  511.16  5373.4  513.07
  5414.9   513.2  5456.3   515.5  5487.4  515.97  5518.5  518.31    5560  519.34
  5580.7  521.39  5632.6  522.48  5663.7  525.23  5684.2  524.62  5740.5  525.62
#Mann= 6 ,-1 , 0
  4238.2     .05       0    4991     .04       0    4997     .05       0
  5067.1     .16       0  5087.4      .1       0  5189.5     .05       0
Bank Sta=4991,4997
XS Rating Curve= 0 ,0
Exp/Cntr=0.3,0.1

Type RM Length L Ch R = 1 ,19880   ,216,216,216
BEGIN DESCRIPTION:
UNT0024 IN CHRS 35.0
END DESCRIPTION:
XS GIS Cut Line= 4
      3418660.16     10584216.27      3419545.53     10584334.32
      3419687.89     10584264.88       3420222.6     10584195.43
#Sta/Elev= 30
  4048.9  518.83  4356.5  515.73  4429.6  513.81  4434.6  514.64  4580.9  510.44
  4654.1  508.83  4659.1  509.52  4706.6  507.56  4732.3  505.02  4737.3  506.38
  4767.1  504.42  4805.4  503.54  4810.4   504.7  4888.6  504.41  4999.4  501.33
  5002.1  500.83  5005.4  501.33  5075.5   506.7  5114.8  506.81  5145.1  504.47
  5167.4  506.91  5185.4  506.88  5241.5  511.55  5336.7  513.43  5394.8  515.99
  5437.5  516.26  5467.8  518.59    5498  518.98    5548  521.75  5639.7  523.25
#Mann= 3 ,-1 , 0
  4048.9     .05       0  4999.4     .04       0  5005.4     .05       0
Bank Sta=4999.4,5005.4
XS Rating Curve= 0 ,0
Exp/Cntr=0.3,0.1

Type RM Length L Ch R = 1 ,19664   ,167,167,167
BEGIN DESCRIPTION:
UNT0024 IN CHRS 34.0
END DESCRIPTION:
XS GIS Cut Line= 2
      3418142.73      10584323.9      3420328.69     10584608.42
#Sta/Elev= 30
  3528.2  528.89  3709.3  525.62  3830.1  524.22  3890.6  522.53  3981.4  521.14
  4089.5  519.95  4094.6  521.02  4122.5  519.53  4152.8  518.69  4400.8  514.72
  4479.9  514.48  4646.9   511.6  4727.6  509.06  4791.1  508.64  4828.5  507.47
    4899  503.38  4969.6  502.36  4989.8  499.25    5007  498.15  5009.7  497.65
    5013  498.15  5023.3  499.46  5030.1  501.78  5040.2  502.92  5191.5  501.91
  5250.4  504.69  5272.2  505.01  5504.1   505.9  5635.2   508.5  5732.6  508.82
#Mann= 3 ,-1 , 0
  3528.2     .05       0    5007     .04       0    5013     .05       0
Bank Sta=5007,5013
XS Rating Curve= 0 ,0
Exp/Cntr=0.3,0.1

Type RM Length L Ch R = 1 ,19497   ,769,769,769
BEGIN DESCRIPTION:
UNT0024 IN CHRS 33.0
END DESCRIPTION:
XS GIS Cut Line= 4
      3418746.91     10584507.93       3419462.2      10584698.9
      3419840.67      10584636.4      3420344.16     10584664.18
#Sta/Elev= 30
  4069.2  523.35  4074.6  524.38  4084.9  523.23  4101.7  518.85    4116  518.08
  4240.2  515.39  4687.5  511.87  4885.1  508.18  4900.7  507.09  4951.3  501.31
  4981.8  501.62  4988.9  499.18  4991.6  498.68  4994.9  499.18    5002  499.21
  5012.4  501.86  5022.3  502.65  5093.2  501.19  5103.4   500.3  5123.7  501.31
  5134.6  502.65  5154.1  502.97  5204.6  501.07  5294.7  500.41  5324.8   501.6
  5354.8  504.79  5364.8  505.12  5535.1  505.14  5645.3  507.14  5697.4   507.4
#Mann= 3 ,-1 , 0
  4069.2     .05       0  4988.9    .035       0  4994.9     .05       0
Bank Sta=4988.9,4994.9
XS Rating Curve= 0 ,0
Exp/Cntr=0.3,0.1

Type RM Length L Ch R = 1 ,18728   ,1041,1041,1041
BEGIN DESCRIPTION:
UNT0024 IN CHRS 32.0
END DESCRIPTION:
XS GIS Cut Line= 3
      3419941.39     10585414.15      3420156.64     10585185.02
      3420969.14      10583650.3
#Sta/Elev= 30
  4598.5  513.37  4615.1     514  4664.5  507.44  4806.1  505.65  4881.4  499.29
  4978.5  498.86  4991.8  496.98  4994.6  496.48  4997.8  496.98  5016.8  498.79
  5143.4  500.94  5429.2  506.01  5577.5  511.03  5593.9  509.24  5643.5  510.83
  5681.9  508.82  5687.5  508.97  5703.9  514.18  5725.9  516.07  5821.9  514.02
  5857.9  509.25  5879.9  507.78  5954.9  508.62  5962.2  507.59  6000.6  509.27
  6063.6  509.51  6132.6  510.62  6170.9  514.96  6308.6  519.69  6649.4  527.55
#Mann= 7 ,-1 , 0
  4598.5     .05       0  4881.4      .1       0  4991.8     .07       0
  4997.8      .1       0  5143.4     .05       0  5954.9      .1       0
  6063.6     .05       0
Bank Sta=4991.8,4997.8
XS Rating Curve= 0 ,0
Exp/Cntr=0.3,0.1

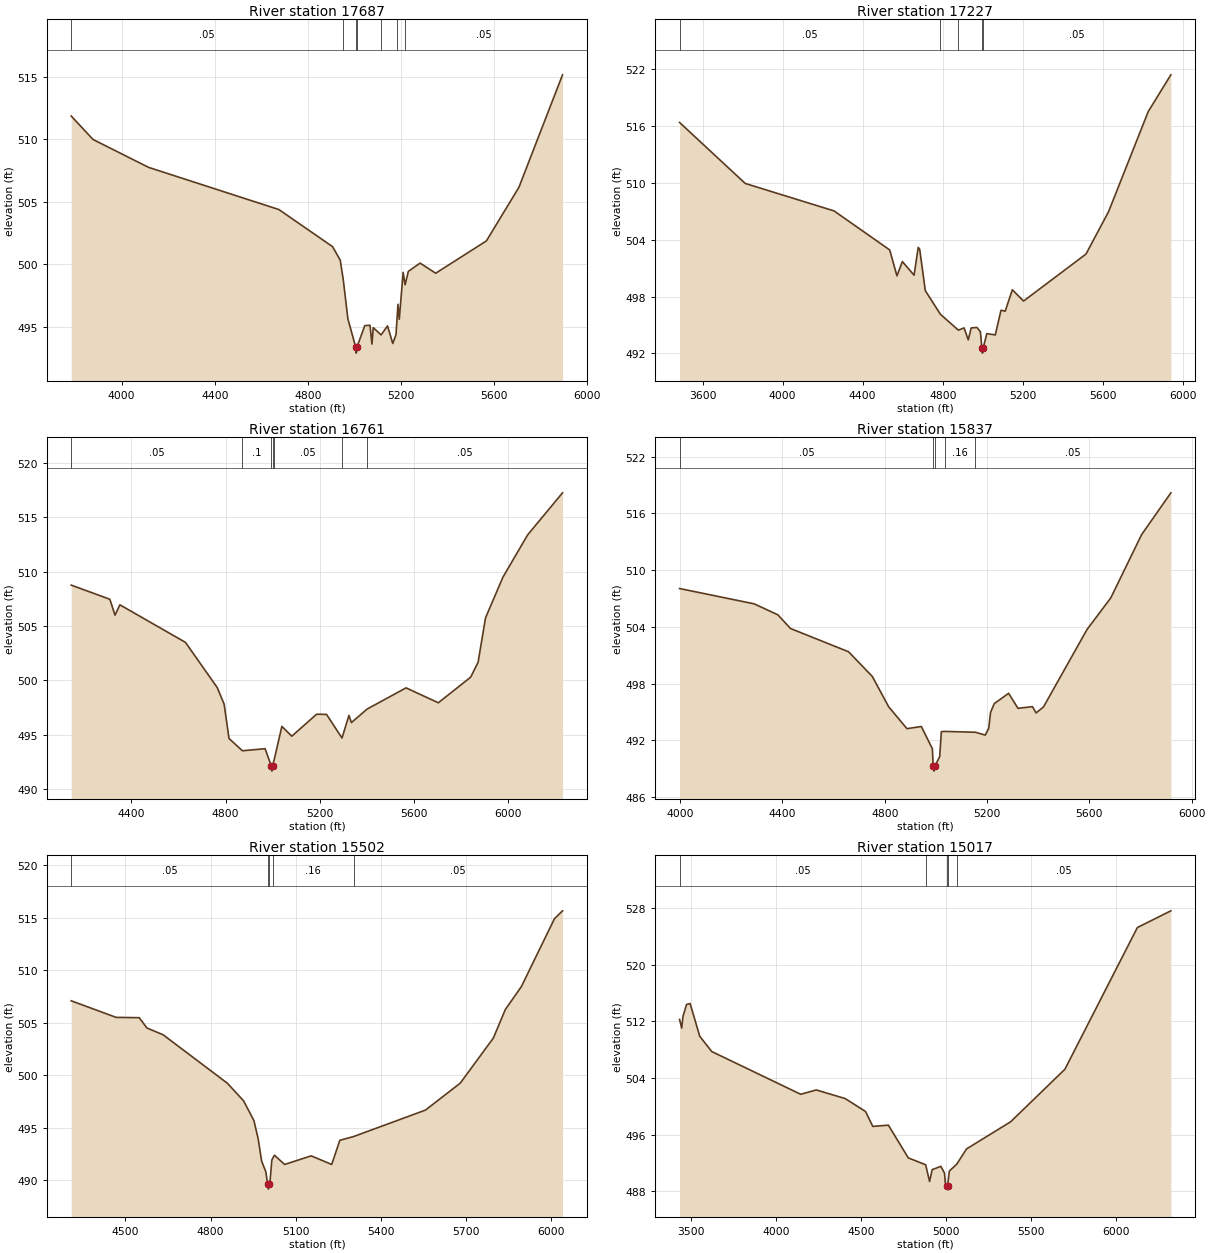
Type RM Length L Ch R = 1 ,17687   ,460,460,460
BEGIN DESCRIPTION:
UNT0024 IN CHRS 30.0
END DESCRIPTION:
XS GIS Cut Line= 3
      3419742.06     10585741.65      3420942.11     10585541.64
      3421742.09     10585141.65
#Sta/Elev= 30
  3783.6  511.86  3877.4  509.98  4115.7  507.75  4675.8  504.37  4906.4   501.4
  4939.4  500.32  4952.2  498.79  4972.3  495.62  5005.6  493.37  5008.3  492.87
  5011.6  493.37  5044.9  495.07  5067.3   495.1  5075.7   493.6  5081.3  494.91
    5115  494.33  5142.7  495.05  5165.1  493.64  5179.1  494.35  5183.7  495.68
  5187.5  496.78  5193.1  495.58  5209.8  499.34  5218.1  498.34  5232.2  499.42
  5282.5  500.08  5349.6  499.27  5567.6  501.86  5707.4  506.16  5894.6  515.16
#Mann= 7 ,-1 , 0
  3783.6     .05       0  4952.2      .1       0  5005.6     .07       0
  5011.6      .1       0    5115     .05       0  5183.7      .1       0
  5218.1     .05       0
Bank Sta=5005.6,5011.6
XS Rating Curve= 0 ,0
Exp/Cntr=0.3,0.1

Type RM Length L Ch R = 1 ,17227   ,466,466,466
BEGIN DESCRIPTION:
UNT0024 IN CHRS 29.0
END DESCRIPTION:
XS GIS Cut Line= 3
      3420292.11     10586991.63      3421192.11     10585791.64
      3421892.08     10585141.66
#Sta/Elev= 30
  3484.9  516.38    3813  509.94  4256.8  507.04  4534.9  502.92  4571.3  500.18
  4598.4  501.69  4656.8  500.25  4677.6  503.19  4684.9  502.99    4713  498.62
  4788.5  496.12  4878.3  494.45  4906.8  494.68  4927.6  493.42  4942.2  494.68
  4971.3  494.73  4988.3  494.27  4995.8  492.52  4998.5  492.02  5001.8  492.52
  5020.3  494.08  5062.8  493.94  5091.2  496.55  5112.2  496.45  5147.9  498.71
    5204  497.52  5515.8  502.48  5628.6  506.95    5827  517.53  5940.1  521.41
#Mann= 5 ,-1 , 0
  3484.9     .05       0  4788.5      .1       0  4878.3     .05       0
  4995.8    .035       0  5001.8     .05       0
Bank Sta=4995.8,5001.8
XS Rating Curve= 0 ,0
Exp/Cntr=0.3,0.1

Type RM Length L Ch R = 1 ,16761   ,924,924,924
BEGIN DESCRIPTION:
UNT0024 IN CHRS 28.0
END DESCRIPTION:
XS GIS Cut Line= 3
      3420642.09     10586691.65      3421292.11     10586191.64
      3422492.12     10585791.64
#Sta/Elev= 30
  4144.6  508.76  4308.6  507.46  4330.4     506  4351.2  506.95  4629.4   503.5
  4764.4  499.34  4793.4  497.83  4814.2  494.67  4871.1  493.54  4967.3  493.73
  4993.3  492.17    4996  491.67  4999.3  492.17  5007.2  492.84  5038.5  495.78
  5080.6  494.88    5186   496.9  5228.2  496.88  5293.7  494.71  5323.1  496.79
  5333.6  496.13  5400.2  497.37  5565.5  499.32  5702.5  497.95  5839.6   500.3
  5871.2  501.67  5902.8  505.75  5976.6  509.49    6082  513.39  6229.6  517.24
#Mann= 7 ,-1 , 0
  4144.6     .05       0  4871.1      .1       0  4993.3     .07       0
  4999.3      .1       0  5007.2     .05       0  5293.7      .1       0
  5400.2     .05       0
Bank Sta=4993.3,4999.3
XS Rating Curve= 0 ,0
Exp/Cntr=0.3,0.1

Type RM Length L Ch R = 1 ,15837   ,335,335,335
BEGIN DESCRIPTION:
UNT0024 IN CHRS 27.0
END DESCRIPTION:
XS GIS Cut Line= 3
      3421142.08     10587241.68      3421792.11     10586441.64
      3422492.07     10585891.67
#Sta/Elev= 30
  3997.7  508.06  4289.4  506.44  4382.1  505.28  4431.6  503.83  4658.6  501.37
  4751.3  498.76  4815.2  495.56  4886.8  493.24    4943  493.47  4986.1  491.12
  4989.6  489.25  4992.3  488.75  4995.6  489.25  5014.9  490.29  5021.3  492.93
  5036.1  492.95  5154.6  492.86    5193  492.56  5206.6  493.29  5213.8  494.97
  5228.2  495.89  5284.3  496.98    5321  495.39  5377.4  495.57  5391.8  494.91
  5420.7  495.54  5590.7  503.72  5683.8  507.07  5804.3  513.76  5918.7  518.18
#Mann= 5 ,-1 , 0
  3997.7     .05       0  4989.6    .035       0  4995.6     .05       0
  5036.1     .16       0  5154.6     .05       0
Bank Sta=4989.6,4995.6
XS Rating Curve= 0 ,0
Exp/Cntr=0.3,0.1

Type RM Length L Ch R = 1 ,15502   ,485,485,485
BEGIN DESCRIPTION:
UNT0024 IN CHRS 26.0
END DESCRIPTION:
XS GIS Cut Line= 3
      3421292.12     10587141.63      3422132.16     10586588.66
      3422542.09     10585991.66
#Sta/Elev= 30
  4309.3   507.1  4467.4  505.52  4548.7  505.49  4575.8  504.51    4633  503.86
    4859  499.25  4916.2  497.57  4952.4   495.7  4967.4  493.98  4979.7  491.83
  4994.5  490.81  5000.6  489.66  5003.3  489.16  5006.6  489.66  5009.6  489.98
  5015.6  491.93  5018.3  492.07  5024.7  492.39  5060.8  491.51  5154.2  492.33
  5226.4  491.51  5255.1  493.81  5303.7  494.17  5556.7  496.69  5679.2  499.26
  5795.6  503.55  5837.6  506.26  5894.4  508.46  6010.8  514.92  6039.2  515.67
#Mann= 5 ,-1 , 0
  4309.3     .05       0  5000.6    .035       0  5006.6     .05       0
  5018.3     .16       0  5303.7     .05       0
Bank Sta=5000.6,5006.6
XS Rating Curve= 0 ,0
Exp/Cntr=0.3,0.1

Type RM Length L Ch R = 1 ,15017   ,936,936,936
BEGIN DESCRIPTION:
UNT0024 IN CHRS 25.0
END DESCRIPTION:
XS GIS Cut Line= 3
      3421198.32     10587955.84      3422142.75     10586990.57
      3422983.04     10585698.89
#Sta/Elev= 30
  3431.5  512.26  3444.2  511.04  3451.4  512.66  3472.5  514.36  3493.6   514.5
  3550.2  509.89  3620.9  507.73  4144.3   501.7  4236.2  502.31  4405.9   501.1
  4526.2  499.27  4568.6  497.17  4660.5  497.34  4777.9  492.72  4879.7  491.76
  4902.9   489.4  4918.1  491.07  4969.4  491.53  4990.5  490.59  4996.5  488.98
  5002.7  488.82  5005.4  488.32  5008.7  488.82  5019.3  490.87  5062.8  491.84
  5120.3  493.99  5379.9  497.82  5699.3  505.23  6125.7  525.22  6322.9  527.58
#Mann= 5 ,-1 , 0
  3431.5     .05       0  4879.7     .16       0  5002.7     .07       0
  5008.7     .16       0  5062.8     .05       0
Bank Sta=5002.7,5008.7
XS Rating Curve= 0 ,0
Exp/Cntr=0.3,0.1

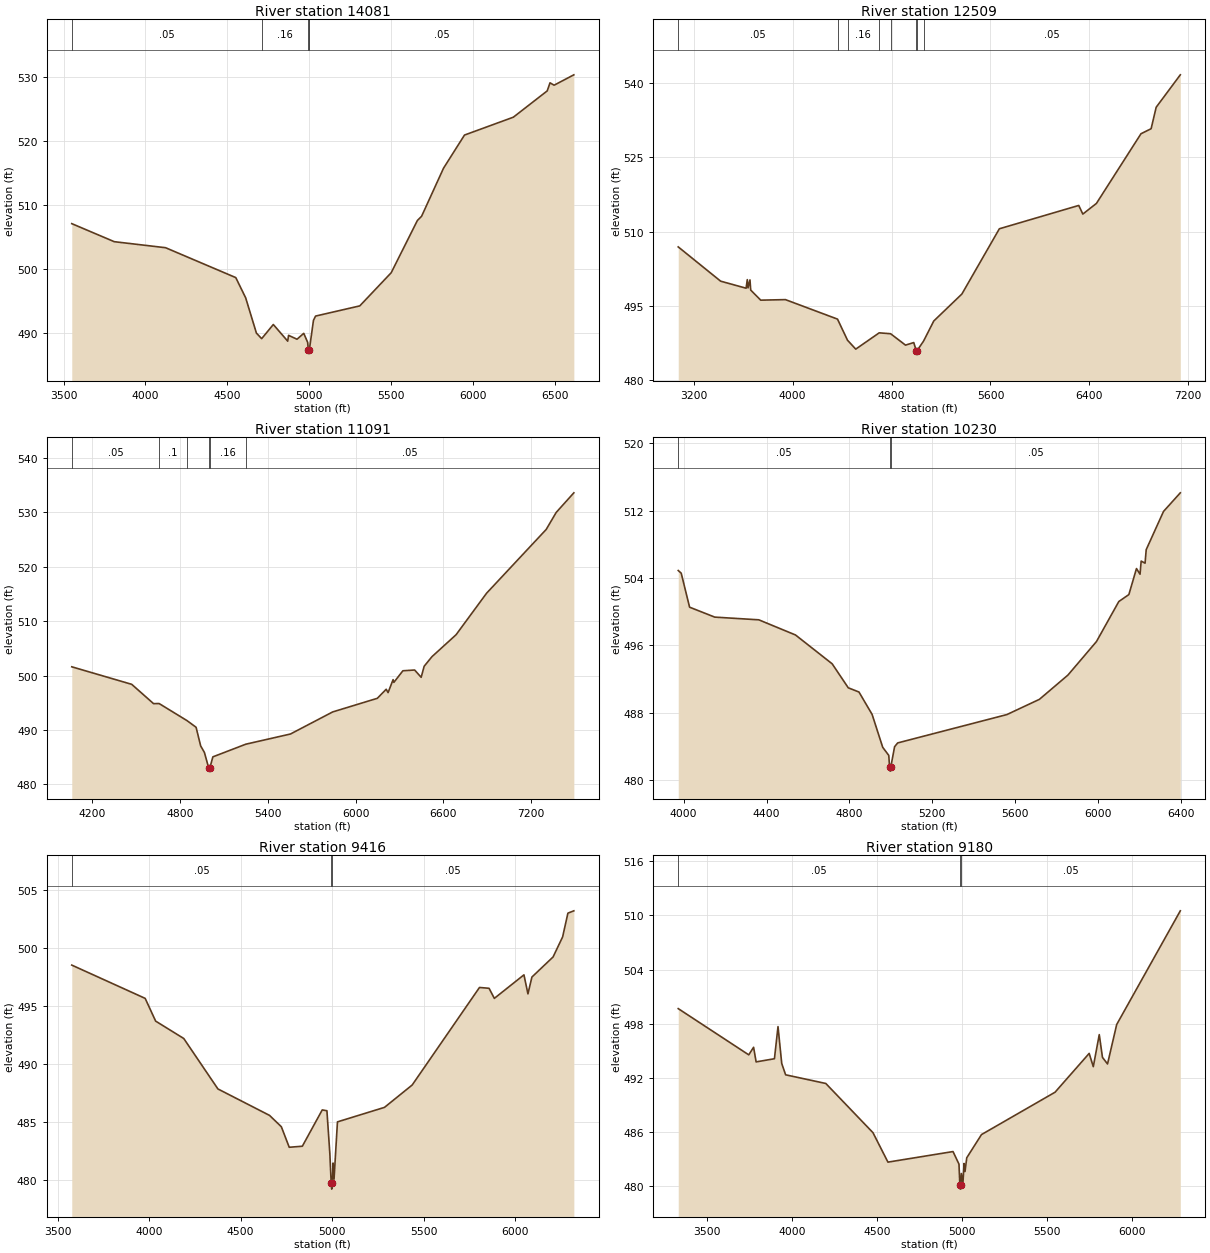
Type RM Length L Ch R = 1 ,14081   ,1572,1572,1572
BEGIN DESCRIPTION:
UNT0024 IN CHRS 22.0
END DESCRIPTION:
XS GIS Cut Line= 4
      3422198.31     10588421.12       3422712.2      10587448.9
      3422871.92     10586830.85      3423281.65     10585566.94
#Sta/Elev= 30
  3550.1  507.07  3809.8  504.25    4123  503.31  4551.9  498.64  4612.3  495.48
  4677.9  489.97    4710   489.1  4781.2  491.31  4869.1  488.71  4874.3  489.62
  4925.8  489.01  4967.1  489.93    4991  488.52  4995.1  487.34  4997.9  486.84
  5001.1  487.34  5001.3  487.38  5026.5  491.97  5039.4  492.63  5309.3  494.22
  5501.2   499.4  5661.1  507.56  5686.8  508.22    5821  515.74  5948.9  520.91
  6247.3   523.7  6454.2  527.81  6471.2  529.07  6496.2   528.7  6616.8  530.32
#Mann= 5 ,-1 , 0
  3550.1     .05       0    4710     .16       0  4995.1     .07       0
  5001.1     .16       0  5001.3     .05       0
Bank Sta=4995.1,5001.1
XS Rating Curve= 0 ,0
Exp/Cntr=0.3,0.1

Type RM Length L Ch R = 1 ,12509   ,1418,1418,1418
BEGIN DESCRIPTION:
UNT0024 IN CHRS 21.0
END DESCRIPTION:
XS GIS Cut Line= 4
      3422392.79     10588580.83       3423587.2     10587914.18
      3423920.53      10587136.4      3424309.42     10585330.86
#Sta/Elev= 30
  3074.4  506.88  3417.2  499.94  3623.3  498.51    3633  500.25  3638.7  498.58
  3654.7  500.19  3660.5  498.14  3741.6  496.09  3941.5   496.2  4362.7  492.25
  4443.7  487.97  4510.3  486.17  4699.9  489.47    4792  489.29  4912.8  486.98
  4979.3   487.5  4999.9  485.86  5002.7  485.36  5005.9  485.86  5058.3  487.78
  5141.3  491.87  5368.6  497.33  5671.8  510.55  6314.1  515.28  6346.9  513.53
  6456.9  515.69  6817.5  529.81  6899.3  530.82  6940.2  535.17  7135.4  541.74
#Mann= 8 ,-1 , 0
  3074.4     .05       0  4362.7      .1       0  4443.7     .16       0
  4699.9      .1       0    4792     .16       0  4999.9     .07       0
  5005.9     .16       0  5058.3     .05       0
Bank Sta=4999.9,5005.9
XS Rating Curve= 0 ,0
Exp/Cntr=0.3,0.1

Type RM Length L Ch R = 1 ,11091   ,861,861,861
BEGIN DESCRIPTION:
UNT0024 IN CHRS 18.0
END DESCRIPTION:
XS GIS Cut Line= 4
      3424330.25     10589115.54       3424212.2     10588414.18
       3424087.2     10587990.57      3424698.24     10585796.35
#Sta/Elev= 30
  4060.9  501.62  4470.5   498.4  4619.8  494.85  4657.6  494.87  4847.9  491.74
  4910.3  490.51  4941.6  487.09  4967.2  485.88  4997.5  482.95  5000.3  482.45
  5003.5  482.95    5025  485.07  5250.2   487.4  5555.2  489.27  5843.9  493.33
  6148.7  495.83  6209.2  497.49  6222.3  496.88  6256.5  499.26  6261.7  498.76
  6323.4  500.89  6403.8  501.03  6448.3  499.69  6468.7  501.72    6522  503.48
  6686.7  507.51  6895.2  515.14  7302.6  526.86    7371  529.99  7491.5  533.59
#Mann= 6 ,-1 , 0
  4060.9     .05       0  4657.6      .1       0  4847.9     .16       0
  4997.5     .07       0  5003.5     .16       0  5250.2     .05       0
Bank Sta=4997.5,5003.5
XS Rating Curve= 0 ,0
Exp/Cntr=0.3,0.1

Type RM Length L Ch R = 1 ,10230   ,814,814,814
BEGIN DESCRIPTION:
UNT0024 IN CHRS 17.0
END DESCRIPTION:
XS GIS Cut Line= 4
      3424601.09     10589205.85      3424726.09     10588393.35
      3425184.42      10587698.9      3425468.56     10586985.09
#Sta/Elev= 30
  3974.1  504.88  3988.5  504.56  4028.9  500.52  4150.4  499.34  4362.8  499.02
  4539.8  497.22  4716.9  493.79  4794.5  490.94  4846.1  490.44  4909.5  487.78
  4960.7  483.87  4989.9  482.91  4993.8  481.54  4996.6  481.04  4999.8  481.54
  5017.9  483.94  5032.9  484.39  5559.8  487.76  5716.7  489.57  5854.2  492.45
  5991.8  496.43  6099.7  501.19  6148.3  502.02    6185  505.11  6202.2  504.44
  6207.6     506  6226.5  505.75  6231.9  507.35  6315.5   511.9  6396.5  514.11
#Mann= 3 ,-1 , 0
  3974.1     .05       0  4993.8    .035       0  4999.8     .05       0
Bank Sta=4993.8,4999.8
XS Rating Curve= 0 ,0
Exp/Cntr=0.3,0.1

Type RM Length L Ch R = 1 ,9416    ,236,236,236
BEGIN DESCRIPTION:
UNT0024 IN CHRS 15.3
END DESCRIPTION:
XS GIS Cut Line= 5
      3424807.77     10589253.67      3425237.48      10588602.6
       3425519.6     10588172.91      3425602.06     10587886.45
      3426062.14     10586831.74
#Sta/Elev= 30
  3577.7  498.56  3978.7  495.69  4035.9  493.73  4189.5  492.23  4376.1  487.88
    4658   485.6  4722.7  484.62  4765.7  482.85  4837.4  482.94    4946  486.07
  4971.6     486  4987.6  482.31    4995  479.74  4997.8  479.24    5001  479.74
  5005.3  481.49  5010.5   480.1  5029.2  485.04  5286.1  486.29  5437.5  488.22
  5805.1  496.63  5857.4  496.56  5886.3  495.69    6048  497.72  6069.8  496.08
  6091.6  497.53  6207.1  499.26  6259.3  500.99  6288.2  503.04  6320.6  503.24
#Mann= 3 ,-1 , 0
  3577.7     .05       0    4995    .035       0    5001     .05       0
Bank Sta=4995,5001
XS Rating Curve= 0 ,0
Exp/Cntr=0.3,0.1

Type RM Length L Ch R = 1 ,9180    ,206,206,206
BEGIN DESCRIPTION:
UNT0024 IN CHRS 15.0
END DESCRIPTION:
XS GIS Cut Line= 4
       3424878.1     10589363.89      3425433.66     10588551.38
      3425968.38     10587606.94      3426294.79     10586787.45
#Sta/Elev= 30
  3331.4  499.67    3746  494.55  3774.4  495.39  3789.3  493.77    3897  494.12
    3918  497.68  3939.8   493.6  3962.7  492.34    4199  491.38  4476.3  485.93
  4564.3  482.67  4946.8  483.84  4981.9  482.45  4987.1  480.18  4989.8  479.68
  4993.1  480.18  4995.8  481.41  5004.9  480.27  5011.7  482.52  5017.4  481.63
  5027.6  483.15  5114.2  485.72  5546.6  490.41  5747.3  494.71  5771.6  493.24
  5806.6  496.79  5825.5  494.27  5855.2  493.54  5909.1  497.91  6283.1   510.5
#Mann= 3 ,-1 , 0
  3331.4     .05       0  4987.1     .03       0  4993.1     .05       0
Bank Sta=4987.1,4993.1
XS Rating Curve= 0 ,0
Exp/Cntr=0.3,0.1

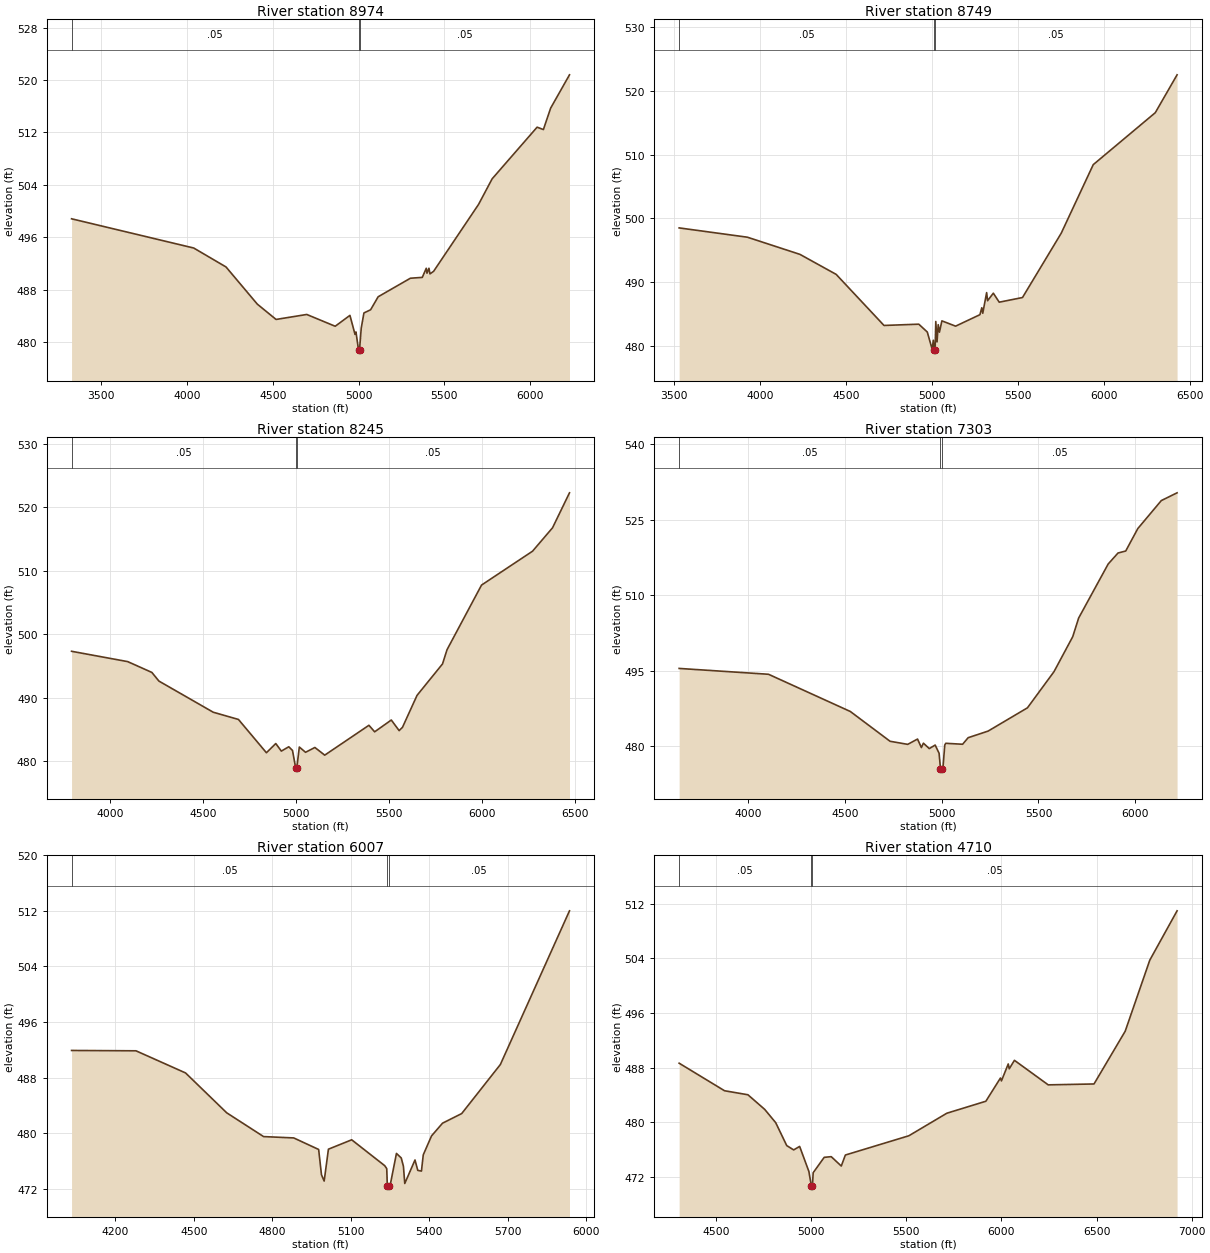
Type RM Length L Ch R = 1 ,8974    ,225,225,225
BEGIN DESCRIPTION:
UNT0024 IN CHRS 15.1
END DESCRIPTION:
XS GIS Cut Line= 5
      3425093.37     10589410.78       3425478.8     10588832.63
      3425843.38     10588254.51      3426129.84     10587619.09
        3426567.     10586916.52
#Sta/Elev= 30
  3326.4  498.82  4038.5  494.36  4226.8  491.47  4409.2   485.8  4518.6  483.46
  4697.6  484.22  4863.3  482.42  4949.2  484.08    4979  481.18  4984.5  481.55
  4999.2  478.82  5001.9  478.32  5005.2  478.82    5015  482.11  5030.8  484.45
  5069.9  484.94  5113.7  486.92  5301.7  489.75  5371.1  489.88  5394.3  491.27
  5398.4  490.52    5410  491.27  5415.9  490.41  5437.2  490.81  5699.2  501.02
  5778.3  504.92  6040.4   512.8    6077  512.44  6119.4  515.71  6229.2  520.79
#Mann= 3 ,-1 , 0
  3326.4     .05       0  4999.2     .04       0  5005.2     .05       0
Bank Sta=4999.2,5005.2
XS Rating Curve= 0 ,0
Exp/Cntr=0.3,0.1

Type RM Length L Ch R = 1 ,8749    ,504,504,504
BEGIN DESCRIPTION:
UNT0024 IN CHRS 15.2
END DESCRIPTION:
XS GIS Cut Line= 4
      3425189.74     10589435.93      3425914.56     10588259.72
      3426036.09     10588133.85      3426622.02      10586931.6
#Sta/Elev= 30
  3530.2  498.52  3927.1  497.06  4232.3  494.37  4442.8  491.23  4720.9  483.22
    4923  483.42  4972.4  482.19  5000.7   479.5  5007.6   480.9  5011.8  479.38
  5014.6  478.88  5017.8  479.38  5021.8  483.84    5029  480.64  5035.9  483.34
  5043.1  482.17  5057.3  483.94    5137  483.11  5278.3  484.91  5289.2     486
  5294.8  485.13  5317.3  488.37  5322.9   487.1  5356.2  488.28  5390.5  486.87
  5525.7   487.6  5751.1   497.7  5936.9  508.44  6297.5  516.59  6424.2  522.53
#Mann= 3 ,-1 , 0
  3530.2     .05       0  5011.8    .035       0  5017.8     .05       0
Bank Sta=5011.8,5017.8
XS Rating Curve= 0 ,0
Exp/Cntr=0.3,0.1

Type RM Length L Ch R = 1 ,8245    ,942,942,942
BEGIN DESCRIPTION:
UNT0024 IN CHRS 13.0
END DESCRIPTION:
XS GIS Cut Line= 4
      3426145.47     10589566.99      3426286.09     10588764.92
      3426364.22     10587728.47      3426671.51     10586962.83
#Sta/Elev= 30
  3792.3   497.3  4094.3  495.67  4224.1  493.97  4262.4   492.6  4554.3  487.69
  4690.1  486.55  4840.5   481.3  4890.9  482.75  4920.8  481.56  4960.9  482.24
  4980.9  481.66    4998   478.9  5000.8   478.4    5004   478.9  5017.6   482.2
  5051.1  481.37  5101.3  482.13  5154.3  480.92  5392.1  485.63  5422.8   484.6
  5512.4  486.46  5554.5  484.79  5572.6  485.31  5650.9  490.35    5788  495.31
  5812.2  497.55  5997.8  507.74  6272.1  513.08  6379.7  516.77    6471  522.29
#Mann= 3 ,-1 , 0
  3792.3     .05       0    4998    .035       0    5004     .05       0
Bank Sta=4998,5004
XS Rating Curve= 0 ,0
Exp/Cntr=0.3,0.1

Type RM Length L Ch R = 1 ,7303    ,1296,1296,1296
BEGIN DESCRIPTION:
UNT0024 IN CHRS 10.0
END DESCRIPTION:
XS GIS Cut Line= 4
      3426587.19     10589525.31      3426864.97     10588497.52
      3426955.25     10587962.79       3427135.8     10587011.44
#Sta/Elev= 30
  3641.7  495.48  4103.9  494.32    4527  486.94  4732.6  481.03  4823.9  480.42
  4874.6  481.47  4894.6  479.79    4905  480.65  4935.4  479.58  4965.9  480.28
  4986.2  478.64  4993.3  475.61    4996  475.11  4999.3  475.61  5006.4  475.85
  5015.5   480.3  5020.6  480.63  5107.9  480.44  5136.4  481.74  5239.7  483.05
  5443.2  487.67  5580.5  494.84  5677.3  501.77  5707.9  505.47  5860.5  516.18
  5911.4  518.37  5951.4  518.77  6013.9  523.22  6135.4  528.77    6217  530.31
#Mann= 3 ,-1 , 0
  3641.7     .05       0  4993.3    .035       0  4999.3     .05       0
Bank Sta=4993.3,4999.3
XS Rating Curve= 0 ,0
Exp/Cntr=0.3,0.1

Type RM Length L Ch R = 1 ,6007    ,1297,1297,1297
BEGIN DESCRIPTION:
UNT0024 IN CHRS 9.0
END DESCRIPTION:
XS GIS Cut Line= 3
      3427448.32     10589309.99      3427601.09     10588719.74
      3428003.87     10587490.55
#Sta/Elev= 30
  4032.6  491.93  4278.8  491.88  4468.3   488.7  4625.6  482.97  4766.6  479.55
  4881.7  479.36    4977   477.7  4987.8  474.07  4998.1  473.16  5014.4  477.74
  5103.3  479.09  5229.6  475.37  5237.3  474.94  5239.5   472.5  5242.3     472
  5245.5   472.5  5250.6   472.6  5274.4  477.13  5292.7  476.48    5301  475.29
  5306.2  472.81  5345.3  476.19  5355.9   474.7  5369.9  474.59  5376.9  476.93
  5408.5  479.65  5450.6  481.48  5523.8  482.86  5671.6  489.91  5935.8     512
#Mann= 3 ,-1 , 0
  4032.6     .05       0  5239.5    .035       0  5245.5     .05       0
Bank Sta=5239.5,5245.5
XS Rating Curve= 0 ,0
Exp/Cntr=0.3,0.1

Type RM Length L Ch R = 1 ,4710    ,769,769,769
BEGIN DESCRIPTION:
UNT0024 IN CHRS 5.0
END DESCRIPTION:
XS GIS Cut Line= 3
      3428205.23     10589060.05      3428684.42     10588240.57
      3429094.13     10586622.54
#Sta/Elev= 30
  4305.1  488.65  4543.6  484.62  4666.8  484.03    4755  481.89    4813  479.94
  4870.9  476.59  4907.3  475.96  4938.7  476.47  4987.4   472.8  5000.1  470.72
  5002.9  470.22  5006.1  470.72  5009.9  472.62  5067.8  474.87  5104.8  474.97
  5157.7   473.6  5179.2  475.21  5513.1  478.03  5712.9  481.33  5917.9  483.08
  5994.7  486.48  5999.9  486.06  6035.7  488.54  6040.9  487.83  6068.2  489.07
  6245.9  485.48  6486.7  485.61  6650.7  493.33    6780  503.73  6923.5  510.95
#Mann= 3 ,-1 , 0
  4305.1     .05       0  5000.1    .035       0  5006.1     .05       0
Bank Sta=5000.1,5006.1
XS Rating Curve= 0 ,0
Exp/Cntr=0.3,0.1

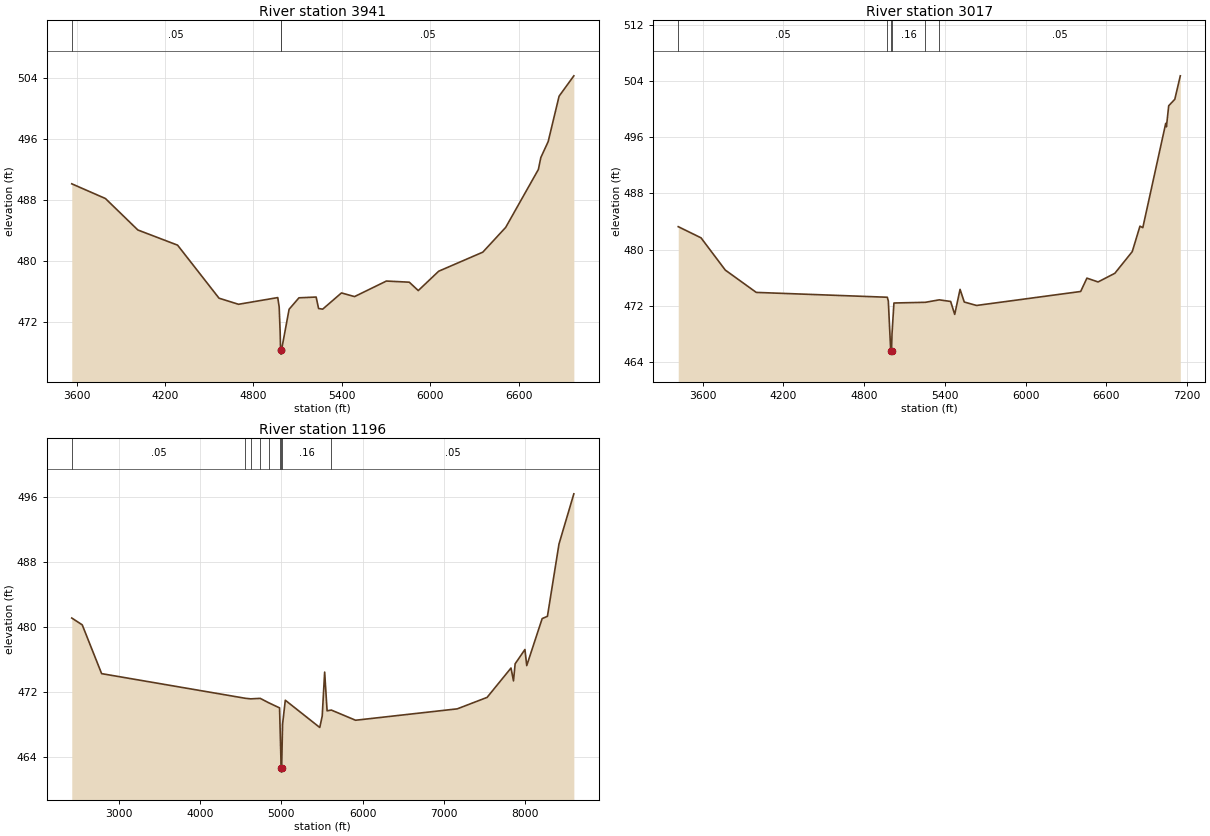
Type RM Length L Ch R = 1 ,3941    ,924,924,924
BEGIN DESCRIPTION:
UNT0024 IN CHRS 3.0
END DESCRIPTION:
XS GIS Cut Line= 3
      3427948.35      10589386.4      3429038.59     10589164.18
      3430087.17     10587122.57
#Sta/Elev= 30
  3567.2  490.17  3795.6  488.24  4015.8  484.11  4285.4  482.12  4566.7  475.16
    4699  474.36  4965.3  475.24    4975     474  4981.8  470.61  4984.5  468.32
  4987.2  467.82  4990.5  468.32  5042.4  473.71  5109.3  475.21  5225.9  475.31
  5242.4  473.81  5270.2  473.72  5397.7  475.85  5486.5  475.37  5702.7  477.41
    5858  477.26    5919  476.16  6057.7   478.7  6357.1   481.2  6512.4  484.45
  6734.2  492.05  6750.8  493.61  6800.8  495.71  6874.9  501.67    6975  504.34
#Mann= 3 ,-1 , 0
  3567.2     .05       0  4984.5    .035       0  4990.5     .05       0
Bank Sta=4984.5,4990.5
XS Rating Curve= 0 ,0
Exp/Cntr=0.3,0.1

Type RM Length L Ch R = 1 ,3017    ,1829,1829,1829
BEGIN DESCRIPTION:
UNT0024 IN CHRS 2.0
END DESCRIPTION:
XS GIS Cut Line= 4
      3428392.77     10589657.24       3429649.7     10589615.57
      3430121.92     10589219.74      3430413.57     10587386.49
#Sta/Elev= 30
  3419.6  483.26    3589  481.67  3769.1  477.08  3999.3   473.9  4972.8  473.21
  4980.4  472.68  4998.2  465.61    5001  465.11  5004.2  465.61  5007.8     468
  5022.1  472.39  5256.1  472.49  5358.6  472.84  5443.4  472.61  5473.7  470.77
  5513.3  474.33  5544.6  472.53  5635.7  472.04  6409.4  474.03  6455.9  475.93
  6538.9  475.39  6663.3  476.62  6792.7  479.71  6849.9  483.33  6871.1  483.12
  7041.5  497.98  7046.6  497.48  7063.5  500.48  7108.8   501.4  7149.7  504.74
#Mann= 6 ,-1 , 0
  3419.6     .05       0  4972.8     .16       0  4998.2     .07       0
  5004.2     .16       0  5256.1      .1       0  5358.6     .05       0
Bank Sta=4998.2,5004.2
XS Rating Curve= 0 ,0
Exp/Cntr=0.3,0.1

Type RM Length L Ch R = 1 ,1196    ,0,0,0
BEGIN DESCRIPTION:
UNT0024 IN CHRS 1.0
END DESCRIPTION:
XS GIS Cut Line= 5
      3428457.94     10589739.86      3430700.94     10590038.46
      3431353.72     10589850.96      3431437.06     10588003.74
      3431173.17     10586642.65
#Sta/Elev= 30
  2420.6  481.11  2549.3  480.27    2788  474.27  4556.2  471.24  4622.2  471.17
  4739.2  471.23  4843.3  470.69  4977.3  470.06    4997  462.66  4999.8  462.16
    5003  462.66  5014.2  468.05  5047.9     471    5472  467.65    5502  469.05
  5532.1  474.46  5562.1   469.7  5614.5  469.79  5912.4  468.54  7163.7  469.94
  7530.7  471.35    7825  474.96  7855.5  473.38  7875.9  475.48  7996.3  477.24
  8018.5  475.26  8208.3  481.04  8273.2  481.32  8415.3  490.21  8598.1  496.38
#Mann= 9 ,-1 , 0
  2420.6     .05       0  4556.2      .1       0  4622.2     .05       0
  4739.2      .1       0  4843.3     .05       0  4977.3     .16       0
    4997     .07       0    5003     .16       0  5614.5     .05       0
Bank Sta=4997,5003
XS Rating Curve= 0 ,0
Exp/Cntr=0.3,0.1

Chan Stop Cuts=-1
Use User Specified Reach Order=0
Composite Channel Slope=5