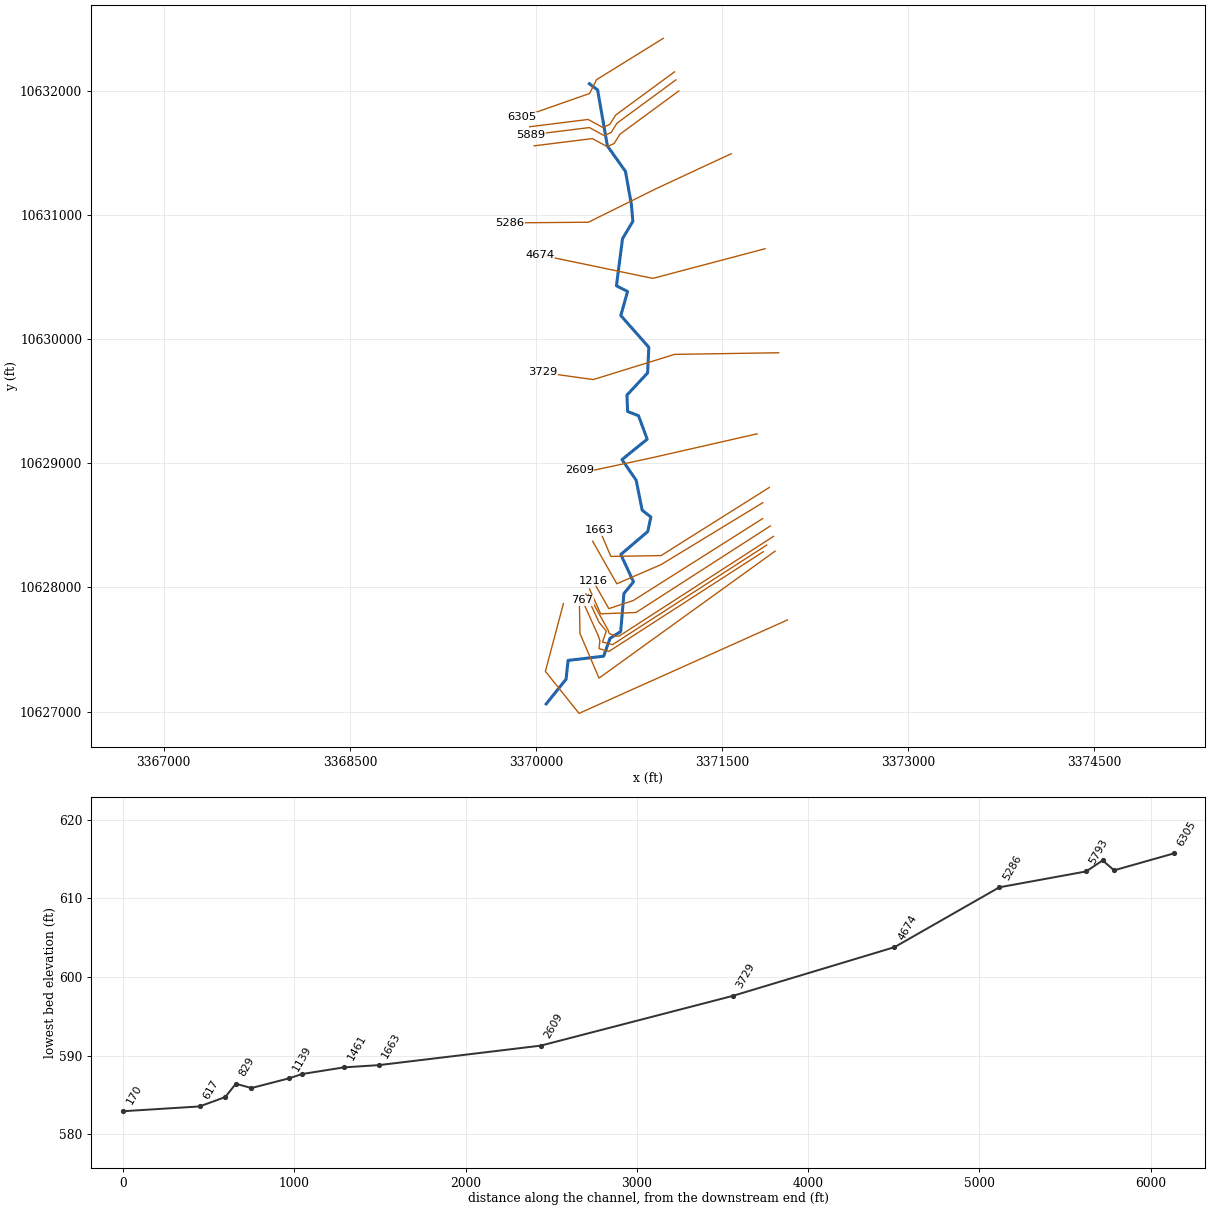
--- UNT00253 IN CHRS.prj (project) ---

Proj Title=UNT00253 IN CHRS Base Level Engineering
Current Plan=p01
Default Exp/Contr=0.3,0.1
English Units
Geom File=g01
Flow File=f01
Plan File=p01
Y Axis Title=Elevation
X Axis Title(PF)=Main Channel Distance
X Axis Title(XS)=Station
BEGIN DESCRIPTION:
UNT00253 IN CHRS
END DESCRIPTION:
DSS Export Rating Curves= 0
DSS Export Rating Curve Sorted= 0
DSS Export Volume Flow Curves= 0
DXF OffsetX= 0
DXF OffsetY= 0
DXF ScaleX= 1
DXF ScaleY= 10

--- UNT00253 IN CHRS.p01 (plan) ---

Plan Title=Multiple Run
Short Identifier=Multiple
Geom File=g01
Flow File=f01
Subcritical Flow
K Sum by GR= 0
Std Step Tol= 0.01
Critical Tol= 0.01
Num of Std Step Trials= 20
Max Error Tol= 0.3
Flow Tol Ratio= 0.001
Split Flow NTrial= 30
Split Flow Tol= 0.02
Split Flow Ratio= 0.02
Log Output Level= 0
Friction Slope Method= 1
Unsteady Friction Slope Method= 2
Unsteady Bridges Friction Slope Method= 1
Parabolic Critical Depth
Global Vel Dist=  1 , 1 , 1
Global Log Level= 0
CheckData=True
Encroach Param= -1, 0, 0, 0
BEGIN DESCRIPTION:
Multiple Run
END DESCRIPTION:

--- UNT00253 IN CHRS.f01 (steady flow) ---

Flow Title=Multiple
Number of Profiles=7
Profile Names=10-year,25-year,50-year,1pct_min,100-year,1pct_plu,500-year
River Rch & RM= UNT00253 IN CHRS,Reach-1,6305
     209     253     285     234     316     427     388
River Rch & RM= UNT00253 IN CHRS,Reach-1,1216
     308     383     438     365     493     667     625
Boundary for River Rch & Prof#=UNT00253 IN CHRS,Reach-1,1
Up Type=0
Dn Type=3
Dn Slope=0.005
Boundary for River Rch & Prof#=UNT00253 IN CHRS,Reach-1,2
Up Type=0
Dn Type=3
Dn Slope=0.005
Boundary for River Rch & Prof#=UNT00253 IN CHRS,Reach-1,3
Up Type=0
Dn Type=3
Dn Slope=0.005
Boundary for River Rch & Prof#=UNT00253 IN CHRS,Reach-1,4
Up Type=0
Dn Type=3
Dn Slope=0.005
Boundary for River Rch & Prof#=UNT00253 IN CHRS,Reach-1,5
Up Type=0
Dn Type=3
Dn Slope=0.005
Boundary for River Rch & Prof#=UNT00253 IN CHRS,Reach-1,6
Up Type=0
Dn Type=3
Dn Slope=0.005
Boundary for River Rch & Prof#=UNT00253 IN CHRS,Reach-1,7
Up Type=0
Dn Type=3
Dn Slope=0.005

--- UNT00253 IN CHRS.g01 (geometry) ---

Geom Title=Existing Conditions
Program Version=4.10

River Reach=UNT00253 IN CHRS,Reach-1
Reach XY= 30
      3370430.11     10632060.37      3370496.58     10632010.34
      3370575.57     10631558.95      3370721.27     10631353.65
      3370768.81     10631085.95      3370780.79     10630951.66
      3370697.25     10630810.74      3370648.32     10630431.98
      3370738.32     10630386.02      3370683.37     10630192.06
      3370909.38     10629936.23      3370899.39     10629729.33
      3370733.37     10629551.36      3370738.19     10629418.97
      3370826.58     10629384.02      3370896.21     10629195.55
      3370692.86     10629030.83      3370807.61      10628864.5
      3370855.83     10628623.12      3370925.89     10628567.89
      3370900.94     10628451.48      3370683.62       10628266.
      3370785.89     10628045.56      3370708.74     10627951.44
      3370682.51      10627644.8      3370596.77     10627590.62
       3370545.2     10627446.35      3370258.46     10627412.02
      3370242.36     10627261.04      3370082.11     10627061.64

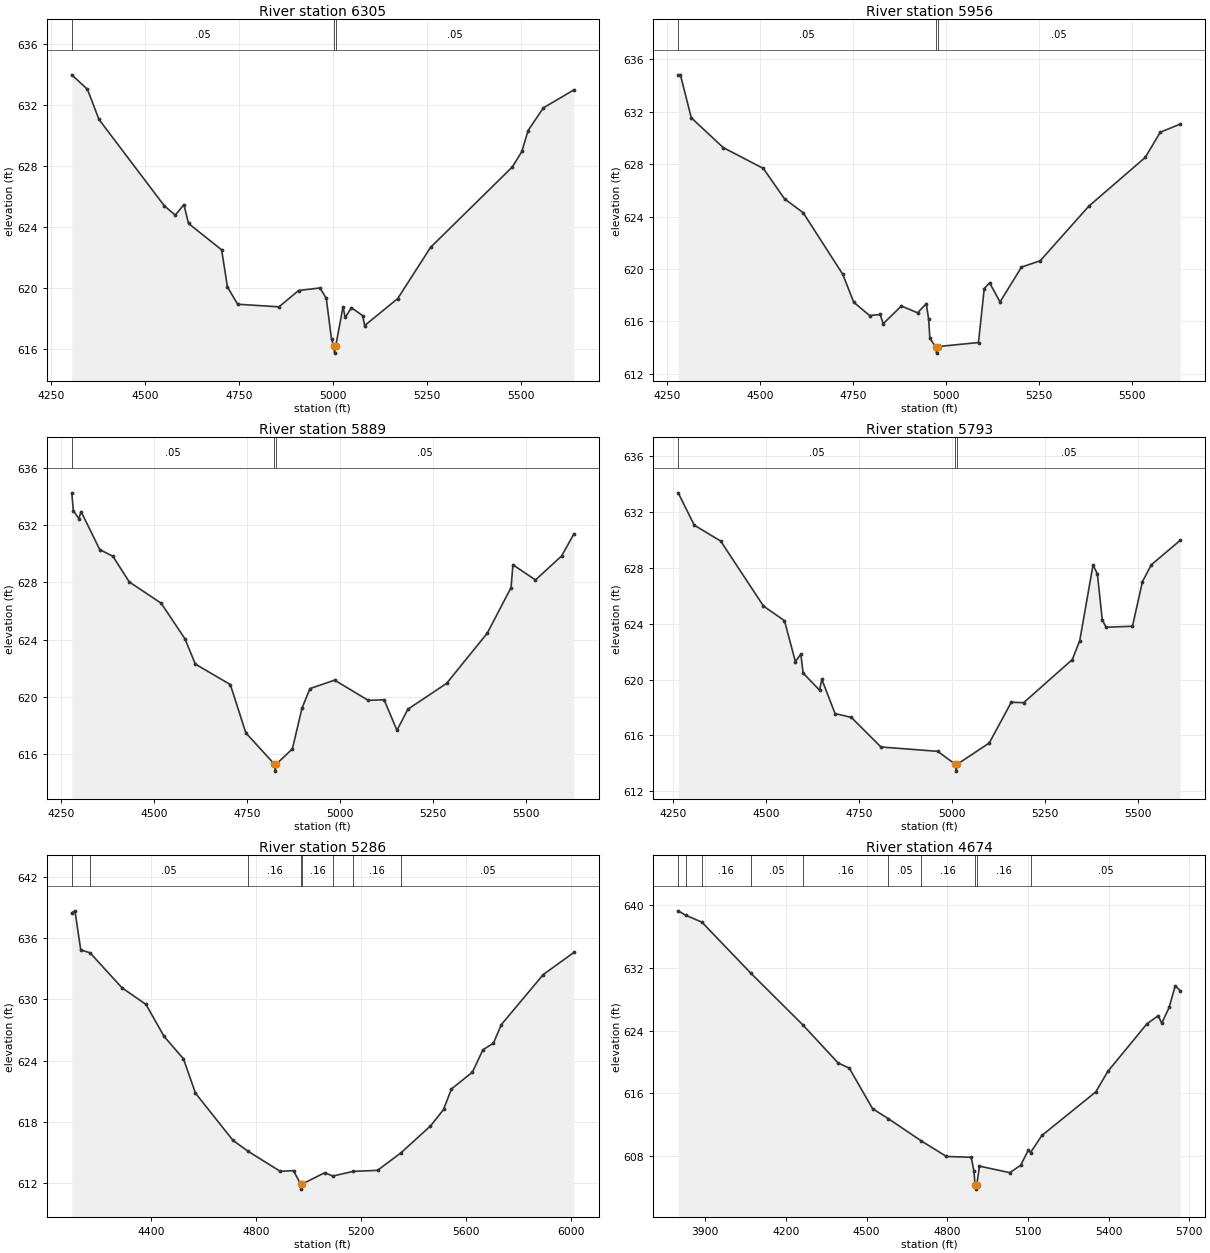
Type RM Length L Ch R = 1 ,6305    ,349,349,349
BEGIN DESCRIPTION:
UNT00253 IN CHRS 9.3
END DESCRIPTION:
XS GIS Cut Line= 4
      3371026.04     10632426.43      3370487.84     10632093.09
      3370432.29     10631981.98      3369887.15     10631791.01
#Sta/Elev= 30
    4305  633.99  4346.7  633.04  4377.4  631.06  4551.1  625.39  4580.2  624.78
  4603.1  625.47  4615.5  624.23  4703.5   622.5  4718.9  620.06  4746.1  618.93
    4856  618.76    4908  619.83  4964.8     620  4981.6  619.32  4995.6  616.64
    5001  616.22  5003.7  615.72    5007  616.22  5026.3  618.77  5031.9  618.06
  5048.7   618.7  5078.4  618.18  5083.7  617.53  5171.5   619.3  5259.2  622.67
  5476.3  627.94    5502  628.97  5518.1  630.33  5558.8  631.82  5639.9     633
#Mann= 3 ,-1 , 0
    4305     .05       0    5001    .035       0    5007     .05       0
Bank Sta=5001,5007
XS Rating Curve= 0 ,0
Exp/Cntr=0.3,0.1

Type RM Length L Ch R = 1 ,5956    ,67,67,67
BEGIN DESCRIPTION:
UNT00253 IN CHRS 9.2
END DESCRIPTION:
XS GIS Cut Line= 6
      3371116.53     10632156.56      3370641.28     10631807.17
       3370595.7     10631733.39      3370539.28     10631707.35
      3370419.92     10631772.45      3369949.03     10631713.86
#Sta/Elev= 30
  4280.4  634.82  4286.2  634.82  4315.5  631.54  4401.1  629.27  4509.3  627.67
  4566.2  625.35  4616.4  624.29  4722.9  619.58  4752.2  617.46  4794.8  616.44
  4823.2  616.52  4831.6  615.82  4880.4  617.17  4923.8  616.65  4947.3  617.34
  4953.7  616.15    4957  614.69  4972.3  614.07    4975  613.57  4978.3  614.07
  5087.7  614.38  5103.1   618.5  5117.5  618.94  5145.6  617.48  5203.3  620.14
  5253.5  620.62  5383.9  624.78  5535.9  628.51  5576.5  630.44  5630.3  631.06
#Mann= 3 ,-1 , 0
  4280.4     .05       0  4972.3    .035       0  4978.3     .05       0
Bank Sta=4972.3,4978.3
XS Rating Curve= 0 ,0
Exp/Cntr=0.3,0.1

Type RM Length L Ch R = 1 ,5889    ,96,96,96
BEGIN DESCRIPTION:
UNT00253 IN CHRS 9.0
END DESCRIPTION:
XS GIS Cut Line= 6
      3371127.39     10632091.46      3370652.13     10631742.07
      3370606.56     10631668.28      3370550.13     10631642.24
      3370430.77     10631707.35      3369959.89     10631648.76
#Sta/Elev= 30
  4279.1  634.25  4283.3  633.01    4298  632.45  4304.2  632.94  4354.3  630.29
  4389.8  629.82  4433.8  628.03  4519.4  626.55  4583.5  624.06  4611.3   622.3
  4705.4  620.87  4747.1   617.5  4823.5  615.33  4826.3  614.83  4829.5  615.33
  4872.2  616.38  4898.2  619.23  4919.5  620.59  4985.8  621.18  5076.2  619.77
  5118.9  619.81  5153.4  617.68  5182.8  619.15  5286.7  620.95  5396.1  624.45
  5460.2  627.64  5465.2  629.23  5525.8  628.17  5596.3  629.85    5629  631.38
#Mann= 3 ,-1 , 0
  4279.1     .05       0  4823.5    .035       0  4829.5     .05       0
Bank Sta=4823.5,4829.5
XS Rating Curve= 0 ,0
Exp/Cntr=0.3,0.1

Type RM Length L Ch R = 1 ,5793    ,507,507,507
BEGIN DESCRIPTION:
UNT00253 IN CHRS 9.1
END DESCRIPTION:
XS GIS Cut Line= 6
      3371151.23     10632002.46        3370676.     10631653.09
      3370630.43     10631579.31        3370574.     10631553.27
      3370454.65     10631618.37       3369985.4     10631560.06
#Sta/Elev= 30
    4265  633.39    4308  631.07    4379  629.93  4493.9  625.27  4550.3  624.22
  4579.6  621.28  4594.2  621.83  4600.4  620.46  4644.4  619.24  4650.6  620.01
  4686.1  617.56    4730  617.28  4809.4  615.16  4961.7  614.85  5008.5  613.93
  5011.3  613.43  5014.5  613.93  5100.2  615.45  5159.3  618.37  5192.6  618.34
  5323.1  621.43  5343.1  622.78  5378.8  628.21  5390.5  627.58  5403.6  624.29
  5413.7  623.75  5484.7  623.82  5511.6  627.03  5535.4  628.23  5613.2  629.99
#Mann= 3 ,-1 , 0
    4265     .05       0  5008.5    .035       0  5014.5     .05       0
Bank Sta=5008.5,5014.5
XS Rating Curve= 0 ,0
Exp/Cntr=0.3,0.1

Type RM Length L Ch R = 1 ,5286    ,612,612,612
BEGIN DESCRIPTION:
UNT00253 IN CHRS 7.0
END DESCRIPTION:
XS GIS Cut Line= 4
      3371573.13     10631496.24      3370968.98       10631215.
       3370422.1     10630944.16      3369785.59     10630938.97
#Sta/Elev= 30
  4097.9  638.47  4110.1  638.67  4132.1  634.84  4167.6  634.56  4289.3  631.13
  4380.8   629.5  4449.4  626.38  4523.6  624.17  4569.3  620.81  4712.1  616.19
  4770.9   615.1  4892.5  613.15  4942.9  613.22  4969.8  611.91  4972.6  611.41
  4975.8  611.91  5062.1  613.02  5092.5  612.69  5170.7  613.15    5263  613.25
    5352  614.96  5464.6  617.59  5514.6  619.21  5544.6  621.22  5624.6  622.87
  5664.6  625.06  5704.6   625.7  5734.6  627.52  5894.6  632.43  6011.1  634.59
#Mann= 8 ,-1 , 0
  4097.9     .16       0  4167.6     .05       0  4770.9     .16       0
  4969.8     .07       0  4975.8     .16       0  5092.5     .05       0
  5170.7     .16       0    5352     .05       0
Bank Sta=4969.8,4975.8
XS Rating Curve= 0 ,0
Exp/Cntr=0.3,0.1

Type RM Length L Ch R = 1 ,4674    ,945,945,945
BEGIN DESCRIPTION:
UNT00253 IN CHRS 6.0
END DESCRIPTION:
XS GIS Cut Line= 3
      3371846.62     10630730.63      3370941.55     10630491.55
       3370031.5     10630681.14
#Sta/Elev= 30
  3800.4  639.27  3827.4  638.72  3888.2  637.83    4070  631.33  4262.4  624.77
  4394.6  619.88    4436  619.22  4522.4  614.06  4580.8  612.79    4703  609.96
  4797.2  607.96  4889.2  607.86  4899.4  606.06  4903.5   604.3  4906.3   603.8
  4909.5   604.3  4919.8  606.73  5032.2   605.9    5073  606.84  5101.6   608.8
  5109.5  608.46  5151.7  610.64  5351.9  616.19  5396.8  618.81  5541.9  624.86
  5583.8   625.9  5597.1  624.95  5624.6  626.96  5647.1  629.71  5666.1   629.1
#Mann= 10 ,-1 , 0
  3800.4     .16       0  3827.4     .05       0  3888.2     .16       0
    4070     .05       0  4262.4     .16       0  4580.8     .05       0
    4703     .16       0  4903.5     .07       0  4909.5     .16       0
  5109.5     .05       0
Bank Sta=4903.5,4909.5
XS Rating Curve= 0 ,0
Exp/Cntr=0.3,0.1

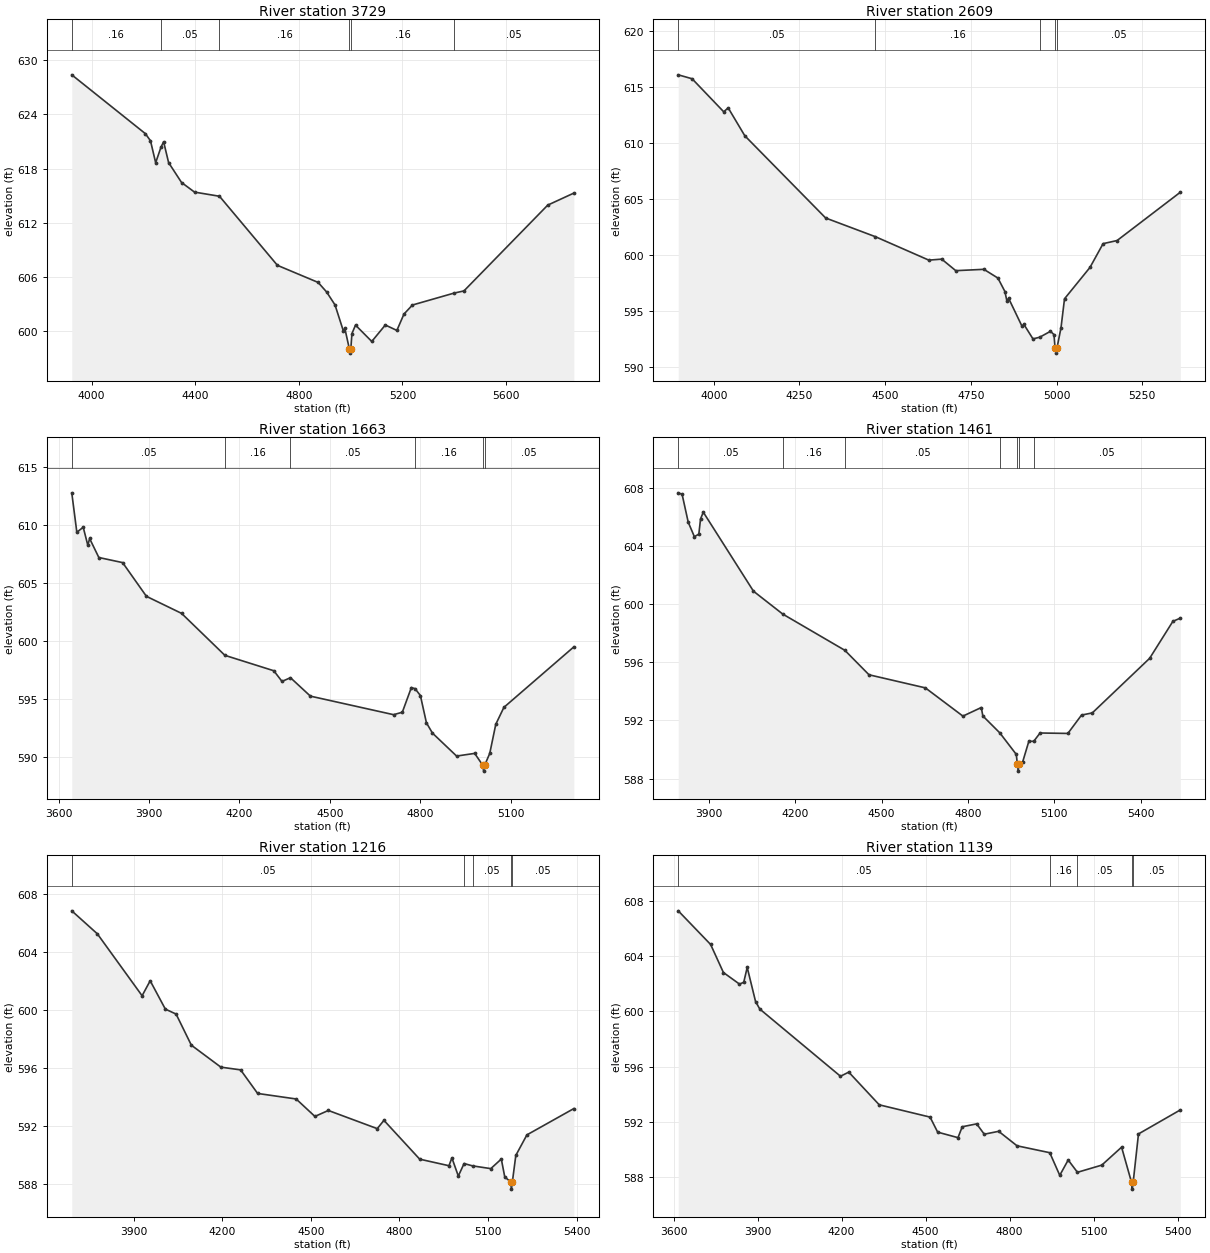
Type RM Length L Ch R = 1 ,3729    ,1120,1120,1120
BEGIN DESCRIPTION:
UNT00253 IN CHRS 4.0
END DESCRIPTION:
XS GIS Cut Line= 4
      3371955.98     10629892.08      3371117.41     10629879.06
      3370461.16     10629675.93       3370052.3     10629733.23
#Sta/Elev= 30
  3923.3  628.38  4207.2  621.88  4227.2  621.09  4247.2  618.66  4267.4  620.35
  4277.9  620.98  4297.2  618.67  4347.2  616.47  4397.2  615.41  4493.6  614.95
  4717.3  607.31  4874.5  605.42  4907.1  604.37  4939.7  602.93  4972.4  600.01
  4977.6  600.34  4994.8   598.1  4997.6   597.6  5000.8   598.1    5005  599.76
  5018.8   600.7  5081.6  598.89  5133.9  600.71  5178.5  600.11  5205.9  601.92
  5238.5  602.92  5399.4  604.24  5437.5  604.48    5761  613.97  5861.8   615.3
#Mann= 6 ,-1 , 0
  3923.3     .16       0  4267.4     .05       0  4493.6     .16       0
  4994.8     .07       0  5000.8     .16       0  5399.4     .05       0
Bank Sta=4994.8,5000.8
XS Rating Curve= 0 ,0
Exp/Cntr=0.3,0.1

Type RM Length L Ch R = 1 ,2609    ,946,946,946
BEGIN DESCRIPTION:
UNT00253 IN CHRS 2.0
END DESCRIPTION:
XS GIS Cut Line= 4
      3371781.51     10629238.44      3370924.45     10629043.44
      3370469.08     10628946.14      3370349.14     10628949.37
#Sta/Elev= 30
  3896.4  616.12  3936.8  615.77  4029.1  612.82  4042.1  613.17  4090.6  610.68
  4326.5  603.34  4471.7  601.67  4627.4  599.58    4665  599.67    4706  598.64
    4788  598.76  4828.9  597.98  4849.3  596.78  4855.1  595.94  4860.2  596.17
  4899.5  593.66  4904.6  593.85  4931.2  592.55  4950.9   592.7  4982.3  593.23
  4992.5  592.93  4995.5  591.78  4998.2  591.28  5001.5  591.78    5013  593.55
  5023.2  596.13  5097.5  598.93  5135.7  601.05  5176.6  601.33    5361  605.64
#Mann= 5 ,-1 , 0
  3896.4     .05       0  4471.7     .16       0  4950.9     .05       0
  4995.5    .035       0  5001.5     .05       0
Bank Sta=4995.5,5001.5
XS Rating Curve= 0 ,0
Exp/Cntr=0.3,0.1

Type RM Length L Ch R = 1 ,1663    ,202,202,202
BEGIN DESCRIPTION:
UNT00253 IN CHRS 3.1
END DESCRIPTION:
XS GIS Cut Line= 4
      3371880.47     10628806.17        3371008.     10628257.18
       3370603.2     10628250.58      3370513.25     10628462.39
#Sta/Elev= 30
  3643.6  612.81  3660.4  609.41  3681.6  609.84  3696.9  608.28  3702.8  608.87
  3733.4  607.23  3812.3  606.79  3891.3  603.88  4007.9  602.41  4151.6  598.79
  4313.9  597.46  4341.1  596.54  4369.2  596.86  4435.3  595.27  4711.3  593.67
  4740.3  593.88  4770.3  596.01  4782.8  595.91  4800.3  595.32  4820.3  592.97
  4840.3  592.08  4920.4   590.1  4980.4  590.33  5007.4   589.3  5010.1   588.8
  5013.4   589.3  5030.4  590.33  5050.4  592.84  5077.3   594.3  5309.4  599.52
#Mann= 6 ,-1 , 0
  3643.6     .05       0  4151.6     .16       0  4369.2     .05       0
  4782.8     .16       0  5007.4     .07       0  5013.4     .05       0
Bank Sta=5007.4,5013.4
XS Rating Curve= 0 ,0
Exp/Cntr=0.3,0.1

Type RM Length L Ch R = 1 ,1461    ,245,245,245
BEGIN DESCRIPTION:
UNT00253 IN CHRS 2.2
END DESCRIPTION:
XS GIS Cut Line= 4
      3371828.33     10628683.74      3371009.85     10628185.54
      3370651.27      10628030.1      3370456.53     10628372.84
#Sta/Elev= 30
  3794.2  607.64  3807.6  607.54  3828.9  605.62  3850.2  604.63  3865.7   604.8
  3871.7  605.85  3881.2  606.31  4055.5  600.88  4157.1  599.31  4372.7  596.82
  4456.5  595.14  4652.2  594.24  4782.6   592.3  4846.4  592.89  4851.8  592.31
  4910.6  591.15  4967.9  589.67  4971.6  589.02  4974.4  588.52  4977.6  589.02
  4989.7  589.13  5011.5  590.57  5028.5  590.57  5050.5  591.14    5147  591.11
  5194.4  592.37  5231.9  592.52  5430.9  596.27  5511.6  598.81  5537.4  599.03
#Mann= 7 ,-1 , 0
  3794.2     .05       0  4157.1     .16       0  4372.7     .05       0
  4910.6     .16       0  4971.6     .07       0  4977.6     .16       0
  5028.5     .05       0
Bank Sta=4971.6,4977.6
XS Rating Curve= 0 ,0
Exp/Cntr=0.3,0.1

Type RM Length L Ch R = 1 ,1216    ,77,77,77
BEGIN DESCRIPTION:
UNT00253 IN CHRS 3.0
END DESCRIPTION:
XS GIS Cut Line= 4
       3371826.6     10628555.26      3370784.95     10627895.55
      3370587.03     10627829.58      3370458.56     10628055.27
#Sta/Elev= 30
  3689.7  606.81  3776.3  605.23    3928  600.97  3955.4     602  4006.8  600.05
  4043.2  599.71  4094.9  597.57  4194.9  596.06  4261.9  595.87  4319.5  594.25
    4450  593.87  4513.6  592.67  4559.1  593.08  4724.8  591.83  4747.5   592.4
  4868.7  589.73  4967.8  589.28  4977.8  589.82  4999.5  588.57  5019.1  589.43
  5047.6  589.27  5109.6  589.08  5145.2  589.74  5156.9  588.51  5176.7  588.17
  5179.5  587.67  5182.7  588.17  5194.4  589.99  5231.9   591.4    5391  593.21
#Mann= 5 ,-1 , 0
  3689.7     .05       0  5019.1     .16       0  5047.6     .05       0
  5176.7     .04       0  5182.7     .05       0
Bank Sta=5176.7,5182.7
XS Rating Curve= 0 ,0
Exp/Cntr=0.3,0.1

Type RM Length L Ch R = 1 ,1139    ,219,219,219
BEGIN DESCRIPTION:
UNT00253 IN CHRS 2.1
END DESCRIPTION:
XS GIS Cut Line= 4
      3371889.15     10628496.27      3370805.78     10627798.33
      3370521.06     10627787.91      3370431.37       10627988.
#Sta/Elev= 30
  3616.8  607.29  3732.5  604.85  3778.1  602.82  3835.5  601.98  3850.7  602.11
  3863.1  603.19    3893  600.71  3908.1  600.17  4196.2   595.3  4225.7   595.6
  4334.6  593.23  4516.1  592.34  4543.2  591.25  4615.8  590.85    4631  591.64
  4682.5  591.85  4709.6   591.1  4761.1  591.31  4826.6  590.26  4943.5  589.76
  4979.2  588.12  5009.3  589.23  5042.4  588.34  5129.3  588.86    5200  590.16
  5235.4  587.62  5238.1  587.12  5241.4  587.62  5260.3  591.12  5409.7  592.86
#Mann= 5 ,-1 , 0
  3616.8     .05       0  4943.5     .16       0  5042.4     .05       0
  5235.4     .07       0  5241.4     .05       0
Bank Sta=5235.4,5241.4
XS Rating Curve= 0 ,0
Exp/Cntr=0.3,0.1

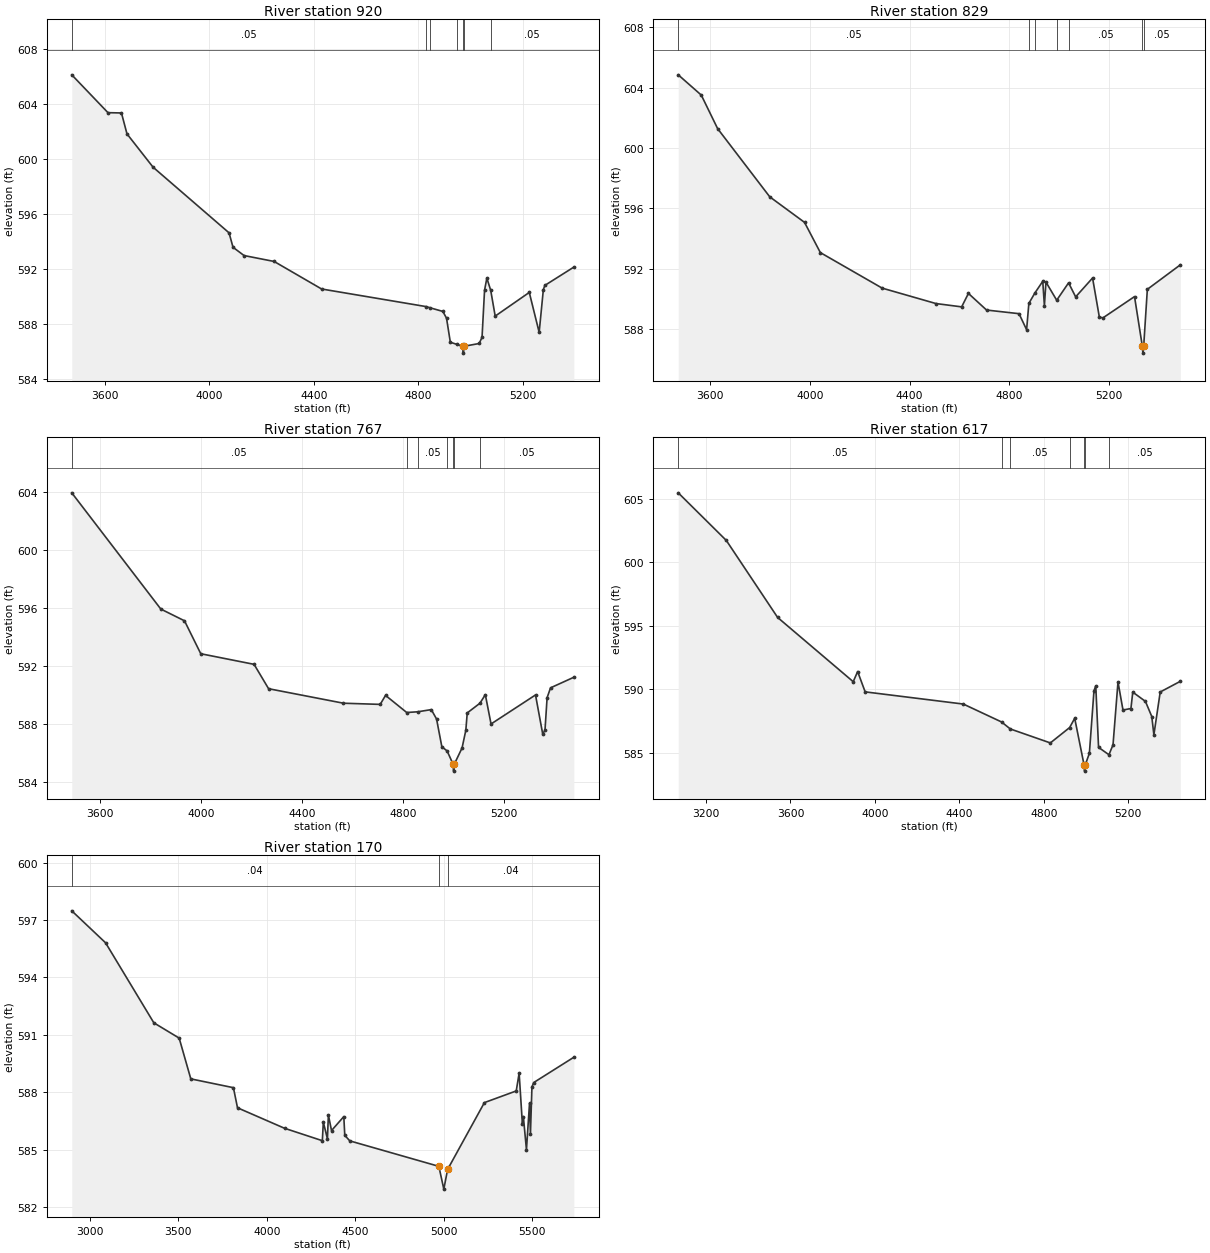
Type RM Length L Ch R = 1 ,920     ,91,91,91
BEGIN DESCRIPTION:
UNT00253 IN CHRS 1.2
END DESCRIPTION:
XS GIS Cut Line= 6
      3371913.63     10628411.53      3370669.89     10627608.41
       3370637.6     10627607.89      3370589.68     10627630.29
      3370581.87     10627655.29      3370422.48     10627942.29
#Sta/Elev= 30
  3474.2  606.11  3612.7  603.36  3664.3  603.34  3685.4  601.82  3785.2   599.4
  4075.9  594.63  4091.1  593.58  4133.3  592.98  4248.4  592.55    4430  590.55
  4830.1  589.27  4843.8  589.19  4893.9  588.92  4907.9  588.43  4922.5  586.68
  4946.9  586.53  4969.6  586.39  4972.4  585.89  4975.6  586.39  5032.8  586.59
  5043.8  587.04  5053.4  590.46  5062.2  591.34    5077  590.45  5094.1  588.58
  5224.5   590.3  5262.3   587.4  5278.3   590.5    5284  590.81    5395  592.14
#Mann= 7 ,-1 , 0
  3474.2     .05       0  4830.1     .16       0  4843.8     .05       0
  4946.9     .16       0  4969.6     .07       0  4975.6     .16       0
    5077     .05       0
Bank Sta=4969.6,4975.6
XS Rating Curve= 0 ,0
Exp/Cntr=0.3,0.1

Type RM Length L Ch R = 1 ,829     ,62,62,62
BEGIN DESCRIPTION:
UNT00253 IN CHRS 1.9
END DESCRIPTION:
XS GIS Cut Line= 6
      3371859.81     10628342.09      3370616.07     10627538.97
      3370535.86     10627560.84      3370566.59     10627648.86
      3370507.56     10627720.05      3370402.27     10627947.89
#Sta/Elev= 30
  3472.6  604.84  3564.9   603.5  3630.5  601.28  3839.3  596.77  3978.7  595.08
  4042.1  593.08  4289.8  590.73  4505.2  589.71  4608.3  589.49  4635.4  590.38
  4708.1  589.28  4838.2  589.04  4868.6  587.98  4877.6  589.72  4901.8  590.41
  4933.3  591.18  4939.9  589.57  4946.1  591.13  4989.2  589.93  5036.8  591.08
  5065.1  590.15  5132.9   591.4    5160  588.82  5174.3  588.76    5301  590.17
  5331.9  586.93  5334.7  586.43  5337.9  586.93  5352.4  590.65  5484.5  592.27
#Mann= 7 ,-1 , 0
  3472.6     .05       0  4877.6     .16       0  4901.8     .05       0
  4989.2     .16       0  5036.8     .05       0  5331.9     .07       0
  5337.9     .05       0
Bank Sta=5331.9,5337.9
XS Rating Curve= 0 ,0
Exp/Cntr=0.3,0.1

Type RM Length L Ch R = 1 ,767     ,150,150,150
BEGIN DESCRIPTION:
UNT00253 IN CHRS 1.3
END DESCRIPTION:
XS GIS Cut Line= 6
      3371832.03     10628288.27      3370588.29     10627485.15
      3370508.08     10627507.02      3370514.85     10627572.13
      3370500.62     10627614.14      3370373.87     10627895.41
#Sta/Elev= 30
  3487.9  603.92  3840.5  595.91  3934.3   595.1  3998.8  592.83  4209.8   592.1
  4267.3  590.42  4563.9  589.42  4709.3  589.34  4730.4  589.96  4814.3  588.78
  4858.2  588.83  4911.6  588.98  4932.5  588.33  4953.4  586.42  4974.3  586.13
  4997.3  585.24    5000  584.74  5003.3  585.24  5033.5  586.34  5048.4  587.56
  5053.9  588.75  5104.3  589.42  5125.6  590.01  5148.2  587.99  5324.3  589.99
  5352.7  587.31  5361.8  587.55  5370.2   589.8  5383.8  590.48  5476.1  591.21
#Mann= 7 ,-1 , 0
  3487.9     .05       0  4814.3     .16       0  4858.2     .05       0
  4974.3     .16       0  4997.3     .07       0  5003.3     .16       0
  5104.3     .05       0
Bank Sta=4997.3,5003.3
XS Rating Curve= 0 ,0
Exp/Cntr=0.3,0.1

Type RM Length L Ch R = 1 ,617     ,447,447,447
BEGIN DESCRIPTION:
UNT00253 IN CHRS 1.1
END DESCRIPTION:
XS GIS Cut Line= 4
      3371927.34     10628293.14      3370508.04     10627269.68
      3370354.39     10627629.06       3370350.1     10627866.86
#Sta/Elev= 30
  3068.2  605.46    3296  601.71    3539  595.65  3897.2  590.59  3918.1  591.39
  3953.7  589.79  4418.8  588.83  4599.9  587.42  4641.3  586.87    4831  585.77
  4922.4  586.98  4946.4  587.71  4990.6  584.05  4993.3  583.55  4996.6  584.05
  5015.9  584.95  5037.7  589.88  5046.2  590.26  5059.4  585.42  5108.6  584.84
  5127.9  585.62  5151.5  590.57  5175.1  588.36  5212.7  588.48  5221.5  589.77
  5281.5  589.04  5311.5  587.85  5321.5  586.41  5351.5  589.78  5446.7  590.62
#Mann= 7 ,-1 , 0
  3068.2     .05       0  4599.9     .16       0  4641.3     .05       0
  4922.4     .16       0  4990.6     .07       0  4996.6     .16       0
  5108.6     .05       0
Bank Sta=4990.6,4996.6
XS Rating Curve= 0 ,0
Exp/Cntr=0.3,0.1

Type RM Length L Ch R = 1 ,170     ,0,0,0
BEGIN DESCRIPTION:
UNT00253 IN CHRS 1.0
END DESCRIPTION:
XS GIS Cut Line= 4
      3372026.58     10627738.41      3370346.92     10626985.39
      3370075.65     10627323.93      3370221.04     10627870.78
#Sta/Elev= 30
  2896.9  597.48  3088.1  595.81  3361.1  591.63  3504.5  590.83  3570.3   588.7
  3811.4  588.24  3834.5  587.19  4100.4  586.12  4314.5  585.47    4320  586.44
  4343.2  585.57  4348.7  586.81  4366.4     586  4435.9  586.73  4441.4  585.75
    4470  585.46  4973.6  584.13  5001.7  582.94  5023.2  583.97  5231.2  587.46
  5411.4  588.07  5427.8     589  5446.4  586.32  5451.6  586.73  5469.2     585
  5486.6  587.43  5491.8  585.82  5500.2  588.28  5510.6  588.51  5737.3  589.83
#Mann= 3 , 0 , 0
  2896.9     .04       0  4973.6     .03       0  5023.2     .04       0
Bank Sta=4973.6,5023.2
XS Rating Curve= 0 ,0
Exp/Cntr=0.3,0.1

Chan Stop Cuts=-1
Use User Specified Reach Order=0
Composite Channel Slope=5