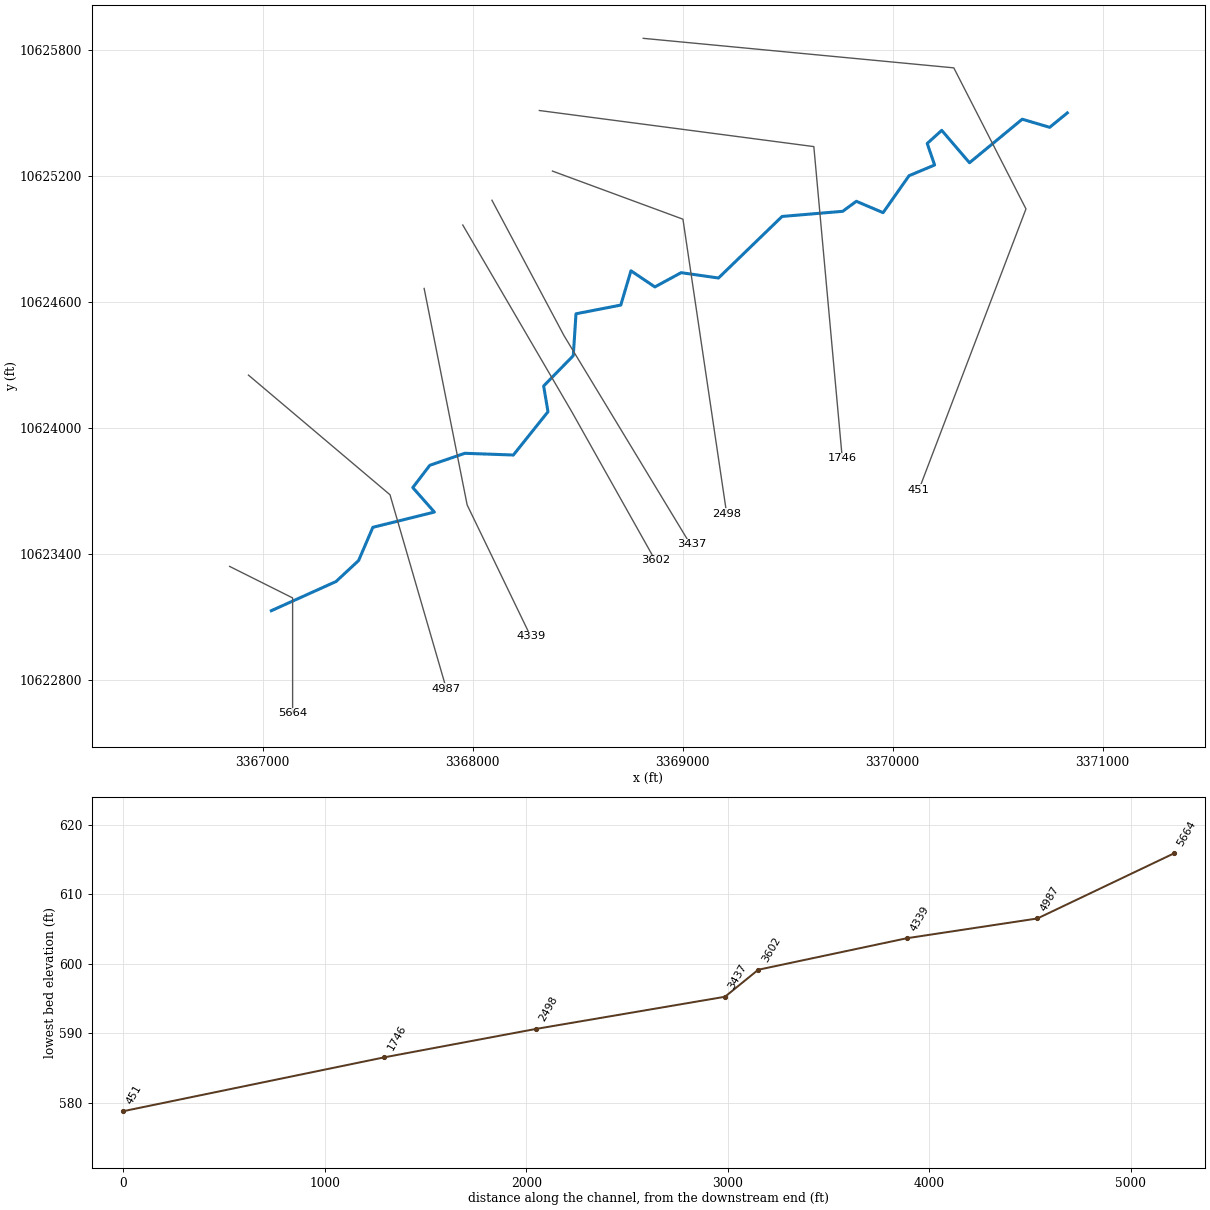
--- UNT00255 IN CHRS.prj (project) ---

Proj Title=UNT00255 IN CHRS Base Level Engineering
Current Plan=p01
Default Exp/Contr=0.3,0.1
English Units
Geom File=g01
Flow File=f01
Plan File=p01
Y Axis Title=Elevation
X Axis Title(PF)=Main Channel Distance
X Axis Title(XS)=Station
BEGIN DESCRIPTION:
UNT00255 IN CHRS
END DESCRIPTION:
DSS Export Rating Curves= 0
DSS Export Rating Curve Sorted= 0
DSS Export Volume Flow Curves= 0
DXF OffsetX= 0
DXF OffsetY= 0
DXF ScaleX= 1
DXF ScaleY= 10

--- UNT00255 IN CHRS.p01 (plan) ---

Plan Title=Multiple Run
Short Identifier=Multiple
Geom File=g01
Flow File=f01
Subcritical Flow
K Sum by GR= 0
Std Step Tol= 0.01
Critical Tol= 0.01
Num of Std Step Trials= 20
Max Error Tol= 0.3
Flow Tol Ratio= 0.001
Split Flow NTrial= 30
Split Flow Tol= 0.02
Split Flow Ratio= 0.02
Log Output Level= 0
Friction Slope Method= 1
Unsteady Friction Slope Method= 2
Unsteady Bridges Friction Slope Method= 1
Parabolic Critical Depth
Global Vel Dist=  1 , 1 , 1
Global Log Level= 0
CheckData=True
Encroach Param= -1, 0, 0, 0
BEGIN DESCRIPTION:
Multiple Run
END DESCRIPTION:

--- UNT00255 IN CHRS.f01 (steady flow) ---

Flow Title=Multiple
Number of Profiles=7
Profile Names=10-year,25-year,50-year,1pct_min,100-year,1pct_plu,500-year
River Rch & RM= UNT00255 IN CHRS,Reach-1,5664
     220     270     305     252     340     460     422
Boundary for River Rch & Prof#=UNT00255 IN CHRS,Reach-1,1
Up Type=0
Dn Type=3
Dn Slope=0.005
Boundary for River Rch & Prof#=UNT00255 IN CHRS,Reach-1,2
Up Type=0
Dn Type=3
Dn Slope=0.005
Boundary for River Rch & Prof#=UNT00255 IN CHRS,Reach-1,3
Up Type=0
Dn Type=3
Dn Slope=0.005
Boundary for River Rch & Prof#=UNT00255 IN CHRS,Reach-1,4
Up Type=0
Dn Type=3
Dn Slope=0.005
Boundary for River Rch & Prof#=UNT00255 IN CHRS,Reach-1,5
Up Type=0
Dn Type=3
Dn Slope=0.005
Boundary for River Rch & Prof#=UNT00255 IN CHRS,Reach-1,6
Up Type=0
Dn Type=3
Dn Slope=0.005
Boundary for River Rch & Prof#=UNT00255 IN CHRS,Reach-1,7
Up Type=0
Dn Type=3
Dn Slope=0.005

--- UNT00255 IN CHRS.g01 (geometry) ---

Geom Title=Existing Conditions
Program Version=4.10

River Reach=UNT00255 IN CHRS,Reach-1
Reach XY= 30
      3367040.82     10623130.77      3367348.85     10623269.57
      3367456.34     10623369.46      3367524.33     10623527.85
      3367817.45      10623600.4      3367714.53     10623717.11
      3367795.59     10623823.32      3367962.57     10623880.43
      3368193.61     10623872.23      3368358.43     10624078.37
      3368337.81     10624200.98      3368478.87      10624345.3
      3368491.89     10624544.95      3368705.16      10624586.3
      3368753.62     10624749.63      3368867.59     10624672.77
      3368992.57     10624740.71      3369170.51     10624715.31
      3369473.44     10625008.52      3369762.08     10625032.96
      3369827.15     10625080.71      3369954.51      10625026.5
      3370078.27     10625202.67      3370199.98     10625253.54
      3370164.72     10625356.06      3370233.84      10625418.6
      3370366.01     10625264.19      3370617.25     10625471.65
      3370747.91     10625433.06      3370832.11     10625501.64

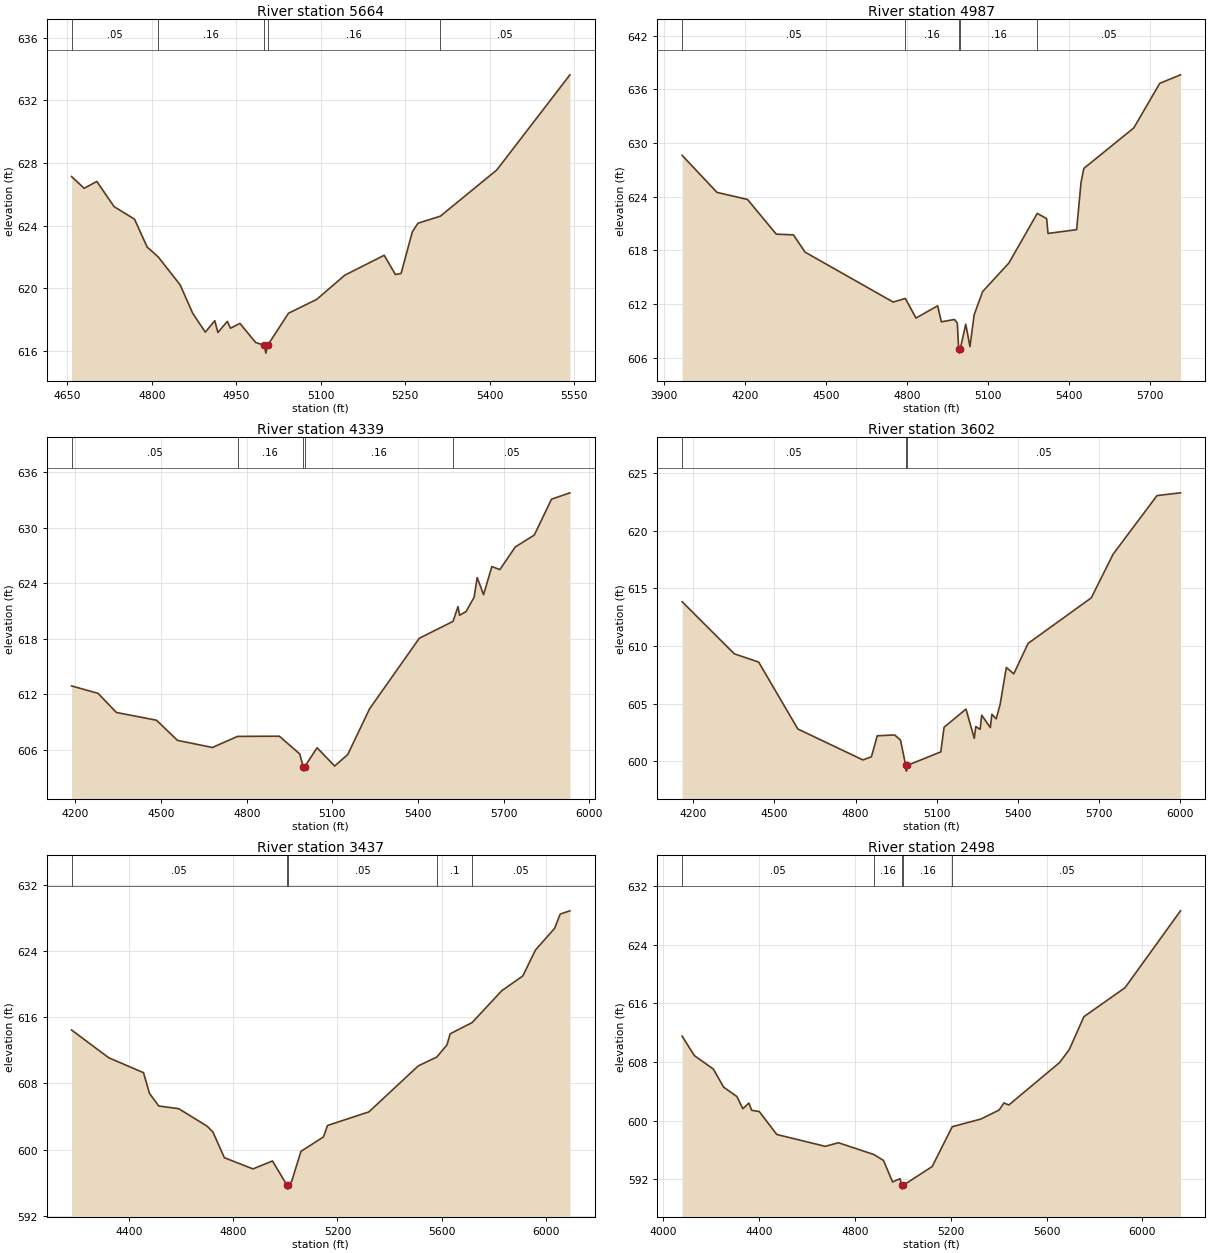
Type RM Length L Ch R = 1 ,5664    ,677,677,677
BEGIN DESCRIPTION:
UNT00255 IN CHRS 9.0
END DESCRIPTION:
XS GIS Cut Line= 3
      3366842.08     10623341.66      3367142.11     10623191.64
      3367142.11     10622641.68
#Sta/Elev= 30
  4657.3  627.13  4679.7  626.38  4702.1  626.82  4732.8  625.21  4769.1  624.41
  4791.5  622.63  4811.4  621.99  4850.2  620.21  4872.6  618.39  4894.9  617.19
  4911.7  617.92  4917.3  617.17    4934  617.88  4939.6  617.44  4956.4  617.75
  4984.4  616.53  4999.7  616.35  5002.5  615.85  5005.7  616.35  5042.7   618.4
  5092.7  619.28  5142.7  620.83  5212.7   622.1  5232.7  620.87  5242.7  620.94
  5262.7   623.6  5272.7  624.15  5312.5   624.6  5412.7  627.55  5542.7  633.63
#Mann= 5 ,-1 , 0
  4657.3     .05       0  4811.4     .16       0  4999.7     .07       0
  5005.7     .16       0  5312.5     .05       0
Bank Sta=4999.7,5005.7
XS Rating Curve= 0 ,0
Exp/Cntr=0.3,0.1

Type RM Length L Ch R = 1 ,4987    ,648,648,648
BEGIN DESCRIPTION:
UNT00255 IN CHRS 7.0
END DESCRIPTION:
XS GIS Cut Line= 3
      3366931.98     10624252.66      3367605.93     10623682.98
      3367874.66     10622757.88
#Sta/Elev= 30
  3966.7  628.61  4095.6  624.47  4208.7  623.68  4315.3   619.8    4379  619.72
  4421.9  617.79  4748.2  612.21  4793.4  612.61  4832.8  610.42    4913  611.79
  4926.9     610  4975.5  610.26  4985.9  609.85  4990.9     607  4993.7   606.5
  4996.9     607  5017.2  609.73  5032.7  607.24  5048.4   610.8  5079.6  613.38
  5177.3  616.59  5281.9  622.12  5316.7  621.54  5321.9  619.88  5427.7   620.3
  5444.1  625.57  5454.5  627.15  5639.4  631.67  5735.7  636.66  5812.5  637.61
#Mann= 5 ,-1 , 0
  3966.7     .05       0  4793.4     .16       0  4990.9     .07       0
  4996.9     .16       0  5281.9     .05       0
Bank Sta=4990.9,4996.9
XS Rating Curve= 0 ,0
Exp/Cntr=0.3,0.1

Type RM Length L Ch R = 1 ,4339    ,737,737,737
BEGIN DESCRIPTION:
UNT00255 IN CHRS 5.1
END DESCRIPTION:
XS GIS Cut Line= 3
      3367768.63     10624665.52      3367973.49      10623634.3
      3368275.59     10623009.25
#Sta/Elev= 30
  4186.6  612.88  4279.3  612.08  4343.5  610.01  4483.9  609.17  4557.6  606.99
  4679.9  606.22  4767.9  607.42  4914.4  607.44  4985.8  605.52  4997.5  604.16
  5000.3  603.66  5003.5  604.16  5046.6  606.19  5108.1  604.21    5154  605.46
  5230.5  610.41  5404.6  618.04  5522.8  619.87  5540.1  621.47  5545.7  620.53
  5568.3  620.93  5596.4  622.47  5607.4  624.61  5629.7  622.76  5658.7   625.8
  5686.8  625.47  5740.7  627.92  5807.4  629.21  5867.6  633.09  5932.2  633.78
#Mann= 5 ,-1 , 0
  4186.6     .05       0  4767.9     .16       0  4997.5     .07       0
  5003.5     .16       0  5522.8     .05       0
Bank Sta=4997.5,5003.5
XS Rating Curve= 0 ,0
Exp/Cntr=0.3,0.1

Type RM Length L Ch R = 1 ,3602    ,165,165,165
BEGIN DESCRIPTION:
UNT00255 IN CHRS 5.0
END DESCRIPTION:
XS GIS Cut Line= 3
      3367952.65     10624967.64      3368473.49     10624075.27
       3368869.3     10623370.45
#Sta/Elev= 30
    4159  613.84  4351.7  609.32  4441.8   608.6  4586.5  602.79  4827.1   600.1
  4858.5  600.38    4880   602.2  4944.5  602.27    4966  601.82    4985  599.63
  4987.8  599.13    4991  599.63  5114.8   600.8    5127  602.94  5207.9  604.52
  5238.5  601.98  5244.2     603  5260.2  602.76  5265.9  603.99  5297.8  602.91
  5303.6  604.07  5319.5  603.67    5334  604.92    5357  608.13  5384.5  607.58
  5437.3  610.22  5670.9  614.18  5751.8  617.98  5913.8  623.06  6000.6   623.3
#Mann= 3 ,-1 , 0
    4159     .05       0    4985     .04       0    4991     .05       0
Bank Sta=4985,4991
XS Rating Curve= 0 ,0
Exp/Cntr=0.3,0.1

Type RM Length L Ch R = 1 ,3437    ,939,939,939
BEGIN DESCRIPTION:
UNT00255 IN CHRS 3.0
END DESCRIPTION:
XS GIS Cut Line= 4
      3368091.55     10625085.68      3368435.29     10624439.85
      3369042.93     10623436.38      3369042.93     10623446.76
#Sta/Elev= 30
  4178.3  614.45  4321.2   611.1  4454.8   609.3  4477.4  606.82  4513.2  605.28
  4589.8  604.96  4699.6  602.84  4721.6  602.13  4765.5  599.04  4875.4  597.69
  4950.4  598.65  5005.6  595.75  5008.3  595.25  5011.6  595.75  5024.1   596.2
  5059.8  599.81  5146.3  601.55  5161.8  602.93  5320.8  604.57  5510.9  610.13
  5581.4  611.18  5620.9  612.65  5633.1  613.99  5717.6  615.35  5831.4  619.19
  5912.3  620.97  5960.9   624.1  6034.6  626.72  6055.9  628.44  6093.4  628.83
#Mann= 5 ,-1 , 0
  4178.3     .05       0  5005.6     .04       0  5011.6     .05       0
  5581.4      .1       0  5717.6     .05       0
Bank Sta=5005.6,5011.6
XS Rating Curve= 0 ,0
Exp/Cntr=0.3,0.1

Type RM Length L Ch R = 1 ,2498    ,752,752,752
BEGIN DESCRIPTION:
UNT00255 IN CHRS 2.1
END DESCRIPTION:
XS GIS Cut Line= 3
      3368379.77     10625224.56      3369001.27     10624995.41
      3369209.61     10623592.59
#Sta/Elev= 30
  4078.1  611.53  4129.2  608.87  4208.5  607.03  4251.1  604.57  4306.5  603.28
  4331.6  601.61  4356.8  602.38  4368.4   601.4  4400.3  601.22  4473.2  598.09
  4675.6  596.47  4730.7  596.96  4878.7  595.35  4918.8  594.54  4956.6   591.6
  4988.2  592.05    4994  591.12  4996.8  590.62    5000  591.12    5122  593.71
  5205.7  599.15  5325.2   600.2  5401.4  601.43  5421.7   602.4  5441.9  602.12
  5654.2  607.93  5694.6  609.71  5755.3  614.19  5927.1  618.15  6158.7  628.66
#Mann= 5 ,-1 , 0
  4078.1     .05       0  4878.7     .16       0    4994     .07       0
    5000     .16       0  5205.7     .05       0
Bank Sta=4994,5000
XS Rating Curve= 0 ,0
Exp/Cntr=0.3,0.1

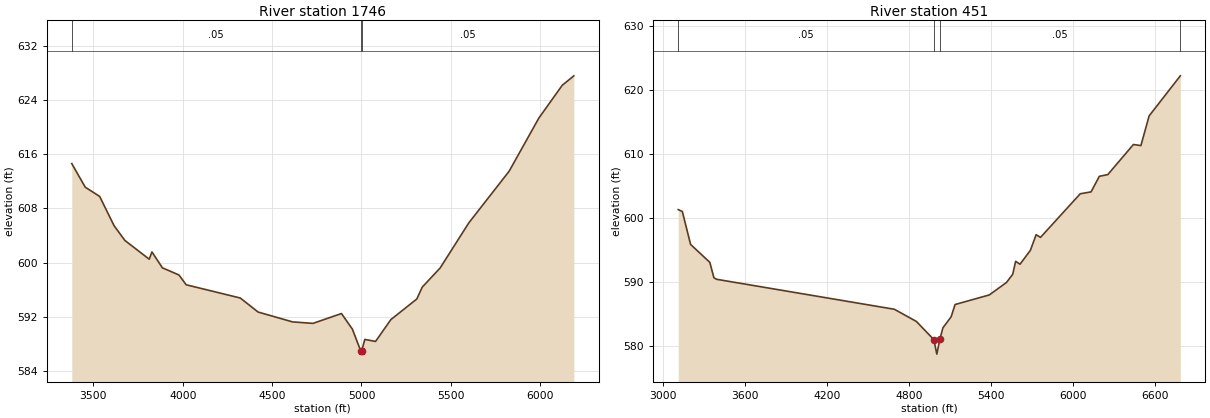
Type RM Length L Ch R = 1 ,1746    ,1295,1295,1295
BEGIN DESCRIPTION:
UNT00255 IN CHRS 2.0
END DESCRIPTION:
XS GIS Cut Line= 3
      3368317.36      10625513.1      3369624.66     10625341.23
      3369760.08     10623856.84
#Sta/Elev= 30
    3379  614.62  3454.4  611.14  3535.1  609.78  3615.8  605.46  3676.3  603.29
  3812.3  600.53  3827.6   601.6    3886  599.26  3978.9   598.2  4019.2  596.76
  4321.8  594.81  4421.7  592.74  4614.3  591.29  4728.4  591.07  4887.9  592.52
  4948.9  590.23  4995.4  587.04  4998.1  586.54  5001.4  587.04  5018.5  588.71
  5078.7  588.41  5164.4  591.63  5309.7  594.67  5339.8  596.41  5440.2  599.24
  5600.4  605.88    5826  613.49  5992.5  621.33    6123  626.15  6188.1  627.55
#Mann= 3 ,-1 , 0
    3379     .05       0  4995.4    .035       0  5001.4     .05       0
Bank Sta=4995.4,5001.4
XS Rating Curve= 0 ,0
Exp/Cntr=0.3,0.1

Type RM Length L Ch R = 1 ,451     ,0,0,0
BEGIN DESCRIPTION:
UNT00255 IN CHRS 1.0
END DESCRIPTION:
XS GIS Cut Line= 4
      3368812.15     10625856.85      3370291.33     10625716.23
      3370635.08     10625044.35      3370124.81     10623706.19
#Sta/Elev= 30
  3112.1  601.38  3142.2  601.08  3202.5  595.94  3343.1  593.14  3373.2  590.73
  3393.3  590.49  4692.9  585.81    4854  583.91  4981.6  581.07  5003.6   578.8
  5026.1  581.13  5048.3  582.91  5108.6  584.64  5137.1  586.55  5387.7  588.05
    5513  589.99  5558.9  591.28  5580.3   593.3  5612.4  592.85  5688.2  595.02
  5730.1  597.46  5762.2  597.04  6052.6  603.85  6132.1  604.15  6192.3  606.58
  6254.5  606.85  6441.7  611.55  6496.5  611.38  6556.7  616.02  6784.8  622.28
#Mann= 4 ,-1 , 0
  3112.1     .05       0  4981.6    .035       0  5026.1     .05       0
  6784.8     .05       0
Bank Sta=4981.6,5026.1
XS Rating Curve= 0 ,0
Exp/Cntr=0.3,0.1

Chan Stop Cuts=-1
Use User Specified Reach Order=0
Composite Channel Slope=5