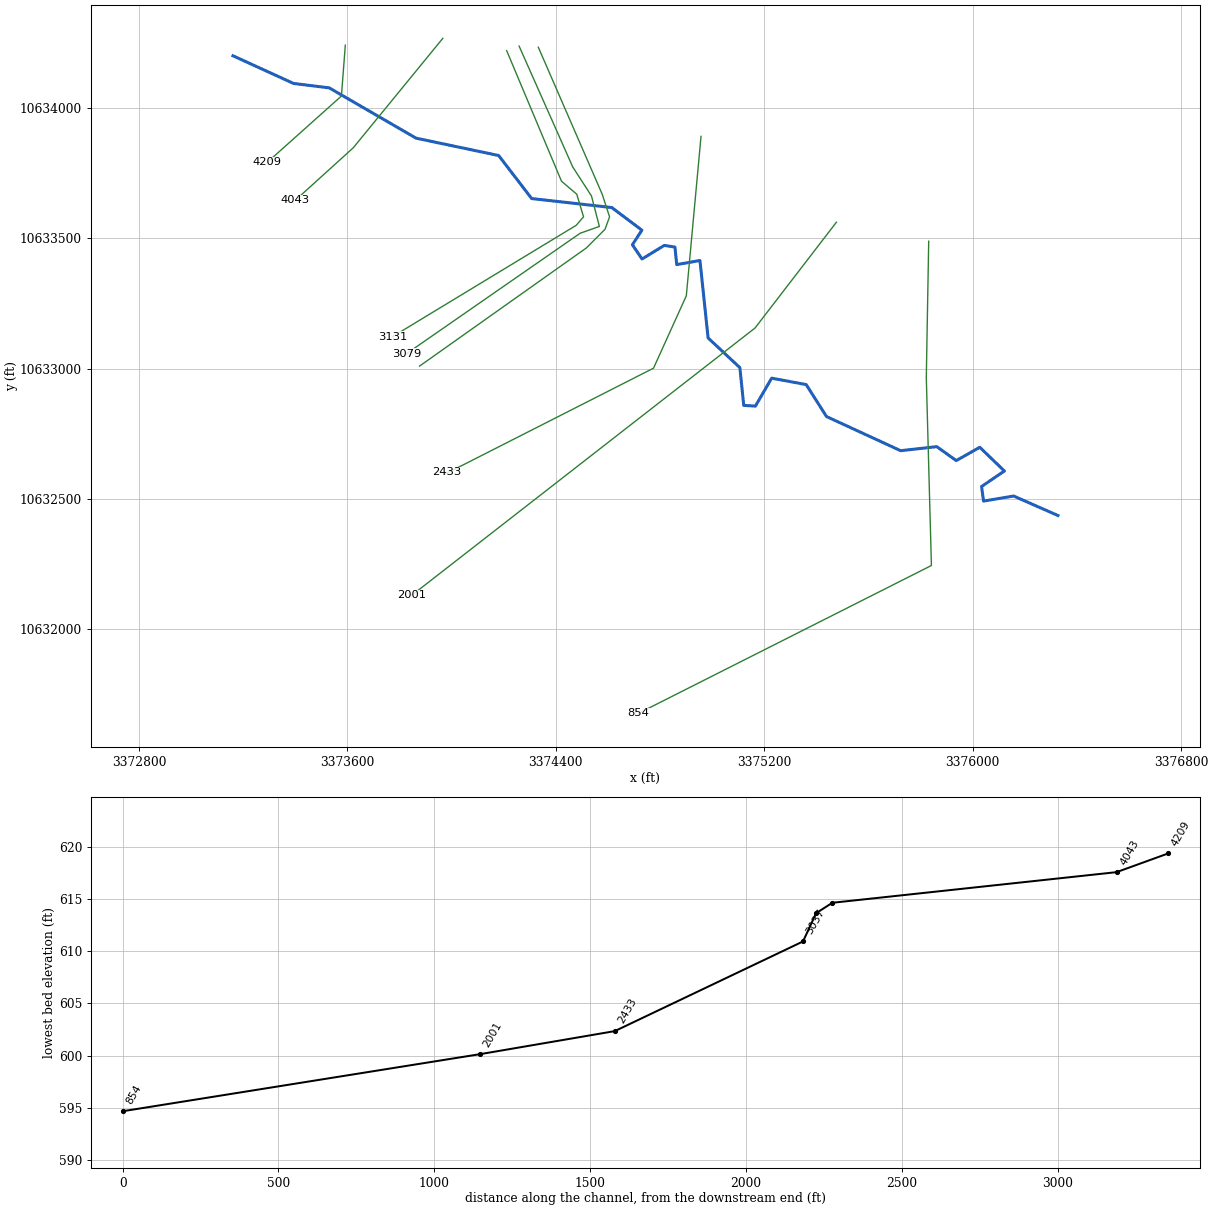
--- UNT00264 IN CHRS.prj (project) ---

Proj Title=UNT00264 IN CHRS Base Level Engineering
Current Plan=p01
Default Exp/Contr=0.3,0.1
English Units
Geom File=g01
Flow File=f01
Plan File=p01
BEGIN DESCRIPTION:
UNT00264 IN CHRS
END DESCRIPTION:

--- UNT00264 IN CHRS.p01 (plan) ---

Plan Title=Multiple Run
Short Identifier=Multiple
Geom File=g01
Flow File=f01
Subcritical Flow
K Sum by GR= 0
Std Step Tol= 0.01
Critical Tol= 0.01
Num of Std Step Trials= 20
Max Error Tol= 0.3
Flow Tol Ratio= 0.001
Split Flow NTrial= 30
Split Flow Tol= 0.02
Split Flow Ratio= 0.02
Log Output Level= 0
Friction Slope Method= 1
Unsteady Friction Slope Method= 2
Unsteady Bridges Friction Slope Method= 1
Parabolic Critical Depth
Global Vel Dist=  1 , 1 , 1
Global Log Level= 0
CheckData=True
Encroach Param= -1, 0, 0, 0
BEGIN DESCRIPTION:
Multiple Run
END DESCRIPTION:

--- UNT00264 IN CHRS.f01 (steady flow) ---

Flow Title=Multiple
Number of Profiles=7
Profile Names=10-year,25-year,50-year,1pct_min,100-year,1pct_plu,500-year
River Rch & RM= UNT00264 IN CHRS,Reach-1,4209
     199     242     272     223     302     408     371
Boundary for River Rch & Prof#=UNT00264 IN CHRS,Reach-1,1
Up Type=0
Dn Type=3
Dn Slope=0.005
Boundary for River Rch & Prof#=UNT00264 IN CHRS,Reach-1,2
Up Type=0
Dn Type=3
Dn Slope=0.005
Boundary for River Rch & Prof#=UNT00264 IN CHRS,Reach-1,3
Up Type=0
Dn Type=3
Dn Slope=0.005
Boundary for River Rch & Prof#=UNT00264 IN CHRS,Reach-1,4
Up Type=0
Dn Type=3
Dn Slope=0.005
Boundary for River Rch & Prof#=UNT00264 IN CHRS,Reach-1,5
Up Type=0
Dn Type=3
Dn Slope=0.005
Boundary for River Rch & Prof#=UNT00264 IN CHRS,Reach-1,6
Up Type=0
Dn Type=3
Dn Slope=0.005
Boundary for River Rch & Prof#=UNT00264 IN CHRS,Reach-1,7
Up Type=0
Dn Type=3
Dn Slope=0.005

--- UNT00264 IN CHRS.g01 (geometry) ---

Geom Title=Existing Conditions

River Reach=UNT00264 IN CHRS,Reach-1
Reach XY= 30
      3373160.90     10634201.03      3373393.41     10634094.82
      3373530.49     10634077.78      3373863.61     10633884.86
      3374180.65     10633818.18      3374307.38     10633652.96
      3374615.00     10633618.46      3374730.56     10633531.67
      3374693.99     10633475.59      3374731.05     10633420.98
      3374816.38     10633473.16      3374857.34     10633466.82
      3374864.16     10633399.53      3374953.39     10633415.13
      3374984.62     10633117.88      3375106.59     10633003.97
      3375121.39     10632859.04      3375166.32     10632856.36
      3375228.51     10632963.62      3375361.13     10632938.96
      3375438.98     10632816.30      3375723.71     10632685.18
      3375862.28     10632700.71      3375937.12     10632647.22
      3376027.40     10632698.26      3376121.84     10632607.29
      3376034.34     10632547.66      3376041.89     10632491.67
      3376157.26     10632511.20      3376327.53     10632436.36

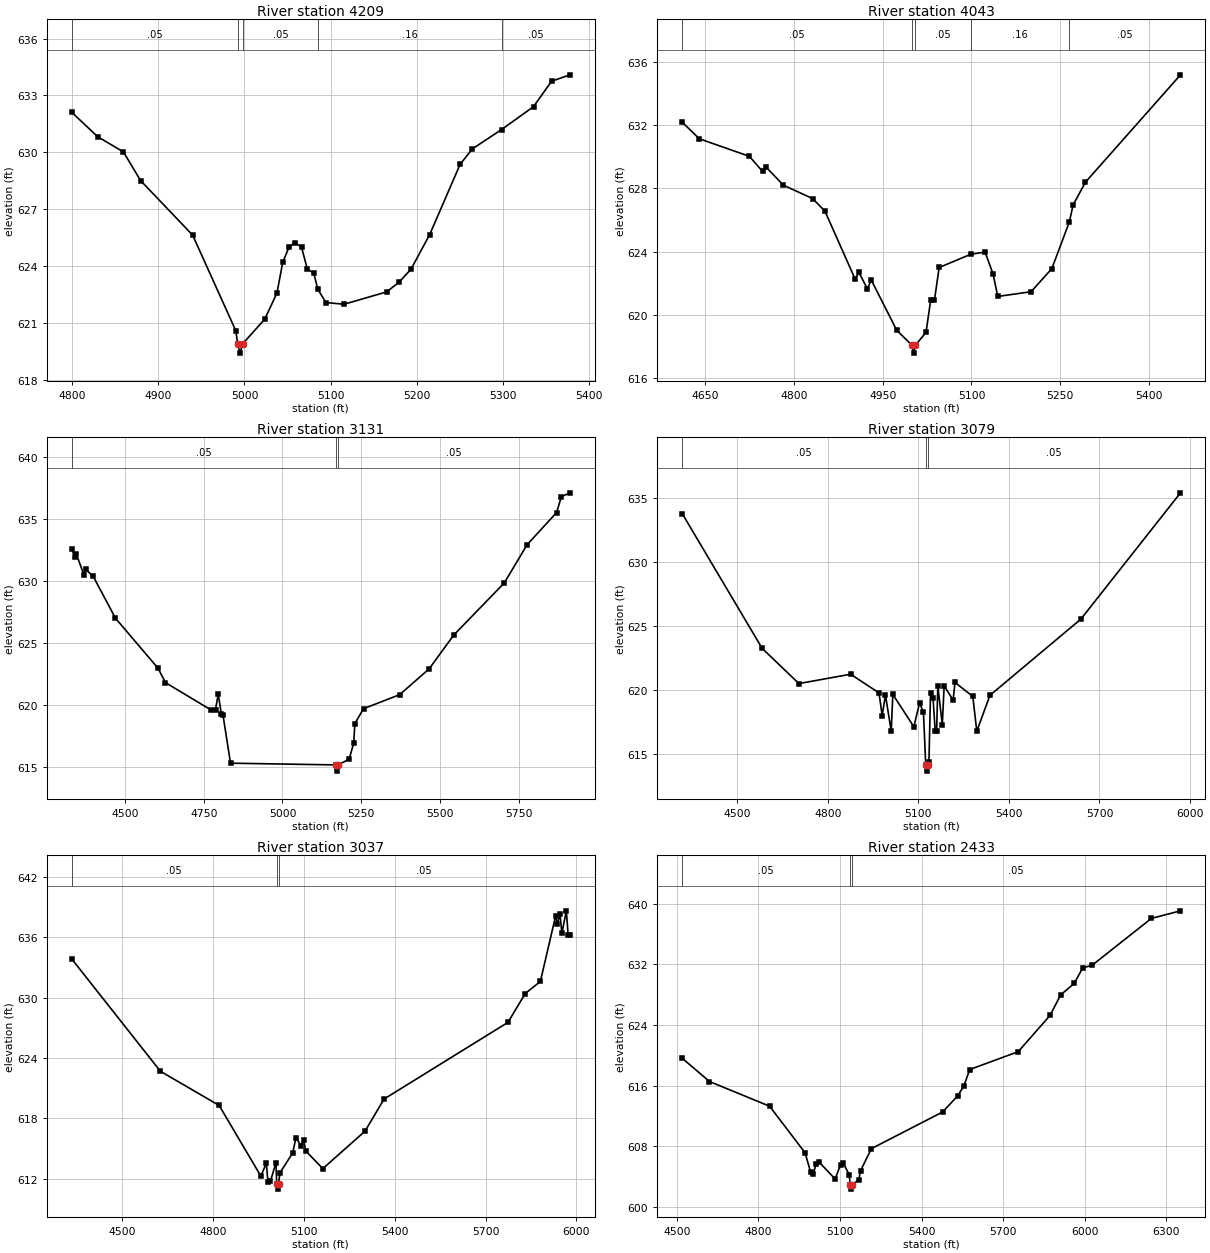
Type RM Length L Ch R = 1,4209,166,166,166
BEGIN DESCRIPTION:
UNT00264 IN CHRS 8.0
END DESCRIPTION:
XS GIS Cut Line= 3
      3373592.10     10634241.61      3373577.18     10634046.56
      3373292.14     10633791.67
#Sta/Elev= 30
  4799.5  632.12  4829.6  630.83  4859.6  630.02  4879.7  628.50  4939.9  625.63
  4990.0  620.58  4992.1  619.90  4994.8  619.40  4998.1  619.90  5023.5  621.19
  5037.7  622.57  5044.4  624.19  5051.9  625.02  5058.7  625.23  5066.2  625.00
  5072.9  623.84  5080.4  623.62  5085.2  622.76  5094.6  622.07  5115.5  621.98
  5164.8  622.63  5179.0  623.13  5193.2  623.83  5214.9  625.66  5250.1  629.36
  5264.3  630.18  5298.2  631.20  5335.3  632.41  5356.2  633.75  5377.5  634.09
#Mann=5,-1,0
  4799.5    0.05       0  4992.1   0.035       0  4998.1    0.05       0
  5085.2    0.16       0  5298.2    0.05       0
Bank Sta=4992.1,4998.1
Exp/Cntr=0.3,0.1

Type RM Length L Ch R = 1,4043,912,912,912
BEGIN DESCRIPTION:
UNT00264 IN CHRS 3.1
END DESCRIPTION:
XS GIS Cut Line= 3
      3373966.32     10634267.98      3373622.58     10633847.85
      3373400.45     10633646.55
#Sta/Elev= 30
  4610.8  632.19  4639.8  631.14  4724.5  630.03  4746.7  629.08  4753.2  629.33
  4781.9  628.21  4831.4  627.36  4852.2  626.57  4903.2  622.28  4909.6  622.70
  4924.0  621.66  4930.5  622.22  4973.5  619.05  4999.2  618.10  5002.0  617.60
  5005.2  618.10  5023.1  618.91  5031.0  620.94  5037.4  620.95  5045.3  623.01
  5099.1  623.85  5122.9  623.98  5136.5  622.60  5144.4  621.18  5200.8  621.48
  5235.9  622.94  5265.4  625.88  5271.8  626.96  5292.7  628.40  5453.4  635.18
#Mann=5,-1,0
  4610.8    0.05       0  4999.2   0.035       0  5005.2    0.05       0
  5099.1    0.16       0  5265.4    0.05       0
Bank Sta=4999.2,5005.2
Exp/Cntr=0.3,0.1

Type RM Length L Ch R = 1,3131,52,52,52
BEGIN DESCRIPTION:
UNT00264 IN CHRS 7.0
END DESCRIPTION:
XS GIS Cut Line= 6
      3374211.41     10634220.83      3374421.91     10633719.52
      3374480.51     10633669.61      3374506.55     10633582.81
      3374478.34     10633550.25      3373773.01     10633122.72
#Sta/Elev= 30
  4330.6  632.59  4340.2  631.94  4345.7  632.14  4369.4  630.50  4374.8  630.91
  4398.6  630.38  4469.9  626.98  4605.0  622.95  4628.7  621.79  4774.4  619.57
  4787.5  619.62  4796.1  620.87  4805.9  619.27  4811.3  619.16  4835.1  615.30
  5170.1  615.16  5172.8  614.66  5176.1  615.16  5211.7  615.62  5226.1  616.92
  5229.8  618.49  5257.3  619.69  5372.0  620.82  5465.6  622.90  5544.0  625.63
  5704.1  629.82  5776.5  632.90  5870.1  635.49  5885.3  636.77  5912.4  637.08
#Mann=3,-1,0
  4330.6    0.05       0  5170.1   0.035       0  5176.1    0.05       0
Bank Sta=5170.1,5176.1
Exp/Cntr=0.3,0.1

Type RM Length L Ch R = 1,3079,42,42,42
BEGIN DESCRIPTION:
UNT00264 IN CHRS 6.0
END DESCRIPTION:
XS GIS Cut Line= 6
      3374259.17     10634238.14      3374465.31     10633773.78
      3374536.93     10633663.10      3374567.31     10633545.91
      3374493.53     10633519.87      3373827.28     10633057.62
#Sta/Elev= 30
  4317.3  633.81  4582.4  623.26  4704.2  620.51  4875.6  621.24  4969.5  619.78
  4980.1  618.01  4990.9  619.61  5010.0  616.79  5015.4  619.66  5085.0  617.13
  5104.1  619.00  5116.8  618.26  5124.4  614.16  5127.1  613.66  5130.4  614.16
  5135.0  614.38  5140.3  619.79  5148.6  619.36  5155.8  616.80  5160.5  616.80
  5164.4  620.30  5179.3  617.29  5185.4  620.33  5215.2  619.21  5221.3  620.60
  5280.4  619.50  5293.6  616.78  5337.1  619.59  5638.4  625.55  5968.6  635.43
#Mann=3,-1,0
  4317.3    0.05       0  5124.4   0.035       0  5130.4    0.05       0
Bank Sta=5124.4,5130.4
Exp/Cntr=0.3,0.1

Type RM Length L Ch R = 1,3037,604,604,604
BEGIN DESCRIPTION:
UNT00264 IN CHRS 5.0
END DESCRIPTION:
XS GIS Cut Line= 6
      3374332.93     10634233.86      3374578.16     10633669.61
      3374606.37     10633582.81      3374589.01     10633535.06
      3374517.40     10633463.45      3373877.23     10633009.91
#Sta/Elev= 30
  4333.4  633.88  4626.7  622.68  4820.6  619.28  4958.2  612.25  4976.4  613.52
  4981.6  611.70  4989.7  611.73  5008.3  613.58  5010.6  611.45  5013.3  610.95
  5016.6  611.45  5021.3  612.57  5063.3  614.55  5074.3  616.08  5091.1  615.27
  5099.2  615.88  5106.3  614.76  5162.8  612.99  5302.2  616.72  5365.1  619.92
  5774.2  627.55  5830.9  630.41  5881.1  631.62  5931.3  638.12  5937.5  637.38
  5945.9  638.31  5952.1  636.42  5966.8  638.65  5972.9  636.20  5978.6  636.20
#Mann=3,-1,0
  4333.4    0.05       0  5010.6   0.035       0  5016.6    0.05       0
Bank Sta=5010.6,5016.6
Exp/Cntr=0.3,0.1

Type RM Length L Ch R = 1,2433,432,432,432
BEGIN DESCRIPTION:
UNT00264 IN CHRS 3.6
END DESCRIPTION:
XS GIS Cut Line= 5
      3374957.43     10633891.66      3374901.01     10633279.71
      3374775.14     10633001.93      3373972.19     10632593.95
      3373980.84     10632602.60
#Sta/Elev= 30
  4519.7  619.61  4620.1  616.54  4841.1  613.28  4971.6  607.14  4991.7  604.63
  5001.8  604.30  5011.8  605.65  5021.8  605.96  5082.1  603.68  5102.2  605.57
  5112.2  605.79  5134.2  604.21  5137.7  602.84  5140.4  602.34  5143.7  602.84
  5169.2  603.61  5176.0  604.79  5215.4  607.68  5477.4  612.52  5532.3  614.62
  5554.8  615.90  5577.2  618.12  5755.5  620.48  5872.4  625.26  5911.3  627.96
  5961.4  629.49  5992.2  631.51  6028.2  631.91  6245.1  638.06  6352.1  639.06
#Mann=3,-1,0
  4519.7    0.05       0  5137.7    0.03       0  5143.7    0.05       0
Bank Sta=5137.7,5143.7
Exp/Cntr=0.3,0.1

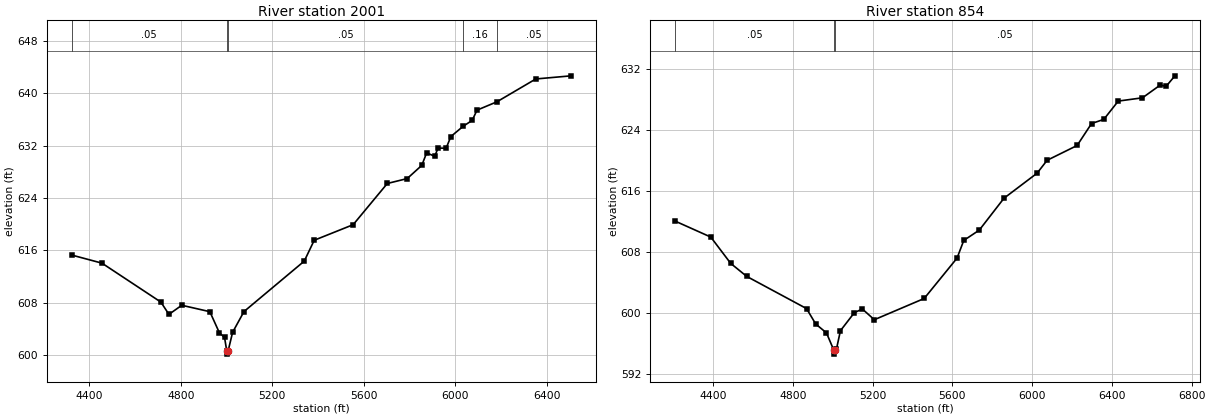
Type RM Length L Ch R = 1,2001,1147,1147,1147
BEGIN DESCRIPTION:
UNT00264 IN CHRS 3.0
END DESCRIPTION:
XS GIS Cut Line= 3
      3375477.25     10633562.30      3375164.72     10633156.01
      3373847.05     10632130.00
#Sta/Elev= 30
  4323.5  615.28  4455.9  614.04  4713.2  608.09  4748.6  606.21  4804.7  607.60
  4927.3  606.62  4968.9  603.40  4991.5  602.68  5001.2  600.63  5003.9  600.13
  5007.2  600.63  5026.8  603.47  5076.5  606.64  5339.8  614.35  5383.3  617.54
  5553.4  619.92  5702.7  626.22  5789.5  626.97  5853.3  628.99  5874.6  630.91
  5909.8  630.37  5924.3  631.64  5959.6  631.61  5980.4  633.40  6034.2  634.97
  6073.6  635.87  6094.4  637.43  6181.6  638.71  6351.4  642.20  6506.1  642.68
#Mann=5,-1,0
  4323.5    0.05       0  5001.2   0.035       0  5007.2    0.05       0
  6034.2    0.16       0  6181.6    0.05       0
Bank Sta=5001.2,5007.2
Exp/Cntr=0.3,0.1

Type RM Length L Ch R = 1,854,0,0,0
BEGIN DESCRIPTION:
UNT00264 IN CHRS 1.0
END DESCRIPTION:
XS GIS Cut Line= 4
      3375831.39     10633489.33      3375822.16     10632966.21
      3375841.81     10632244.55      3374716.94     10631676.91
#Sta/Elev= 30
  4210.9  612.07  4388.6  609.99  4488.6  606.54  4568.6  604.84  4868.7  600.62
  4914.8  598.60  4968.8  597.43  5005.8  595.15  5008.5  594.65  5011.8  595.15
  5018.8  595.31  5038.8  597.72  5108.8  600.09  5148.8  600.56  5208.8  599.16
  5458.7  601.94  5623.5  607.23  5657.3  609.55  5735.0  610.90  5858.9  615.08
  6024.9  618.36  6075.1  620.05  6225.6  621.99  6298.1  624.87  6359.4  625.41
  6431.9  627.81  6553.4  628.24  6643.0  629.92  6671.6  629.73  6716.0  631.12
#Mann=3,-1,0
  4210.9    0.05       0  5005.8    0.03       0  5011.8    0.05       0
Bank Sta=5005.8,5011.8
Exp/Cntr=0.3,0.1

Chan Stop Cuts=-1