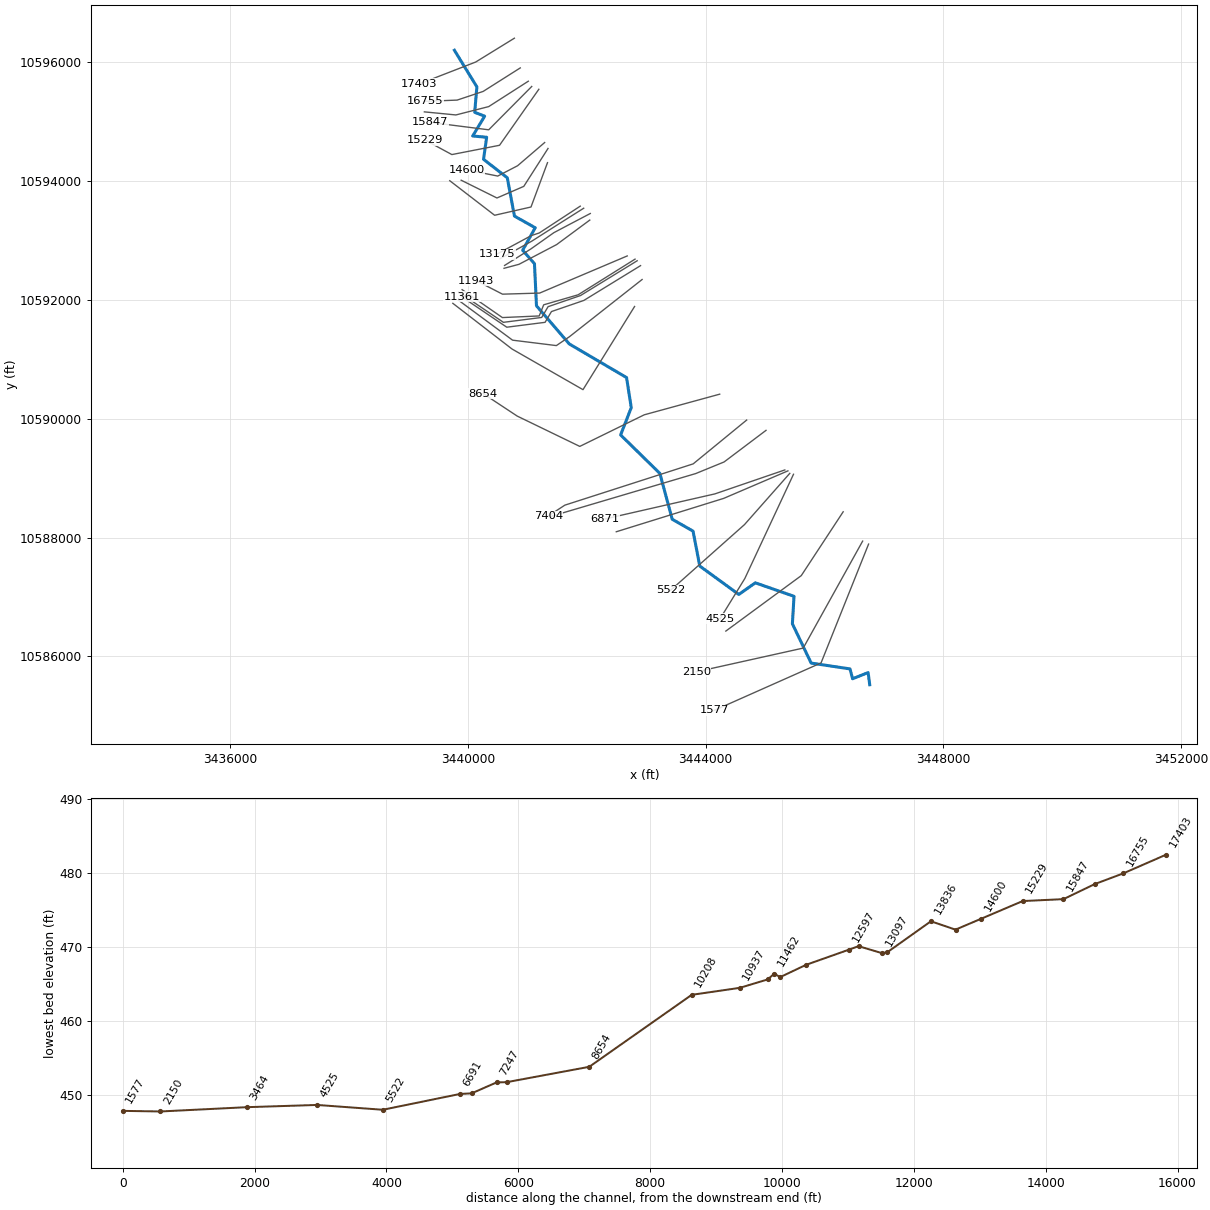
--- UNT0027 IN CHRS.prj (project) ---

Proj Title=UNT0027 IN CHRS Base Level Engineering
Current Plan=p01
Default Exp/Contr=0.3,0.1
English Units
Geom File=g01
Flow File=f01
Plan File=p01
Y Axis Title=Elevation
X Axis Title(PF)=Main Channel Distance
X Axis Title(XS)=Station
BEGIN DESCRIPTION:
UNT0027 IN CHRS
END DESCRIPTION:
DSS Export Rating Curves= 0
DSS Export Rating Curve Sorted= 0
DSS Export Volume Flow Curves= 0
DXF OffsetX= 0
DXF OffsetY= 0
DXF ScaleX= 1
DXF ScaleY= 10

--- UNT0027 IN CHRS.p01 (plan) ---

Plan Title=Multiple Run
Short Identifier=Multiple
Geom File=g01
Flow File=f01
Subcritical Flow
K Sum by GR= 0
Std Step Tol= 0.01
Critical Tol= 0.01
Num of Std Step Trials= 20
Max Error Tol= 0.3
Flow Tol Ratio= 0.001
Split Flow NTrial= 30
Split Flow Tol= 0.02
Split Flow Ratio= 0.02
Log Output Level= 0
Friction Slope Method= 1
Unsteady Friction Slope Method= 2
Unsteady Bridges Friction Slope Method= 1
Parabolic Critical Depth
Global Vel Dist=  1 , 1 , 1
Global Log Level= 0
CheckData=True
Encroach Param= -1, 0, 0, 0
BEGIN DESCRIPTION:
Multiple Run
END DESCRIPTION:

--- UNT0027 IN CHRS.f01 (steady flow) ---

Flow Title=Multiple
Number of Profiles=7
Profile Names=10-year,25-year,50-year,1pct_min,100-year,1pct_plu,500-year
River Rch & RM= UNT0027 IN CHRS,Reach-1,17403
     358     444     506     420     568     768     713
River Rch & RM= UNT0027 IN CHRS,Reach-1,13175
     548     695     803     675     913    1235    1178
River Rch & RM= UNT0027 IN CHRS,Reach-1,8654
     657     840     977     825    1116    1509    1454
River Rch & RM= UNT0027 IN CHRS,Reach-1,6871
     781    1005    1174     996    1347    1821    1768
River Rch & RM= UNT0027 IN CHRS,Reach-1,3464
     754     966    1124     950    1285    1738    1675
Boundary for River Rch & Prof#=UNT0027 IN CHRS,Reach-1,1
Up Type=0
Dn Type=3
Dn Slope=0.005
Boundary for River Rch & Prof#=UNT0027 IN CHRS,Reach-1,2
Up Type=0
Dn Type=3
Dn Slope=0.005
Boundary for River Rch & Prof#=UNT0027 IN CHRS,Reach-1,3
Up Type=0
Dn Type=3
Dn Slope=0.005
Boundary for River Rch & Prof#=UNT0027 IN CHRS,Reach-1,4
Up Type=0
Dn Type=3
Dn Slope=0.005
Boundary for River Rch & Prof#=UNT0027 IN CHRS,Reach-1,5
Up Type=0
Dn Type=3
Dn Slope=0.005
Boundary for River Rch & Prof#=UNT0027 IN CHRS,Reach-1,6
Up Type=0
Dn Type=3
Dn Slope=0.005
Boundary for River Rch & Prof#=UNT0027 IN CHRS,Reach-1,7
Up Type=0
Dn Type=3
Dn Slope=0.005

--- UNT0027 IN CHRS.g01 (geometry) ---

Geom Title=Existing Conditions
Program Version=4.10

River Reach=UNT0027 IN CHRS ,Reach-1
Reach XY= 30
      3439772.11     10596201.64      3440150.15     10595585.79
      3440113.36     10595157.27      3440280.89     10595092.52
      3440080.04     10594758.85      3440314.69     10594737.66
      3440262.11     10594366.64      3440661.74     10594056.49
      3440782.49     10593411.22      3441131.77     10593214.85
      3440920.83     10592836.32      3441119.33      10592610.5
      3441153.15     10591901.71       3441705.3     10591259.53
      3442669.06     10590693.78      3442747.95     10590186.94
      3442569.23     10589728.08      3443229.62     10589080.69
      3443437.73     10588309.23      3443788.14     10588109.67
      3443900.93     10587522.12      3444557.81     10587043.86
      3444836.07     10587239.52      3445487.05     10587012.65
      3445459.71     10586550.41       3445775.5     10585888.95
      3446429.46     10585790.86      3446472.69     10585625.24
      3446734.15      10585729.4      3446760.88     10585524.98

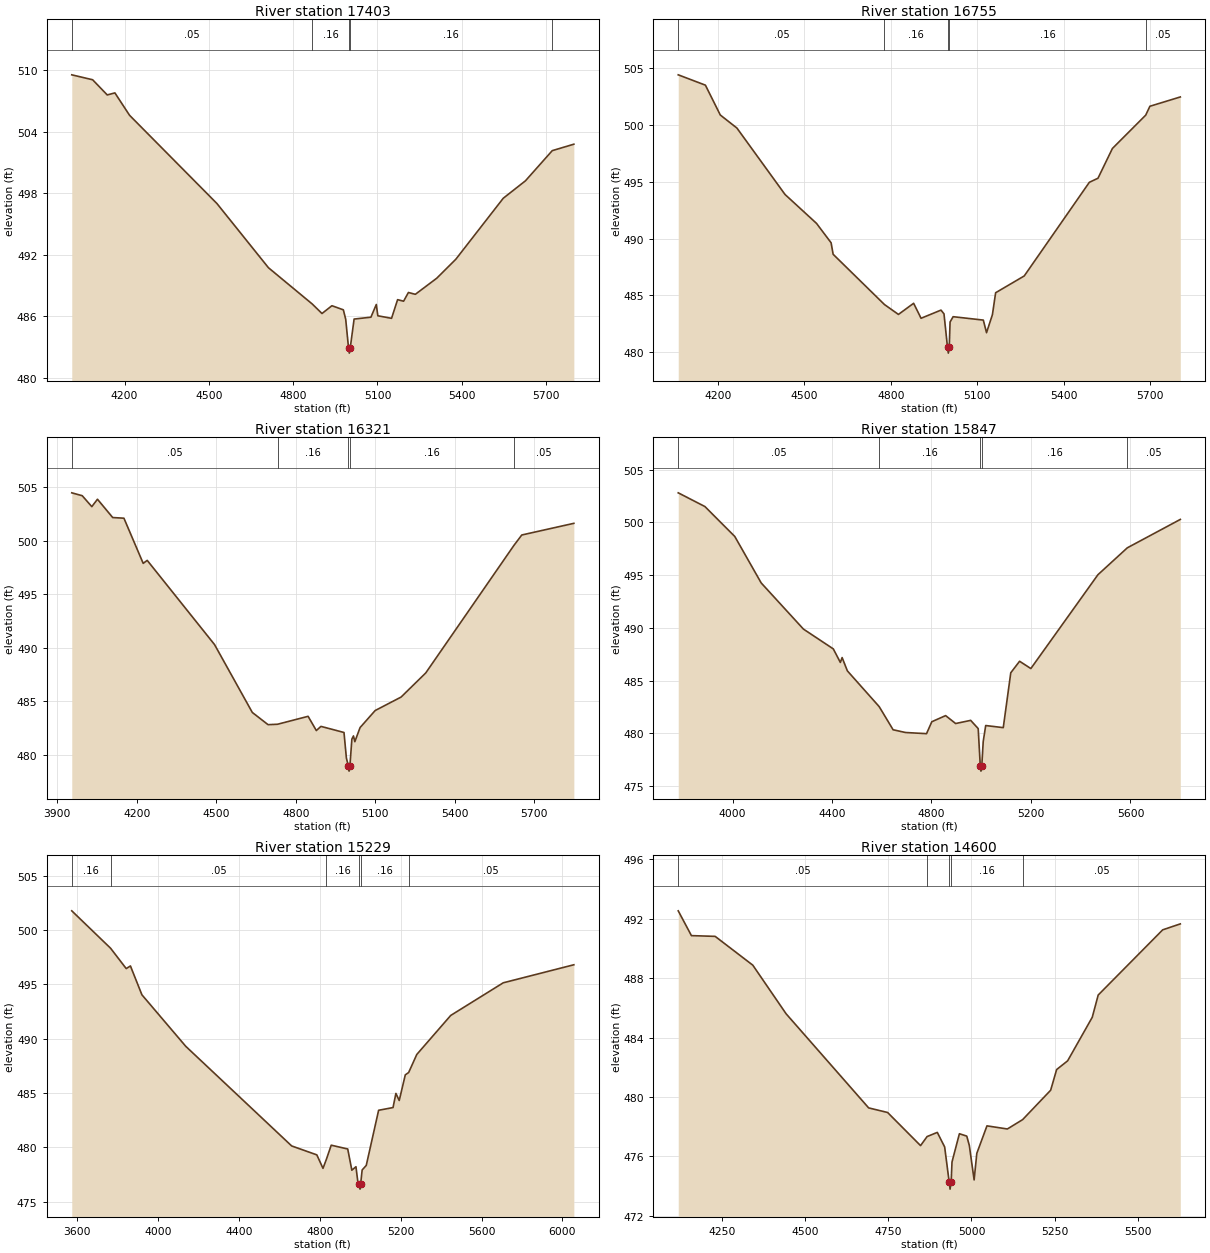
Type RM Length L Ch R = 1 ,17403   ,648,648,648
BEGIN DESCRIPTION:
UNT0027 IN CHRS 8.1
END DESCRIPTION:
XS GIS Cut Line= 3
      3440781.44     10596404.87       3440130.4     10596003.82
      3439177.27     10595634.03
#Sta/Elev= 30
    4012  509.55  4086.2  509.07  4138.3  507.59  4165.5  507.79  4217.6  505.61
  4528.6  497.01  4712.1  490.75  4867.8  487.22  4902.6  486.29  4937.9  487.05
  4978.6  486.65    4987  485.73  4997.1  482.93  4999.8  482.43  5003.1  482.93
  5016.9  485.75  5076.7  485.93  5095.9  487.17  5101.3  486.07  5150.2  485.82
  5171.7  487.64  5193.1  487.49  5210.2  488.34  5234.8  488.16  5311.1  489.73
    5379  491.58  5547.7  497.52  5626.7  499.22  5722.1  502.16    5799  502.79
#Mann= 5 ,-1 , 0
    4012     .05       0  4867.8     .16       0  4997.1     .07       0
  5003.1     .16       0  5722.1     .05       0
Bank Sta=4997.1,5003.1
XS Rating Curve= 0 ,0
Exp/Cntr=0.3,0.1

Type RM Length L Ch R = 1 ,16755   ,434,434,434
BEGIN DESCRIPTION:
UNT0027 IN CHRS 7.0
END DESCRIPTION:
XS GIS Cut Line= 4
      3440880.37     10595904.84       3440255.4     10595509.03
       3439817.9      10595363.2      3439276.63     10595342.38
#Sta/Elev= 30
    4062  504.43  4156.3  503.52    4208  500.89  4265.7  499.74  4432.6  493.89
    4542  491.34  4592.6  489.63  4599.6  488.62  4777.8  484.19  4826.3  483.32
    4879   484.3  4904.8  482.98  4973.9   483.7  4984.4  483.37  4996.6  480.41
  4999.4  479.91  5002.6  480.41  5005.5  482.65  5016.1  483.12  5120.9  482.82
    5132  481.71  5152.5   483.3  5163.6  485.23  5262.9  486.71  5488.9  494.96
  5518.9  495.32  5568.9  497.94  5684.6  500.88    5699  501.66  5804.6  502.48
#Mann= 5 ,-1 , 0
    4062     .05       0  4777.8     .16       0  4996.6     .07       0
  5002.6     .16       0  5684.6     .05       0
Bank Sta=4996.6,5002.6
XS Rating Curve= 0 ,0
Exp/Cntr=0.3,0.1

Type RM Length L Ch R = 1 ,16321   ,474,474,474
BEGIN DESCRIPTION:
UNT0027 IN CHRS 6.0
END DESCRIPTION:
XS GIS Cut Line= 4
      3441015.78     10595680.88      3440349.15     10595253.82
      3439797.07      10595113.2      3439266.51     10595165.21
#Sta/Elev= 30
  3954.9  504.46  3994.4  504.19  4030.5  503.17  4051.9  503.86  4109.4  502.15
  4151.7  502.09  4224.4  497.87  4239.6  498.15  4493.7  490.28  4636.2  483.94
  4695.6   482.8  4731.5  482.84  4846.7  483.58  4877.7  482.25  4895.2  482.64
  4982.1  482.07  4991.2  479.67  4998.5  478.96  5001.3  478.46  5004.5  478.96
  5011.8  481.45  5017.9  481.75    5023  481.21  5042.8  482.53  5099.7  484.12
  5197.6  485.38  5290.5  487.63  5622.8  499.53  5652.9  500.52  5849.4  501.61
#Mann= 5 ,-1 , 0
  3954.9     .05       0  4731.5     .16       0  4998.5     .07       0
  5004.5     .16       0  5622.8     .05       0
Bank Sta=4998.5,5004.5
XS Rating Curve= 0 ,0
Exp/Cntr=0.3,0.1

Type RM Length L Ch R = 1 ,15847   ,618,618,618
BEGIN DESCRIPTION:
UNT0027 IN CHRS 5.0
END DESCRIPTION:
XS GIS Cut Line= 3
      3441073.12     10595592.37      3440349.15      10594863.2
      3439365.98     10594988.05
#Sta/Elev= 30
  3781.8   502.8  3889.1   501.5  4009.3  498.66  4115.4  494.26  4285.1  489.89
  4405.3  488.01  4433.6  486.73  4440.7  487.19  4461.8  485.93  4589.8  482.54
  4645.7  480.35  4695.2  480.09  4780.1  479.98  4801.3  481.11  4856.8  481.69
  4897.1  480.94  4957.6  481.24  4987.8  480.46  4996.2  476.93  4998.9  476.43
  5002.2  476.93    5008  479.24    5018  480.75  5088.6  480.55  5118.8  485.75
  5154.2  486.84  5199.5  486.15  5469.2  495.04  5587.4  497.59  5800.4  500.28
#Mann= 5 ,-1 , 0
  3781.8     .05       0  4589.8     .16       0  4996.2     .07       0
  5002.2     .16       0  5587.4     .05       0
Bank Sta=4996.2,5002.2
XS Rating Curve= 0 ,0
Exp/Cntr=0.3,0.1

Type RM Length L Ch R = 1 ,15229   ,629,629,629
BEGIN DESCRIPTION:
UNT0027 IN CHRS 4.0
END DESCRIPTION:
XS GIS Cut Line= 4
       3441192.9     10595545.49      3440531.44     10594602.78
      3439729.36     10594446.53      3439276.67     10594691.09
#Sta/Elev= 30
  3573.2  501.76  3765.2  498.32  3842.5  496.45  3863.4  496.69  3920.1  494.04
  4137.1   489.3  4660.9  480.14  4785.3  479.32  4815.8  478.08  4832.7  478.92
  4856.5  480.21  4938.1  479.86  4958.5  477.91  4978.8  478.23    4989   476.7
  4996.2  476.67    4999  476.17  5002.2  476.67  5009.4  477.93  5029.8  478.35
  5090.9  483.42  5162.2  483.67  5176.4  484.97  5192.8  484.32  5222.9  486.68
  5239.4  486.89  5279.6  488.55  5447.5  492.14  5707.1  495.14  6056.5   496.8
#Mann= 6 ,-1 , 0
  3573.2     .16       0  3765.2     .05       0  4832.7     .16       0
  4996.2     .07       0  5002.2     .16       0  5239.4     .05       0
Bank Sta=4996.2,5002.2
XS Rating Curve= 0 ,0
Exp/Cntr=0.3,0.1

Type RM Length L Ch R = 1 ,14600   ,390,390,390
BEGIN DESCRIPTION:
UNT0027 IN CHRS 3.0
END DESCRIPTION:
XS GIS Cut Line= 4
      3441291.02      10594649.1      3440835.26     10594258.45
      3440501.06     10594084.84      3439980.25       10594189.
#Sta/Elev= 30
  4119.2  492.53  4158.8  490.86  4230.1  490.81  4343.2  488.87  4443.1   485.6
  4691.1  479.26  4748.1  478.95    4847  476.72  4866.7  477.33  4897.3  477.61
  4919.4  476.63  4932.9  474.29  4935.7  473.79  4938.9  474.29  4941.5  475.62
  4963.7  477.52  4985.8  477.36  4993.5  476.73  5007.9  474.41    5016   476.2
  5046.5  478.05  5107.8  477.84  5153.6  478.47  5237.8  480.45  5255.7  481.84
  5288.8  482.43  5362.7  485.36  5380.6  486.86  5574.3  491.25  5627.2  491.65
#Mann= 5 ,-1 , 0
  4119.2     .05       0  4866.7     .16       0  4932.9     .07       0
  4938.9     .16       0  5153.6     .05       0
Bank Sta=4932.9,4938.9
XS Rating Curve= 0 ,0
Exp/Cntr=0.3,0.1

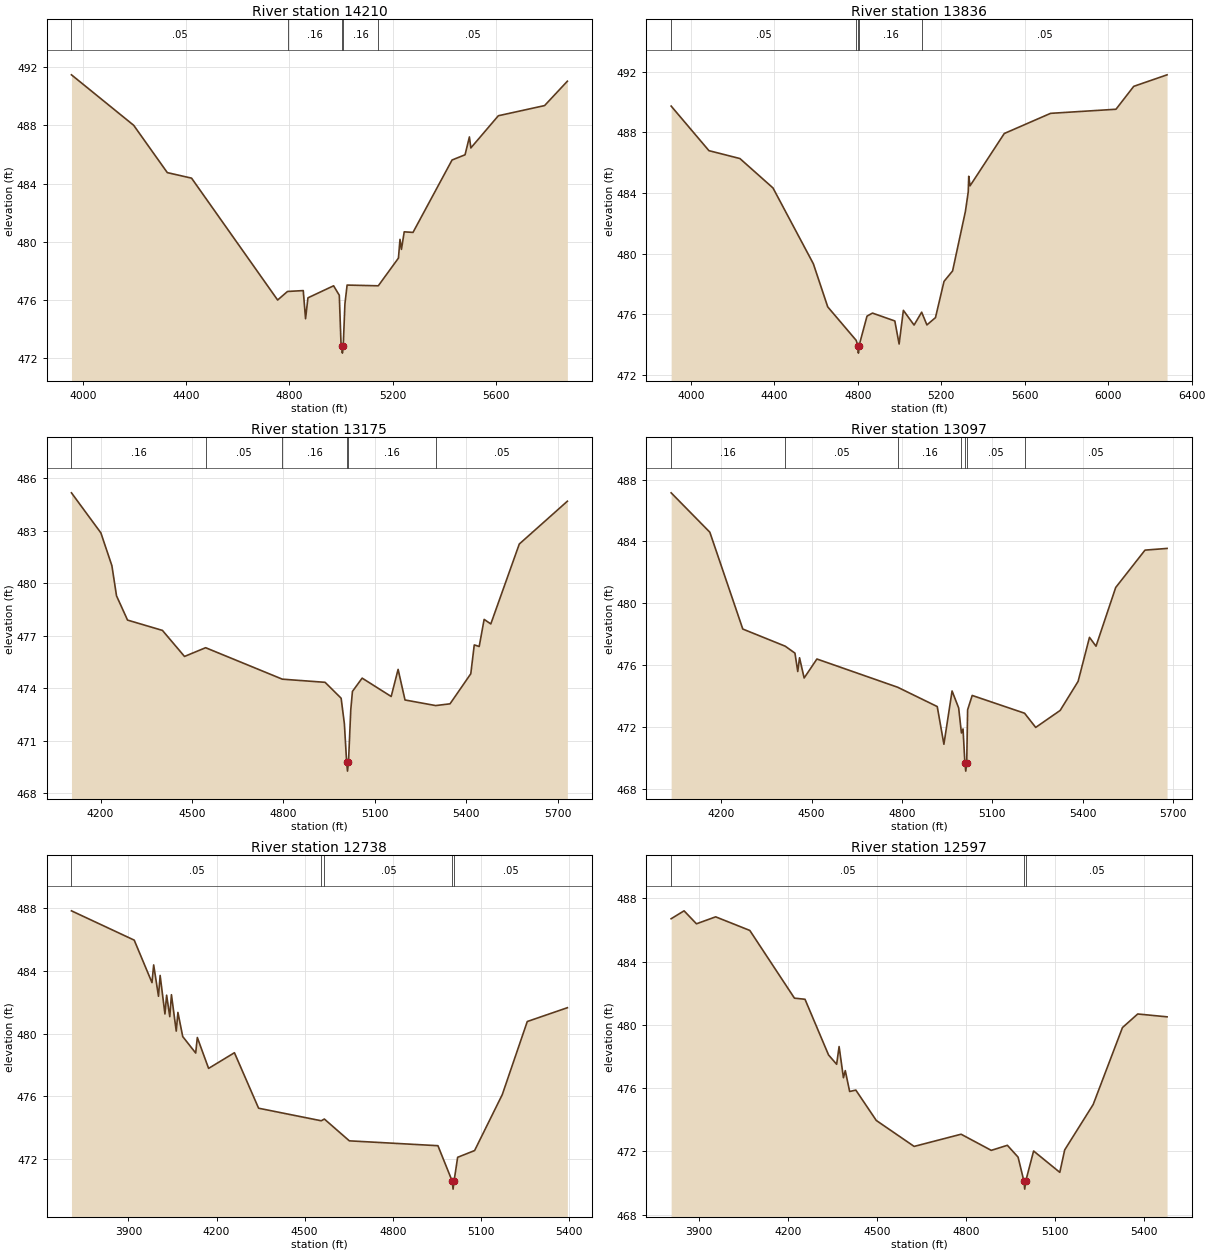
Type RM Length L Ch R = 1 ,14210   ,374,374,374
BEGIN DESCRIPTION:
UNT0027 IN CHRS 2.0
END DESCRIPTION:
XS GIS Cut Line= 4
      3441347.42     10594549.26      3440939.43     10593911.23
      3440488.04     10593715.92       3439885.9     10594014.82
#Sta/Elev= 30
  3955.8  491.49    4197  488.01  4327.2  484.75  4421.1  484.37  4754.6  475.97
  4792.9  476.56  4853.9  476.62  4862.8  474.68    4872  476.12  4971.4  476.95
  4993.5   476.3  5000.3  472.91  5002.8  472.81  5005.5  472.31  5008.8  472.81
  5015.3   475.7  5023.8     477  5144.6  476.95  5222.7  478.86  5228.7  480.15
  5234.3  479.46  5245.1  480.67  5279.1  480.63  5430.4  485.62  5480.8  485.98
  5497.6  487.21  5503.2  486.45  5609.7  488.67  5788.9  489.37  5877.2  491.05
#Mann= 5 ,-1 , 0
  3955.8     .05       0  4792.9     .16       0  5002.8     .07       0
  5008.8     .16       0  5144.6     .05       0
Bank Sta=5002.8,5008.8
XS Rating Curve= 0 ,0
Exp/Cntr=0.3,0.1

Type RM Length L Ch R = 1 ,13836   ,661,661,661
BEGIN DESCRIPTION:
UNT0027 IN CHRS 1.1
END DESCRIPTION:
XS GIS Cut Line= 4
      3441338.73     10594310.52      3441060.96     10593564.01
      3440448.98     10593425.12      3439693.81     10594006.68
#Sta/Elev= 30
  3904.9  489.73    4086  486.79  4234.5  486.27  4393.1  484.33  4586.6  479.33
  4655.5  476.49    4792  474.28  4799.8  473.94  4802.5  473.44  4805.8  473.94
  4843.8  475.88  4869.8  476.08  4977.1  475.56  4997.6  474.04  5018.1  476.26
  5069.4  475.29  5105.7  476.14  5130.9   475.3  5171.9  475.78  5212.9  478.17
    5254  478.86  5315.5  482.79    5329  484.07  5331.4   485.1  5337.7  484.47
  5501.7  487.92  5723.7  489.25  6037.2  489.52  6122.3  491.03  6282.1  491.79
#Mann= 5 ,-1 , 0
  3904.9     .05       0    4792     .16       0  4799.8     .07       0
  4805.8     .16       0  5105.7     .05       0
Bank Sta=4799.8,4805.8
XS Rating Curve= 0 ,0
Exp/Cntr=0.3,0.1

Type RM Length L Ch R = 1 ,13175   ,78,78,78
BEGIN DESCRIPTION:
UNT0027 IN CHRS 12.0
END DESCRIPTION:
XS GIS Cut Line= 4
      3441889.46     10593578.38      3441199.38     10593127.01
        3441067.     10593083.61      3440483.21     10592768.93
#Sta/Elev= 30
  4104.5  485.18    4201  482.89  4237.2  481.01  4252.3  479.29  4288.5   477.9
    4403  477.31  4475.4  475.82  4544.7  476.32  4796.4  474.52  4936.7  474.34
  4989.3  473.43  4999.9  471.98  5007.4  469.76  5010.2  469.26  5013.4  469.76
  5020.9  472.76  5026.4  473.82  5058.2  474.58  5153.5  473.53  5176.2  475.08
  5198.9  473.33  5299.5  473.01  5346.6  473.11  5414.7  474.83  5426.1  476.48
  5442.3  476.39  5458.5  477.94  5480.4  477.68  5573.8  482.25  5731.6   484.7
#Mann= 6 ,-1 , 0
  4104.5     .16       0  4544.7     .05       0  4796.4     .16       0
  5007.4     .07       0  5013.4     .16       0  5299.5     .05       0
Bank Sta=5007.4,5013.4
XS Rating Curve= 0 ,0
Exp/Cntr=0.3,0.1

Type RM Length L Ch R = 1 ,13097   ,359,359,359
BEGIN DESCRIPTION:
UNT0027 IN CHRS 12.2
END DESCRIPTION:
XS GIS Cut Line= 4
      3441948.04     10593543.65      3441566.13     10593302.79
      3441075.68     10592990.29      3440539.67     10592692.99
#Sta/Elev= 30
  4033.9  487.15  4162.3   484.6  4271.7  478.33  4412.5  477.22  4444.8  476.77
  4454.1  475.58    4460  476.47  4475.3  475.16  4517.7  476.39  4785.9  474.56
  4917.1  473.31  4939.2  470.87  4966.3  474.32  4988.2  473.22  4997.3   471.6
  5002.7  471.86  5008.9  469.63  5011.7  469.13  5014.9  469.63  5017.9   473.1
  5033.1  474.03  5206.9  472.88  5243.9  471.96  5325.1  473.06  5384.6  474.94
  5422.4  477.79  5444.1  477.22  5509.4  481.02  5606.7  483.44  5679.9  483.55
#Mann= 7 ,-1 , 0
  4033.9     .16       0  4412.5     .05       0  4785.9     .16       0
  4997.3     .05       0  5008.9     .04       0  5014.9     .05       0
  5206.9     .05       0
Bank Sta=5008.9,5014.9
XS Rating Curve= 0 ,0
Exp/Cntr=0.3,0.1

Type RM Length L Ch R = 1 ,12738   ,141,141,141
BEGIN DESCRIPTION:
UNT0027 IN CHRS 12.3
END DESCRIPTION:
XS GIS Cut Line= 5
      3442058.76     10593454.71      3441657.28      10593244.2
       3441444.6     10593131.35      3441058.32     10592857.91
      3440616.36     10592580.61
#Sta/Elev= 30
  3705.8  487.83  3919.6  485.96  3980.1  483.25  3985.8  484.38  4002.2  482.38
  4007.8  483.71  4024.2  481.25  4029.9  482.45  4040.7  481.08  4046.3  482.48
  4062.7  480.16  4068.4  481.35  4084.8  479.81  4128.9  478.76  4134.5  479.75
  4172.9  477.78  4260.9  478.78  4343.2  475.24  4556.5  474.44  4567.2  474.55
  4652.2  473.16    4954  472.85  5002.8  470.58  5005.6  470.08  5008.8  470.58
  5021.2  472.11  5078.9  472.54  5173.2  476.11  5258.3  480.77  5394.9  481.65
#Mann= 5 ,-1 , 0
  3705.8     .05       0  4556.5     .16       0  4567.2     .05       0
  5002.8    .035       0  5008.8     .05       0
Bank Sta=5002.8,5008.8
XS Rating Curve= 0 ,0
Exp/Cntr=0.3,0.1

Type RM Length L Ch R = 1 ,12597   ,654,654,654
BEGIN DESCRIPTION:
UNT0027 IN CHRS 12.1
END DESCRIPTION:
XS GIS Cut Line= 4
      3442050.06     10593344.01      3441492.34      10592931.7
      3440858.66     10592599.67      3440606.97      10592532.4
#Sta/Elev= 30
  3807.8  486.71  3851.3  487.21    3893  486.39  3957.7  486.83  4072.6  485.97
  4222.9  481.69  4258.4  481.62  4337.7   478.1  4364.9  477.51  4373.2  478.63
  4387.8  476.66    4394  477.11  4408.7  475.79  4429.5  475.88  4498.4  473.96
  4625.8  472.32  4783.9  473.09  4885.5  472.07  4939.7  472.39  4975.8  471.64
  4995.4  470.12  4998.1  469.62  5001.4  470.12    5028  472.03  5116.2  470.68
  5132.7   472.1  5228.6  474.97  5327.1  479.83  5378.5  480.69  5477.3  480.51
#Mann= 3 ,-1 , 0
  3807.8     .05       0  4995.4    .035       0  5001.4     .05       0
Bank Sta=4995.4,5001.4
XS Rating Curve= 0 ,0
Exp/Cntr=0.3,0.1

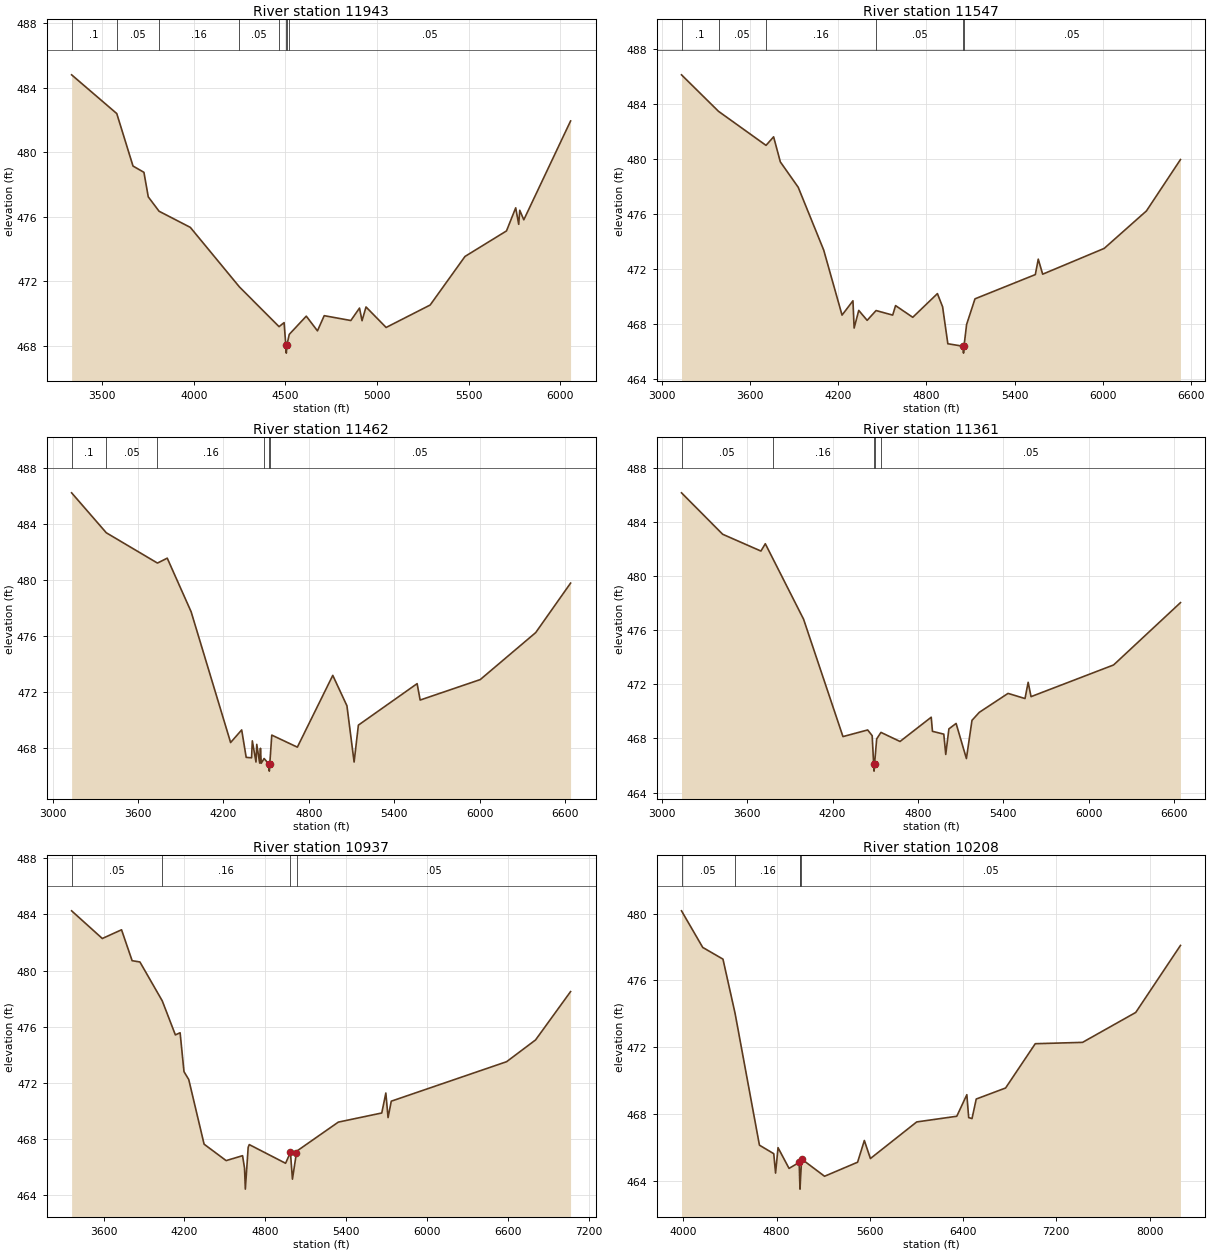
Type RM Length L Ch R = 1 ,11943   ,396,396,396
BEGIN DESCRIPTION:
UNT0027 IN CHRS 11.2
END DESCRIPTION:
XS GIS Cut Line= 4
      3442680.36     10592740.54      3441206.41     10592115.54
      3440581.41     10592097.31      3440141.35     10592323.85
#Sta/Elev= 30
  3334.1   484.8  3580.4   482.4  3668.9  479.15  3728.5  478.76  3752.2  477.24
    3811  476.35  3981.5  475.35  4249.4  471.66  4465.5   469.2  4492.9  469.45
  4502.3  468.06    4505  467.56  4508.3  468.06    4521  468.72  4613.9  469.85
  4674.9  468.94  4711.7  469.88  4856.9  469.58  4904.2  470.35    4918  469.57
  4939.7  470.42  5049.4  469.15  5289.5  470.54  5479.6  473.55  5705.8  475.13
    5756  476.56  5772.5  475.54  5778.1  476.41  5800.3  475.82  6055.3  481.94
#Mann= 8 ,-1 , 0
  3334.1      .1       0  3580.4     .05       0    3811     .16       0
  4249.4     .05       0  4465.5     .16       0  4502.3    .035       0
  4508.3     .16       0    4521     .05       0
Bank Sta=4502.3,4508.3
XS Rating Curve= 0 ,0
Exp/Cntr=0.3,0.1

Type RM Length L Ch R = 1 ,11547   ,85,85,85
BEGIN DESCRIPTION:
UNT0027 IN CHRS 11.3
END DESCRIPTION:
XS GIS Cut Line= 6
      3442811.98     10592686.87      3441853.81     10592086.69
      3441274.69     10591918.22      3441198.88      10591730.8
      3440579.76     10591703.42      3439901.68     10592173.02
#Sta/Elev= 30
  3134.2  486.09    3386  483.44  3709.3  480.97  3760.8  481.59  3806.6  479.77
  3928.2  477.93  4101.6  473.37  4226.4  468.65  4300.6  469.69  4308.6  467.71
  4340.1  468.99  4397.2  468.27  4457.9  468.98    4571  468.65  4590.5  469.34
  4707.4  468.49  4875.3  470.21  4910.5  469.25  4946.1  466.57    5050  466.39
  5052.7  465.89    5056  466.39  5073.8  467.97  5130.7  469.83  5541.3  471.59
  5561.3  472.71  5591.3  471.62  6009.7  473.49  6297.1  476.21  6528.7  479.94
#Mann= 6 ,-1 , 0
  3134.2      .1       0    3386     .05       0  3709.3     .16       0
  4457.9     .05       0    5050    .035       0    5056     .05       0
Bank Sta=5050,5056
XS Rating Curve= 0 ,0
Exp/Cntr=0.3,0.1

Type RM Length L Ch R = 1 ,11462   ,101,101,101
BEGIN DESCRIPTION:
UNT0027 IN CHRS 11.1
END DESCRIPTION:
XS GIS Cut Line= 6
      3442847.75     10592659.47      3441893.82     10592074.06
       3441348.4     10591886.63        3441241.     10591705.53
       3440596.6      10591623.4      3439842.69     10592133.03
#Sta/Elev= 30
  3133.4  486.23  3377.2  483.38  3736.6  481.22  3805.4  481.57  3973.1  477.75
  4250.7  468.42  4328.5  469.32  4360.2  467.36  4397.9  467.33  4403.2  468.54
  4429.1  467.03  4434.4  468.29  4455.1  466.95  4460.4  468.01  4465.9  466.94
    4486  467.28  4519.9  466.88  4522.6  466.38  4525.9  466.88  4539.9  468.95
  4719.7  468.09  4968.6  473.21  5068.1  471.04  5118.5  467.03  5148.5  469.66
  5561.3  472.62  5582.6  471.45  6004.9  472.91  6394.5  476.26  6639.6  479.79
#Mann= 6 ,-1 , 0
  3133.4      .1       0  3377.2     .05       0  3736.6     .16       0
    4486     .05       0  4519.9    .035       0  4525.9     .05       0
Bank Sta=4519.9,4525.9
XS Rating Curve= 0 ,0
Exp/Cntr=0.3,0.1

Type RM Length L Ch R = 1 ,11361   ,424,424,424
BEGIN DESCRIPTION:
UNT0027 IN CHRS 11.4
END DESCRIPTION:
XS GIS Cut Line= 6
      3442904.64     10592577.37      3441950.68     10591991.93
      3441405.26     10591804.51      3441297.86      10591623.4
      3440653.46     10591541.27      3439899.59     10592050.87
#Sta/Elev= 30
  3138.7  486.14    3428  483.08  3696.8  481.84  3727.6  482.38  3779.8   481.3
  3996.4  476.81  4273.3  468.14  4446.8  468.63  4478.5  468.21    4489  466.09
  4491.8  465.59    4495  466.09  4510.2  467.97  4540.4  468.45  4674.2  467.78
  4893.4  469.57  4902.2  468.53  4981.9  468.32  4995.5  466.82  5017.7  468.71
  5068.3  469.11  5140.7  466.52  5179.9  469.34  5231.2  469.93  5433.3  471.33
  5552.5  470.95  5574.7  472.15  5594.9  471.09  6175.1  473.43  6644.9  478.03
#Mann= 5 ,-1 , 0
  3138.7     .05       0  3779.8     .16       0    4489    .035       0
    4495     .16       0  4540.4     .05       0
Bank Sta=4489,4495
XS Rating Curve= 0 ,0
Exp/Cntr=0.3,0.1

Type RM Length L Ch R = 1 ,10937   ,729,729,729
BEGIN DESCRIPTION:
UNT0027 IN CHRS 11.9
END DESCRIPTION:
XS GIS Cut Line= 5
      3442930.68     10592343.89      3441706.73     10591380.35
      3441487.98     10591231.92        3440751.     10591323.06
      3439835.68     10591999.15
#Sta/Elev= 30
  3363.2  484.26    3591  482.29  3733.7  482.91  3812.3  480.71  3870.1  480.62
  4035.9  477.85  4133.1  475.43  4168.3  475.58  4197.2  472.81  4232.5  472.25
  4346.3  467.65  4509.9  466.48  4631.8  466.83  4646.3  465.95  4652.4  464.45
  4673.4  467.43  4681.5  467.62    4951  466.29    4987  467.07  5001.9  465.16
  5031.8  467.05  5037.8  467.18  5342.3  469.22  5664.8  469.87    5695  471.29
  5711.4  469.54  5735.3  470.71    6591  473.52    6806  475.07  7065.8  478.51
#Mann= 4 ,-1 , 0
  3363.2     .05       0  4035.9     .16       0    4987    .035       0
  5037.8     .05       0
Bank Sta=4987,5031.8
XS Rating Curve= 0 ,0
Exp/Cntr=0.3,0.1

Type RM Length L Ch R = 1 ,10208   ,1554,1554,1554
BEGIN DESCRIPTION:
UNT0027 IN CHRS 11.0
END DESCRIPTION:
XS GIS Cut Line= 4
      3442804.07     10591889.98      3441936.03     10590490.27
      3440742.45     10591173.86      3439745.67     10591943.12
#Sta/Elev= 30
  3984.1  480.16  4166.3  477.97  4339.9  477.27    4444  474.02  4652.9  466.14
  4775.8  465.63  4791.2  464.47  4812.5  465.99    4907  464.75  4994.1  465.11
  4998.5  464.01  5001.2  463.51  5004.5  464.01  5012.6     465  5016.8   465.3
  5211.7  464.28  5495.2  465.12  5553.1  466.42  5605.1  465.34  6002.4  467.53
  6346.3  467.87  6432.6  469.16  6448.4  467.79  6476.9  467.73  6513.2   468.9
    6765  469.56  7019.7  472.21  7425.3  472.29  7881.8  474.08  8265.7  478.09
#Mann= 5 ,-1 , 0
  3984.1     .05       0    4444     .16       0  4998.5     .07       0
  5004.5     .16       0  5012.6     .05       0
Bank Sta=4994.1,5016.8
XS Rating Curve= 0 ,0
Exp/Cntr=0.3,0.1

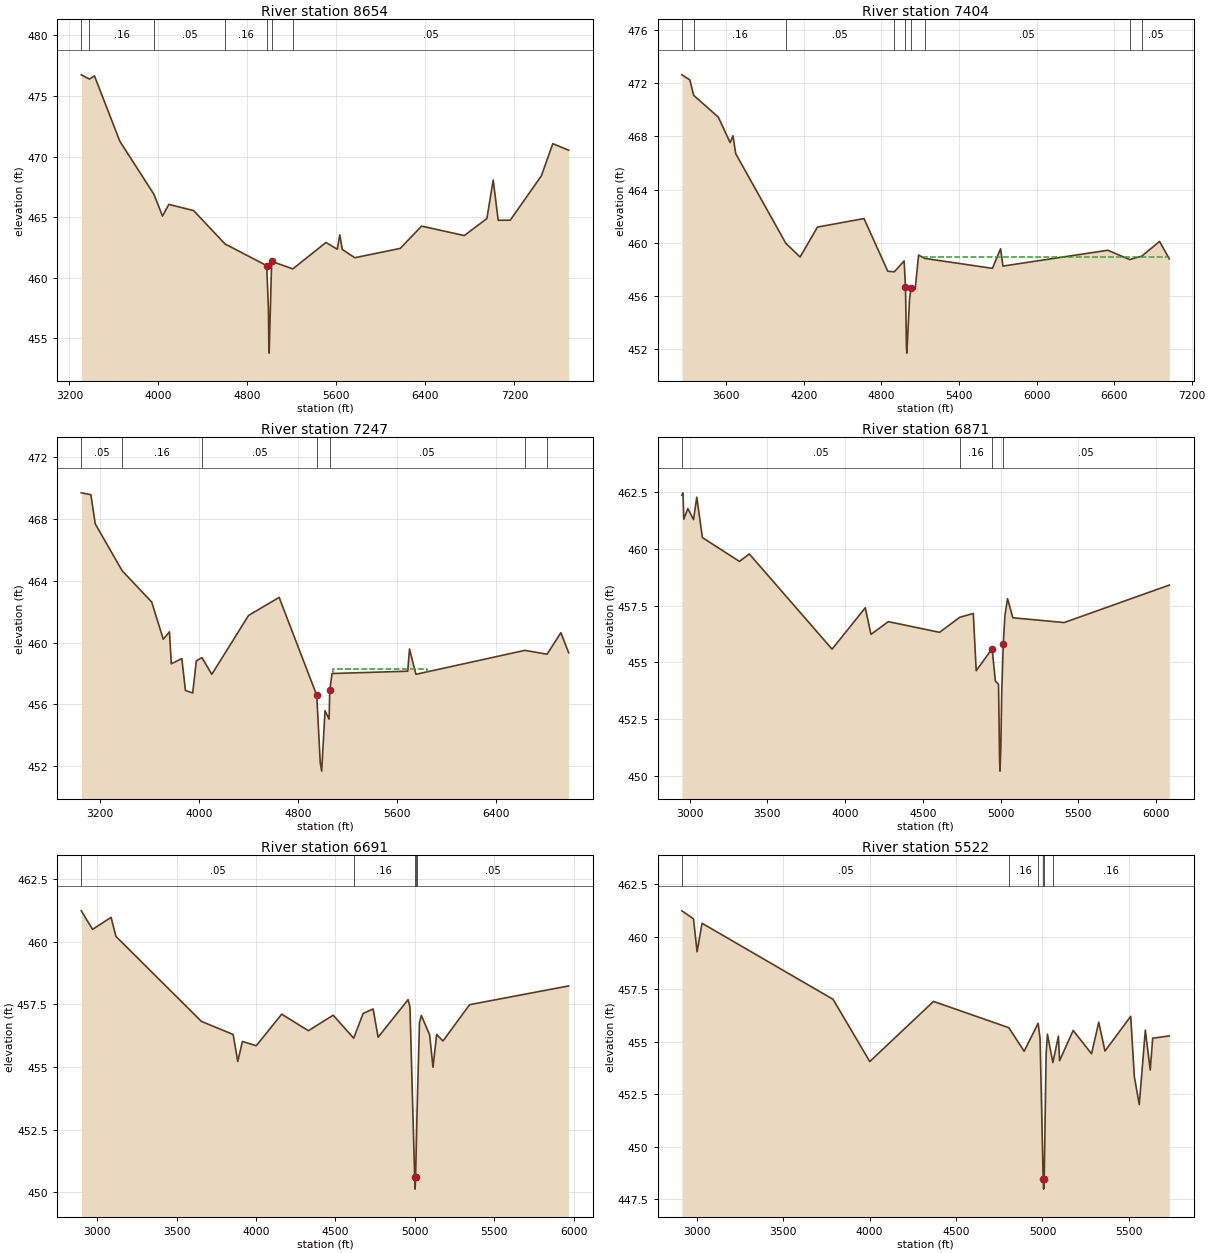
Type RM Length L Ch R = 1 ,8654    ,1250,1250,1250
BEGIN DESCRIPTION:
UNT0027 IN CHRS 9.0
END DESCRIPTION:
XS GIS Cut Line= 5
      3444236.41     10590414.32      3442966.85     10590067.09
      3441881.78      10589535.4      3440829.26     10590045.39
      3440255.64      10590424.2
#Sta/Elev= 30
  3306.6  476.75  3379.8   476.4  3425.1  476.66  3653.2  471.27  3959.2   466.9
  4036.8   465.1  4093.8  466.06  4316.4  465.55  4598.2   462.8  4973.3  461.01
  4988.7  457.43  4992.6  454.29  4995.3  453.79  5017.8  461.36  5208.2  460.74
  5506.2  462.92    5608  462.36  5630.3  463.55  5652.6  462.35  5764.8  461.66
  6173.8  462.43  6365.6  464.27  6749.4  463.49  6952.6  464.89  7009.3  468.07
  7054.3  464.75  7162.7  464.76  7442.6  468.42    7545  471.07  7688.1  470.53
#Mann= 7 ,-1 , 0
  3306.6     .05       0  3379.8     .16       0  3959.2     .05       0
  4598.2     .16       0  4973.3     .07       0  5017.8     .16       0
  5208.2     .05       0
Bank Sta=4973.3,5017.8
XS Rating Curve= 0 ,0
Exp/Cntr=0.3,0.1

Type RM Length L Ch R = 1 ,7404    ,157,157,157
BEGIN DESCRIPTION:
UNT0027 IN CHRS 8.0
END DESCRIPTION:
XS GIS Cut Line= 4
      3444690.58      10589979.1      3443790.01     10589241.29
      3441630.72     10588546.84       3441348.6     10588362.38
#Sta/Elev= 30
  3257.1  472.63  3318.7  472.25  3348.4  471.09    3539  469.45  3630.2  467.54
  3652.4  468.05  3673.3  466.71  4061.1  459.97  4171.3  458.94  4305.6  461.19
  4665.5  461.83  4849.8  457.87  4900.2  457.83  4975.9  458.65  4986.4  456.69
  4993.9  452.22  4996.7  451.72  5017.9  455.79    5029  456.58  5061.1  456.52
  5087.9  459.09  5133.4  458.84  5658.6  458.09  5721.7  459.56  5740.2  458.26
  6551.5  459.45  6719.9  458.75  6814.1  459.01  6951.2  460.11  7026.6   458.8
#Mann= 9 ,-1 , 0
  3257.1     .05       0  3348.4     .16       0  4061.1     .05       0
  4900.2     .16       0  4986.4     .07       0    5029     .16       0
  5133.4     .05       0  6719.9     .08       0  6814.1     .05       0
#XS Ineff= 1 ,-1
 5122.11 7128.71  458.91
Permanent Ineff=
       F
Bank Sta=4986.4,5029
XS Rating Curve= 0 ,0
Exp/Cntr=0.3,0.1

Type RM Length L Ch R = 1 ,7247    ,376,376,376
BEGIN DESCRIPTION:
UNT0027 IN CHRS 7.1
END DESCRIPTION:
XS GIS Cut Line= 4
       3445016.1     10589805.49      3444310.84     10589273.84
      3443833.41     10589078.53      3441398.51     10588358.04
#Sta/Elev= 30
  3050.5   469.7    3128  469.58  3163.4  467.69  3380.3  464.66  3619.4  462.63
    3713  460.22    3763   460.7  3777.6  458.63  3862.9  458.97  3892.1   456.9
  3950.6  456.74    3980  458.82  4025.1  459.03  4105.2  457.95    4402  461.76
    4649  462.93  4953.1  456.59  4981.2  452.23  4992.9  451.68  5019.7  455.59
  5052.9  455.05  5058.1  456.93  5076.6     458  5688.2  458.15  5702.3  459.59
  5754.5  457.95  6634.3   459.5  6813.8  459.25  6925.5  460.64  6988.8  459.34
#Mann= 7 ,-1 , 0
  3050.5     .05       0  3380.3     .16       0  4025.1     .05       0
  4953.1     .04       0  5058.1     .05       0  6634.3     .08       0
  6813.8     .05       0
#XS Ineff= 1 ,-1
 5085.81 5843.56  458.29
Permanent Ineff=
       F
Bank Sta=4953.1,5058.1
XS Rating Curve= 0 ,0
Exp/Cntr=0.3,0.1

Type RM Length L Ch R = 1 ,6871    ,180,180,180
BEGIN DESCRIPTION:
UNT0027 IN CHRS 6.1
END DESCRIPTION:
XS GIS Cut Line= 3
       3445332.6     10589139.34       3444155.4     10588736.13
      3442310.66     10588315.64
#Sta/Elev= 30
  2949.6  462.36  2956.7  462.46    2962   461.3    2988  461.77  3024.5  461.28
  3045.2  462.27  3081.8  460.49  3320.1  459.44  3383.5  459.77    3916  455.58
  4129.7   457.4  4166.3  456.23  4277.9  456.79  4607.6  456.32  4737.2  456.98
  4824.8  457.15  4843.5  454.63    4946   455.6  4966.6  454.18  4987.1  454.03
  4993.9  450.71  4996.6  450.21    5002  451.28  5007.6  453.66  5017.8  455.82
  5028.1  457.06    5045   457.8  5079.4  456.96  5409.6  456.75    6086   458.4
#Mann= 4 ,-1 , 0
  2949.6     .05       0  4737.2     .16       0    4946    .035       0
  5017.8     .05       0
Bank Sta=4946,5017.8
XS Rating Curve= 0 ,0
Exp/Cntr=0.3,0.1

Type RM Length L Ch R = 1 ,6691    ,1169,1169,1169
BEGIN DESCRIPTION:
UNT0027 IN CHRS 5.2
END DESCRIPTION:
XS GIS Cut Line= 3
      3445384.67     10589123.71      3444303.88     10588660.76
      3442496.14     10588098.95
#Sta/Elev= 30
  2900.5  461.24  2971.6   460.5  3088.2  460.98  3118.5  460.22  3657.2  456.82
  3856.7   456.3  3885.7  455.22    3915  456.02  4002.1  455.85  4162.3  457.11
  4330.3  456.45  4486.5  457.07  4615.6  456.15    4675  457.14  4737.9  457.32
  4769.3  456.19  4957.8  457.69  4969.8   457.4  4999.4  450.62  5002.1  450.12
  5005.4  450.62    5014  453.08  5029.7  456.77  5041.5  457.06  5093.9  456.28
  5114.8  454.99  5137.9   456.3  5177.7  456.04  5345.2  457.49  5969.3  458.24
#Mann= 5 ,-1 , 0
  2900.5     .05       0  4615.6     .16       0  4999.4     .07       0
  5005.4     .16       0    5014     .05       0
Bank Sta=4999.4,5005.4
XS Rating Curve= 0 ,0
Exp/Cntr=0.3,0.1

Type RM Length L Ch R = 1 ,5522    ,997,997,997
BEGIN DESCRIPTION:
UNT0027 IN CHRS 5.1
END DESCRIPTION:
XS GIS Cut Line= 3
      3445415.89     10589082.02      3444653.46     10588219.16
      3443406.84     10587111.45
#Sta/Elev= 30
  2914.5  461.23  2981.6  460.85  3002.5  459.28    3031  460.64  3788.8  457.02
  4001.3  454.06  4369.8  456.92  4805.4  455.67  4894.1  454.55    4975  455.88
  4986.1  455.15    5004  448.49  5006.8  447.99    5010  448.49  5021.2  454.43
  5028.7  455.36  5060.2  454.01  5092.3  455.27    5099   454.1  5177.6  455.54
  5283.8  454.43  5325.6  455.93  5361.6  454.56  5510.4  456.21  5531.3  453.35
  5559.8  452.01  5594.9  455.55  5623.3  453.66  5637.5  455.17  5733.6  455.28
#Mann= 6 ,-1 , 0
  2914.5     .05       0  4805.4     .16       0    4975     .12       0
    5004     .07       0    5010     .12       0  5060.2     .16       0
Bank Sta=5004,5010
XS Rating Curve= 0 ,0
Exp/Cntr=0.3,0.1

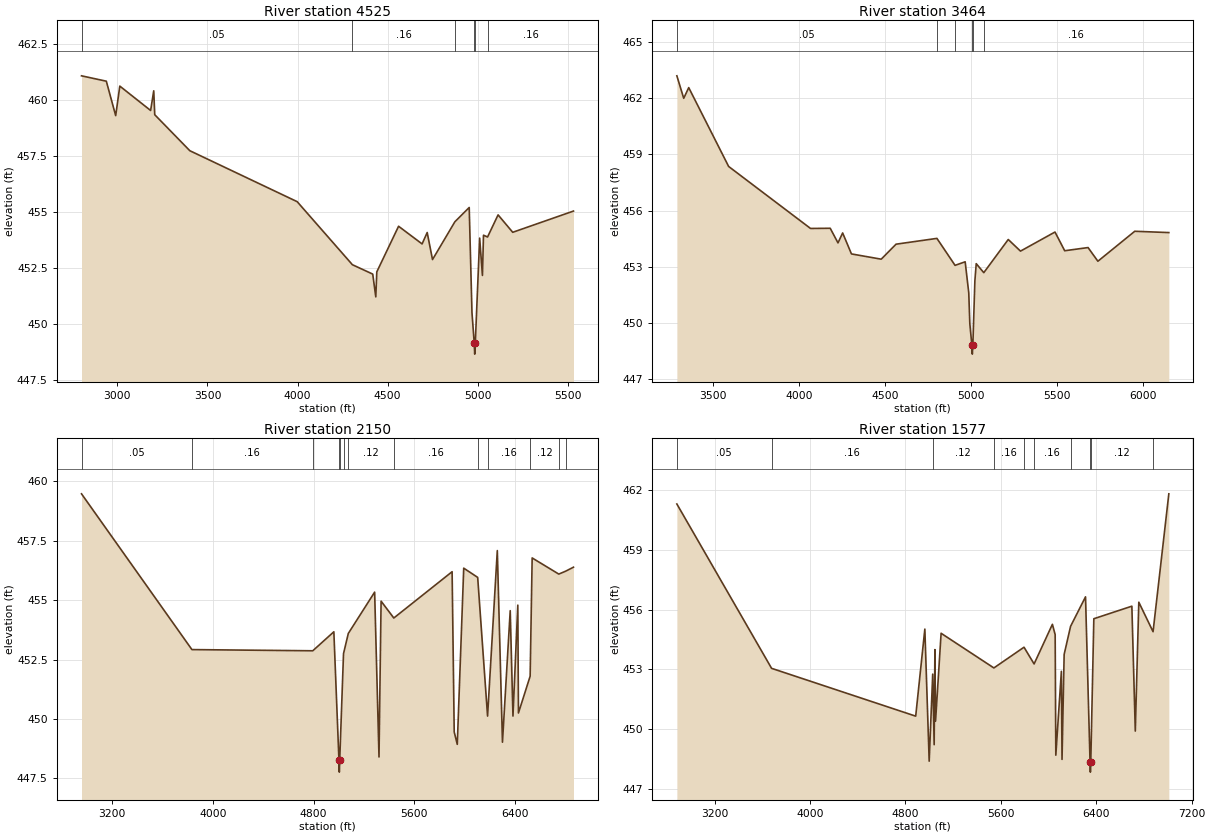
Type RM Length L Ch R = 1 ,4525    ,1061,1061,1061
BEGIN DESCRIPTION:
UNT0027 IN CHRS 4.1
END DESCRIPTION:
XS GIS Cut Line= 3
      3445478.38     10589066.37      3444659.32     10587312.11
      3444242.93     10586635.17
#Sta/Elev= 30
  2800.9  461.09  2938.6  460.85  2990.6  459.31  3013.5  460.63  3184.5  459.54
  3201.8  460.42  3207.4  459.35  3402.1  457.74    3998  455.46  4304.5  452.64
  4417.4  452.22  4434.4   451.2    4440  452.32  4560.9  454.36  4691.4  453.57
  4719.7  454.08  4749.2  452.87  4873.3  454.56  4952.9   455.2  4968.3  450.49
  4980.7  449.14  4983.5  448.64  4986.7  449.14  5010.9  453.83  5026.3  452.16
  5032.2  453.96  5054.8  453.88  5113.2  454.87  5194.4  454.09  5531.7  455.04
#Mann= 6 ,-1 , 0
  2800.9     .05       0  4304.5     .16       0  4873.3     .12       0
  4980.7     .07       0  4986.7     .12       0  5054.8     .16       0
Bank Sta=4980.7,4986.7
XS Rating Curve= 0 ,0
Exp/Cntr=0.3,0.1

Type RM Length L Ch R = 1 ,3464    ,1314,1314,1314
BEGIN DESCRIPTION:
UNT0027 IN CHRS 3.1
END DESCRIPTION:
XS GIS Cut Line= 3
      3446314.54     10588434.97      3445609.26     10587360.78
      3444339.75     10586427.64
#Sta/Elev= 30
  3291.2   463.2  3331.1     462  3360.2  462.57  3592.3  458.36  4068.4  455.05
  4182.9  455.06  4228.1  454.28  4255.2  454.81  4306.4  453.69  4479.5  453.41
  4565.6  454.21  4803.3  454.52  4908.8  453.08  4967.6  453.27  4988.5  451.61
  4994.7  449.96  5006.3  448.84  5009.1  448.34  5012.3  448.84    5024  452.25
  5031.9  453.17  5075.9  452.69  5218.1  454.46  5289.3  453.84  5489.9  454.86
  5546.3  453.86  5682.1  454.03  5739.3   453.3  5953.7   454.9  6151.8  454.83
#Mann= 6 ,-1 , 0
  3291.2     .05       0  4803.3     .16       0  4908.8     .12       0
  5006.3     .07       0  5012.3     .12       0  5075.9     .16       0
Bank Sta=5006.3,5012.3
XS Rating Curve= 0 ,0
Exp/Cntr=0.3,0.1

Type RM Length L Ch R = 1 ,2150    ,573,573,573
BEGIN DESCRIPTION:
UNT0027 IN CHRS 2.1
END DESCRIPTION:
XS GIS Cut Line= 3
      3446642.11     10587941.65      3445642.11     10586141.64
      3443842.15     10585741.65
#Sta/Elev= 30
  2959.3  459.48  3835.2  452.92  4793.9  452.87  4961.2  453.67  5001.7  448.26
  5004.5  447.76  5007.7  448.26  5037.9  452.75  5075.9   453.6  5284.8  455.34
  5319.4   448.4    5336  454.96  5436.9  454.25  5899.4   456.2  5916.1  449.45
  5940.4  448.93  5991.6  456.35  6102.3  455.96  6180.7  450.12    6258  457.09
  6298.9  449.02  6360.4  454.56  6382.2  450.12  6420.6  454.79  6425.7  450.25
  6518.5   451.8  6534.5  456.78  6745.7   456.1  6799.3  456.22  6862.3  456.39
#Mann= 13 ,-1 , 0
  2959.3     .05       0  3835.2     .16       0  4793.9     .12       0
  5001.7     .07       0  5007.7     .12       0  5037.9     .16       0
  5075.9     .12       0  5436.9     .16       0  6102.3     .12       0
  6180.7     .16       0  6518.5     .12       0  6745.7     .16       0
  6799.3     .12       0
Bank Sta=5001.7,5007.7
XS Rating Curve= 0 ,0
Exp/Cntr=0.3,0.1

Type RM Length L Ch R = 1 ,1577    ,0,0,0
BEGIN DESCRIPTION:
UNT0027 IN CHRS 1.0
END DESCRIPTION:
XS GIS Cut Line= 3
      3446742.12     10587891.67      3445942.11     10585891.64
      3444142.08     10585091.63
#Sta/Elev= 30
  2884.2   461.3  3678.2  453.05  4886.2  450.65  4962.9  455.02  4999.3  448.39
  5028.8  452.76    5041  449.22  5047.2  453.99  5052.7   450.4  5099.2  454.81
  5541.6  453.07  5794.2  454.11  5878.7  453.27  6032.1  455.26  6055.3  454.74
  6060.8  448.69  6107.3   452.9  6112.8  448.48  6130.6  453.75  6184.6  455.16
  6309.8  456.64  6347.8  448.34  6350.5  447.84  6353.8  448.34  6379.5  455.54
  6698.2  456.17    6727   449.9  6756.4  456.37  6875.9  454.89  7008.1  461.81
#Mann= 10 ,-1 , 0
  2884.2     .05       0  3678.2     .16       0  5028.8     .12       0
  5541.6     .16       0  5794.2     .12       0  5878.7     .16       0
  6184.6     .12       0  6347.8     .07       0  6353.8     .12       0
  6875.9     .16       0
Bank Sta=6347.8,6353.8
XS Rating Curve= 0 ,0
Exp/Cntr=0.3,0.1

Chan Stop Cuts=-1
Use User Specified Reach Order=0
Composite Channel Slope=5