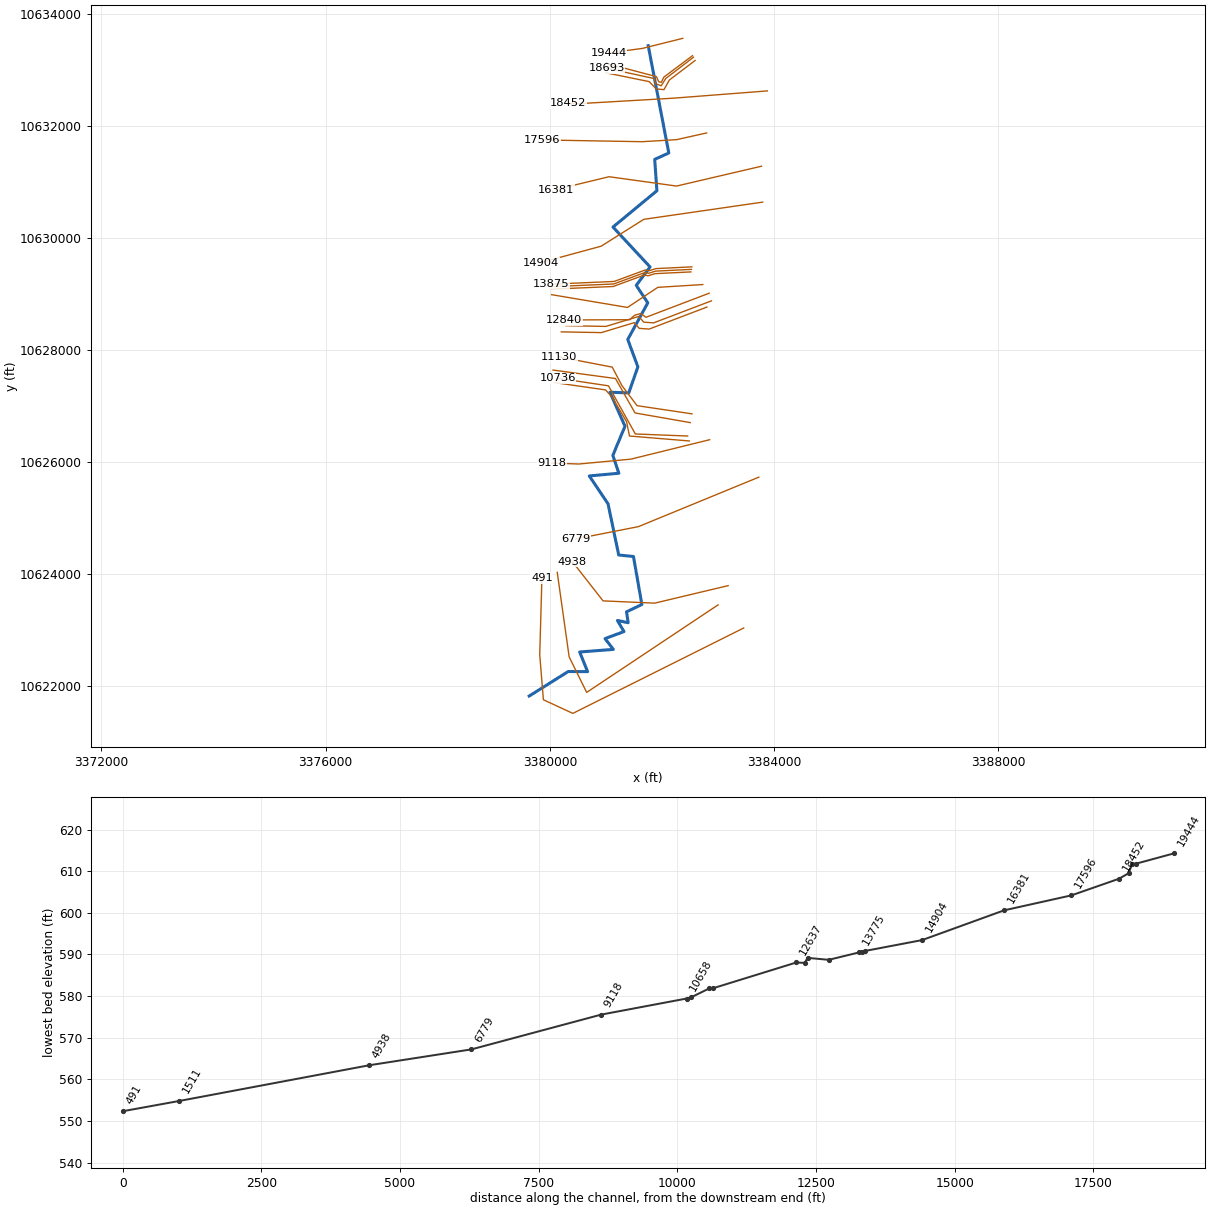
--- UNT00270 IN CHRS.prj (project) ---

Proj Title=UNT00270 IN CHRS Base Level Engineering
Current Plan=p01
Default Exp/Contr=0.3,0.1
English Units
Geom File=g01
Flow File=f01
Plan File=p01
Y Axis Title=Elevation
X Axis Title(PF)=Main Channel Distance
X Axis Title(XS)=Station
BEGIN DESCRIPTION:
UNT00270 IN CHRS
END DESCRIPTION:
DSS Export Rating Curves= 0
DSS Export Rating Curve Sorted= 0
DSS Export Volume Flow Curves= 0
DXF OffsetX= 0
DXF OffsetY= 0
DXF ScaleX= 1
DXF ScaleY= 10

--- UNT00270 IN CHRS.p01 (plan) ---

Plan Title=Multiple Run
Short Identifier=Multiple
Geom File=g01
Flow File=f01
Subcritical Flow
K Sum by GR= 0
Std Step Tol= 0.01
Critical Tol= 0.01
Num of Std Step Trials= 20
Max Error Tol= 0.3
Flow Tol Ratio= 0.001
Split Flow NTrial= 30
Split Flow Tol= 0.02
Split Flow Ratio= 0.02
Log Output Level= 0
Friction Slope Method= 1
Unsteady Friction Slope Method= 2
Unsteady Bridges Friction Slope Method= 1
Parabolic Critical Depth
Global Vel Dist=  1 , 1 , 1
Global Log Level= 0
CheckData=True
Encroach Param= -1, 0, 0, 0
BEGIN DESCRIPTION:
Multiple Run
END DESCRIPTION:

--- UNT00270 IN CHRS.f01 (steady flow) ---

Flow Title=Multiple
Number of Profiles=7
Profile Names=10-year,25-year,50-year,1pct_min,100-year,1pct_plu,500-year
River Rch & RM= UNT00270 IN CHRS,Reach-1,19444
     325     404     461     383     518     700     653
River Rch & RM= UNT00270 IN CHRS,Reach-1,13220
     383     480     550     459     621     840     790
River Rch & RM= UNT00270 IN CHRS,Reach-1,10736
     493     627     726     611     827    1118    1071
Boundary for River Rch & Prof#=UNT00270 IN CHRS,Reach-1,1
Up Type=0
Dn Type=3
Dn Slope=0.005
Boundary for River Rch & Prof#=UNT00270 IN CHRS,Reach-1,2
Up Type=0
Dn Type=3
Dn Slope=0.005
Boundary for River Rch & Prof#=UNT00270 IN CHRS,Reach-1,3
Up Type=0
Dn Type=3
Dn Slope=0.005
Boundary for River Rch & Prof#=UNT00270 IN CHRS,Reach-1,4
Up Type=0
Dn Type=3
Dn Slope=0.005
Boundary for River Rch & Prof#=UNT00270 IN CHRS,Reach-1,5
Up Type=0
Dn Type=3
Dn Slope=0.005
Boundary for River Rch & Prof#=UNT00270 IN CHRS,Reach-1,6
Up Type=0
Dn Type=3
Dn Slope=0.005
Boundary for River Rch & Prof#=UNT00270 IN CHRS,Reach-1,7
Up Type=0
Dn Type=3
Dn Slope=0.005

--- UNT00270 IN CHRS.g01 (geometry) ---

Geom Title=Existing Conditions
Program Version=4.10

River Reach=UNT00270 IN CHRS,Reach-1
Reach XY= 30
      3381754.31      10633425.9       3382121.1     10631511.83
      3381869.76     10631397.93      3381908.72     10630838.23
       3381125.7     10630190.18       3381787.4     10629478.18
      3381540.16     10629150.83      3381746.73      10628837.7
      3381389.44     10628184.44      3381569.56      10627695.6
      3381407.24     10627230.88      3381071.12     10627242.78
      3381340.16     10626636.04       3381123.2      10626115.9
      3381230.35     10625797.45      3380703.29     10625748.95
      3381037.96     10625251.14      3381227.73     10624338.48
      3381490.94     10624311.47      3381640.89     10623454.59
        3381368.     10623324.49      3381396.21     10623130.27
      3381205.42     10623169.81      3381321.75     10622971.69
      3380984.15     10622845.99      3381131.97     10622653.88
      3380532.25     10622607.57      3380673.74     10622256.76
      3380327.85     10622259.04      3379632.11     10621821.64

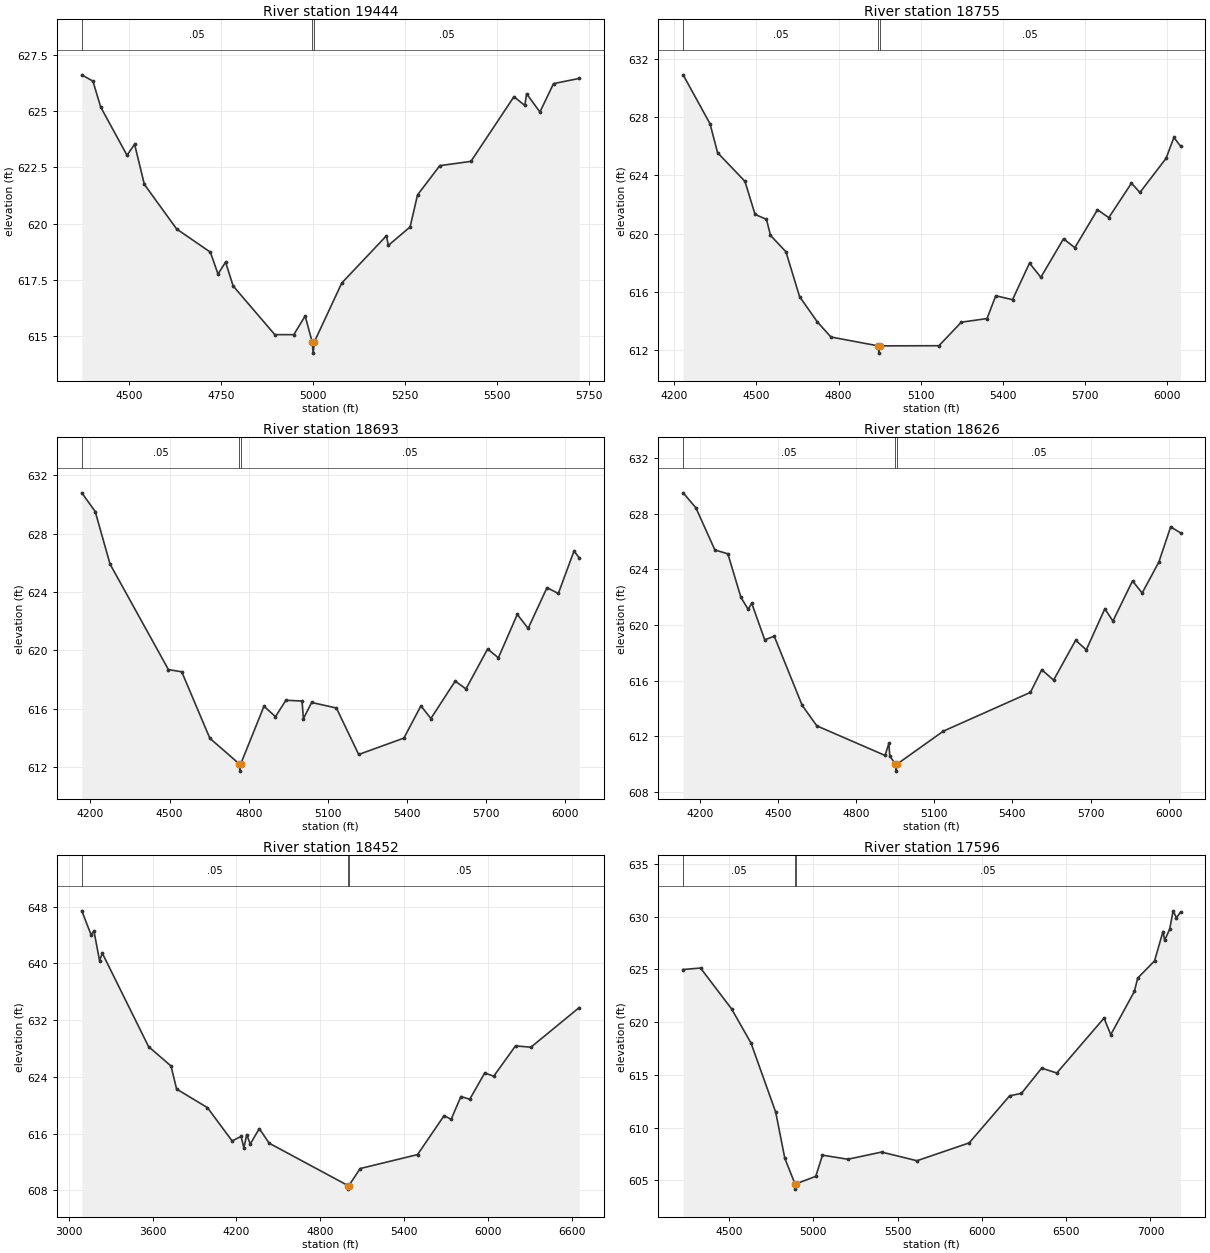
Type RM Length L Ch R = 1 ,19444   ,689,689,689
BEGIN DESCRIPTION:
UNT00270 IN CHRS 21.0
END DESCRIPTION:
XS GIS Cut Line= 3
      3382371.47     10633557.97      3381648.81     10633377.85
      3381046.29     10633297.66
#Sta/Elev= 30
  4371.7  626.61    4402  626.33  4423.1  625.18  4494.7  623.04  4515.3  623.53
  4541.8  621.75  4629.6  619.77  4721.4  618.74  4742.1  617.77  4762.7   618.3
  4783.3  617.24  4896.6  615.08  4948.2  615.08  4979.1  615.91  4998.1  614.76
  5000.9  614.26  5004.1  614.76  5078.6  617.37  5200.2  619.47  5205.2  619.04
  5264.5  619.86  5284.6  621.28  5345.2  622.58  5429.9  622.77  5546.9  625.64
  5576.3  625.25  5581.3  625.77  5617.5  624.96  5654.5  626.22  5724.3  626.45
#Mann= 3 ,-1 , 0
  4371.7     .05       0  4998.1     .03       0  5004.1     .05       0
Bank Sta=4998.1,5004.1
XS Rating Curve= 0 ,0
Exp/Cntr=0.3,0.1

Type RM Length L Ch R = 1 ,18755   ,62,62,62
BEGIN DESCRIPTION:
UNT00270 IN CHRS 20.1
END DESCRIPTION:
XS GIS Cut Line= 6
      3382542.92     10633247.65       3382035.1     10632867.87
      3381987.36     10632774.55      3381941.78     10632781.06
      3381900.55     10632874.38      3381008.67     10633110.91
#Sta/Elev= 30
  4232.2  630.93  4330.5  627.56  4358.1  625.57    4458   623.6  4495.1  621.32
  4536.8  620.98  4551.4  619.88  4607.8  618.75  4657.8  615.66  4722.3  613.93
  4772.3  612.88  4944.8  612.27  4947.6  611.77  4950.8  612.27    5167  612.28
  5248.8   613.9  5342.8  614.15  5374.6  615.72  5435.9  615.45    5498  617.97
  5539.4  616.99  5622.2  619.64  5663.6  619.03  5746.3  621.64  5787.7   621.1
  5870.5  623.47  5901.5  622.83    5997  625.18  6025.7  626.62  6049.9  626.02
#Mann= 3 ,-1 , 0
  4232.2     .05       0  4944.8    .035       0  4950.8     .05       0
Bank Sta=4944.8,4950.8
XS Rating Curve= 0 ,0
Exp/Cntr=0.3,0.1

Type RM Length L Ch R = 1 ,18693   ,67,67,67
BEGIN DESCRIPTION:
UNT00270 IN CHRS 19.0
END DESCRIPTION:
XS GIS Cut Line= 6
      3382562.45     10633221.61      3382067.65     10632841.83
      3381985.19     10632711.62      3381883.19     10632750.68
      3381863.66     10632839.66      3381012.98     10633024.11
#Sta/Elev= 30
  4167.7  630.79  4218.6  629.51  4274.8  625.91  4495.9  618.69  4546.3  618.54
  4652.8  613.99    4764  612.24  4766.8  611.74    4770  612.24  4857.8  616.18
  4901.5  615.47  4940.8  616.59  5002.1  616.54  5007.2  615.33  5038.4  616.44
  5132.2  616.06  5216.7  612.88  5387.8     614  5452.4  616.21  5490.1  615.34
  5582.2   617.9  5623.1  617.37    5705   620.1  5745.9   619.5  5817.5  622.47
  5858.5  621.51  5930.1   624.3  5972.9   623.9  6032.4  626.81    6052  626.34
#Mann= 3 ,-1 , 0
  4167.7     .05       0    4764     .03       0    4770     .05       0
Bank Sta=4764,4770
XS Rating Curve= 0 ,0
Exp/Cntr=0.3,0.1

Type RM Length L Ch R = 1 ,18626   ,174,174,174
BEGIN DESCRIPTION:
UNT00270 IN CHRS 20.0
END DESCRIPTION:
XS GIS Cut Line= 6
      3382590.63     10633162.99      3382130.59     10632813.61
       3382035.1     10632642.17      3381896.21     10632655.19
      3381772.51      10632785.4      3380997.75     10632943.83
#Sta/Elev= 30
  4136.4  629.51  4185.5  628.43  4258.2   625.4  4308.1  625.12  4358.1  621.99
  4385.7  621.13  4399.7  621.56  4449.6  618.93  4486.1  619.19  4593.1  614.22
  4649.4  612.74  4911.2  610.61  4925.8  611.47  4929.6  610.57  4950.9  609.98
  4953.7  609.48  4956.9  609.98  5135.2  612.36  5469.2  615.15  5512.6  616.78
    5558  616.03  5642.7   618.9  5683.5  618.21  5754.8  621.17  5785.6  620.28
  5860.9  623.17  5897.9   622.3  5961.8  624.52  6007.2  627.06  6045.2  626.63
#Mann= 3 ,-1 , 0
  4136.4     .05       0  4950.9     .03       0  4956.9     .05       0
Bank Sta=4950.9,4956.9
XS Rating Curve= 0 ,0
Exp/Cntr=0.3,0.1

Type RM Length L Ch R = 1 ,18452   ,856,856,856
BEGIN DESCRIPTION:
UNT00270 IN CHRS 18.0
END DESCRIPTION:
XS GIS Cut Line= 4
      3383878.78     10632619.73      3382196.49     10632489.52
      3380488.16     10632390.56      3380326.86     10632395.76
#Sta/Elev= 30
  3093.6   647.4  3160.5     644  3180.5  644.58  3220.7  640.39  3240.7  641.42
  3571.7  628.25  3732.2  625.52  3772.3  622.27    3993  619.65  4169.4  614.96
  4233.7  615.59  4253.7  613.98  4273.8  615.85  4299.4  614.52  4364.1   616.7
  4434.4  614.64  4999.1  608.66  5001.9  608.16  5005.1  608.66  5085.8  611.06
  5496.5  613.03  5686.8  618.53  5736.9     618    5807  621.22  5870.2  620.83
  5977.3  624.54  6041.8  624.08  6197.7  628.36  6307.9  628.17  6653.5  633.76
#Mann= 3 ,-1 , 0
  3093.6     .05       0  4999.1     .03       0  5005.1     .05       0
Bank Sta=4999.1,5005.1
XS Rating Curve= 0 ,0
Exp/Cntr=0.3,0.1

Type RM Length L Ch R = 1 ,17596   ,1215,1215,1215
BEGIN DESCRIPTION:
UNT00270 IN CHRS 17.0
END DESCRIPTION:
XS GIS Cut Line= 4
      3382795.46     10631869.73      3382258.99     10631749.94
      3381644.41     10631713.48      3379857.93     10631744.73
#Sta/Elev= 30
  4226.7  624.98  4330.1  625.12    4514  621.26  4629.7  618.01  4776.4  611.46
  4830.2   607.1  4890.5  604.68  4893.2  604.18  4896.5  604.68  5013.7  605.39
  5053.8   607.4    5204  607.01  5404.4  607.69  5614.4  606.87  5924.4  608.56
  6164.5  613.02  6234.5  613.25  6354.5  615.64  6444.5  615.18  6724.6  620.38
  6764.6  618.81  6904.6   622.9  6924.6  624.17  7024.6   625.8  7074.6  628.58
  7084.6  627.75  7114.6  628.82  7134.6  630.54  7154.6  629.88  7178.8  630.42
#Mann= 3 ,-1 , 0
  4226.7     .05       0  4890.5     .03       0  4896.5     .05       0
Bank Sta=4890.5,4896.5
XS Rating Curve= 0 ,0
Exp/Cntr=0.3,0.1

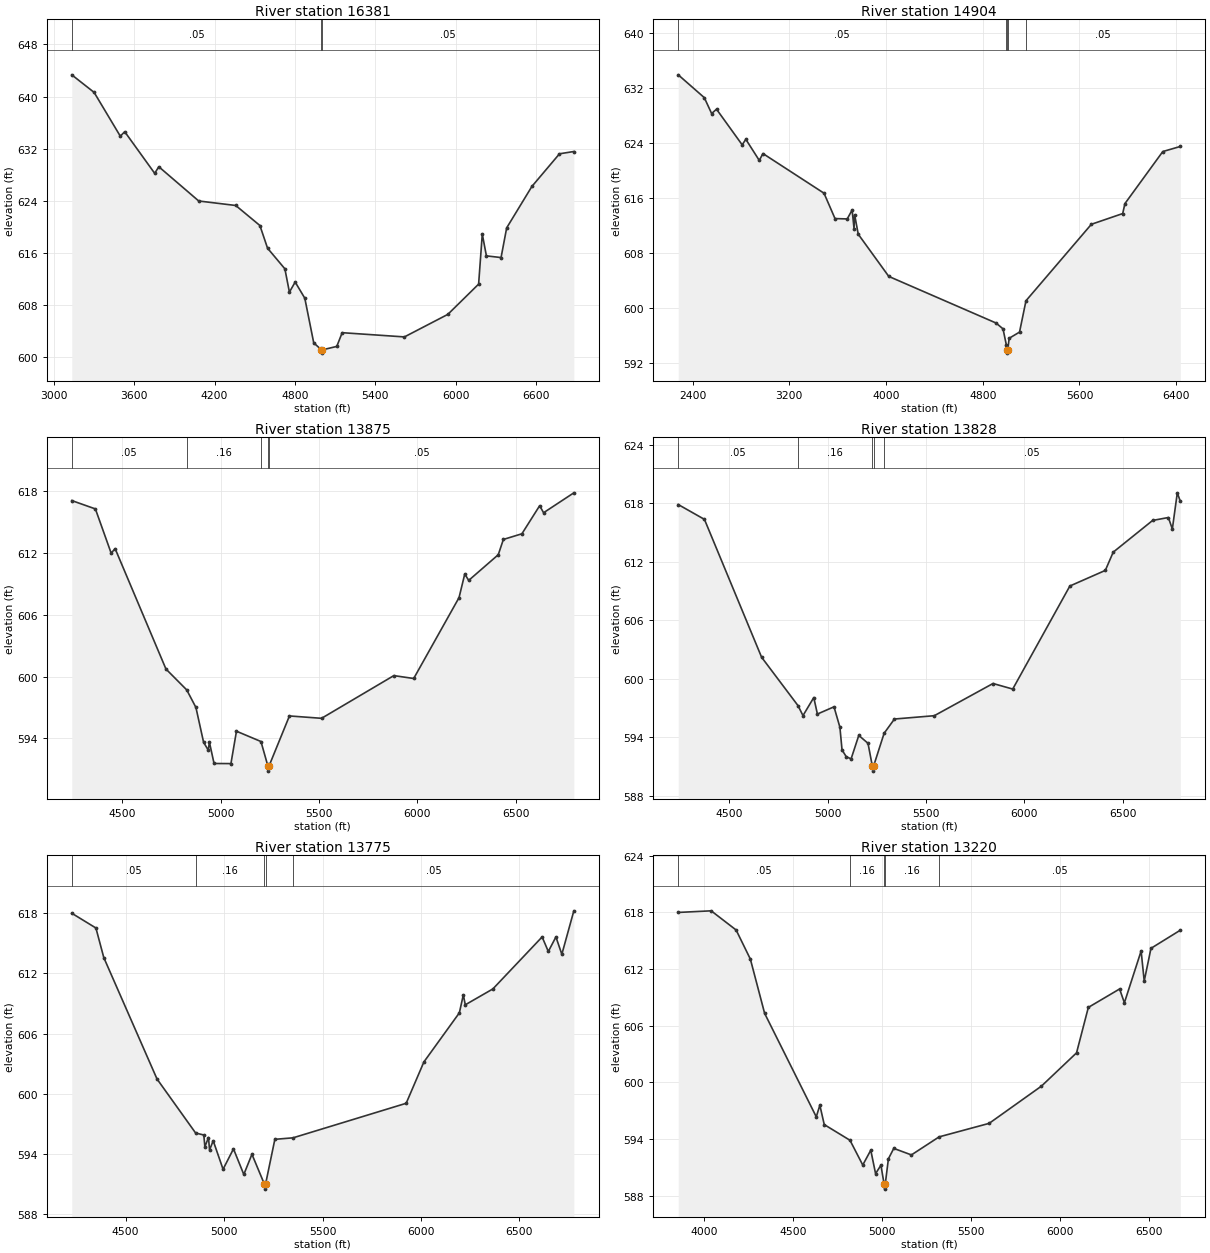
Type RM Length L Ch R = 1 ,16381   ,1477,1477,1477
BEGIN DESCRIPTION:
UNT00270 IN CHRS 15.0
END DESCRIPTION:
XS GIS Cut Line= 4
      3383774.57     10631275.97      3382258.99     10630921.81
      3381055.87     10631088.48        3380108.     10630859.32
#Sta/Elev= 30
  3134.9  643.33  3301.7  640.63  3496.9  633.91  3530.1  634.59  3753.6   628.2
  3784.4  629.21  4082.2  623.95  4358.4  623.26  4538.7  620.18  4595.7   616.7
    4725  613.53  4758.8  609.95  4801.8   611.5  4873.6  609.02  4940.3  602.16
  4998.1  601.08  5000.9  600.58  5004.1  601.08  5112.2  601.61  5152.6  603.72
    5617  603.07  5940.7  606.53  6170.6  611.18  6197.9  618.86  6228.7  615.52
    6338  615.26  6379.9  619.82  6568.2  626.19    6774   631.2  6881.1  631.55
#Mann= 3 ,-1 , 0
  3134.9     .05       0  4998.1     .03       0  5004.1     .05       0
Bank Sta=4998.1,5004.1
XS Rating Curve= 0 ,0
Exp/Cntr=0.3,0.1

Type RM Length L Ch R = 1 ,14904   ,1029,1029,1029
BEGIN DESCRIPTION:
UNT00270 IN CHRS 13.0
END DESCRIPTION:
XS GIS Cut Line= 4
      3383795.44     10630635.35      3381675.66     10630328.06
      3380915.24     10629848.89      3379842.31     10629557.22
#Sta/Elev= 30
  2281.7  633.92  2497.3   630.6  2557.9  628.29  2598.3  628.92  2810.5  623.74
  2840.8  624.54    2952  621.47  2982.3  622.47  3487.5   616.7  3578.4  613.01
  3679.5  612.96  3719.9  614.26  3735.8  611.56  3740.8  613.56  3770.4  610.74
    4023   604.6  4910.3  597.82  4967.9  596.97  4995.5  594.63  5001.4  593.94
  5004.2  593.44  5007.4  593.94  5018.8   595.6  5104.5   596.5  5157.9  601.06
  5698.7  612.18  5957.8  613.74  5976.2  615.19  6289.4  622.76  6434.3   623.5
#Mann= 5 ,-1 , 0
  2281.7     .05       0  4995.5     .16       0  5001.4     .07       0
  5007.4     .16       0  5157.9     .05       0
Bank Sta=5001.4,5007.4
XS Rating Curve= 0 ,0
Exp/Cntr=0.3,0.1

Type RM Length L Ch R = 1 ,13875   ,47,47,47
BEGIN DESCRIPTION:
UNT00270 IN CHRS 11.2
END DESCRIPTION:
XS GIS Cut Line= 6
      3382532.01     10629480.16      3381893.09     10629448.91
      3381768.09     10629410.71      3381702.11      10629424.6
      3381146.56     10629219.74      3380028.53     10629171.13
#Sta/Elev= 30
  4244.4  617.06  4364.4  616.25  4444.5  611.96  4464.6   612.4  4722.8  600.73
  4828.5   598.7  4875.1     597  4914.1  593.62  4937.9  592.86  4943.4  593.65
  4967.2  591.57  5052.9  591.56    5081   594.7  5205.5   593.7  5240.5  591.33
  5243.2  590.83  5246.5  591.33  5350.1  596.18  5513.3  595.95  5880.4  600.09
  5981.3  599.81  6211.6  607.65  6240.7  609.94  6260.7  609.32  6410.9  611.81
  6436.8  613.29    6531  613.84  6621.1  616.56  6641.1  615.88  6794.8  617.81
#Mann= 5 ,-1 , 0
  4244.4     .05       0  4828.5     .16       0  5205.5     .05       0
  5240.5     .07       0  5246.5     .05       0
Bank Sta=5240.5,5246.5
XS Rating Curve= 0 ,0
Exp/Cntr=0.3,0.1

Type RM Length L Ch R = 1 ,13828   ,53,53,53
BEGIN DESCRIPTION:
UNT00270 IN CHRS 11.1
END DESCRIPTION:
XS GIS Cut Line= 6
      3382525.08     10629435.02      3381886.14     10629403.77
      3381761.14     10629365.57      3381695.17     10629379.46
      3381139.61      10629174.6       3380021.6     10629125.99
#Sta/Elev= 30
  4241.4  617.87  4374.5  616.35  4664.9  602.22  4849.9  597.26  4875.1  596.24
  4929.9  598.09  4948.3   596.4  5032.6  597.14  5062.6  595.05  5073.5  592.72
  5094.5  592.04  5119.4   591.8  5158.5  594.21  5205.4   593.4  5227.5  591.05
  5230.3  590.55  5233.5  591.05  5287.2  594.43  5339.7  595.89  5542.2  596.23
  5840.4  599.53  5940.5  598.96  6230.8  609.52  6410.9  611.12    6451  612.99
  6651.2  616.24  6731.2  616.54  6751.3  615.36  6776.5  619.07  6791.8  618.21
#Mann= 5 ,-1 , 0
  4241.4     .05       0  4849.9     .16       0  5227.5     .07       0
  5233.5     .16       0  5287.2     .05       0
Bank Sta=5227.5,5233.5
XS Rating Curve= 0 ,0
Exp/Cntr=0.3,0.1

Type RM Length L Ch R = 1 ,13775   ,555,555,555
BEGIN DESCRIPTION:
UNT00270 IN CHRS 11.3
END DESCRIPTION:
XS GIS Cut Line= 6
      3382514.57     10629389.88      3381875.72     10629358.63
      3381750.72     10629320.43      3381684.75     10629334.32
       3381129.2     10629129.46      3380011.19     10629080.85
#Sta/Elev= 30
  4226.4  617.98    4349  616.51  4389.1  613.56  4659.4  601.47  4855.5  596.09
  4897.1  595.89  4902.5  594.72  4920.9  595.64  4926.3   594.4  4944.8  595.32
  4994.9  592.48  5047.8  594.51  5100.3  591.96  5141.6  593.97  5204.8     591
  5207.5   590.5  5210.8     591    5258  595.46  5350.3  595.61    5925  599.05
  6015.1  603.17  6195.2  608.06  6215.3  609.85  6225.3  608.86  6365.4  610.44
  6615.6  615.62    6647  614.17  6685.7  615.62  6715.7  613.89  6776.7  618.22
#Mann= 5 ,-1 , 0
  4226.4     .05       0  4855.5     .16       0  5204.8     .07       0
  5210.8     .16       0  5350.3     .05       0
Bank Sta=5204.8,5210.8
XS Rating Curve= 0 ,0
Exp/Cntr=0.3,0.1

Type RM Length L Ch R = 1 ,13220   ,380,380,380
BEGIN DESCRIPTION:
UNT00270 IN CHRS 11.4
END DESCRIPTION:
XS GIS Cut Line= 4
      3382727.05     10629164.29      3381925.66     10629114.52
      3381384.71     10628755.81      3380031.97     10628983.63
#Sta/Elev= 30
  3853.6  617.98  4038.9  618.15  4179.2  616.12  4259.3  613.04  4339.5   607.3
    4630  596.35  4650.1  597.58  4674.8  595.53  4819.6  593.87  4891.4  591.25
  4936.5  592.82  4963.5  590.34  4993.6  591.23  5011.7   589.2  5014.4   588.7
  5017.7   589.2  5035.7  591.91  5065.8  593.01    5165  592.32  5320.9  594.23
  5602.3  595.66  5896.4   599.6  6093.8  603.12  6160.1  607.93  6335.9  609.88
  6362.9  608.42    6457   613.9  6474.4  610.72  6512.4  614.18  6677.4   616.1
#Mann= 5 ,-1 , 0
  3853.6     .05       0  4819.6     .16       0  5011.7     .07       0
  5017.7     .16       0  5320.9     .05       0
Bank Sta=5011.7,5017.7
XS Rating Curve= 0 ,0
Exp/Cntr=0.3,0.1

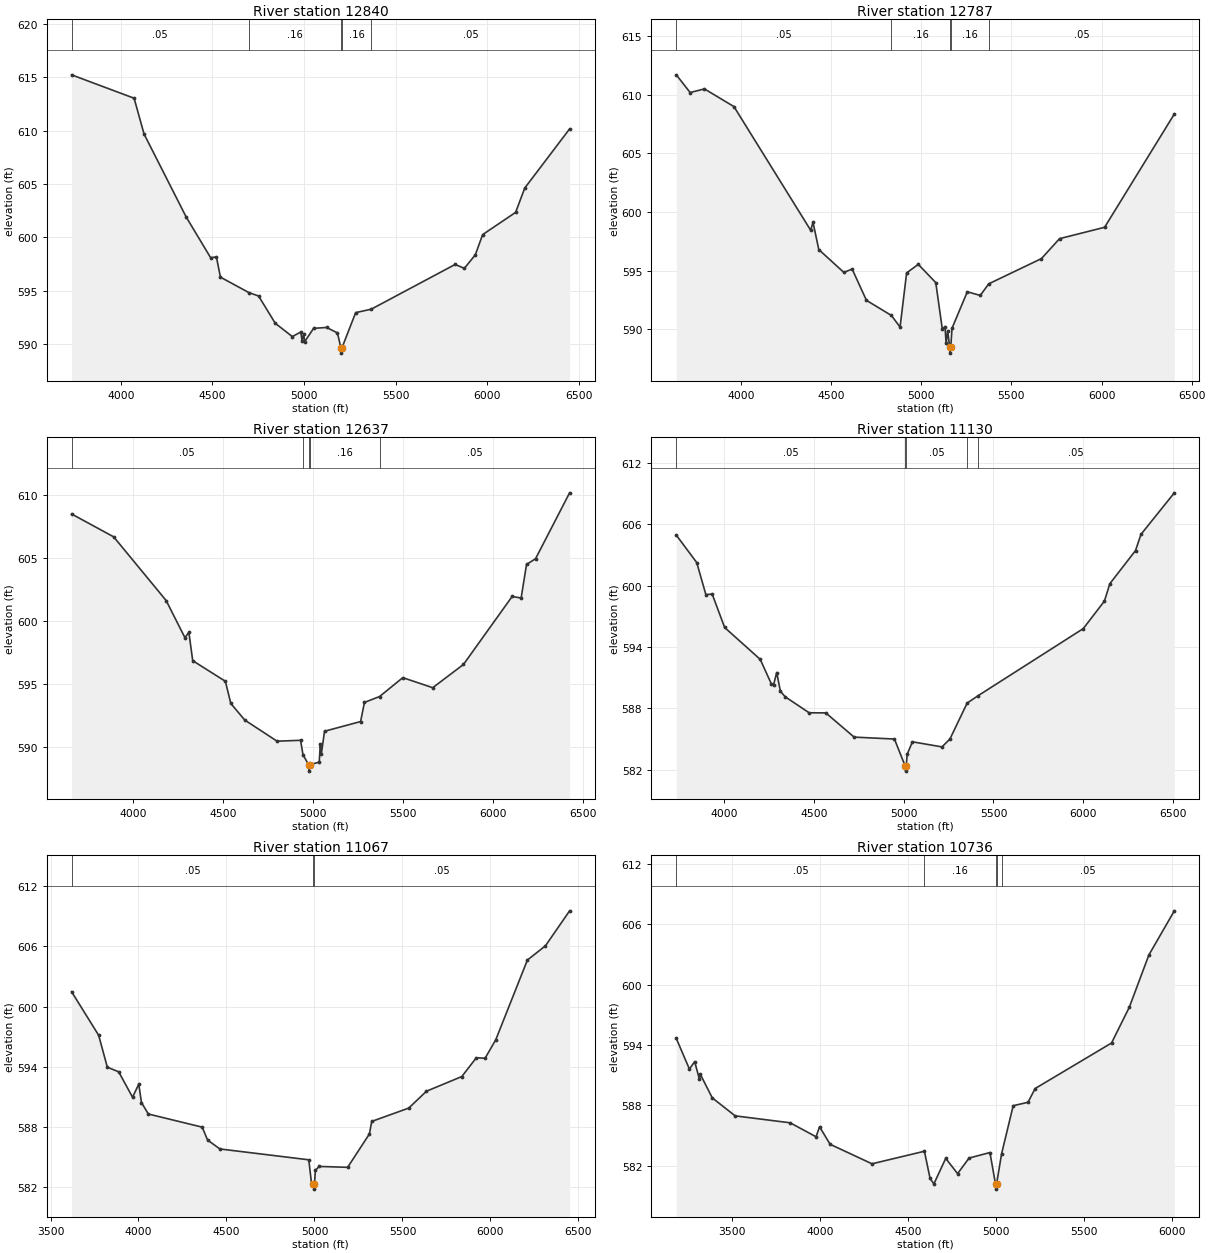
Type RM Length L Ch R = 1 ,12840   ,53,53,53
BEGIN DESCRIPTION:
UNT00270 IN CHRS 6.2
END DESCRIPTION:
XS GIS Cut Line= 6
      3382841.91     10629009.85      3381713.43     10628580.16
      3381620.12     10628647.44      3381513.78     10628617.06
      3381422.64     10628536.76      3380257.26     10628532.42
#Sta/Elev= 30
  3730.7  615.21  4072.3  613.02  4126.4  609.68  4357.2  601.89  4490.2   598.1
  4521.8  598.17  4543.7  596.28  4699.6  594.83  4751.9  594.52  4843.3  591.96
  4936.3  590.72  4983.2  591.15  4989.4   590.3    4998  590.93  5004.1  590.25
  5052.6  591.49  5123.9  591.57  5182.8  591.06  5201.6  589.67  5204.4  589.17
  5207.6  589.67  5282.3  592.96  5367.3  593.28  5825.8  597.47  5875.8   597.1
  5935.8  598.37  5975.9  600.26  6155.9  602.34  6205.9  604.62  6450.7  610.15
#Mann= 5 ,-1 , 0
  3730.7     .05       0  4699.6     .16       0  5201.6     .07       0
  5207.6     .16       0  5367.3     .05       0
Bank Sta=5201.6,5207.6
XS Rating Curve= 0 ,0
Exp/Cntr=0.3,0.1

Type RM Length L Ch R = 1 ,12787   ,150,150,150
BEGIN DESCRIPTION:
UNT00270 IN CHRS 6.5
END DESCRIPTION:
XS GIS Cut Line= 6
        3382881.     10628873.14      3381850.15     10628480.34
      3381674.37     10628493.36       3381585.4     10628595.35
      3380999.46      10628417.4      3380285.22     10628430.39
#Sta/Elev= 30
  3640.5  611.69  3717.3  610.18  3796.8  610.49  3960.4  608.98    4386  598.44
  4399.1  599.11  4431.2  596.79  4570.3  594.84  4616.1  595.13  4695.6  592.46
  4834.2  591.17  4882.1  590.18  4918.5   594.8  4983.2  595.53  5080.3  593.97
  5116.6     590  5131.5  590.22  5137.6  588.79  5146.4  589.86  5157.4  588.46
  5160.1  587.96  5163.4  588.46  5170.4  590.08  5255.2  593.19  5327.1  592.88
  5374.2  593.87  5666.6  596.02    5767  597.72  6017.1  598.69    6404  608.35
#Mann= 5 ,-1 , 0
  3640.5     .05       0  4834.2     .16       0  5157.4     .07       0
  5163.4     .16       0  5374.2     .05       0
Bank Sta=5157.4,5163.4
XS Rating Curve= 0 ,0
Exp/Cntr=0.3,0.1

Type RM Length L Ch R = 1 ,12637   ,1507,1507,1507
BEGIN DESCRIPTION:
UNT00270 IN CHRS 6.6
END DESCRIPTION:
XS GIS Cut Line= 6
      3382800.72     10628762.47      3381769.86     10628369.66
      3381594.08     10628382.68       3381505.1     10628484.68
      3380919.16     10628306.73      3380203.04     10628319.75
#Sta/Elev= 30
  3657.8   608.5  3891.7  606.68  4182.9  601.62  4287.2  598.67  4309.1  599.09
  4330.5  596.84  4511.9   595.2    4542  593.44  4619.4  592.12  4798.8  590.44
  4929.2  590.51  4942.8  589.37  4974.3  588.56    4977  588.06  4980.3  588.56
  5032.9  588.78  5039.1   590.2  5044.6  589.41  5062.4  591.23  5262.7     592
    5284  593.52  5368.1  593.99  5497.1  595.49  5663.2  594.69    5834  596.54
  6104.1  601.94  6154.1  601.82  6184.1  604.49  6234.1  604.94  6423.2  610.18
#Mann= 5 ,-1 , 0
  3657.8     .05       0  4942.8     .16       0  4974.3     .07       0
  4980.3     .16       0  5368.1     .05       0
Bank Sta=4974.3,4980.3
XS Rating Curve= 0 ,0
Exp/Cntr=0.3,0.1

Type RM Length L Ch R = 1 ,11130   ,63,63,63
BEGIN DESCRIPTION:
UNT00270 IN CHRS 9.0
END DESCRIPTION:
XS GIS Cut Line= 5
      3382534.69     10626857.26      3381555.52     10627003.09
      3381284.69     10627362.46      3381112.81     10627690.59
      3380170.06     10627872.89
#Sta/Elev= 30
  3735.7  604.95  3849.5  602.26  3900.1  599.13  3935.3  599.18  4004.6  595.91
  4202.5  592.79    4264  590.41  4276.9  590.31  4294.4   591.5  4314.6  589.68
  4341.2  589.13  4474.8  587.56  4567.4  587.55  4724.9  585.18  4949.2  584.99
  5008.9  582.35  5011.6  581.85  5014.9  582.35  5020.1   583.5  5049.2  584.72
  5213.9  584.22    5258     585  5353.7  588.51  5413.5  589.22  5999.7   595.8
  6117.2  598.49  6147.7   600.2  6290.3  603.44  6320.9  605.03  6506.3  609.09
#Mann= 5 ,-1 , 0
  3735.7     .05       0  5008.9     .03       0  5014.9     .05       0
  5353.7     .16       0  5413.5     .05       0
Bank Sta=5008.9,5014.9
XS Rating Curve= 0 ,0
Exp/Cntr=0.3,0.1

Type RM Length L Ch R = 1 ,11067   ,331,331,331
BEGIN DESCRIPTION:
UNT00270 IN CHRS 8.0
END DESCRIPTION:
XS GIS Cut Line= 4
      3382503.42     10626701.01      3381519.06     10626872.88
       3381170.1     10627487.46      3380056.28      10627638.4
#Sta/Elev= 30
  3619.7  601.49  3773.6  597.15  3822.9  593.97  3887.5  593.51  3966.2  590.98
  4001.5  592.28  4016.9  590.45  4055.9  589.31  4362.1     588  4392.5  586.72
  4462.5  585.83  4967.7  584.75  4983.6  582.34    4994  582.33  4996.8  581.83
    5000  582.33  5005.2  583.71  5026.9  584.09  5188.4     584  5312.4  587.33
  5325.2  588.57  5535.6   589.9  5636.5  591.58  5837.1  593.04  5919.7  594.91
  5969.5  594.86  6030.1   596.7  6209.9  604.64  6312.6  606.06  6449.7  609.54
#Mann= 3 ,-1 , 0
  3619.7     .05       0    4994     .04       0    5000     .05       0
Bank Sta=4994,5000
XS Rating Curve= 0 ,0
Exp/Cntr=0.3,0.1

Type RM Length L Ch R = 1 ,10736   ,78,78,78
BEGIN DESCRIPTION:
UNT00270 IN CHRS 7.0
END DESCRIPTION:
XS GIS Cut Line= 4
      3382456.52     10626461.42      3381524.27     10626497.88
       3381045.1     10627357.26      3380138.86     10627492.67
#Sta/Elev= 30
    3181  594.66  3255.5  591.62  3285.5  592.35  3312.5  590.61  3317.5   591.1
  3385.6  588.75  3515.7  586.96  3828.6  586.27    3976  584.88    3996  585.87
  4056.1  584.13  4294.3  582.19  4592.4  583.44  4624.6  580.74  4646.3  580.19
  4713.6  582.73  4781.2  581.21  4846.3  582.76  4965.2  583.31  4996.9  580.17
  4999.6  579.67  5002.9  580.17  5031.4  583.18  5097.5  587.97  5181.8  588.31
  5222.3  589.68    5657  594.21  5758.1  597.77  5869.4  602.97  6014.2  607.36
#Mann= 5 ,-1 , 0
    3181     .05       0  4592.4     .16       0  4996.9     .07       0
  5002.9     .16       0  5031.4     .05       0
Bank Sta=4996.9,5002.9
XS Rating Curve= 0 ,0
Exp/Cntr=0.3,0.1

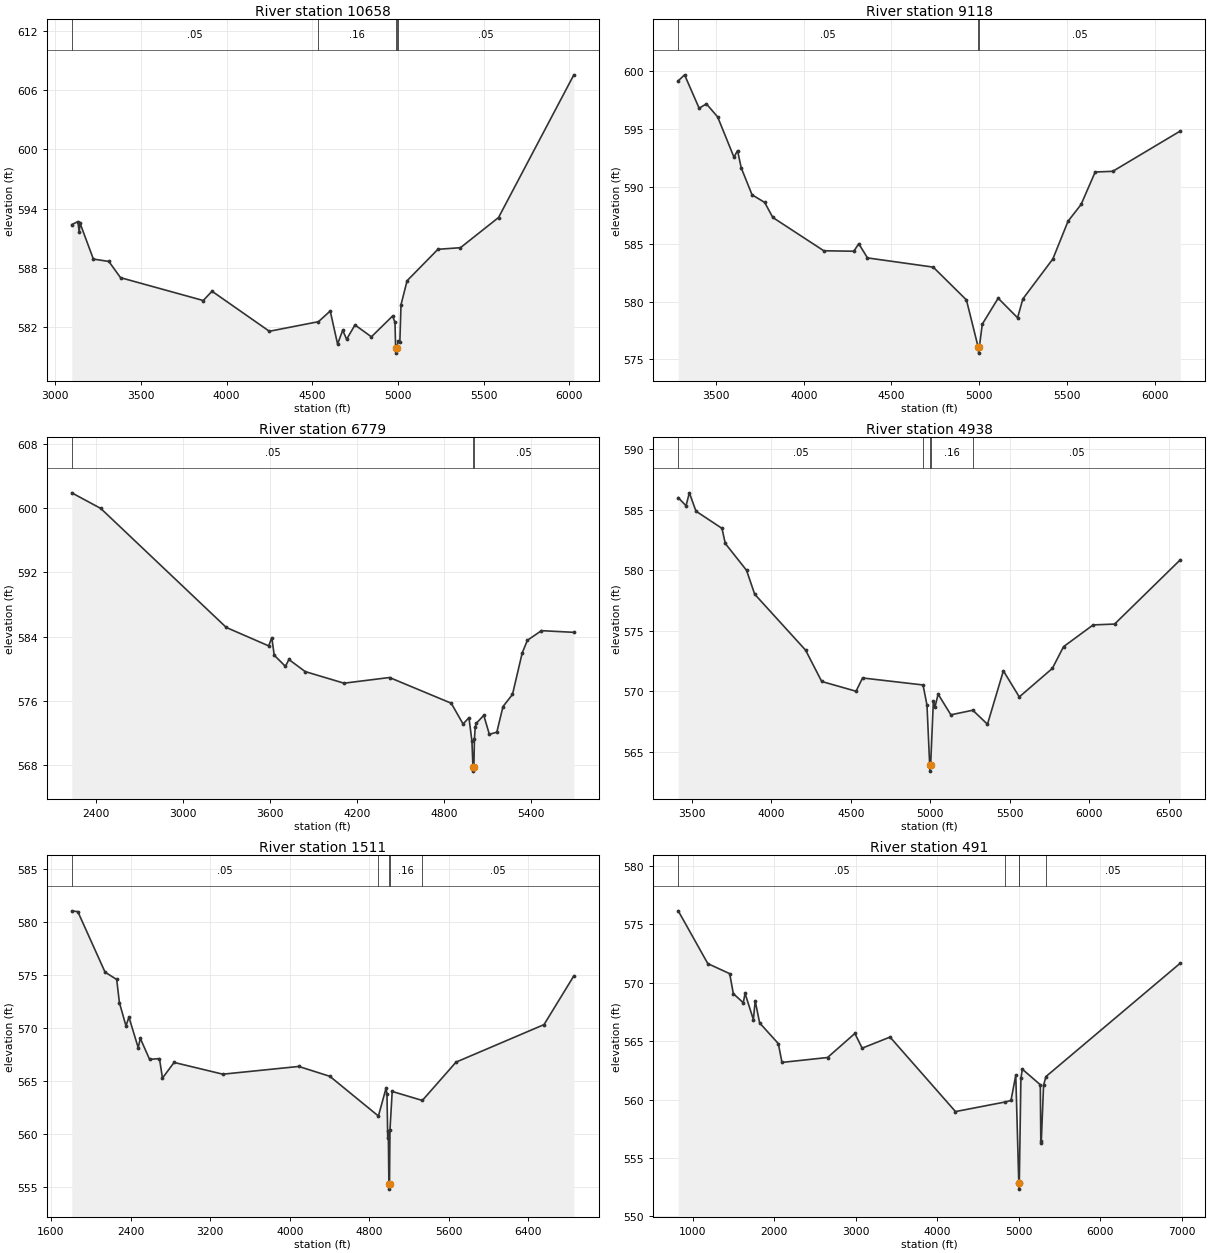
Type RM Length L Ch R = 1 ,10658   ,1540,1540,1540
BEGIN DESCRIPTION:
UNT00270 IN CHRS 6.0
END DESCRIPTION:
XS GIS Cut Line= 6
      3382487.81     10626372.88       3381420.1     10626461.42
      3381368.02     10626716.63       3381107.6     10627159.34
      3380993.02     10627284.34      3380086.96     10627414.52
#Sta/Elev= 30
  3096.8   592.4  3132.6   592.7    3140  591.66    3145  592.54  3222.9  588.91
  3313.2  588.67  3381.4  587.03  3864.2  584.72  3915.3  585.66    4250  581.61
  4536.6  582.58  4605.3  583.66  4648.2  580.32  4678.1  581.71    4701   580.8
  4749.8  582.25  4845.5  581.05  4969.2  583.15  4983.3  582.51  4987.1   579.9
  4989.9   579.4  4993.1   579.9  5002.2  580.58  5011.7  580.56  5018.5   584.3
  5053.9  586.72    5234   589.9  5365.3  590.06  5587.6  593.11  6027.2  607.54
#Mann= 5 ,-1 , 0
  3096.8     .05       0  4536.6     .16       0  4987.1     .07       0
  4993.1     .16       0  5002.2     .05       0
Bank Sta=4987.1,4993.1
XS Rating Curve= 0 ,0
Exp/Cntr=0.3,0.1

Type RM Length L Ch R = 1 ,9118    ,2339,2339,2339
BEGIN DESCRIPTION:
UNT00270 IN CHRS 5.0
END DESCRIPTION:
XS GIS Cut Line= 4
      3382850.17     10626395.78      3381443.89     10626048.55
      3380515.07     10625961.74      3380037.66      10625979.1
#Sta/Elev= 30
  3285.6  599.19  3321.7  599.71  3404.6  596.81  3446.1  597.19  3510.2  596.05
  3602.9  592.56  3623.5  593.13  3644.1  591.64  3705.9  589.29  3777.7  588.63
  3824.3  587.32  4114.5  584.43  4285.5  584.39  4313.6  585.04  4363.3  583.81
  4737.5  583.01  4926.7  580.16    4994  576.04  4996.8  575.54    5000  576.04
  5017.1  578.06  5107.5  580.31    5218  578.61  5248.1  580.25  5418.9  583.72
  5505.5     587  5579.6  588.45  5659.9  591.27    5760  591.33  6144.7  594.83
#Mann= 3 ,-1 , 0
  3285.6     .05       0    4994     .03       0    5000     .05       0
Bank Sta=4994,5000
XS Rating Curve= 0 ,0
Exp/Cntr=0.3,0.1

Type RM Length L Ch R = 1 ,6779    ,1841,1841,1841
BEGIN DESCRIPTION:
UNT00270 IN CHRS 3.0
END DESCRIPTION:
XS GIS Cut Line= 3
       3383726.9     10625727.38      3381580.36      10624844.6
      3380463.02     10624624.94
#Sta/Elev= 30
  2234.7  601.94  2434.5  599.99  3299.5  585.13  3591.5  582.83  3613.1  583.86
  3629.7  581.67    3707  580.27  3730.9  581.13    3843  579.62  4110.5  578.17
  4424.2  578.88  4849.4  575.67    4931  573.08  4971.7  573.86  4992.1  570.94
  4999.3  567.69  5002.1  567.19  5005.3  567.69  5009.5  571.25  5014.6  572.67
  5022.7  573.17  5073.7  574.16  5112.3  571.78  5163.7  572.06  5206.1  575.25
  5271.6  576.77  5338.6  581.95  5374.4  583.53  5471.1  584.73  5694.4  584.52
#Mann= 3 ,-1 , 0
  2234.7     .05       0  4999.3    .035       0  5005.3     .05       0
Bank Sta=4999.3,5005.3
XS Rating Curve= 0 ,0
Exp/Cntr=0.3,0.1

Type RM Length L Ch R = 1 ,4938    ,3427,3427,3427
BEGIN DESCRIPTION:
UNT00270 IN CHRS 2.0
END DESCRIPTION:
XS GIS Cut Line= 4
      3383179.98      10623791.6      3381869.24      10623479.1
      3380948.68      10623519.7       3380400.9     10624220.36
#Sta/Elev= 30
  3414.8  586.01    3464  585.34  3484.6  586.41  3526.6  584.89    3690  583.47
  3710.7  582.22  3844.4     580  3895.8  578.02    4216  573.39  4317.3   570.8
  4533.2  569.99  4574.3  571.09  4954.7  570.51  4979.6  568.84  4996.6  563.88
  4999.4  563.38  5002.6  563.88  5019.7  569.18  5029.7  568.68  5049.7  569.75
  5129.8  568.04  5267.7  568.42    5360  567.26  5460.1  571.68  5560.2  569.52
  5768.1  571.88  5838.6  573.68  6024.9  575.48  6159.7  575.55  6573.1  580.87
#Mann= 5 ,-1 , 0
  3414.8     .05       0  4954.7     .16       0  4996.6     .07       0
  5002.6     .16       0  5267.7     .05       0
Bank Sta=4996.6,5002.6
XS Rating Curve= 0 ,0
Exp/Cntr=0.3,0.1

Type RM Length L Ch R = 1 ,1511    ,1020,1020,1020
BEGIN DESCRIPTION:
UNT00270 IN CHRS 1.0
END DESCRIPTION:
XS GIS Cut Line= 4
      3383000.56     10623448.69      3380656.85     10621886.22
      3380344.35      10622519.9      3380131.94     10624028.49
#Sta/Elev= 30
  1809.1  581.07  1870.1  580.99  2143.8  575.28  2260.7  574.59    2288   572.4
  2353.9  570.21  2383.9  571.03    2477  568.15  2498.1  569.03  2591.2  567.05
  2690.6  567.12  2720.7  565.28  2837.6  566.76  3327.4  565.65  4090.8  566.38
    4403  565.45  4891.4   561.7  4968.2  564.33  4977.6  563.75  4985.1  559.62
  4990.7  560.31  4996.9   555.3  4999.6   554.8  5002.9   555.3  5007.6  560.39
    5030  564.02    5333  563.17  5671.9  566.79  6556.1  570.33  6855.9  574.93
#Mann= 5 ,-1 , 0
  1809.1     .05       0  4891.4     .16       0  4996.9     .07       0
  5002.9     .16       0    5333     .05       0
Bank Sta=4996.9,5002.9
XS Rating Curve= 0 ,0
Exp/Cntr=0.3,0.1

Type RM Length L Ch R = 1 ,491     ,0,0,0
BEGIN DESCRIPTION:
UNT00270 IN CHRS 1.9
END DESCRIPTION:
XS GIS Cut Line= 5
      3383456.79     10623035.54      3380409.89     10621512.09
      3379884.72     10621755.14      3379819.61     10622558.09
      3379858.63     10623928.12
#Sta/Elev= 30
   821.1  576.16  1184.1  571.64  1452.4  570.78  1497.2  569.07  1619.1  568.29
  1641.4  569.09  1743.1  566.85  1765.5  568.45  1820.3  566.56  2049.5  564.79
  2094.2  563.18  2653.3   563.6  2988.7  565.66  3078.1   564.4  3420.2  565.35
  4223.6  558.97  4831.5  559.79  4904.3  559.92  4963.3  562.08  5000.5  552.83
  5003.2  552.33  5006.5  552.83  5026.4  561.81  5043.6   562.6  5264.3  561.27
  5270.5  556.46  5275.5  556.25  5304.5  561.23  5333.7  561.97  6982.5  571.68
#Mann= 5 ,-1 , 0
   821.1     .05       0  4831.5     .16       0  5000.5     .07       0
  5006.5     .16       0  5333.7     .05       0
Bank Sta=5000.5,5006.5
XS Rating Curve= 0 ,0
Exp/Cntr=0.3,0.1

Chan Stop Cuts=-1
Use User Specified Reach Order=0
Composite Channel Slope=5