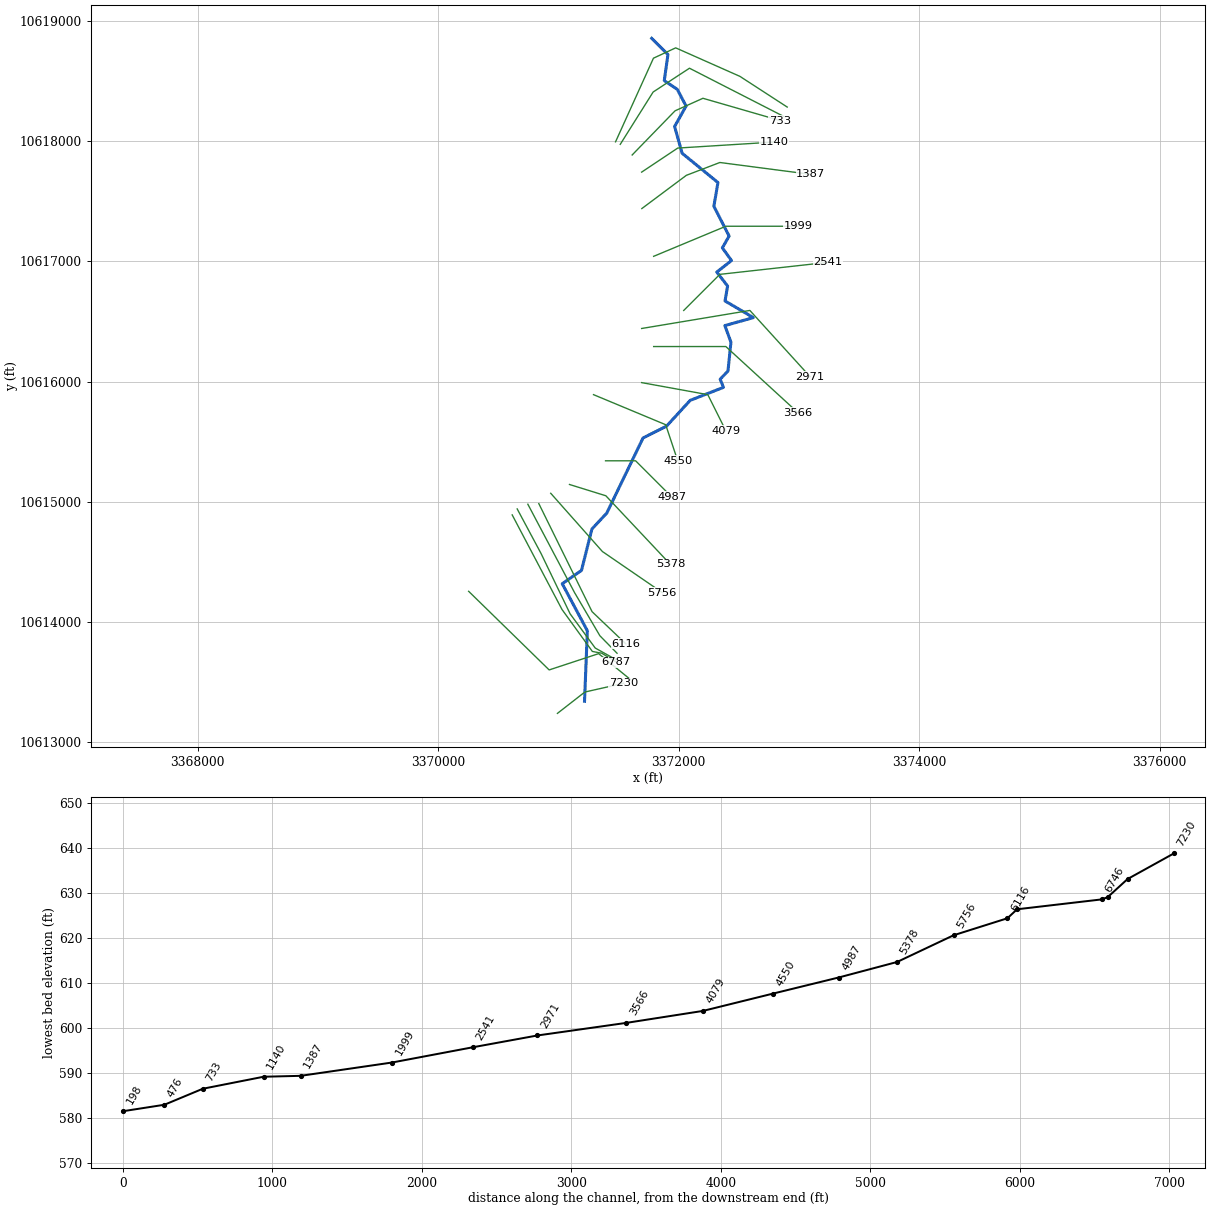
--- UNT00277 IN CHRS.prj (project) ---

Proj Title=UNT00277 IN CHRS Base Level Engineering
Current Plan=p01
Default Exp/Contr=0.3,0.1
English Units
Geom File=g01
Flow File=f01
Plan File=p01
Y Axis Title=Elevation
X Axis Title(PF)=Main Channel Distance
X Axis Title(XS)=Station
BEGIN DESCRIPTION:
UNT00277 IN CHRS
END DESCRIPTION:
DSS Export Rating Curves= 0
DSS Export Rating Curve Sorted= 0
DSS Export Volume Flow Curves= 0
DXF OffsetX= 0
DXF OffsetY= 0
DXF ScaleX= 1
DXF ScaleY= 10

--- UNT00277 IN CHRS.p01 (plan) ---

Plan Title=Multiple Run
Short Identifier=Multiple
Geom File=g01
Flow File=f01
Subcritical Flow
K Sum by GR= 0
Std Step Tol= 0.01
Critical Tol= 0.01
Num of Std Step Trials= 20
Max Error Tol= 0.3
Flow Tol Ratio= 0.001
Split Flow NTrial= 30
Split Flow Tol= 0.02
Split Flow Ratio= 0.02
Log Output Level= 0
Friction Slope Method= 1
Unsteady Friction Slope Method= 2
Unsteady Bridges Friction Slope Method= 1
Parabolic Critical Depth
Global Vel Dist=  1 , 1 , 1
Global Log Level= 0
CheckData=True
Encroach Param= -1, 0, 0, 0
BEGIN DESCRIPTION:
Multiple Run
END DESCRIPTION:

--- UNT00277 IN CHRS.f01 (steady flow) ---

Flow Title=Multiple
Program Version=4.10
Number of Profiles= 7
Profile Names=10-year,25-year,50-year,1pct_min,100-year,1pct_plu,500-year
River Rch & RM=UNT00277 IN CHRS,Reach-1         ,7230
     214     261     295     243     328     444     406
Boundary for River Rch & Prof#=UNT00277 IN CHRS,Reach-1         , 1
Up Type= 0
Dn Type= 3
Dn Slope=0.005
Boundary for River Rch & Prof#=UNT00277 IN CHRS,Reach-1         , 2
Up Type= 0
Dn Type= 3
Dn Slope=0.005
Boundary for River Rch & Prof#=UNT00277 IN CHRS,Reach-1         , 3
Up Type= 0
Dn Type= 3
Dn Slope=0.005
Boundary for River Rch & Prof#=UNT00277 IN CHRS,Reach-1         , 4
Up Type= 0
Dn Type= 3
Dn Slope=0.005
Boundary for River Rch & Prof#=UNT00277 IN CHRS,Reach-1         , 5
Up Type= 0
Dn Type= 3
Dn Slope=0.005
Boundary for River Rch & Prof#=UNT00277 IN CHRS,Reach-1         , 6
Up Type= 0
Dn Type= 3
Dn Slope=0.005
Boundary for River Rch & Prof#=UNT00277 IN CHRS,Reach-1         , 7
Up Type= 0
Dn Type= 3
Dn Slope=0.005
DSS Import GetInterval= 0
DSS Import GetPeak= 0
DSS Import FillOption= 0

--- UNT00277 IN CHRS.g01 (geometry) ---

Geom Title=Existing Conditions
Program Version=4.10

River Reach=UNT00277 IN CHRS,Reach-1
Reach XY= 30
      3371217.31     10613342.13      3371240.84     10613928.78
        3371032.     10614319.59      3371192.16     10614430.27
      3371278.72     10614774.53      3371402.24     10614906.71
      3371704.11     10615531.74      3371898.67     10615629.21
      3372095.73     10615843.98        3372372.     10615951.91
      3372345.18     10616020.48      3372409.94     10616087.46
      3372434.73     10616327.56       3372384.2     10616465.68
      3372621.26     10616532.06      3372385.58     10616670.39
      3372406.82     10616794.86       3372316.9     10616910.61
      3372439.36     10617006.42      3372363.31     10617112.26
      3372419.57     10617210.05      3372292.69     10617457.75
      3372326.82     10617654.97      3372028.68     10617898.75
      3371966.33     10618121.06      3372061.86     10618290.91
      3371988.69     10618429.83      3371880.36     10618502.74
      3371910.92     10618719.41      3371776.07     10618854.02

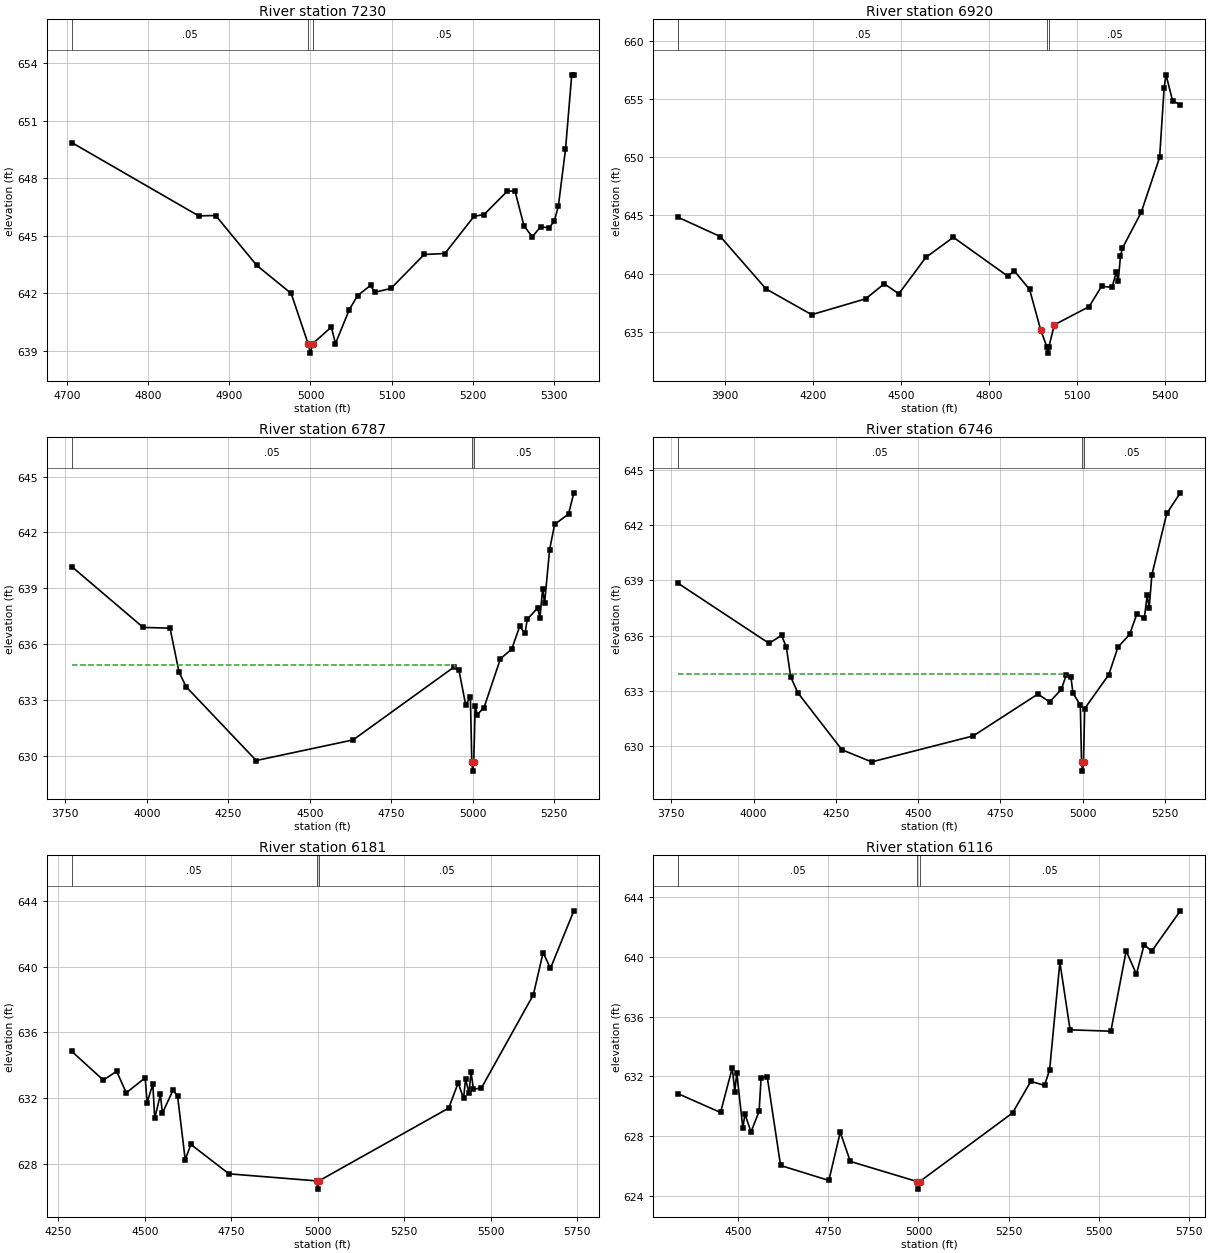
Type RM Length L Ch R = 1 ,7230    ,310,310,310
BEGIN DESCRIPTION:
UNT00277 IN CHRS 15.0
END DESCRIPTION:
XS GIS Cut Line= 3
      3370992.11     10613241.64        3371220.     10613419.04
      3371542.12     10613491.65
#Sta/Elev= 30
  4705.7  649.86  4862.2  646.04  4883.1  646.06  4933.8  643.46  4976.2     642
    4997  639.39  4999.8  638.89    5003  639.39  5025.7  640.25  5030.8  639.39
  5047.9  641.16  5058.2  641.89    5074  642.42  5079.2  642.06  5099.2  642.26
  5140.2  644.03  5165.7  644.08  5201.7  646.02    5214  646.11  5242.7  647.33
  5252.1  647.34  5263.2  645.53  5273.4  644.95  5283.7  645.47  5293.9  645.42
  5300.5  645.75  5305.6  646.55  5314.4   649.5  5322.1  653.39  5324.7  653.39
#Mann= 3 ,-1 , 0
  4705.7     .05       0    4997    .035       0    5003     .05       0
Bank Sta=4997,5003
XS Rating Curve= 0 ,0
Exp/Cntr=0.3,0.1

Type RM Length L Ch R = 1 ,6920    ,133,133,133
BEGIN DESCRIPTION:
UNT00277 IN CHRS 14.0
END DESCRIPTION:
XS GIS Cut Line= 4
      3370253.94     10614256.53      3370923.22     10613602.87
      3371334.68     10613738.29      3371600.27     10613522.17
#Sta/Elev= 30
  3740.2  644.84  3883.8  643.19  4039.4   638.7    4195  636.49  4378.9  637.85
  4442.4  639.14    4492  638.28  4583.9   641.4  4677.8  643.13    4864  639.78
  4885.1  640.26  4937.7  638.65  4975.1  635.21    4997  633.69  4999.8  633.19
    5003  633.69    5022  635.62  5140.5  637.18  5182.9  638.92  5218.8  638.84
  5233.1  640.14  5239.6  639.35  5247.4  641.53    5254   642.2  5317.9  645.26
  5380.8  649.99  5396.2  655.98  5402.6  657.07  5424.9  654.85  5451.3  654.49
#Mann= 3 ,-1 , 0
  3740.2     .05       0    4997    .035       0    5003     .05       0
Bank Sta=4975.1,5022
XS Rating Curve= 0 ,0
Exp/Cntr=0.3,0.1

Type RM Length L Ch R = 1 ,6787    ,41,41,41
BEGIN DESCRIPTION:
UNT00277 IN CHRS 13.1
END DESCRIPTION:
XS GIS Cut Line= 5
      3370615.93     10614891.95      3371029.99     10614105.48
       3371282.6     10613756.52      3371360.51     10613741.87
      3371480.93      10613668.1
#Sta/Elev= 30
  3769.9  640.16  3988.9  636.89  4071.3  636.85    4099  634.48  4121.1  633.69
  4335.7  629.73  4632.9  630.84  4942.5  634.76  4957.2  634.62    4978  632.74
  4992.7  633.13    4997  629.66  4999.8  629.16    5003  629.66  5007.4  632.69
  5013.6   632.2  5034.5  632.58  5084.7   635.2  5119.5  635.73    5144  636.95
  5160.2  636.57    5167  637.32    5199  637.94  5205.8  637.41  5214.4  638.96
  5220.2  638.19  5235.7  641.08  5251.1  642.43  5293.7  642.99    5310  644.13
#Mann= 3 ,-1 , 0
  3769.9     .05       0    4997    .035       0    5003     .05       0
#XS Ineff= 2 , 0
         4945.81  634.88
Permanent Ineff=
       F       F
Bank Sta=4997,5003
XS Rating Curve= 0 ,0
Exp/Cntr=0.3,0.1

Type RM Length L Ch R = 1 ,6746    ,565,565,565
BEGIN DESCRIPTION:
UNT00277 IN CHRS 13.0
END DESCRIPTION:
XS GIS Cut Line= 5
      3370657.61      10614941.4      3370855.52     10614571.62
       3371097.7     10614069.02      3371306.04     10613785.16
      3371477.51     10613689.04
#Sta/Elev= 30
  3771.2  638.84  4047.2  635.59  4085.4  636.02  4099.8  635.38    4113  633.77
    4135   632.9  4268.6  629.82  4359.1  629.16  4667.9  630.57  4864.5  632.84
    4900  632.41  4935.5  633.09  4950.1  633.85  4964.8  633.75    4971  632.88
  4993.3  632.25    4997  629.16  4999.8  628.66    5003  629.16  5006.5  632.05
  5079.8  633.89  5107.6  635.38  5143.1  636.07  5164.9  637.17  5187.8  636.96
  5196.7  638.21  5202.4  637.48  5210.8  639.31    5256  642.63  5297.2  643.75
#Mann= 3 ,-1 , 0
  3771.2     .05       0    4997    .035       0    5003     .05       0
#XS Ineff= 2 , 0
         4949.53  633.95
Permanent Ineff=
       F       F
Bank Sta=4997,5003
XS Rating Curve= 0 ,0
Exp/Cntr=0.3,0.1

Type RM Length L Ch R = 1 ,6181    ,65,65,65
BEGIN DESCRIPTION:
UNT00277 IN CHRS 13.2
END DESCRIPTION:
XS GIS Cut Line= 4
      3370746.14     10614980.59      3371134.16     10614246.21
       3371345.1     10613886.84      3371487.69     10613741.65
#Sta/Elev= 30
    4289  634.85  4380.3   633.1  4418.7  633.64  4446.4  632.33  4501.1  633.24
  4506.7  631.73  4523.1  632.86  4528.8  630.77  4545.1  632.23  4550.8  631.09
  4581.9   632.5  4594.8  632.12  4616.8  628.26  4633.2  629.19  4743.2   627.4
    4997  626.97  4999.8  626.47    5003  626.97  5378.2   631.4  5405.5  632.93
  5421.2  631.99  5426.9  633.17  5436.8  632.32  5442.6   633.6  5449.6  632.55
  5472.7  632.62  5622.7  638.29    5651  640.86  5672.2   639.9  5739.8   643.4
#Mann= 3 ,-1 , 0
    4289     .05       0    4997     .04       0    5003     .05       0
Bank Sta=4997,5003
XS Rating Curve= 0 ,0
Exp/Cntr=0.3,0.1

Type RM Length L Ch R = 1 ,6116    ,360,360,360
BEGIN DESCRIPTION:
UNT00277 IN CHRS 13.3
END DESCRIPTION:
XS GIS Cut Line= 3
      3370837.28     10614985.82      3371279.99     10614087.36
      3371561.27      10613819.1
#Sta/Elev= 30
  4334.7  630.84  4451.9  629.59  4484.3  632.57  4491.3  630.99  4496.8  632.23
  4513.7  628.53  4519.3  629.49  4536.2  628.29  4558.6  629.66  4564.2  631.92
  4581.1  631.97  4618.1  626.05  4751.8  625.05  4783.3  628.27  4811.3  626.32
    4997  624.97  4999.8  624.47    5003  624.97  5260.5  629.56    5311  631.67
    5349   631.4  5363.1  632.44  5391.5  639.63  5419.8  635.11  5532.7  635.02
  5575.1  640.38  5603.4  638.83  5624.8  640.79  5645.9  640.37    5725  643.06
#Mann= 3 ,-1 , 0
  4334.7     .05       0    4997     .04       0    5003     .05       0
Bank Sta=4997,5003
XS Rating Curve= 0 ,0
Exp/Cntr=0.3,0.1

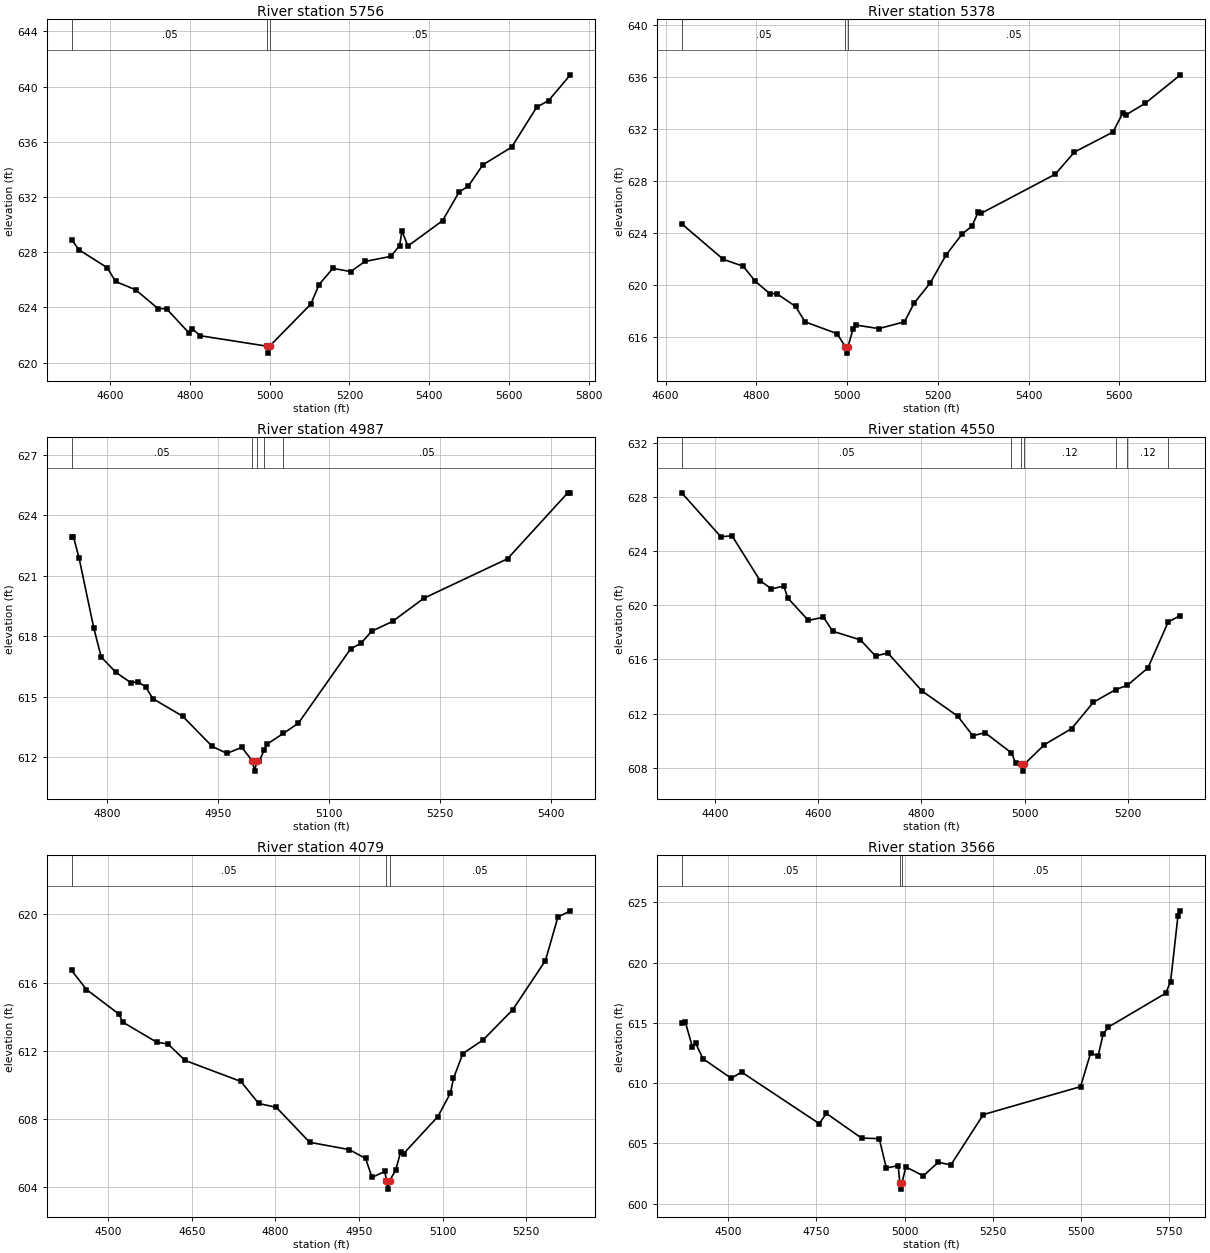
Type RM Length L Ch R = 1 ,5756    ,378,378,378
BEGIN DESCRIPTION:
UNT00277 IN CHRS 12.0
END DESCRIPTION:
XS GIS Cut Line= 3
      3370936.28      10615071.7      3371365.93     10614587.36
        3371863.     10614246.43
#Sta/Elev= 30
  4503.5  628.92  4521.7  628.18  4592.8  626.88  4613.7  625.88  4663.9  625.28
  4719.9  623.92  4741.7   623.9  4797.7  622.15  4805.2  622.47  4826.1  621.95
  4993.8  621.19  4996.5  620.69  4999.8  621.19    5103  624.24  5123.9  625.66
  5158.4  626.83  5203.1   626.6  5238.9  627.33  5303.9   627.7  5325.6  628.48
  5331.6  629.53  5346.5  628.45  5433.2  630.28  5475.1  632.37    5498  632.79
  5534.3  634.33  5606.5  635.61  5669.4  638.51  5699.2  638.99  5753.7  640.85
#Mann= 3 ,-1 , 0
  4503.5     .05       0  4993.8    .035       0  4999.8     .05       0
Bank Sta=4993.8,4999.8
XS Rating Curve= 0 ,0
Exp/Cntr=0.3,0.1

Type RM Length L Ch R = 1 ,5378    ,391,391,391
BEGIN DESCRIPTION:
UNT00277 IN CHRS 11.0
END DESCRIPTION:
XS GIS Cut Line= 3
      3371092.51     10615144.64      3371394.58      10615050.9
      3371931.07     10614480.55
#Sta/Elev= 30
  4635.4  624.71  4726.9  621.98  4771.1  621.44  4797.3  620.29  4829.9  619.33
  4844.4  619.34  4886.3  618.35  4907.2  617.16  4977.9  616.25  4995.9  615.25
  4998.7  614.75  5001.9  615.25  5013.1  616.62    5020  616.91  5069.7  616.64
  5126.4  617.16  5147.4  618.59    5183  620.15  5218.2  622.32  5253.4  623.92
  5274.9  624.53    5289  625.62  5295.9  625.53  5458.6  628.53    5501  630.24
    5586  631.78  5607.5  633.25  5614.3   633.1  5656.8  633.99  5734.7  636.19
#Mann= 3 ,-1 , 0
  4635.4     .05       0  4995.9    .035       0  5001.9     .05       0
Bank Sta=4995.9,5001.9
XS Rating Curve= 0 ,0
Exp/Cntr=0.3,0.1

Type RM Length L Ch R = 1 ,4987    ,437,437,437
BEGIN DESCRIPTION:
UNT00277 IN CHRS 10.0
END DESCRIPTION:
XS GIS Cut Line= 3
      3371392.08     10615341.64      3371642.11     10615341.64
      3371942.11     10615041.64
#Sta/Elev= 30
  4752.2  622.93  4754.7  622.93  4762.2  621.89  4782.2   618.4  4792.2  616.96
  4812.2   616.2  4832.2  615.69  4842.2  615.73  4852.2  615.48  4862.2  614.89
  4902.2  614.03  4942.2  612.53  4962.2  612.18  4982.2  612.48  4996.7   611.8
  4999.5   611.3  5002.7   611.8  5005.8   611.8  5012.5  612.33  5016.4  612.64
  5038.5  613.17  5058.8  613.68  5129.5  617.37  5143.6  617.65  5157.8  618.24
  5186.1  618.73  5228.5  619.88  5341.6  621.84    5423  625.11  5426.5  625.11
#Mann= 5 ,-1 , 0
  4752.2     .05       0  4996.7    .035       0  5002.7     .05       0
  5012.5     .12       0  5038.5     .05       0
Bank Sta=4996.7,5002.7
XS Rating Curve= 0 ,0
Exp/Cntr=0.3,0.1

Type RM Length L Ch R = 1 ,4550    ,471,471,471
BEGIN DESCRIPTION:
UNT00277 IN CHRS 9.0
END DESCRIPTION:
XS GIS Cut Line= 3
      3371292.11     10615891.64      3371892.11     10615641.64
       3371992.1     10615341.66
#Sta/Elev= 30
  4335.6  628.33  4411.4  625.08  4433.1  625.15  4487.3  621.84  4509.5  621.22
  4533.3  621.43  4541.4  620.53    4581  618.89  4610.2  619.13  4628.1  618.09
  4681.7  617.45    4711  616.26  4734.8  616.48  4801.4  613.66  4870.2  611.81
  4899.5  610.36  4923.3  610.58  4974.3  609.09  4982.9  608.31  4993.1  608.24
  4995.9  607.74  4999.1  608.24  5038.3   609.7    5091  610.89  5133.2  612.84
  5176.2  613.77  5198.9  614.09  5238.6  615.37  5278.2  618.79  5301.8  619.25
#Mann= 7 ,-1 , 0
  4335.6     .05       0  4974.3     .12       0  4993.1     .07       0
  4999.1     .12       0  5176.2     .05       0  5198.9     .12       0
  5278.2     .05       0
Bank Sta=4993.1,4999.1
XS Rating Curve= 0 ,0
Exp/Cntr=0.3,0.1

Type RM Length L Ch R = 1 ,4079    ,513,513,513
BEGIN DESCRIPTION:
UNT00277 IN CHRS 8.0
END DESCRIPTION:
XS GIS Cut Line= 3
      3371692.12     10615991.64      3372242.11     10615891.64
       3372392.1     10615591.66
#Sta/Elev= 30
  4434.5  616.71  4461.2  615.59  4519.6  614.14    4526  613.68  4586.9   612.5
  4607.3  612.39  4637.8  611.43  4738.1  610.19  4769.9   608.9  4801.7  608.67
  4861.4  606.62  4932.5  606.19  4961.7  605.67  4973.2  604.56  4996.3  604.91
  4998.9  604.37  5001.6  603.87  5004.9  604.37  5015.9     605  5024.3  606.03
  5029.8  605.95  5091.3  608.13  5113.7   609.5  5119.3  610.37  5136.1  611.83
  5172.4  612.63  5225.5   614.4  5284.2  617.29  5306.6  619.85  5328.9  620.21
#Mann= 3 ,-1 , 0
  4434.5     .05       0  4998.9    .035       0  5004.9     .05       0
Bank Sta=4998.9,5004.9
XS Rating Curve= 0 ,0
Exp/Cntr=0.3,0.1

Type RM Length L Ch R = 1 ,3566    ,595,595,595
BEGIN DESCRIPTION:
UNT00277 IN CHRS 7.0
END DESCRIPTION:
XS GIS Cut Line= 3
      3371792.13     10616291.64      3372392.11     10616291.64
       3372992.1     10615741.65
#Sta/Elev= 30
  4368.3  614.98  4378.3  615.09  4398.3  613.03  4408.3  613.29  4428.3  612.03
  4508.3  610.41  4538.3  610.91  4758.3  606.64  4778.3  607.49  4878.3  605.44
  4928.3   605.4  4948.3  602.96  4982.1  603.16  4986.5  601.71  4989.3  601.21
  4992.5  601.71  5003.7  603.05  5053.1  602.31  5095.6  603.44  5131.1  603.21
  5223.2  607.39  5498.9  609.71  5527.2  612.47  5548.8  612.27    5563  614.06
  5577.2  614.64    5740  617.45  5754.2  618.41  5775.1  623.88  5782.2  624.29
#Mann= 3 ,-1 , 0
  4368.3     .05       0  4986.5    .035       0  4992.5     .05       0
Bank Sta=4986.5,4992.5
XS Rating Curve= 0 ,0
Exp/Cntr=0.3,0.1

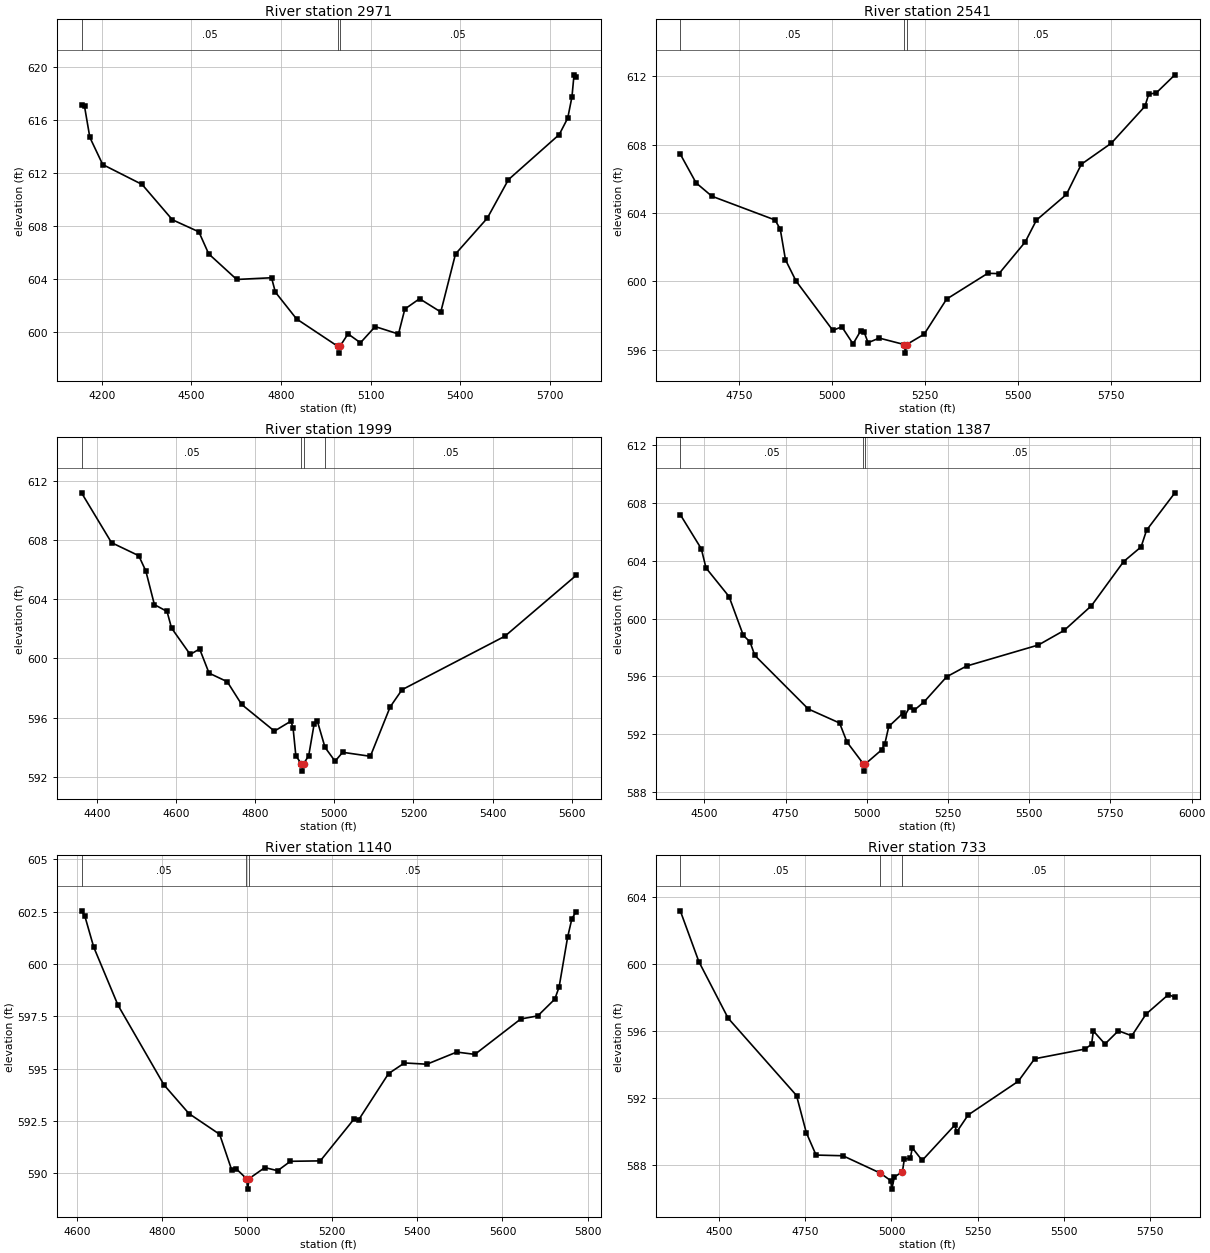
Type RM Length L Ch R = 1 ,2971    ,430,430,430
BEGIN DESCRIPTION:
UNT00277 IN CHRS 6.0
END DESCRIPTION:
XS GIS Cut Line= 3
      3371692.15     10616441.65      3372592.11     10616591.64
      3373092.13     10616041.62
#Sta/Elev= 30
  4131.9  617.13    4142     617  4159.7  614.67  4202.8  612.62  4334.6  611.12
    4436  608.46  4524.7  607.55  4557.6  605.89  4651.4  603.96    4768  604.09
  4780.7  603.01  4851.6  600.99  4990.6  598.91  4993.3  598.41  4996.6  598.91
    5024  599.86  5065.6  599.19  5114.9  600.41  5192.9  599.85  5214.2  601.73
  5263.5  602.51  5334.5  601.51  5383.8  605.88  5490.2  608.58  5560.9  611.48
  5731.1  614.88  5759.5  616.12  5773.7  617.73  5780.5  619.38  5787.6  619.21
#Mann= 3 ,-1 , 0
  4131.9     .05       0  4990.6    .035       0  4996.6     .05       0
Bank Sta=4990.6,4996.6
XS Rating Curve= 0 ,0
Exp/Cntr=0.3,0.1

Type RM Length L Ch R = 1 ,2541    ,542,542,542
BEGIN DESCRIPTION:
UNT00277 IN CHRS 5.0
END DESCRIPTION:
XS GIS Cut Line= 3
      3372042.11     10616591.64      3372342.11     10616891.64
      3373242.11     10616991.64
#Sta/Elev= 30
    4593  607.44  4635.4  605.76  4677.8  604.98  4847.6  603.59  4861.7  603.06
  4875.8  601.26  4904.1  600.02  5003.1  597.13  5027.3  597.34  5057.5  596.34
  5077.6  597.09  5087.7  597.01  5097.8  596.41  5127.9  596.68  5195.4   596.3
  5198.1   595.8  5201.4   596.3  5248.7  596.91    5309  598.96  5419.7  600.47
  5449.9  600.45  5520.3   602.3  5550.5  603.58    5631  605.08  5671.3  606.85
  5751.8  608.08  5842.3  610.24  5852.4  610.95  5872.5  611.02  5922.8  612.08
#Mann= 3 ,-1 , 0
    4593     .05       0  5195.4    .035       0  5201.4     .05       0
Bank Sta=5195.4,5201.4
XS Rating Curve= 0 ,0
Exp/Cntr=0.3,0.1

Type RM Length L Ch R = 1 ,1999    ,612,612,612
BEGIN DESCRIPTION:
UNT00277 IN CHRS 4.0
END DESCRIPTION:
XS GIS Cut Line= 3
      3371792.09     10617041.64      3372392.11     10617291.64
      3372992.09     10617291.64
#Sta/Elev= 30
  4361.3  611.17  4437.1  607.81  4505.9  606.93  4523.8   605.9  4545.5  603.63
  4577.4  603.17  4588.8  602.05  4635.9  600.27  4659.8  600.64  4683.6  599.01
  4729.6  598.43  4765.9   596.9  4848.8   595.1  4890.5  595.77  4895.9  595.32
    4903  593.43  4916.8   592.9  4919.5   592.4  4922.8   592.9  4935.5  593.45
    4949  595.55  4957.1  595.79  4976.7     594  5002.1  593.07  5021.3  593.67
  5091.3   593.4  5141.3  596.73  5171.3  597.89  5431.3   601.5  5611.3   605.6
#Mann= 4 ,-1 , 0
  4361.3     .05       0  4916.8    .035       0  4922.8     .05       0
  4976.7     .05       0
Bank Sta=4916.8,4922.8
XS Rating Curve= 0 ,0
Exp/Cntr=0.3,0.1

Type RM Length L Ch R = 1 ,1387    ,247,247,247
BEGIN DESCRIPTION:
UNT00277 IN CHRS 3.0
END DESCRIPTION:
XS GIS Cut Line= 4
      3371694.04     10617438.91      3372063.85     10617714.96
      3372342.49     10617821.73      3373098.69     10617722.98
#Sta/Elev= 30
    4426  607.19  4490.6  604.83  4505.2   603.5  4576.1  601.52  4619.9  598.84
  4640.7  598.38  4655.3  597.45    4820  593.74  4916.3  592.77  4939.2  591.45
  4989.7  589.94  4992.5  589.44  4995.7  589.94  5046.2  590.92  5055.7  591.34
  5067.7  592.53  5110.5  593.43  5115.8  593.23  5131.9  593.86  5145.8  593.65
  5175.9  594.22    5246  595.97    5307  596.71  5528.4  598.17  5607.7  599.18
  5691.7  600.89  5790.6  603.94  5844.5  604.96  5861.2  606.11  5948.5   608.7
#Mann= 3 ,-1 , 0
    4426     .05       0  4989.7    .035       0  4995.7     .05       0
Bank Sta=4989.7,4995.7
XS Rating Curve= 0 ,0
Exp/Cntr=0.3,0.1

Type RM Length L Ch R = 1 ,1140    ,407,407,407
BEGIN DESCRIPTION:
UNT00277 IN CHRS 2.0
END DESCRIPTION:
XS GIS Cut Line= 3
      3371692.09     10617741.63      3371992.11     10617941.64
      3372792.07     10617991.64
#Sta/Elev= 30
    4611  602.54  4618.5  602.31  4639.6  600.81  4696.7  598.03  4804.8  594.22
  4863.4  592.85  4935.5  591.86  4964.1  590.14  4974.1  590.22  4998.6  589.74
  5001.4  589.24  5004.6  589.74  5041.7  590.27  5071.8  590.12  5101.8  590.57
    5172  590.59  5252.1  592.61  5262.1  592.55  5332.3  594.76  5369.8  595.27
  5422.5  595.21  5492.6  595.79  5535.2  595.68  5642.9  597.37    5683  597.52
    5723  598.32  5733.1   598.9  5753.1  601.28  5763.1  602.16  5773.1   602.5
#Mann= 3 ,-1 , 0
    4611     .05       0  4998.6    .035       0  5004.6     .05       0
Bank Sta=4998.6,5004.6
XS Rating Curve= 0 ,0
Exp/Cntr=0.3,0.1

Type RM Length L Ch R = 1 ,733     ,257,257,257
BEGIN DESCRIPTION:
UNT00277 IN CHRS 1.2
END DESCRIPTION:
XS GIS Cut Line= 4
      3371613.35     10617884.26       3371970.1     10618251.42
      3372201.87     10618355.59      3372842.49     10618170.69
#Sta/Elev= 30
  4388.2  603.16    4442  600.13  4526.8  596.76  4724.9  592.15  4753.2  589.94
  4781.5   588.6  4859.2  588.56  4968.1  587.52    4998  587.07  5000.8  586.57
  5008.5  587.29  5031.6  587.61  5037.1  588.34  5054.8  588.44  5060.3  589.03
  5088.9  588.28  5183.5  590.39  5188.7  589.97  5222.1  590.99  5367.3     593
  5414.7  594.34  5560.4  594.92  5579.6   595.2  5584.8     596  5618.4  595.22
  5657.3  596.01  5696.1  595.71  5737.3     597  5802.3  598.17    5821     598
#Mann= 3 , 0 , 0
  4388.2     .05       0  4968.1      .2       0  5031.6     .05       0
Bank Sta=4968.1,5031.6
XS Rating Curve= 0 ,0
Exp/Cntr=0.3,0.1

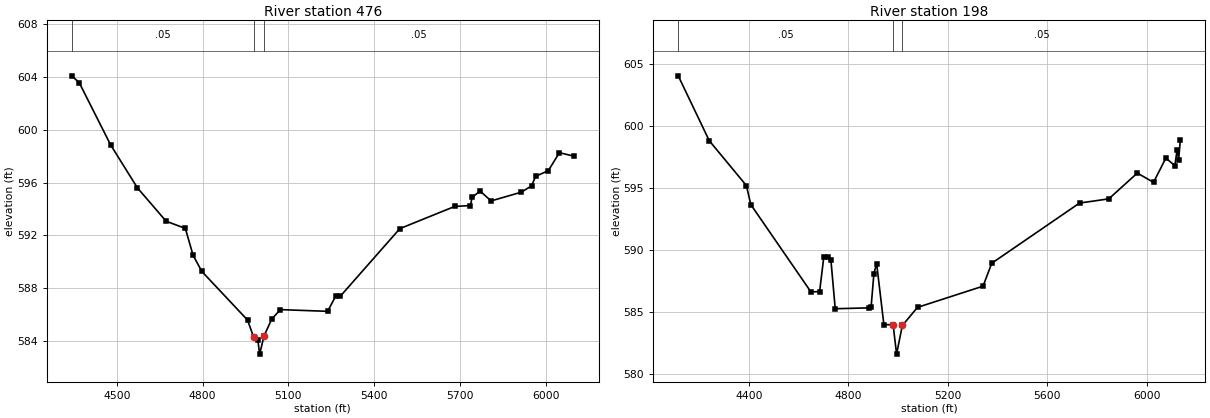
Type RM Length L Ch R = 1 ,476     ,278,278,278
BEGIN DESCRIPTION:
UNT00277 IN CHRS 1.1
END DESCRIPTION:
XS GIS Cut Line= 4
      3371514.35     10617972.74      3371787.81     10618407.67
      3372089.89     10618605.59      3372873.76     10618204.54
#Sta/Elev= 30
  4342.8  604.08  4368.9  603.56  4478.4  598.86  4572.6  595.59  4672.8  593.07
  4739.9  592.53    4767  590.49  4797.6  589.27  4957.3  585.59  4978.8  584.29
  4993.2  584.09  4999.7  583.01    5015  584.39  5042.1  585.67  5072.3  586.38
  5237.2  586.25  5265.1  587.38  5281.6  587.39  5489.8  592.51  5681.4  594.19
  5736.8  594.26  5742.4  594.89  5770.6  595.35    5809  594.61  5914.5  595.27
  5950.3  595.75  5964.5  596.47  6008.9   596.9  6047.7  598.26  6098.2     598
#Mann= 3 , 0 , 0
  4342.8     .05       0  4978.8     .02       0    5015     .05       0
Bank Sta=4978.8,5015
XS Rating Curve= 0 ,0
Exp/Cntr=0.3,0.1

Type RM Length L Ch R = 1 ,198     ,0,0,0
BEGIN DESCRIPTION:
UNT00277 IN CHRS 1.0
END DESCRIPTION:
XS GIS Cut Line= 5
       3371475.3      10617993.6      3371790.41     10618688.92
      3371975.31     10618774.86      3372509.16     10618537.88
      3372902.43     10618282.64
#Sta/Elev= 30
  4115.8  604.01  4240.6  598.78  4390.1  595.16  4407.7  593.63  4649.6  586.59
  4684.6  586.61  4701.3  589.37  4717.5  589.44  4729.9   589.2  4747.5  585.23
  4882.9   585.3    4892   585.4  4903.1  588.07  4914.1  588.87  4943.3  583.94
  4980.3  583.95  4994.4  581.57  5017.5  583.88  5078.6  585.34  5342.2  587.05
  5377.4   588.9  5730.4  593.75  5848.3  594.09    5963  596.17  6028.3  595.42
  6077.8  597.38    6114  596.77  6123.2  598.04  6129.2  597.26    6136   598.8
#Mann= 3 , 0 , 0
  4115.8     .05       0  4980.3      .2       0  5017.5     .05       0
Bank Sta=4980.3,5017.5
XS Rating Curve= 0 ,0
Exp/Cntr=0.3,0.1

Chan Stop Cuts=-1
Use User Specified Reach Order=0
Composite Channel Slope=5