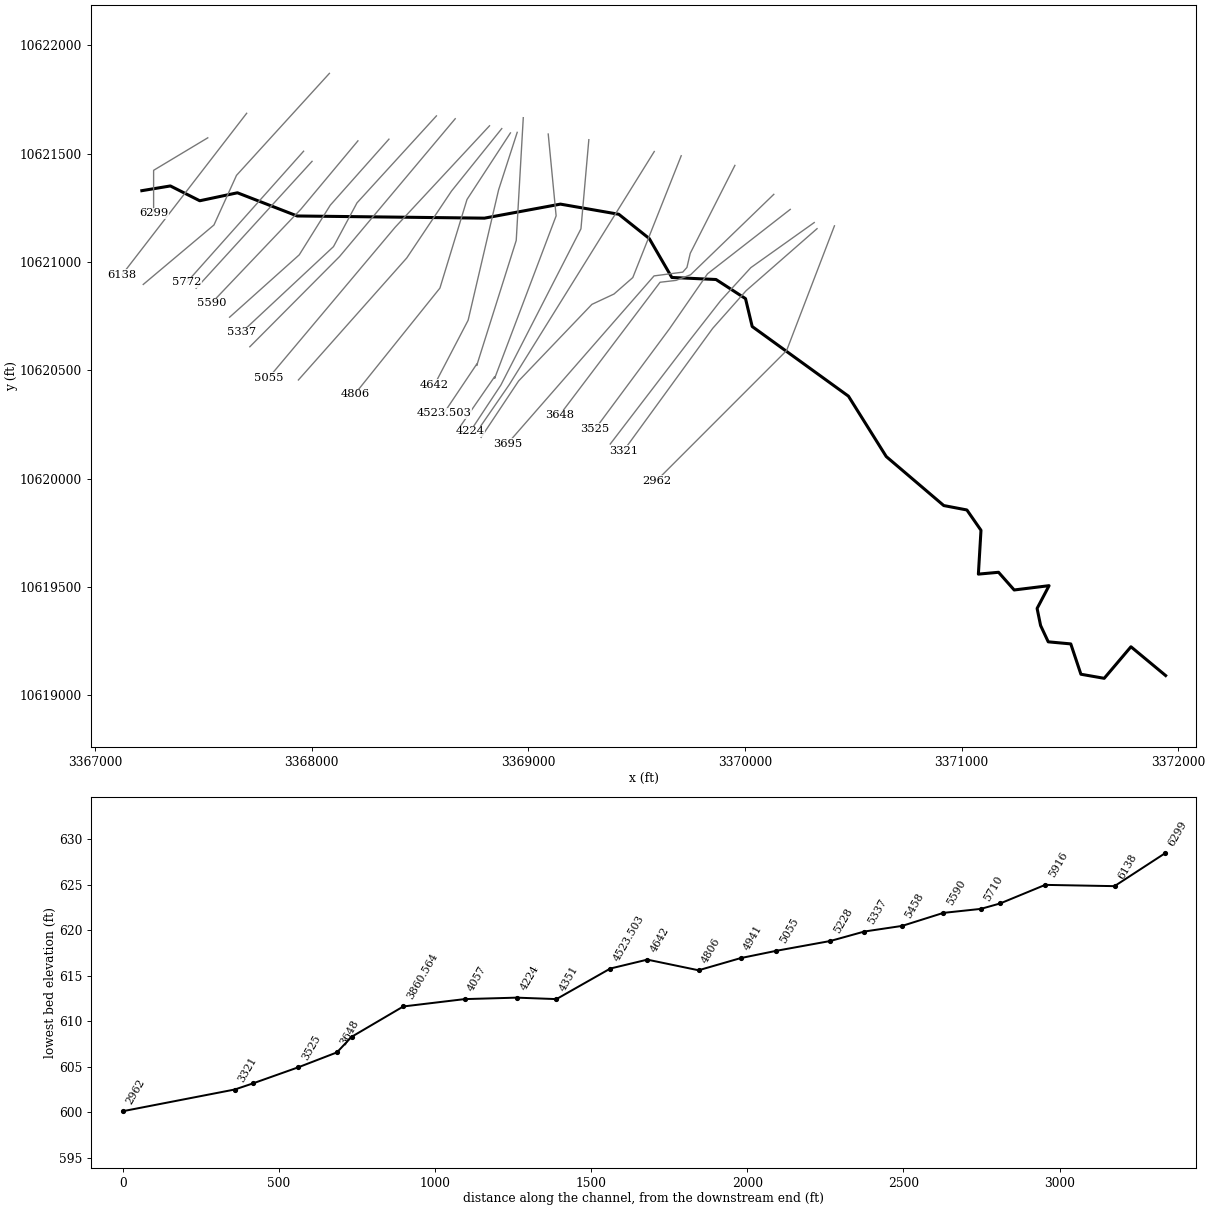
--- UNT00278 IN CHRS.prj (project) ---

Proj Title=UNT00278 IN CHRS Base Level Engineering
Current Plan=p01
Default Exp/Contr=0.3,0.1
English Units
Geom File=g01
Flow File=f01
Plan File=p01
Y Axis Title=Elevation
X Axis Title(PF)=Main Channel Distance
X Axis Title(XS)=Station
BEGIN DESCRIPTION:
UNT00278 IN CHRS
END DESCRIPTION:
DSS File=dss
DSS Export Rating Curves= 0
DSS Export Rating Curve Sorted= 0
DSS Export Volume Flow Curves= 0
DXF OffsetX= 0
DXF OffsetY= 0
DXF ScaleX= 1
DXF ScaleY= 10

--- UNT00278 IN CHRS.p01 (plan) ---

Plan Title=Multiple Run
Program Version=4.10
Geom File=g01
Flow File=f01
Subcritical Flow
K Sum by GR= 0
Std Step Tol= 0.01
Critical Tol= 0.01
Num of Std Step Trials= 20
Max Error Tol= 0.3
Flow Tol Ratio= 0.001
Split Flow NTrial= 30
Split Flow Tol= 0.02
Split Flow Ratio= 0.02
Log Output Level= 0
Friction Slope Method= 1
Unsteady Friction Slope Method= 2
Unsteady Bridges Friction Slope Method= 1
Parabolic Critical Depth
Global Vel Dist= 1 , 1 , 1
Global Log Level= 0
CheckData=True
Encroach Param=-1 ,0,0, 0
BEGIN DESCRIPTION:
Multiple Run
END DESCRIPTION:
Computation Interval=1HOUR
Output Interval=1HOUR
Run HTab= 0
Run UNet= 0
Run PostProcess= 0
Run WQNet= 0
UNET Theta= 1
UNET Theta Warmup= 1
UNET ZTol= 0.02
UNET ZSATol= 0.05
UNET MxIter= 20
UNET MaxInSteps= 0
UNET DtIC= 0
UNET DtMin= 0
UNET MaxCRTS= 20
UNET WFStab= 2
UNET SFStab= 1
UNET WFX= 1
UNET SFX= 1
UNET DSS MLevel= 4
UNET DZMax Abort= 100
UNET Convert EG Bridges= 0
UNET Use Existing IB Tables=-1
UNET Froude Reduction=False
UNET Froude Limit= 1
UNET Froude Power= 10
UNET Time Slicing=0,0, 5
UNET Junction Losses=0
Instantaneous Interval=1HOUR
DSS File=dss
Write IC File= 0
Write IC File at Sim End=0
Echo Input=False
Echo Parameters=False
Echo Output=False
Write Detailed= 0
WQ AD Non Conservative
WQ ULTIMATE=-1
WQ Max Comp Step=1HOUR
WQ Output Interval=15MIN
WQ Output Selected Increments= 0
WQ Output face flow=0
WQ Output face velocity=0
WQ Output face area=0
WQ Output face dispersion=0
WQ Output cell volume=0
WQ Output cell surface area=0
WQ Output cell continuity=0
WQ Output cumulative cell continuity=0
WQ Output face conc=0
WQ Output face dconc_dx=0
WQ Output face courant=0
WQ Output face peclet=0
WQ Output face adv mass=0
WQ Output face disp mass=0
WQ Output cell mass=0
WQ Output cell source sink temp=0
WQ Output cell source sink nsm=0
WQ Output MaxMinRange=-1
WQ Daily Max Min Mean=-1
WQ Daily Range=0
WQ Daily Time=0
WQ Create Restart=0
WQ Fixed Restart=0
WQ System Summary=0
WQ Use Fixed Temperature=0
Sorting and Armoring Iterations= 10
XS Update Threshold= 0.02
Hydraulics Update Threshold= 0.02
Energy Slope Method= 1
Volume Change Method= 0
XS Weighting Method= 0
Number of US Weighted Cross Sections= 1
Number of DS Weighted Cross Sections= 1
Upstream XS Weight=0.25
Main XS Weight=0.5
Downstream XS Weight=0.25
Number of DS XS's Weighted with US Boundary= 1
Upstream Boundary Weight= 1
Weight of XSs Associated with US Boundary= 0
Number of US XS's Weighted with DS Boundary= 1
Downstream Boundary Weight= 0.5
Weight of XSs Associated with DS Boundary= 0.5
Sediment Output Level= 4
Mass or Volume Output= 0
Output Increment Type= 1
Profile and TS Output Increment= 10
XS Output Flag= 0
XS Output Increment= 10
Disregard all LS=0
Disregard all Conn=0
Disregard all Breaches=0
Disregard all Pumps=0

--- UNT00278 IN CHRS.f01 (steady flow) ---

Flow Title=Multiple
Program Version=4.10
Number of Profiles= 7
Profile Names=10-year,25-year,50-year,1pct_min,100-year,1pct_plu,500-year
River Rch & RM=UNT00278 IN CHRS,Reach-1         ,6299
      93     106     114      91     123     166     139
River Rch & RM=UNT00278 IN CHRS,Reach-1         ,5590
     189     228     255     208     281     381     342
Boundary for River Rch & Prof#=UNT00278 IN CHRS,Reach-1         , 1
Up Type= 0
Dn Type= 3
Dn Slope=0.005
Boundary for River Rch & Prof#=UNT00278 IN CHRS,Reach-1         , 2
Up Type= 0
Dn Type= 3
Dn Slope=0.005
Boundary for River Rch & Prof#=UNT00278 IN CHRS,Reach-1         , 3
Up Type= 0
Dn Type= 3
Dn Slope=0.005
Boundary for River Rch & Prof#=UNT00278 IN CHRS,Reach-1         , 4
Up Type= 0
Dn Type= 3
Dn Slope=0.005
Boundary for River Rch & Prof#=UNT00278 IN CHRS,Reach-1         , 5
Up Type= 0
Dn Type= 3
Dn Slope=0.005
Boundary for River Rch & Prof#=UNT00278 IN CHRS,Reach-1         , 6
Up Type= 0
Dn Type= 3
Dn Slope=0.005
Boundary for River Rch & Prof#=UNT00278 IN CHRS,Reach-1         , 7
Up Type= 0
Dn Type= 3
Dn Slope=0.005
DSS Import GetInterval= 0
DSS Import GetPeak= 0
DSS Import FillOption= 0

--- UNT00278 IN CHRS.g01 (geometry) ---

Geom Title=Existing Conditions
Program Version=4.10

River Reach=UNT00278 IN CHRS,Reach-1
Reach XY= 30
      3367215.21      10621329.5      3367346.84     10621351.33
      3367482.57     10621282.97      3367656.54     10621319.76
      3367932.44     10621212.73      3368797.13      10621202.7
      3369147.79     10621267.48      3369417.32     10621220.61
      3369557.95     10621108.63      3369662.11     10620928.94
      3369866.14     10620919.54      3370002.38     10620831.28
      3370033.24     10620702.51      3370477.56     10620381.17
      3370652.04     10620102.52       3370917.7     10619876.25
      3371024.44     10619855.91      3371089.54     10619762.16
       3371077.5     10619559.86      3371170.62     10619568.26
      3371242.82     10619486.62      3371403.94     10619506.53
       3371348.6     10619401.38      3371364.74     10619322.67
      3371400.03     10619247.32      3371504.09     10619237.73
      3371550.88     10619097.75      3371658.47     10619078.94
      3371781.92     10619224.55      3371942.11     10619091.64

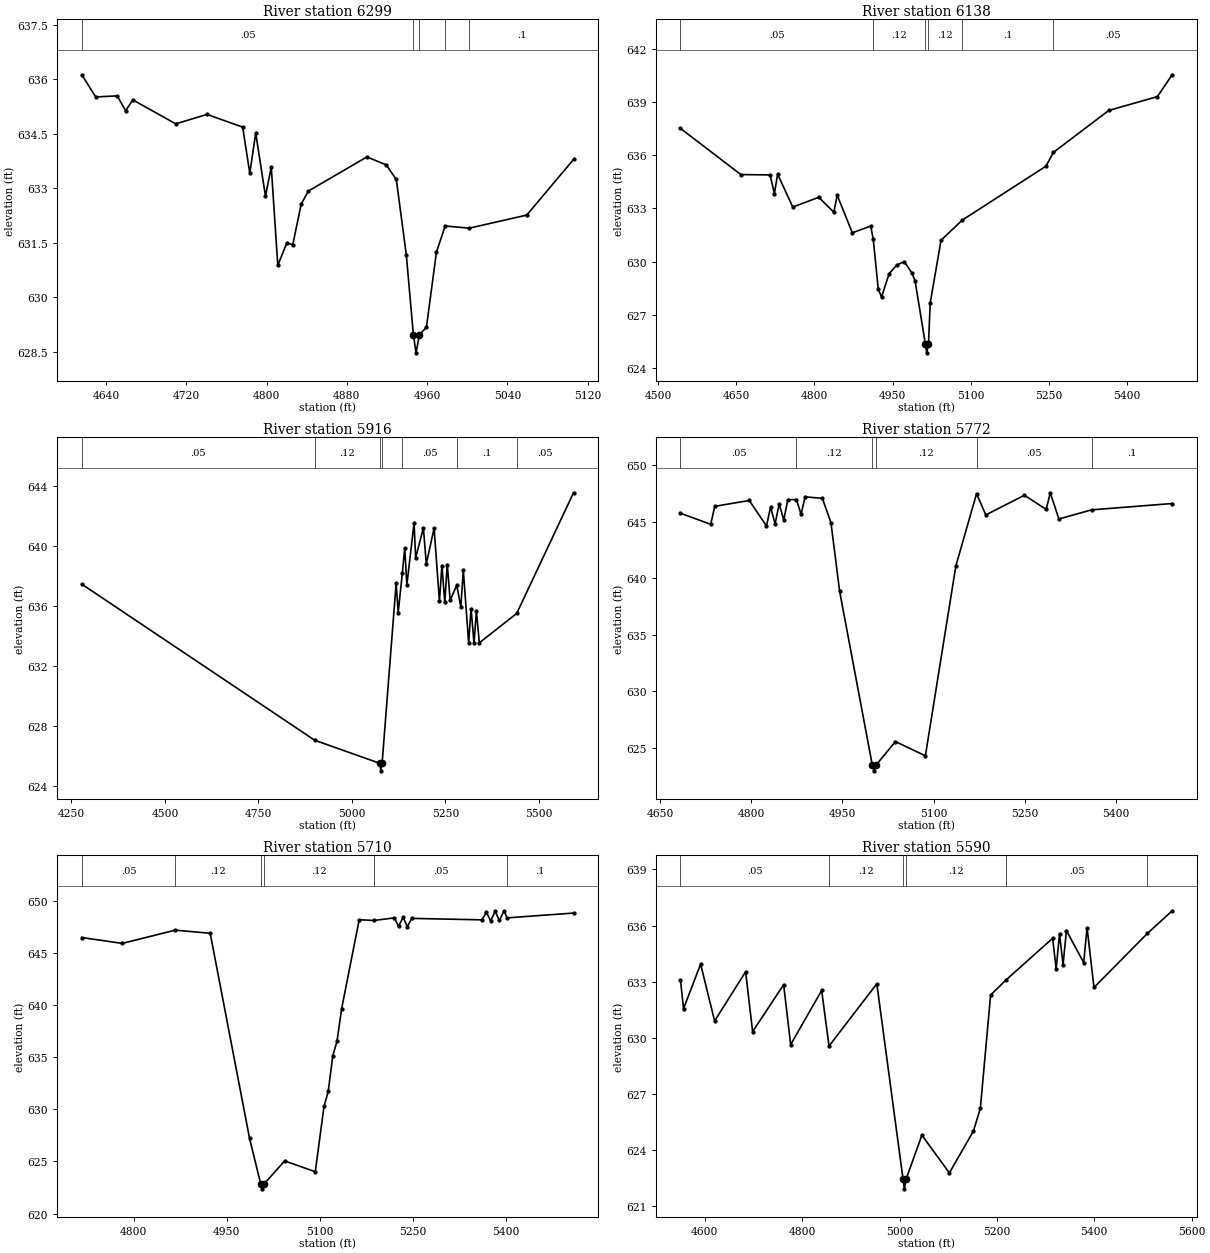
Type RM Length L Ch R = 1 ,6299    ,161,161,161
BEGIN DESCRIPTION:
UNT00278 IN CHRS 10.0
END DESCRIPTION:
XS GIS Cut Line= 3
      3367519.56     10621573.46      3367269.54     10621423.45
      3367269.54     10621225.02
#Sta/Elev= 30
  4615.9  636.12  4629.8  635.51  4651.2  635.54  4659.6  635.13  4666.7  635.43
  4709.5  634.77  4740.6  635.03  4776.2  634.68  4783.3  633.41  4789.2  634.52
  4798.9  632.78  4804.7  633.58  4811.2  630.88  4820.3   631.5  4826.1  631.44
  4834.5  632.56  4841.6  632.92    4900  633.86  4919.3  633.64  4929.3  633.24
  4939.3  631.16  4946.3  628.97    4949  628.47  4952.3  628.97  4959.3  629.17
  4969.3  631.24    4978  631.96    5002   631.9  5059.3  632.26  5105.9  633.79
#Mann= 5 ,-1 , 0
  4615.9     .05       0  4946.3     .07       0  4952.3     .05       0
    4978     .12       0    5002      .1       0
Bank Sta=4946.3,4952.3
XS Rating Curve= 0 ,0
Exp/Cntr=0.3,0.1

Type RM Length L Ch R = 1 ,6138    ,222,222,222
BEGIN DESCRIPTION:
UNT00278 IN CHRS 9.1
END DESCRIPTION:
XS GIS Cut Line= 2
      3367699.14     10621686.67      3367122.78     10620940.18
#Sta/Elev= 30
    4543  637.51  4658.8  634.91  4714.9  634.89  4723.1  633.84  4729.4  634.93
  4758.4  633.08  4808.2  633.63  4837.2  632.79  4843.6  633.75  4872.6  631.63
  4907.9  632.01  4912.8  631.26  4922.4  628.45  4928.7  628.01  4943.2  629.33
  4957.7  629.81  4972.2  630.01  4986.7  629.38    4993  628.92  5012.7  625.37
  5015.4  624.87  5018.7  625.37    5022  627.68  5042.8  631.21  5083.7  632.35
  5243.9  635.38  5258.4  636.16  5364.4  638.52  5457.7   639.3  5486.1  640.53
#Mann= 6 ,-1 , 0
    4543     .05       0  4912.8     .12       0  5012.7     .07       0
  5018.7     .12       0  5083.7      .1       0  5258.4     .05       0
Bank Sta=5012.7,5018.7
XS Rating Curve= 0 ,0
Exp/Cntr=0.3,0.1

Type RM Length L Ch R = 1 ,5916    ,144,144,144
BEGIN DESCRIPTION:
UNT00278 IN CHRS 9.0
END DESCRIPTION:
XS GIS Cut Line= 4
      3368081.14     10621870.77      3367652.29     10621400.25
      3367548.13     10621171.09      3367221.74     10620896.79
#Sta/Elev= 30
  4277.9  637.45  4900.5  627.05  5074.8  625.51  5077.5  625.01  5080.8  625.51
  5118.3   637.5  5123.8  635.56  5134.9  638.18  5141.4  639.88  5146.9  637.39
  5166.3  641.53  5170.4   639.2  5191.2   641.2    5199   638.8  5219.8  641.18
  5234.1   636.3  5240.7  638.69  5248.4  636.23    5255  638.76  5262.7  636.38
  5280.4  637.37  5291.3  635.94  5297.9  638.38  5312.2  633.54  5318.7  635.82
  5326.5  633.53    5333  635.63  5340.8  633.54  5440.7   635.5  5592.6  643.54
#Mann= 7 ,-1 , 0
  4277.9     .05       0  4900.5     .12       0  5074.8     .07       0
  5080.8     .12       0  5134.9     .05       0  5280.4      .1       0
  5440.7     .05       0
Bank Sta=5074.8,5080.8
XS Rating Curve= 0 ,0
Exp/Cntr=0.3,0.1

Type RM Length L Ch R = 1 ,5772    ,62,62,62
BEGIN DESCRIPTION:
UNT00278 IN CHRS 8.1
END DESCRIPTION:
XS GIS Cut Line= 2
      3367962.07      10621511.7       3367423.1     10620907.17
#Sta/Elev= 30
  4683.2  645.76    4733  644.78  4739.7  646.37  4796.5  646.89  4824.9  644.63
  4831.6  646.31  4839.1  644.82  4845.8  646.59  4853.3  645.16    4860  646.96
  4874.3  646.97  4881.8  645.66  4888.5  647.21  4916.9  647.08  4931.1  644.92
  4945.3  638.87  4999.2  623.47  5001.9  622.97  5005.2  623.47  5037.3  625.56
  5086.6   624.3  5136.8   641.1  5170.9  647.49  5186.1  645.61  5249.7  647.35
  5285.6   646.1  5292.3  647.57  5306.5  645.25  5360.3  646.06  5493.1  646.62
#Mann= 6 ,-1 , 0
  4683.2     .05       0  4874.3     .12       0  4999.2     .07       0
  5005.2     .12       0  5170.9     .05       0  5360.3      .1       0
Bank Sta=4999.2,5005.2
XS Rating Curve= 0 ,0
Exp/Cntr=0.3,0.1

Type RM Length L Ch R = 1 ,5710    ,120,120,120
BEGIN DESCRIPTION:
UNT00278 IN CHRS 7.3
END DESCRIPTION:
XS GIS Cut Line= 2
      3368001.09     10621464.93      3367465.93     10620878.93
#Sta/Elev= 30
  4716.1  646.49  4781.4  645.93  4866.9   647.2  4923.3   646.9  4986.8  627.22
  5004.7  622.87  5007.5  622.37  5010.7  622.87  5043.5  625.05  5092.9  624.01
    5107  630.28  5113.8  631.72  5121.2  635.14    5128  636.54  5135.4  639.65
  5163.8   648.2  5187.7  648.13  5220.5  648.38  5227.3  647.56  5234.7  648.44
  5241.5  647.53  5248.7  648.33  5361.7  648.19  5369.2  648.92  5375.9  648.09
  5383.3  649.01  5390.1  648.13  5397.5  649.06  5402.5  648.38  5509.7  648.84
#Mann= 6 ,-1 , 0
  4716.1     .05       0  4866.9     .12       0  5004.7     .07       0
  5010.7     .12       0  5187.7     .05       0  5402.5      .1       0
Bank Sta=5004.7,5010.7
XS Rating Curve= 0 ,0
Exp/Cntr=0.3,0.1

Type RM Length L Ch R = 1 ,5590    ,132,132,132
BEGIN DESCRIPTION:
UNT00278 IN CHRS 8.0
END DESCRIPTION:
XS GIS Cut Line= 3
      3368212.84     10621559.45      3367949.83     10621244.37
      3367536.47      10620810.2
#Sta/Elev= 30
  4550.1  633.09  4556.4  631.56  4591.5  633.94  4620.2   630.9  4683.9  633.53
  4698.3  630.33    4762  632.84  4776.4  629.64  4840.1  632.53  4855.2  629.56
  4953.4  632.89  5007.3  622.43    5010  621.93  5013.3  622.43  5045.9   624.8
  5102.4  622.78  5151.8  625.02    5166  626.23  5187.1  632.29  5219.5  633.11
  5314.5  635.32  5321.7  633.68  5328.6  635.55  5335.9  633.91  5342.8  635.73
  5378.3  634.02  5385.2  635.89  5399.4  632.69  5509.2  635.58    5560  636.79
#Mann= 6 ,-1 , 0
  4550.1     .05       0  4855.2     .12       0  5007.3     .07       0
  5013.3     .12       0  5219.5     .05       0  5509.2      .1       0
Bank Sta=5007.3,5013.3
XS Rating Curve= 0 ,0
Exp/Cntr=0.3,0.1

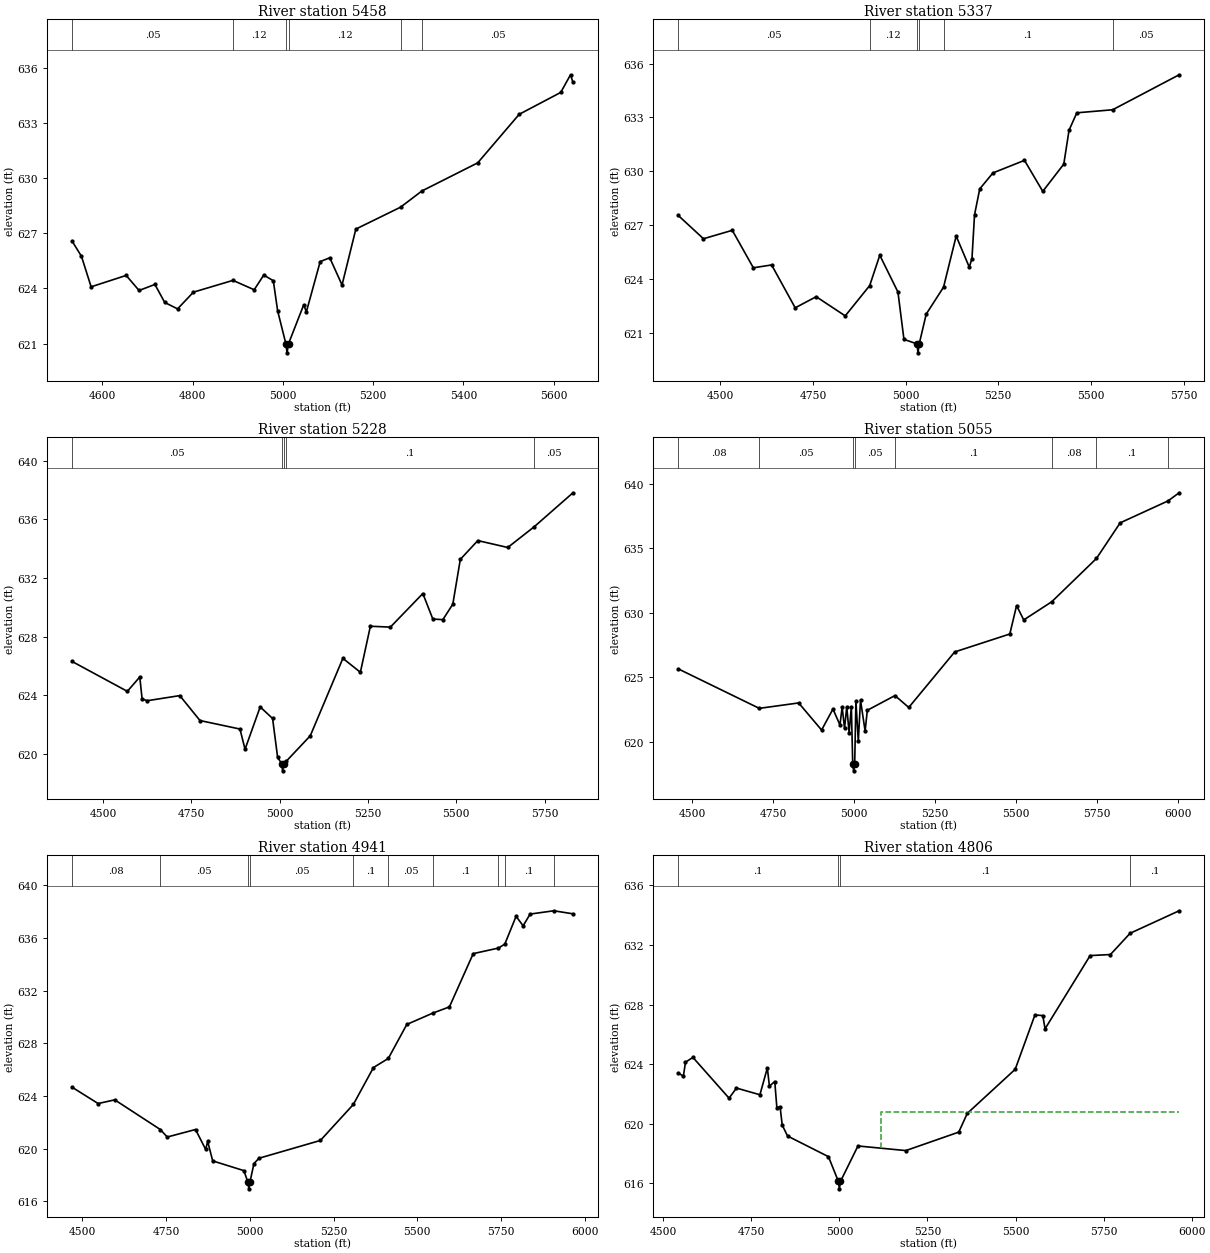
Type RM Length L Ch R = 1 ,5458    ,121,121,121
BEGIN DESCRIPTION:
UNT00278 IN CHRS 7.0
END DESCRIPTION:
XS GIS Cut Line= 4
      3368356.06     10621567.26      3368085.25     10621262.59
      3367942.02     10621033.43      3367620.34     10620745.47
#Sta/Elev= 30
    4533  626.58  4553.9  625.75  4575.3  624.09    4653  624.71  4681.5  623.89
  4716.6  624.22  4738.3  623.24  4766.8  622.89  4801.9   623.8  4889.5  624.44
  4936.5  623.93  4957.7  624.73  4978.9  624.42  4988.4  622.79  5006.6     621
  5009.3   620.5  5012.6     621  5046.2  623.11  5052.1  622.73  5082.7  625.46
  5103.9  625.67  5131.1  624.19  5161.7  627.23  5260.7  628.42  5307.9   629.3
  5431.6  630.83  5523.5  633.47  5615.5  634.66  5637.2  635.62  5642.6  635.21
#Mann= 6 ,-1 , 0
    4533     .05       0  4889.5     .12       0  5006.6     .07       0
  5012.6     .12       0  5260.7      .1       0  5307.9     .05       0
Bank Sta=5006.6,5012.6
XS Rating Curve= 0 ,0
Exp/Cntr=0.3,0.1

Type RM Length L Ch R = 1 ,5337    ,109,109,109
BEGIN DESCRIPTION:
UNT00278 IN CHRS 7.2
END DESCRIPTION:
XS GIS Cut Line= 4
       3368575.3     10621674.63      3368208.51     10621273.12
      3368100.01      10621071.3      3367677.14     10620676.62
#Sta/Elev= 30
  4386.5  627.54  4454.7  626.24  4532.4  626.71  4589.2  624.62  4638.5  624.78
  4702.1  622.39  4758.8  623.01  4837.1  621.94  4903.1  623.63  4930.3  625.32
  4979.3  623.27  4995.5  620.63  5030.7  620.38  5033.4  619.88  5036.7  620.38
  5055.6  622.04  5102.3  623.54  5136.4  626.39  5171.7  624.66    5179  625.13
  5185.9  627.57    5200  629.02  5235.7  629.91  5320.7  630.61    5370  628.88
  5426.7   630.4  5440.9  632.29  5461.9  633.26  5558.6  633.43  5737.9  635.38
#Mann= 6 ,-1 , 0
  4386.5     .05       0  4903.1     .12       0  5030.7     .07       0
  5036.7     .12       0  5102.3      .1       0  5558.6     .05       0
Bank Sta=5030.7,5036.7
XS Rating Curve= 0 ,0
Exp/Cntr=0.3,0.1

Type RM Length L Ch R = 1 ,5228    ,173,173,173
BEGIN DESCRIPTION:
UNT00278 IN CHRS 7.1
END DESCRIPTION:
XS GIS Cut Line= 3
      3368662.06     10621661.56      3368128.22     10621025.73
      3367713.76     10620609.09
#Sta/Elev= 30
  4412.1   626.3  4568.7  624.26  4603.9  625.24  4610.4  623.75  4624.7  623.62
  4717.1  623.97  4774.3  622.27  4887.5  621.69  4901.8  620.31  4944.7   623.2
  4979.8  622.41  4994.1  619.75  5005.4  619.34  5008.2  618.84  5011.4  619.34
  5018.7   619.5  5086.5  621.23  5178.8  626.51  5228.3  625.56  5256.6   628.7
  5313.2  628.64  5405.1  630.93  5433.4  629.19  5461.7  629.15  5489.9   630.2
  5511.2  633.26  5560.7  634.54  5645.5  634.07  5720.2  635.48    5830   637.8
#Mann= 5 ,-1 , 0
  4412.1     .05       0  5005.4     .04       0  5011.4     .05       0
  5018.7      .1       0  5720.2     .05       0
Bank Sta=5005.4,5011.4
XS Rating Curve= 0 ,0
Exp/Cntr=0.3,0.1

Type RM Length L Ch R = 1 ,5055    ,114,114,114
BEGIN DESCRIPTION:
UNT00278 IN CHRS 6.0
END DESCRIPTION:
XS GIS Cut Line= 3
      3368820.47       10621629.       3368384.3     10621160.27
      3367800.84      10620466.2
#Sta/Elev= 30
  4456.7  625.66  4707.1   622.6  4828.7  623.02  4899.5  620.92  4934.7  622.55
  4956.2  621.31    4963   622.7  4970.4  621.04  4977.2  622.73  4984.5  620.71
  4991.4  622.73  4995.7  618.26  4998.5  617.76  5001.7  618.26  5005.5  623.16
  5012.9  620.06  5019.7  623.25  5033.9  620.84  5040.7  622.45  5126.1  623.59
  5168.7  622.67  5310.5  626.97  5480.8  628.36  5501.7  630.56  5523.8  629.45
  5610.4  630.86  5748.3  634.21  5821.6  636.97  5969.4  638.67  6003.7   639.3
#Mann= 8 ,-1 , 0
  4456.7     .08       0  4707.1     .05       0  4995.7     .04       0
  5001.7     .05       0  5126.1      .1       0  5610.4     .08       0
  5748.3      .1       0  5969.4     .08       0
Bank Sta=4995.7,5001.7
XS Rating Curve= 0 ,0
Exp/Cntr=0.3,0.1

Type RM Length L Ch R = 1 ,4941    ,135,135,135
BEGIN DESCRIPTION:
UNT00278 IN CHRS 6.2
END DESCRIPTION:
XS GIS Cut Line= 4
      3368876.95     10621616.04      3368644.71     10621327.38
      3368438.55     10621019.22      3367937.99     10620455.81
#Sta/Elev= 30
  4469.6  624.67  4547.5  623.43  4597.1  623.71    4733  621.46  4753.8  620.89
  4838.2  621.46  4868.4  619.95  4874.4  620.56  4889.4  619.08  4982.5  618.34
  4994.5  617.46  4997.3  616.96  5000.5  617.46  5012.5  618.88  5027.5  619.28
  5210.8  620.63  5309.1  623.36  5369.2  626.16  5413.5  626.85  5468.7  629.43
  5546.4  630.29  5595.8  630.76  5666.9   634.8  5741.9  635.22  5761.1  635.52
  5794.8  637.63  5815.8  636.91  5836.7   637.8  5907.3  638.05  5964.5  637.82
#Mann= 10 ,-1 , 0
  4469.6     .08       0    4733     .05       0  4994.5    .035       0
  5000.5     .05       0  5309.1      .1       0  5413.5     .05       0
  5546.4      .1       0  5741.9     .08       0  5761.1      .1       0
  5907.3     .08       0
Bank Sta=4994.5,5000.5
XS Rating Curve= 0 ,0
Exp/Cntr=0.3,0.1

Type RM Length L Ch R = 1 ,4806    ,164,164,164
BEGIN DESCRIPTION:
UNT00278 IN CHRS 6.9
END DESCRIPTION:
XS GIS Cut Line= 4
      3368917.01     10621596.13      3368716.49     10621288.85
      3368591.49     10620879.99      3368198.27     10620390.41
#Sta/Elev= 30
  4542.2   623.4  4556.9  623.19  4562.9  624.13    4584  624.45  4686.6  621.71
  4707.7  622.39  4774.2  621.94  4795.3  623.74  4801.2  622.52  4816.4  622.83
  4822.3  621.08  4831.5  621.13  4837.5  619.91  4852.6  619.17  4968.9  617.78
    4997  616.12  4999.8  615.62    5003  616.12  5052.6   618.5  5188.5  618.19
  5338.8  619.43  5363.1  620.69  5499.1  623.65  5555.1   627.3  5577.5  627.26
  5583.9  626.37  5711.9  631.29  5769.5  631.36  5825.5  632.79  5964.6   634.3
#Mann= 4 ,-1 , 0
  4542.2      .1       0    4997     .05       0    5003      .1       0
  5825.5      .1       0
#XS Ineff= 2 , 0
       0                 5119.09       0  620.81
Permanent Ineff=
       F       T
Bank Sta=4997,5003
XS Rating Curve= 0 ,0
Exp/Cntr=0.3,0.1

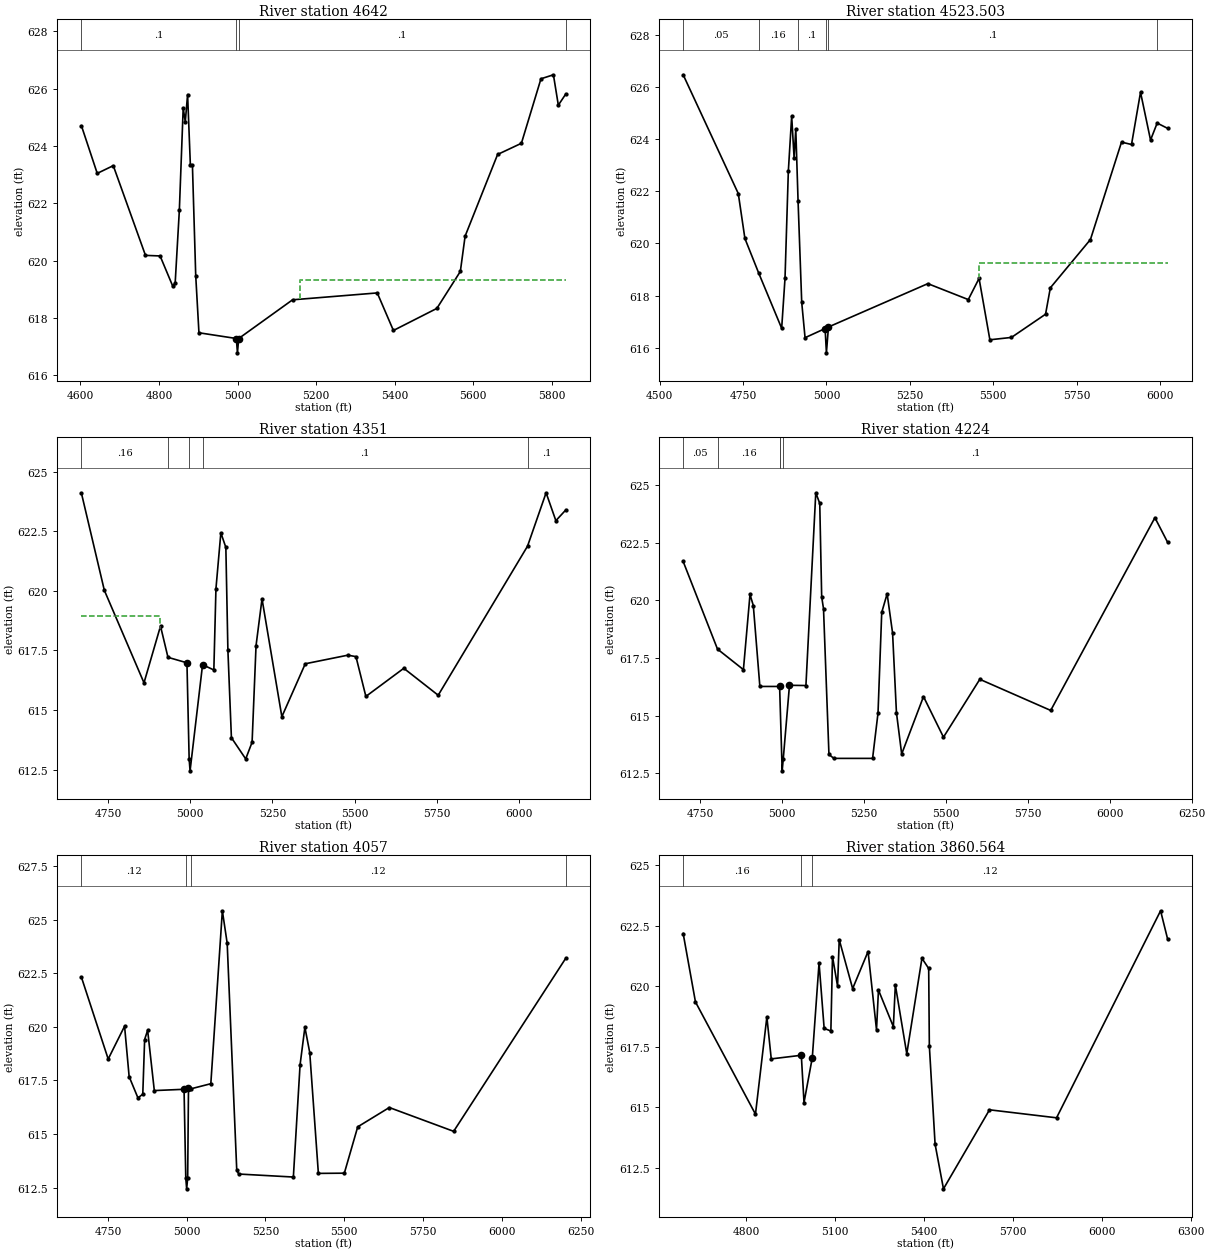
Type RM Length L Ch R = 1 ,4642    ,118.497,118.497,118.497
BEGIN DESCRIPTION:
UNT00278 IN CHRS 6.8
END DESCRIPTION:
XS GIS Cut Line= 4
      3368948.25      10621598.7      3368862.33     10621333.12
       3368721.7     10620731.55      3368566.29     10620433.67
#Sta/Elev= 30
  4602.7  624.71  4642.9  623.05  4683.7  623.32  4765.7  620.19  4802.9  620.17
    4835  619.12  4841.3  619.23  4851.9  621.76  4861.7  625.33    4867  624.85
  4872.9   625.8    4880  623.33  4885.2  623.33  4893.6  619.48  4901.8  617.49
    4997  617.29  4999.8  616.79    5003  617.29  5140.1  618.64  5355.7  618.88
  5396.8  617.57  5507.4  618.34  5567.2  619.63  5579.3  620.86    5662  623.71
  5722.6   624.1  5772.4  626.35  5804.1  626.49  5816.6  625.43  5835.6  625.82
#Mann= 4 ,-1 , 0
  4602.7      .1       0    4997     .07       0    5003      .1       0
  5835.6     .05       0
#XS Ineff= 2 , 0
       0                    5160       0  619.33
Permanent Ineff=
       F       T
Bank Sta=4997,5003
XS Rating Curve= 0 ,0
Exp/Cntr=0.3,0.1

Type RM Length L Ch R = 1 ,4523.503,172.503,172.503,172.503
BEGIN DESCRIPTION:
UNT00278 IN CHRS 6.1
END DESCRIPTION:
XS GIS Cut Line= 5
      3368976.31     10621666.32      3368943.76     10621099.95
      3368761.47     10620522.69      3368761.47      10620529.2
      3368609.75     10620302.93
#Sta/Elev= 30
  4570.5  626.46  4735.7  621.91  4755.5  620.19  4796.7  618.87  4865.7  616.75
  4875.7  618.66  4885.7  622.77  4895.7  624.87    4903  623.27    4908  624.38
  4914.8  621.64  4925.8  617.74  4935.8  616.39  4995.9  616.74  4999.8  615.81
  5005.9   616.8  5303.8  618.46    5425  617.85  5457.3  618.66  5489.7  616.31
  5554.3   616.4  5656.6  617.29  5670.9   618.3  5791.1  620.15  5884.2  623.88
  5914.2  623.79  5941.2  625.79  5971.2  623.96  5991.1  624.61  6022.1  624.41
#Mann= 6 ,-1 , 0
  4570.5     .05       0  4796.7     .16       0  4914.8      .1       0
  4999.8     .07       0  5005.9      .1       0  5991.1      .1       0
#XS Ineff= 2 , 0
       0 4890.91  619.31 5456.48       0  619.26
Permanent Ineff=
       T       T
Bank Sta=4995.9,5005.9
XS Rating Curve= 0 ,0
Exp/Cntr=0.3,0.1

Type RM Length L Ch R = 1 ,4351    ,127,127,127
BEGIN DESCRIPTION:
UNT00278 IN CHRS 6.7
END DESCRIPTION:
XS GIS Cut Line= 5
      3369091.49     10621590.94      3369127.95     10621213.33
       3368844.1     10620463.33       3368844.1     10620471.14
      3368682.68     10620237.84
#Sta/Elev= 30
  4669.5  624.09  4739.1  620.02  4859.7  616.14  4909.9  618.52  4932.6  617.21
  4990.3  616.98    4997  612.95  4999.8  612.45  5037.8   616.9  5072.1  616.68
  5078.5  620.09  5093.4  622.43  5108.6  621.82  5114.8  617.52  5125.5  613.84
    5169  612.95  5188.4  613.65  5200.4   617.7  5218.6  619.66  5278.9  614.72
  5350.1  616.94  5479.4   617.3  5504.2  617.24  5534.4  615.57  5649.7  616.75
  5754.3  615.62  6025.9  621.87  6082.4  624.11  6112.1  622.94  6142.3  623.39
#Mann= 5 ,-1 , 0
  4669.5     .16       0  4932.6      .1       0    4997     .07       0
  5037.8      .1       0  6025.9      .1       0
#XS Ineff= 2 , 0
       0 4907.27  618.96 5093.64       0  619.52
Permanent Ineff=
       T       T
Bank Sta=4990.3,5037.8
XS Rating Curve= 0 ,0
Exp/Cntr=0.3,0.1

Type RM Length L Ch R = 1 ,4224    ,167,167,167
BEGIN DESCRIPTION:
UNT00278 IN CHRS 6.6
END DESCRIPTION:
XS GIS Cut Line= 4
      3369278.99     10621564.87      3369242.54     10621153.43
      3368872.74     10620432.08      3368732.12     10620219.55
#Sta/Elev= 30
  4697.6  621.69  4802.4  617.89  4881.5     617  4901.6  620.26  4911.7  619.78
  4931.7  616.27    4992  616.27  4999.8  612.61    5003  613.11  5022.1  616.32
  5072.3  616.31  5102.4  624.67  5114.5  624.21  5120.4  620.16    5126  619.64
  5142.6  613.32  5157.6  613.15  5275.8  613.15  5292.4  615.12  5303.7  619.48
  5320.2  620.29  5336.8  618.59  5348.6  615.14  5364.6  613.34  5431.2  615.83
  5492.2  614.07  5603.1  616.58  5819.5  615.23  6137.6  623.59  6176.1  622.53
#Mann= 5 ,-1 , 0
  4697.6     .05       0  4802.4     .16       0    4992     .07       0
    4992     .07       0    5003      .1       0
#XS Ineff= 2 , 0
       0 4900.91   619.2 5117.27       0  619.66
Permanent Ineff=
       T       T
Bank Sta=4992,5022.1
XS Rating Curve= 0 ,0
Exp/Cntr=0.3,0.1

Type RM Length L Ch R = 1 ,4057    ,196.436,196.436,196.436
BEGIN DESCRIPTION:
UNT00278 IN CHRS 6.5
END DESCRIPTION:
XS GIS Cut Line= 3
      3369581.07     10621510.19      3368911.81     10620434.68
      3368758.16     10620211.74
#Sta/Elev= 30
  4665.8  622.31  4750.7   618.5  4802.7  620.03  4817.2  617.68  4845.1  616.69
  4860.5  616.86  4866.4  619.41  4875.9  619.84  4897.1  617.03  4991.5  617.09
    4997  612.95  4999.8  612.45    5003  612.95  5005.6  617.14  5012.8  617.11
  5076.5  617.35  5113.1  625.41  5128.4   623.9  5158.8  613.32    5165  613.14
  5338.5     613  5359.8  618.23  5375.1  619.98  5390.5   618.8  5417.9  613.17
  5500.3  613.18  5542.8  615.34  5643.1  616.24  5847.3  615.13  6203.3   623.2
#Mann= 4 ,-1 , 0
  4665.8     .12       0    4997      .1       0  5012.8     .12       0
  6203.3      .1       0
#XS Ineff= 2 , 0
       0 4872.05  619.01 5132.84       0  619.06
Permanent Ineff=
       T       T
Bank Sta=4991.5,5005.6
XS Rating Curve= 0 ,0
Exp/Cntr=0.3,0.1

Type RM Length L Ch R = 1 ,3860.564,165.564,165.564,165.564
BEGIN DESCRIPTION:
UNT00278 IN CHRS 5.0
END DESCRIPTION:
XS GIS Cut Line= 6
      3369705.49     10621490.61      3369481.95      10620928.5
      3369395.15     10620852.55      3369293.15     10620804.81
      3368954.61     10620451.07      3368781.63     10620190.95
#Sta/Elev= 30
  4586.4  622.17  4627.9  619.35  4830.5  614.72    4869  618.73  4883.8     617
  4985.3  617.15 4994.43   615.2  5022.4  617.05  5045.2  620.96  5062.4  618.26
  5085.1  618.15  5090.6  621.22  5107.7     620  5113.3  621.92  5158.6   619.9
  5210.7  621.43  5239.2   618.2  5245.8  619.84  5296.1  618.33  5302.8  620.05
  5341.4  617.21  5392.6  621.15  5415.4  620.73  5417.6  617.54    5437  613.48
  5465.3  611.64  5620.7   614.9  5847.1  614.57  6198.4  623.11  6221.8  621.96
#Mann= 3 , 0 , 0
  4586.4     .16       0  4985.3     .07       0  5022.4     .12       0
#XS Ineff= 2 , 0
       0 4869.06  618.71  5044.8       0  620.88
Permanent Ineff=
       T       T
Bank Sta=4985.3,5022.4
XS Rating Curve= 0 ,0
Exp/Cntr=0.3,0.1

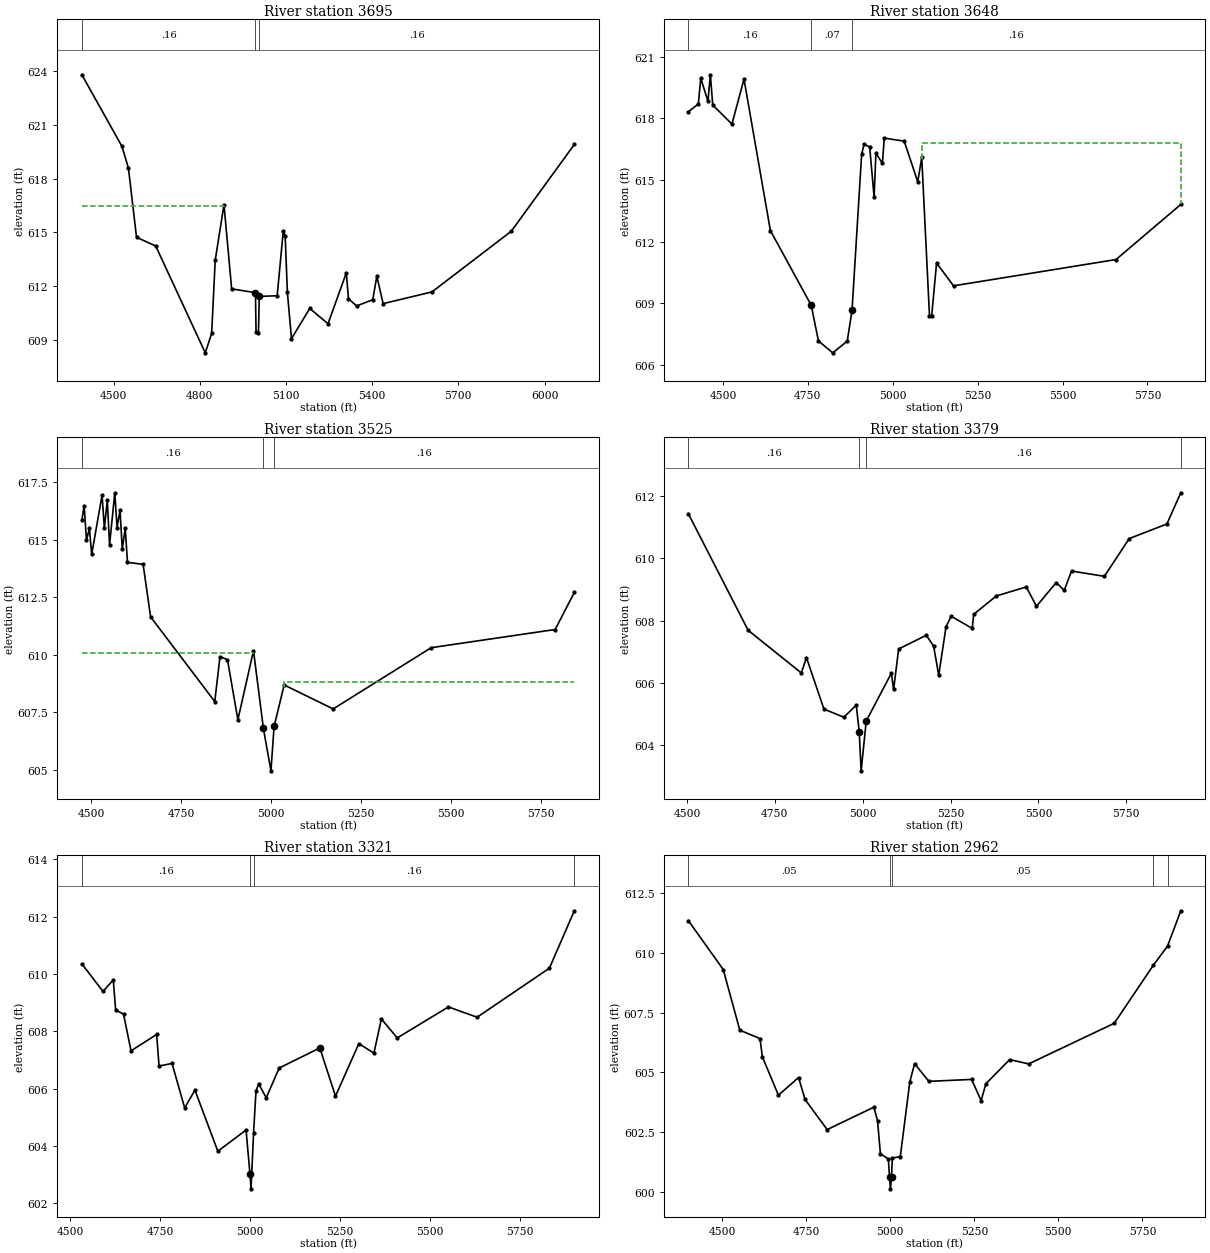
Type RM Length L Ch R = 1 ,3695    ,47,47,47
BEGIN DESCRIPTION:
UNT00278 IN CHRS 3.9
END DESCRIPTION:
XS GIS Cut Line= 6
      3369953.32     10621446.17      3369747.14     10621040.32
      3369731.95     10620975.22      3369712.42     10620953.51
      3369580.04     10620936.15      3368902.94     10620161.39
#Sta/Elev= 30
  4389.8  623.78  4529.5  619.79  4551.9  618.58  4580.1  614.73  4646.8  614.25
  4819.3   608.3  4841.5  609.38  4853.9  613.45  4884.4  616.55  4911.1  611.86
  4993.9  611.65 4996.04  609.46 5004.48  609.43  5007.1  611.44  5069.5  611.48
  5090.8  615.09  5097.4   614.8    5105  611.68  5119.3  609.09  5182.9  610.77
  5246.5  609.92  5310.1  612.75  5317.7  611.31  5346.1  610.91  5402.1  611.26
  5416.4  612.57  5438.2  611.04  5608.1  611.69  5884.3  615.07  6103.6   619.9
#Mann= 3 , 0 , 0
  4389.8     .16       0  4993.9     .07       0  5007.1     .16       0
#XS Ineff= 2 , 0
       0 4883.17   616.5 5091.09       0  615.05
Permanent Ineff=
       T       T
Bank Sta=4993.9,5007.1
XS Rating Curve= 0 ,0
Exp/Cntr=0.3,0.1

Type RM Length L Ch R = 1 ,3648    ,123,123,123
BEGIN DESCRIPTION:
UNT00278 IN CHRS 3.4
END DESCRIPTION:
XS GIS Cut Line= 5
      3370132.99     10621312.62      3369748.88     10620941.52
       3369681.6     10620915.48      3369607.82      10620906.8
      3369143.41     10620292.65
#Sta/Elev= 30
  4397.9  618.32  4427.4   618.7  4434.6  619.95  4455.7  618.83  4462.9  620.12
  4469.8  618.65  4526.4  617.72  4561.9  619.91  4639.6  612.54    4760   608.9
  4781.1  607.17  4823.3  606.59    4866  607.16  4880.1  608.66  4908.4  616.25
  4915.4  616.73    4932  616.62  4945.1  614.17  4950.4   616.3  4969.6  615.81
    4975  617.04  5033.8  616.89  5073.7  614.91  5085.4   616.1  5108.2   608.4
  5114.5  608.36  5129.1  610.96    5179  609.85  5657.6  611.13  5848.4  613.81
#Mann= 3 , 0 , 0
  4397.9     .16       0    4760     .07       0  4880.1     .16       0
#XS Ineff= 2 , 0
       0                 5085.68       0  616.79
Permanent Ineff=
       F       T
Bank Sta=4760,4880.1
XS Rating Curve= 0 ,0
Exp/Cntr=0.3,0.1

Type RM Length L Ch R = 1 ,3525    ,146,146,146
BEGIN DESCRIPTION:
UNT00278 IN CHRS 3.3
END DESCRIPTION:
XS GIS Cut Line= 4
      3370208.92     10621243.15        3369827.     10620945.87
      3369651.22     10620691.96      3369308.35     10620229.74
#Sta/Elev= 30
  4474.7  615.85  4481.1  616.48  4487.5  614.97  4495.6   615.5    4502  614.36
  4530.9  616.94  4537.2  615.51  4545.4  616.71  4551.7  614.78  4566.2  617.04
  4572.5  615.52  4580.7  616.28    4587  614.61  4595.2  615.49  4601.5  614.02
  4644.9  613.93  4665.7  611.65    4844  607.97  4858.5  609.92  4879.3  609.79
  4908.2  607.18  4951.6  610.18  4979.1   606.8  5000.1  604.96  5008.8  606.89
  5036.8  608.69    5173  607.65  5445.3  610.31  5789.7   611.1    5843  612.71
#Mann= 3 , 0 , 0
  4474.7     .16       0  4979.1     .07       0  5008.8     .16       0
#XS Ineff= 2 , 0
       0  4949.5  610.09 5035.45       0  608.82
Permanent Ineff=
       T       T
Bank Sta=4979.1,5008.8
XS Rating Curve= 0 ,0
Exp/Cntr=0.3,0.1

Type RM Length L Ch R = 1 ,3379    ,58,58,58
BEGIN DESCRIPTION:
UNT00278 IN CHRS 3.1
END DESCRIPTION:
XS GIS Cut Line= 5
      3370319.65     10621182.43      3370026.66     10620974.08
      3369887.77     10620822.17       3369740.2     10620633.37
      3369377.81      10620160.3
#Sta/Elev= 30
    4504  611.43  4674.1  607.69  4825.4  606.32  4840.1  606.81  4889.8  605.16
  4946.6   604.9  4981.7  605.29  4990.1  604.44  4995.6  603.18  5010.1  604.78
  5081.5  606.31  5087.9  605.79  5102.3  607.09    5181  607.53  5201.8  607.18
  5216.3  606.25  5237.1   607.8  5251.6  608.14  5311.5  607.75  5315.8   608.2
  5380.1  608.79  5465.3  609.08  5494.4  608.46  5550.5  609.22  5573.3  608.97
  5594.1  609.59  5687.5  609.42  5758.2  610.63  5865.4   611.1  5904.9   612.1
#Mann= 4 ,-1 , 0
    4504     .16       0  4990.1     .12       0  5010.1     .16       0
  5904.9      .1       0
Bank Sta=4990.1,5010.1
XS Rating Curve= 0 ,0
Exp/Cntr=0.3,0.1

Type RM Length L Ch R = 1 ,3321    ,359,359,359
BEGIN DESCRIPTION:
UNT00278 IN CHRS 3.2
END DESCRIPTION:
XS GIS Cut Line= 4
      3370332.62     10621154.17      3370004.96     10620867.74
      3369850.88     10620694.13      3369438.56     10620127.74
#Sta/Elev= 30
  4532.9  610.35  4591.6  609.39  4620.1  609.79  4626.8  608.74  4648.6   608.6
  4669.5  607.32  4740.7  607.89  4747.3  606.79  4783.4  606.88  4818.5  605.33
    4847  605.95  4910.6  603.82    4989  604.56    5000  603.01  5002.8  602.51
  5009.9  604.47  5016.6  605.92  5024.1  606.17    5045  605.68    5081  606.72
  5193.9  607.42  5237.4  605.74  5302.3  607.57  5344.1  607.24  5364.9  608.43
    5409  607.77  5551.1  608.85  5630.7  608.49  5831.6   610.2  5900.8   612.2
#Mann= 4 ,-1 , 0
  4532.9     .16       0    5000     .12       0  5009.9     .16       0
  5900.8      .1       0
Bank Sta=5000,5193.9
XS Rating Curve= 0 ,0
Exp/Cntr=0.3,0.1

Type RM Length L Ch R = 1 ,2962    ,228,228,228
BEGIN DESCRIPTION:
UNT00278 IN CHRS 3.0
END DESCRIPTION:
XS GIS Cut Line= 3
      3370412.94     10621167.22      3370192.11     10620591.64
      3369592.11     10619991.65
#Sta/Elev= 30
  4399.2  611.35  4503.1   609.3  4552.4  606.76  4612.5  606.41  4619.4  605.65
  4667.2  604.04  4727.2  604.78  4746.5  603.86  4812.2   602.6  4951.4  603.54
  4962.1  602.97  4970.6  601.59  4994.3  601.37  4997.7  600.62  5000.4  600.12
  5003.7  600.62    5006  601.41  5029.8  601.47  5058.1   604.6  5072.3  605.36
  5114.7  604.62    5242   604.7  5270.2  603.81  5284.4  604.52  5355.1  605.53
  5411.7  605.35  5666.2  607.05    5783  609.49  5824.7  610.28  5864.2  611.76
#Mann= 5 ,-1 , 0
  4399.2     .05       0  4997.7     .03       0  5003.7     .05       0
    5783      .1       0  5824.7     .05       0
Bank Sta=4997.7,5003.7
XS Rating Curve= 0 ,0
Exp/Cntr=0.3,0.1