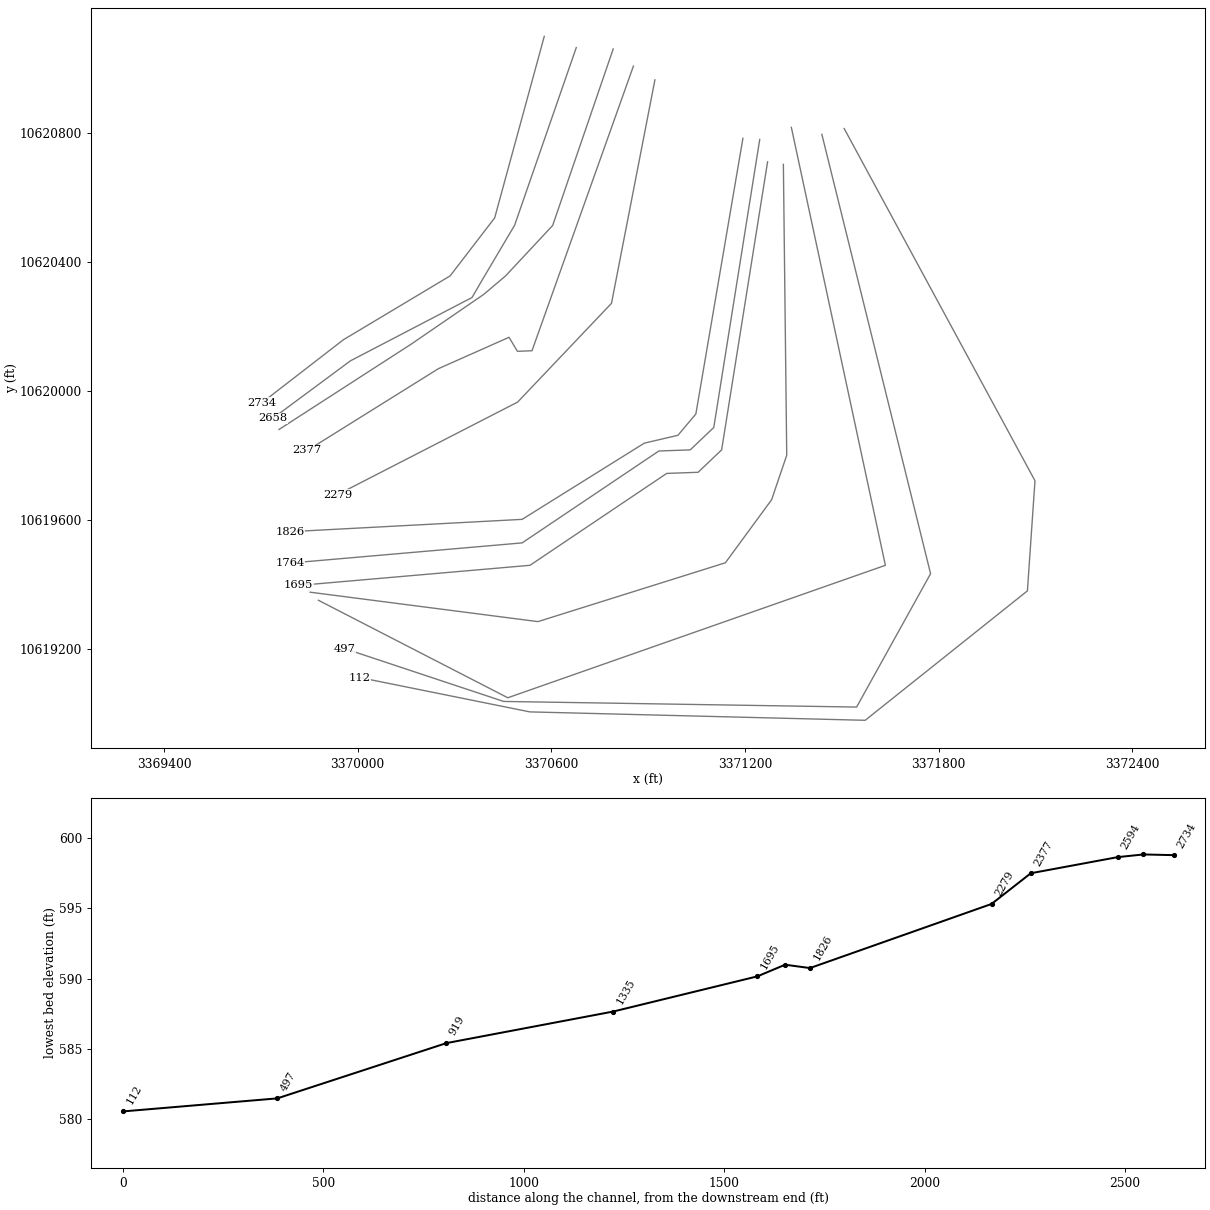
HEC-RAS study UNT00278 IN CHRS.prj: UNT00278 IN CHRS Base Level Engineering

--- UNT00278 IN CHRS.g01 (geometry) --- (continued)

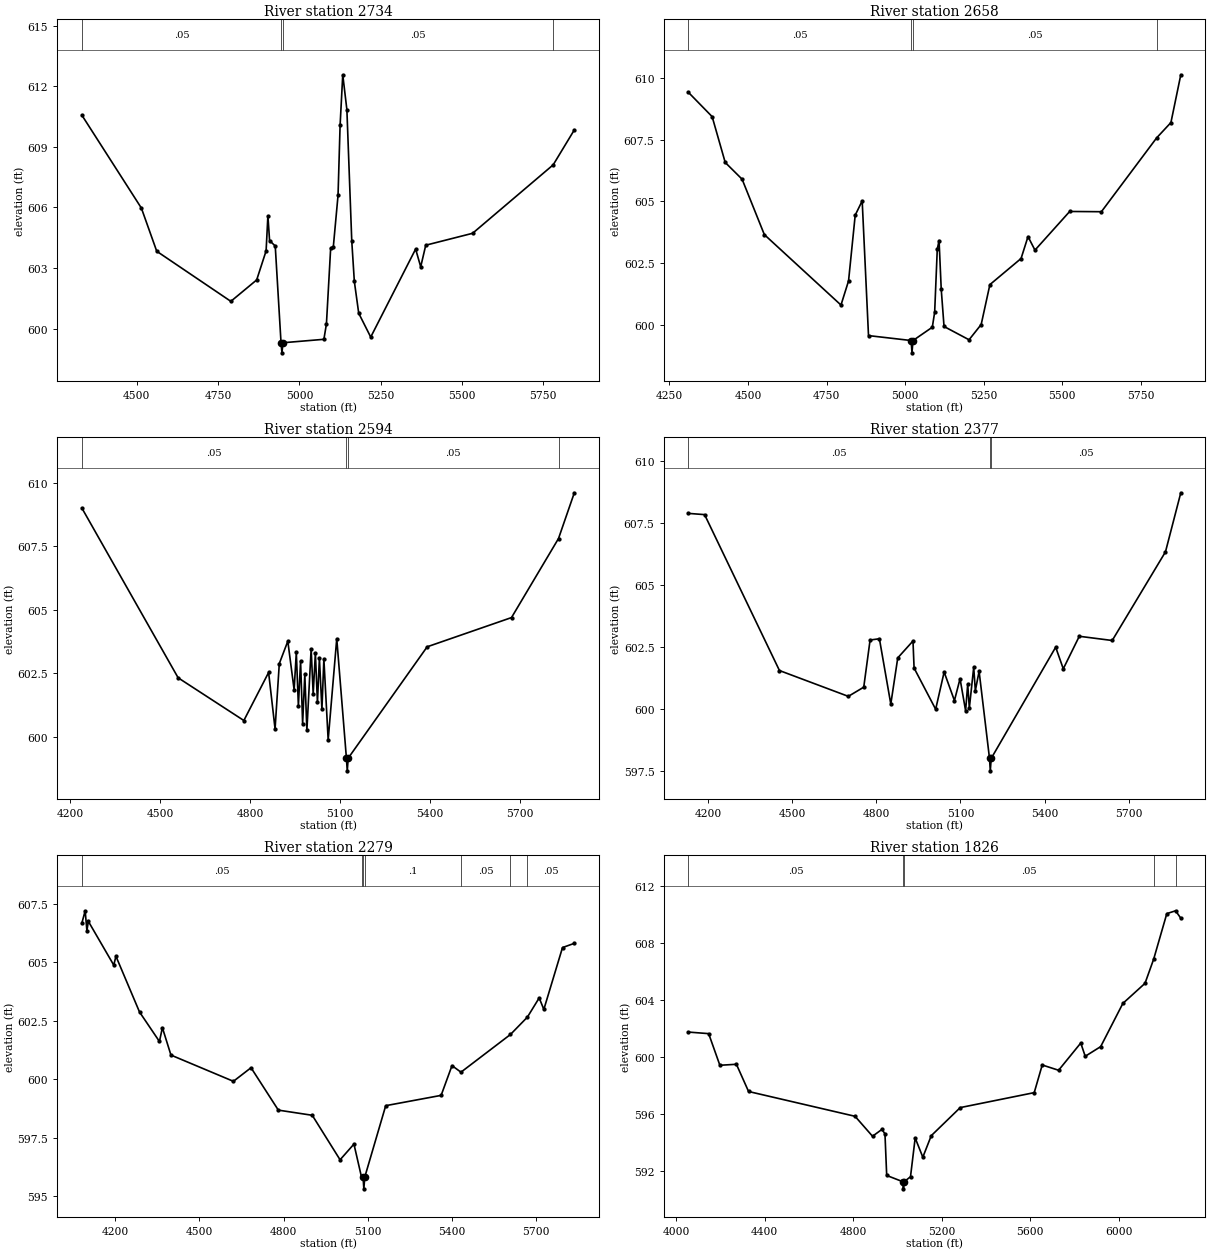
Type RM Length L Ch R = 1 ,2734    ,76,76,76
BEGIN DESCRIPTION:
UNT00278 IN CHRS 3.5
END DESCRIPTION:
XS GIS Cut Line= 5
      3370577.97     10621098.18      3370424.32     10620535.69
       3370286.3       10620356.      3369955.57     10620158.09
      3369702.97     10619962.78
#Sta/Elev= 30
    4331  610.57    4514  605.97  4561.3  603.83  4789.2  601.35  4868.6  602.41
  4897.6  603.85  4903.1  605.59  4908.3  604.36  4925.7  604.09  4943.5   599.3
  4946.3   598.8  4949.5   599.3  5075.3  599.47  5083.1  600.23  5096.1  603.98
  5104.3  604.05  5118.8   606.6  5125.1  610.06  5133.3  612.57    5146  610.84
    5161  604.34  5168.9  602.34  5182.4  600.76  5219.3  599.58  5357.4  603.94
    5373  603.06  5388.5  604.13  5532.6  604.72  5780.4  608.11  5845.4  609.84
#Mann= 4 ,-1 , 0
    4331     .05       0  4943.5    .033       0  4949.5     .05       0
  5780.4      .1       0
Bank Sta=4943.5,4949.5
XS Rating Curve= 0 ,0
Exp/Cntr=0.3,0.1

Type RM Length L Ch R = 1 ,2658    ,64,64,64
BEGIN DESCRIPTION:
UNT00278 IN CHRS 3.8
END DESCRIPTION:
XS GIS Cut Line= 6
      3370677.08     10621063.28      3370486.12     10620512.97
      3370385.42     10620342.83      3370354.17     10620289.01
      3369977.44     10620092.83      3369736.64     10619914.39
#Sta/Elev= 30
  4309.9  609.43  4385.7  608.44  4427.3  606.58    4481   605.9  4551.8  603.65
  4795.6  600.79  4819.7  601.77  4840.9  604.44  4863.1  605.02  4883.2  599.55
  5018.8  599.35  5021.5  598.85  5024.8  599.35  5086.2  599.89  5093.7   600.5
    5102  603.06  5107.7  603.41  5114.6  601.43  5123.5  599.92  5203.1  599.38
  5241.7     600  5269.4  601.62  5368.6  602.68  5390.7  603.57  5412.8  603.02
  5523.3  604.59  5624.2  604.58  5800.1  607.58  5845.4   608.2  5876.8  610.14
#Mann= 4 ,-1 , 0
  4309.9     .05       0  5018.8    .033       0  5024.8     .05       0
  5800.1      .1       0
Bank Sta=5018.8,5024.8
XS Rating Curve= 0 ,0
Exp/Cntr=0.3,0.1

Type RM Length L Ch R = 1 ,2594    ,217,217,217
BEGIN DESCRIPTION:
UNT00278 IN CHRS 3.7
END DESCRIPTION:
XS GIS Cut Line= 6
      3370791.51     10621059.11      3370604.01     10620512.25
      3370458.18       10620356.      3370390.47     10620298.71
      3370166.51     10620145.07      3369756.05     10619880.08
#Sta/Elev= 30
  4239.3     609  4560.1  602.32    4779  600.64  4861.5  602.53    4883  600.31
  4897.1  602.88  4925.5  603.76  4946.5  601.85  4953.8  603.32  4960.7  601.21
    4968  602.98  4974.8  600.51  4982.1  602.46    4989  600.25  5003.2  603.46
    5010  601.69  5017.3  603.29  5024.2  601.35  5030.7   603.1  5039.1  601.08
  5045.6  603.06  5059.9  599.88  5088.5  603.86  5120.7  599.16  5123.5  598.66
  5126.7  599.16  5389.7  603.54  5670.7  604.69  5827.3   607.8    5880   609.6
#Mann= 4 ,-1 , 0
  4239.3     .05       0  5120.7    .033       0  5126.7     .05       0
  5827.3      .1       0
Bank Sta=5120.7,5126.7
XS Rating Curve= 0 ,0
Exp/Cntr=0.3,0.1

Type RM Length L Ch R = 1 ,2377    ,98,98,98
BEGIN DESCRIPTION:
UNT00278 IN CHRS 3.6
END DESCRIPTION:
XS GIS Cut Line= 6
      3370854.16     10621005.98      3370539.94     10620124.08
       3370494.8     10620122.34      3370468.76     10620165.74
      3370250.01     10620068.52      3369843.75     10619815.04
#Sta/Elev= 30
    4130  607.88    4188  607.83  4454.8  601.55  4700.2  600.51  4755.2  600.88
  4777.8  602.78    4811  602.83  4851.6   600.2  4876.4  602.06  4930.7  602.74
  4934.6  601.65  5011.5  599.99  5041.7  601.49  5078.4  600.34  5098.4  601.22
  5118.2  599.93  5125.7     601  5131.5  600.04  5147.1  601.68  5152.9  600.74
  5166.3  601.52  5203.4  598.01  5206.2  597.51  5209.4  598.01  5439.2  602.49
  5466.3  601.62  5523.4  602.93  5640.7  602.76  5830.5  606.33  5885.1  608.71
#Mann= 3 ,-1 , 0
    4130     .05       0  5203.4    .035       0  5209.4     .05       0
Bank Sta=5203.4,5209.4
XS Rating Curve= 0 ,0
Exp/Cntr=0.3,0.1

Type RM Length L Ch R = 1 ,2279    ,453,453,453
BEGIN DESCRIPTION:
UNT00278 IN CHRS 5.1
END DESCRIPTION:
XS GIS Cut Line= 4
      3370920.76     10620963.24      3370786.21     10620270.95
      3370495.41     10619964.96      3369937.64     10619678.48
#Sta/Elev= 30
    4081  606.66  4092.8  607.19    4099  606.34  4104.1  606.74  4194.7  604.87
  4202.4  605.25  4286.4  602.87  4357.4  601.61  4367.9   602.2  4398.4  601.03
  4620.9  599.91  4683.7  600.49    4781  598.68  4901.8  598.46  5000.9  596.56
  5050.3  597.23  5077.3  595.82  5082.8  595.82  5085.6  595.32  5088.8  595.82
  5163.5  598.87  5360.9  599.31  5399.6  600.58  5431.6   600.3  5607.9  601.91
  5668.2  602.65  5710.2  603.47  5726.8  602.98  5793.3  605.62  5835.4   605.8
#Mann= 7 ,-1 , 0
    4081     .05       0  5077.3      .1       0  5082.8    .035       0
  5088.8      .1       0  5431.6     .05       0  5607.9     .08       0
  5668.2     .05       0
Bank Sta=5082.8,5088.8
XS Rating Curve= 0 ,0
Exp/Cntr=0.3,0.1

Type RM Length L Ch R = 1 ,1826    ,62,62,62
BEGIN DESCRIPTION:
UNT00278 IN CHRS 2.0
END DESCRIPTION:
XS GIS Cut Line= 6
      3371193.43     10620782.25      3371047.59     10619928.05
      3370992.03     10619862.08      3370887.87     10619837.77
      3370509.39     10619601.66      3369790.66     10619563.47
#Sta/Elev= 30
  4054.5  601.75  4146.4  601.64  4197.1  599.42  4271.8  599.49  4326.8  597.58
    4808  595.84    4887  594.44  4929.4  594.92  4943.2  594.61    4951  591.69
  5023.9  591.25  5026.7  590.75  5029.9  591.25  5058.6   591.6  5079.7  594.32
  5114.3  592.97  5152.4  594.48  5283.3  596.45  5617.7   597.5  5653.9  599.44
  5727.9  599.07    5828  600.98  5848.2  600.05  5918.1  600.73  6018.3  603.76
  6118.4  605.17  6157.6  606.87  6216.9  610.06  6256.5  610.26  6280.1  609.74
#Mann= 5 ,-1 , 0
  4054.5     .05       0  5023.9     .03       0  5029.9     .05       0
  6157.6     .08       0  6256.5      .1       0
Bank Sta=5023.9,5029.9
XS Rating Curve= 0 ,0
Exp/Cntr=0.3,0.1

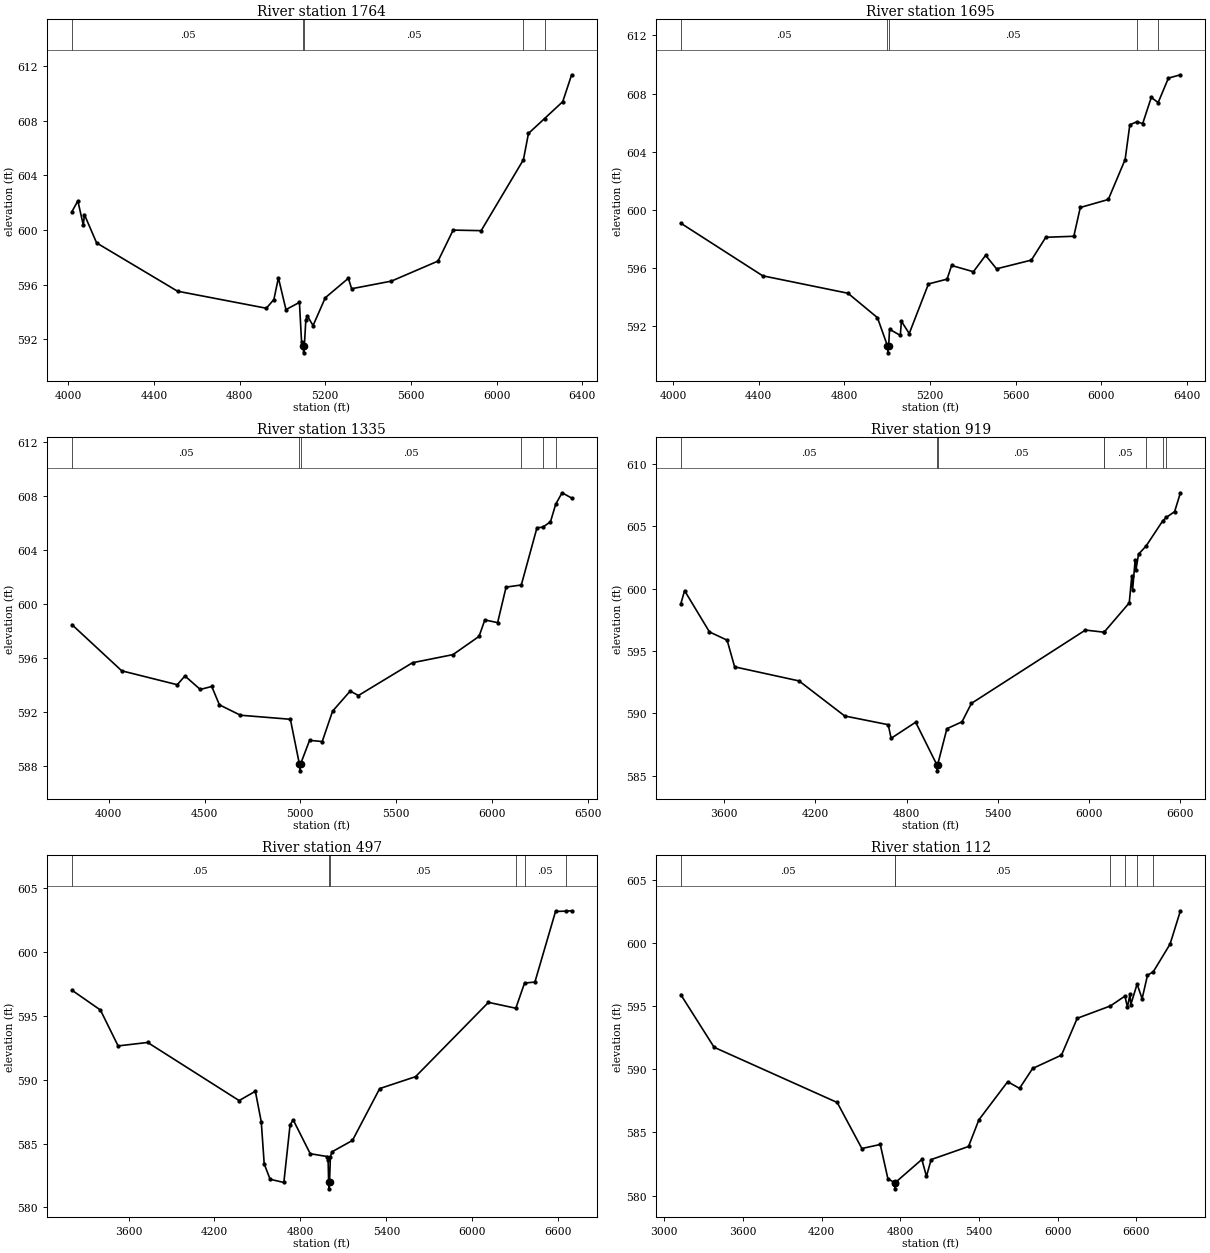
Type RM Length L Ch R = 1 ,1764    ,69,69,69
BEGIN DESCRIPTION:
UNT00278 IN CHRS 2.2
END DESCRIPTION:
XS GIS Cut Line= 6
      3371245.51     10620778.78      3371103.14     10619886.39
      3371030.23     10619816.94        3370933.     10619813.47
      3370509.39     10619528.75      3369790.67     10619466.25
#Sta/Elev= 30
  4016.8  601.35  4044.3  602.13  4069.9  600.35  4074.9  601.13    4132  599.05
  4509.8  595.51  4924.6  594.26    4960   594.9  4981.1  596.49  5016.4  594.16
  5079.3  594.69  5089.3  591.79  5096.3  591.49  5099.1  590.99  5102.3  591.49
  5109.3  593.42  5116.4  593.69  5143.1  592.99  5200.1  595.03  5308.1  596.46
  5323.1  595.69  5509.1  596.25  5726.8  597.72  5797.3  599.99  5928.2  599.95
  6125.6  605.15  6149.2  607.08  6224.4  608.17  6309.3  609.41  6350.8  611.38
#Mann= 5 ,-1 , 0
  4016.8     .05       0  5096.3    .035       0  5102.3     .05       0
  6125.6     .08       0  6224.4      .1       0
Bank Sta=5096.3,5102.3
XS Rating Curve= 0 ,0
Exp/Cntr=0.3,0.1

Type RM Length L Ch R = 1 ,1695    ,360,360,360
BEGIN DESCRIPTION:
UNT00278 IN CHRS 2.1
END DESCRIPTION:
XS GIS Cut Line= 6
      3371269.82     10620709.34      3371127.45     10619816.94
      3371054.53      10619747.5      3370957.31     10619744.02
       3370533.7      10619459.3      3369815.98     10619396.84
#Sta/Elev= 30
  4036.4  599.08  4418.9  595.46  4817.1  594.26  4954.7  592.58  5001.1  590.66
  5003.8  590.16  5007.1  590.66  5011.3  591.78  5061.5  591.36  5066.5  592.33
  5103.2  591.49  5192.9   594.9  5279.8  595.23    5301  596.17  5402.8  595.74
  5459.8  596.87  5510.8  595.94  5673.4  596.54  5740.7  598.11  5871.6  598.18
  5901.8  600.16  6032.6  600.71  6111.2  603.46  6133.1  605.85  6166.7  606.06
  6193.1  605.93  6233.2  607.73  6265.5  607.38  6313.2  609.06  6369.4  609.29
#Mann= 5 ,-1 , 0
  4036.4     .05       0  5001.1    .035       0  5007.1     .05       0
  6166.7     .08       0  6265.5      .1       0
Bank Sta=5001.1,5007.1
XS Rating Curve= 0 ,0
Exp/Cntr=0.3,0.1

Type RM Length L Ch R = 1 ,1335    ,416,416,416
BEGIN DESCRIPTION:
UNT00278 IN CHRS 1.8
END DESCRIPTION:
XS GIS Cut Line= 6
      3371318.76     10620701.55      3371329.17     10619800.47
       3371282.3     10619662.45      3371139.07     10619467.13
      3370558.34     10619284.84      3369852.58     10619375.99
#Sta/Elev= 30
  3807.6  598.48  4067.5  595.06  4357.5  594.03  4397.5  594.68  4477.6  593.68
  4537.6   593.9  4577.6  592.54  4687.6  591.77  4948.2  591.47  4995.3  588.15
  4998.1  587.65  5001.3  588.15  5048.5  589.91  5114.5  589.82  5168.6  592.07
  5260.6  593.56  5303.5  593.23  5586.1  595.66  5797.4  596.26  5933.5  597.61
  5963.7  598.83  6030.5  598.63  6074.7  601.26  6154.3  601.42    6236  605.66
  6266.2   605.7  6306.6   606.1  6333.8   607.4  6367.1  608.25    6417  607.86
#Mann= 6 ,-1 , 0
  3807.6     .05       0  4995.3     .03       0  5001.3     .05       0
  6154.3     .08       0  6266.2      .1       0  6333.8     .08       0
Bank Sta=4995.3,5001.3
XS Rating Curve= 0 ,0
Exp/Cntr=0.3,0.1

Type RM Length L Ch R = 1 ,919     ,422,422,422
BEGIN DESCRIPTION:
UNT00278 IN CHRS 1.9
END DESCRIPTION:
XS GIS Cut Line= 4
      3371343.41     10620816.23      3371634.77     10619459.28
      3370464.92     10619048.91      3369878.13     10619350.99
#Sta/Elev= 30
  3313.7  598.78  3338.8  599.85  3502.5  596.54  3618.6  595.88    3668  593.74
    4092  592.61  4392.3   589.8  4678.7   589.1  4697.8  588.01  4859.3   589.3
  4998.1   585.9  5000.9   585.4  5004.1   585.9  5064.7  588.78    5164  589.33
    5226  590.81  5976.3  596.69  6096.6  596.52  6099.2  596.52  6264.6  598.87
  6281.1  601.01  6286.7  599.93  6303.3   602.3  6308.9  601.52  6325.4  602.77
  6376.5  603.45  6484.9  605.45  6509.2  605.73  6563.1  606.19  6601.3   607.7
#Mann= 8 ,-1 , 0
  3313.7     .05       0  4998.1     .03       0  5004.1     .05       0
  6096.6      .1       0  6099.2     .05       0  6376.5     .08       0
  6484.9      .1       0  6509.2     .08       0
Bank Sta=4998.1,5004.1
XS Rating Curve= 0 ,0
Exp/Cntr=0.3,0.1

Type RM Length L Ch R = 1 ,497     ,385,385,385
BEGIN DESCRIPTION:
UNT00278 IN CHRS 1.9
END DESCRIPTION:
XS GIS Cut Line= 5
      3371438.02     10620794.43      3371774.83     10619433.32
      3371545.66     10619020.12      3370452.09     10619037.54
      3369958.78     10619201.44
#Sta/Elev= 30
    3205  597.01  3403.6  595.46  3527.2  592.65  3733.3  592.92    4372  588.37
  4485.3   589.1  4526.5  586.71  4547.1  583.41  4588.3  582.21  4684.2  581.96
  4727.7  586.47  4749.4  586.86  4868.4  584.21  4986.4  583.99  4993.2  583.73
    4997  581.96  4999.8  581.46    5003  581.96  5009.2  583.99  5020.7  584.36
  5163.2  585.25  5353.3  589.31  5603.3  590.24  6112.7  596.06  6303.6   595.6
  6364.5  597.57  6436.8  597.65  6580.9  603.18  6652.9   603.2  6693.2  603.23
#Mann= 6 ,-1 , 0
    3205     .05       0    4997     .03       0    5003     .05       0
  6303.6      .1       0  6364.5     .05       0  6652.9     .08       0
#XS Ineff= 2 , 0
       0 4706.79  583.89               0
Permanent Ineff=
       T       F
Bank Sta=4997,5003
XS Rating Curve= 0 ,0
Exp/Cntr=0.3,0.1

Type RM Length L Ch R = 1 ,112     ,0,0,0
BEGIN DESCRIPTION:
UNT00278 IN CHRS 1.0
END DESCRIPTION:
XS GIS Cut Line= 6
      3371507.14     10620812.41      3372098.27      10619721.3
      3372074.83     10619380.15      3371572.23     10618979.11
      3370533.17     10619005.15      3370005.82     10619111.66
#Sta/Elev= 30
    3126  595.94  3380.3  591.76    4319  587.38  4506.9  583.73  4647.3  584.05
  4705.7  581.32  4756.3  581.03    4759  580.53  4762.3  581.03  4964.3  582.86
  4999.7  581.52    5035  582.85  5320.3  583.89    5399     586    5619  589.03
  5709.1   588.5  5809.1  590.08  6029.2  591.14  6149.2  594.06  6402.1  595.04
  6512.9  595.82  6531.9  594.95  6552.2  595.99  6557.3  595.13  6605.6  596.77
  6644.1  595.62  6684.9  597.47  6729.6  597.76  6856.8  599.94  6936.2  602.59
#Mann= 7 ,-1 , 0
    3126     .05       0  4756.3     .03       0  4762.3     .05       0
  6402.1      .1       0  6512.9     .05       0  6605.6      .1       0
  6729.6     .05       0
Bank Sta=4756.3,4762.3
XS Rating Curve= 0 ,0
Exp/Cntr=0.3,0.1

Chan Stop Cuts=-1
Use User Specified Reach Order=0
Composite Channel Slope=5