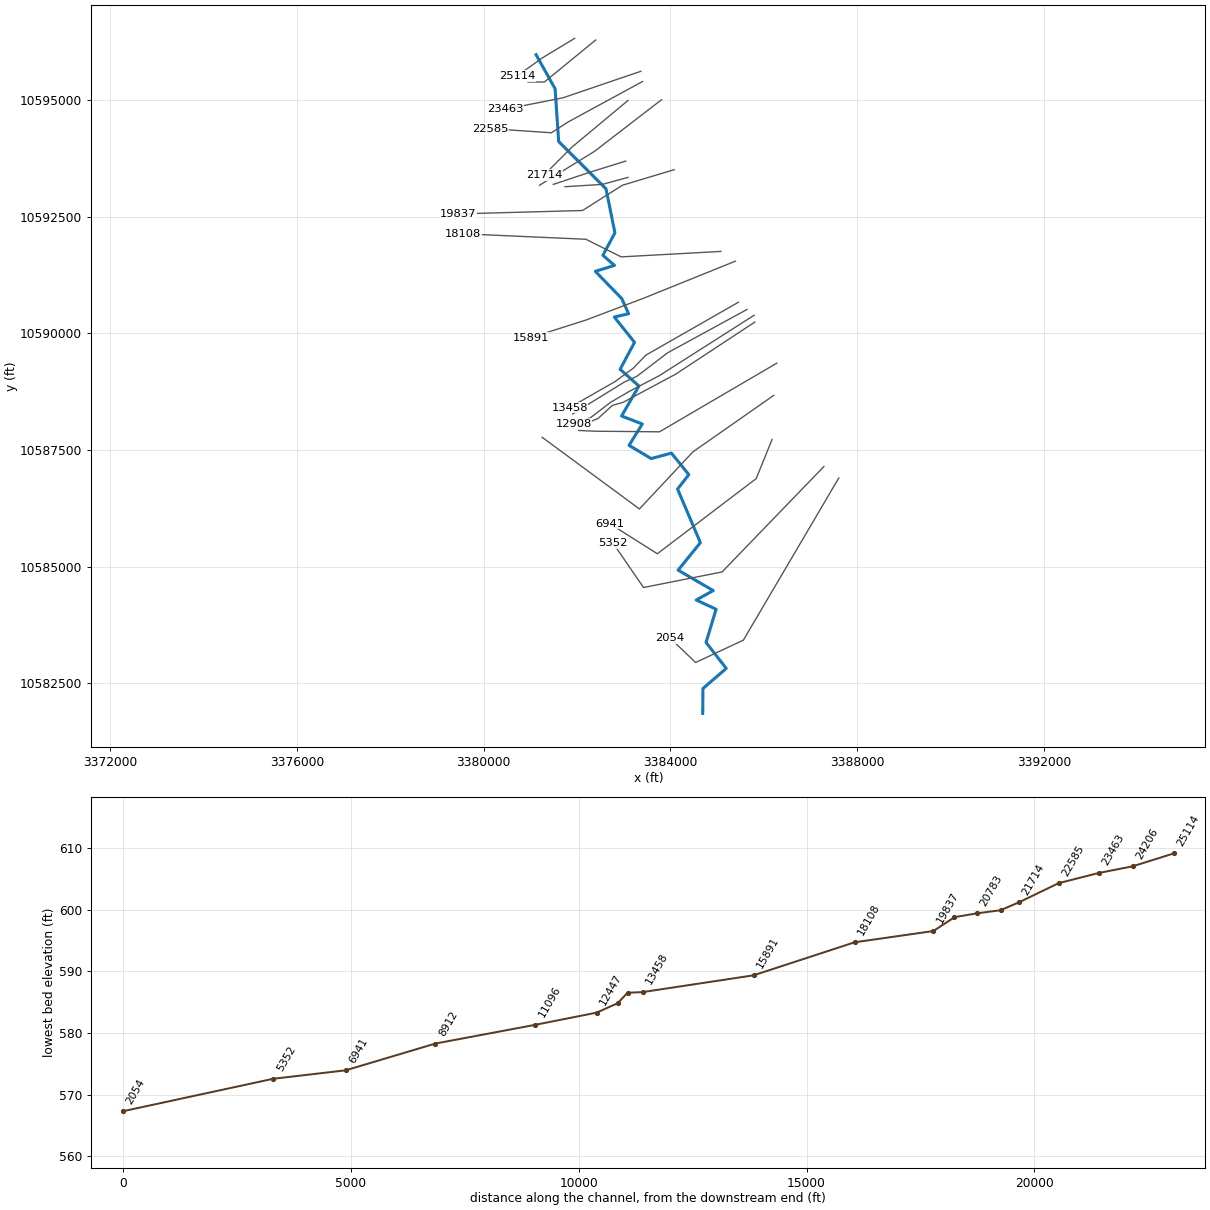
--- UNT0029 IN CHRS.prj (project) ---

Proj Title=UNT0029 IN CHRS Base Level Engineering
Current Plan=p01
Default Exp/Contr=0.3,0.1
English Units
Geom File=g01
Flow File=f01
Plan File=p01
Y Axis Title=Elevation
X Axis Title(PF)=Main Channel Distance
X Axis Title(XS)=Station
BEGIN DESCRIPTION:
UNT0029 IN CHRS
END DESCRIPTION:
DSS Export Rating Curves= 0
DSS Export Rating Curve Sorted= 0
DSS Export Volume Flow Curves= 0
DXF OffsetX= 0
DXF OffsetY= 0
DXF ScaleX= 1
DXF ScaleY= 10

--- UNT0029 IN CHRS.p01 (plan) ---

Plan Title=Multiple Run
Short Identifier=Multiple
Geom File=g01
Flow File=f01
Subcritical Flow
K Sum by GR= 0
Std Step Tol= 0.01
Critical Tol= 0.01
Num of Std Step Trials= 20
Max Error Tol= 0.3
Flow Tol Ratio= 0.001
Split Flow NTrial= 30
Split Flow Tol= 0.02
Split Flow Ratio= 0.02
Log Output Level= 0
Friction Slope Method= 1
Unsteady Friction Slope Method= 2
Unsteady Bridges Friction Slope Method= 1
Parabolic Critical Depth
Global Vel Dist=  1 , 1 , 1
Global Log Level= 0
CheckData=True
Encroach Param= -1, 0, 0, 0
BEGIN DESCRIPTION:
Multiple Run
END DESCRIPTION:

--- UNT0029 IN CHRS.f01 (steady flow) ---

Flow Title=Multiple
Number of Profiles=7
Profile Names=10-year,25-year,50-year,1pct_min,100-year,1pct_plu,500-year
River Rch & RM= UNT0029 IN CHRS,Reach-1,25114
     382     478     548     457     618     835     783
River Rch & RM= UNT0029 IN CHRS,Reach-1,21714
     462     582     670     560     758    1025     969
River Rch & RM= UNT0029 IN CHRS,Reach-1,15891
     575     730     844     708     958    1296    1233
River Rch & RM= UNT0029 IN CHRS,Reach-1,8912
     654     832     964     809    1094    1480    1411
Boundary for River Rch & Prof#=UNT0029 IN CHRS,Reach-1,1
Up Type=0
Dn Type=3
Dn Slope=0.005
Boundary for River Rch & Prof#=UNT0029 IN CHRS,Reach-1,2
Up Type=0
Dn Type=3
Dn Slope=0.005
Boundary for River Rch & Prof#=UNT0029 IN CHRS,Reach-1,3
Up Type=0
Dn Type=3
Dn Slope=0.005
Boundary for River Rch & Prof#=UNT0029 IN CHRS,Reach-1,4
Up Type=0
Dn Type=3
Dn Slope=0.005
Boundary for River Rch & Prof#=UNT0029 IN CHRS,Reach-1,5
Up Type=0
Dn Type=3
Dn Slope=0.005
Boundary for River Rch & Prof#=UNT0029 IN CHRS,Reach-1,6
Up Type=0
Dn Type=3
Dn Slope=0.005
Boundary for River Rch & Prof#=UNT0029 IN CHRS,Reach-1,7
Up Type=0
Dn Type=3
Dn Slope=0.005

--- UNT0029 IN CHRS.g01 (geometry) ---

Geom Title=Existing Conditions
Program Version=4.10

River Reach=UNT0029 IN CHRS ,Reach-1
Reach XY= 30
      3381122.11     10595971.64      3381529.83     10595241.09
      3381606.55     10594109.64      3382620.87     10593095.73
      3382811.09     10592152.07       3382553.1     10591671.87
       3382801.9     10591454.98      3382392.05     10591326.91
      3382956.65     10590744.65      3383105.09     10590418.11
      3382798.18     10590348.11      3383230.76      10589805.9
      3382923.05     10589227.42      3383325.31     10588869.27
      3382953.61     10588225.85      3383397.69     10588055.31
      3383114.14     10587597.22      3383587.89     10587313.37
      3384021.86     10587431.26      3384394.56     10586969.14
      3384153.11     10586661.12      3384642.11     10585511.64
       3384164.8     10584922.58      3384916.98     10584484.18
      3384552.57     10584282.09      3384978.44     10584084.41
       3384763.7      10583371.9      3385196.15     10582815.53
      3384697.27     10582384.44      3384692.11     10581851.64

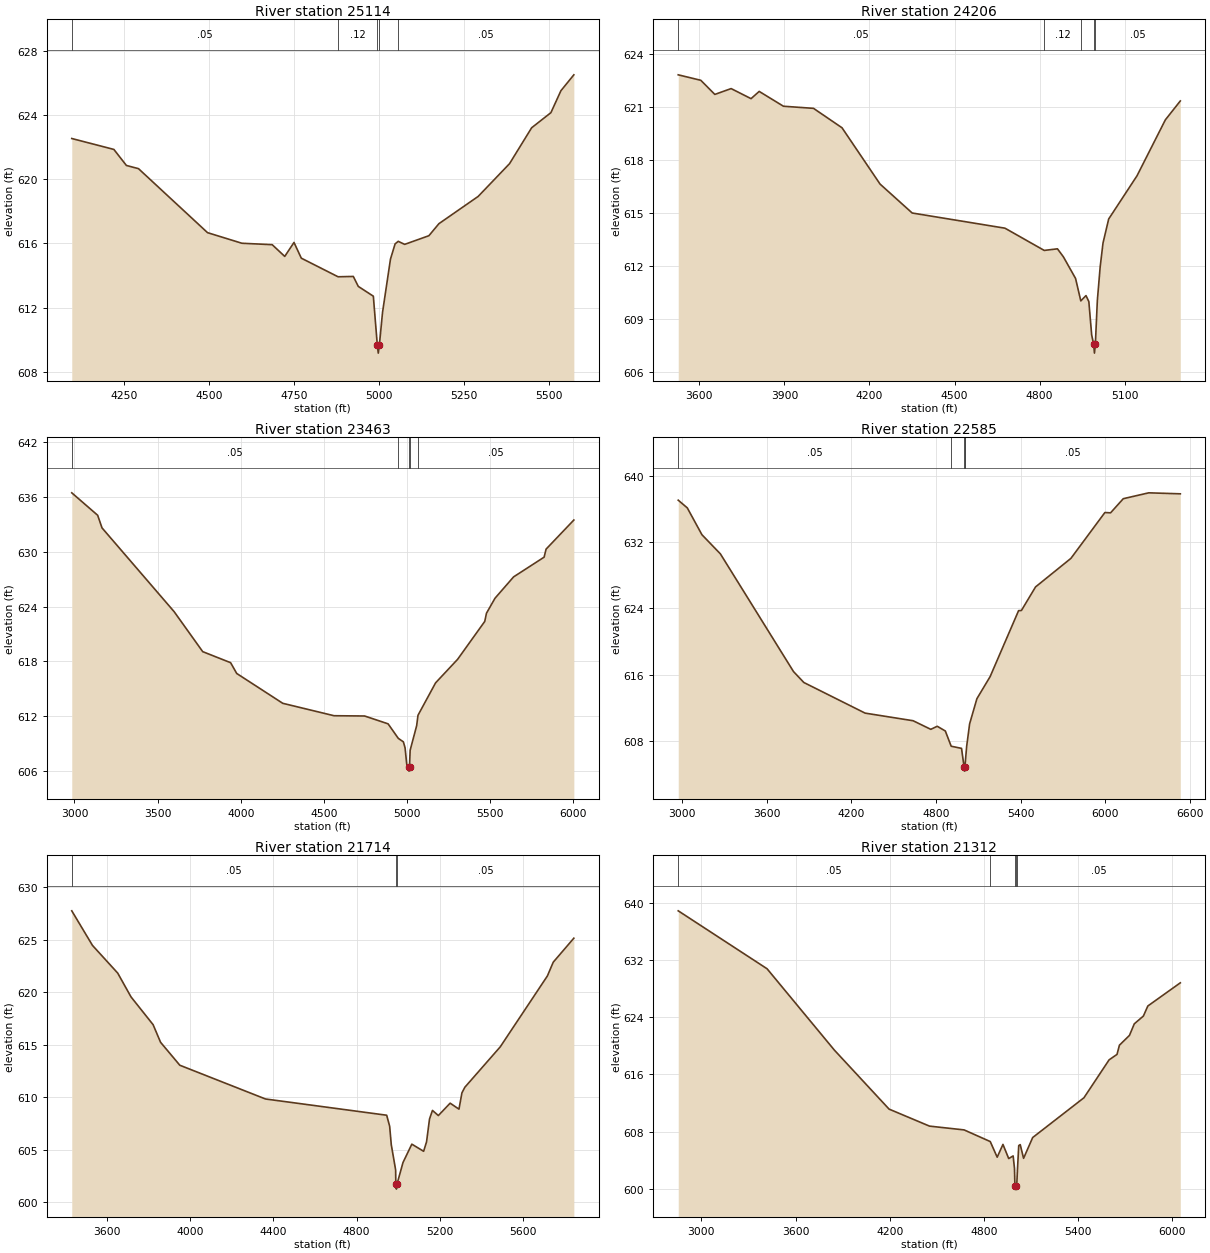
Type RM Length L Ch R = 1 ,25114   ,908,908,908
BEGIN DESCRIPTION:
UNT0029 IN CHRS 28.6
END DESCRIPTION:
XS GIS Cut Line= 3
      3381950.16     10596322.44      3381260.08     10595905.78
      3380714.24     10595515.89
#Sta/Elev= 30
  4095.2  622.54    4219  621.86  4255.9  620.86  4291.5  620.66  4494.6  616.67
  4595.6  616.01  4684.8  615.92  4721.7  615.19  4748.9  616.06  4770.4  615.08
  4878.5  613.92  4923.4  613.94    4938  613.32  4982.3  612.71    4994  609.66
  4996.8  609.16    5000  609.66  5009.4  611.71  5032.7  615.02  5046.3  615.97
  5055.5  616.13  5074.4  615.94  5145.7  616.48  5175.2  617.23  5290.7  618.93
  5382.9  620.97    5448  623.21  5504.6  624.15  5534.1  625.52  5572.1  626.51
#Mann= 5 ,-1 , 0
  4095.2     .05       0  4878.5     .12       0    4994     .07       0
    5000     .12       0  5055.5     .05       0
Bank Sta=4994,5000
XS Rating Curve= 0 ,0
Exp/Cntr=0.3,0.1

Type RM Length L Ch R = 1 ,24206   ,743,743,743
BEGIN DESCRIPTION:
UNT0029 IN CHRS 28.0
END DESCRIPTION:
XS GIS Cut Line= 3
      3382399.44     10596286.47       3381299.4     10595386.43
      3380949.41     10595386.43
#Sta/Elev= 30
  3525.3  622.83  3604.9  622.52  3654.4  621.72  3711.9  622.05  3782.2  621.48
  3810.9  621.89  3896.5  621.05  4002.6  620.93  4103.1  619.83  4237.3  616.64
  4350.7     615    4678  614.14  4816.5  612.88  4863.2  612.97    4884  612.52
  4927.1  611.29  4945.5  610.02  4963.9  610.32  4973.9  609.98  4983.9  608.09
  4990.9  607.56  4993.7  607.06  4996.9  607.56  5003.9  610.04  5013.9  611.95
  5023.9   613.3  5043.9  614.66  5143.9  617.11  5243.9  620.28  5296.6  621.35
#Mann= 5 ,-1 , 0
  3525.3     .05       0  4816.5     .12       0  4945.5     .05       0
  4990.9    .035       0  4996.9     .05       0
Bank Sta=4990.9,4996.9
XS Rating Curve= 0 ,0
Exp/Cntr=0.3,0.1

Type RM Length L Ch R = 1 ,23463   ,878,878,878
BEGIN DESCRIPTION:
UNT0029 IN CHRS 26.0
END DESCRIPTION:
XS GIS Cut Line= 3
      3383367.32     10595615.93      3381700.63     10595048.21
      3380466.68     10594803.51
#Sta/Elev= 30
  2983.8  636.47  3139.6  634.01  3165.6  632.63  3599.3  623.45  3771.1  619.07
  3938.9  617.86  3975.5  616.68  4252.4  613.41  4560.7  612.05  4744.5  612.02
  4885.7  611.16  4947.1  609.57  4977.5  609.19  4987.7  608.54  4997.9  606.72
  5008.4  606.48  5011.2  605.98  5014.4  606.48  5018.3  608.27  5057.5  610.96
  5065.5   612.1  5171.2  615.65  5303.7  618.23  5466.8  622.38  5477.2  623.28
  5528.4  624.92  5640.2  627.26  5823.7  629.42  5835.6   630.3  6002.5  633.49
#Mann= 5 ,-1 , 0
  2983.8     .05       0  4947.1     .12       0  5008.4     .07       0
  5014.4     .12       0  5065.5     .05       0
Bank Sta=5008.4,5014.4
XS Rating Curve= 0 ,0
Exp/Cntr=0.3,0.1

Type RM Length L Ch R = 1 ,22585   ,871,871,871
BEGIN DESCRIPTION:
UNT0029 IN CHRS 24.0
END DESCRIPTION:
XS GIS Cut Line= 4
      3383403.78     10595397.18       3381804.8     10594527.38
      3381450.63     10594298.21        3380139.      10594386.7
#Sta/Elev= 30
    2974  637.07  3038.2  636.14  3141.8   632.9  3272.8  630.58  3790.6  616.36
  3863.8  615.04  4297.8  611.34  4637.9  610.42  4763.2  609.38  4808.7  609.75
  4866.1  609.18  4907.5  607.34  4980.9  607.08    4999  604.83  5001.7  604.33
    5005  604.83  5006.2  605.13  5017.1  607.31  5038.3  610.05  5089.7  613.08
  5183.4  615.75    5385  623.72    5405  623.74  5505.3  626.59  5755.8  630.04
  5996.4  635.58  6036.5  635.54  6126.7  637.25  6307.1  637.96  6530.7  637.84
#Mann= 5 ,-1 , 0
    2974     .05       0  4907.5     .16       0    4999     .07       0
    5005     .16       0  5006.2     .05       0
Bank Sta=4999,5005
XS Rating Curve= 0 ,0
Exp/Cntr=0.3,0.1

Type RM Length L Ch R = 1 ,21714   ,402,402,402
BEGIN DESCRIPTION:
UNT0029 IN CHRS 23.0
END DESCRIPTION:
XS GIS Cut Line= 3
      3383092.08     10594991.62      3381892.11     10593991.64
      3381292.14     10593391.67
#Sta/Elev= 30
  3432.7  627.77  3532.2  624.47  3653.3  621.83  3717.1  619.56  3823.2  616.91
    3859  615.23  3951.4  613.04  4362.7  609.82  4944.6  608.27  4958.9  607.22
  4966.7  605.46  4987.6  603.05  4988.5  601.72  4991.2  601.22  4994.5  601.72
    5023  603.76  5065.4  605.51    5122  604.83  5136.1  605.74  5150.3  607.91
  5164.4  608.73  5192.7  608.24  5249.3  609.42  5291.7  608.85  5305.8   610.4
    5320  610.94  5489.7  614.79    5716  621.55  5744.3  622.87  5843.2  625.16
#Mann= 3 ,-1 , 0
  3432.7     .05       0  4988.5    .035       0  4994.5     .05       0
Bank Sta=4988.5,4994.5
XS Rating Curve= 0 ,0
Exp/Cntr=0.3,0.1

Type RM Length L Ch R = 1 ,21312   ,529,529,529
BEGIN DESCRIPTION:
UNT0029 IN CHRS 22.0
END DESCRIPTION:
XS GIS Cut Line= 3
      3383810.03     10595006.56      3382377.72     10593902.38
      3381196.26     10593173.73
#Sta/Elev= 30
  2853.2   638.9  3418.8  630.79    3847  619.41  4195.7  611.14    4453  608.76
  4673.4  608.23  4839.7   606.6  4883.9  604.41  4920.6   606.2  4957.3  604.22
  4985.5  604.59    4994  602.84  4996.8  600.44  4999.6  599.94  5002.8  600.44
    5009   600.8    5013  602.67  5021.1  606.04  5030.6  606.17  5051.9  604.25
  5109.8  607.16  5436.3  612.73  5596.5  618.04  5646.8   618.8  5662.2  620.09
    5726  621.46  5756.8  623.08  5814.7  624.17  5843.2  625.58  6049.8  628.82
#Mann= 5 ,-1 , 0
  2853.2     .05       0  4839.7     .12       0  4996.8     .07       0
  5002.8     .12       0    5013     .05       0
Bank Sta=4996.8,5002.8
XS Rating Curve= 0 ,0
Exp/Cntr=0.3,0.1

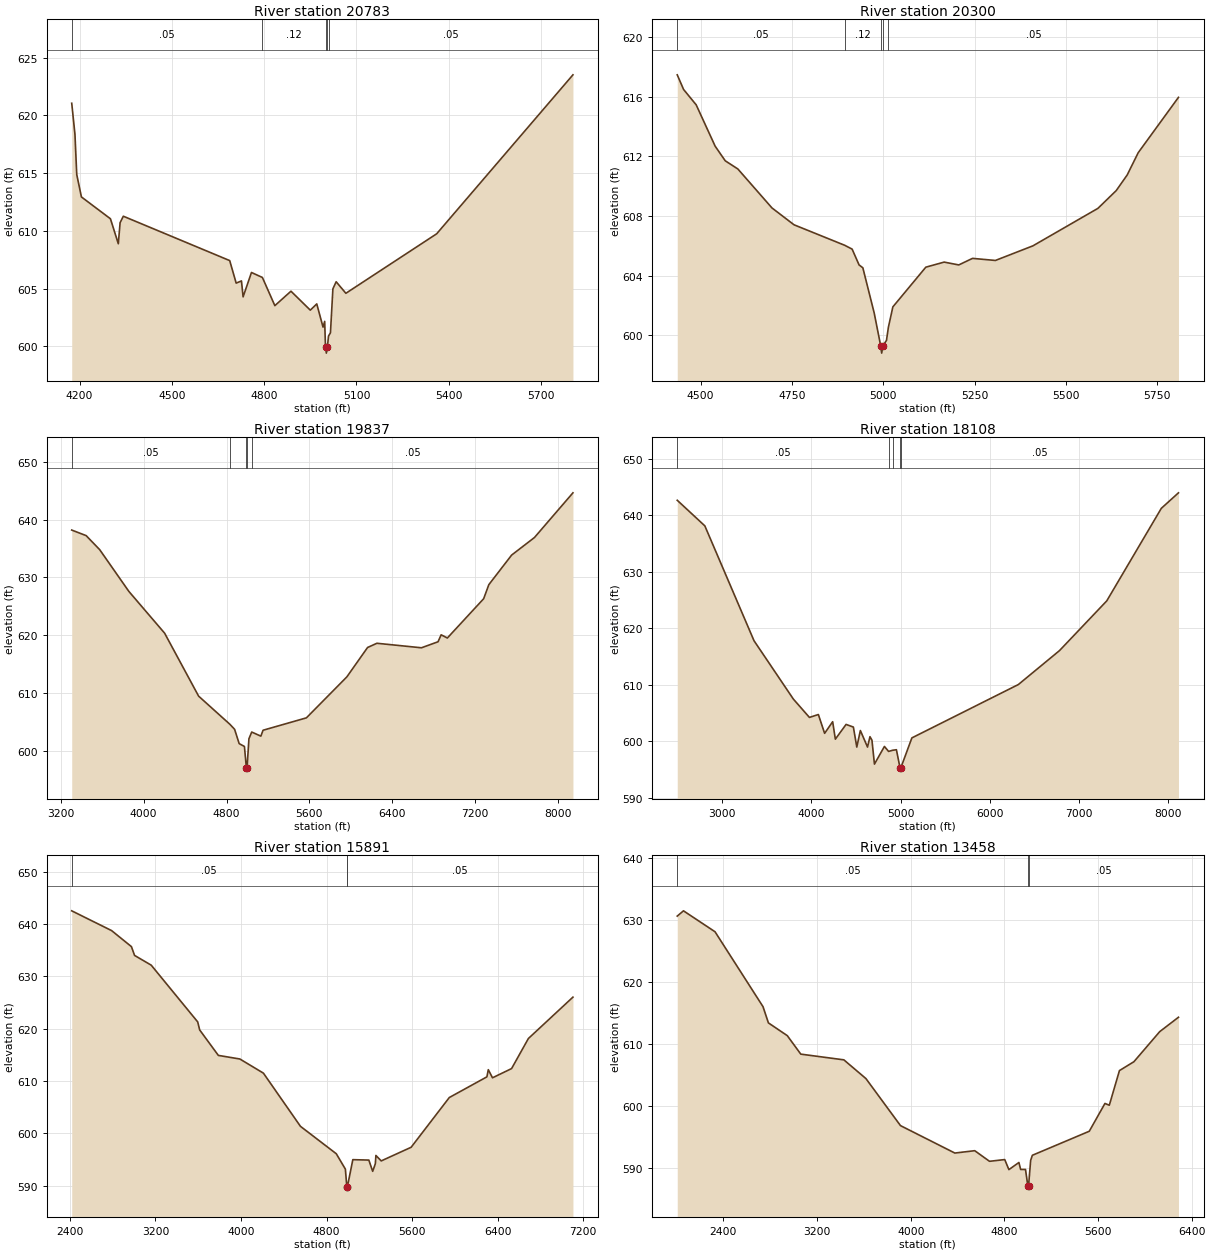
Type RM Length L Ch R = 1 ,20783   ,483,483,483
BEGIN DESCRIPTION:
UNT0029 IN CHRS 21.0
END DESCRIPTION:
XS GIS Cut Line= 3
      3383042.14     10593691.65      3382242.11     10593441.64
      3381492.07     10593191.63
#Sta/Elev= 30
  4174.7  621.05  4185.2  618.36    4191  614.88  4206.2  612.94  4300.5  611.05
  4326.1  608.89  4331.9  610.71  4342.4  611.27  4688.1  607.43  4709.1  605.48
  4726.3  605.67  4731.6  604.29  4758.8   606.4  4794.3  605.97  4834.8  603.53
  4887.2  604.78    4950  603.14    4971  603.68  4991.4  601.67  4996.7  602.17
  4999.4  599.92  5002.2  599.42  5005.4  599.92  5009.2   600.9  5015.5  601.18
  5023.4  604.98    5034   605.6  5065.6   604.6  5360.7  609.75  5803.5  623.51
#Mann= 5 ,-1 , 0
  4174.7     .05       0  4794.3     .12       0  4999.4     .07       0
  5005.4     .12       0  5009.2     .05       0
Bank Sta=4999.4,5005.4
XS Rating Curve= 0 ,0
Exp/Cntr=0.3,0.1

Type RM Length L Ch R = 1 ,20300   ,463,463,463
BEGIN DESCRIPTION:
UNT0029 IN CHRS 20.0
END DESCRIPTION:
XS GIS Cut Line= 3
      3383092.13     10593341.65      3382542.11     10593191.64
      3381742.08     10593141.64
#Sta/Elev= 30
    4436  617.46  4453.3  616.48  4487.8  615.45  4539.7  612.68  4567.3   611.7
  4601.9  611.15  4695.2  608.54  4755.6  607.41    4894  606.04  4914.6  605.78
  4933.6  604.72  4943.9  604.53    4975   601.5  4992.7  599.31  4995.5  598.81
  4998.7  599.31  5008.6  599.66  5013.9  600.55  5026.1  601.91  5116.3  604.57
  5166.4  604.91  5206.5  604.72  5244.1  605.16  5306.7  605.02  5409.4     606
  5587.2  608.51  5637.3   609.7  5667.4  610.75  5697.5  612.24  5807.7  615.95
#Mann= 5 ,-1 , 0
    4436     .05       0    4894     .12       0  4992.7     .07       0
  4998.7     .12       0  5013.9     .05       0
Bank Sta=4992.7,4998.7
XS Rating Curve= 0 ,0
Exp/Cntr=0.3,0.1

Type RM Length L Ch R = 1 ,19837   ,1729,1729,1729
BEGIN DESCRIPTION:
UNT0029 IN CHRS 19.0
END DESCRIPTION:
XS GIS Cut Line= 4
      3384080.84     10593506.55      3382971.47     10593173.21
       3382117.3     10592631.55       3379450.6     10592558.63
#Sta/Elev= 30
  3306.2  638.19  3445.4  637.23  3576.4   634.8  3857.5   627.6  4202.9  620.38
  4530.9  609.51  4833.2  604.64  4878.3  603.78  4922.3  601.31    4973  600.82
  4992.2  597.06    4995  596.56  4998.2  597.06  5016.4  602.15  5043.5  603.31
  5131.6   602.6  5152.8  603.62  5571.2  605.76  5961.4  612.83  6161.5  617.91
  6251.5  618.64  6681.7  617.86  6841.7   618.9  6871.7   620.1  6931.7  619.55
  7281.9  626.33  7331.9  628.76    7552  633.87  7772.1   636.9  8143.7  644.62
#Mann= 5 ,-1 , 0
  3306.2     .05       0  4833.2     .12       0  4992.2     .07       0
  4998.2     .12       0  5043.5     .05       0
Bank Sta=4992.2,4998.2
XS Rating Curve= 0 ,0
Exp/Cntr=0.3,0.1

Type RM Length L Ch R = 1 ,18108   ,2217,2217,2217
BEGIN DESCRIPTION:
UNT0029 IN CHRS 16.0
END DESCRIPTION:
XS GIS Cut Line= 4
      3385080.83     10591754.59      3382945.43     10591637.41
      3382190.22     10592015.01        3379560.      10592132.2
#Sta/Elev= 30
  2497.6  642.68  2806.8  638.15  3357.6  617.82  3798.3  607.49  3978.6  604.24
  4078.7  604.75  4148.8  601.42  4238.9  603.48    4269  600.39  4389.2     603
    4471  602.53  4509.3  598.99  4549.4  601.92  4629.5  598.99  4656.8  600.83
  4679.1  600.21  4707.1  595.97  4818.9   599.1  4865.4  598.22  4909.9  598.42
  4953.1  598.52  4994.8  595.23  4997.5  594.73  5000.8  595.23  5126.4  600.61
  6319.5  610.06    6780  616.06    7310  624.87  7921.1  641.25  8113.4     644
#Mann= 5 ,-1 , 0
  2497.6     .05       0  4865.4     .12       0  4909.9     .05       0
  4994.8    .035       0  5000.8     .05       0
Bank Sta=4994.8,5000.8
XS Rating Curve= 0 ,0
Exp/Cntr=0.3,0.1

Type RM Length L Ch R = 1 ,15891   ,2433,2433,2433
BEGIN DESCRIPTION:
UNT0029 IN CHRS 14.0
END DESCRIPTION:
XS GIS Cut Line= 4
      3385393.33     10591546.26       3383427.2     10590751.99
      3382190.22     10590283.24      3381005.35     10589905.65
#Sta/Elev= 30
  2416.8  642.54  2789.9  638.76    2975   635.7  3004.5  634.02  3160.1  632.16
  3594.8  621.32  3613.5  619.78  3787.8  614.92  3989.1  614.23  4209.2  611.53
  4555.6  601.37  4890.7  596.13  4975.8  593.19  4988.9  589.87  4991.6  589.37
  4994.9  589.87  5045.4     595  5195.1  594.92  5231.1  592.77  5255.9  594.22
  5261.2   595.8  5310.9  594.76  5590.8  597.37  5947.5  606.87    6299  610.82
  6312.3  612.19  6351.4  610.64  6529.9   612.4  6687.3  618.15  7103.7  626.05
#Mann= 3 ,-1 , 0
  2416.8     .05       0  4988.9    .035       0  4994.9     .05       0
Bank Sta=4988.9,4994.9
XS Rating Curve= 0 ,0
Exp/Cntr=0.3,0.1

Type RM Length L Ch R = 1 ,13458   ,332,332,332
BEGIN DESCRIPTION:
UNT0029 IN CHRS 11.1
END DESCRIPTION:
XS GIS Cut Line= 5
      3385458.27     10590666.25      3383473.93     10589530.85
      3383208.31     10589254.81      3382812.48     10588963.14
      3381839.21     10588406.25
#Sta/Elev= 30
  2005.4  630.62  2058.6  631.47  2328.1   628.1  2738.3  616.03  2784.3  613.42
  2945.5  611.37  3060.9  608.39    3429  607.47  3617.6  604.45  3912.6  596.88
  4377.1  592.46  4546.9  592.84  4673.4  591.13  4803.4  591.41  4838.9  589.79
  4924.5  590.94  4939.2  589.82  4980.9  589.81  5000.9  587.15  5003.7  586.65
  5006.9  587.15  5024.8  591.28  5039.4   592.1  5525.7  595.97  5659.6  600.45
  5696.8  600.16  5783.4  605.74  5907.1  607.17  6127.3  612.01  6287.7  614.33
#Mann= 3 ,-1 , 0
  2005.4     .05       0  5000.9    .035       0  5006.9     .05       0
Bank Sta=5000.9,5006.9
XS Rating Curve= 0 ,0
Exp/Cntr=0.3,0.1

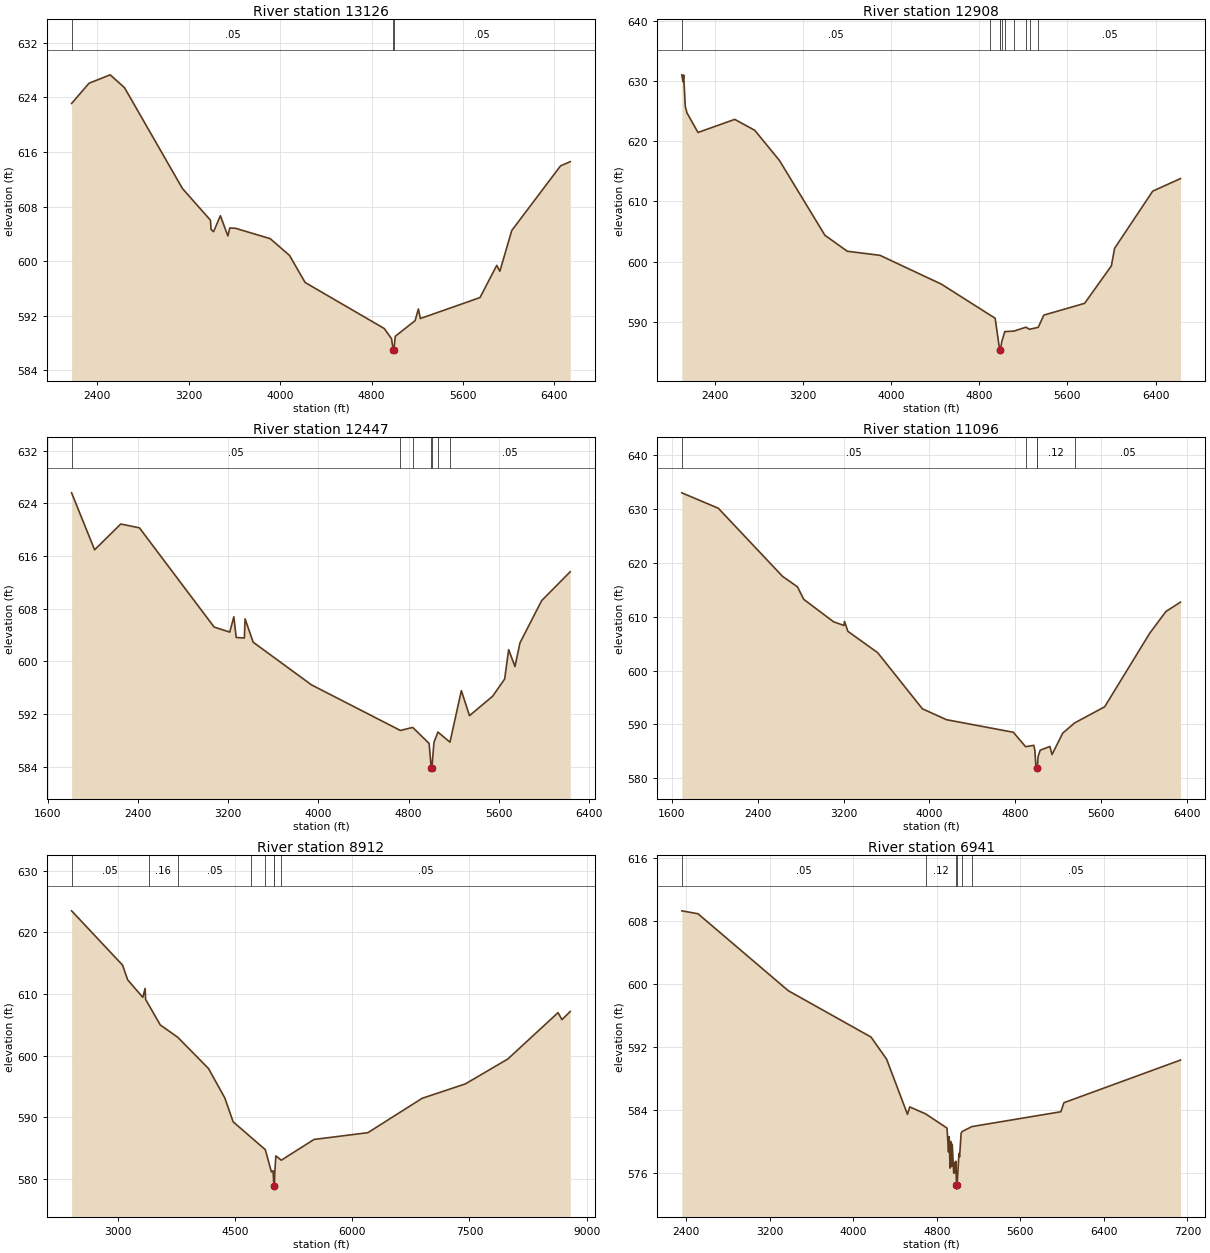
Type RM Length L Ch R = 1 ,13126   ,218,218,218
BEGIN DESCRIPTION:
UNT0029 IN CHRS 11.0
END DESCRIPTION:
XS GIS Cut Line= 5
      3385640.57       10590510.      3383942.68     10589582.93
      3383281.23     10589077.73      3383010.39     10588952.73
      3381906.71     10588270.73
#Sta/Elev= 30
  2175.6  623.11  2328.2  626.08  2513.2  627.31  2638.5  625.43  3145.2  610.66
  3390.1  606.02  3395.8  604.66  3417.6  604.33  3477.4  606.67  3542.9   603.7
    3559  604.87  3609.4  604.83    3913  603.31  4081.9  600.86  4218.5  596.89
  4910.6  590.15  4974.5  588.66  4988.9  587.04  4991.6  586.54  4994.9  587.04
  5007.5  589.01  5180.9   591.3  5209.4  593.01  5226.8  591.61  5748.5  594.68
  5895.1   599.4  5922.2  598.53  6026.3   604.5  6453.1  613.97  6538.1  614.59
#Mann= 3 ,-1 , 0
  2175.6     .05       0  4988.9    .035       0  4994.9     .05       0
Bank Sta=4988.9,4994.9
XS Rating Curve= 0 ,0
Exp/Cntr=0.3,0.1

Type RM Length L Ch R = 1 ,12908   ,461,461,461
BEGIN DESCRIPTION:
UNT0029 IN CHRS 8.2
END DESCRIPTION:
XS GIS Cut Line= 6
      3385791.63     10590385.01       3383765.6     10589093.35
      3383130.18     10588760.02      3382718.73     10588520.43
      3382291.64     10588192.31      3381921.88     10588062.11
#Sta/Elev= 30
  2099.6     631  2110.1  629.85    2116  630.97  2131.2  625.72  2146.5  624.68
  2246.3  621.44  2579.8  623.61  2761.7   621.8    2986  616.79  3398.2   604.4
  3601.3  601.74  3898.3  601.06  4456.1  596.28  4895.3  591.19  4944.2  590.63
  4985.3  585.34    4988  584.84  4991.3  585.34  5004.7  586.79  5031.4  588.41
  5114.1  588.49  5223.5  589.14  5256.7  588.79  5335.4  589.12  5385.5  591.14
  5756.3   593.1  5999.2  599.31  6028.2  602.22  6374.7  611.71  6626.6  613.79
#Mann= 10 ,-1 , 0
  2099.6     .05       0  4895.3     .12       0  4985.3     .07       0
  4991.3     .12       0  5004.7     .05       0  5031.4     .12       0
  5114.1     .16       0  5223.5     .05       0  5256.7     .16       0
  5335.4     .05       0
Bank Sta=4985.3,4991.3
XS Rating Curve= 0 ,0
Exp/Cntr=0.3,0.1

Type RM Length L Ch R = 1 ,12447   ,1351,1351,1351
BEGIN DESCRIPTION:
UNT0029 IN CHRS 8.1
END DESCRIPTION:
XS GIS Cut Line= 6
      3385807.26     10590239.18      3384114.56      10589124.6
      3382989.56     10588520.43      3382755.18     10588452.73
      3382447.89     10588171.48      3382020.78      10588004.8
#Sta/Elev= 30
    1811   625.6  2015.2  616.94  2247.1  620.86  2412.8  620.28  3075.3   605.2
  3213.9  604.44    3250  606.77  3271.1  603.62  3343.4  603.54  3349.7  606.45
  3421.7   602.9  3938.7  596.42  4727.3  589.49  4836.7  589.95  4982.4  587.51
  5000.7  583.81  5003.5  583.31  5006.7  583.81  5025.1  587.67  5060.1  589.25
  5167.2  587.71    5268  595.54  5340.5  591.74  5545.9   594.7    5652   597.3
  5687.8  601.77  5743.9   599.2    5788   602.8  5980.8  609.23    6234  613.61
#Mann= 7 ,-1 , 0
    1811     .05       0  4727.3     .16       0  4836.7     .12       0
  5000.7     .07       0  5006.7     .12       0  5060.1     .16       0
  5167.2     .05       0
Bank Sta=5000.7,5006.7
XS Rating Curve= 0 ,0
Exp/Cntr=0.3,0.1

Type RM Length L Ch R = 1 ,11096   ,2184,2184,2184
BEGIN DESCRIPTION:
UNT0029 IN CHRS 8.0
END DESCRIPTION:
XS GIS Cut Line= 4
       3386278.8     10589358.79      3383765.74     10587887.41
      3382385.53     10587900.43      3382036.78     10587916.25
#Sta/Elev= 30
    1695  633.03  2034.4  630.17  2632.5  617.51  2771.3  615.57    2830  613.24
  3107.6  609.07  3203.4  608.39  3209.2  609.14  3240.6   607.3  3518.2  603.33
  3934.6   592.9  4159.4  590.88  4780.8  588.55  4894.9  585.87  4970.8  586.12
  4980.8   585.2  4990.8  582.18  4997.8  581.83  5000.5  581.33  5003.8  581.83
  5010.8  584.01  5030.8  585.22  5120.8  585.91  5140.8  584.41  5240.8   588.4
  5351.2  590.28  5630.8  593.28  6050.9  606.97    6201  610.99  6336.5  612.72
#Mann= 5 ,-1 , 0
    1695     .05       0  4894.9     .12       0  4997.8     .07       0
  5003.8     .12       0  5351.2     .05       0
Bank Sta=4997.8,5003.8
XS Rating Curve= 0 ,0
Exp/Cntr=0.3,0.1

Type RM Length L Ch R = 1 ,8912    ,1971,1971,1971
BEGIN DESCRIPTION:
UNT0029 IN CHRS 6.0
END DESCRIPTION:
XS GIS Cut Line= 4
      3386213.65     10588668.65      3384481.88     10587457.72
      3383336.05     10586233.76       3381252.7     10587770.23
#Sta/Elev= 30
  2410.9  623.51  3062.8  614.69  3128.2   612.3  3321.8  609.46  3351.5   610.9
  3357.6  609.11  3398.2  608.23  3545.1  604.97  3767.7  602.98  4161.6   597.9
  4370.1  593.13  4477.3  589.24  4711.8  586.66  4888.7  584.71  4966.9  581.09
  4987.9  581.29  4999.1   578.8  5001.9   578.3  5005.1   578.8  5009.4  580.88
  5023.6   583.7  5093.4     583  5511.6  586.37  6200.6  587.47  6895.7  593.06
  7447.1  595.39    7990  599.43  8633.2  606.97  8683.3  605.83  8789.3  607.16
#Mann= 8 ,-1 , 0
  2410.9     .05       0  3398.2     .16       0  3767.7     .05       0
  4711.8     .16       0  4888.7     .12       0  4999.1     .07       0
  5005.1     .12       0  5093.4     .05       0
Bank Sta=4999.1,5005.1
XS Rating Curve= 0 ,0
Exp/Cntr=0.3,0.1

Type RM Length L Ch R = 1 ,6941    ,1589,1589,1589
BEGIN DESCRIPTION:
UNT0029 IN CHRS 3.0
END DESCRIPTION:
XS GIS Cut Line= 4
      3386178.06     10587724.91       3385837.8     10586884.67
      3383719.74     10585273.56      3382698.87     10585919.41
#Sta/Elev= 30
  2358.2  609.27  2512.8   608.9  3377.9  599.13  4170.1  593.25  4319.8  590.43
  4519.4  583.44  4540.9  584.38  4692.9   583.5  4897.8   581.7  4912.4  578.67
  4918.6   580.6  4926.9  576.62  4933.2     580  4941.4  576.81  4947.7  579.65
  4962.3  575.96  4968.5  577.35  4976.8  576.05  4983.1  577.49  4988.3  574.45
  4991.1  573.95  4994.3  574.45  5012.2  578.48  5018.4  578.07    5033  581.05
  5044.7  581.28  5137.1  581.89    5988  583.77  6017.8  584.92  7133.9  590.33
#Mann= 6 ,-1 , 0
  2358.2     .05       0  4692.9     .12       0  4988.3     .07       0
  4994.3     .12       0  5044.7     .16       0  5137.1     .05       0
Bank Sta=4988.3,4994.3
XS Rating Curve= 0 ,0
Exp/Cntr=0.3,0.1

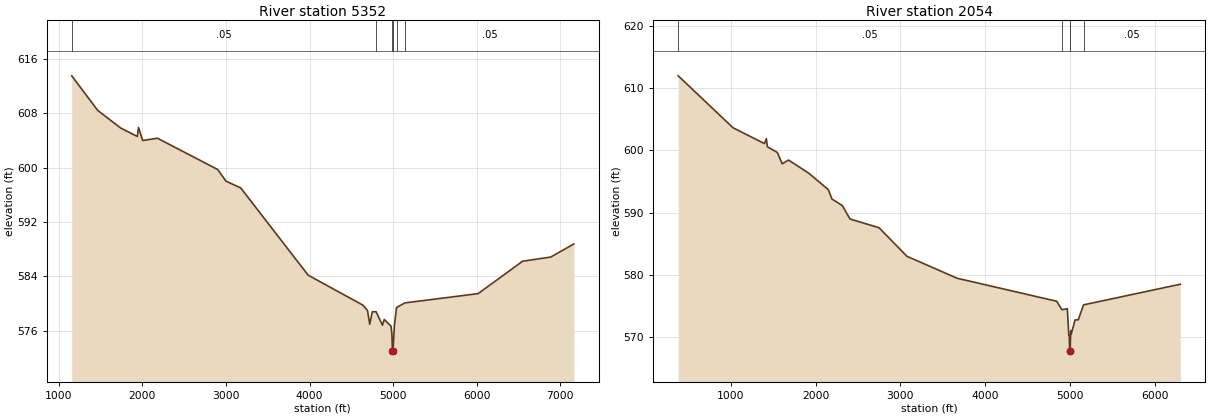
Type RM Length L Ch R = 1 ,5352    ,3298,3298,3298
BEGIN DESCRIPTION:
UNT0029 IN CHRS 2.0
END DESCRIPTION:
XS GIS Cut Line= 4
      3387288.66      10587143.8      3385106.35     10584883.37
      3383424.06     10584550.04      3382773.49     10585497.26
#Sta/Elev= 30
  1156.1  613.48  1466.3   608.4  1742.3   605.8  1940.1  604.57  1954.3   605.9
  2003.9  603.97  2180.7  604.31    2902  599.71    3001     598  3177.8     597
    3984  584.18  4637.6  579.79  4693.9     579  4720.4  576.97    4751   578.8
  4796.1  578.82  4873.3  576.83  4893.6  577.67  4975.2   576.7  4985.4  575.59
  4992.6  573.08  4995.4  572.58  4998.6  573.08    5016  576.82  5041.4  579.43
  5141.4  580.11  6017.1  581.47  6548.8  586.23  6886.6  586.85  7162.2  588.77
#Mann= 6 ,-1 , 0
  1156.1     .05       0  4796.1     .12       0  4992.6     .07       0
  4998.6     .12       0  5041.4     .16       0  5141.4     .05       0
Bank Sta=4992.6,4998.6
XS Rating Curve= 0 ,0
Exp/Cntr=0.3,0.1

Type RM Length L Ch R = 1 ,2054    ,0,0,0
BEGIN DESCRIPTION:
UNT0029 IN CHRS 1.0
END DESCRIPTION:
XS GIS Cut Line= 4
       3387606.9     10586897.85      3385562.61     10583421.26
      3384539.91     10582942.39      3383991.31     10583466.69
#Sta/Elev= 30
   380.5  611.95  1025.5  603.63    1397  601.08    1420  601.87  1431.8  600.57
  1548.8  599.66  1607.4  597.84  1681.7  598.44  1916.1  596.37  2150.4   593.7
  2193.4  592.19  2316.4  591.13  2406.2  588.98    2748  587.59  3078.1     583
  3669.8  579.48  4844.1  575.79    4905  574.43  4969.3  574.59  4986.6   570.4
  4992.1  570.41  4996.4  567.81  4999.1  567.31  5002.4  567.81  5009.5  571.07
    5015  570.51  5060.6  572.79  5098.7  572.82  5160.1  575.21  6301.7  578.52
#Mann= 5 ,-1 , 0
   380.5     .05       0    4905     .12       0  4996.4     .07       0
  5002.4     .12       0  5160.1     .05       0
Bank Sta=4996.4,5002.4
XS Rating Curve= 0 ,0
Exp/Cntr=0.3,0.1

Chan Stop Cuts=-1
Use User Specified Reach Order=0
Composite Channel Slope=5