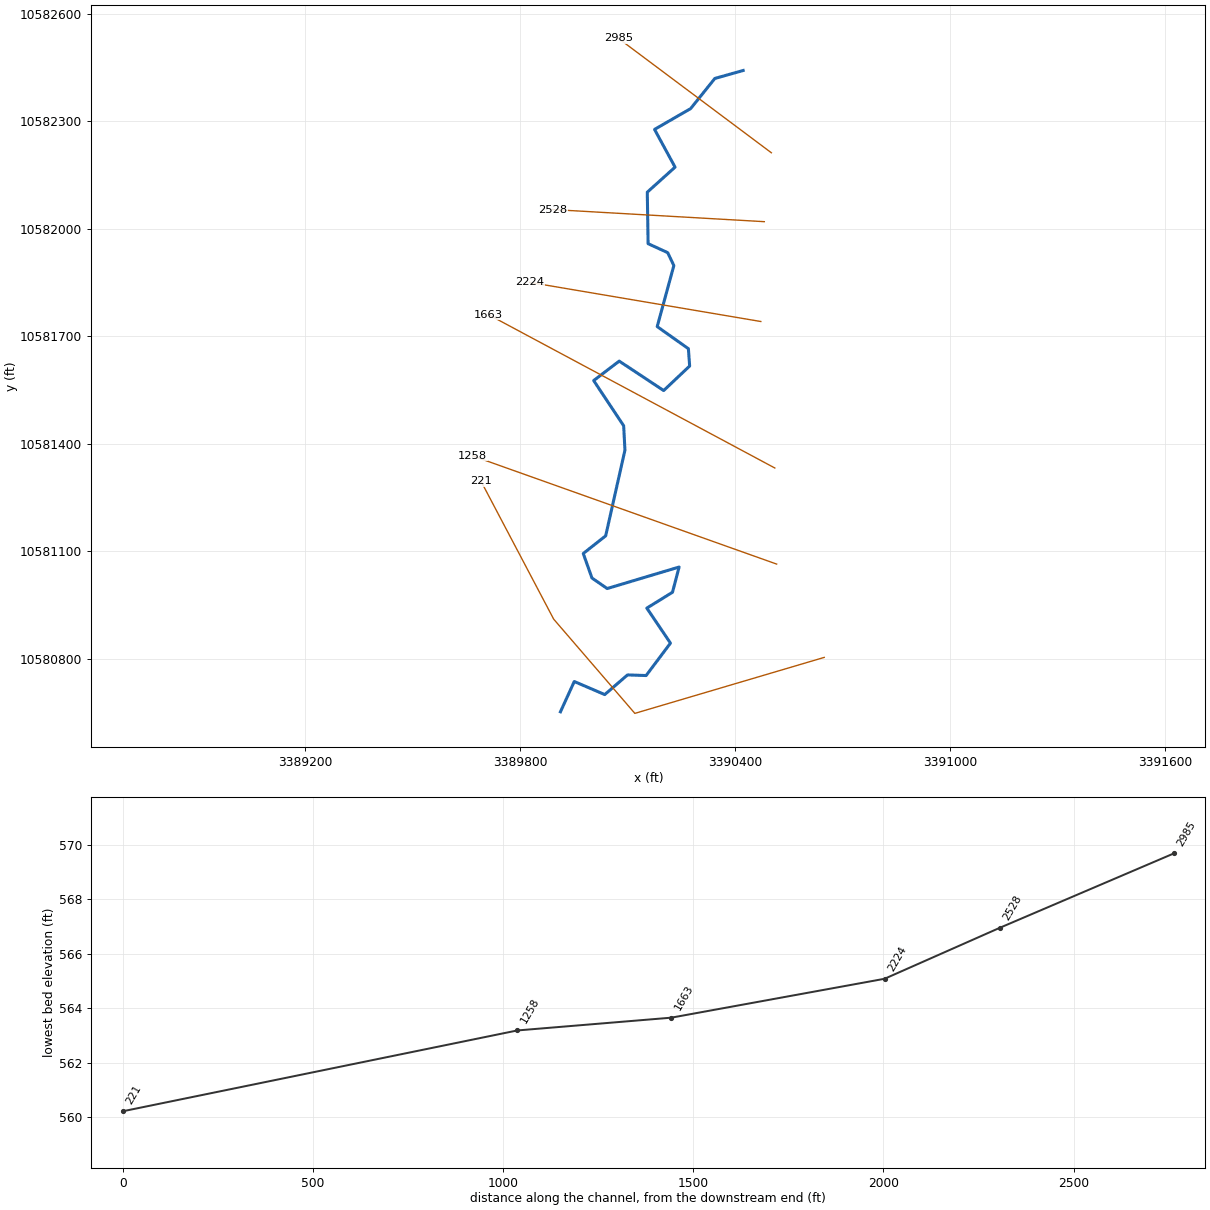
--- UNT0030 IN CHRS.prj (project) ---

Proj Title=UNT0030 IN CHRS Base Level Engineering
Current Plan=p01
Default Exp/Contr=0.3,0.1
English Units
Geom File=g01
Flow File=f01
Plan File=p01
BEGIN DESCRIPTION:
UNT0030 IN CHRS
END DESCRIPTION:

--- UNT0030 IN CHRS.p01 (plan) ---

Plan Title=Multiple Run
Short Identifier=Multiple
Geom File=g01
Flow File=f01
Subcritical Flow
K Sum by GR= 0
Std Step Tol= 0.01
Critical Tol= 0.01
Num of Std Step Trials= 20
Max Error Tol= 0.3
Flow Tol Ratio= 0.001
Split Flow NTrial= 30
Split Flow Tol= 0.02
Split Flow Ratio= 0.02
Log Output Level= 0
Friction Slope Method= 1
Unsteady Friction Slope Method= 2
Unsteady Bridges Friction Slope Method= 1
Parabolic Critical Depth
Global Vel Dist=  1 , 1 , 1
Global Log Level= 0
CheckData=True
Encroach Param= -1, 0, 0, 0
BEGIN DESCRIPTION:
Multiple Run
END DESCRIPTION:

--- UNT0030 IN CHRS.f01 (steady flow) ---

Flow Title=Multiple
Number of Profiles=7
Profile Names=10-year,25-year,50-year,1pct_min,100-year,1pct_plu,500-year
River Rch & RM= UNT0030 IN CHRS,Reach-1,2985
     340     423     482     401     542     733     682
Boundary for River Rch & Prof#=UNT0030 IN CHRS,Reach-1,1
Up Type=0
Dn Type=3
Dn Slope=0.005
Boundary for River Rch & Prof#=UNT0030 IN CHRS,Reach-1,2
Up Type=0
Dn Type=3
Dn Slope=0.005
Boundary for River Rch & Prof#=UNT0030 IN CHRS,Reach-1,3
Up Type=0
Dn Type=3
Dn Slope=0.005
Boundary for River Rch & Prof#=UNT0030 IN CHRS,Reach-1,4
Up Type=0
Dn Type=3
Dn Slope=0.005
Boundary for River Rch & Prof#=UNT0030 IN CHRS,Reach-1,5
Up Type=0
Dn Type=3
Dn Slope=0.005
Boundary for River Rch & Prof#=UNT0030 IN CHRS,Reach-1,6
Up Type=0
Dn Type=3
Dn Slope=0.005
Boundary for River Rch & Prof#=UNT0030 IN CHRS,Reach-1,7
Up Type=0
Dn Type=3
Dn Slope=0.005

--- UNT0030 IN CHRS.g01 (geometry) ---

Geom Title=Existing Conditions

River Reach=UNT0030 IN CHRS,Reach-1
Reach XY= 30
      3390422.11     10582441.64      3390342.99     10582419.37
      3390275.44     10582335.22      3390174.70     10582277.18
      3390231.96     10582171.78      3390154.43     10582101.98
      3390156.70     10581958.25      3390211.37     10581933.22
      3390228.60     10581897.13      3390182.11     10581726.78
      3390269.17     10581665.09      3390272.64     10581616.74
      3390200.18     10581548.31      3390076.08     10581630.46
      3390004.78     10581576.13      3390088.50     10581450.09
      3390092.06     10581381.86      3390038.31     10581142.78
      3389975.72     10581093.46      3390000.03     10581025.04
      3390042.47     10580995.66      3390243.29     10581055.71
      3390224.79     10580985.32      3390153.16     10580940.99
      3390219.10     10580843.37      3390151.20     10580752.86
      3390099.33     10580754.57      3390035.64     10580699.71
      3389950.64     10580736.19      3389912.11     10580651.64

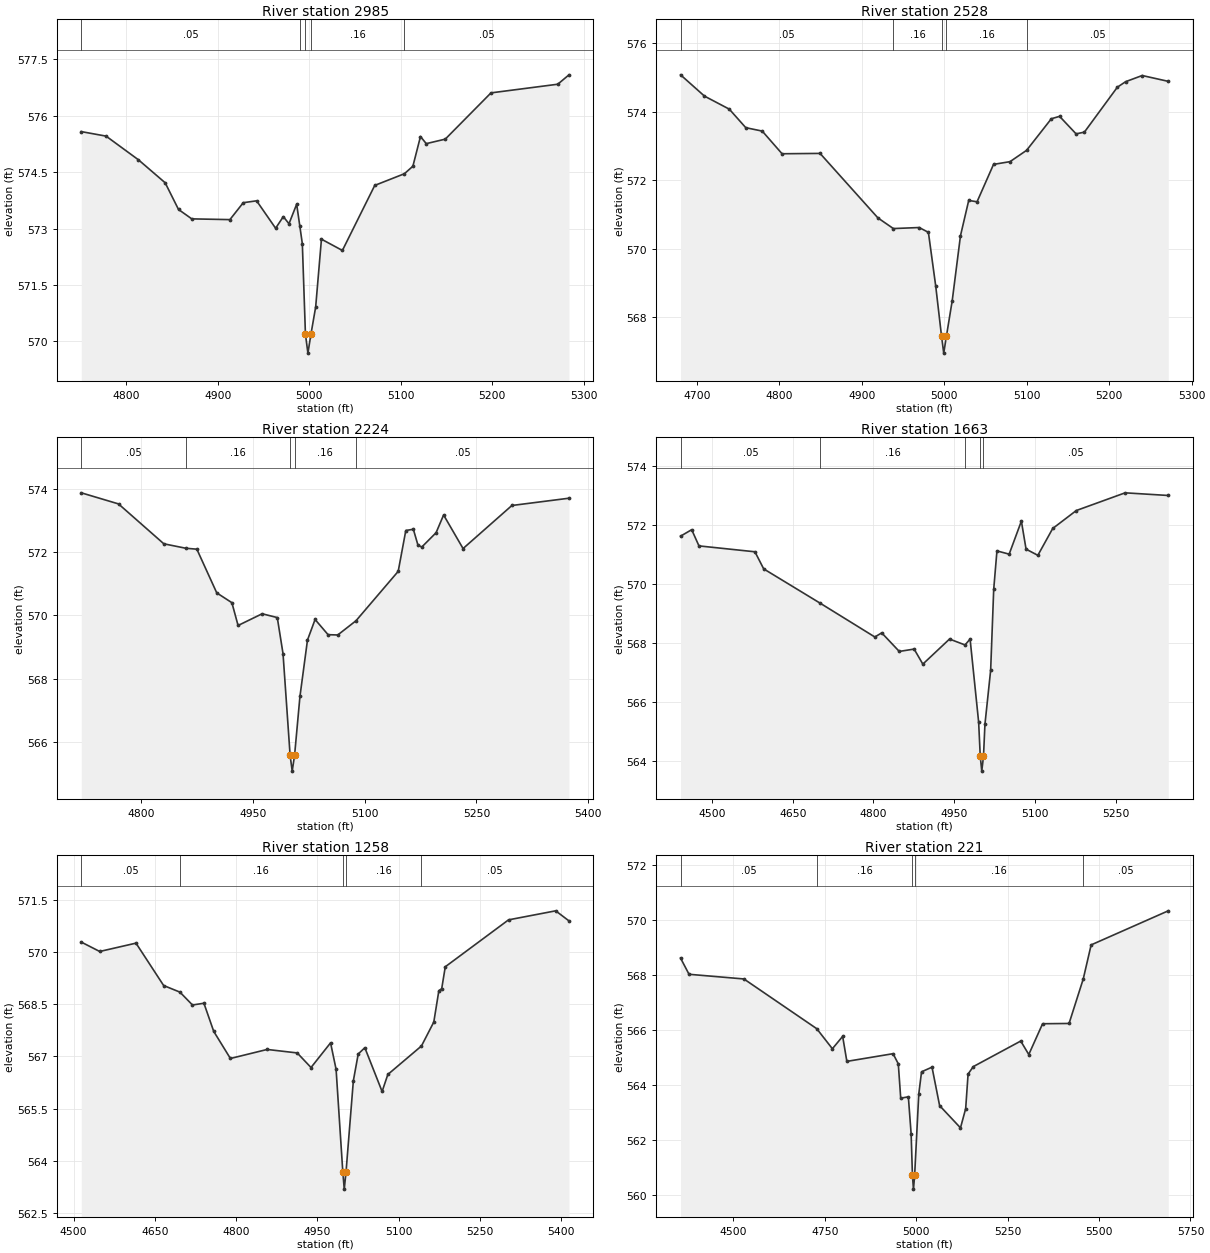
Type RM Length L Ch R = 1,2985,457,457,457
BEGIN DESCRIPTION:
UNT0030 IN CHRS 1.4
END DESCRIPTION:
XS GIS Cut Line= 2
      3390500.77     10582211.94      3390073.72     10582531.36
#Sta/Elev= 30
  4750.6  575.58  4777.7  575.46  4813.1  574.83  4842.3  574.22  4856.9  573.51
  4871.4  573.26  4913.1  573.24  4927.7  573.69  4942.3  573.74  4963.1  573.01
  4971.5  573.32  4977.7  573.13  4986.1  573.65  4989.6  573.06  4992.3  572.60
  4995.7  570.19  4998.4  569.69  5001.7  570.19  5006.9  570.92  5013.2  572.72
  5036.1  572.42  5071.5  574.15  5103.9  574.46  5113.2  574.66  5121.5  575.45
  5127.8  575.26  5148.6  575.38  5198.6  576.61  5271.6  576.84  5283.9  577.09
#Mann=5,-1,0
  4750.6    0.05       0  4989.6    0.16       0  4995.7    0.07       0
  5001.7    0.16       0  5103.9    0.05       0
Bank Sta=4995.7,5001.7
Exp/Cntr=0.3,0.1

Type RM Length L Ch R = 1,2528,304,304,304
BEGIN DESCRIPTION:
UNT0030 IN CHRS 1.5
END DESCRIPTION:
XS GIS Cut Line= 2
      3390481.07     10582019.66      3389890.54     10582053.50
#Sta/Elev= 30
  4680.1  575.07  4709.1  574.45  4739.2  574.07  4759.2  573.53  4779.2  573.43
  4803.2  572.77  4849.3  572.78  4919.5  570.90  4938.2  570.59  4969.5  570.62
  4980.7  570.48  4989.6  568.91  4996.6  567.46  4999.3  566.96  5002.6  567.46
  5009.6  568.49  5019.6  570.38  5029.6  571.41  5039.7  571.37  5059.7  572.46
  5079.7  572.54  5099.8  572.87  5129.8  573.79  5139.8  573.86  5159.8  573.35
  5169.9  573.40  5209.9  574.71  5219.9  574.87  5240.0  575.05  5271.6  574.88
#Mann=5,-1,0
  4680.1    0.05       0  4938.2    0.16       0  4996.6    0.07       0
  5002.6    0.16       0  5099.8    0.05       0
Bank Sta=4996.6,5002.6
Exp/Cntr=0.3,0.1

Type RM Length L Ch R = 1,2224,561,561,561
BEGIN DESCRIPTION:
UNT0030 IN CHRS 1.3
END DESCRIPTION:
XS GIS Cut Line= 2
      3390471.28     10581741.00      3389826.26     10581850.24
#Sta/Elev= 30
  4720.0  573.87  4769.9  573.52  4830.7  572.26  4860.1  572.12  4875.0  572.09
  4901.7  570.71  4922.0  570.40  4930.3  569.68  4962.6  570.05  4982.9  569.93
  4990.6  568.79  5000.1  565.58  5002.9  565.08  5006.1  565.58  5013.3  567.44
  5023.4  569.22  5033.6  569.87  5051.0  569.39  5064.0  569.38  5088.5  569.83
  5145.1  571.39  5155.3  572.68  5165.4  572.72  5171.7  572.21  5176.8  572.16
  5195.9  572.61  5206.0  573.17  5232.1  572.11  5297.6  573.47  5374.2  573.70
#Mann=5,-1,0
  4720.0    0.05       0  4860.1    0.16       0  5000.1    0.07       0
  5006.1    0.16       0  5088.5    0.05       0
Bank Sta=5000.1,5006.1
Exp/Cntr=0.3,0.1

Type RM Length L Ch R = 1,1663,405,405,405
BEGIN DESCRIPTION:
UNT0030 IN CHRS 1.2
END DESCRIPTION:
XS GIS Cut Line= 2
      3390510.36     10581332.14      3389711.49     10581759.92
#Sta/Elev= 30
  4441.6  571.62  4462.3  571.84  4475.8  571.29  4579.8  571.09  4596.1  570.51
  4701.6  569.34  4802.6  568.20  4815.4  568.34  4848.0  567.71  4875.6  567.79
  4891.8  567.28  4941.4  568.13  4970.2  567.93  4979.6  568.13  4995.5  565.31
  4998.5  564.15  5001.3  563.65  5004.5  564.15  5007.2  565.24  5017.8  567.07
  5023.5  569.82  5029.5  571.12  5052.2  571.01  5074.9  572.13  5083.6  571.18
  5105.5  570.97  5133.1  571.88  5177.0  572.49  5267.7  573.09  5347.8  573.00
#Mann=5,-1,0
  4441.6    0.05       0  4701.6    0.16       0  4970.2    0.05       0
  4998.5   0.035       0  5004.5    0.05       0
Bank Sta=4998.5,5004.5
Exp/Cntr=0.3,0.1

Type RM Length L Ch R = 1,1258,1037,1037,1037
BEGIN DESCRIPTION:
UNT0030 IN CHRS 1.1
END DESCRIPTION:
XS GIS Cut Line= 2
      3390515.51     10581063.94      3389666.83     10581365.92
#Sta/Elev= 30
  4514.1  570.29  4548.1  570.02  4615.1  570.26  4666.2  569.04  4696.3  568.85
  4719.4  568.48  4740.6  568.53  4758.7  567.72  4789.5  566.94  4857.4  567.20
  4912.9  567.10  4938.4  566.68  4974.5  567.39  4984.7  566.63  4997.1  563.68
  4999.8  563.18  5003.1  563.68  5016.6  566.30  5025.6  567.07  5037.8  567.25
  5069.7  565.99  5080.3  566.48  5142.4  567.30  5165.2  567.99  5174.5  568.89
  5179.8  568.95  5186.4  569.58  5303.2  570.93  5390.3  571.19  5414.9  570.90
#Mann=5,-1,0
  4514.1    0.05       0  4696.3    0.16       0  4997.1    0.07       0
  5003.1    0.16       0  5142.4    0.05       0
Bank Sta=4997.1,5003.1
Exp/Cntr=0.3,0.1

Type RM Length L Ch R = 1,221,0,0,0
BEGIN DESCRIPTION:
UNT0030 IN CHRS 1.0
END DESCRIPTION:
XS GIS Cut Line= 4
      3390648.34     10580803.49      3390119.72     10580647.25
      3389893.16     10580910.27      3389690.05     10581295.66
#Sta/Elev= 30
  4355.3  568.62  4378.5  568.03  4528.6  567.86  4727.8  566.05  4770.6  565.32
  4798.7  565.77  4810.2  564.86  4936.6  565.14  4950.9  564.77  4957.5  563.52
  4978.4  563.57  4986.0  562.22  4989.6  560.71  4992.4  560.21  4995.6  560.71
  5006.9  563.67  5014.5  564.48  5043.1  564.65  5063.9  563.25  5121.0  562.44
  5135.2  563.14  5141.8  564.40  5156.1  564.67  5285.8  565.60  5307.8  565.11
  5345.6  566.23  5418.0  566.24  5456.8  567.86  5478.4  569.10  5689.3  570.34
#Mann=5,-1,0
  4355.3    0.05       0  4727.8    0.16       0  4989.6    0.07       0
  4995.6    0.16       0  5456.8    0.05       0
Bank Sta=4989.6,4995.6
Exp/Cntr=0.3,0.1

Chan Stop Cuts=-1