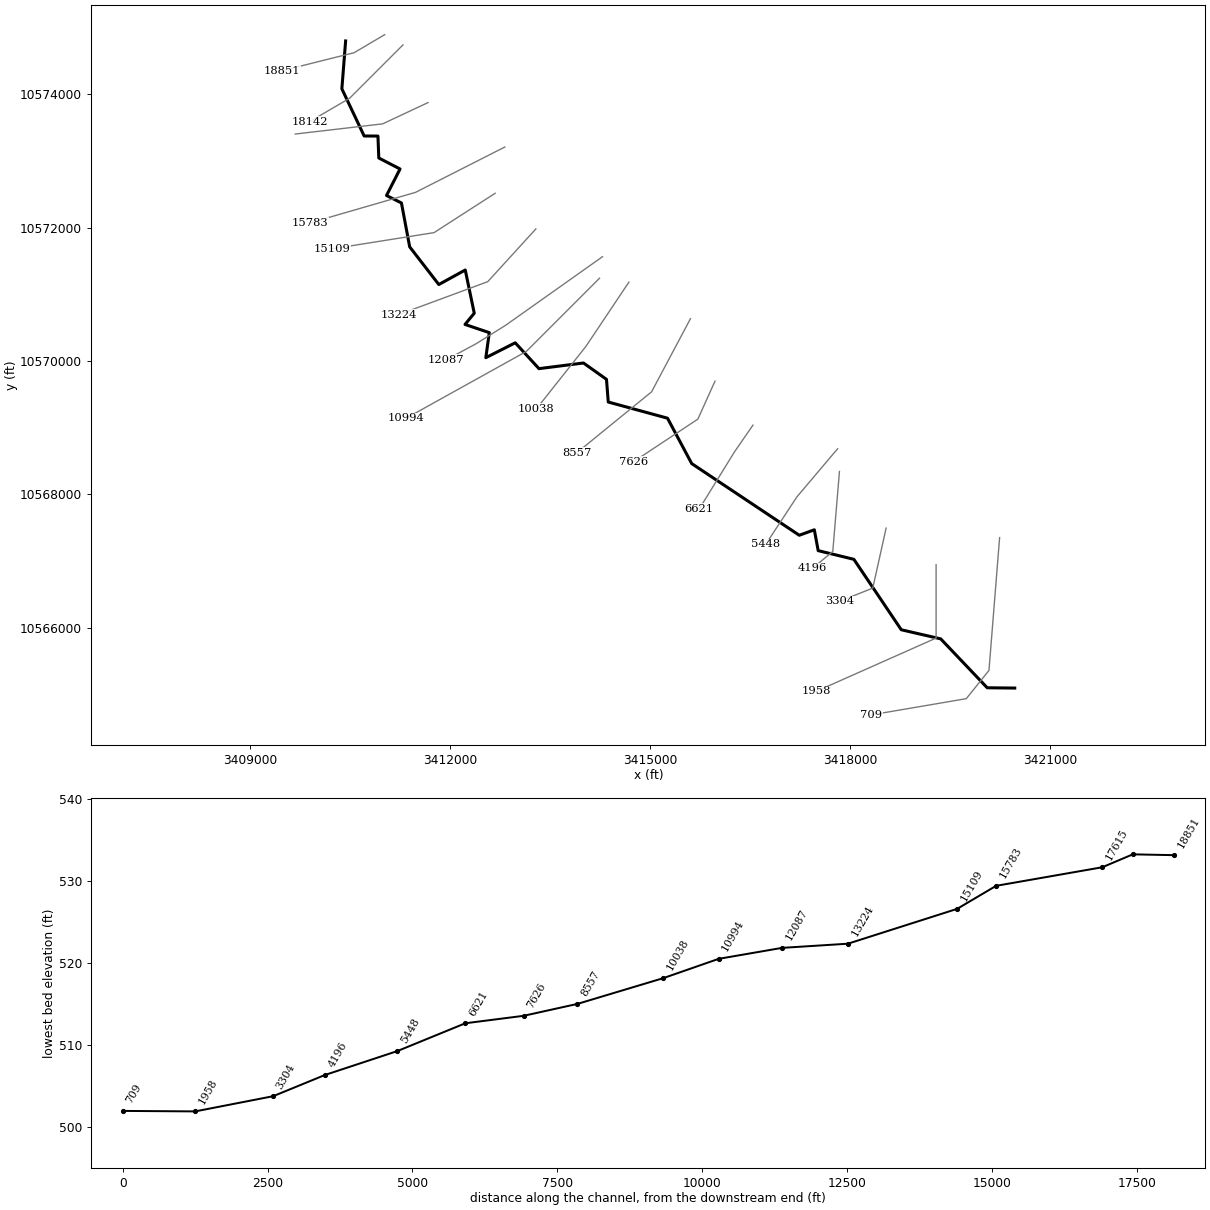
--- UNT0032 IN CHRS.prj (project) ---

Proj Title=UNT0032 IN CHRS Base Level Engineering
Current Plan=p01
Default Exp/Contr=0.3,0.1
English Units
Geom File=g01
Flow File=f01
Plan File=p01
BEGIN DESCRIPTION:
UNT0032 IN CHRS
END DESCRIPTION:

--- UNT0032 IN CHRS.p01 (plan) ---

Plan Title=Multiple Run
Short Identifier=Multiple
Geom File=g01
Flow File=f01
Subcritical Flow
K Sum by GR= 0
Std Step Tol= 0.01
Critical Tol= 0.01
Num of Std Step Trials= 20
Max Error Tol= 0.3
Flow Tol Ratio= 0.001
Split Flow NTrial= 30
Split Flow Tol= 0.02
Split Flow Ratio= 0.02
Log Output Level= 0
Friction Slope Method= 1
Unsteady Friction Slope Method= 2
Unsteady Bridges Friction Slope Method= 1
Parabolic Critical Depth
Global Vel Dist=  1 , 1 , 1
Global Log Level= 0
CheckData=True
Encroach Param= -1, 0, 0, 0
BEGIN DESCRIPTION:
Multiple Run
END DESCRIPTION:

--- UNT0032 IN CHRS.f01 (steady flow) ---

Flow Title=Multiple
Number of Profiles=7
Profile Names=10-year,25-year,50-year,1pct_min,100-year,1pct_plu,500-year
River Rch & RM= UNT0032 IN CHRS,Reach-1,18851
     422     529     608     508     687     929     876
River Rch & RM= UNT0032 IN CHRS,Reach-1,18142
     501     633     730     612     828    1120    1063
River Rch & RM= UNT0032 IN CHRS,Reach-1,13224
     549     694     800     670     906    1226    1162
River Rch & RM= UNT0032 IN CHRS,Reach-1,8557
     679     867    1006     847    1146    1549    1485
Boundary for River Rch & Prof#=UNT0032 IN CHRS,Reach-1,1
Up Type=0
Dn Type=3
Dn Slope=0.005
Boundary for River Rch & Prof#=UNT0032 IN CHRS,Reach-1,2
Up Type=0
Dn Type=3
Dn Slope=0.005
Boundary for River Rch & Prof#=UNT0032 IN CHRS,Reach-1,3
Up Type=0
Dn Type=3
Dn Slope=0.005
Boundary for River Rch & Prof#=UNT0032 IN CHRS,Reach-1,4
Up Type=0
Dn Type=3
Dn Slope=0.005
Boundary for River Rch & Prof#=UNT0032 IN CHRS,Reach-1,5
Up Type=0
Dn Type=3
Dn Slope=0.005
Boundary for River Rch & Prof#=UNT0032 IN CHRS,Reach-1,6
Up Type=0
Dn Type=3
Dn Slope=0.005
Boundary for River Rch & Prof#=UNT0032 IN CHRS,Reach-1,7
Up Type=0
Dn Type=3
Dn Slope=0.005

--- UNT0032 IN CHRS.g01 (geometry) ---

Geom Title=Existing Conditions

River Reach=UNT0032 IN CHRS,Reach-1
Reach XY= 30
      3410432.11     10574801.64      3410375.71     10574083.24
      3410710.18     10573375.47      3410917.07     10573374.40
      3410929.84     10573045.29      3411248.71     10572880.52
      3411045.72     10572482.60      3411269.72     10572370.65
      3411393.22     10571712.11      3411830.36     10571146.63
      3412227.14     10571364.48      3412362.31     10570716.28
      3412223.70     10570547.69      3412588.08     10570424.81
      3412535.71     10570048.82      3412977.10     10570272.25
      3413333.30     10569884.38      3414001.37     10569969.17
      3414346.42     10569723.85      3414372.82     10569383.70
      3415261.95     10569140.95      3415625.29     10568459.78
      3417239.07     10567384.54      3417464.98     10567466.28
      3417522.84     10567153.70      3418058.30     10567023.42
      3418769.43     10565966.65      3419361.64     10565829.68
      3420059.19     10565095.83      3420472.11     10565091.64

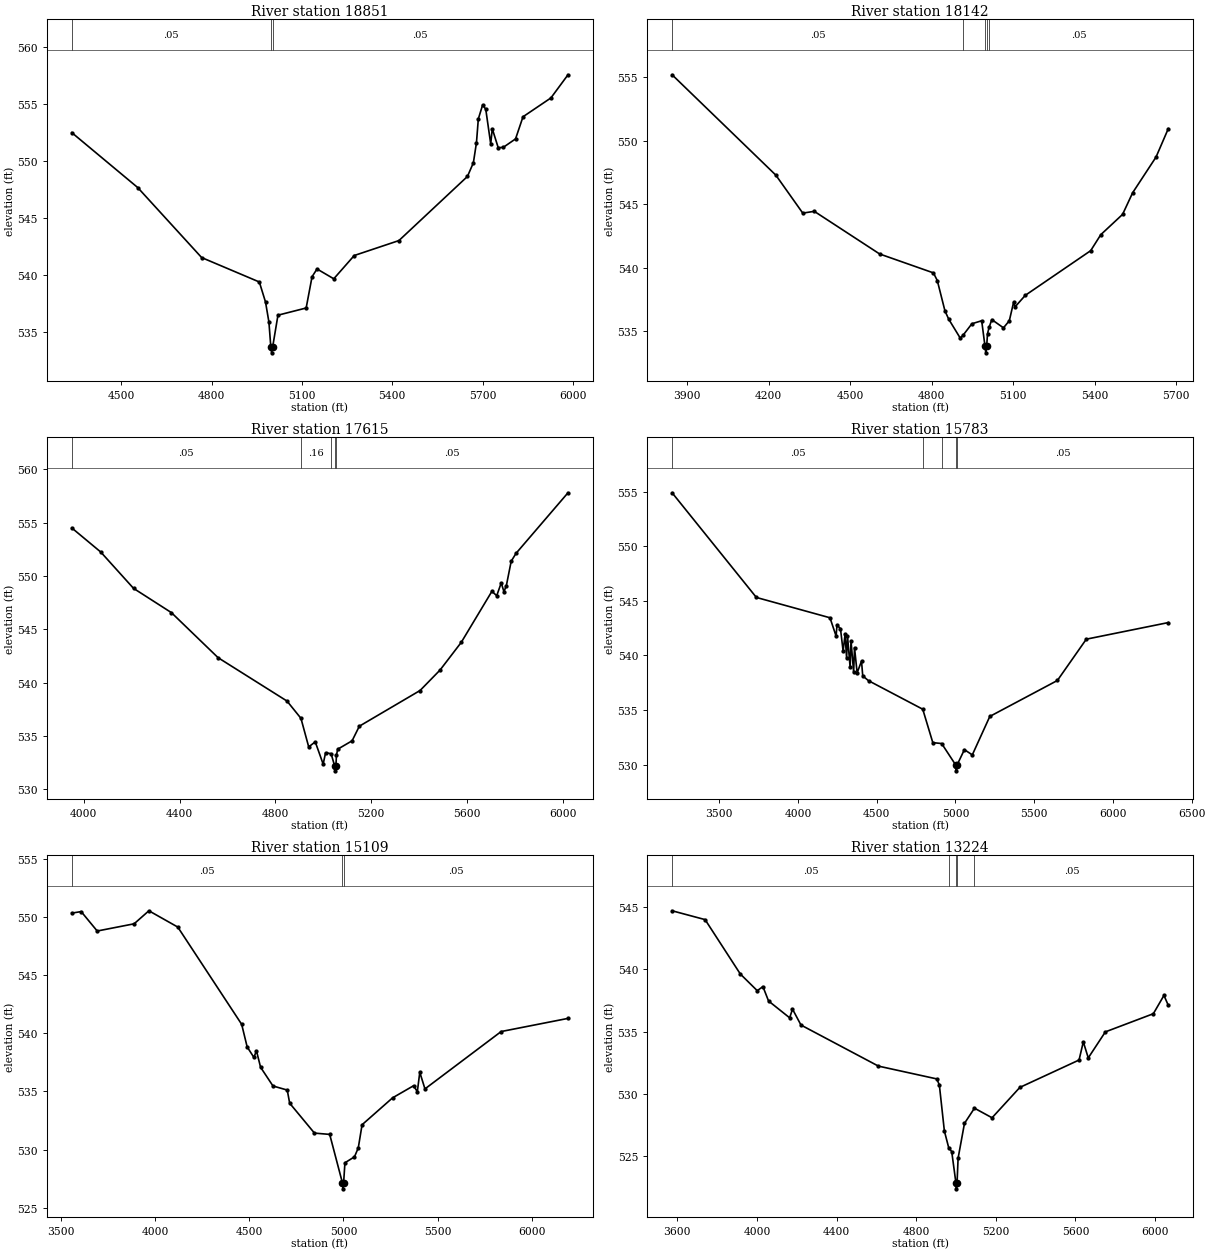
Type RM Length L Ch R = 1,18851,709,709,709
BEGIN DESCRIPTION:
UNT0032 IN CHRS 28.3
END DESCRIPTION:
XS GIS Cut Line= 3
      3411018.58     10574896.21      3410560.28     10574625.40
      3409477.05     10574354.59
#Sta/Elev= 30
  4334.9  552.49  4553.8  547.68  4766.4  541.54  4958.1  539.40  4978.7  537.64
  4990.0  535.88  4996.3  533.69  4999.1  533.19  5002.3  533.69  5020.0  536.49
  5113.7  537.12  5133.3  539.86  5149.8  540.54  5205.5  539.68  5273.5  541.72
  5422.0  543.03  5649.7  548.65  5669.4  549.85  5679.7  551.62  5685.8  553.69
  5700.3  554.93  5710.6  554.53  5727.0  551.50  5732.2  552.83  5751.8  551.18
  5768.2  551.19  5809.5  551.94  5834.3  553.88  5927.0  555.53  5983.8  557.56
#Mann=3,-1,0
  4334.9    0.05       0  4996.3   0.035       0  5002.3    0.05       0
Bank Sta=4996.3,5002.3
Exp/Cntr=0.3,0.1

Type RM Length L Ch R = 1,18142,527,527,527
BEGIN DESCRIPTION:
UNT0032 IN CHRS 28.0
END DESCRIPTION:
XS GIS Cut Line= 3
      3411292.09     10574741.63      3410492.11     10573941.64
      3409892.08     10573591.63
#Sta/Elev= 30
  3844.4  555.20  4226.2  547.29  4325.2  544.30  4367.6  544.44  4608.1  541.08
  4806.0  539.59  4820.2  538.99  4848.5  536.59  4862.6  535.93  4905.0  534.44
  4916.6  534.72  4947.5  535.58  4983.6  535.82  4995.9  533.79  4998.7  533.29
  5001.9  533.79  5005.1  534.81  5010.9  535.29  5020.8  535.91  5063.8  535.26
  5085.3  535.82  5101.0  537.27  5106.8  536.92  5144.0  537.82  5384.7  541.34
  5421.9  542.60  5502.1  544.20  5539.3  545.91  5625.3  548.72  5670.4  550.96
#Mann=5,-1,0
  3844.4    0.05       0  4916.6    0.16       0  4995.9    0.07       0
  5001.9    0.16       0  5010.9    0.05       0
Bank Sta=4995.9,5001.9
Exp/Cntr=0.3,0.1

Type RM Length L Ch R = 1,17615,1832,1832,1832
BEGIN DESCRIPTION:
UNT0032 IN CHRS 25.0
END DESCRIPTION:
XS GIS Cut Line= 3
      3411668.81     10573876.99      3410988.25     10573557.55
      3409676.41     10573404.84
#Sta/Elev= 30
  3949.9  554.51  4070.8  552.25  4207.7  548.84  4366.0  546.56  4561.0  542.33
  4848.8  538.26  4907.0  536.64  4939.4  533.96  4966.8  534.43  4999.8  532.34
  5009.9  533.41  5033.0  533.32  5047.2  532.21  5049.9  531.71  5053.2  532.21
  5055.3  533.17  5060.4  533.74  5120.7  534.53  5150.9  535.90  5404.5  539.25
  5488.0  541.17  5576.6  543.77  5704.6  548.56  5724.7  548.15  5743.6  549.35
  5754.9  548.52  5765.0  549.10  5785.1  551.38  5805.2  552.12  6022.4  557.81
#Mann=5,-1,0
  3949.9    0.05       0  4907.0    0.16       0  5033.0    0.05       0
  5047.2    0.07       0  5053.2    0.05       0
Bank Sta=5047.2,5053.2
Exp/Cntr=0.3,0.1

Type RM Length L Ch R = 1,15783,674,674,674
BEGIN DESCRIPTION:
UNT0032 IN CHRS 24.0
END DESCRIPTION:
XS GIS Cut Line= 3
      3412821.61     10573210.34      3411481.30     10572529.77
      3409898.00     10572071.44
#Sta/Elev= 30
  3200.2  554.89  3735.4  545.31  4202.9  543.45  4241.8  541.77  4247.4  542.79
  4269.6  542.44  4286.3  540.40  4298.7  541.92  4308.5  539.76  4314.1  541.80
  4330.8  538.91  4336.4  541.34  4353.1  538.49  4358.7  540.72  4375.3  538.41
  4403.2  539.48  4410.9  538.13  4447.7  537.69  4792.0  535.08  4856.0  532.02
  4912.1  531.94  5003.0  529.94  5005.8  529.44  5009.0  529.94  5056.5  531.38
  5106.8  530.90  5218.0  534.42  5647.2  537.71  5830.8  541.49  6351.7  543.01
#Mann=5,-1,0
  3200.2    0.05       0  4792.0    0.16       0  4912.1    0.05       0
  5003.0   0.035       0  5009.0    0.05       0
Bank Sta=5003,5009
Exp/Cntr=0.3,0.1

Type RM Length L Ch R = 1,15109,1885,1885,1885
BEGIN DESCRIPTION:
UNT0032 IN CHRS 22.0
END DESCRIPTION:
XS GIS Cut Line= 3
      3412675.71     10572515.85      3411759.08     10571925.60
      3410231.32     10571682.55
#Sta/Elev= 30
  3556.0  550.32  3605.9  550.45  3691.1  548.78  3887.2  549.40  3965.8  550.52
  4119.3  549.12  4458.9  540.76  4488.0  538.82  4523.7  537.92  4537.5  538.48
  4559.4  537.07  4625.3  535.46  4701.1  535.11  4714.0  533.98  4845.7  531.41
  4926.7  531.30  4994.6  527.12  4997.3  526.62  5000.6  527.12  5007.7  528.86
  5058.3  529.37  5078.6  530.14  5098.8  532.13  5260.8  534.44  5372.2  535.48
  5392.5  534.97  5405.5  536.64  5433.0  535.21  5838.0  540.14  6193.2  541.27
#Mann=3,-1,0
  3556.0    0.05       0  4994.6    0.03       0  5000.6    0.05       0
Bank Sta=4994.6,5000.6
Exp/Cntr=0.3,0.1

Type RM Length L Ch R = 1,13224,1137,1137,1137
BEGIN DESCRIPTION:
UNT0032 IN CHRS 21.0
END DESCRIPTION:
XS GIS Cut Line= 3
      3413286.85     10571981.14      3412564.64     10571189.49
      3411231.55     10570696.52
#Sta/Elev= 30
  3573.7  544.70  3739.4  543.99  3916.4  539.62  4001.5  538.28  4029.9  538.61
  4058.3  537.45  4164.3  536.10  4178.5  536.80  4221.1  535.52  4610.2  532.22
  4903.9  531.19  4916.4  530.69  4941.5  527.01  4963.2  525.67  4978.5  525.35
  4999.3  522.86  5002.1  522.36  5005.3  522.86  5010.5  524.82  5042.5  527.62
  5092.7  528.84  5181.1  528.07  5320.8  530.51  5618.2  532.71  5639.5  534.17
  5664.4  532.88  5750.3  534.97  5991.4  536.43  6044.7  537.90  6066.6  537.10
#Mann=5,-1,0
  3573.7    0.05       0  4963.2    0.16       0  4999.3    0.07       0
  5005.3    0.16       0  5092.7    0.05       0
Bank Sta=4999.3,5005.3
Exp/Cntr=0.3,0.1

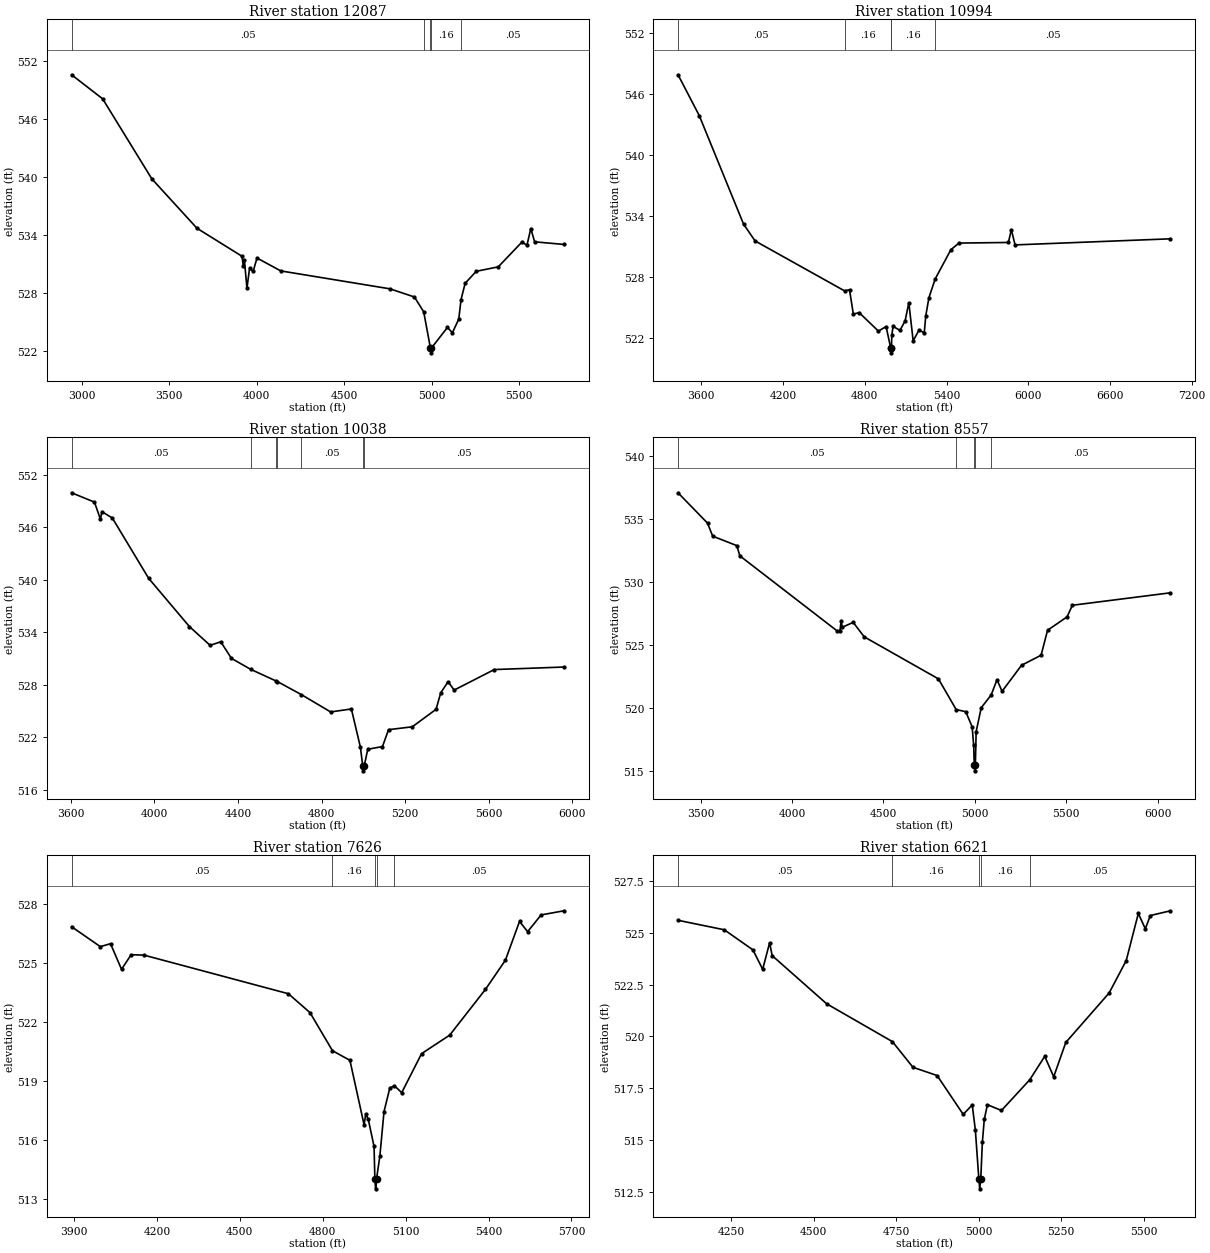
Type RM Length L Ch R = 1,12087,1093,1093,1093
BEGIN DESCRIPTION:
UNT0032 IN CHRS 19.0
END DESCRIPTION:
XS GIS Cut Line= 4
      3414286.88     10571564.50      3412835.47     10570536.71
      3412391.03     10570258.93      3411940.38     10570016.28
#Sta/Elev= 30
  2942.7  550.53  3120.1  548.05  3401.0  539.80  3659.2  534.70  3916.6  531.81
  3924.0  530.81  3930.1  531.42  3944.9  528.52  3959.7  530.56  3980.6  530.27
  4002.3  531.63  4138.1  530.30  4762.7  528.45  4902.0  527.61  4955.1  526.08
  4993.4  522.35  4996.1  521.85  4999.4  522.35  5090.7  524.47  5118.9  523.92
  5155.4  525.33  5168.5  527.35  5192.0  529.03  5255.6  530.26  5381.3  530.72
  5516.6  533.28  5545.2  532.95  5567.1  534.67  5589.0  533.30  5757.1  533.03
#Mann=5,-1,0
  2942.7    0.05       0  4955.1    0.16       0  4993.4    0.07       0
  4999.4    0.16       0  5168.5    0.05       0
Bank Sta=4993.4,4999.4
Exp/Cntr=0.3,0.1

Type RM Length L Ch R = 1,10994,956,956,956
BEGIN DESCRIPTION:
UNT0032 IN CHRS 18.0
END DESCRIPTION:
XS GIS Cut Line= 3
      3414242.11     10571241.65      3413142.11     10570141.64
      3411342.08     10569141.63
#Sta/Elev= 30
  3429.2  547.87  3584.8  543.86  3910.0  533.18  3994.9  531.52  4651.2  526.61
  4687.9  526.72  4716.1  524.32  4758.6  524.47  4900.0  522.65  4956.6  523.10
  4989.8  521.01  4992.6  520.51  4995.8  521.01  4998.6  522.25  5007.7  523.12
  5058.1  522.72  5095.8  523.64  5123.3  525.44  5155.3  521.69  5198.8  522.77
  5236.5  522.46  5248.0  524.17  5270.8  525.93  5316.8  527.78  5432.1  530.66
  5491.6  531.31  5854.2  531.37  5876.0  532.62  5903.4  531.13  7044.0  531.73
#Mann=5,-1,0
  3429.2    0.05       0  4651.2    0.16       0  4989.8    0.07       0
  4995.8    0.16       0  5316.8    0.05       0
Bank Sta=4989.8,4995.8
Exp/Cntr=0.3,0.1

Type RM Length L Ch R = 1,10038,1481,1481,1481
BEGIN DESCRIPTION:
UNT0032 IN CHRS 16.0
END DESCRIPTION:
XS GIS Cut Line= 3
      3414682.72     10571182.59      3414036.86     10570217.27
      3413293.81     10569279.78
#Sta/Elev= 30
  3603.4  549.97  3712.8  548.90  3741.1  546.97  3748.9  547.80  3798.2  547.09
  3972.3  540.18  4167.5  534.66  4266.6  532.51  4317.6  532.92  4368.7  531.02
  4460.4  529.77  4581.7  528.44  4588.4  528.37  4703.0  526.88  4843.6  524.89
  4942.9  525.23  4986.2  520.85  4997.6  518.65  5000.4  518.15  5003.6  518.65
  5021.5  520.62  5091.9  520.93  5120.8  522.86  5234.6  523.19  5348.3  525.19
  5370.8  527.08  5406.0  528.35  5434.9  527.39  5627.0  529.74  5961.1  530.03
#Mann=7,-1,0
  3603.4    0.05       0  4460.4     0.1       0  4581.7    0.05       0
  4588.4     0.1       0  4703.0    0.05       0  4997.6   0.035       0
  5003.6    0.05       0
Bank Sta=4997.6,5003.6
Exp/Cntr=0.3,0.1

Type RM Length L Ch R = 1,8557,931,931,931
BEGIN DESCRIPTION:
UNT0032 IN CHRS 15.0
END DESCRIPTION:
XS GIS Cut Line= 3
      3415606.31     10570633.94      3415022.97     10569536.71
      3413897.99     10568620.06
#Sta/Elev= 30
  3377.0  537.10  3538.2  534.69  3566.7  533.65  3698.6  532.90  3714.9  532.09
  4247.4  526.12  4263.0  526.15  4269.3  526.92  4275.0  526.41  4335.3  526.80
  4395.5  525.65  4801.4  522.31  4898.5  519.87  4951.0  519.70  4986.1  518.49
  4994.1  517.03  4997.5  515.50  5000.3  515.00  5003.5  515.50  5007.8  518.12
  5035.7  520.02  5089.6  521.02  5121.9  522.24  5149.6  521.32  5256.1  523.39
  5363.2  524.19  5398.3  526.17  5505.3  527.24  5534.1  528.16  6070.8  529.15
#Mann=5,-1,0
  3377.0    0.05       0  4898.5    0.16       0  4997.5    0.07       0
  5003.5    0.16       0  5089.6    0.05       0
Bank Sta=4997.5,5003.5
Exp/Cntr=0.3,0.1

Type RM Length L Ch R = 1,7626,1005,1005,1005
BEGIN DESCRIPTION:
UNT0032 IN CHRS 13.0
END DESCRIPTION:
XS GIS Cut Line= 3
      3415974.34     10569696.40      3415717.42     10569126.99
      3414752.18     10568488.13
#Sta/Elev= 30
  3891.0  526.84  3995.0  525.83  4031.8  525.98  4071.7  524.68  4106.6  525.42
  4152.9  525.40  4675.7  523.44  4753.9  522.48  4835.1  520.55  4898.3  520.06
  4949.5  516.79  4955.5  517.33  4964.5  517.08  4985.6  515.69  4988.6  514.04
  4991.3  513.54  4994.6  514.04  5006.6  515.20  5021.7  517.46  5042.7  518.66
  5059.4  518.77  5085.7  518.42  5157.6  520.40  5259.4  521.34  5388.7  523.66
  5460.9  525.14  5512.1  527.11  5541.4  526.59  5590.3  527.44  5673.2  527.65
#Mann=5,-1,0
  3891.0    0.05       0  4835.1    0.16       0  4988.6    0.07       0
  4994.6    0.16       0  5059.4    0.05       0
Bank Sta=4988.6,4994.6
Exp/Cntr=0.3,0.1

Type RM Length L Ch R = 1,6621,1173,1173,1173
BEGIN DESCRIPTION:
UNT0032 IN CHRS 11.0
END DESCRIPTION:
XS GIS Cut Line= 3
      3416543.78     10569036.67      3416266.03     10568633.93
      3415738.25     10567779.76
#Sta/Elev= 30
  4088.2  525.62  4228.6  525.16  4315.2  524.19  4344.9  523.25  4365.9  524.53
  4373.7  523.91  4539.0  521.58  4738.4  519.75  4800.6  518.51  4873.9  518.11
  4953.1  516.23  4980.3  516.69  4989.8  515.48  5000.3  513.13  5003.1  512.63
  5006.3  513.13  5011.1  514.89  5016.9  515.99  5026.4  516.70  5069.0  516.42
  5155.0  517.91  5200.2  519.04  5227.4  518.05  5264.0  519.71  5395.3  522.10
  5447.3  523.67  5484.0  525.95  5505.2  525.21  5520.5  525.85  5581.5  526.08
#Mann=5,-1,0
  4088.2    0.05       0  4738.4    0.16       0  5000.3    0.07       0
  5006.3    0.16       0  5155.0    0.05       0
Bank Sta=5000.3,5006.3
Exp/Cntr=0.3,0.1

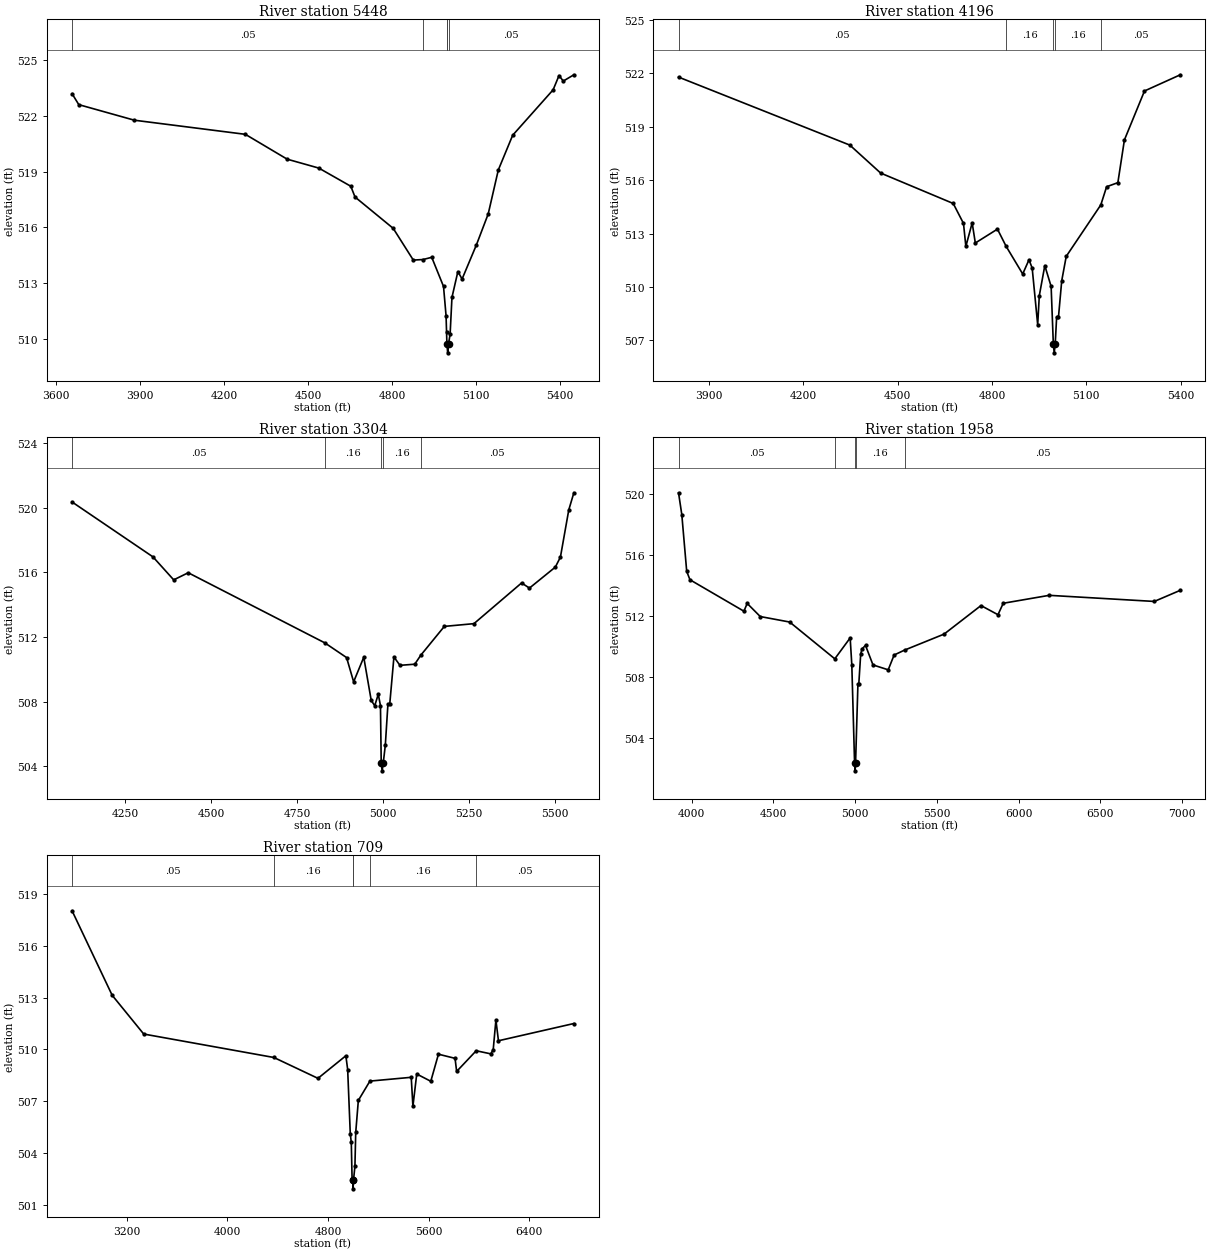
Type RM Length L Ch R = 1,5448,1252,1252,1252
BEGIN DESCRIPTION:
UNT0032 IN CHRS 9.0
END DESCRIPTION:
XS GIS Cut Line= 3
      3417814.65     10568682.56      3417203.53     10567960.32
      3416738.24     10567251.97
#Sta/Elev= 30
  3656.3  523.20  3680.3  522.61  3879.2  521.77  4275.7  521.01  4425.2  519.67
  4538.3  519.19  4652.6  518.21  4667.7  517.63  4804.2  515.94  4876.0  514.23
  4910.9  514.26  4941.9  514.38  4984.0  512.81  4993.1  511.23  4994.8  510.38
  4996.1  509.73  4998.9  509.23  5002.1  509.73  5007.6  510.24  5014.2  512.22
  5035.3  513.61  5050.4  513.21  5101.6  515.05  5143.8  516.72  5179.9  519.09
  5231.2  520.96  5375.8  523.41  5396.9  524.18  5412.0  523.88  5449.9  524.22
#Mann=5,-1,0
  3656.3    0.05       0  4910.9    0.16       0  4994.8    0.05       0
  4996.1   0.035       0  5002.1    0.05       0
Bank Sta=4996.1,5002.1
Exp/Cntr=0.3,0.1

Type RM Length L Ch R = 1,4196,892,892,892
BEGIN DESCRIPTION:
UNT0032 IN CHRS 7.0
END DESCRIPTION:
XS GIS Cut Line= 3
      3417842.10     10568341.63      3417742.11     10567141.64
      3417442.08     10566891.62
#Sta/Elev= 30
  3804.0  521.79  4348.4  517.97  4446.2  516.40  4677.0  514.69  4709.6  513.57
  4717.1  512.28  4737.2  513.60  4747.2  512.47  4817.5  513.25  4845.2  512.28
  4897.8  510.73  4917.8  511.53  4927.9  511.06  4945.4  507.88  4950.5  509.51
  4968.0  511.20  4988.1  510.03  4995.1  506.80  4997.9  506.30  5001.1  506.80
  5005.6  508.30  5011.4  508.30  5021.8  510.35  5036.1  511.72  5146.0  514.61
  5164.4  515.63  5200.2  515.86  5221.0  518.26  5284.8  521.01  5398.7  521.92
#Mann=5,-1,0
  3804.0    0.05       0  4845.2    0.16       0  4995.1    0.07       0
  5001.1    0.16       0  5146.0    0.05       0
Bank Sta=4995.1,5001.1
Exp/Cntr=0.3,0.1

Type RM Length L Ch R = 1,3304,1346,1346,1346
BEGIN DESCRIPTION:
UNT0032 IN CHRS 5.0
END DESCRIPTION:
XS GIS Cut Line= 3
      3418542.11     10567491.66      3418342.11     10566591.64
      3417842.09     10566391.64
#Sta/Elev= 30
  4095.3  520.35  4330.9  516.95  4391.1  515.53  4433.4  515.97  4831.0  511.63
  4894.3  510.72  4914.8  509.22  4944.3  510.74  4966.0  508.07  4976.3  507.74
  4986.5  508.45  4992.9  507.75  4995.1  504.21  4997.8  503.71  5001.1  504.21
  5007.0  505.29  5014.7  507.86  5020.0  507.86  5032.1  510.76  5049.6  510.24
  5092.7  510.31  5110.4  510.87  5178.8  512.65  5265.0  512.82  5403.7  515.34
  5426.5  515.02  5501.9  516.32  5516.7  516.94  5541.0  519.86  5555.8  520.92
#Mann=5,-1,0
  4095.3    0.05       0  4831.0    0.16       0  4995.1    0.07       0
  5001.1    0.16       0  5110.4    0.05       0
Bank Sta=4995.1,5001.1
Exp/Cntr=0.3,0.1

Type RM Length L Ch R = 1,1958,1249,1249,1249
BEGIN DESCRIPTION:
UNT0032 IN CHRS 3.0
END DESCRIPTION:
XS GIS Cut Line= 3
      3419292.11     10566941.69      3419292.11     10565841.64
      3417492.12     10565041.65
#Sta/Elev= 30
  3919.1  520.07  3939.1  518.64  3969.1  514.92  3989.1  514.37  4319.1  512.31
  4339.1  512.82  4419.1  511.96  4599.1  511.60  4875.1  509.19  4969.1  510.56
  4979.1  508.81  4996.1  502.35  4998.9  501.85  5002.1  502.35  5016.6  507.54
  5021.9  507.54  5033.5  509.50  5041.0  509.83  5062.9  510.07  5108.7  508.79
  5201.8  508.47  5238.0  509.44  5301.6  509.76  5543.7  510.81  5769.4  512.68
  5873.4  512.08  5905.5  512.83  6186.6  513.35  6829.6  512.95  6988.9  513.68
#Mann=5,-1,0
  3919.1    0.05       0  4875.1    0.16       0  4996.1    0.07       0
  5002.1    0.16       0  5301.6    0.05       0
Bank Sta=4996.1,5002.1
Exp/Cntr=0.3,0.1

Type RM Length L Ch R = 1,709,0,0,0
BEGIN DESCRIPTION:
UNT0032 IN CHRS 1.0
END DESCRIPTION:
XS GIS Cut Line= 4
      3420245.19     10567349.17      3420085.47     10565356.16
      3419745.19     10564932.55      3418321.55     10564689.48
#Sta/Elev= 30
  2766.0  518.04  3084.5  513.14  3335.3  510.89  4369.3  509.53  4719.8  508.32
  4941.4  509.63  4955.8  508.83  4976.6  505.09  4984.6  504.60  4991.0  502.43
  4996.0  502.41  4998.7  501.91  5002.0  502.41  5013.4  503.21  5019.8  505.18
  5040.6  507.04  5132.6  508.16  5460.8  508.38  5474.2  506.70  5504.6  508.57
  5616.2  508.15  5677.1  509.72  5809.0  509.48  5821.7  508.72  5977.0  509.92
  6093.0  509.74  6112.3  509.99  6133.6  511.70  6153.9  510.50  6753.0  511.50
#Mann=6,-1,0
  2766.0    0.05       0  4369.3    0.16       0  4996.0    0.07       0
  5002.0    0.16       0  5132.6    0.16       0  5977.0    0.05       0
Bank Sta=4996,5002
Exp/Cntr=0.3,0.1

Chan Stop Cuts=-1