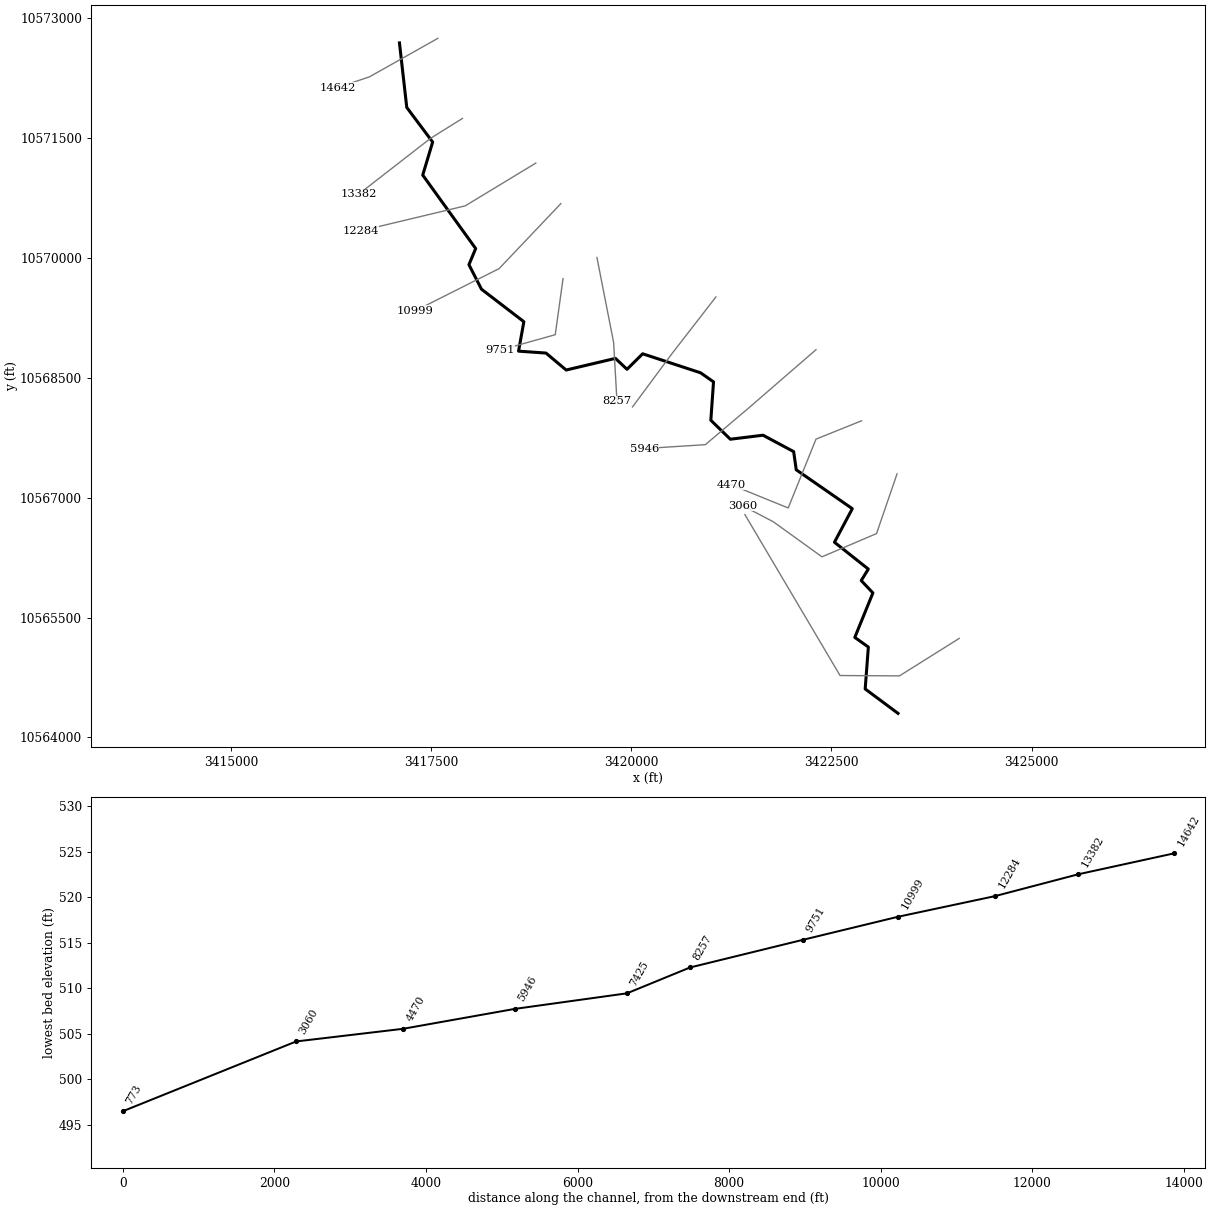
--- UNT0033 IN CHRS.prj (project) ---

Proj Title=UNT0033 IN CHRS Base Level Engineering
Current Plan=p01
Default Exp/Contr=0.3,0.1
English Units
Geom File=g01
Flow File=f01
Plan File=p01
BEGIN DESCRIPTION:
UNT0033 IN CHRS
END DESCRIPTION:

--- UNT0033 IN CHRS.p01 (plan) ---

Plan Title=Multiple Run
Short Identifier=Multiple
Geom File=g01
Flow File=f01
Subcritical Flow
K Sum by GR= 0
Std Step Tol= 0.01
Critical Tol= 0.01
Num of Std Step Trials= 20
Max Error Tol= 0.3
Flow Tol Ratio= 0.001
Split Flow NTrial= 30
Split Flow Tol= 0.02
Split Flow Ratio= 0.02
Log Output Level= 0
Friction Slope Method= 1
Unsteady Friction Slope Method= 2
Unsteady Bridges Friction Slope Method= 1
Parabolic Critical Depth
Global Vel Dist=  1 , 1 , 1
Global Log Level= 0
CheckData=True
Encroach Param= -1, 0, 0, 0
BEGIN DESCRIPTION:
Multiple Run
END DESCRIPTION:

--- UNT0033 IN CHRS.f01 (steady flow) ---

Flow Title=Multiple
Number of Profiles=7
Profile Names=10-year,25-year,50-year,1pct_min,100-year,1pct_plu,500-year
River Rch & RM= UNT0033 IN CHRS,Reach-1,14642
     332     409     464     384     519     702     646
River Rch & RM= UNT0033 IN CHRS,Reach-1,13382
     471     590     677     564     763    1032     968
River Rch & RM= UNT0033 IN CHRS,Reach-1,7425
     480     602     690     574     777    1050     984
River Rch & RM= UNT0033 IN CHRS,Reach-1,4470
     537     676     777     649     878    1187    1118
Boundary for River Rch & Prof#=UNT0033 IN CHRS,Reach-1,1
Up Type=0
Dn Type=3
Dn Slope=0.005
Boundary for River Rch & Prof#=UNT0033 IN CHRS,Reach-1,2
Up Type=0
Dn Type=3
Dn Slope=0.005
Boundary for River Rch & Prof#=UNT0033 IN CHRS,Reach-1,3
Up Type=0
Dn Type=3
Dn Slope=0.005
Boundary for River Rch & Prof#=UNT0033 IN CHRS,Reach-1,4
Up Type=0
Dn Type=3
Dn Slope=0.005
Boundary for River Rch & Prof#=UNT0033 IN CHRS,Reach-1,5
Up Type=0
Dn Type=3
Dn Slope=0.005
Boundary for River Rch & Prof#=UNT0033 IN CHRS,Reach-1,6
Up Type=0
Dn Type=3
Dn Slope=0.005
Boundary for River Rch & Prof#=UNT0033 IN CHRS,Reach-1,7
Up Type=0
Dn Type=3
Dn Slope=0.005

--- UNT0033 IN CHRS.g01 (geometry) ---

Geom Title=Existing Conditions

River Reach=UNT0033 IN CHRS,Reach-1
Reach XY= 30
      3417104.79     10572685.69      3417196.15     10571878.45
      3417519.61     10571445.92      3417395.49     10571032.73
      3418056.74     10570114.35      3417972.66     10569912.16
      3418129.55     10569605.65      3418658.59     10569199.54
      3418592.48     10568831.22      3418934.90     10568807.28
      3419187.14     10568595.22      3419802.69     10568740.77
      3419946.98     10568604.10      3420142.44     10568798.25
      3420866.24     10568560.33      3421027.68     10568447.03
      3420994.10     10567967.13      3421237.88     10567729.77
      3421646.04     10567780.00      3422028.64     10567574.90
      3422060.79     10567347.73      3422761.29     10566861.54
      3422538.23     10566441.57      3422961.11     10566106.14
      3422872.74     10565962.28      3423018.48     10565807.79
      3422792.35     10565251.60      3422961.59     10565131.39
      3422922.05     10564607.02      3423332.11     10564301.64

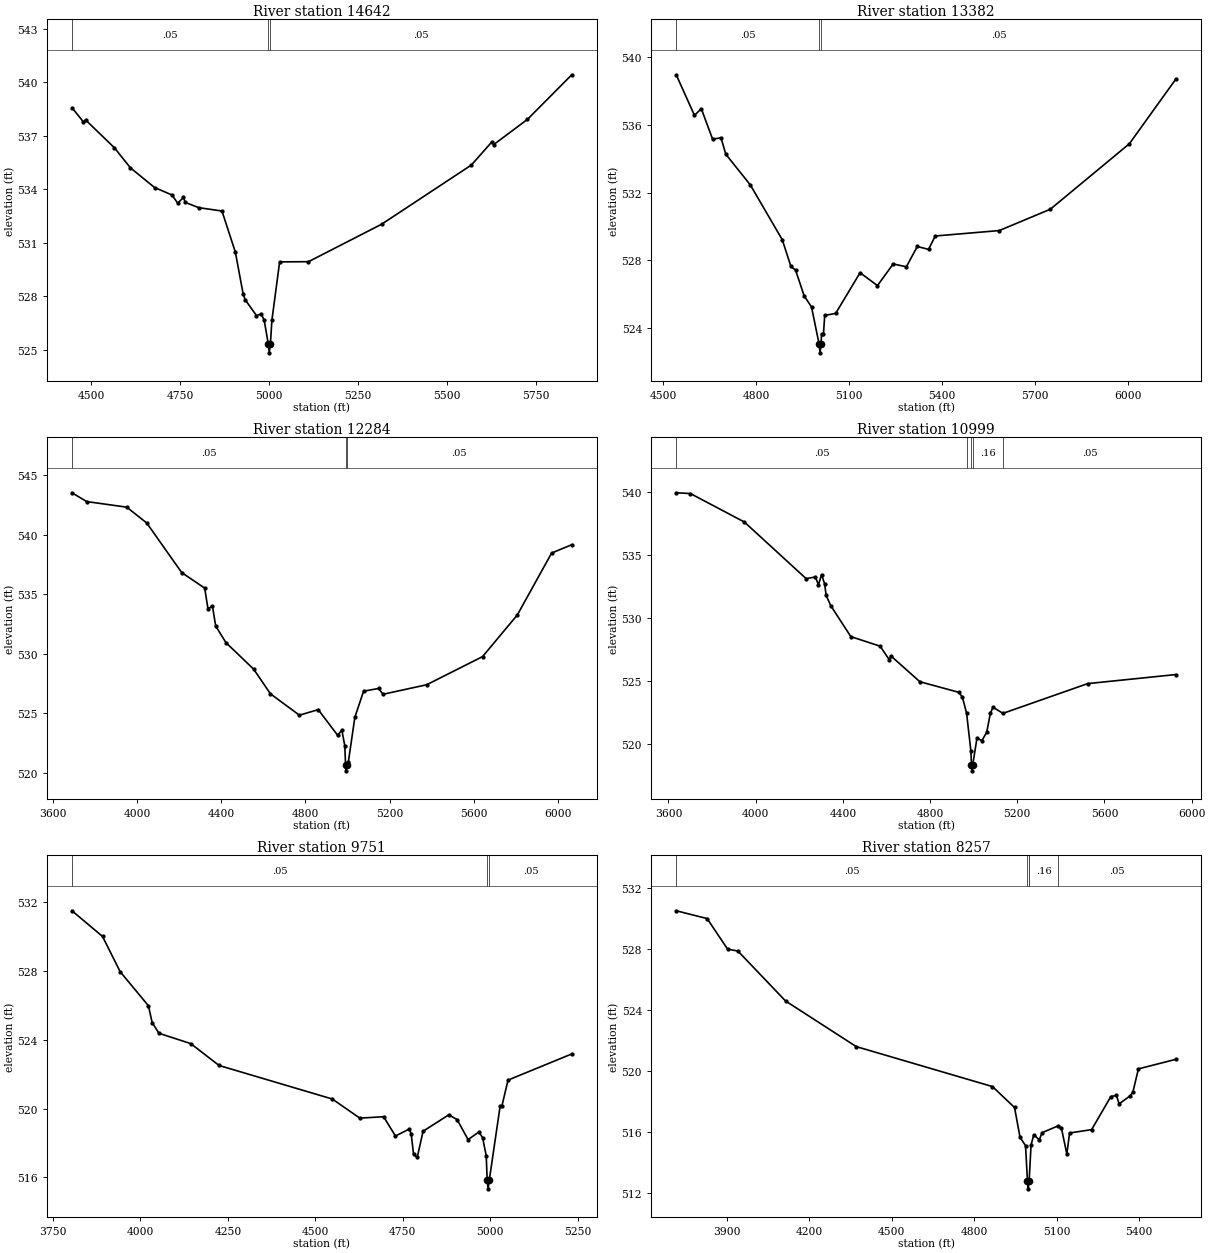
Type RM Length L Ch R = 1,14642,1260,1260,1260
BEGIN DESCRIPTION:
UNT0033 IN CHRS 15.5
END DESCRIPTION:
XS GIS Cut Line= 3
      3417584.70     10572742.83      3416729.63     10572261.03
      3416330.54     10572126.56
#Sta/Elev= 30
  4446.7  538.58  4479.0  537.77  4484.8  537.89  4565.7  536.33  4610.4  535.21
  4678.4  534.10  4727.5  533.68  4743.4  533.22  4759.4  533.54  4765.1  533.26
  4802.7  532.97  4867.7  532.78  4905.3  530.47  4926.9  528.15  4932.7  527.81
  4964.5  526.92  4977.7  527.01  4986.2  526.66  4997.6  525.33  5000.4  524.83
  5003.6  525.33  5007.8  526.66  5029.5  529.93  5110.4  529.94  5315.6  532.04
  5567.6  535.36  5625.3  536.66  5630.6  536.51  5725.0  537.92  5849.3  540.42
#Mann=3,-1,0
  4446.7    0.05       0  4997.6    0.03       0  5003.6    0.05       0
Bank Sta=4997.6,5003.6
Exp/Cntr=0.3,0.1

Type RM Length L Ch R = 1,13382,1098,1098,1098
BEGIN DESCRIPTION:
UNT0033 IN CHRS 15.0
END DESCRIPTION:
XS GIS Cut Line= 3
      3417892.09     10571741.63      3417492.11     10571491.64
      3416592.07     10570791.62
#Sta/Elev= 30
  4542.2  538.96  4601.1  536.56  4623.0  536.96  4659.5  535.16  4686.6  535.24
  4702.0  534.27  4781.0  532.46  4884.2  529.22  4911.9  527.65  4927.2  527.42
  4954.9  525.90  4978.5  525.25  5003.2  523.04  5006.0  522.54  5009.2  523.04
  5010.9  523.66  5017.1  523.66  5021.1  524.75  5056.4  524.87  5135.1  527.27
  5191.2  526.51  5241.9  527.79  5284.4  527.62  5319.7  528.82  5355.9  528.65
  5377.7  529.44  5584.0  529.76  5748.7  531.02  6003.8  534.89  6154.1  538.72
#Mann=3,-1,0
  4542.2    0.05       0  5003.2   0.035       0  5009.2    0.05       0
Bank Sta=5003.2,5009.2
Exp/Cntr=0.3,0.1

Type RM Length L Ch R = 1,12284,1285,1285,1285
BEGIN DESCRIPTION:
UNT0033 IN CHRS 12.0
END DESCRIPTION:
XS GIS Cut Line= 3
      3418807.70     10571182.55      3417925.75     10570647.82
      3416620.22     10570335.33
#Sta/Elev= 30
  3691.1  543.53  3761.2  542.79  3951.2  542.32  4046.2  540.99  4212.2  536.82
  4321.5  535.51  4337.0  533.78  4358.3  533.99  4373.8  532.32  4422.7  530.92
  4554.2  528.69  4633.7  526.62  4771.5  524.82  4860.7  525.29  4952.5  523.14
  4973.0  523.55  4986.9  522.25  4990.6  520.64  4993.3  520.14  4996.6  520.64
  5003.9  520.90  5034.7  524.64  5076.1  526.84  5147.8  527.07  5168.4  526.58
  5375.6  527.38  5641.4  529.75  5806.3  533.25  5969.3  538.46  6064.9  539.16
#Mann=3,-1,0
  3691.1    0.05       0  4990.6   0.035       0  4996.6    0.05       0
Bank Sta=4990.6,4996.6
Exp/Cntr=0.3,0.1

Type RM Length L Ch R = 1,10999,1248,1248,1248
BEGIN DESCRIPTION:
UNT0033 IN CHRS 10.0
END DESCRIPTION:
XS GIS Cut Line= 3
      3419120.19     10570675.60      3418349.36     10569863.10
      3417302.10     10569336.00
#Sta/Elev= 30
  3635.9  539.92  3700.9  539.86  3948.5  537.60  4231.6  533.11  4274.1  533.24
  4288.3  532.62  4302.4  533.43  4316.6  532.69  4323.5  531.78  4344.5  530.97
  4436.7  528.51  4571.0  527.75  4613.5  526.67  4620.4  526.98  4753.4  524.93
  4931.9  524.09  4948.4  523.71  4967.8  522.43  4987.5  519.41  4990.1  518.36
  4992.8  517.86  4996.1  518.36  5015.4  520.46  5037.7  520.25  5060.0  520.92
  5076.7  522.42  5088.7  522.91  5134.5  522.42  5523.1  524.78  5928.3  525.50
#Mann=5,-1,0
  3635.9    0.05       0  4967.8    0.16       0  4990.1    0.07       0
  4996.1    0.16       0  5134.5    0.05       0
Bank Sta=4990.1,4996.1
Exp/Cntr=0.3,0.1

Type RM Length L Ch R = 1,9751,1494,1494,1494
BEGIN DESCRIPTION:
UNT0033 IN CHRS 9.0
END DESCRIPTION:
XS GIS Cut Line= 3
      3419147.98     10569738.13      3419050.75     10569036.71
      3418356.67     10568842.37
#Sta/Elev= 30
  3804.3  531.50  3891.6  530.01  3942.1  527.96  4022.9  525.98  4033.6  525.00
  4053.1  524.38  4144.0  523.78  4224.8  522.51  4548.6  520.56  4627.2  519.45
  4695.4  519.53  4729.1  518.41  4768.9  518.82  4774.1  518.54  4781.0  517.34
  4791.4  517.17  4808.2  518.69  4881.6  519.64  4905.6  519.36  4936.8  518.20
  4967.9  518.65  4978.3  518.31  4988.7  517.26  4991.4  515.84  4994.1  515.34
  4997.4  515.84  5028.5  520.16  5033.7  520.17  5051.0  521.66  5233.2  523.18
#Mann=3,-1,0
  3804.3    0.05       0  4991.4   0.035       0  4997.4    0.05       0
Bank Sta=4991.4,4997.4
Exp/Cntr=0.3,0.1

Type RM Length L Ch R = 1,8257,832,832,832
BEGIN DESCRIPTION:
UNT0033 IN CHRS 8.0
END DESCRIPTION:
XS GIS Cut Line= 3
      3419571.59     10570001.95      3419779.92     10568939.49
      3419821.49     10568205.05
#Sta/Elev= 30
  3716.0  530.51  3828.4  530.00  3902.7  528.00  3940.5  527.87  4113.7  524.60
  4371.0  521.61  4866.6  518.99  4946.8  517.62  4966.8  515.67  4986.8  515.12
  4993.9  512.79  4996.6  512.29  4999.9  512.79  5000.0  512.82  5006.9  515.16
  5016.9  515.84  5036.9  515.50  5046.9  515.97  5104.5  516.41  5117.0  516.30
  5137.1  514.57  5147.1  515.95  5227.2  516.17  5297.3  518.34  5317.4  518.41
  5327.4  517.86  5367.4  518.38  5377.5  518.64  5397.5  520.15  5534.3  520.78
#Mann=5,-1,0
  3716.0    0.05       0  4993.9    0.07       0  4999.9    0.05       0
  5000.0    0.16       0  5104.5    0.05       0
Bank Sta=4993.9,4999.9
Exp/Cntr=0.3,0.1

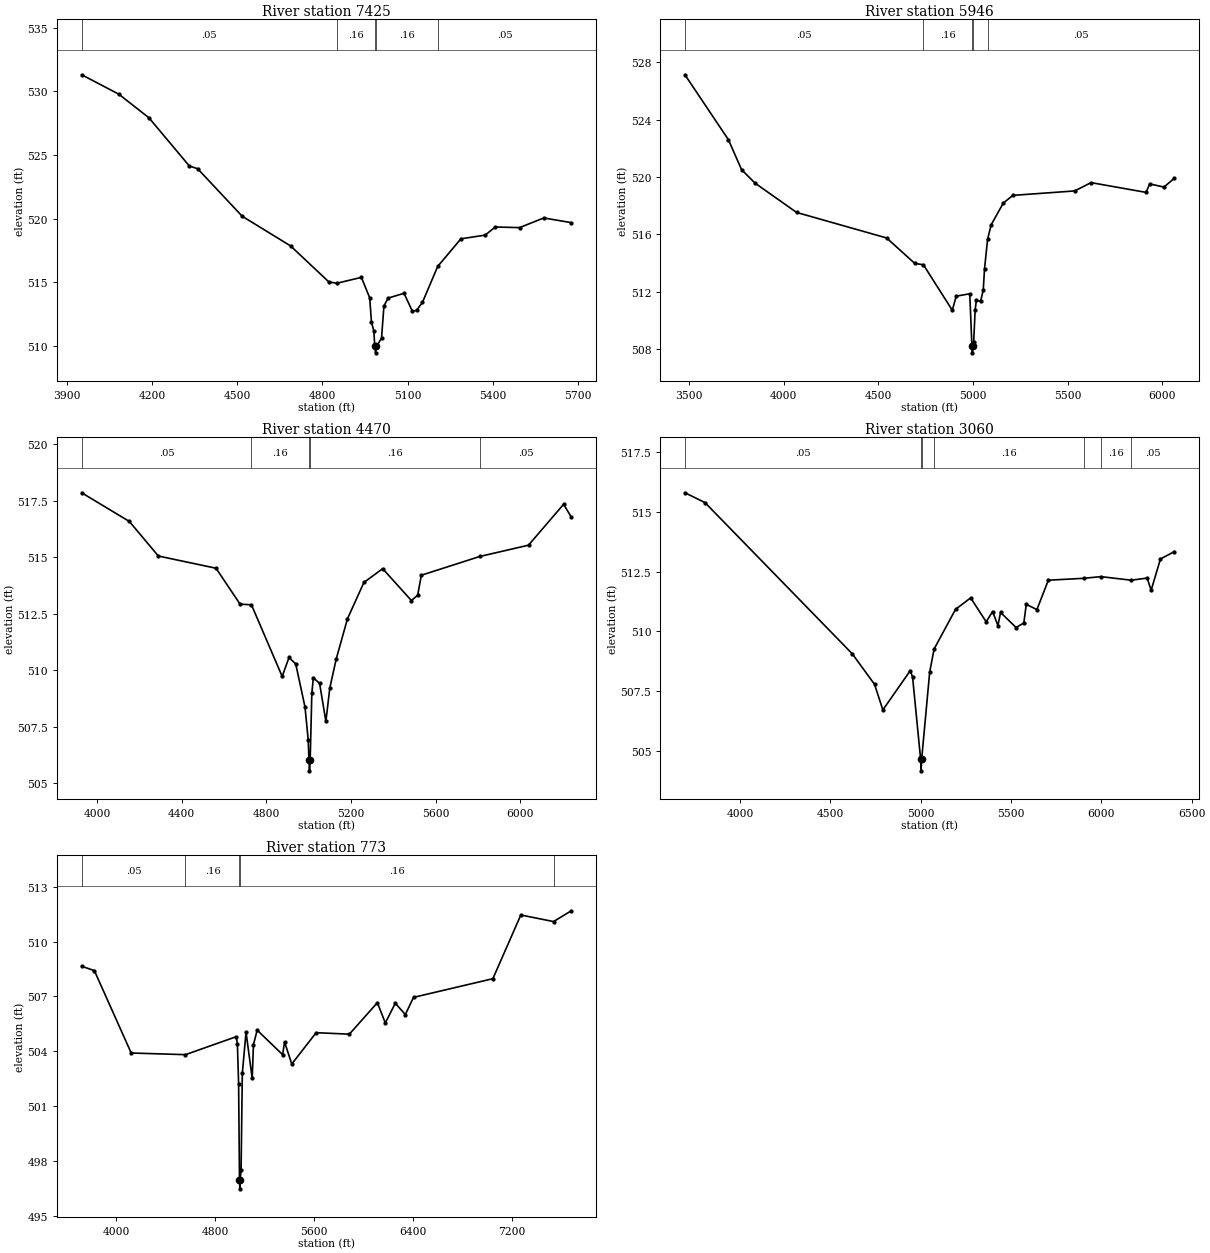
Type RM Length L Ch R = 1,7425,1479,1479,1479
BEGIN DESCRIPTION:
UNT0033 IN CHRS 7.0
END DESCRIPTION:
XS GIS Cut Line= 3
      3421057.67     10569508.91      3420509.08     10568800.60
      3420016.02     10568133.93
#Sta/Elev= 30
  3951.9  531.30  4082.4  529.78  4188.8  527.92  4331.3  524.13  4360.3  523.92
  4517.6  520.18  4688.1  517.85  4822.9  515.02  4851.2  514.92  4937.5  515.38
  4966.8  513.77  4973.0  511.86  4981.4  511.16  4984.6  509.95  4987.4  509.45
  4990.6  509.95  5008.5  510.61  5016.9  513.13  5031.5  513.75  5087.8  514.13
  5117.1  512.72  5131.7  512.78  5152.5  513.41  5206.4  516.24  5288.2  518.41
  5373.8  518.70  5409.3  519.34  5494.8  519.29  5580.4  520.05  5677.0  519.68
#Mann=5,-1,0
  3951.9    0.05       0  4851.2    0.16       0  4984.6    0.07       0
  4990.6    0.16       0  5206.4    0.05       0
Bank Sta=4984.6,4990.6
Exp/Cntr=0.3,0.1

Type RM Length L Ch R = 1,5946,1476,1476,1476
BEGIN DESCRIPTION:
UNT0033 IN CHRS 5.0
END DESCRIPTION:
XS GIS Cut Line= 4
      3422307.72     10568849.23      3421474.36     10568126.99
      3420925.75     10567661.71      3420161.82     10567613.10
#Sta/Elev= 30
  3477.5  527.13  3706.9  522.61  3777.1  520.51  3848.4  519.57  4067.7  517.53
  4543.6  515.75  4691.9  513.98  4738.1  513.88  4890.7  510.71  4911.5  511.69
  4983.0  511.86  4994.3  508.24  4997.0  507.74  5000.3  508.24  5003.8  508.51
  5011.5  510.74  5018.1  511.40  5040.1  511.33  5054.4  512.12  5061.0  513.59
  5077.3  515.66  5096.1  516.67  5160.2  518.18  5210.4  518.72  5537.8  519.03
  5623.9  519.61  5914.5  518.93  5934.5  519.52  6009.5  519.30  6065.1  519.92
#Mann=5,-1,0
  3477.5    0.05       0  4738.1    0.16       0  4994.3    0.07       0
  5000.3    0.16       0  5077.3    0.05       0
Bank Sta=4994.3,5000.3
Exp/Cntr=0.3,0.1

Type RM Length L Ch R = 1,4470,1410,1410,1410
BEGIN DESCRIPTION:
UNT0033 IN CHRS 3.0
END DESCRIPTION:
XS GIS Cut Line= 4
      3422877.09     10567960.30      3422307.69     10567731.16
      3421960.47     10566870.05      3421246.14     10567161.33
#Sta/Elev= 30
  3926.9  517.86  4152.1  516.59  4289.2  515.06  4561.7  514.52  4675.4  512.93
  4729.2  512.90  4874.4  509.73  4906.8  510.57  4938.5  510.28  4982.2  508.38
  4997.6  506.91  5000.8  506.05  5003.5  505.55  5006.8  506.05  5014.6  508.99
  5021.8  509.67  5051.3  509.42  5080.9  507.74  5099.6  509.22  5129.2  510.48
  5182.9  512.28  5260.7  513.89  5349.3  514.50  5485.1  513.09  5514.6  513.32
  5532.2  514.21  5808.2  515.04  6038.6  515.54  6204.4  517.35  6240.6  516.79
#Mann=5,-1,0
  3926.9    0.05       0  4729.2    0.16       0  5000.8    0.07       0
  5006.8    0.16       0  5808.2    0.05       0
Bank Sta=5000.8,5006.8
Exp/Cntr=0.3,0.1

Type RM Length L Ch R = 1,3060,2287,2287,2287
BEGIN DESCRIPTION:
UNT0033 IN CHRS 2.0
END DESCRIPTION:
XS GIS Cut Line= 5
      3423319.90     10567296.53      3423063.83     10566550.01
      3422382.41     10566259.21      3421774.77     10566697.58
      3421393.38     10566896.94
#Sta/Elev= 30
  3695.2  515.80  3806.1  515.39  4621.3  509.06  4744.8  507.78  4790.7  506.71
  4942.9  508.36  4955.4  508.07  4999.6  504.66  5002.4  504.16  5005.6  504.66
  5049.9  508.29  5074.4  509.26  5193.0  510.92  5276.7  511.40  5362.6  510.40
  5398.3  510.83  5427.6  510.24  5442.3  510.79  5528.2  510.16  5570.9  510.35
  5584.6  511.13  5643.5  510.91  5706.6  512.14  5903.4  512.22  5997.8  512.29
  6165.3  512.14  6253.6  512.23  6275.7  511.72  6327.4  513.03  6404.9  513.34
#Mann=7,-1,0
  3695.2    0.05       0  4999.6   0.035       0  5005.6    0.05       0
  5074.4    0.16       0  5903.4    0.05       0  5997.8    0.16       0
  6165.3    0.05       0
Bank Sta=4999.6,5005.6
Exp/Cntr=0.3,0.1

Type RM Length L Ch R = 1,773,0,0,0
BEGIN DESCRIPTION:
UNT0033 IN CHRS 1.0
END DESCRIPTION:
XS GIS Cut Line= 4
      3424096.85     10565239.27      3423350.29     10564770.50
      3422608.10     10564774.84      3421419.50     10566787.66
#Sta/Elev= 30
  3719.5  508.65  3822.0  508.41  4120.0  503.91  4559.3  503.82  4969.2  504.80
  4979.2  504.42  4989.2  502.23  4996.2  496.99  4999.0  496.49  5002.2  496.99
  5009.2  497.54  5019.2  502.80  5049.2  505.05  5099.2  502.52  5109.2  504.36
  5139.2  505.16  5345.3  503.82  5360.9  504.51  5419.4  503.31  5616.5  505.02
  5885.4  504.94  6112.0  506.66  6176.3  505.55  6257.0  506.63  6338.3  506.01
  6404.7  506.95  7046.7  507.97  7272.8  511.45  7537.9  511.09  7680.8  511.68
#Mann=5,-1,0
  3719.5    0.05       0  4559.3    0.16       0  4996.2    0.07       0
  5002.2    0.16       0  7537.9    0.05       0
Bank Sta=4996.2,5002.2
Exp/Cntr=0.3,0.1

Chan Stop Cuts=-1