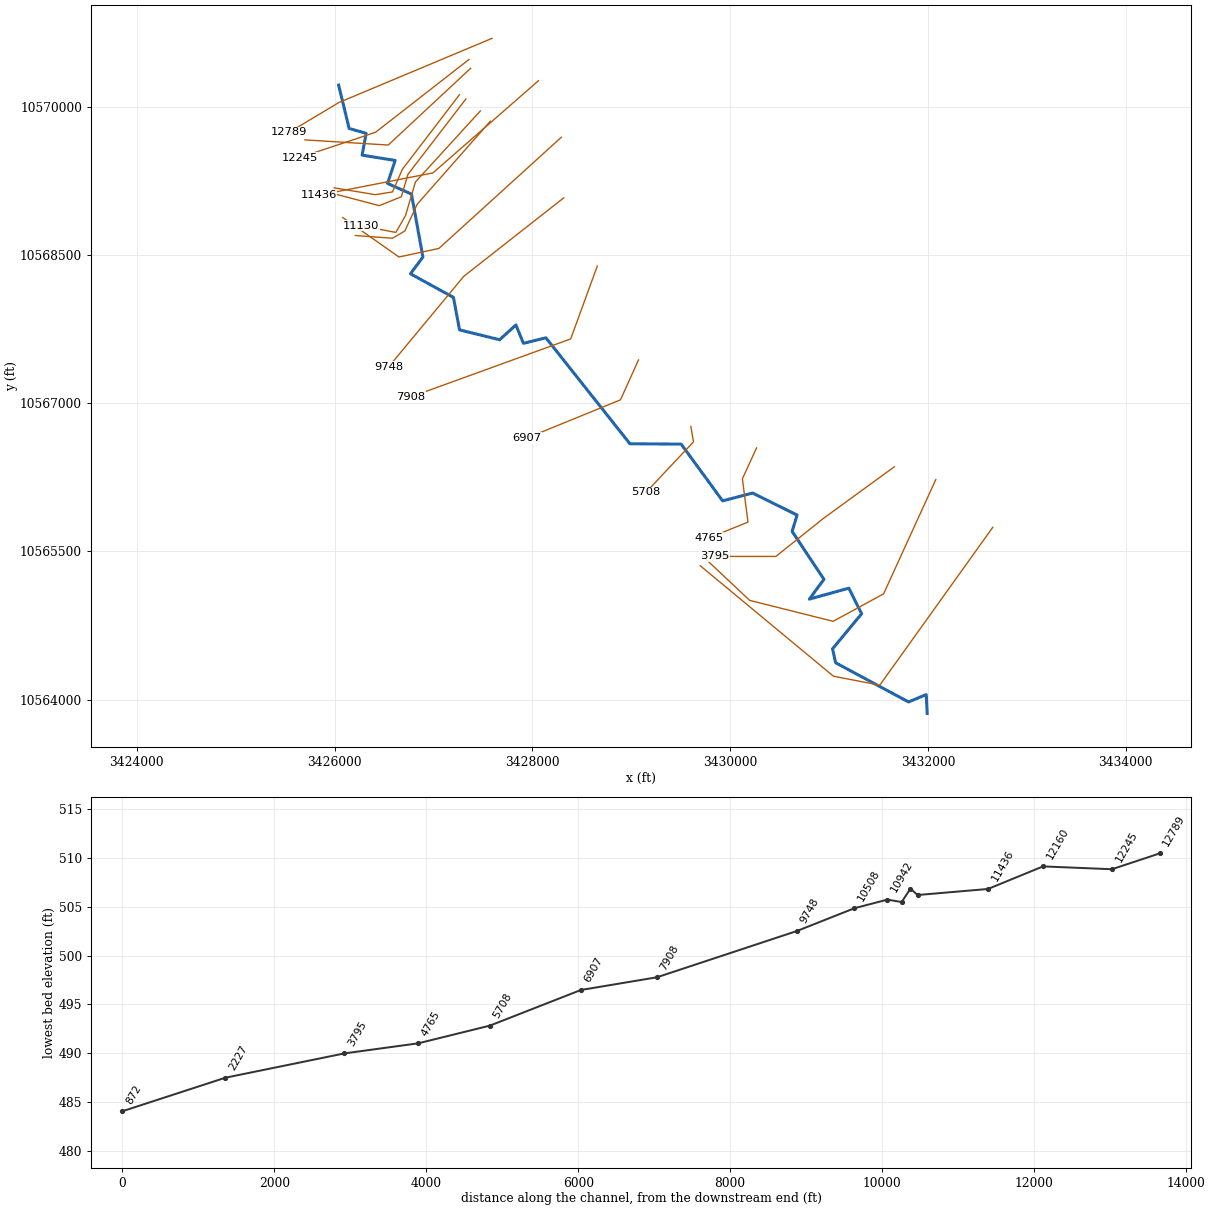
--- UNT0035 IN CHRS.prj (project) ---

Proj Title=UNT0035 IN CHRS Base Level Engineering
Current Plan=p01
Default Exp/Contr=0.3,0.1
English Units
Geom File=g01
Flow File=f01
Plan File=p01
Y Axis Title=Elevation
X Axis Title(PF)=Main Channel Distance
X Axis Title(XS)=Station
BEGIN DESCRIPTION:
UNT0035 IN CHRS
END DESCRIPTION:
DSS Export Rating Curves= 0
DSS Export Rating Curve Sorted= 0
DSS Export Volume Flow Curves= 0
DXF OffsetX= 0
DXF OffsetY= 0
DXF ScaleX= 1
DXF ScaleY= 10

--- UNT0035 IN CHRS.p01 (plan) ---

Plan Title=Multiple Run
Short Identifier=Multiple
Geom File=g01
Flow File=f01
Subcritical Flow
K Sum by GR= 0
Std Step Tol= 0.01
Critical Tol= 0.01
Num of Std Step Trials= 20
Max Error Tol= 0.3
Flow Tol Ratio= 0.001
Split Flow NTrial= 30
Split Flow Tol= 0.02
Split Flow Ratio= 0.02
Log Output Level= 0
Friction Slope Method= 1
Unsteady Friction Slope Method= 2
Unsteady Bridges Friction Slope Method= 1
Parabolic Critical Depth
Global Vel Dist=  1 , 1 , 1
Global Log Level= 0
CheckData=True
Encroach Param= -1, 0, 0, 0
BEGIN DESCRIPTION:
Multiple Run
END DESCRIPTION:

--- UNT0035 IN CHRS.f01 (steady flow) ---

Flow Title=Multiple
Number of Profiles=7
Profile Names=10-year,25-year,50-year,1pct_min,100-year,1pct_plu,500-year
River Rch & RM= UNT0035 IN CHRS,Reach-1,12789
     325     399     451     371     502     679     621
River Rch & RM= UNT0035 IN CHRS,Reach-1,10508
     403     499     569     471     637     861     797
River Rch & RM= UNT0035 IN CHRS,Reach-1,4765
     586     741     856     718     971    1313    1246
Boundary for River Rch & Prof#=UNT0035 IN CHRS,Reach-1,1
Up Type=0
Dn Type=3
Dn Slope=0.005
Boundary for River Rch & Prof#=UNT0035 IN CHRS,Reach-1,2
Up Type=0
Dn Type=3
Dn Slope=0.005
Boundary for River Rch & Prof#=UNT0035 IN CHRS,Reach-1,3
Up Type=0
Dn Type=3
Dn Slope=0.005
Boundary for River Rch & Prof#=UNT0035 IN CHRS,Reach-1,4
Up Type=0
Dn Type=3
Dn Slope=0.005
Boundary for River Rch & Prof#=UNT0035 IN CHRS,Reach-1,5
Up Type=0
Dn Type=3
Dn Slope=0.005
Boundary for River Rch & Prof#=UNT0035 IN CHRS,Reach-1,6
Up Type=0
Dn Type=3
Dn Slope=0.005
Boundary for River Rch & Prof#=UNT0035 IN CHRS,Reach-1,7
Up Type=0
Dn Type=3
Dn Slope=0.005

--- UNT0035 IN CHRS.g01 (geometry) ---

Geom Title=Existing Conditions
Program Version=4.10

River Reach=UNT0035 IN CHRS ,Reach-1
Reach XY= 30
      3426040.78     10570218.01      3426147.35     10569779.09
      3426319.39     10569730.85       3426277.9     10569509.83
      3426612.37     10569456.09      3426535.33     10569223.88
       3426777.3     10569115.38      3426892.95     10568479.26
      3426767.35     10568309.27      3427201.79     10568070.35
      3427263.19     10567742.09      3427668.55     10567641.92
      3427833.58     10567791.86      3427908.96     10567605.72
      3428136.91     10567661.55       3428986.1     10566589.47
      3429504.41     10566585.92      3429923.39     10566012.05
      3430226.95     10566091.08       3430676.3     10565868.02
      3430626.37     10565702.82       3430947.8     10565217.73
      3430800.63     10565017.87      3431199.86     10565128.34
      3431328.82     10564869.49      3431035.08     10564514.67
      3431066.27     10564373.56      3431803.55     10563977.15
      3431982.11     10564051.64      3431992.11     10563861.64

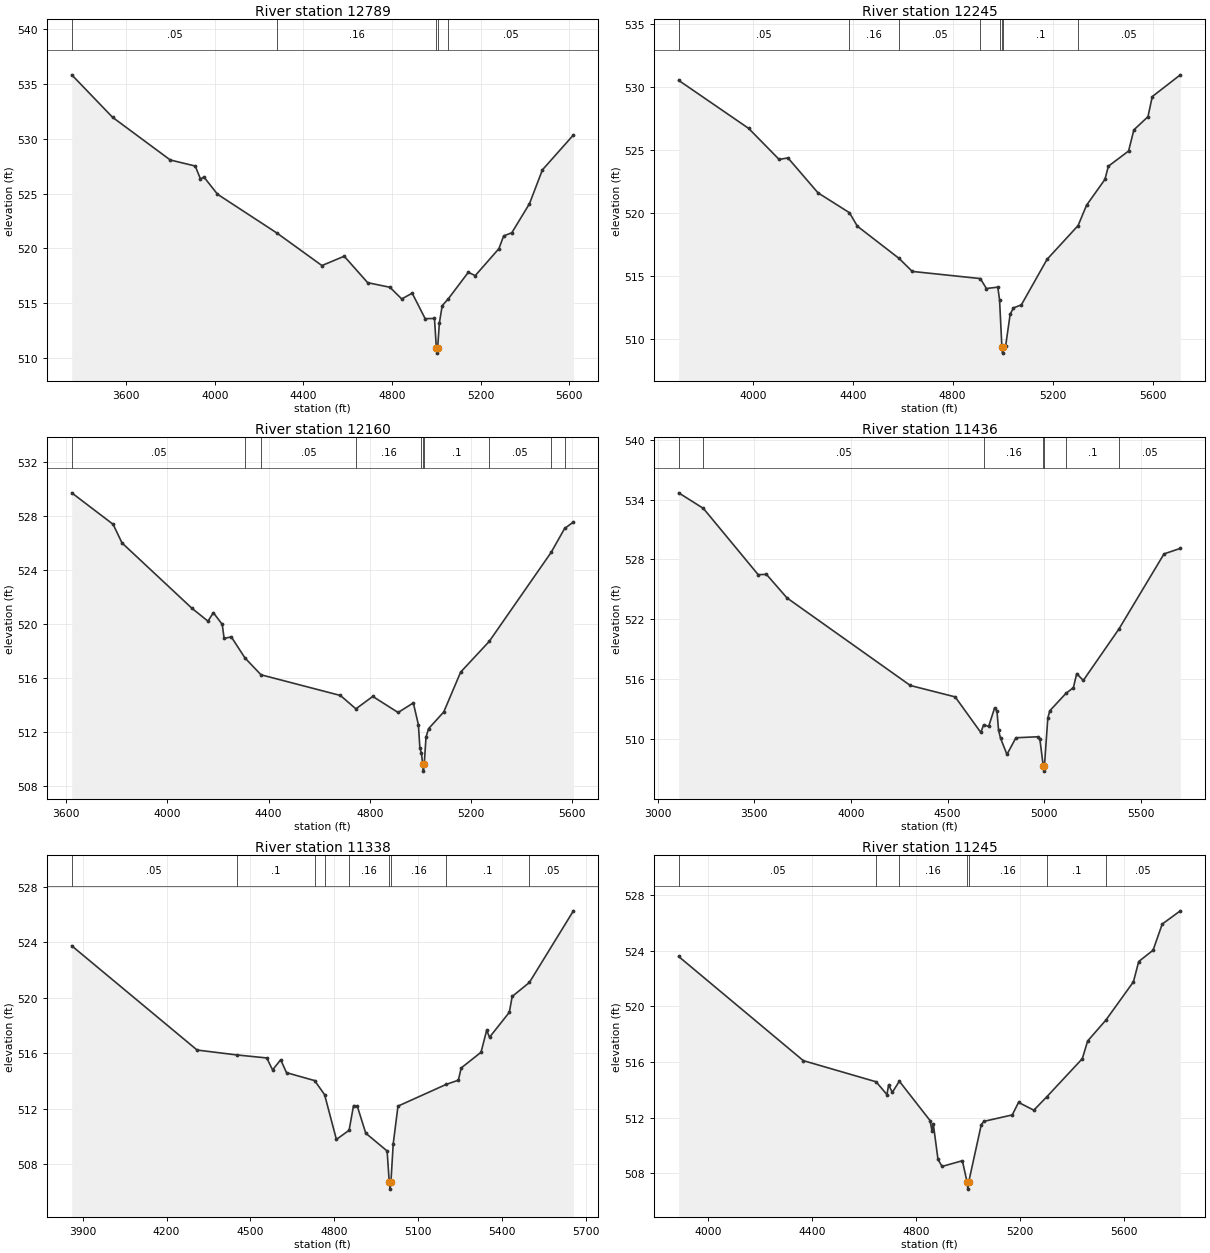
Type RM Length L Ch R = 1 ,12789   ,629,629,629
BEGIN DESCRIPTION:
UNT0035 IN CHRS 13.0
END DESCRIPTION:
XS GIS Cut Line= 3
      3427592.07     10570691.63      3426042.11     10570041.64
      3425542.13     10569741.66
#Sta/Elev= 30
  3354.3  535.82  3538.6  531.95  3798.9  528.06  3911.5  527.51  3935.2  526.33
  3950.7  526.51    4012  524.94  4280.4   521.4  4483.3  518.44  4583.8  519.29
  4689.7  516.88  4790.2  516.46  4843.2   515.4  4890.7  515.92  4949.1   513.6
  4991.2  513.62  4999.5  510.96  5002.3  510.46  5005.5  510.96  5013.3  513.21
  5025.9  514.78  5054.3  515.43  5143.9  517.83    5175  517.52  5281.9  519.98
  5303.3  521.14  5340.2  521.43  5419.9  524.08  5478.2  527.16  5618.1  530.34
#Mann= 5 ,-1 , 0
  3354.3     .05       0  4280.4     .16       0  4999.5     .07       0
  5005.5     .16       0  5054.3     .05       0
Bank Sta=4999.5,5005.5
XS Rating Curve= 0 ,0
Exp/Cntr=0.3,0.1

Type RM Length L Ch R = 1 ,12245   ,907,907,907
BEGIN DESCRIPTION:
UNT0035 IN CHRS 12.0
END DESCRIPTION:
XS GIS Cut Line= 4
      3427359.23     10570477.92      3426414.76     10569741.79
       3426209.9     10569672.34      3425645.53     10569485.38
#Sta/Elev= 30
  3703.1  530.54  3983.2  526.72  4105.2  524.25  4140.6  524.37    4261  521.59
  4386.8  520.01  4418.4  518.94  4585.7  516.37  4638.2  515.34  4910.8  514.77
    4935  513.98  4980.7  514.09  4987.7  513.08    4997  509.34  4999.8  508.84
    5003  509.34  5012.1  509.42  5030.1  511.93  5043.5  512.44    5075  512.68
  5177.8   516.3  5302.2  518.99  5335.8   520.6  5409.5  522.66  5423.3  523.71
  5504.3  524.92  5525.4   526.6  5581.8  527.65  5599.1  529.25  5711.4  530.98
#Mann= 8 ,-1 , 0
  3703.1     .05       0  4386.8     .16       0  4585.7     .05       0
  4910.8     .16       0  4987.7      .1       0    4997     .07       0
    5003      .1       0  5302.2     .05       0
Bank Sta=4997,5003
XS Rating Curve= 0 ,0
Exp/Cntr=0.3,0.1

Type RM Length L Ch R = 1 ,12160   ,724,724,724
BEGIN DESCRIPTION:
UNT0035 IN CHRS 12.0
END DESCRIPTION:
XS GIS Cut Line= 3
      3427375.94      10570388.9      3426542.59     10569611.97
      3425700.54     10569664.06
#Sta/Elev= 30
  3621.6  529.73  3785.1   527.4  3820.3  526.02  4096.4  521.19    4160  520.23
  4181.4  520.86  4216.5  519.99  4223.9  518.95  4252.2  519.07  4306.2  517.51
  4369.8  516.26  4683.6  514.73  4744.8  513.74  4811.5  514.66  4911.7  513.47
  4971.8  514.18  4991.9  512.56  4997.7  510.85  5004.1  510.44  5008.9  509.63
  5011.7  509.13  5014.9  509.63  5021.9  511.63  5031.9  512.27  5092.1  513.51
  5158.9  516.46  5271.7  518.73  5516.8  525.33  5569.8  527.09  5604.6  527.57
#Mann= 10 ,-1 , 0
  3621.6     .05       0  4306.2     .16       0  4369.8     .05       0
  4744.8     .16       0  5004.1      .1       0  5008.9     .07       0
  5014.9      .1       0  5271.7     .05       0  5516.8      .1       0
  5569.8     .05       0
Bank Sta=5008.9,5014.9
XS Rating Curve= 0 ,0
Exp/Cntr=0.3,0.1

Type RM Length L Ch R = 1 ,11436   ,928,928,928
BEGIN DESCRIPTION:
UNT0035 IN CHRS 10.0
END DESCRIPTION:
XS GIS Cut Line= 3
      3428061.66     10570262.99      3426993.98     10569329.85
      3425839.42     10569104.15
#Sta/Elev= 30
    3109  534.67  3236.9  533.11  3520.2  526.48    3563  526.51  3669.3  524.15
  4307.1  515.39  4538.9  514.25  4671.5  510.69  4686.1  511.45  4712.3   511.3
  4742.9  513.15  4755.2  512.84  4763.2  510.92  4773.4  510.13  4806.7  508.49
  4853.2  510.16    4967  510.26  4977.2  509.99  4994.6  507.32  4997.3  506.82
  5000.6  507.32    5018  512.12  5028.2  512.86  5111.3  514.59  5150.4  515.18
  5167.5  516.58  5201.4  515.89  5386.1  521.05  5619.1  528.56  5703.4  529.11
#Mann= 7 ,-1 , 0
    3109     .16       0  3236.9     .05       0  4686.1     .16       0
  4994.6     .07       0  5000.6     .16       0  5111.3      .1       0
  5386.1     .05       0
Bank Sta=4994.6,5000.6
XS Rating Curve= 0 ,0
Exp/Cntr=0.3,0.1

Type RM Length L Ch R = 1 ,11338   ,93,93,93
BEGIN DESCRIPTION:
UNT0035 IN CHRS 12.2
END DESCRIPTION:
XS GIS Cut Line= 5
      3427261.96     10570120.23       3426685.6     10569366.79
       3426584.9     10569137.62      3426411.29     10569109.84
      3425995.86     10569179.08
#Sta/Elev= 30
  3860.4  523.73  4309.2  516.22  4450.2  515.87  4558.5  515.65  4579.3  514.79
  4608.4  515.52  4629.2  514.59  4729.8  514.02  4765.5  513.01  4807.8  509.78
  4853.3  510.44  4869.2  512.22  4882.7  512.17  4912.9  510.23  4989.4  508.95
    4997   506.7  4999.8   506.2    5003   506.7  5011.2  509.46  5028.3  512.18
  5200.3  513.74  5244.5  514.05  5254.6  514.93  5325.6  516.06  5345.8  517.65
    5356  517.14  5426.9  518.94  5437.1  520.08  5498.7  521.09  5656.3  526.25
#Mann= 9 ,-1 , 0
  3860.4     .05       0  4450.2      .1       0  4729.8     .16       0
  4765.5      .1       0  4853.3     .16       0    4997     .07       0
    5003     .16       0  5200.3      .1       0  5498.7     .05       0
Bank Sta=4997,5003
XS Rating Curve= 0 ,0
Exp/Cntr=0.3,0.1

Type RM Length L Ch R = 1 ,11245   ,115,115,115
BEGIN DESCRIPTION:
UNT0035 IN CHRS 12.1
END DESCRIPTION:
XS GIS Cut Line= 5
      3427327.95     10570078.58      3426741.15     10569314.71
      3426675.18     10569089.01      3426452.96     10568998.73
      3425977.25     10569123.74
#Sta/Elev= 30
  3887.3  523.57  4366.8  516.09  4646.9  514.57  4688.6  513.65  4694.9  514.33
  4709.4  513.82  4736.4  514.61  4854.7  511.78    4862  511.03  4867.2  511.51
    4885     509  4900.6  508.49  4978.8   508.9    4997  507.36  4999.8  506.86
    5003  507.36  5051.7   511.5  5062.1  511.73  5170.8  512.19  5194.9  513.09
  5253.8  512.53  5304.5  513.51  5440.3  516.23  5460.8   517.5  5530.9     519
  5636.9  521.75  5657.3  523.21  5712.5  524.02  5747.7   525.9  5817.4  526.85
#Mann= 7 ,-1 , 0
  3887.3     .05       0  4646.9      .1       0  4736.4     .16       0
    4997     .07       0    5003     .16       0  5304.5      .1       0
  5530.9     .05       0
Bank Sta=4997,5003
XS Rating Curve= 0 ,0
Exp/Cntr=0.3,0.1

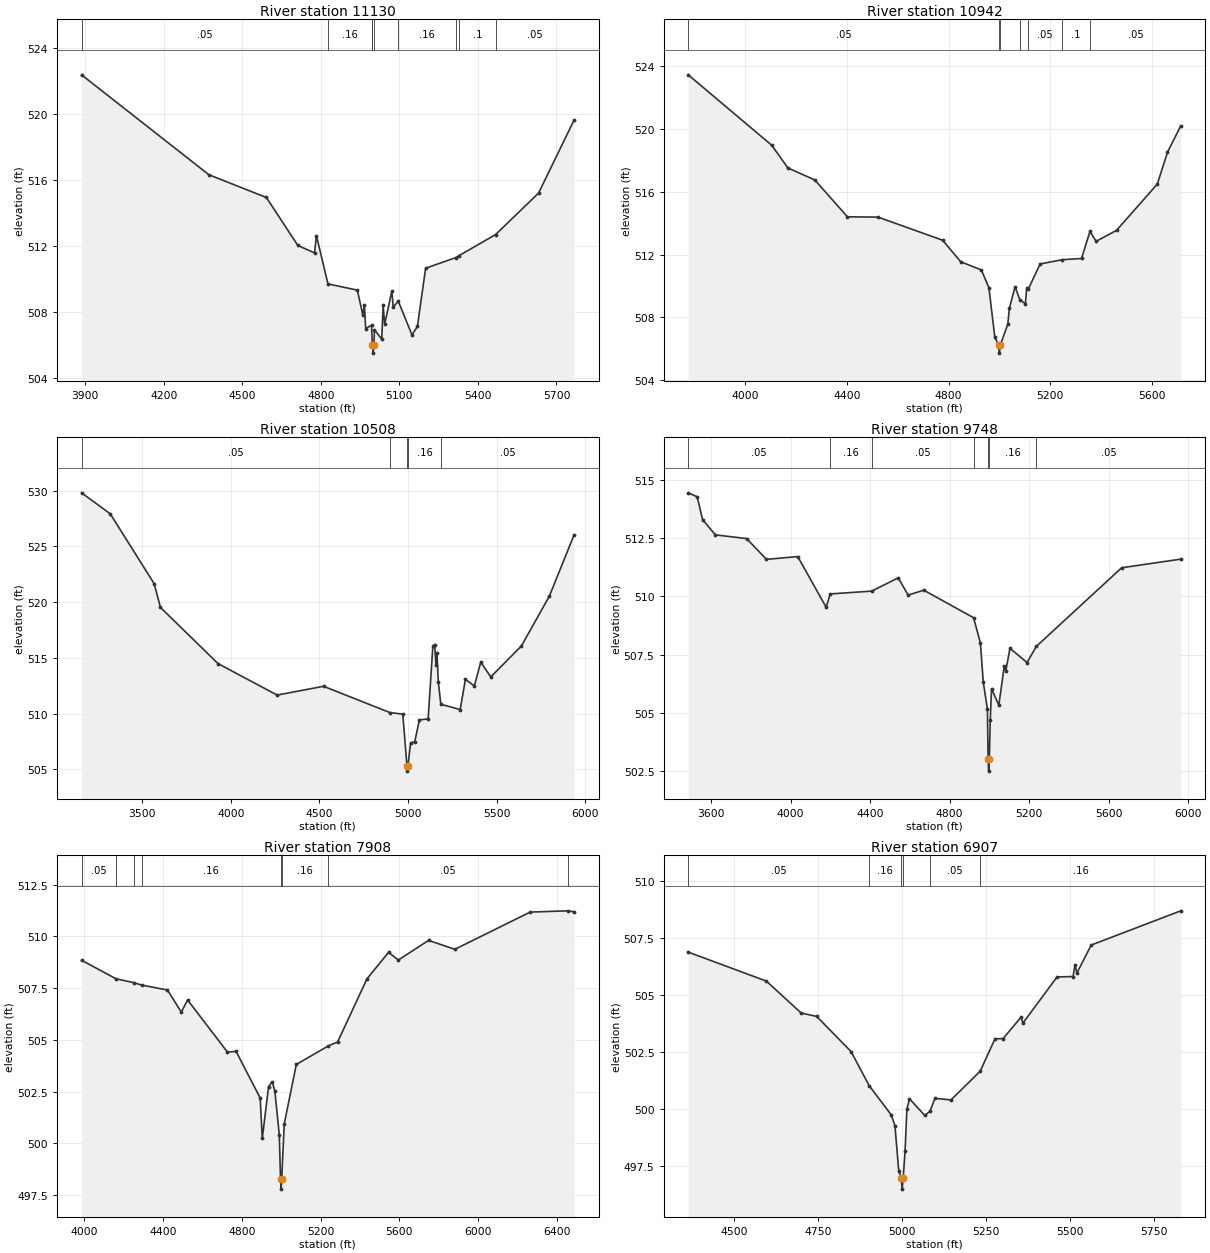
Type RM Length L Ch R = 1 ,11130   ,188,188,188
BEGIN DESCRIPTION:
UNT0035 IN CHRS 12.3
END DESCRIPTION:
XS GIS Cut Line= 5
      3427473.82      10569957.1      3426817.54     10569238.32
      3426716.85     10568898.04      3426619.62      10568727.9
      3426268.92     10568793.87
#Sta/Elev= 30
  3886.2  522.36  4372.5   516.3  4592.1  514.92  4712.3  512.01  4775.9  511.56
  4783.3   512.6  4827.2  509.68  4939.5   509.3  4960.3  507.79  4966.2  508.41
  4971.4  506.97  4993.6  507.17    4997  505.98  4999.8  505.48    5003  505.98
  5004.6   506.9  5032.7  506.33  5037.9  508.37  5043.8  507.23  5071.2  509.25
  5076.4  508.28  5095.9  508.63  5148.1  506.58  5168.9   507.1  5200.2  510.63
  5314.7  511.27  5328.8   511.4  5467.3  512.67  5631.7  515.19  5767.2  519.62
#Mann= 9 ,-1 , 0
  3886.2     .05       0  4827.2     .16       0  4993.6     .05       0
    4997     .04       0    5003     .05       0  5095.9     .16       0
  5314.7     .05       0  5328.8      .1       0  5467.3     .05       0
Bank Sta=4997,5003
XS Rating Curve= 0 ,0
Exp/Cntr=0.3,0.1

Type RM Length L Ch R = 1 ,10942   ,434,434,434
BEGIN DESCRIPTION:
UNT0035 IN CHRS 12.4
END DESCRIPTION:
XS GIS Cut Line= 5
      3427574.51     10569852.93       3426834.9     10569012.62
       3426709.9     10568741.79       3426584.9     10568668.87
      3426209.96     10568696.65
#Sta/Elev= 30
  3775.2  523.43  4103.8  518.95  4167.3  517.51  4273.6  516.74  4401.7   514.4
  4522.2  514.38  4776.5  512.91  4847.6  511.54  4928.8  511.02  4958.6  509.88
  4981.6  506.75    4997  506.23  4999.8  505.73    5003  506.23    5033  507.58
  5038.9  508.58  5061.4  509.95  5080.1  509.13  5101.8  508.87  5107.3  509.85
  5113.4   509.8    5160   511.4  5246.7  511.67  5322.9  511.75  5356.2  513.47
  5380.5  512.84  5460.8  513.54  5621.2  516.48  5661.3  518.51  5713.6  520.19
#Mann= 7 ,-1 , 0
  3775.2     .05       0    4997     .04       0    5003     .05       0
  5080.1     .16       0  5113.4     .05       0  5246.7      .1       0
  5356.2     .05       0
Bank Sta=4997,5003
XS Rating Curve= 0 ,0
Exp/Cntr=0.3,0.1

Type RM Length L Ch R = 1 ,10508   ,760,760,760
BEGIN DESCRIPTION:
UNT0035 IN CHRS 8.0
END DESCRIPTION:
XS GIS Cut Line= 4
      3428291.76     10569690.13      3427054.74     10568565.97
       3426651.1     10568479.16      3426083.81     10568877.56
#Sta/Elev= 30
  3158.7  529.81  3320.4  527.93  3567.9  521.67  3603.7  519.53  3928.7  514.49
  4261.8  511.67  4523.4  512.46  4897.9   510.1  4970.3  509.96  4993.6  505.35
  4996.3  504.85  4999.6  505.35  5014.6   507.4  5037.5  507.47  5063.9  509.45
  5113.3  509.53  5139.8  516.07    5150   516.2  5157.5  514.35  5162.6  515.46
  5170.5  512.87  5184.8  510.85  5293.9  510.37  5323.5  513.08    5374  512.49
  5409.8  514.62  5466.4   513.3  5638.9  516.07  5796.7  520.54  5936.3  526.04
#Mann= 5 ,-1 , 0
  3158.7     .05       0  4897.9     .16       0  4993.6     .07       0
  4999.6     .16       0  5184.8     .05       0
Bank Sta=4993.6,4999.6
XS Rating Curve= 0 ,0
Exp/Cntr=0.3,0.1

Type RM Length L Ch R = 1 ,9748    ,1840,1840,1840
BEGIN DESCRIPTION:
UNT0035 IN CHRS 7.0
END DESCRIPTION:
XS GIS Cut Line= 3
      3428317.79     10569078.14      3427306.48     10568283.85
      3426547.02     10567368.16
#Sta/Elev= 30
    3486  514.43    3531  514.26  3558.2  513.28  3622.3  512.63  3779.6  512.47
    3879  511.58  4036.3   511.7  4179.1  509.53  4199.9   510.1  4408.4  510.22
  4541.5  510.79  4591.2  510.05  4669.9  510.26  4920.1  509.08  4954.6  507.99
  4968.9  506.32  4989.7  505.16  4993.2  503.01    4996  502.51  4999.2  503.01
  5004.1  504.71  5010.5  506.04    5047  505.33  5074.4  507.01  5082.2  506.81
    5103  507.77    5189  507.16  5235.1  507.85  5664.3  511.22  5961.6  511.59
#Mann= 7 ,-1 , 0
    3486     .05       0  4199.9     .16       0  4408.4     .05       0
  4920.1     .16       0  4993.2     .07       0  4999.2     .16       0
  5235.1     .05       0
Bank Sta=4993.2,4999.2
XS Rating Curve= 0 ,0
Exp/Cntr=0.3,0.1

Type RM Length L Ch R = 1 ,7908    ,1001,1001,1001
BEGIN DESCRIPTION:
UNT0035 IN CHRS 6.0
END DESCRIPTION:
XS GIS Cut Line= 3
       3428656.3     10568387.99      3428387.21     10567650.17
      3426772.61     10567064.22
#Sta/Elev= 30
  3985.1  508.85  4161.1  507.95  4249.4  507.77  4289.9  507.65  4421.7  507.41
  4492.1  506.34  4524.1  506.93  4726.3  504.41  4770.5  504.44  4892.8  502.19
  4903.6  500.23  4935.5  502.74  4954.1  502.97  4967.4  502.53    4990  500.41
  4996.3  498.28    4999  497.78  5002.3  498.28  5015.3  500.94  5076.5  503.81
  5239.9  504.71  5286.5   504.9  5435.5  507.95  5545.1  509.23    5595  508.86
  5748.7  509.81  5882.3  509.38  6265.2  511.18  6456.9  511.24  6488.1  511.19
#Mann= 8 ,-1 , 0
  3985.1     .05       0  4161.1     .16       0  4249.4     .05       0
  4289.9     .16       0  4996.3     .07       0  5002.3     .16       0
  5239.9     .05       0  6456.9      .1       0
Bank Sta=4996.3,5002.3
XS Rating Curve= 0 ,0
Exp/Cntr=0.3,0.1

Type RM Length L Ch R = 1 ,6907    ,1199,1199,1199
BEGIN DESCRIPTION:
UNT0035 IN CHRS 4.0
END DESCRIPTION:
XS GIS Cut Line= 3
      3429072.97     10567437.49      3428890.68     10567033.85
      3427945.79     10566648.09
#Sta/Elev= 30
  4364.9  506.87    4597   505.6  4700.5   504.2  4746.7  504.05  4848.7  502.51
  4902.3  501.02  4968.3  499.73  4979.1  499.26  4990.4  497.28  4997.7  496.98
  5000.4  496.48  5003.7  496.98  5009.1  498.13  5014.5  499.98  5022.3  500.44
  5067.9  499.71  5083.5   499.9  5097.9  500.46  5145.4  500.39  5232.4  501.65
  5276.4  503.07  5300.4  503.08  5353.9  504.02  5359.3  503.76  5460.8  505.78
  5508.3   505.8  5514.2  506.32  5519.6  505.95  5562.3  507.18  5828.4  508.68
#Mann= 6 ,-1 , 0
  4364.9     .05       0  4902.3     .16       0  4997.7     .07       0
  5003.7     .16       0  5083.5     .05       0  5232.4     .16       0
Bank Sta=4997.7,5003.7
XS Rating Curve= 0 ,0
Exp/Cntr=0.3,0.1

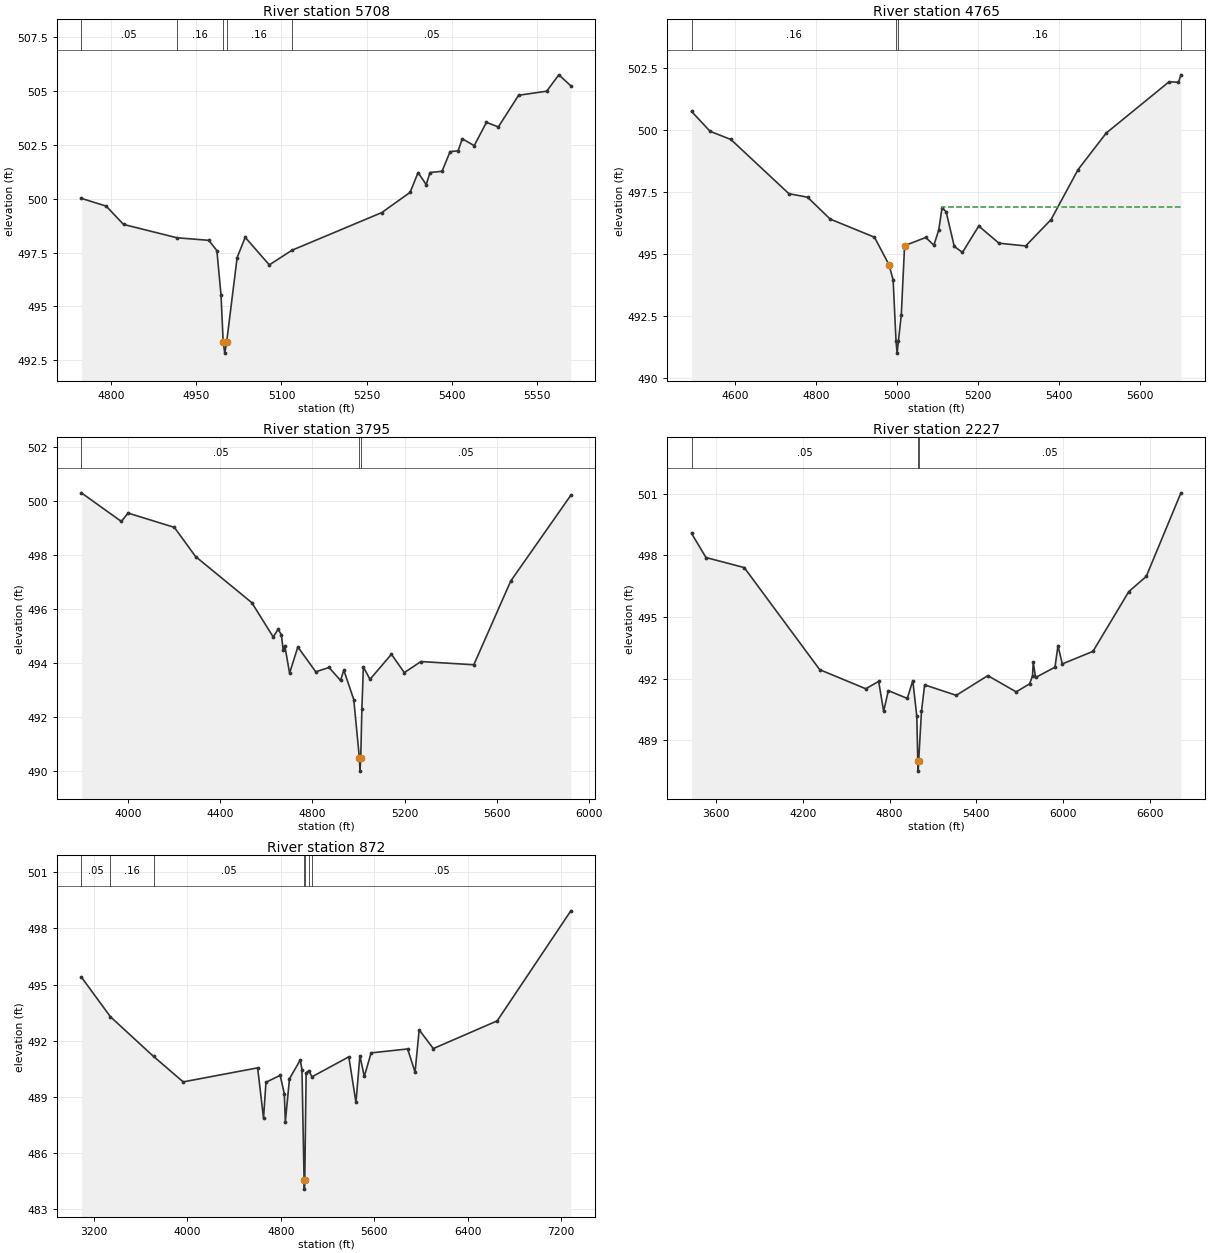
Type RM Length L Ch R = 1 ,5708    ,943,943,943
BEGIN DESCRIPTION:
UNT0035 IN CHRS 3.0
END DESCRIPTION:
XS GIS Cut Line= 3
      3429602.49     10566764.73      3429628.53      10566608.5
      3429147.04     10566096.65
#Sta/Elev= 30
    4748  500.02  4791.7  499.66  4822.1  498.81  4916.1  498.19  4972.2  498.07
  4986.4  497.59  4993.7  495.52  4997.5  493.33  5000.3  492.83  5003.5  493.33
    5022  497.27  5036.2  498.21  5078.6  496.93  5118.5  497.61  5276.5  499.36
  5326.3   500.3  5340.4  501.22  5354.6  500.66  5361.4  501.22  5382.6  501.28
  5396.6  502.19  5410.8  502.23  5418.1  502.79  5439.1  502.47  5460.6  503.55
  5481.6  503.34  5517.2  504.81  5566.6     505    5588  505.76  5609.1  505.25
#Mann= 5 ,-1 , 0
    4748     .05       0  4916.1     .16       0  4997.5     .07       0
  5003.5     .16       0  5118.5     .05       0
Bank Sta=4997.5,5003.5
XS Rating Curve= 0 ,0
Exp/Cntr=0.3,0.1

Type RM Length L Ch R = 1 ,4765    ,970,970,970
BEGIN DESCRIPTION:
UNT0035 IN CHRS 2.1
END DESCRIPTION:
XS GIS Cut Line= 4
      3430266.53      10566547.7      3430123.32     10566235.24
      3430179.74     10565796.87      3429786.41     10565636.94
#Sta/Elev= 30
  4491.5  500.74  4537.4  499.94  4588.9  499.61  4732.4  497.43  4778.4  497.29
  4834.4  496.41    4944  495.68    4980  494.57  4990.1  493.96  4997.2  491.52
  4999.9  491.02  5003.2  491.52  5010.2  492.54  5018.4  495.34  5070.7  495.67
  5090.9  495.36    5103  495.98  5111.1  496.87  5121.2   496.7  5141.3  495.31
  5161.5  495.07  5201.8  496.13  5251.9  495.44  5317.8  495.33  5380.6  496.39
  5447.4   498.4  5517.1  499.87  5672.4  501.93  5695.7  501.91  5701.8  502.21
#Mann= 4 ,-1 , 0
  4491.5     .16       0  4997.2    .012       0  5003.2     .16       0
  5701.8     .16       0
#XS Ineff= 2 , 0
       0                  5110.5       0  496.88
Permanent Ineff=
       F       T
Bank Sta=4980,5018.4
XS Rating Curve= 0 ,0
Exp/Cntr=0.3,0.1

Type RM Length L Ch R = 1 ,3795    ,1568,1568,1568
BEGIN DESCRIPTION:
UNT0035 IN CHRS 1.1
END DESCRIPTION:
XS GIS Cut Line= 4
      3431659.79     10566356.78      3430939.29     10565831.59
      3430461.86     10565449.65      3429841.17     10565449.65
#Sta/Elev= 30
  3797.6   500.3  3970.9  499.24  4000.2  499.55  4201.1  499.02    4293  497.94
  4537.2  496.23  4629.9  494.96  4650.7  495.24  4665.4  495.05  4673.3  494.46
  4680.1  494.64    4701  493.62  4736.8  494.59  4814.6  493.67  4872.2  493.83
  4921.9  493.35  4936.3  493.73  4979.5  492.64  5003.7  490.49  5006.5  489.99
  5009.7  490.49  5014.7  492.29  5021.1  493.85  5049.9  493.39  5142.8  494.32
  5198.8  493.64  5270.8  494.05  5500.4  493.93  5660.4  497.03  5921.3  500.21
#Mann= 3 ,-1 , 0
  3797.6     .05       0  5003.7    .035       0  5009.7     .05       0
Bank Sta=5003.7,5009.7
XS Rating Curve= 0 ,0
Exp/Cntr=0.3,0.1

Type RM Length L Ch R = 1 ,2227    ,1355,1355,1355
BEGIN DESCRIPTION:
UNT0035 IN CHRS 2.0
END DESCRIPTION:
XS GIS Cut Line= 5
      3432078.83     10566227.11      3431551.06     10565070.88
      3431040.64      10564793.1      3430196.89     10565004.91
      3429717.74     10565456.29
#Sta/Elev= 30
  3432.5  499.08  3532.5   497.9  3796.8  497.41  4317.9  492.44    4636  491.51
  4725.1  491.87  4759.6  490.41  4791.9  491.42  4922.9  491.04  4960.9  491.91
  4988.5  490.17  4995.3     488  4998.1   487.5  5001.3     488  5020.8  490.41
  5042.6   491.7  5261.1  491.19    5479  492.15  5674.9  491.36  5767.7  491.75
  5787.6  492.14  5792.7  492.79  5808.9  492.06  5942.9  492.56  5963.6  493.61
  5993.3  492.72    6205  493.33  6452.6  496.24  6573.2  496.98  6812.8  501.05
#Mann= 3 ,-1 , 0
  3432.5     .05       0  4995.3    .035       0  5001.3     .05       0
Bank Sta=4995.3,5001.3
XS Rating Curve= 0 ,0
Exp/Cntr=0.3,0.1

Type RM Length L Ch R = 1 ,872     ,0,0,0
BEGIN DESCRIPTION:
UNT0035 IN CHRS 1.0
END DESCRIPTION:
XS GIS Cut Line= 4
      3432655.24     10565744.51      3431512.86     10564147.27
      3431044.11     10564237.55      3429696.98     10565355.53
#Sta/Elev= 30
  3092.5   495.4  3341.3  493.28  3710.6  491.16  3964.4   489.8    4602  490.55
  4652.4  487.86  4673.3  489.78  4794.9  490.15  4830.6  489.16  4839.2  487.67
  4874.8  489.97    4967  490.97  4981.7  490.46  4999.6  484.57  5002.3  484.07
  5005.6  484.57  5017.3  490.28  5040.6   490.4  5066.8  490.07  5382.9  491.14
    5444   488.7  5477.8   491.2  5515.3  490.09  5573.9  491.35  5886.4  491.56
  5950.2  490.32  5985.4  492.58  6106.5  491.58  6653.4  493.06  7284.2  498.94
#Mann= 7 ,-1 , 0
  3092.5     .05       0  3341.3     .16       0  3710.6     .05       0
  4999.6    .035       0  5005.6     .05       0  5040.6     .16       0
  5066.8     .05       0
Bank Sta=4999.6,5005.6
XS Rating Curve= 0 ,0
Exp/Cntr=0.3,0.1

Chan Stop Cuts=-1
Use User Specified Reach Order=0
Composite Channel Slope=5