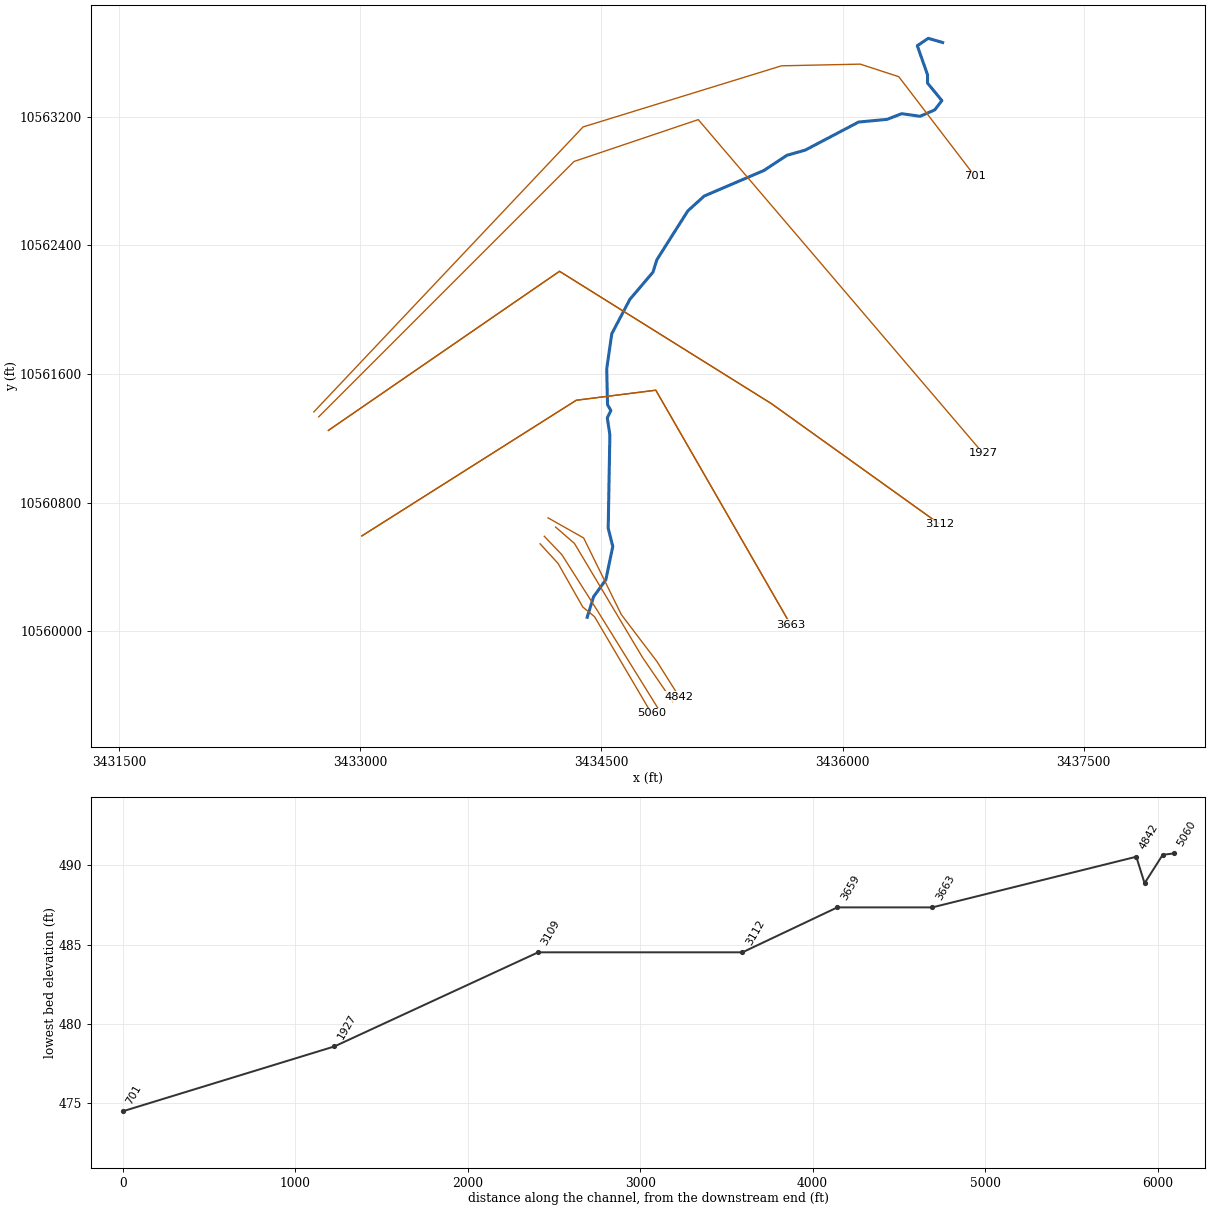
--- UNT0036 IN CHRS.prj (project) ---

Proj Title=UNT0036 IN CHRS Base Level Engineering
Current Plan=p01
Default Exp/Contr=0.3,0.1
English Units
Geom File=g01
Flow File=f01
Plan File=p01
Y Axis Title=Elevation
X Axis Title(PF)=Main Channel Distance
X Axis Title(XS)=Station
BEGIN DESCRIPTION:
UNT0036 IN CHRS
END DESCRIPTION:
DSS Export Rating Curves= 0
DSS Export Rating Curve Sorted= 0
DSS Export Volume Flow Curves= 0
DXF OffsetX= 0
DXF OffsetY= 0
DXF ScaleX= 1
DXF ScaleY= 10

--- UNT0036 IN CHRS.p01 (plan) ---

Plan Title=Multiple Run
Short Identifier=Multiple
Geom File=g01
Flow File=f01
Subcritical Flow
K Sum by GR= 0
Std Step Tol= 0.01
Critical Tol= 0.01
Num of Std Step Trials= 20
Max Error Tol= 0.3
Flow Tol Ratio= 0.001
Split Flow NTrial= 30
Split Flow Tol= 0.02
Split Flow Ratio= 0.02
Log Output Level= 0
Friction Slope Method= 1
Unsteady Friction Slope Method= 2
Unsteady Bridges Friction Slope Method= 1
Parabolic Critical Depth
Global Vel Dist=  1 , 1 , 1
Global Log Level= 0
CheckData=True
Encroach Param= -1, 0, 0, 0
BEGIN DESCRIPTION:
Multiple Run
END DESCRIPTION:

--- UNT0036 IN CHRS.f01 (steady flow) ---

Flow Title=Multiple
Program Version=4.10
Number of Profiles= 7
Profile Names=10-year,25-year,50-year,1pct_min,100-year,1pct_plu,500-year
River Rch & RM=UNT0036 IN CHRS,Reach-1         ,5060
     376     467     532     442     597     808     751
River Rch & RM=UNT0036 IN CHRS,Reach-1         ,4995
     376     467     532     442     597     808     751
Boundary for River Rch & Prof#=UNT0036 IN CHRS,Reach-1         , 1
Up Type= 0
Dn Type= 3
Dn Slope=0.005
Boundary for River Rch & Prof#=UNT0036 IN CHRS,Reach-1         , 2
Up Type= 0
Dn Type= 3
Dn Slope=0.005
Boundary for River Rch & Prof#=UNT0036 IN CHRS,Reach-1         , 3
Up Type= 0
Dn Type= 3
Dn Slope=0.005
Boundary for River Rch & Prof#=UNT0036 IN CHRS,Reach-1         , 4
Up Type= 0
Dn Type= 3
Dn Slope=0.005
Boundary for River Rch & Prof#=UNT0036 IN CHRS,Reach-1         , 5
Up Type= 0
Dn Type= 3
Dn Slope=0.005
Boundary for River Rch & Prof#=UNT0036 IN CHRS,Reach-1         , 6
Up Type= 0
Dn Type= 3
Dn Slope=0.005
Boundary for River Rch & Prof#=UNT0036 IN CHRS,Reach-1         , 7
Up Type= 0
Dn Type= 3
Dn Slope=0.005
DSS Import GetInterval= 0
DSS Import GetPeak= 0
DSS Import FillOption= 0

--- UNT0036 IN CHRS.g01 (geometry) ---

Geom Title=Existing Conditions
Program Version=4.10

River Reach=UNT0036 IN CHRS ,Reach-1
Reach XY= 30
       3434411.1     10560086.59      3434451.25     10560214.63
       3434527.2     10560319.88      3434570.39     10560527.23
      3434541.92      10560640.2      3434552.23     10561221.72
      3434536.19     10561326.78      3434558.52     10561372.75
       3434537.7     10561408.37      3434532.56     10561632.06
       3434564.4     10561850.69      3434676.82      10562064.4
      3434820.08     10562232.53      3434844.67     10562310.56
      3435037.16     10562614.33      3435139.31     10562706.87
      3435510.47     10562865.58      3435652.92     10562959.78
      3435766.99     10562992.07      3436099.34     10563166.87
      3436276.27      10563183.6      3436367.55     10563219.16
       3436481.6     10563202.58      3436572.96     10563242.56
      3436617.46     10563300.52       3436528.2     10563409.04
      3436528.33     10563460.45       3436464.4     10563641.81
      3436532.58      10563687.6      3436622.11     10563661.64

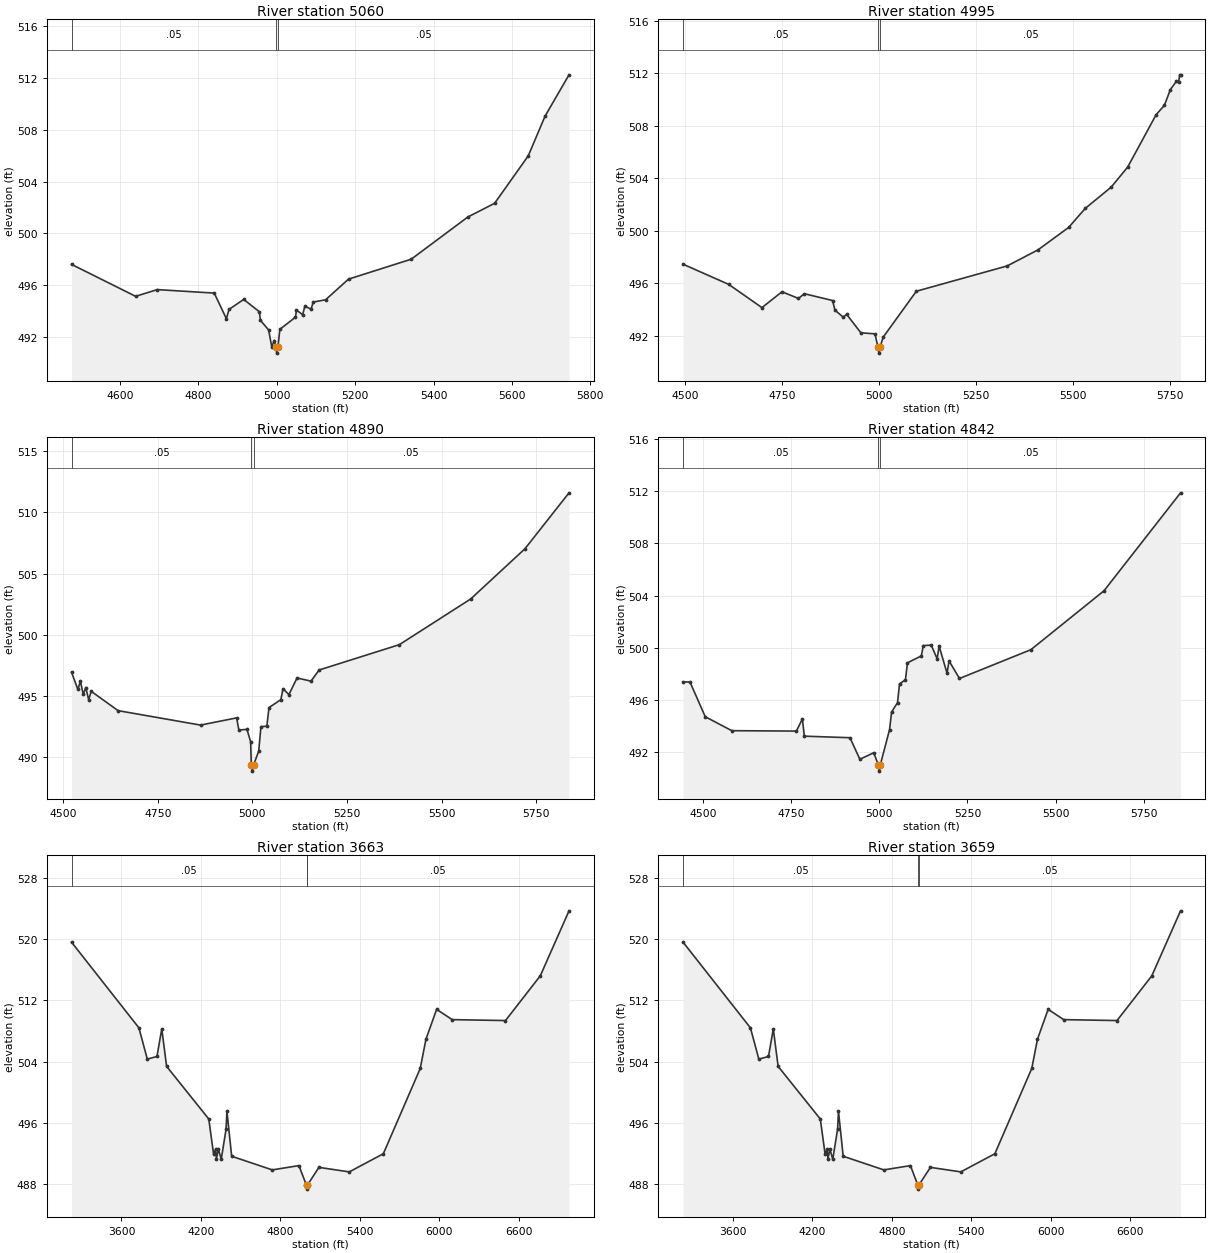
Type RM Length L Ch R = 1 ,5060    ,65,65,65
BEGIN DESCRIPTION:
UNT0036 IN CHRS 5.3
END DESCRIPTION:
XS GIS Cut Line= 5
      3434118.26      10560543.5      3434230.21     10560421.13
      3434383.86      10560150.3      3434456.78      10560090.4
      3434810.95     10559488.82
#Sta/Elev= 30
  4476.1  497.61  4639.7  495.14  4694.8  495.66  4840.4  495.39  4871.3  493.41
    4878  494.13  4915.5   494.9  4955.4  493.95  4958.3  493.28  4979.1  492.54
    4987  491.25  4993.5  491.72    4997  491.25  4999.8  490.75    5003  491.25
  5007.8  492.59  5047.7  493.53  5050.2  494.08  5065.9  493.72  5071.7  494.38
  5087.3  494.15  5093.1   494.7  5124.4  494.87    5183  496.47  5343.1  498.01
  5487.5  501.27  5555.9  502.33  5641.8     506  5684.7  509.07  5745.8  512.26
#Mann= 3 ,-1 , 0
  4476.1     .05       0    4997     .03       0    5003     .05       0
Bank Sta=4997,5003
XS Rating Curve= 0 ,0
Exp/Cntr=0.3,0.1

Type RM Length L Ch R = 1 ,4995    ,105,105,105
BEGIN DESCRIPTION:
UNT0036 IN CHRS 5.0
END DESCRIPTION:
XS GIS Cut Line= 4
       3434144.3     10560590.37      3434253.65     10560475.82
      3434480.21     10560119.05      3434850.01     10559522.69
#Sta/Elev= 30
  4494.7  497.44  4612.5   495.9  4698.1  494.13  4749.8  495.34  4792.2  494.83
  4807.4  495.19  4880.3  494.67  4886.2  493.94  4907.4  493.41  4916.7  493.61
  4953.1  492.21  4989.5  492.13    4997  491.16  4999.8  490.66    5003  491.16
  5010.7  491.88  5096.2  495.38  5330.5  497.31  5409.7  498.53  5488.8  500.24
  5531.5  501.69  5598.7  503.32  5641.2  504.85  5714.4  508.84  5735.7  509.55
  5751.1  510.75  5766.4  511.38  5772.3   511.3  5775.1  511.88  5777.4  511.88
#Mann= 3 ,-1 , 0
  4494.7     .05       0    4997     .03       0    5003     .05       0
Bank Sta=4997,5003
XS Rating Curve= 0 ,0
Exp/Cntr=0.3,0.1

Type RM Length L Ch R = 1 ,4890    ,48,48,48
BEGIN DESCRIPTION:
UNT0036 IN CHRS 5.1
END DESCRIPTION:
XS GIS Cut Line= 4
      3434214.55     10560647.72      3434331.78     10560546.13
      3434756.26     10559835.19      3434943.76     10559561.74
#Sta/Elev= 30
    4522  496.95  4538.8  495.54  4545.4  496.22    4553  495.13  4559.6   495.7
  4567.3   494.7  4573.9  495.39  4645.1  493.81    4863  492.63  4958.3  493.22
  4964.2  492.23  4985.6  492.28  4995.3  491.27    4997  489.37  4999.8  488.87
    5003  489.37  5016.7  490.51  5022.5   492.5  5038.1  492.54  5043.9  494.06
  5075.1  494.71  5080.9   495.6  5096.5  495.12  5117.9  496.48  5154.9  496.22
  5176.3  497.13  5388.4   499.2  5576.8  502.93  5720.2  507.03  5836.7   511.6
#Mann= 3 ,-1 , 0
    4522     .05       0    4997     .03       0    5003     .05       0
Bank Sta=4997,5003
XS Rating Curve= 0 ,0
Exp/Cntr=0.3,0.1

Type RM Length L Ch R = 1 ,4842    ,1183,1183,1183
BEGIN DESCRIPTION:
UNT0036 IN CHRS 5.2
END DESCRIPTION:
XS GIS Cut Line= 6
      3434167.71     10560704.99      3434389.07     10560579.98
      3434540.11     10560272.69      3434623.44     10560103.42
       3434844.8     10559811.75      3434982.82     10559593.01
#Sta/Elev= 30
  4443.8  497.38  4463.4  497.37  4506.7  494.71  4581.9  493.64  4765.1  493.61
    4782  494.54  4787.6  493.22  4916.9   493.1  4944.9  491.45  4984.3  491.95
    4997  491.04  4999.8  490.54    5003  491.04  5029.2  493.73  5034.8  495.07
  5051.7  495.79  5057.3  497.22  5074.2  497.55  5079.8  498.84  5119.1  499.37
  5124.7  500.16  5147.2   500.2    5164  499.15  5169.6  500.12  5192.1  498.04
  5197.7  498.99  5227.3  497.64  5429.8  499.85  5636.9  504.36  5853.9  511.87
#Mann= 3 ,-1 , 0
  4443.8     .05       0    4997     .03       0    5003     .05       0
Bank Sta=4997,5003
XS Rating Curve= 0 ,0
Exp/Cntr=0.3,0.1

Type RM Length L Ch R = 1 ,3663    ,551,551,551
BEGIN DESCRIPTION:
UNT0036 IN CHRS 4.0
END DESCRIPTION:
XS GIS Cut Line= 4
      3433009.88     10560592.74       3434343.2     10561436.48
      3434837.99     10561498.98      3435676.53     10560040.65
#Sta/Elev= 30
  3222.7  519.58  3731.6   508.4  3795.2  504.32  3868.1  504.66  3904.5  508.26
    3941  503.37  4259.7   496.5  4296.1   491.9  4311.4  492.59  4317.3  491.34
  4332.6  492.55  4353.8  491.25  4390.2  495.16  4396.9  497.51  4432.6  491.64
  4739.5  489.86  4940.6  490.42    4998  487.85  5000.8  487.35    5004  487.85
  5091.8  490.19  5321.3   489.6  5578.6  491.97  5857.4   503.1  5900.6  506.92
  5981.1  510.81  6098.9  509.47  6501.4  509.35  6764.5  515.19  6981.5  523.67
#Mann= 3 ,-1 , 0
  3222.7     .05       0    4998    .035       0    5004     .05       0
Bank Sta=4998,5004
XS Rating Curve= 0 ,0
Exp/Cntr=0.3,0.1

Type RM Length L Ch R = 1 ,3659    ,550,550,550
BEGIN DESCRIPTION:
UNT0036 IN CHRS 4.0
END DESCRIPTION:
XS GIS Cut Line= 4
      3433009.88     10560592.74       3434343.2     10561436.48
      3434837.99     10561498.98      3435676.53     10560040.65
#Sta/Elev= 30
  3222.7  519.58  3731.6   508.4  3795.2  504.32  3868.1  504.66  3904.5  508.26
    3941  503.37  4259.7   496.5  4296.1   491.9  4311.4  492.59  4317.3  491.34
  4332.6  492.55  4353.8  491.25  4390.2  495.16  4396.9  497.51  4432.6  491.64
  4739.5  489.86  4940.6  490.42    4997  487.85  4999.8  487.35    5003  487.85
  5091.8  490.19  5321.3   489.6  5578.6  491.97  5857.4   503.1  5900.6  506.92
  5981.1  510.81  6098.9  509.47  6501.4  509.35  6764.5  515.19  6981.5  523.67
#Mann= 3 ,-1 , 0
  3222.7     .05       0    4997    .035       0    5003     .05       0
Bank Sta=4997,5003
XS Rating Curve= 0 ,0
Exp/Cntr=0.3,0.1

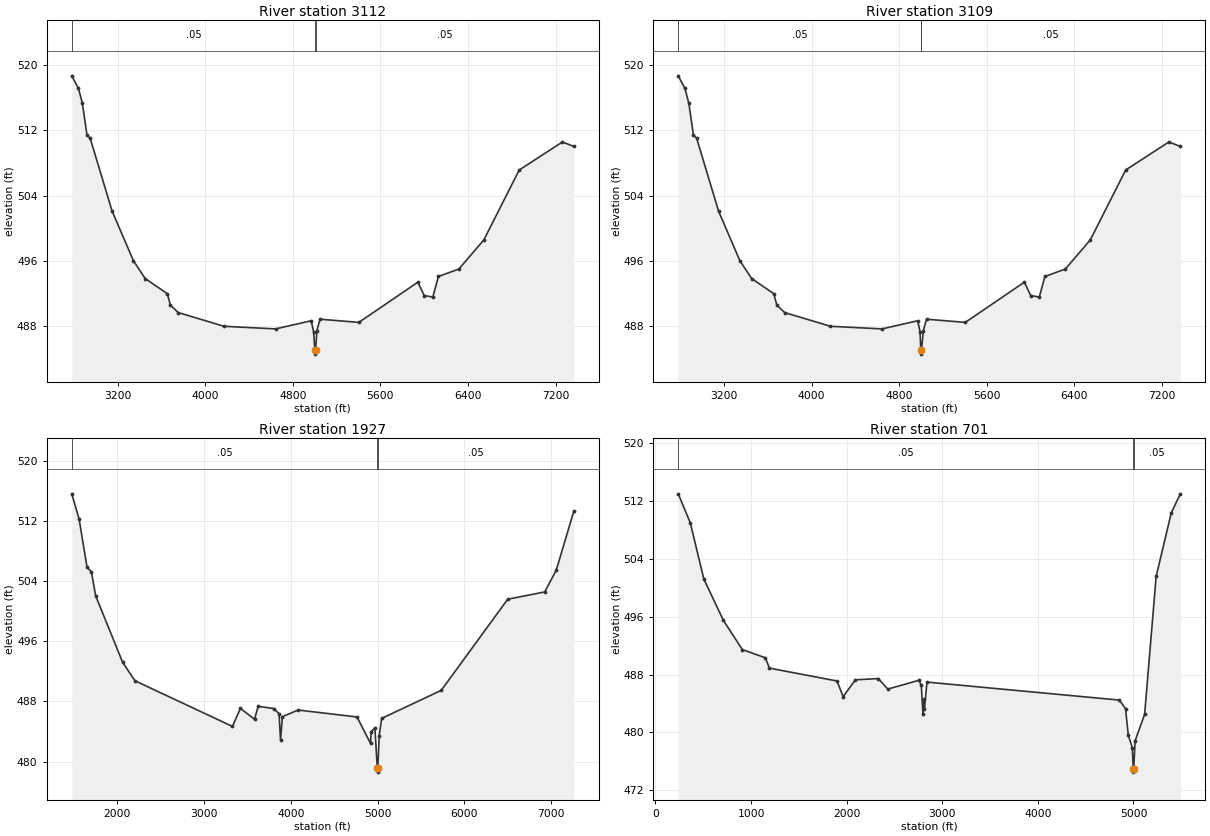
Type RM Length L Ch R = 1 ,3112    ,1185,1185,1185
BEGIN DESCRIPTION:
UNT0036 IN CHRS 3.0
END DESCRIPTION:
XS GIS Cut Line= 4
      3432801.54     10561248.99      3434239.03     10562238.56
      3435556.74     10561415.65      3436602.93     10560666.14
#Sta/Elev= 30
  2781.3  518.71  2842.2  517.17    2878  515.34  2919.9  511.46  2949.7  511.03
  3149.9  502.08    3344  496.01  3451.5  493.81  3654.5  491.94  3681.5  490.55
  3753.2  489.63  4171.2  487.94  4642.7  487.62  4968.3  488.62  4989.9  487.27
  5001.8  485.02  5004.6  484.52  5007.8  485.02  5020.2  487.42  5048.9  488.81
  5403.5  488.42  5942.5  493.36  6000.3  491.72  6079.1  491.53  6129.8  494.06
  6316.5  494.97  6544.9  498.55    6868  507.14  7262.3  510.58    7367  510.04
#Mann= 3 ,-1 , 0
  2781.3     .05       0  5001.8    .035       0  5007.8     .05       0
Bank Sta=5001.8,5007.8
XS Rating Curve= 0 ,0
Exp/Cntr=0.3,0.1

Type RM Length L Ch R = 1 ,3109    ,1182,1182,1182
BEGIN DESCRIPTION:
UNT0036 IN CHRS 3.0
END DESCRIPTION:
XS GIS Cut Line= 4
      3432801.54     10561248.99      3434239.03     10562238.56
      3435556.74     10561415.65      3436602.93     10560666.14
#Sta/Elev= 30
  2781.3  518.71  2842.2  517.17    2878  515.34  2919.9  511.46  2949.7  511.03
  3149.9  502.08    3344  496.01  3451.5  493.81  3654.5  491.94  3681.5  490.55
  3753.2  489.63  4171.2  487.94  4642.7  487.62  4968.3  488.62  4989.9  487.27
    4997  485.02  4999.8  484.52    5003  485.02  5020.2  487.42  5048.9  488.81
  5403.5  488.42  5942.5  493.36  6000.3  491.72  6079.1  491.53  6129.8  494.06
  6316.5  494.97  6544.9  498.55    6868  507.14  7262.3  510.58    7367  510.04
#Mann= 3 ,-1 , 0
  2781.3     .05       0    4997    .035       0    5003     .05       0
Bank Sta=4997,5003
XS Rating Curve= 0 ,0
Exp/Cntr=0.3,0.1

Type RM Length L Ch R = 1 ,1927    ,1226,1226,1226
BEGIN DESCRIPTION:
UNT0036 IN CHRS 2.0
END DESCRIPTION:
XS GIS Cut Line= 4
      3432740.86     10561333.02      3434329.41     10562921.58
      3435101.98     10563181.99      3436872.83     10561107.33
#Sta/Elev= 30
  1473.8  515.66  1558.6  512.28  1650.5  505.85    1700  505.28  1749.5  502.07
  2060.6  493.21    2202  490.76  3326.3  484.68  3418.3  487.08  3580.9  485.64
  3623.3  487.36  3800.6  487.06  3863.6  486.39  3881.5  482.86  3902.6  485.98
  4083.9  486.86  4762.7  485.94  4918.6  482.42  4926.3  483.96  4969.1   484.5
    4997  479.09  4999.8  478.59    5003  479.09  5018.5  483.41  5047.1  485.75
  5734.3  489.48  6500.7  501.62  6926.7  502.59  7060.6  505.49  7263.3  513.37
#Mann= 3 ,-1 , 0
  1473.8     .05       0    4997    .035       0    5003     .05       0
Bank Sta=4997,5003
XS Rating Curve= 0 ,0
Exp/Cntr=0.3,0.1

Type RM Length L Ch R = 1 ,701     ,0,0,0
BEGIN DESCRIPTION:
UNT0036 IN CHRS 1.0
END DESCRIPTION:
XS GIS Cut Line= 6
      3432711.21     10561364.13      3434385.69     10563136.49
      3435620.07      10563516.7      3436109.65     10563527.12
      3436349.24     10563448.99      3436823.19     10562829.21
#Sta/Elev= 30
   238.2  512.99   364.4  508.98     506  501.21   711.1  495.48   908.9  491.45
  1149.6  490.32  1192.1  488.89  1899.4  487.11  1963.2  484.94  2090.6  487.27
  2330.9  487.45    2430  485.99  2756.4  487.21  2780.7  486.51  2798.3  482.48
  2808.2  484.58  2813.4  483.26  2840.1  486.96  4852.8  484.47  4917.2  483.28
  4945.6  479.64  4987.9  477.89    4997  475.01  4999.8  474.51    5003  475.01
    5017  478.84  5116.7   482.5  5237.3  501.57  5395.1  510.34    5490  512.99
#Mann= 3 ,-1 , 0
   238.2     .05       0    4997    .035       0    5003     .05       0
Bank Sta=4997,5003
XS Rating Curve= 0 ,0
Exp/Cntr=0.3,0.1

Chan Stop Cuts=-1
Use User Specified Reach Order=0
Composite Channel Slope=5