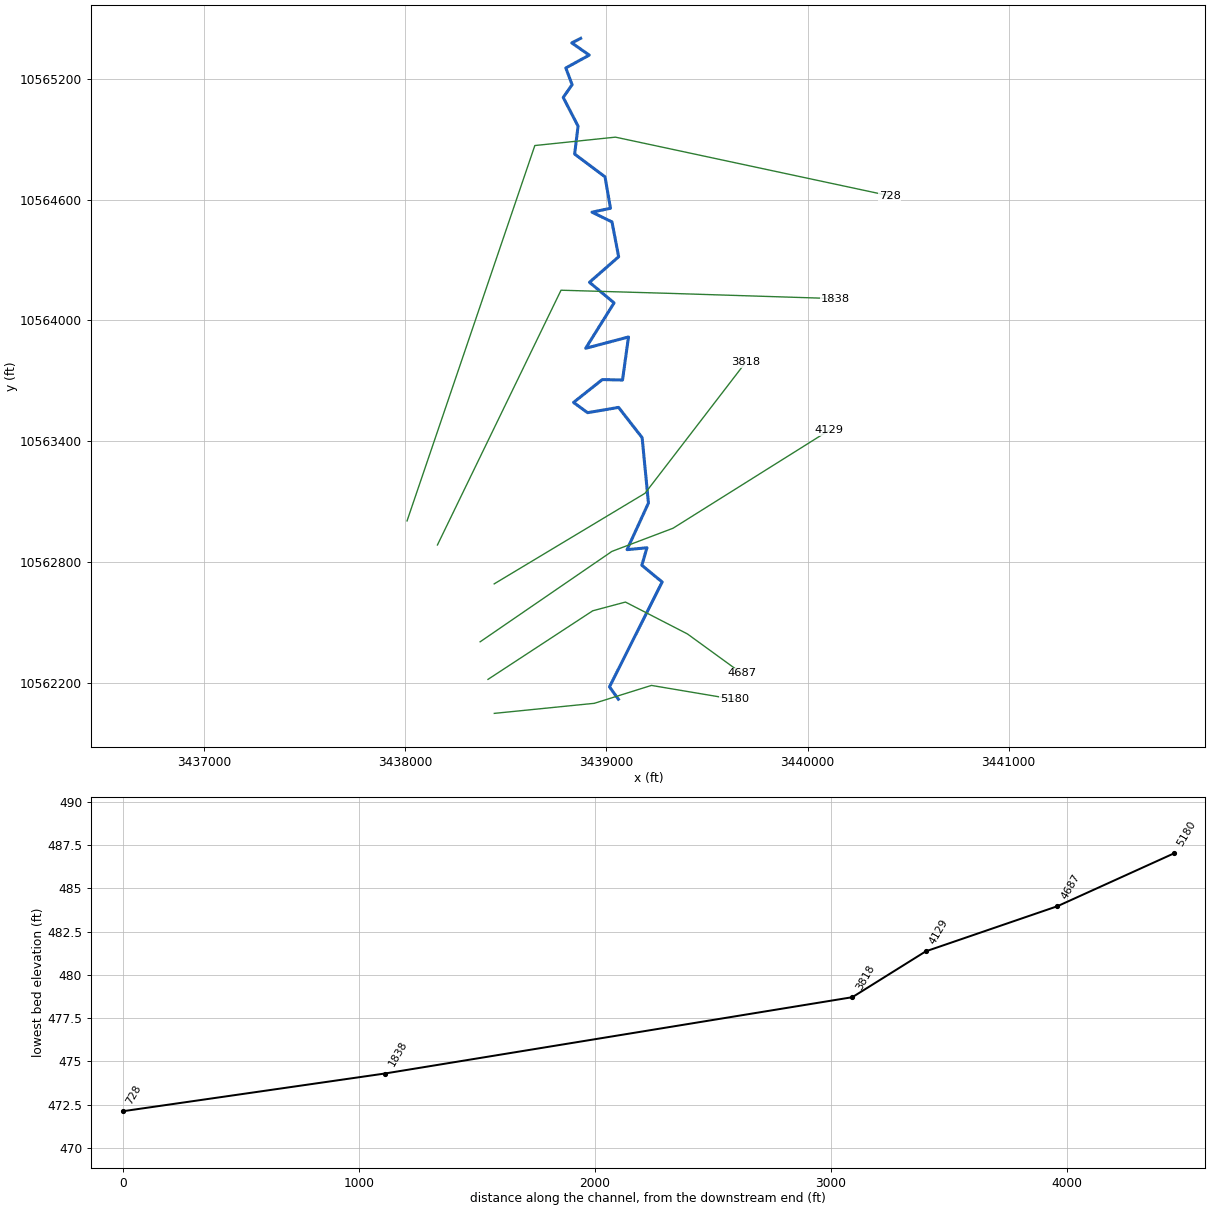
--- UNT0037 IN CHRS.prj (project) ---

Proj Title=UNT0037 IN CHRS Base Level Engineering
Current Plan=p01
Default Exp/Contr=0.3,0.1
English Units
Geom File=g01
Flow File=f01
Plan File=p01
BEGIN DESCRIPTION:
UNT0037 IN CHRS
END DESCRIPTION:

--- UNT0037 IN CHRS.p01 (plan) ---

Plan Title=Multiple Run
Short Identifier=Multiple
Geom File=g01
Flow File=f01
Subcritical Flow
K Sum by GR= 0
Std Step Tol= 0.01
Critical Tol= 0.01
Num of Std Step Trials= 20
Max Error Tol= 0.3
Flow Tol Ratio= 0.001
Split Flow NTrial= 30
Split Flow Tol= 0.02
Split Flow Ratio= 0.02
Log Output Level= 0
Friction Slope Method= 1
Unsteady Friction Slope Method= 2
Unsteady Bridges Friction Slope Method= 1
Parabolic Critical Depth
Global Vel Dist=  1 , 1 , 1
Global Log Level= 0
CheckData=True
Encroach Param= -1, 0, 0, 0
BEGIN DESCRIPTION:
Multiple Run
END DESCRIPTION:

--- UNT0037 IN CHRS.f01 (steady flow) ---

Flow Title=Multiple
Number of Profiles=7
Profile Names=10-year,25-year,50-year,1pct_min,100-year,1pct_plu,500-year
River Rch & RM= UNT0037 IN CHRS,Reach-1,5180
     541     694     809     686     928    1256    1220
River Rch & RM= UNT0037 IN CHRS,Reach-1,3818
     563     721     840     712     963    1303    1263
Boundary for River Rch & Prof#=UNT0037 IN CHRS,Reach-1,1
Up Type=0
Dn Type=3
Dn Slope=0.005
Boundary for River Rch & Prof#=UNT0037 IN CHRS,Reach-1,2
Up Type=0
Dn Type=3
Dn Slope=0.005
Boundary for River Rch & Prof#=UNT0037 IN CHRS,Reach-1,3
Up Type=0
Dn Type=3
Dn Slope=0.005
Boundary for River Rch & Prof#=UNT0037 IN CHRS,Reach-1,4
Up Type=0
Dn Type=3
Dn Slope=0.005
Boundary for River Rch & Prof#=UNT0037 IN CHRS,Reach-1,5
Up Type=0
Dn Type=3
Dn Slope=0.005
Boundary for River Rch & Prof#=UNT0037 IN CHRS,Reach-1,6
Up Type=0
Dn Type=3
Dn Slope=0.005
Boundary for River Rch & Prof#=UNT0037 IN CHRS,Reach-1,7
Up Type=0
Dn Type=3
Dn Slope=0.005

--- UNT0037 IN CHRS.g01 (geometry) ---

Geom Title=Existing Conditions

River Reach=UNT0037 IN CHRS,Reach-1
Reach XY= 30
      3439059.56     10562118.76      3439015.28     10562179.89
      3439277.21     10562700.83      3439176.27     10562783.99
      3439201.56     10562870.89      3439102.63     10562861.55
      3439209.02     10563093.09      3439177.56     10563417.94
      3439060.46     10563568.24      3438906.47     10563541.93
      3438836.48     10563592.85      3438979.53     10563706.53
      3439080.07     10563704.18      3439109.78     10563918.05
      3438896.77     10563861.80      3439038.19     10564087.50
      3438915.79     10564189.70      3439060.86     10564316.57
      3439027.66     10564489.75      3438928.38     10564538.03
      3439020.10     10564557.40      3438993.14     10564713.61
      3438842.04     10564826.72      3438858.95     10564965.49
      3438785.31     10565107.97      3438829.37     10565171.58
      3438798.13     10565254.35      3438914.73     10565318.31
      3438827.81     10565378.97      3438872.11     10565401.64

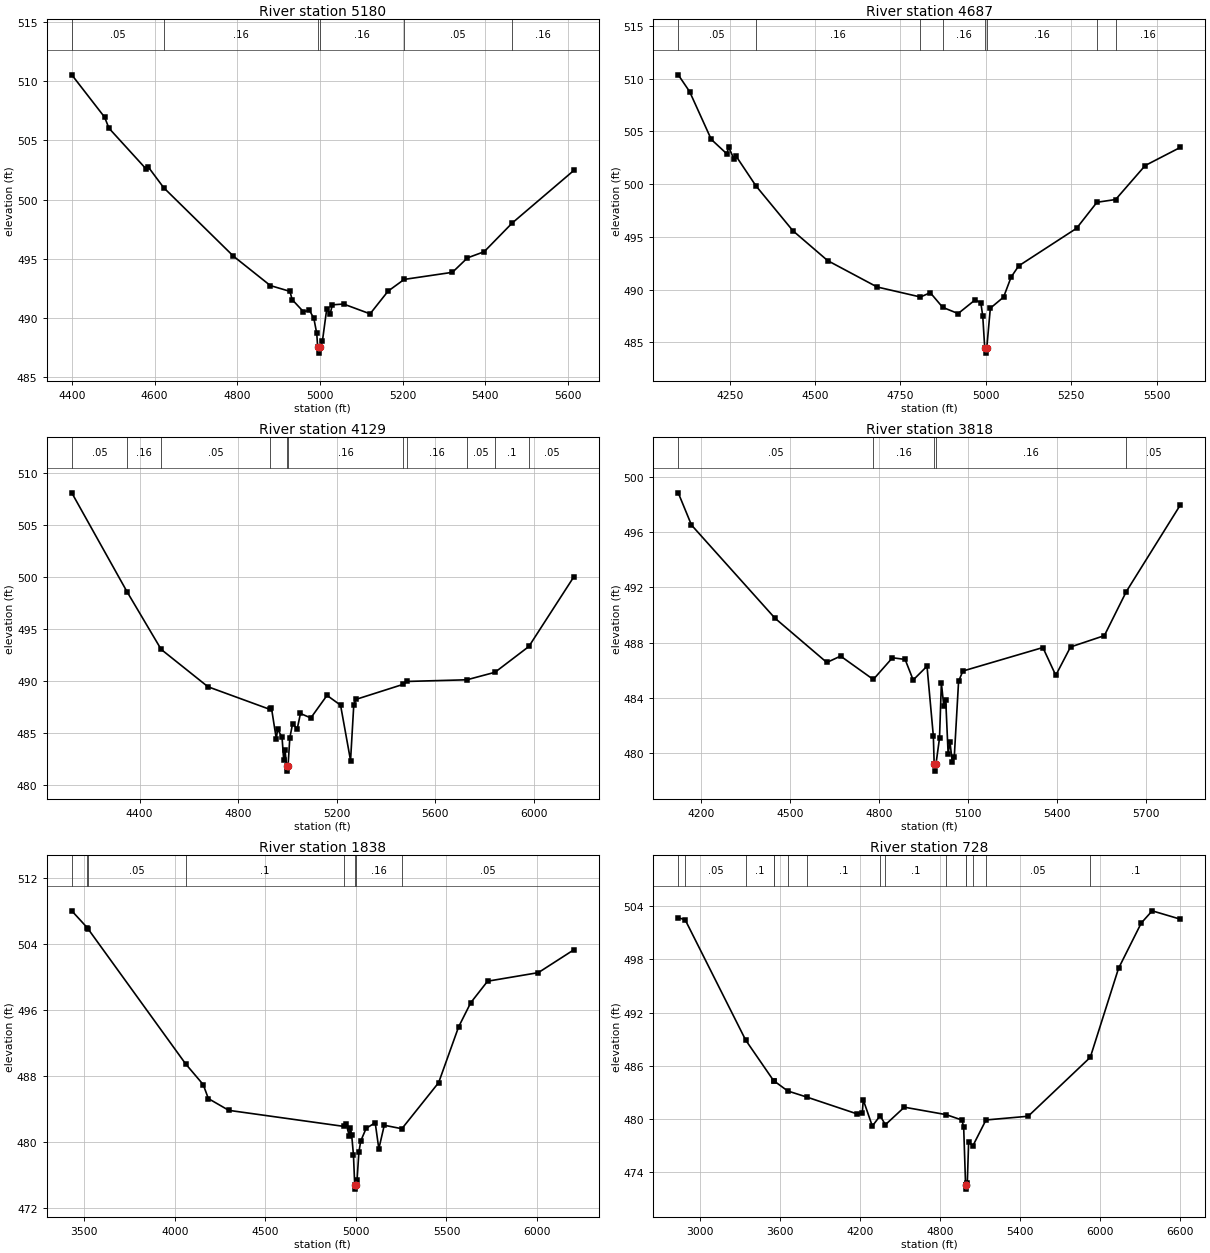
Type RM Length L Ch R = 1,5180,493,493,493
BEGIN DESCRIPTION:
UNT0037 IN CHRS 2.0
END DESCRIPTION:
XS GIS Cut Line= 4
      3438442.57     10562048.23      3438939.57     10562098.15
      3439223.86     10562187.13      3439636.16     10562117.69
#Sta/Elev= 30
  4399.3  510.54  4478.8  506.96  4489.3  506.03  4579.1  502.59  4584.1  502.77
  4621.9  501.00  4790.8  495.21  4880.0  492.73  4927.4  492.24  4932.9  491.54
  4959.9  490.53  4974.8  490.63  4985.3  489.97  4992.4  488.68  4994.6  487.52
  4997.3  487.02  5000.6  487.52  5006.2  488.06  5016.7  490.79  5024.8  490.32
  5030.1  491.10  5057.3  491.17  5121.5  490.34  5165.1  492.26  5204.1  493.25
  5320.9  493.85  5357.2  495.07  5397.7  495.59  5465.7  498.02  5614.8  502.46
#Mann=6,-1,0
  4399.3    0.05       0  4621.9    0.16       0  4994.6    0.07       0
  5000.6    0.16       0  5204.1    0.05       0  5465.7    0.16       0
Bank Sta=4994.6,5000.6
Exp/Cntr=0.3,0.1

Type RM Length L Ch R = 1,4687,558,558,558
BEGIN DESCRIPTION:
UNT0037 IN CHRS 1.5
END DESCRIPTION:
XS GIS Cut Line= 5
      3438411.16     10562217.12      3438932.02     10562557.84
      3439094.78     10562601.24      3439402.94     10562442.82
      3439672.08     10562247.48
#Sta/Elev= 30
  4099.3  510.35  4132.6  508.76  4196.0  504.23  4241.2  502.87  4247.2  503.47
  4262.3  502.38  4268.3  502.66  4326.4  499.84  4435.0  495.57  4536.7  492.74
  4681.5  490.24  4808.5  489.29  4837.1  489.70  4873.5  488.31  4918.7  487.72
  4968.7  489.02  4985.2  488.74  4990.8  487.49  4996.6  484.47  4999.3  483.97
  5002.6  484.47  5013.0  488.23  5051.8  489.28  5073.9  491.18  5096.1  492.24
  5265.4  495.80  5325.2  498.27  5379.8  498.53  5466.3  501.75  5569.2  503.47
#Mann=8,-1,0
  4099.3    0.05       0  4326.4    0.16       0  4808.5    0.05       0
  4873.5    0.16       0  4996.6    0.07       0  5002.6    0.16       0
  5325.2    0.05       0  5379.8    0.16       0
Bank Sta=4996.6,5002.6
Exp/Cntr=0.3,0.1

Type RM Length L Ch R = 1,4129,311,311,311
BEGIN DESCRIPTION:
UNT0037 IN CHRS 1.1
END DESCRIPTION:
XS GIS Cut Line= 4
      3438372.10     10562403.75      3439027.51     10562852.98
      3439331.33     10562968.00      3440108.71     10563455.22
#Sta/Elev= 30
  4125.1  508.11  4349.6  498.59  4487.8  493.06  4677.6  489.47  4928.3  487.30
  4935.3  487.42  4954.8  484.47  4960.2  485.38  4978.1  484.63  4985.0  482.39
  4990.3  483.40  4996.5  481.86  4999.2  481.36  5002.5  481.86  5009.8  484.58
  5020.8  485.89  5039.9  485.44  5052.9  486.90  5094.9  486.47  5160.6  488.64
  5215.6  487.70  5256.1  482.38  5269.1  487.69  5277.3  488.25  5468.1  489.69
  5486.3  489.98  5728.2  490.14  5842.0  490.86  5979.5  493.34  6162.0  500.04
#Mann=11,-1,0
  4125.1    0.05       0  4349.6    0.16       0  4487.8    0.05       0
  4928.3    0.16       0  4996.5    0.07       0  5002.5    0.16       0
  5468.1     0.1       0  5486.3    0.16       0  5728.2    0.05       0
  5842.0     0.1       0  5979.5    0.05       0
Bank Sta=4996.5,5002.5
Exp/Cntr=0.3,0.1

Type RM Length L Ch R = 1,3818,1980,1980,1980
BEGIN DESCRIPTION:
UNT0037 IN CHRS 3.0
END DESCRIPTION:
XS GIS Cut Line= 3
      3438442.07     10562691.62      3439192.11     10563141.64
      3439692.08     10563791.61
#Sta/Elev= 30
  4122.3  498.84  4167.0  496.51  4448.9  489.77  4623.8  486.57  4670.4  487.03
  4780.7  485.34  4845.4  486.91  4888.1  486.79  4915.3  485.30  4962.0  486.30
  4983.4  481.25  4986.2  479.21  4989.0  478.71  4992.2  479.21  5004.2  481.10
  5010.5  485.08  5018.7  483.42  5025.1  483.88  5033.3  479.97  5039.6  480.81
  5047.4  479.34  5054.1  479.76  5068.6  485.21  5083.1  485.95  5353.1  487.65
  5396.6  485.64  5446.4  487.69  5560.6  488.51  5634.8  491.70  5817.0  497.96
#Mann=5,-1,0
  4122.3    0.05       0  4780.7    0.16       0  4986.2    0.07       0
  4992.2    0.16       0  5634.8    0.05       0
Bank Sta=4986.2,4992.2
Exp/Cntr=0.3,0.1

Type RM Length L Ch R = 1,1838,1110,1110,1110
BEGIN DESCRIPTION:
UNT0037 IN CHRS 2.1
END DESCRIPTION:
XS GIS Cut Line= 4
      3438159.71     10562884.71      3438774.30     10564150.35
      3439315.96     10564134.72      3440137.99     10564108.71
#Sta/Elev= 30
  3431.9  508.07  3517.7  506.01  3524.1  505.81  4060.3  489.50  4157.6  486.98
  4185.7  485.29  4298.5  483.86  4934.2  481.91  4946.7  482.17  4964.5  480.72
  4969.5  481.76  4976.7  480.91  4986.7  478.45  4993.7  474.80  4996.5  474.30
  4999.7  474.80  5006.7  475.46  5016.8  478.79  5026.8  480.13  5056.8  481.68
  5106.8  482.35  5126.8  479.19  5156.8  482.05  5253.9  481.63  5456.9  487.22
  5567.0  493.98  5634.1  496.92  5727.1  499.53  6007.2  500.57  6203.2  503.34
#Mann=8,-1,0
  3431.9    0.05       0  3517.7     0.1       0  3524.1    0.05       0
  4060.3     0.1       0  4934.2    0.16       0  4993.7    0.07       0
  4999.7    0.16       0  5253.9    0.05       0
Bank Sta=4993.7,4999.7
Exp/Cntr=0.3,0.1

Type RM Length L Ch R = 1,728,0,0,0
BEGIN DESCRIPTION:
UNT0037 IN CHRS 1.0
END DESCRIPTION:
XS GIS Cut Line= 4
      3438008.67     10563004.51      3438644.09     10564869.10
      3439045.13     10564910.76      3440408.45     10564619.37
#Sta/Elev= 30
  2837.6  502.70  2889.6  502.46  3343.5  488.91  3552.6  484.35  3553.6  484.34
  3658.7  483.18  3802.4  482.49  4176.3  480.61  4218.6  480.67  4225.8  482.18
  4293.8  479.22  4352.7  480.39  4391.7  479.37  4534.0  481.35  4848.2  480.51
  4966.4  479.90  4979.4  479.08  4993.5  472.62  4996.3  472.12  4999.5  472.62
  5006.6  472.83  5016.6  477.48  5047.7  476.98  5146.8  479.91  5463.2  480.33
  5929.4  486.97  6141.3  496.99  6312.0  502.10  6393.8  503.47  6604.8  502.53
#Mann=15,-1,0
  2837.6     0.1       0  2889.6    0.05       0  3343.5     0.1       0
  3552.6    0.05       0  3553.6     0.1       0  3658.7    0.05       0
  3802.4     0.1       0  4352.7    0.16       0  4391.7     0.1       0
  4848.2    0.16       0  4993.5    0.07       0  4999.5    0.16       0
  5047.7     0.1       0  5146.8    0.05       0  5929.4     0.1       0
Bank Sta=4993.5,4999.5
Exp/Cntr=0.3,0.1

Chan Stop Cuts=-1