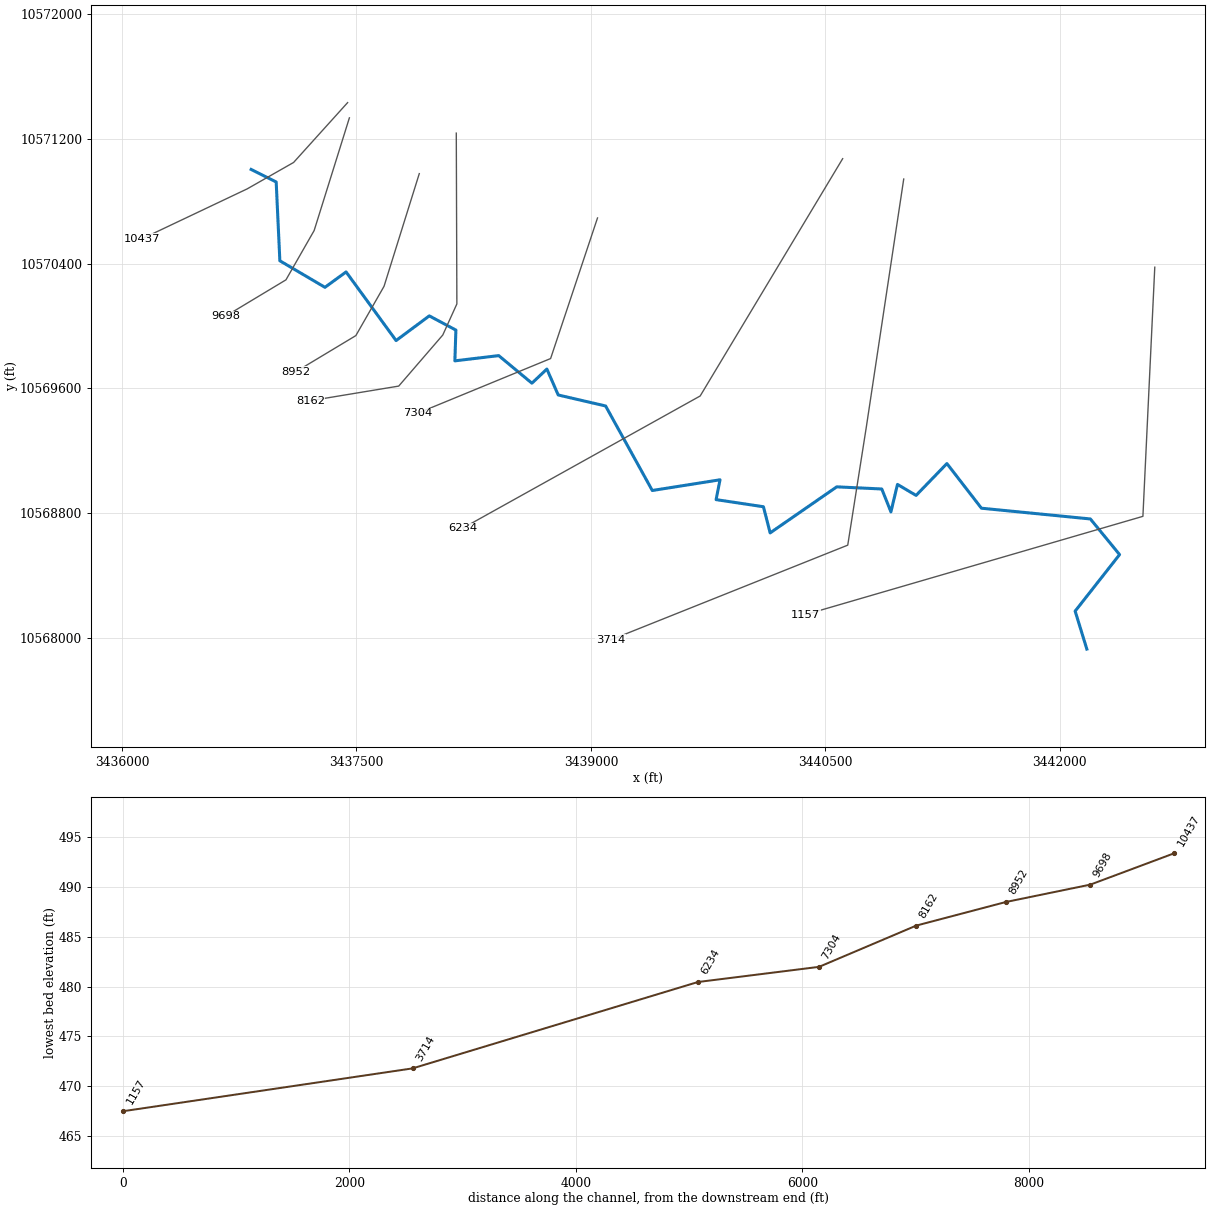
--- UNT0039 IN CHRS.prj (project) ---

Proj Title=UNT0039 IN CHRS Base Level Engineering
Current Plan=p01
Default Exp/Contr=0.3,0.1
English Units
Geom File=g01
Flow File=f01
Plan File=p01
BEGIN DESCRIPTION:
UNT0039 IN CHRS
END DESCRIPTION:

--- UNT0039 IN CHRS.p01 (plan) ---

Plan Title=Multiple Run
Short Identifier=Multiple
Geom File=g01
Flow File=f01
Subcritical Flow
K Sum by GR= 0
Std Step Tol= 0.01
Critical Tol= 0.01
Num of Std Step Trials= 20
Max Error Tol= 0.3
Flow Tol Ratio= 0.001
Split Flow NTrial= 30
Split Flow Tol= 0.02
Split Flow Ratio= 0.02
Log Output Level= 0
Friction Slope Method= 1
Unsteady Friction Slope Method= 2
Unsteady Bridges Friction Slope Method= 1
Parabolic Critical Depth
Global Vel Dist=  1 , 1 , 1
Global Log Level= 0
CheckData=True
Encroach Param= -1, 0, 0, 0
BEGIN DESCRIPTION:
Multiple Run
END DESCRIPTION:

--- UNT0039 IN CHRS.f01 (steady flow) ---

Flow Title=Multiple
Number of Profiles=7
Profile Names=10-year,25-year,50-year,1pct_min,100-year,1pct_plu,500-year
River Rch & RM= UNT0039 IN CHRS,Reach-1,10437
     400     503     578     484     655     886     838
River Rch & RM= UNT0039 IN CHRS,Reach-1,6234
     460     580     668     560     757    1024     970
Boundary for River Rch & Prof#=UNT0039 IN CHRS,Reach-1,1
Up Type=0
Dn Type=3
Dn Slope=0.005
Boundary for River Rch & Prof#=UNT0039 IN CHRS,Reach-1,2
Up Type=0
Dn Type=3
Dn Slope=0.005
Boundary for River Rch & Prof#=UNT0039 IN CHRS,Reach-1,3
Up Type=0
Dn Type=3
Dn Slope=0.005
Boundary for River Rch & Prof#=UNT0039 IN CHRS,Reach-1,4
Up Type=0
Dn Type=3
Dn Slope=0.005
Boundary for River Rch & Prof#=UNT0039 IN CHRS,Reach-1,5
Up Type=0
Dn Type=3
Dn Slope=0.005
Boundary for River Rch & Prof#=UNT0039 IN CHRS,Reach-1,6
Up Type=0
Dn Type=3
Dn Slope=0.005
Boundary for River Rch & Prof#=UNT0039 IN CHRS,Reach-1,7
Up Type=0
Dn Type=3
Dn Slope=0.005

--- UNT0039 IN CHRS.g01 (geometry) ---

Geom Title=Existing Conditions

River Reach=UNT0039 IN CHRS,Reach-1
Reach XY= 30
      3436826.55     10571002.27      3436986.72     10570921.87
      3437010.23     10570417.48      3437298.78     10570247.58
      3437433.84     10570346.07      3437753.64     10569906.82
      3437966.13     10570064.73      3438136.24     10569973.82
      3438129.68     10569776.94      3438410.12     10569810.39
      3438622.50     10569633.86      3438718.23     10569724.47
      3438790.71     10569558.53      3439094.01     10569487.94
      3439392.55     10568946.97      3439825.75     10569015.46
      3439800.66     10568888.53      3440103.37     10568843.01
      3440146.50     10568675.67      3440572.45     10568970.33
      3440860.53     10568956.65      3440918.98     10568810.03
      3440960.90     10568985.96      3441079.87     10568915.47
      3441277.04     10569119.39      3441497.91     10568833.59
      3442194.88     10568764.77      3442381.59     10568536.64
      3442097.35     10568174.77      3442172.11     10567931.64

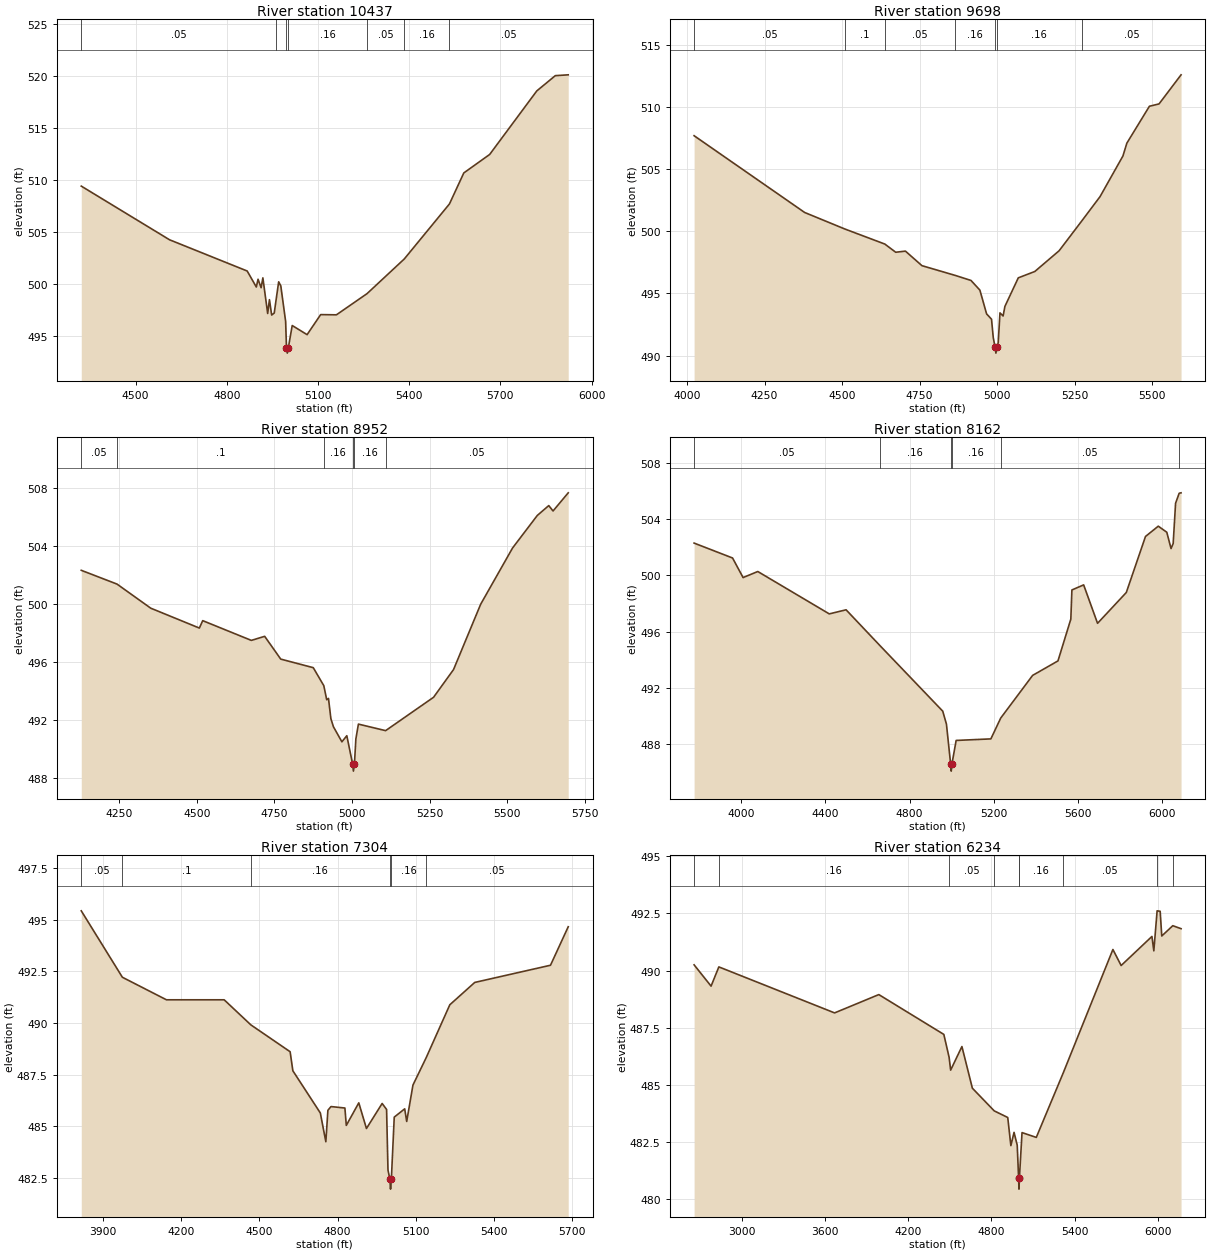
Type RM Length L Ch R = 1,10437,739,739,739
BEGIN DESCRIPTION:
UNT0039 IN CHRS 5.0
END DESCRIPTION:
XS GIS Cut Line= 4
      3437443.67     10571430.04      3437098.04     10571046.84
      3436801.22     10570877.77      3436128.73     10570558.43
#Sta/Elev= 30
  4321.1  509.42  4611.5  504.25  4867.0  501.24  4897.0  499.70  4902.7  500.45
  4912.8  499.63  4918.6  500.58  4934.4  497.15  4940.2  498.48  4947.5  497.00
  4956.0  497.19  4963.2  498.69  4970.6  500.20  4977.6  499.81  4993.5  496.38
  4996.3  493.83  4999.0  493.33  5002.3  493.83  5015.1  495.99  5064.1  495.11
  5108.7  497.04  5160.6  497.02  5261.3  499.06  5383.8  502.40  5532.4  507.70
  5579.7  510.69  5664.8  512.47  5819.8  518.59  5880.7  520.06  5923.2  520.14
#Mann=7,-1,0
  4321.1    0.05       0  4963.2    0.16       0  4996.3    0.07       0
  5002.3    0.16       0  5261.3    0.05       0  5383.8    0.16       0
  5532.4    0.05       0
Bank Sta=4996.3,5002.3
Exp/Cntr=0.3,0.1

Type RM Length L Ch R = 1,9698,746,746,746
BEGIN DESCRIPTION:
UNT0039 IN CHRS 4.2
END DESCRIPTION:
XS GIS Cut Line= 4
      3437454.98     10571332.44      3437229.54     10570611.01
      3437049.20     10570295.41      3436662.22     10570062.47
#Sta/Elev= 30
  4022.5  507.70  4379.2  501.52  4508.9  500.19  4637.7  498.98  4672.9  498.32
  4704.3  498.41  4757.5  497.24  4865.6  496.45  4915.8  496.05  4944.5  495.27
  4966.1  493.36  4982.0  492.93  4987.7  491.43  4993.4  490.70  4996.2  490.20
  4999.4  490.70  5003.6  491.03  5009.3  493.44  5019.4  493.19  5025.2  493.96
  5068.4  496.26  5121.6  496.77  5200.1  498.44  5273.2  500.84  5332.2  502.80
  5406.0  506.07  5418.6  507.10  5491.4  510.07  5522.5  510.26  5593.5  512.60
#Mann=7,-1,0
  4022.5    0.05       0  4508.9     0.1       0  4637.7    0.05       0
  4865.6    0.16       0  4993.4    0.07       0  4999.4    0.16       0
  5273.2    0.05       0
Bank Sta=4993.4,4999.4
Exp/Cntr=0.3,0.1

Type RM Length L Ch R = 1,8952,790,790,790
BEGIN DESCRIPTION:
UNT0039 IN CHRS 4.1
END DESCRIPTION:
XS GIS Cut Line= 4
      3437902.07     10570975.46      3437676.64     10570254.08
      3437496.30     10569938.48      3437110.22     10569706.08
#Sta/Elev= 30
  4127.3  502.30  4242.6  501.35  4351.3  499.69  4508.0  498.32  4518.9  498.83
  4675.6  497.47  4718.6  497.75  4770.4  496.18  4875.2  495.59  4909.2  494.35
  4918.6  493.38  4924.3  493.47  4932.0  492.08  4940.2  491.52  4967.5  490.48
  4983.4  490.90  5002.0  488.96  5004.7  488.46  5008.0  488.96  5012.6  490.68
  5020.8  491.70  5108.5  491.25  5263.1  493.55  5327.5  495.46  5414.9  499.96
  5517.8  503.84  5597.5  506.08  5634.4  506.76  5648.3  506.39  5697.2  507.64
#Mann=6,-1,0
  4127.3    0.05       0  4242.6     0.1       0  4909.2    0.16       0
  5002.0    0.07       0  5008.0    0.16       0  5108.5    0.05       0
Bank Sta=5002,5008
Exp/Cntr=0.3,0.1

Type RM Length L Ch R = 1,8162,858,858,858
BEGIN DESCRIPTION:
UNT0039 IN CHRS 3.1
END DESCRIPTION:
XS GIS Cut Line= 5
      3438138.77     10571234.68      3438142.53     10570141.37
      3438052.36     10569942.24      3437770.57     10569615.36
      3437205.15     10569521.75
#Sta/Elev= 30
  3775.1  502.30  3958.1  501.24  4008.1  499.85  4078.1  500.28  4418.1  497.27
  4498.1  497.56  4659.7  495.01  4957.9  490.36  4975.5  489.44  4995.6  486.60
  4998.3  486.10  5001.6  486.60  5021.7  488.28  5186.9  488.39  5233.8  489.87
  5385.5  492.90  5506.1  493.93  5567.3  496.90  5572.4  498.97  5628.3  499.33
  5694.4  496.60  5831.2  498.79  5922.5  502.77  5983.3  503.50  6023.8  503.07
  6044.1  501.91  6054.2  502.27  6065.6  505.13  6082.7  505.84  6091.7  505.87
#Mann=6,-1,0
  3775.1    0.05       0  4659.7    0.16       0  4995.6    0.07       0
  5001.6    0.16       0  5233.8    0.05       0  6082.7     0.1       0
Bank Sta=4995.6,5001.6
Exp/Cntr=0.3,0.1

Type RM Length L Ch R = 1,7304,1070,1070,1070
BEGIN DESCRIPTION:
UNT0039 IN CHRS 4.0
END DESCRIPTION:
XS GIS Cut Line= 3
      3439042.12     10570691.68      3438742.11     10569791.64
      3437892.07     10569441.63
#Sta/Elev= 30
  3816.5  495.42  3974.2  492.21  4143.3  491.12  4364.7  491.12  4466.9  489.91
  4617.7  488.61  4628.2  487.69  4733.6  485.65  4754.7  484.26  4762.6  485.78
  4774.5  485.96  4827.8  485.89  4833.2  485.05  4881.1  486.14  4910.5  484.90
  4970.7  486.11  4987.7  485.82  4993.1  482.89  5000.1  482.47  5002.9  481.97
  5006.1  482.47  5017.1  485.45  5057.2  485.85  5064.9  485.24  5088.9  487.00
  5139.9  488.33  5230.3  490.88  5326.0  491.96  5616.5  492.79  5684.5  494.65
#Mann=6,-1,0
  3816.5    0.05       0  3974.2     0.1       0  4466.9    0.16       0
  5000.1    0.07       0  5006.1    0.16       0  5139.9    0.05       0
Bank Sta=5000.1,5006.1
Exp/Cntr=0.3,0.1

Type RM Length L Ch R = 1,6234,2520,2520,2520
BEGIN DESCRIPTION:
UNT0039 IN CHRS 3.0
END DESCRIPTION:
XS GIS Cut Line= 3
      3440610.26     10571071.10      3439698.77     10569551.97
      3438180.60     10568706.13
#Sta/Elev= 30
  2657.4  490.25  2779.7  489.32  2835.8  490.16  3669.9  488.15  3988.6  488.95
  4457.2  487.21  4495.2  486.21  4506.3  485.65  4587.5  486.68  4662.9  484.86
  4820.2  483.87  4917.8  483.58  4940.3  482.35  4963.2  482.93  4986.1  482.37
  4996.0  480.95  4998.7  480.45  5002.0  480.95  5020.7  482.92  5123.6  482.71
  5317.8  485.53  5675.7  490.92  5735.1  490.22  5956.9  491.49  5970.6  490.86
  5994.3  492.61  6016.3  492.59  6027.8  491.51  6107.2  491.96  6166.9  491.83
#Mann=9,-1,0
  2657.4    0.05       0  2835.8    0.16       0  4495.2    0.05       0
  4820.2    0.16       0  4996.0    0.07       0  5002.0    0.16       0
  5317.8    0.05       0  5994.3     0.1       0  6107.2    0.05       0
Bank Sta=4996,5002
Exp/Cntr=0.3,0.1

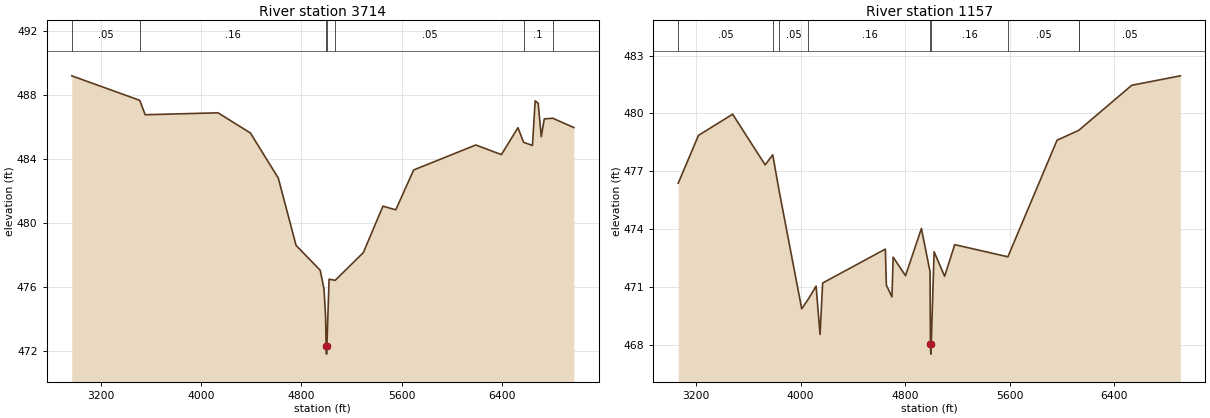
Type RM Length L Ch R = 1,3714,2557,2557,2557
BEGIN DESCRIPTION:
UNT0039 IN CHRS 2.0
END DESCRIPTION:
XS GIS Cut Line= 4
      3441000.86     10570940.86      3440762.14     10569356.66
      3440642.78     10568597.11      3439125.43     10567990.17
#Sta/Elev= 30
  2969.3  489.18  3511.3  487.65  3555.1  486.75  4136.0  486.87  4394.4  485.61
  4617.0  482.79  4758.7  478.59  4951.0  477.04  4981.4  475.87  4993.5  474.25
  4998.6  472.30  5001.4  471.80  5004.6  472.30  5021.9  476.48  5070.8  476.41
  5295.2  478.14  5451.6  481.04  5554.0  480.81  5696.7  483.30  6191.9  484.86
  6396.7  484.26  6528.7  485.94  6573.2  485.03  6644.2  484.83  6666.0  487.62
  6690.2  487.46  6714.5  485.38  6738.7  486.49  6806.9  486.53  6974.5  485.95
#Mann=7,-1,0
  2969.3    0.05       0  3511.3    0.16       0  4998.6    0.07       0
  5004.6    0.16       0  5070.8    0.05       0  6573.2     0.1       0
  6806.9    0.05       0
Bank Sta=4998.6,5004.6
Exp/Cntr=0.3,0.1

Type RM Length L Ch R = 1,1157,0,0,0
BEGIN DESCRIPTION:
UNT0039 IN CHRS 1.0
END DESCRIPTION:
XS GIS Cut Line= 3
      3442606.76     10570376.59      3442530.81     10568781.57
      3440371.48     10568152.22
#Sta/Elev= 30
  3062.4  476.38  3217.5  478.86  3479.2  479.96  3728.1  477.33  3786.6  477.85
  3832.6  476.08  4008.4  469.86  4058.9  470.37  4118.5  471.04  4148.6  468.53
  4168.6  471.20  4649.1  472.96  4656.7  471.09  4699.5  470.48  4708.7  472.54
  4803.7  471.58  4925.2  474.03  4991.2  471.79  4994.4  468.01  4997.2  467.51
  5000.4  468.01  5022.4  472.82  5103.1  471.55  5180.5  473.19  5587.6  472.56
  5964.2  478.61  6130.4  479.12  6131.9  479.13  6536.6  481.46  6908.4  481.95
#Mann=9,-1,0
  3062.4    0.05       0  3786.6    0.16       0  3832.6    0.05       0
  4058.9    0.16       0  4994.4    0.07       0  5000.4    0.16       0
  5587.6    0.05       0  6130.4    0.16       0  6131.9    0.05       0
Bank Sta=4994.4,5000.4
Exp/Cntr=0.3,0.1

Chan Stop Cuts=-1