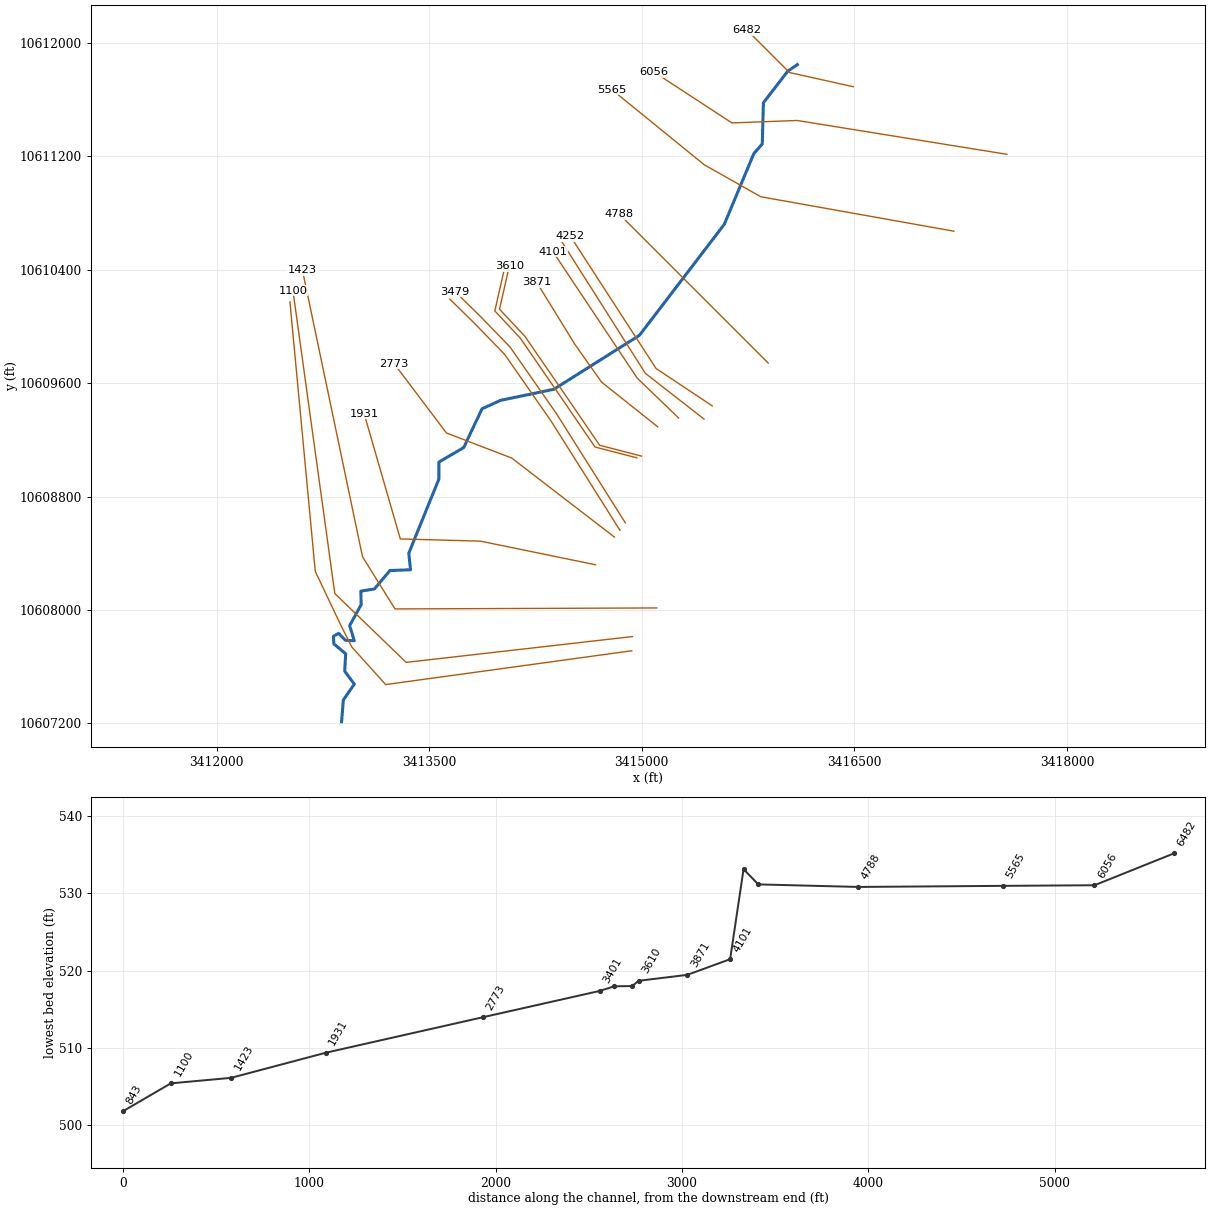
--- UNT00396 IN CHRS.prj (project) ---

Proj Title=UNT00396 IN CHRS Base Level Engineering
Current Plan=p01
Default Exp/Contr=0.3,0.1
English Units
Geom File=g01
Flow File=f01
Plan File=p01
Y Axis Title=Elevation
X Axis Title(PF)=Main Channel Distance
X Axis Title(XS)=Station
BEGIN DESCRIPTION:
UNT00396 IN CHRS
END DESCRIPTION:
DSS Export Rating Curves= 0
DSS Export Rating Curve Sorted= 0
DSS Export Volume Flow Curves= 0
DXF OffsetX= 0
DXF OffsetY= 0
DXF ScaleX= 1
DXF ScaleY= 10

--- UNT00396 IN CHRS.p01 (plan) ---

Plan Title=Multiple Run
Short Identifier=Multiple
Geom File=g01
Flow File=f01
Subcritical Flow
K Sum by GR= 0
Std Step Tol= 0.01
Critical Tol= 0.01
Num of Std Step Trials= 20
Max Error Tol= 0.3
Flow Tol Ratio= 0.001
Split Flow NTrial= 30
Split Flow Tol= 0.02
Split Flow Ratio= 0.02
Log Output Level= 0
Friction Slope Method= 1
Unsteady Friction Slope Method= 2
Unsteady Bridges Friction Slope Method= 1
Parabolic Critical Depth
Global Vel Dist=  1 , 1 , 1
Global Log Level= 0
CheckData=True
Encroach Param= -1, 0, 0, 0
BEGIN DESCRIPTION:
Multiple Run
END DESCRIPTION:

--- UNT00396 IN CHRS.f01 (steady flow) ---

Flow Title=Multiple
Number of Profiles=7
Profile Names=10-year,25-year,50-year,1pct_min,100-year,1pct_plu,500-year
River Rch & RM= UNT00396 IN CHRS,Reach-1,6482
     276     339     383     316     428     579     532
Boundary for River Rch & Prof#=UNT00396 IN CHRS,Reach-1,1
Up Type=0
Dn Type=3
Dn Slope=0.005
Boundary for River Rch & Prof#=UNT00396 IN CHRS,Reach-1,2
Up Type=0
Dn Type=3
Dn Slope=0.005
Boundary for River Rch & Prof#=UNT00396 IN CHRS,Reach-1,3
Up Type=0
Dn Type=3
Dn Slope=0.005
Boundary for River Rch & Prof#=UNT00396 IN CHRS,Reach-1,4
Up Type=0
Dn Type=3
Dn Slope=0.005
Boundary for River Rch & Prof#=UNT00396 IN CHRS,Reach-1,5
Up Type=0
Dn Type=3
Dn Slope=0.005
Boundary for River Rch & Prof#=UNT00396 IN CHRS,Reach-1,6
Up Type=0
Dn Type=3
Dn Slope=0.005
Boundary for River Rch & Prof#=UNT00396 IN CHRS,Reach-1,7
Up Type=0
Dn Type=3
Dn Slope=0.005

--- UNT00396 IN CHRS.g01 (geometry) ---

Geom Title=Existing Conditions
Program Version=4.10

River Reach=UNT00396 IN CHRS,Reach-1
Reach XY= 30
      3416098.01     10611847.55      3416029.52     10611800.73
      3415858.21     10611578.54      3415850.03     10611287.42
       3415790.7     10611220.04      3415582.27     10610721.02
      3414983.31     10609937.53      3414379.84     10609556.97
      3414003.31     10609478.85      3413872.94     10609419.23
       3413743.8     10609145.97      3413568.25     10609043.14
      3413568.49     10608923.19       3413356.1     10608400.32
      3413368.42     10608283.53      3413223.55     10608278.16
      3413113.22     10608147.95      3413018.11     10608133.04
      3413019.85     10608037.33      3412939.15     10607889.29
      3412971.65     10607782.98      3412909.48     10607785.95
      3412861.17     10607835.16      3412824.53     10607814.57
      3412827.72     10607760.61      3412910.89     10607691.06
      3412904.18     10607567.67      3412971.89     10607476.37
       3412894.5      10607365.3      3412882.11     10607211.64

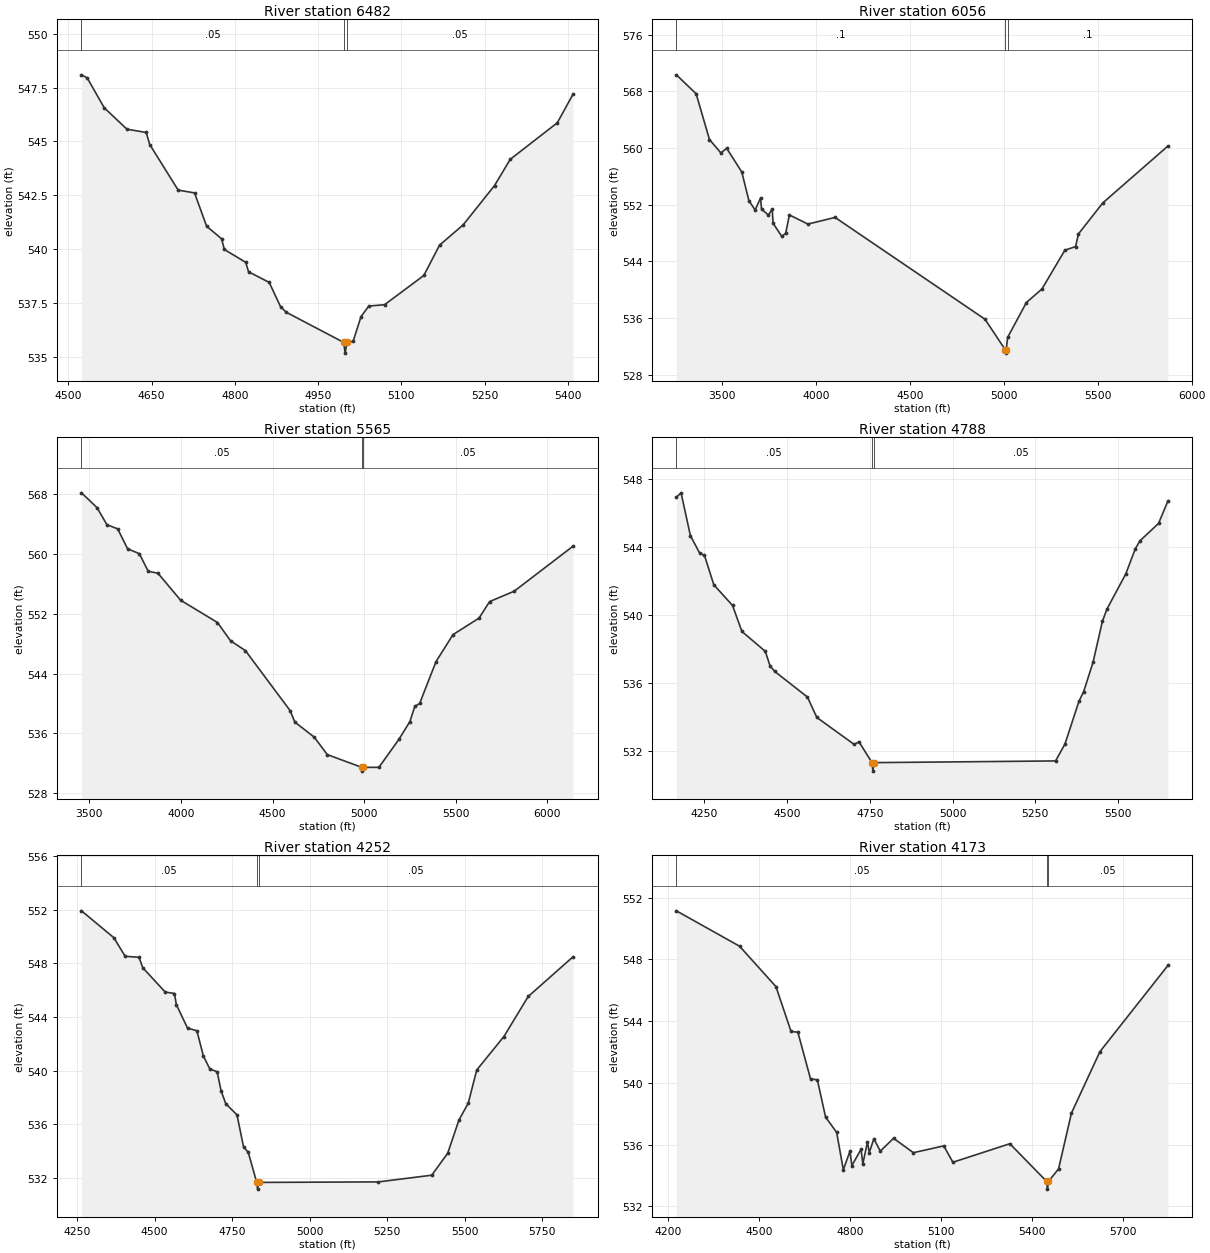
Type RM Length L Ch R = 1 ,6482    ,426,426,426
BEGIN DESCRIPTION:
UNT00396 IN CHRS 13.0
END DESCRIPTION:
XS GIS Cut Line= 3
      3416492.08     10611691.65      3416042.11     10611791.64
      3415742.11     10612091.63
#Sta/Elev= 30
  4523.9   548.1  4534.1  547.96  4564.8  546.57  4605.8  545.57  4640.4  545.42
  4646.8  544.86    4698  542.74  4727.5  542.61  4749.2  541.06  4776.1  540.48
  4781.2  539.98  4819.7  539.38  4824.8  538.94  4861.9  538.45  4882.4  537.32
  4892.7  537.06    4996  535.66  4998.7  535.16    5002  535.66  5013.1  535.71
  5027.3  536.86  5041.4  537.35  5069.7  537.41  5140.4  538.77  5168.7  540.18
  5211.1  541.12  5267.7  542.95    5296  544.17  5380.8  545.87  5409.1   547.2
#Mann= 3 ,-1 , 0
  4523.9     .05       0    4996     .03       0    5002     .05       0
Bank Sta=4996,5002
XS Rating Curve= 0 ,0
Exp/Cntr=0.3,0.1

Type RM Length L Ch R = 1 ,6056    ,491,491,491
BEGIN DESCRIPTION:
UNT00396 IN CHRS 12.0
END DESCRIPTION:
XS GIS Cut Line= 4
      3417576.01     10611214.69      3416095.94     10611453.41
      3415635.87     10611436.05       3415085.9     10611795.48
#Sta/Elev= 30
  3256.9  570.31  3362.1  567.64  3433.1  561.18  3493.8  559.29  3524.8  559.94
  3605.2   556.6  3643.3  552.53  3676.2  551.24  3705.1  552.93  3710.2  551.36
  3747.1  550.52  3766.9  551.39    3772  549.36    3818  547.51  3838.8  547.94
  3858.5  550.54  3957.3  549.25  4101.6  550.19    4900  535.82  5007.1  531.54
  5009.9  531.04  5013.1  531.54  5020.1  533.25  5120.2  538.18    5203  540.09
  5324.9  545.56  5382.2  546.08  5397.3  547.86    5527  552.24  5873.5  560.26
#Mann= 3 ,-1 , 0
  3256.9      .1       0  5007.1     .07       0  5020.1      .1       0
Bank Sta=5007.1,5013.1
XS Rating Curve= 0 ,0
Exp/Cntr=0.3,0.1

Type RM Length L Ch R = 1 ,5565    ,777,777,777
BEGIN DESCRIPTION:
UNT00396 IN CHRS 10.0
END DESCRIPTION:
XS GIS Cut Line= 4
      3417202.71     10610672.16      3415839.87     10610915.22
      3415440.56     10611140.91      3414789.53     10611670.42
#Sta/Elev= 30
  3457.6  568.19  3542.3  566.21  3596.2  563.93  3655.1  563.37    3709  560.71
  3773.1  560.05  3821.8  557.69  3874.7  557.44  3998.7  553.82  4199.7  550.84
  4270.8   548.4  4352.1  547.08  4595.9  539.06  4621.8  537.52  4727.9   535.5
    4799  533.17  4987.8  531.46  4990.5  530.96  4993.8  531.46  5080.6  531.47
    5190  535.22  5249.2  537.57  5276.6  539.62  5302.8  540.01  5392.1  545.61
  5484.8  549.22    5627  551.43  5684.5  553.64  5818.8  555.03  6139.8  561.05
#Mann= 3 ,-1 , 0
  3457.6     .05       0  4987.8    .035       0  4993.8     .05       0
Bank Sta=4987.8,4993.8
XS Rating Curve= 0 ,0
Exp/Cntr=0.3,0.1

Type RM Length L Ch R = 1 ,4788    ,536,536,536
BEGIN DESCRIPTION:
UNT00396 IN CHRS 9.0
END DESCRIPTION:
XS GIS Cut Line= 3
      3415892.11     10609741.63      3415292.11     10610341.64
      3414842.13     10610791.62
#Sta/Elev= 30
  4165.8  546.94    4180   547.2  4208.2  544.68  4236.5  543.64  4250.7  543.52
  4278.9  541.79  4335.5  540.57  4363.8  539.04  4434.5  537.87  4448.7  537.02
  4462.8  536.69  4561.8  535.18  4590.1  533.98  4703.2  532.39  4717.4  532.55
  4756.8  531.32  4759.5  530.82  4762.8  531.32  5311.3  531.42  5339.6  532.41
    5382  534.93  5396.2   535.5  5424.5  537.22  5452.7  539.63  5466.9  540.37
  5523.5  542.43  5551.7  543.88  5565.9  544.37  5622.5   545.4  5650.7  546.72
#Mann= 3 ,-1 , 0
  4165.8     .05       0  4756.8    .035       0  4762.8     .05       0
Bank Sta=4756.8,4762.8
XS Rating Curve= 0 ,0
Exp/Cntr=0.3,0.1

Type RM Length L Ch R = 1 ,4252    ,79,79,79
BEGIN DESCRIPTION:
UNT00396 IN CHRS 7.9
END DESCRIPTION:
XS GIS Cut Line= 3
      3415496.66     10609440.37      3415100.82      10609703.4
      3414496.87     10610635.35
#Sta/Elev= 30
  4264.3  551.92  4368.9  549.91    4405  548.53  4449.9  548.45  4462.1  547.67
  4534.3  545.86  4564.3  545.75  4570.3  544.92  4606.4  543.17  4636.5  542.97
  4657.5  541.09  4678.6  540.11    4702  539.91  4714.6  538.49  4729.7  537.53
    4766  536.69  4787.1   534.3  4802.3   533.9  4829.6  531.65  4832.3  531.15
  4835.6  531.65  5222.3  531.69  5394.4  532.19  5445.8  533.83  5482.1  536.31
    5512  537.56  5539.4  540.04  5627.1  542.54  5705.6  545.53  5850.1  548.49
#Mann= 3 ,-1 , 0
  4264.3     .05       0  4829.6    .035       0  4835.6     .05       0
Bank Sta=4829.6,4835.6
XS Rating Curve= 0 ,0
Exp/Cntr=0.3,0.1

Type RM Length L Ch R = 1 ,4173    ,72,72,72
BEGIN DESCRIPTION:
UNT00396 IN CHRS 7.0
END DESCRIPTION:
XS GIS Cut Line= 3
      3415439.33     10609346.65       3415025.3     10609669.55
       3414436.9     10610596.39
#Sta/Elev= 30
    4227  551.14  4435.6  548.85  4555.9  546.23  4605.6  543.33  4628.2  543.28
  4669.9  540.26  4692.5   540.2  4719.6  537.79  4756.3  536.79  4778.2  534.37
  4800.3  535.58  4806.3  534.64  4836.8   535.7  4842.7  534.76  4857.9  536.17
  4863.9  535.49  4879.1  536.38  4900.3  535.58  4944.1  536.41  5009.6  535.48
  5109.9  535.92    5140  534.86  5328.1  536.06  5449.6  533.62  5452.3  533.12
  5455.6  533.62  5488.9  534.43  5531.4  538.04  5625.4  542.02  5849.9   547.6
#Mann= 3 ,-1 , 0
    4227     .05       0  5449.6     .03       0  5455.6     .05       0
Bank Sta=5449.6,5455.6
XS Rating Curve= 0 ,0
Exp/Cntr=0.3,0.1

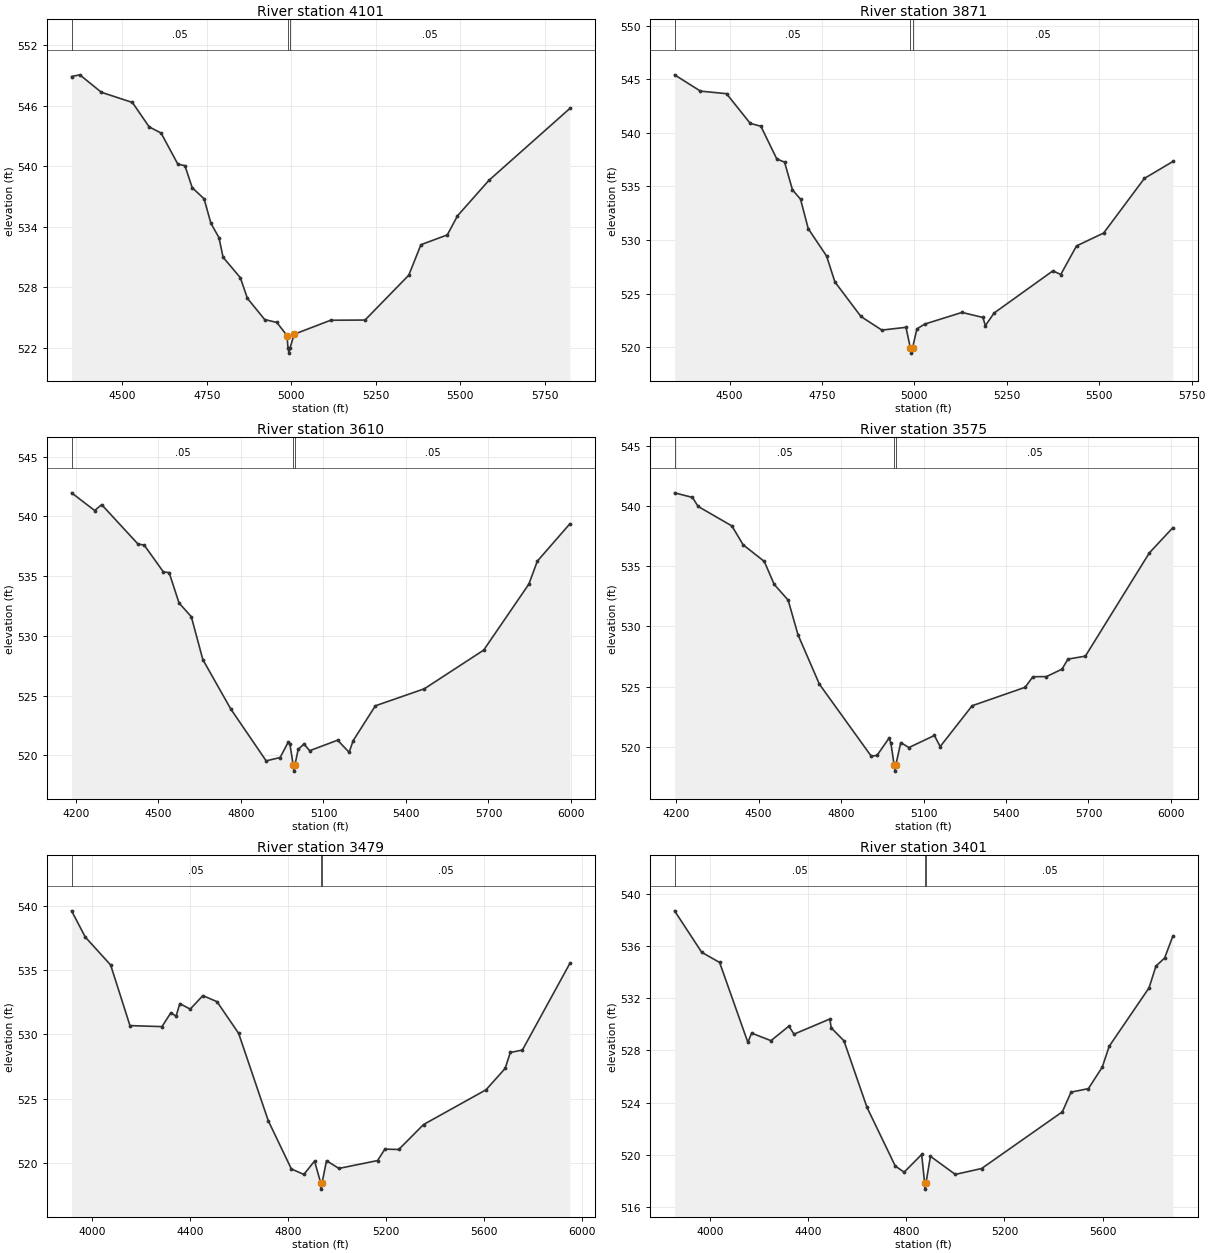
Type RM Length L Ch R = 1 ,4101    ,230,230,230
BEGIN DESCRIPTION:
UNT00396 IN CHRS 7.8
END DESCRIPTION:
XS GIS Cut Line= 3
      3415259.66     10609354.45        3414968.     10609635.69
      3414374.23     10610526.35
#Sta/Elev= 30
  4349.5  548.89  4373.9  549.06  4437.7  547.33  4529.6  546.32  4579.2   543.9
  4614.5  543.29  4664.1  540.21  4685.2  540.05  4706.6  537.88  4741.8  536.77
  4762.1  534.34  4785.8  532.93  4798.1  530.98  4849.2  528.95  4870.2   526.9
  4921.3   524.8  4957.4  524.51  4987.4  523.21  4990.4  521.97  4993.2  521.47
  4996.4  521.97  5008.4  523.34  5116.6  524.73  5218.5  524.75    5348   529.2
    5384  532.22  5462.1  533.19  5492.2  535.08  5585.3   538.6  5825.1  545.73
#Mann= 3 ,-1 , 0
  4349.5     .05       0  4990.4     .03       0  4996.4     .05       0
Bank Sta=4987.4,5008.4
XS Rating Curve= 0 ,0
Exp/Cntr=0.3,0.1

Type RM Length L Ch R = 1 ,3871    ,261,261,261
BEGIN DESCRIPTION:
UNT00396 IN CHRS 6.0
END DESCRIPTION:
XS GIS Cut Line= 4
       3415111.6     10609292.79      3414715.73     10609607.92
      3414528.23     10609873.55      3414257.39     10610313.67
#Sta/Elev= 30
  4351.4  545.42  4421.4   543.9  4491.9  543.66    4556  540.89  4584.8  540.62
    4628  537.56  4648.9  537.27  4670.3  534.68  4692.1  533.81  4712.9  531.06
  4762.6   528.5    4785  526.09  4855.5  522.86    4912  521.59  4977.3  521.85
  4989.1  519.94  4991.8  519.44  4995.1  519.94  5006.9   521.7  5027.8  522.15
  5128.8  523.24  5185.4  522.77    5192     522  5215.5  523.18  5374.7  527.12
    5396  526.78  5438.6  529.45    5512  530.65  5622.1  535.75  5699.3  537.33
#Mann= 3 ,-1 , 0
  4351.4     .05       0  4989.1     .03       0  4995.1     .05       0
Bank Sta=4989.1,4995.1
XS Rating Curve= 0 ,0
Exp/Cntr=0.3,0.1

Type RM Length L Ch R = 1 ,3610    ,35,35,35
BEGIN DESCRIPTION:
UNT00396 IN CHRS 5.3
END DESCRIPTION:
XS GIS Cut Line= 6
      3414997.97      10609085.5      3414702.82     10609161.89
      3414470.18     10609502.17      3414175.04     10609930.99
      3413996.22     10610121.96      3414065.57     10610427.11
#Sta/Elev= 30
    4184  541.97    4268  540.49  4293.4  540.98  4425.2  537.69  4448.3  537.59
  4517.8  535.35  4538.8  535.29  4574.7  532.75  4619.4   531.6  4661.3  528.01
    4763  523.87  4891.6  519.53  4942.4  519.81  4972.1  521.11  4978.2   520.9
  4990.1  519.17  4992.8  518.67  4996.1  519.17    5008  520.49  5028.9  520.94
  5049.9  520.38  5151.4  521.26  5193.3  520.25  5208.2  521.23  5288.7  524.14
  5466.5  525.56  5682.6   528.8    5847  534.33  5877.8  536.25  5996.2  539.38
#Mann= 3 ,-1 , 0
    4184     .05       0  4990.1     .04       0  4996.1     .05       0
Bank Sta=4990.1,4996.1
XS Rating Curve= 0 ,0
Exp/Cntr=0.3,0.1

Type RM Length L Ch R = 1 ,3575    ,96,96,96
BEGIN DESCRIPTION:
UNT00396 IN CHRS 5.0
END DESCRIPTION:
XS GIS Cut Line= 6
        3414965.     10609073.34      3414669.83     10609149.74
       3414437.2     10609490.02      3414142.06     10609918.84
      3413963.24     10610109.81      3414032.67     10610415.33
#Sta/Elev= 30
  4194.5   541.1  4259.5  540.72  4280.1  539.97  4403.1  538.35  4443.7  536.79
  4520.9   535.4  4556.8   533.5  4607.6  532.19  4643.5  529.31  4721.3  525.21
  4909.6  519.24  4930.6  519.29  4974.3  520.72  4981.3  520.33  4993.2  518.49
    4996  517.99  4999.2  518.49  5017.2  520.36  5046.9  519.95  5139.6  520.95
  5160.6  520.03  5276.9  523.42  5469.5  524.95  5497.8  525.83  5547.1  525.84
  5603.8  526.46  5625.3  527.29  5688.8  527.54  5921.3  536.11  6007.1  538.21
#Mann= 3 ,-1 , 0
  4194.5     .05       0  4993.2     .04       0  4999.2     .05       0
Bank Sta=4993.2,4999.2
XS Rating Curve= 0 ,0
Exp/Cntr=0.3,0.1

Type RM Length L Ch R = 1 ,3479    ,78,78,78
BEGIN DESCRIPTION:
UNT00396 IN CHRS 5.2
END DESCRIPTION:
XS GIS Cut Line= 5
      3414883.93     10608614.47      3414397.84     10609385.27
      3414071.46     10609854.02      3413863.12      10610069.3
      3413682.59     10610246.36
#Sta/Elev= 30
    3917  539.59    3973  537.55  4076.5  535.38  4155.4  530.67    4286  530.59
  4322.5  531.67  4343.7   531.4    4359  532.38  4401.4  531.95  4453.1     533
  4510.8  532.53  4599.1  530.07  4720.3  523.27  4814.5  519.53  4865.5   519.1
  4909.1  520.14  4934.1  518.46  4936.8  517.96  4940.1  518.46    4958  520.17
  5008.6  519.57  5166.6  520.18  5196.3  521.07    5253  521.04  5354.2  522.98
  5609.4  525.68  5687.4  527.34  5708.5  528.58  5757.9  528.77  5951.9  535.51
#Mann= 3 ,-1 , 0
    3917     .05       0  4934.1     .03       0  4940.1     .05       0
Bank Sta=4934.1,4940.1
XS Rating Curve= 0 ,0
Exp/Cntr=0.3,0.1

Type RM Length L Ch R = 1 ,3401    ,628,628,628
BEGIN DESCRIPTION:
UNT00396 IN CHRS 5.1
END DESCRIPTION:
XS GIS Cut Line= 5
      3414845.77     10608562.35      3414359.65     10609333.19
      3414033.26     10609801.94      3413824.93     10610017.22
      3413645.72     10610192.98
#Sta/Elev= 30
    3854  538.71  3964.7  535.53  4037.7  534.75    4153  528.62  4168.3  529.33
  4247.2  528.75  4320.2  529.86  4341.4  529.25  4487.3  530.41  4493.2  529.73
    4545  528.74  4639.1  523.63  4754.5  519.13  4790.6  518.66  4862.1  520.02
    4874  517.86  4876.7  517.36    4880  517.86  4897.9  519.88  4999.2  518.49
  5106.5  518.94  5436.1  523.29  5471.5   524.8  5542.3  525.07  5598.9  526.72
  5627.2  528.32  5789.7   532.8    5818  534.47  5853.3  535.09  5887.1  536.78
#Mann= 3 ,-1 , 0
    3854     .05       0    4874     .03       0    4880     .05       0
Bank Sta=4874,4880
XS Rating Curve= 0 ,0
Exp/Cntr=0.3,0.1

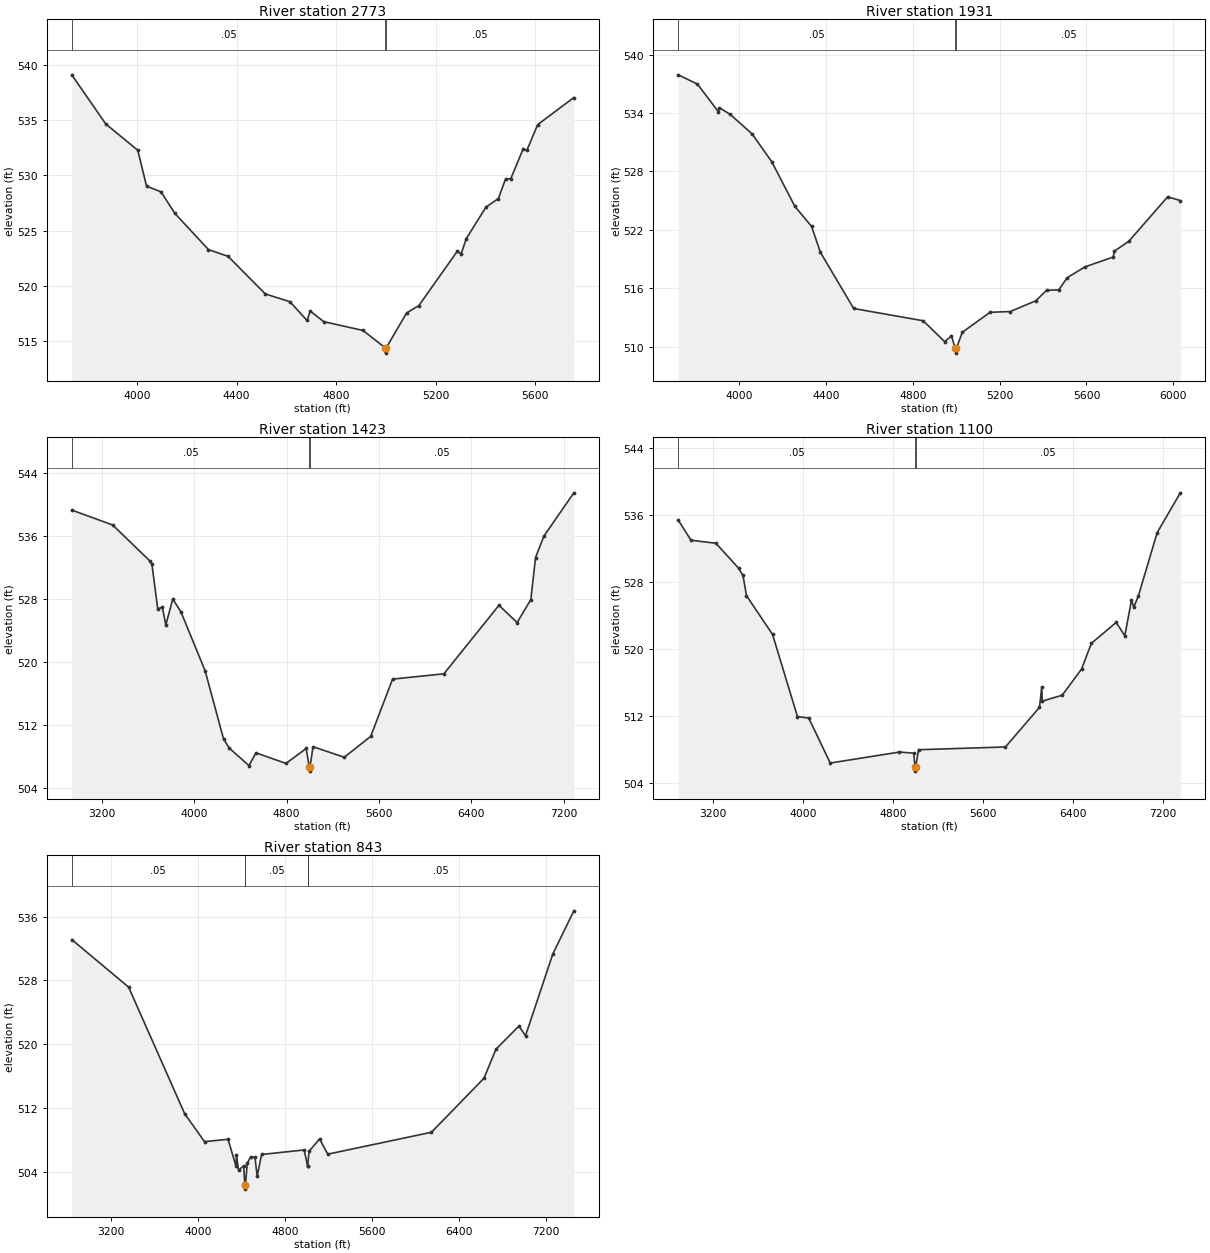
Type RM Length L Ch R = 1 ,2773    ,842,842,842
BEGIN DESCRIPTION:
UNT00396 IN CHRS 4.0
END DESCRIPTION:
XS GIS Cut Line= 4
       3414806.9     10608514.16      3414082.92     10609071.47
      3413621.98     10609248.55      3413252.77     10609737.36
#Sta/Elev= 30
  3736.5  539.08  3873.4  534.64  4002.1  532.27  4037.4  529.02  4095.4  528.52
  4151.5  526.56  4286.5   523.3  4365.4  522.69  4514.9   519.3  4614.5  518.59
  4683.1   516.9  4695.8  517.75  4750.5  516.79  4908.1     516  4996.2  514.45
  4998.9  513.95  5002.2  514.45  5083.8  517.58  5133.1  518.25  5288.3  523.17
  5302.9   522.9  5323.7  524.29  5402.8  527.13  5452.7  527.91  5481.9  529.68
  5502.7   529.7  5552.6  532.39  5567.2  532.25  5610.9  534.58  5756.5  537.03
#Mann= 3 ,-1 , 0
  3736.5     .05       0  4996.2     .03       0  5002.2     .05       0
Bank Sta=4996.2,5002.2
XS Rating Curve= 0 ,0
Exp/Cntr=0.3,0.1

Type RM Length L Ch R = 1 ,1931    ,508,508,508
BEGIN DESCRIPTION:
UNT00396 IN CHRS 3.0
END DESCRIPTION:
XS GIS Cut Line= 4
      3414674.09     10608318.86      3413861.57     10608485.53
      3413296.46     10608501.15      3413041.26     10609383.95
#Sta/Elev= 30
  3718.9  537.92  3807.5  536.97  3903.3  534.15  3908.4  534.55  3958.8  533.85
  4059.6  531.85  4149.7  529.01  4256.1  524.43  4333.4  522.36  4374.2   519.7
  4527.4  513.94  4847.9  512.68  4946.7  510.54    4978  511.13    4995  509.86
  4997.7  509.36    5001  509.86    5028   511.5  5155.8  513.55  5249.5  513.63
  5366.3  514.73    5416   515.8  5472.4  515.85  5511.2   517.1    5593  518.21
  5723.3  519.22  5728.5  519.82  5795.7  520.85  5974.2   525.4  6032.6  525.02
#Mann= 3 ,-1 , 0
  3718.9     .05       0    4995     .03       0    5001     .05       0
Bank Sta=4995,5001
XS Rating Curve= 0 ,0
Exp/Cntr=0.3,0.1

Type RM Length L Ch R = 1 ,1423    ,323,323,323
BEGIN DESCRIPTION:
UNT00396 IN CHRS 1.2
END DESCRIPTION:
XS GIS Cut Line= 4
      3415106.05     10608014.17      3413258.85     10608007.23
      3413029.68     10608375.28      3412606.08     10610396.08
#Sta/Elev= 30
  2941.1  539.24    3295  537.35  3615.1  532.81  3635.1  532.34  3685.1  526.72
  3725.1  526.91  3755.1  524.66  3815.1  527.95  3885.1  526.35  4095.1  518.85
  4255.1  510.18  4305.1  509.02  4475.1  506.81  4535.1  508.43  4795.5  507.09
  4970.2  508.99  4996.7  506.61  4999.4  506.11  5002.7  506.61  5029.1  509.21
  5299.9  507.87  5528.3  510.52  5717.8  517.79  6161.9  518.46  6638.4  527.16
  6795.5  524.96  6914.2  527.88  6955.1  533.21  7026.6  535.92  7286.6  541.43
#Mann= 3 ,-1 , 0
  2941.1     .05       0  4996.7     .03       0  5002.7     .05       0
Bank Sta=4996.7,5002.7
XS Rating Curve= 0 ,0
Exp/Cntr=0.3,0.1

Type RM Length L Ch R = 1 ,1100    ,257,257,257
BEGIN DESCRIPTION:
UNT00396 IN CHRS 1.1
END DESCRIPTION:
XS GIS Cut Line= 4
      3414934.94     10607812.39      3413337.68     10607630.09
      3412834.21      10608116.2      3412539.07     10610251.62
#Sta/Elev= 30
  2892.5  535.42  3006.1  533.01  3227.5  532.65  3428.8  529.67  3468.2   528.8
  3499.2  526.38  3730.7  521.75  3952.2  511.93  4052.8  511.74  4244.1  506.37
  4858.7  507.68  4986.1  507.55  4997.2   505.9  4999.9   505.4  5003.2   505.9
  5028.5  507.96  5801.1  508.29  6103.9  513.03  6123.7  515.44  6128.8  513.77
  6305.8  514.48  6477.4  517.59  6564.9  520.68  6785.5  523.18  6862.4  521.59
  6921.6  525.83  6941.8  525.02  6982.2  526.32  7149.8  533.91  7355.7  538.68
#Mann= 3 ,-1 , 0
  2892.5     .05       0  4997.2    .035       0  5003.2     .05       0
Bank Sta=4997.2,5003.2
XS Rating Curve= 0 ,0
Exp/Cntr=0.3,0.1

Type RM Length L Ch R = 1 ,843     ,0,0,0
BEGIN DESCRIPTION:
UNT00396 IN CHRS 1.0
END DESCRIPTION:
XS GIS Cut Line= 6
      3414929.48      10607712.2      3413193.36     10607473.48
      3412954.65     10607738.24      3412878.69     10607887.98
       3412696.4     10608272.09      3412517.58     10610173.79
#Sta/Elev= 30
  2841.9  533.12  3364.1  527.15  3878.9  511.26  4061.5  507.75  4277.6  508.05
  4349.6  504.71  4354.7  506.11  4373.6  504.16  4421.6  504.72  4431.1  502.29
  4433.9  501.79  4437.1  502.29  4454.3  505.05  4484.6  505.81    4525  505.77
  4545.2  503.41  4585.5  506.14  4977.1  506.71  5007.7   504.7    5009  504.73
  5021.9  506.54    5118  508.09  5193.6  506.18  6146.1  508.93  6628.2  515.71
  6738.7  519.36  6949.6  522.26  7009.9  521.04    7261  531.32    7454  536.73
#Mann= 5 ,-1 , 0
  2841.9     .05       0  4431.1    .035       0  4437.1     .05       0
  5007.7     .16       0    5009     .05       0
Bank Sta=4431.1,4437.1
XS Rating Curve= 0 ,0
Exp/Cntr=0.3,0.1

Chan Stop Cuts=-1
Use User Specified Reach Order=0
Composite Channel Slope=5