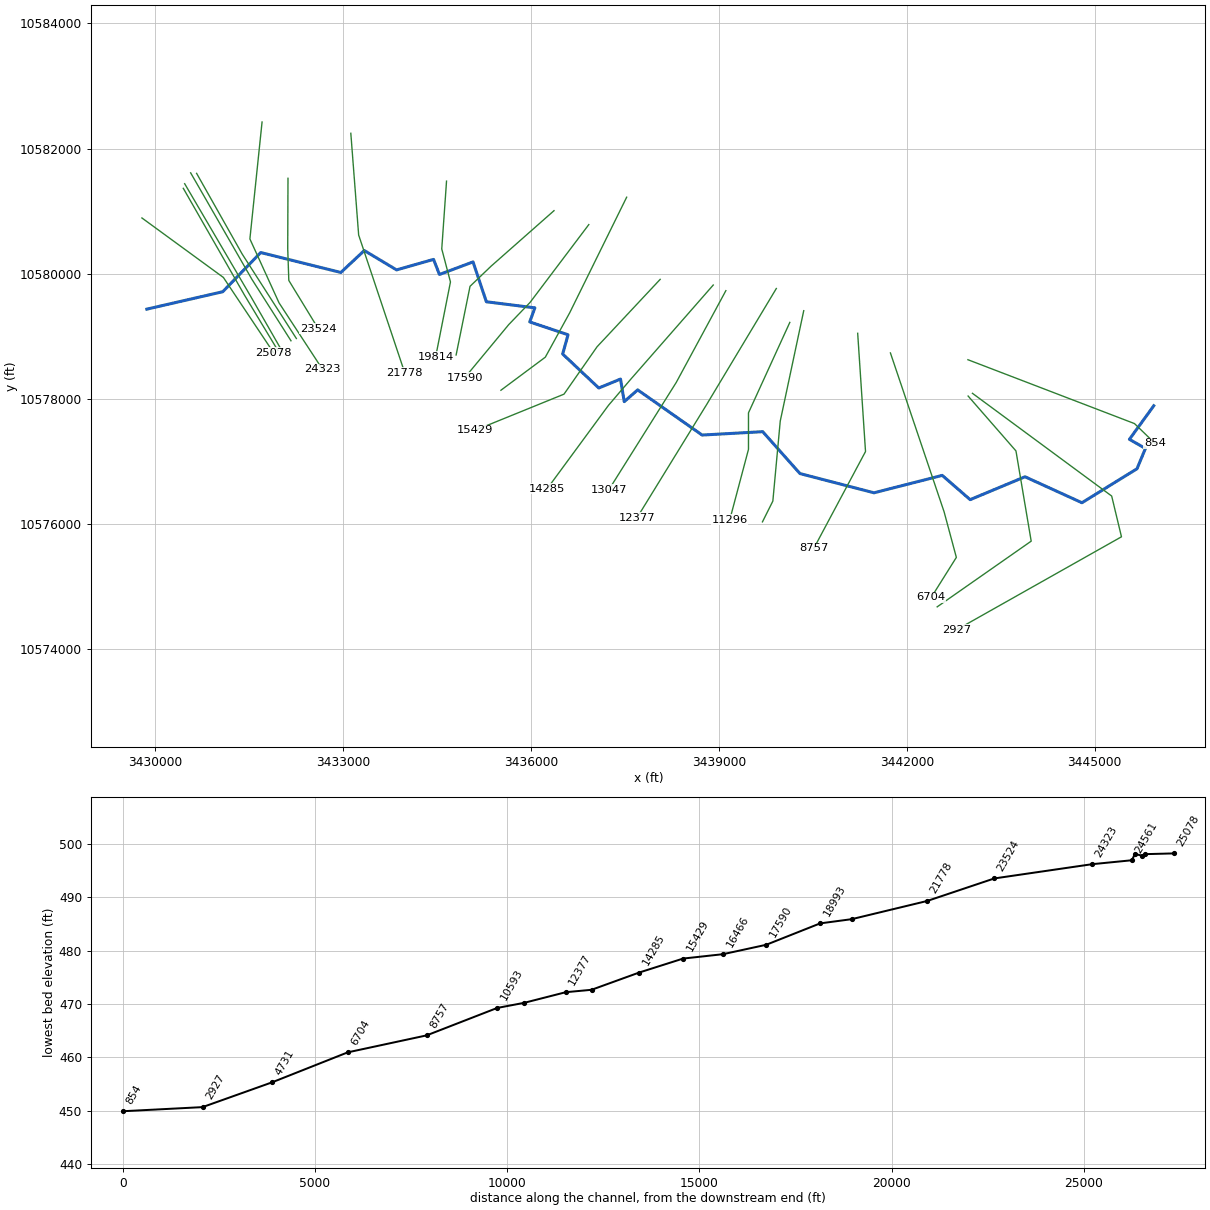
--- UNT0040 IN CHRS.prj (project) ---

Proj Title=UNT0040 IN CHRS Base Level Engineering
Current Plan=p01
Default Exp/Contr=0.3,0.1
English Units
Geom File=g01
Flow File=f01
Plan File=p01
Y Axis Title=Elevation
X Axis Title(PF)=Main Channel Distance
X Axis Title(XS)=Station
BEGIN DESCRIPTION:
UNT0040 IN CHRS
END DESCRIPTION:
DSS Export Rating Curves= 0
DSS Export Rating Curve Sorted= 0
DSS Export Volume Flow Curves= 0
DXF OffsetX= 0
DXF OffsetY= 0
DXF ScaleX= 1
DXF ScaleY= 10

--- UNT0040 IN CHRS.p01 (plan) ---

Plan Title=Multiple Run
Short Identifier=Multiple
Geom File=g01
Flow File=f01
Subcritical Flow
K Sum by GR= 0
Std Step Tol= 0.01
Critical Tol= 0.01
Num of Std Step Trials= 20
Max Error Tol= 0.3
Flow Tol Ratio= 0.001
Split Flow NTrial= 30
Split Flow Tol= 0.02
Split Flow Ratio= 0.02
Log Output Level= 0
Friction Slope Method= 1
Unsteady Friction Slope Method= 2
Unsteady Bridges Friction Slope Method= 1
Parabolic Critical Depth
Global Vel Dist=  1 , 1 , 1
Global Log Level= 0
CheckData=True
Encroach Param= -1, 0, 0, 0
BEGIN DESCRIPTION:
Multiple Run
END DESCRIPTION:

--- UNT0040 IN CHRS.f01 (steady flow) ---

Flow Title=Multiple
Number of Profiles=7
Profile Names=10-year,25-year,50-year,1pct_min,100-year,1pct_plu,500-year
River Rch & RM= UNT0040 IN CHRS,Reach-1,25078
     601     764     884     744    1006    1361    1300
River Rch & RM= UNT0040 IN CHRS,Reach-1,21778
     682     867    1005     844    1142    1544    1474
River Rch & RM= UNT0040 IN CHRS,Reach-1,13047
     814    1042    1213    1024    1385    1873    1802
River Rch & RM= UNT0040 IN CHRS,Reach-1,6704
     962    1241    1452    1231    1664    2251    2185
Boundary for River Rch & Prof#=UNT0040 IN CHRS,Reach-1,1
Up Type=0
Dn Type=3
Dn Slope=0.005
Boundary for River Rch & Prof#=UNT0040 IN CHRS,Reach-1,2
Up Type=0
Dn Type=3
Dn Slope=0.005
Boundary for River Rch & Prof#=UNT0040 IN CHRS,Reach-1,3
Up Type=0
Dn Type=3
Dn Slope=0.005
Boundary for River Rch & Prof#=UNT0040 IN CHRS,Reach-1,4
Up Type=0
Dn Type=3
Dn Slope=0.005
Boundary for River Rch & Prof#=UNT0040 IN CHRS,Reach-1,5
Up Type=0
Dn Type=3
Dn Slope=0.005
Boundary for River Rch & Prof#=UNT0040 IN CHRS,Reach-1,6
Up Type=0
Dn Type=3
Dn Slope=0.005
Boundary for River Rch & Prof#=UNT0040 IN CHRS,Reach-1,7
Up Type=0
Dn Type=3
Dn Slope=0.005

--- UNT0040 IN CHRS.g01 (geometry) ---

Geom Title=Existing Conditions
Program Version=4.10

River Reach=UNT0040 IN CHRS ,Reach-1
Reach XY= 30
      3429870.06     10579435.31      3431082.43     10579713.66
      3431688.04     10580339.47      3432967.36       10580021.
      3433341.35     10580371.62      3433856.22     10580062.19
       3434446.6      10580230.1      3434541.21     10579989.16
      3435077.15     10580189.96       3435289.9     10579553.06
      3436063.91     10579456.11      3435981.93     10579231.51
      3436593.48     10579026.25      3436507.43     10578719.04
      3437084.06     10578175.56      3437430.95     10578318.64
      3437490.53      10577957.6      3437704.42      10578145.9
      3438733.61     10577424.25      3439700.83     10577478.06
      3440295.52      10576808.9      3441476.96     10576501.99
      3442566.06     10576779.98      3443011.78     10576392.44
      3443887.24     10576757.93      3444796.08      10576343.3
      3445674.63     10576885.85      3445809.42     10577209.83
      3445553.72     10577355.93      3445942.11     10577891.64

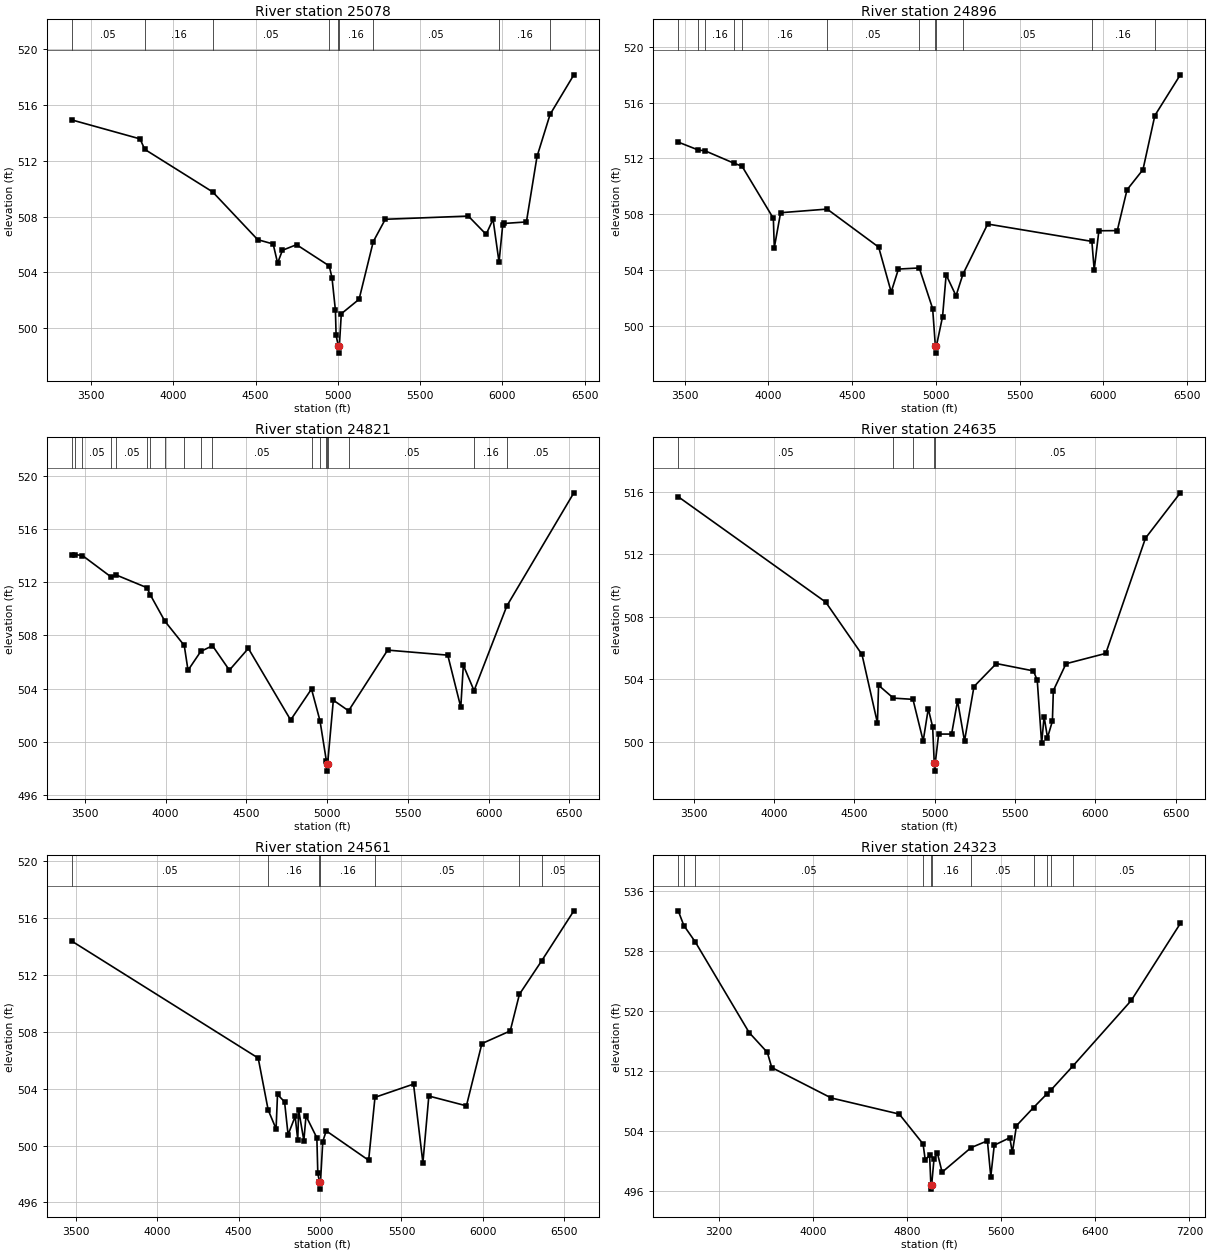
Type RM Length L Ch R = 1 ,25078   ,755,755,755
BEGIN DESCRIPTION:
UNT0040 IN CHRS 28.0
END DESCRIPTION:
XS GIS Cut Line= 3
      3429792.13     10580891.62      3431092.11     10579941.64
       3431892.1     10578741.65
#Sta/Elev= 30
  3382.6  514.93  3797.6  513.57  3826.2  512.82  4239.2  509.77  4512.8  506.35
  4606.9  506.04    4634  504.67  4663.3  505.59  4749.1  505.99  4947.7  504.47
  4964.5  503.63  4985.4  501.29  4989.6  499.49  5003.2  498.72    5006  498.22
  5009.2  498.72  5021.2  501.04  5129.4  502.08  5215.5  506.21  5288.6  507.81
  5793.4  508.04  5901.6  506.73  5943.7  507.81  5980.1  504.74  6002.2  507.37
  6009.8  507.51  6146.5  507.62  6211.1  512.31  6290.3  515.32  6434.9  518.16
#Mann= 9 ,-1 , 0
  3382.6     .05       0  3826.2     .16       0  4239.2     .05       0
  4947.7     .16       0  5003.2     .07       0  5009.2     .16       0
  5215.5     .05       0  5980.1     .16       0  6290.3     .05       0
Bank Sta=5003.2,5009.2
XS Rating Curve= 0 ,0
Exp/Cntr=0.3,0.1

Type RM Length L Ch R = 1 ,24896   ,75,75,75
BEGIN DESCRIPTION:
UNT0040 IN CHRS 28.1
END DESCRIPTION:
XS GIS Cut Line= 3
      3430452.43     10581365.06      3431428.99     10579659.34
      3431962.02     10578775.29
#Sta/Elev= 30
  3461.7  513.17  3582.3   512.6  3621.3  512.55  3796.4  511.65  3842.3  511.45
  4029.6  507.72  4035.3  505.62  4072.8  508.12  4350.7  508.38  4658.4  505.66
  4733.2  502.45  4776.4  504.09  4900.9  504.17  4980.8  501.26    4997  498.58
  4999.8  498.08    5003  498.58  5039.8  500.68  5061.3  503.68  5120.3  502.18
  5161.8  503.73  5309.3  507.31  5931.4  506.07  5945.3  504.03  5973.3  506.83
  6083.1  506.84  6141.4  509.76  6236.5   511.2  6307.5  515.07  6459.5  517.98
#Mann= 12 ,-1 , 0
  3461.7     .16       0  3582.3     .05       0  3621.3     .16       0
  3796.4     .05       0  3842.3     .16       0  4350.7     .05       0
  4900.9     .16       0    4997     .07       0    5003     .16       0
  5161.8     .05       0  5931.4     .16       0  6307.5     .05       0
Bank Sta=4997,5003
XS Rating Curve= 0 ,0
Exp/Cntr=0.3,0.1

Type RM Length L Ch R = 1 ,24821   ,186,186,186
BEGIN DESCRIPTION:
UNT0040 IN CHRS 28.0
END DESCRIPTION:
XS GIS Cut Line= 3
      3430474.13     10581438.84      3431541.84     10579615.93
      3432036.64     10578752.19
#Sta/Elev= 30
  3419.6  514.03  3440.5  514.09  3485.6  514.02  3662.6  512.41  3695.7  512.55
  3884.8   511.6  3905.8  511.06  3995.8  509.08  4115.9  507.25  4139.2  505.38
    4218   506.8  4290.7  507.23  4395.3  505.39  4512.6  507.03  4774.5  501.64
  4903.6  503.97  4956.2  501.58  4995.5  498.57    4997  498.29  4999.8  497.79
    5003  498.29  5038.8  503.13  5133.1  502.33  5374.9   506.9  5747.1  506.52
  5827.7   502.6  5843.5  505.76  5909.9  503.85  6112.7  510.22  6527.6  518.74
#Mann= 19 ,-1 , 0
  3419.6     .05       0  3440.5     .16       0  3485.6     .05       0
  3662.6     .16       0  3695.7     .05       0  3884.8     .16       0
  3905.8     .05       0  3995.8     .16       0  4115.9     .05       0
    4218     .16       0  4290.7     .05       0  4903.6     .16       0
  4956.2     .05       0  4995.5     .16       0    4997     .07       0
    5003     .16       0  5133.1     .05       0  5909.9     .16       0
  6112.7     .05       0
Bank Sta=4997,5003
XS Rating Curve= 0 ,0
Exp/Cntr=0.3,0.1

Type RM Length L Ch R = 1 ,24635   ,74,74,74
BEGIN DESCRIPTION:
UNT0040 IN CHRS 27.0
END DESCRIPTION:
XS GIS Cut Line= 3
      3430569.61     10581612.46      3431550.52     10579906.73
      3432171.19     10578930.14
#Sta/Elev= 30
  3403.6  515.68  4321.5  508.94  4547.2  505.59  4643.4  501.21  4650.4  503.62
  4742.7   502.8  4864.5  502.72  4928.1  500.06  4959.7  502.12    4987  500.96
    4997  498.63  4999.8  498.13    5003  498.63  5024.4   500.5  5104.8   500.5
  5142.2  502.63  5185.3  500.06  5244.3  503.54  5383.4  505.01  5614.3  504.54
    5638  503.94  5665.4   499.9  5680.6  501.62  5701.8  500.27  5732.3  501.33
  5738.2  503.28    5817     505  6064.5  505.66  6311.6  513.03  6528.4  515.93
#Mann= 5 ,-1 , 0
  3403.6     .05       0  4742.7     .16       0  4864.5     .05       0
    4997     .04       0    5003     .05       0
Bank Sta=4997,5003
XS Rating Curve= 0 ,0
Exp/Cntr=0.3,0.1

Type RM Length L Ch R = 1 ,24561   ,1037,1037,1037
BEGIN DESCRIPTION:
UNT0040 IN CHRS 27.1
END DESCRIPTION:
XS GIS Cut Line= 3
       3430665.1     10581603.77      3431389.93     10580319.06
      3432256.96     10578966.48
#Sta/Elev= 30
  3476.5  514.39  4620.8  506.16    4682  502.51  4730.5  501.18  4739.3   503.6
  4782.6  503.08  4804.2  500.77  4847.6  502.05  4863.5  500.41  4869.2   502.5
    4901  500.36  4914.2  502.09  4980.8  500.55  4986.7  498.06    4997  497.44
  4999.8  496.94    5003  497.44  5017.2  500.29  5038.3  501.04  5298.7  498.97
  5337.6   503.4  5574.2  504.33  5631.7  498.79  5668.1  503.49  5898.8   502.8
  5993.8  507.18  6167.7  508.07  6224.2  510.65    6360  512.99  6558.2  516.52
#Mann= 7 ,-1 , 0
  3476.5     .05       0    4682     .16       0    4997     .07       0
    5003     .16       0  5337.6     .05       0  6224.2      .1       0
    6360     .05       0
Bank Sta=4997,5003
XS Rating Curve= 0 ,0
Exp/Cntr=0.3,0.1

Type RM Length L Ch R = 1 ,24323   ,2545,2545,2545
BEGIN DESCRIPTION:
UNT0040 IN CHRS 27.0
END DESCRIPTION:
XS GIS Cut Line= 4
      3431709.63     10582424.83      3431515.18     10580556.74
      3431980.46     10579535.91      3432673.83     10578475.05
#Sta/Elev= 30
  2854.6  533.35  2902.2  531.39  2999.8  529.19  3457.3   517.1  3611.9  514.45
  3649.4  512.43  4154.8  508.37  4732.8  506.22  4935.7  502.23  4953.6  500.12
  4991.1  500.71  5002.1   496.7  5004.9   496.2  5008.1   496.7  5028.2  500.17
  5057.1  501.03  5097.3  498.46  5343.7  501.74  5482.5  502.65  5511.1  497.87
  5540.6  502.06  5672.4  503.06  5694.5   501.1  5729.5  504.67  5874.5  507.09
  5988.7  508.92  6019.6  509.38  6212.2  512.69  6704.8  521.38    7122  531.66
#Mann= 11 ,-1 , 0
  2854.6     .05       0  2902.2      .1       0  2999.8     .05       0
  4935.7     .16       0  5002.1     .07       0  5008.1     .16       0
  5343.7     .05       0  5874.5     .16       0  5988.7     .05       0
  6019.6      .1       0  6212.2     .05       0
Bank Sta=5002.1,5008.1
XS Rating Curve= 0 ,0
Exp/Cntr=0.3,0.1

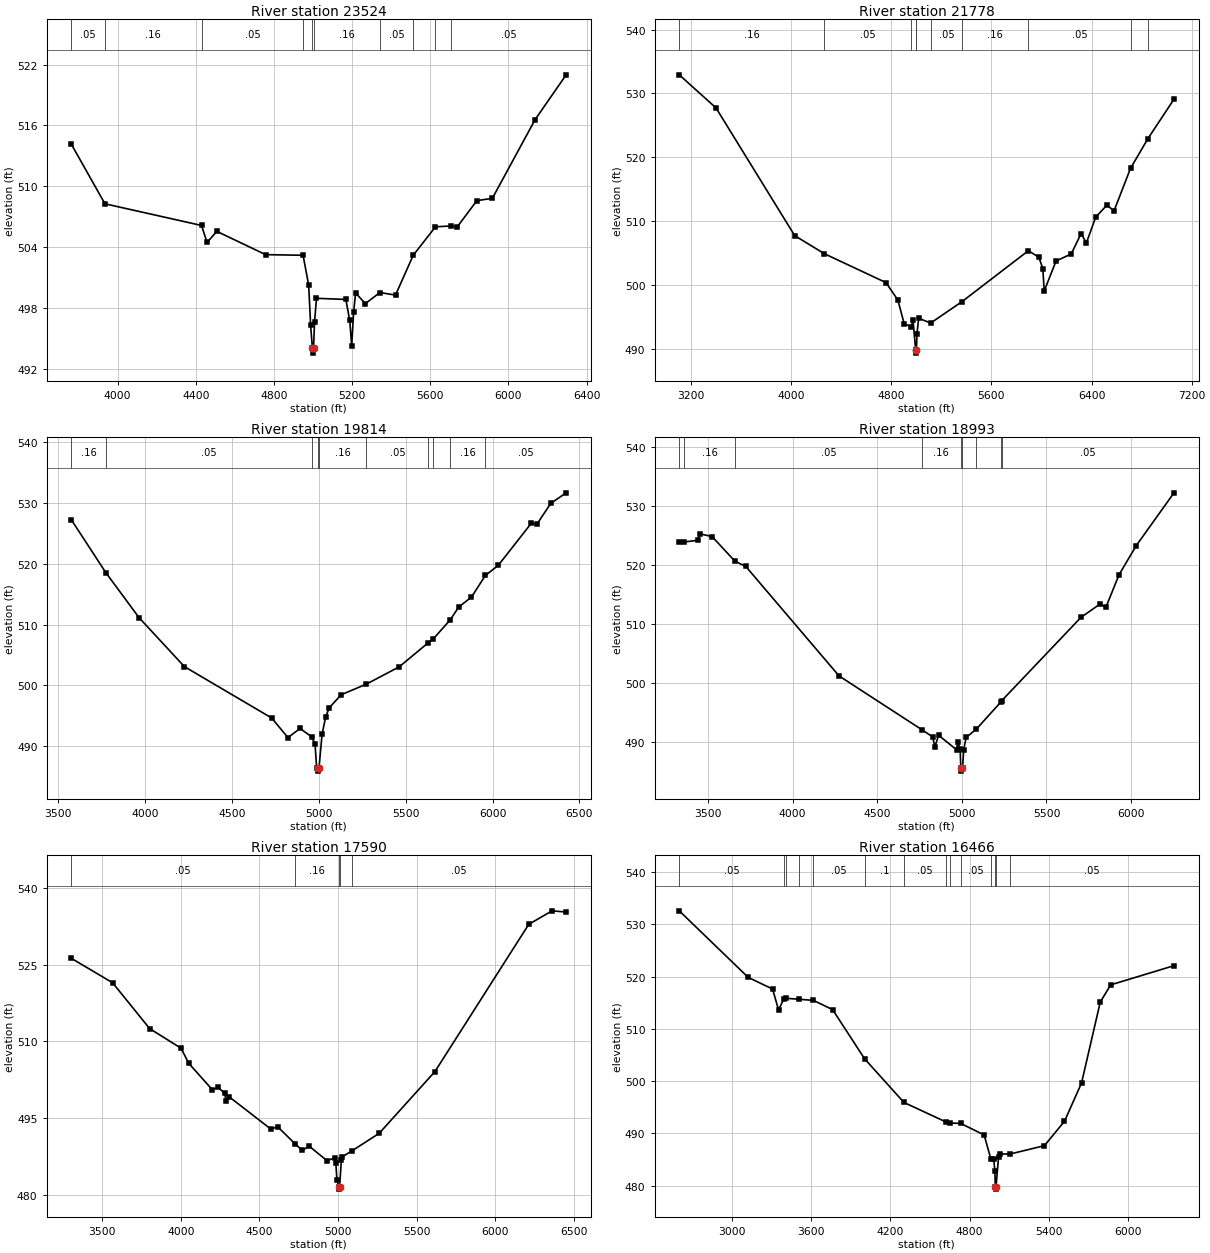
Type RM Length L Ch R = 1 ,23524   ,1746,1746,1746
BEGIN DESCRIPTION:
UNT0040 IN CHRS 27.2
END DESCRIPTION:
XS GIS Cut Line= 4
      3432123.43     10581525.68      3432119.09     10580405.86
      3432136.45     10579893.71      3432604.83      10579126.1
#Sta/Elev= 30
    3764  514.14  3935.6  508.27    4430  506.13    4458  504.45    4508  505.55
    4758  503.25  4949.4  503.19  4978.1  500.23  4988.1  496.29    4997  494.03
  4999.8  493.53    5003  494.03  5008.1  496.61  5018.1  498.94  5168.2  498.83
  5188.2  496.76  5198.2  494.25  5208.2  497.62  5218.2  499.46  5268.3  498.42
  5342.5  499.51  5422.4  499.26  5513.1  503.19  5626.9     506  5705.6  506.08
  5737.8  505.98  5838.5  508.58  5917.9  508.81  6136.7  516.58  6295.5     521
#Mann= 10 ,-1 , 0
    3764     .05       0  3935.6     .16       0    4430     .05       0
  4949.4     .16       0    4997     .07       0    5003     .16       0
  5342.5     .05       0  5513.1     .16       0  5626.9      .1       0
  5705.6     .05       0
Bank Sta=4997,5003
XS Rating Curve= 0 ,0
Exp/Cntr=0.3,0.1

Type RM Length L Ch R = 1 ,21778   ,1964,1964,1964
BEGIN DESCRIPTION:
UNT0040 IN CHRS 26.0
END DESCRIPTION:
XS GIS Cut Line= 3
       3433126.3     10582244.19      3433251.29     10580619.24
      3433987.26     10578418.28
#Sta/Elev= 30
    3108  532.92  3401.4  527.74  4029.8  507.72  4267.6  504.88  4758.8  500.36
  4853.6  497.63  4903.9  493.94  4959.2  493.43  4974.6  494.43  4995.8  489.81
  4998.6  489.31  5001.8  489.81  5006.2  492.38  5019.9  494.78  5115.4  494.02
  5365.8  497.38  5895.7  505.36  5979.4  504.34  6011.1  502.55  6022.2  499.05
  6116.9  503.75    6238  504.85  6316.9  508.05    6359  506.57  6432.8   510.6
  6522.2  512.49  6580.1  511.62  6711.4  518.27  6850.5  522.93  7058.5   529.1
#Mann= 10 ,-1 , 0
    3108     .16       0  4267.6     .05       0  4959.2     .16       0
  4995.8     .07       0  5001.8     .16       0  5115.4     .05       0
  5365.8     .16       0  5895.7     .05       0  6711.4     .16       0
  6850.5     .05       0
Bank Sta=4995.8,5001.8
XS Rating Curve= 0 ,0
Exp/Cntr=0.3,0.1

Type RM Length L Ch R = 1 ,19814   ,821,821,821
BEGIN DESCRIPTION:
UNT0040 IN CHRS 23.0
END DESCRIPTION:
XS GIS Cut Line= 4
      3434654.07     10581480.36      3434577.68     10580397.02
      3434716.57     10579869.24      3434480.64     10578675.71
#Sta/Elev= 30
  3574.8  527.23  3773.3  518.54  3964.5  511.14  4225.1   503.1  4728.4  494.63
  4821.5  491.41  4891.5  492.92  4957.4  491.55  4977.3  490.39  4986.9  486.42
  4994.3   486.4    4997   485.9  5000.3   486.4    5018  491.97  5038.6  494.82
  5059.3  496.32  5128.3  498.47  5273.7  500.22  5462.9  503.07  5630.5  507.05
  5655.8  507.57  5756.6  510.81  5805.5  512.92  5878.1  514.52  5958.1  518.09
  6031.9  519.73  6223.5  526.71  6254.1  526.48  6334.4  529.94  6423.2  531.68
#Mann= 10 ,-1 , 0
  3574.8     .16       0  3773.3     .05       0  4957.4     .16       0
  4994.3     .07       0  5000.3     .16       0  5273.7     .05       0
  5630.5     .16       0  5655.8     .05       0  5756.6     .16       0
  5958.1     .05       0
Bank Sta=4994.3,5000.3
XS Rating Curve= 0 ,0
Exp/Cntr=0.3,0.1

Type RM Length L Ch R = 1 ,18993   ,1403,1403,1403
BEGIN DESCRIPTION:
UNT0040 IN CHRS 22.0
END DESCRIPTION:
XS GIS Cut Line= 4
      3436369.31      10581008.1       3435362.4     10580119.24
      3435029.07      10579799.8      3434806.98     10578703.25
#Sta/Elev= 30
  3329.8  523.94  3357.6  523.92  3438.6  524.19  3452.8  525.29    3524  524.83
  3659.6  520.64  3722.2   519.8  4274.3  501.23  4762.7  492.14  4826.9  490.91
    4841  489.26  4862.4  491.18  4968.4  488.73  4975.6   490.1  4989.8  488.87
  4993.7  485.61  4996.5  485.11  4999.7  485.61  5003.9  485.61  5010.9  488.75
    5025  490.82  5084.4  492.19  5230.2  496.81  5236.5  497.07  5704.1  511.16
  5816.3   513.4  5850.9  512.84  5928.5  518.36  6030.6  523.31  6253.4  532.24
#Mann= 9 ,-1 , 0
  3329.8     .05       0  3357.6     .16       0  3659.6     .05       0
  4762.7     .16       0  4993.7     .07       0  4999.7     .16       0
  5084.4     .05       0  5230.2     .16       0  5236.5     .05       0
Bank Sta=4993.7,4999.7
XS Rating Curve= 0 ,0
Exp/Cntr=0.3,0.1

Type RM Length L Ch R = 1 ,17590   ,1124,1124,1124
BEGIN DESCRIPTION:
UNT0040 IN CHRS 19.0
END DESCRIPTION:
XS GIS Cut Line= 4
      3436924.89     10580785.89       3435987.4     10579542.85
      3435647.13     10579188.69      3434946.41     10578342.27
#Sta/Elev= 30
  3304.1  526.23  3566.2  521.46  3801.4  512.51  4001.2  508.66  4051.2  505.68
  4201.1  500.52  4236.5  501.01  4280.2  499.82  4286.5  498.42  4309.3  499.12
  4573.7  492.82  4615.4  493.32  4725.6     490  4773.5  488.66  4815.2  489.53
  4929.4  486.68  4978.8  487.19    4986  486.19  4992.9  482.92  5004.1   481.6
  5006.8   481.1  5010.1   481.6  5021.2  486.76  5028.4  487.46  5089.1  488.59
  5261.8  492.01  5616.6   504.1  6213.2  532.89  6361.6  535.53    6451  535.29
#Mann= 5 ,-1 , 0
  3304.1     .05       0  4725.6     .16       0  5004.1     .07       0
  5010.1     .16       0  5089.1     .05       0
Bank Sta=5004.1,5010.1
XS Rating Curve= 0 ,0
Exp/Cntr=0.3,0.1

Type RM Length L Ch R = 1 ,16466   ,1037,1037,1037
BEGIN DESCRIPTION:
UNT0040 IN CHRS 18.0
END DESCRIPTION:
XS GIS Cut Line= 4
      3437529.08     10581223.44      3436619.35     10579376.19
      3436230.46     10578667.85      3435522.14     10578140.09
#Sta/Elev= 30
  2598.8  532.57  3121.5  519.84  3306.8   517.6  3351.7   513.6  3392.7   515.8
  3411.1  515.84  3504.2  515.66  3615.7  515.44  3761.6  513.67  4003.8  504.27
    4302  495.92  4619.5   492.2  4653.4  491.99  4732.9   491.9  4910.1   489.7
  4961.7  485.05  4982.5  485.17  4991.6  482.76  4994.3  479.84  4997.1  479.34
  5000.3  479.84  5019.1   485.4  5028.2  486.06  5105.7  486.05  5366.9  487.65
  5519.1  492.31  5648.4  499.64  5790.2  515.11  5869.5  518.41  6349.3  522.08
#Mann= 14 ,-1 , 0
  2598.8     .05       0  3392.7      .1       0  3411.1     .05       0
  3504.2      .1       0  3615.7     .05       0  4003.8      .1       0
    4302     .05       0  4619.5      .1       0  4653.4     .16       0
  4732.9     .05       0  4961.7     .16       0  4994.3     .07       0
  5000.3     .16       0  5105.7     .05       0
Bank Sta=4994.3,5000.3
XS Rating Curve= 0 ,0
Exp/Cntr=0.3,0.1

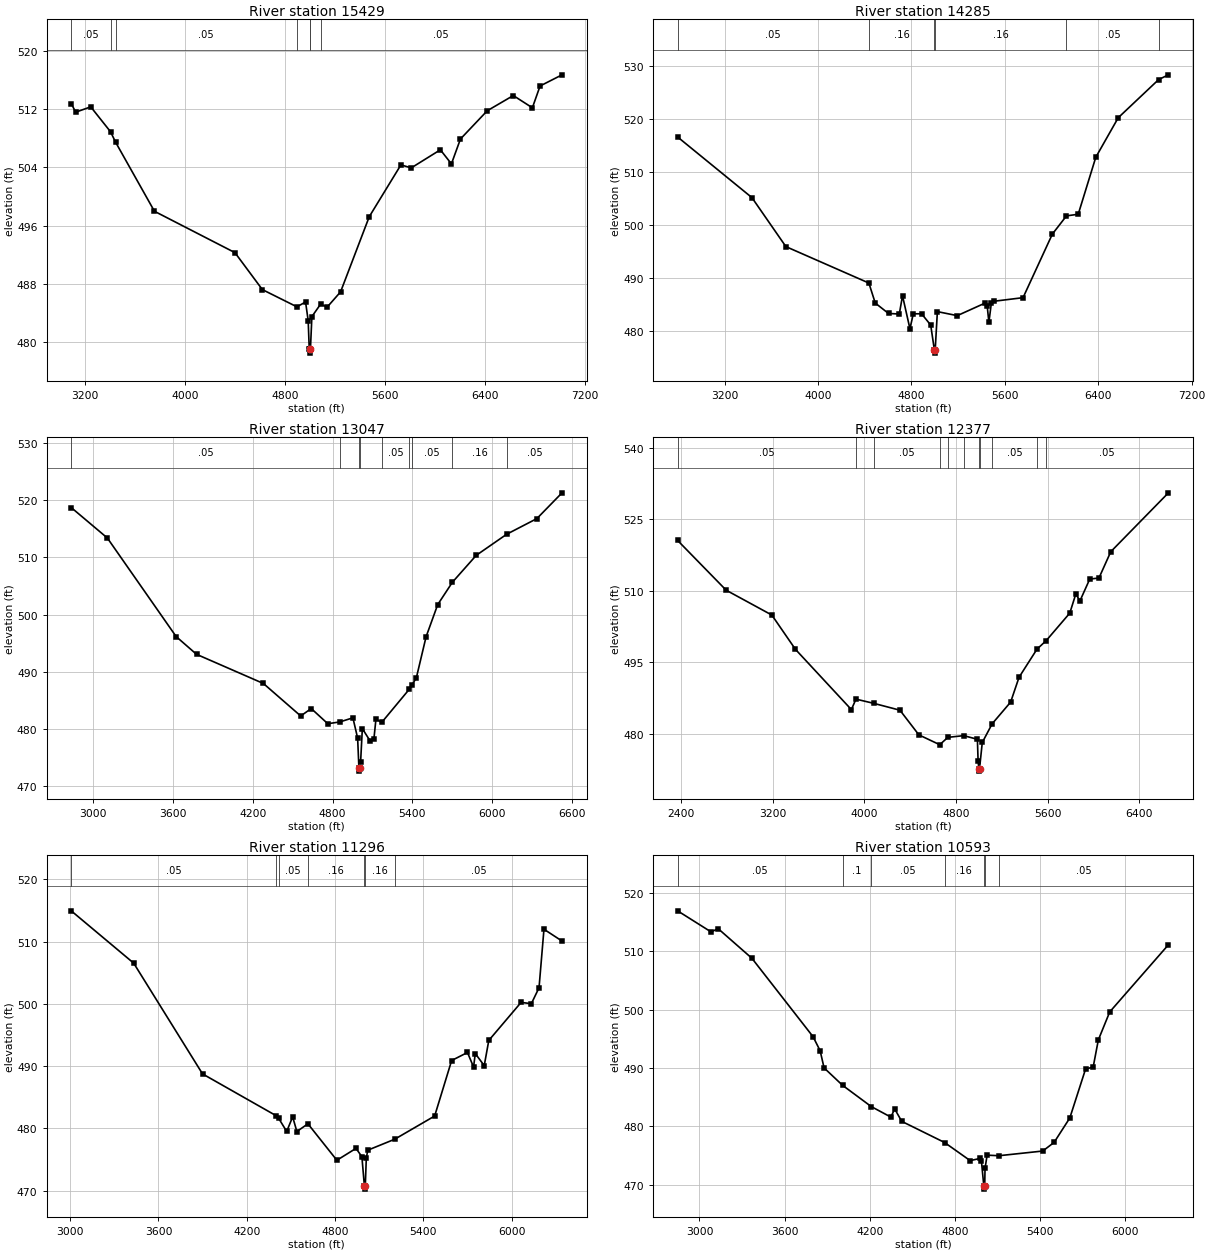
Type RM Length L Ch R = 1 ,15429   ,1144,1144,1144
BEGIN DESCRIPTION:
UNT0040 IN CHRS 16.0
END DESCRIPTION:
XS GIS Cut Line= 4
      3438063.76     10579910.88      3437056.85     10578834.52
      3436529.07     10578077.58      3435112.43      10577501.2
#Sta/Elev= 30
  3088.8  512.74  3124.9  511.56  3245.1  512.29  3403.1  508.88  3444.6  507.42
  3754.6  497.97  4398.4   492.3  4617.9  487.23  4894.1  484.87  4963.4  485.53
  4984.3  482.99  4992.9  479.07  4996.2  479.02  4998.9  478.52  5002.2  479.02
    5014  483.53  5083.4  485.23  5136.2  484.83  5243.5  486.92  5472.9  497.23
    5726  504.33  5808.9  503.92  6041.7   506.4  6130.1  504.47  6202.3  507.88
  6416.4  511.75  6625.1  513.84  6777.7  512.16  6839.2  515.15  7014.9  516.68
#Mann= 7 ,-1 , 0
  3088.8     .05       0  3403.1     .16       0  3444.6     .05       0
  4894.1     .16       0  4996.2     .07       0  5002.2     .16       0
  5083.4     .05       0
Bank Sta=4996.2,5002.2
XS Rating Curve= 0 ,0
Exp/Cntr=0.3,0.1

Type RM Length L Ch R = 1 ,14285   ,1238,1238,1238
BEGIN DESCRIPTION:
UNT0040 IN CHRS 13.0
END DESCRIPTION:
XS GIS Cut Line= 4
      3438911.02     10579820.63      3437598.51     10578320.63
       3437237.4     10577897.02      3436259.33     10576565.17
#Sta/Elev= 30
  2798.2  516.67  3434.7  505.23  3725.4  495.99  4435.9  489.12  4490.4  485.35
    4604  483.38  4696.4  483.28  4723.9  486.72  4787.4   480.5  4816.3  483.32
  4887.3  483.32  4965.3  481.19  4997.4   476.4  5000.1   475.9  5003.4   476.4
  5022.4  483.73  5192.6  482.97  5427.9  485.31  5448.8  484.82  5463.4   481.7
  5484.3  485.32  5505.2  485.68  5755.9  486.36  6006.7  498.35  6127.8  501.79
  6228.2  502.09  6378.6  512.84  6570.8   520.3  6917.1   527.5  7000.4  528.39
#Mann= 6 ,-1 , 0
  2798.2     .05       0  4435.9     .16       0  4997.4     .07       0
  5003.4     .16       0  6127.8     .05       0  6917.1     .16       0
Bank Sta=4997.4,5003.4
XS Rating Curve= 0 ,0
Exp/Cntr=0.3,0.1

Type RM Length L Ch R = 1 ,13047   ,670,670,670
BEGIN DESCRIPTION:
UNT0040 IN CHRS 11.0
END DESCRIPTION:
XS GIS Cut Line= 3
      3439112.42     10579730.39      3438320.74     10578265.08
      3437244.37     10576549.84
#Sta/Elev= 30
  2835.1   518.7  3106.5  513.39  3624.1  496.17  3777.3  493.07  4279.8  487.98
  4560.8   482.3  4639.8   483.6  4764.4  480.95    4855  481.26  4953.2  481.98
  4988.7  478.43  4998.5  473.17  5001.2  472.67  5004.5  473.17  5010.9  474.18
  5024.1   480.1  5083.1  477.92  5111.1  478.29  5126.4  481.76  5169.6  481.17
  5378.2     487  5395.4  487.63  5430.4  488.99  5503.4  496.13  5590.8  501.75
  5701.4  505.66  5880.4  510.35  6109.6  514.04  6336.4  516.77  6525.6  521.27
#Mann= 9 ,-1 , 0
  2835.1     .05       0    4855     .16       0  4998.5     .07       0
  5004.5     .16       0  5169.6     .05       0  5378.2     .16       0
  5395.4     .05       0  5701.4     .16       0  6109.6     .05       0
Bank Sta=4998.5,5004.5
XS Rating Curve= 0 ,0
Exp/Cntr=0.3,0.1

Type RM Length L Ch R = 1 ,12377   ,1081,1081,1081
BEGIN DESCRIPTION:
UNT0040 IN CHRS 10.0
END DESCRIPTION:
XS GIS Cut Line= 3
      3439917.95     10579765.06      3438813.79      10577924.8
      3437695.75     10576105.37
#Sta/Elev= 30
  2370.8  520.58  2794.4  510.15  3192.9  504.94  3398.9  497.75  3886.8  485.12
  3926.8  487.31  4080.1  486.44  4310.5  484.99  4475.7  479.82  4657.6  477.76
  4728.4   479.3    4867  479.66  4986.2  478.89    4992  474.44  4998.6  472.72
  5001.3  472.22  5004.6  472.72  5028.7  478.23  5115.1  482.15  5276.1  486.69
  5349.5   491.9  5505.9  497.79  5585.7  499.56  5792.2  505.35  5844.3  509.34
    5881  507.92  5966.2  512.48  6046.4   512.7  6149.7  518.22  6652.4  530.56
#Mann= 11 ,-1 , 0
  2370.8     .05       0  3926.8     .16       0  4080.1     .05       0
  4657.6     .16       0  4728.4     .05       0    4867     .16       0
  4998.6     .07       0  5004.6     .16       0  5115.1     .05       0
  5505.9     .16       0  5585.7     .05       0
Bank Sta=4998.6,5004.6
XS Rating Curve= 0 ,0
Exp/Cntr=0.3,0.1

Type RM Length L Ch R = 1 ,11296   ,703,703,703
BEGIN DESCRIPTION:
UNT0040 IN CHRS 8.0
END DESCRIPTION:
XS GIS Cut Line= 4
      3440133.24     10579223.41      3439473.51     10577778.96
      3439473.51     10577195.63      3439174.89     10576070.59
#Sta/Elev= 30
    3007  514.96  3431.6  506.55  3899.4  488.75  4398.3  482.05    4417   481.6
  4471.3   479.5  4511.8  481.85  4540.4  479.49  4615.5  480.73  4812.3  474.87
  4942.3  476.78  4982.3  475.44  4999.3  470.73    5002  470.23  5005.3  470.73
  5012.3  475.22  5022.3  476.49  5205.3  478.25  5476.7  481.98  5592.1   490.9
  5699.7  492.19  5741.1  489.86  5752.8  492.02  5813.6  490.08  5844.6  494.13
  6063.9  500.24  6133.9  500.04    6186   502.6  6219.5     512  6342.3   510.1
#Mann= 7 ,-1 , 0
    3007     .05       0  4398.3     .16       0    4417     .05       0
  4615.5     .16       0  4999.3     .07       0  5005.3     .16       0
  5205.3     .05       0
Bank Sta=4999.3,5005.3
XS Rating Curve= 0 ,0
Exp/Cntr=0.3,0.1

Type RM Length L Ch R = 1 ,10593   ,1836,1836,1836
BEGIN DESCRIPTION:
UNT0040 IN CHRS 6.0
END DESCRIPTION:
XS GIS Cut Line= 4
      3440355.45     10579410.86      3439980.46     10577647.02
       3439862.4     10576369.24      3439696.61     10576037.66
#Sta/Elev= 30
  2846.1   516.9  3082.1  513.29  3131.7  513.85  3369.5  508.78  3800.5  495.35
  3850.2  492.95  3877.9  490.02    4008  487.04  4210.2   483.4  4348.2   481.6
  4375.3  482.99  4424.9  480.87  4726.8  477.25    4907  474.15  4976.1  474.52
  4986.2  474.07  5003.3  469.77    5006  469.27  5009.3  469.77  5011.6  472.82
  5026.3  475.08  5109.9  474.99    5418  475.79  5498.3  477.27  5608.8  481.45
  5719.3  489.79  5773.6  490.19  5809.7  494.81    5890   499.6  6303.3  511.09
#Mann= 7 ,-1 , 0
  2846.1     .05       0    4008      .1       0  4210.2     .05       0
  4726.8     .16       0  5003.3     .07       0  5009.3     .16       0
  5109.9     .05       0
Bank Sta=5003.3,5009.3
XS Rating Curve= 0 ,0
Exp/Cntr=0.3,0.1

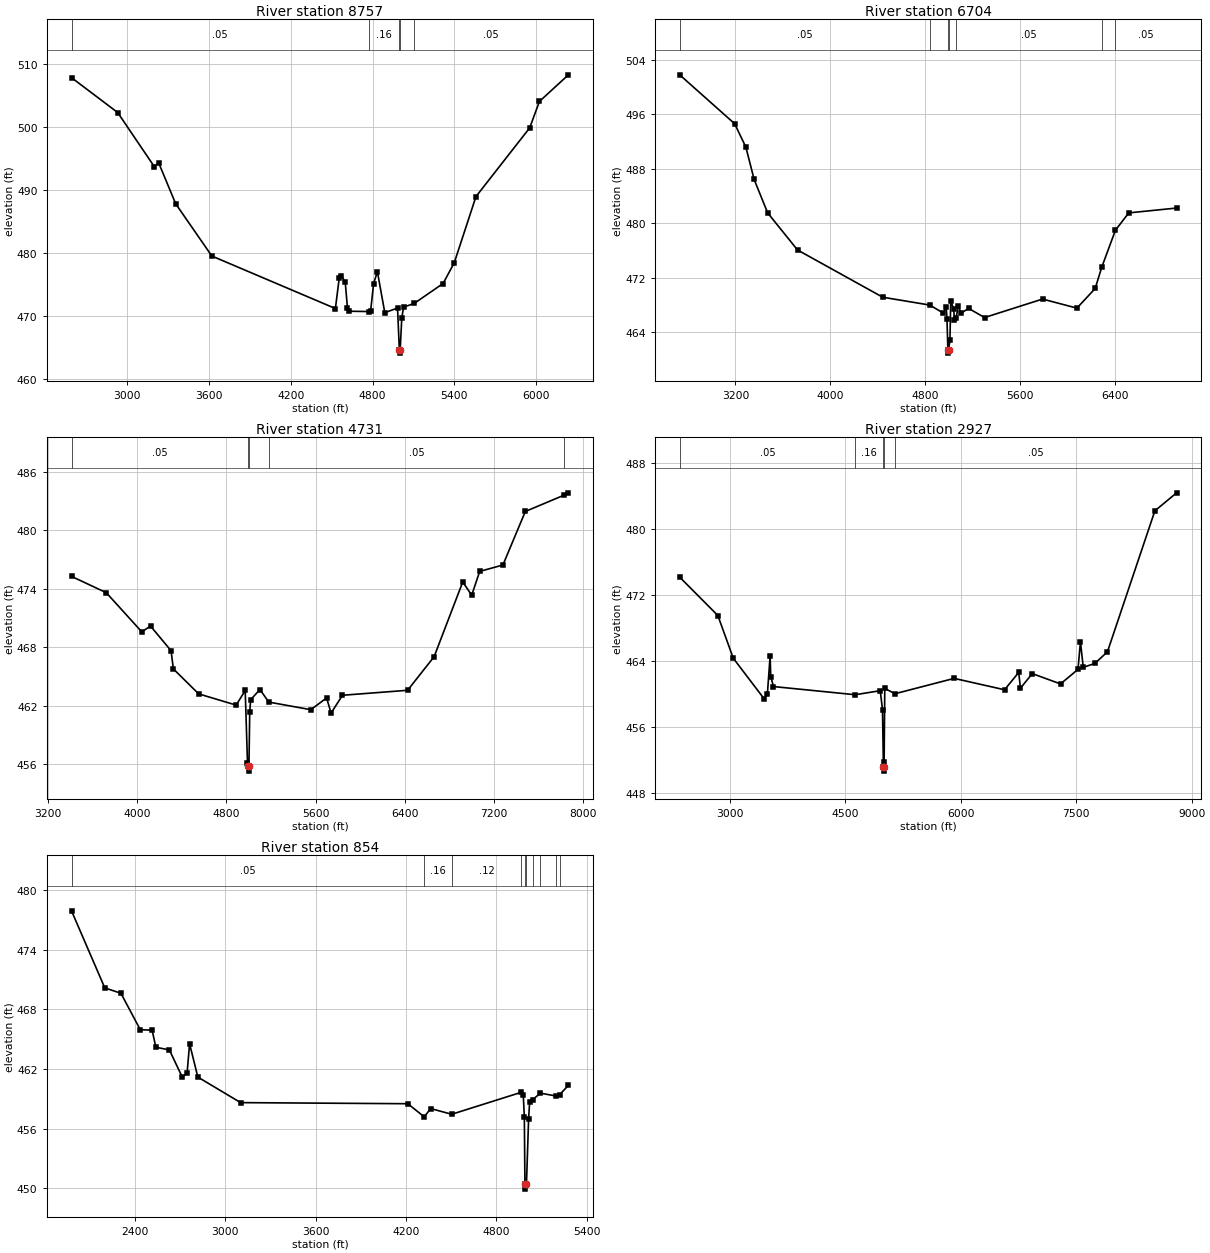
Type RM Length L Ch R = 1 ,8757    ,2053,2053,2053
BEGIN DESCRIPTION:
UNT0040 IN CHRS 5.0
END DESCRIPTION:
XS GIS Cut Line= 3
      3441216.57     10579049.76      3441341.57     10577160.91
      3440515.18     10575612.29
#Sta/Elev= 30
  2589.5  507.85  2928.4  502.32  3198.6  493.69    3229  494.36  3354.5  487.83
  3619.9  479.54    4527  471.21  4555.5  476.12  4571.8  476.42  4599.4  475.36
  4615.7  471.24    4629  470.78  4770.8  470.73  4785.7  470.84  4807.6  475.17
  4835.3  477.07  4889.7  470.55  4983.3  471.29  4996.6  464.63  4999.3  464.13
  5002.6  464.63  5014.4  469.67  5027.2  471.43  5104.9  472.01  5317.6  475.18
  5399.7  478.47  5559.1  488.98  5953.5  499.88  6025.1  504.08  6237.8   508.3
#Mann= 5 ,-1 , 0
  2589.5     .05       0  4770.8     .16       0  4996.6     .07       0
  5002.6     .16       0  5104.9     .05       0
Bank Sta=4996.6,5002.6
XS Rating Curve= 0 ,0
Exp/Cntr=0.3,0.1

Type RM Length L Ch R = 1 ,6704    ,1973,1973,1973
BEGIN DESCRIPTION:
UNT0040 IN CHRS 4.0
END DESCRIPTION:
XS GIS Cut Line= 4
      3441738.91     10578736.19      3442596.13     10576197.09
      3442791.44     10575470.09      3442389.99     10574829.94
#Sta/Elev= 30
  2730.3  501.77  3193.9  494.59  3288.3  491.15  3357.8  486.42  3471.8  481.52
  3723.5  476.08  4441.9  469.15  4838.4     468  4951.6  466.83  4976.8  467.71
  4983.2  465.94  4990.8  461.45  4993.5  460.95  4996.8  461.45  5008.2  462.82
  5014.9   468.6  5039.7  467.43  5046.5  465.83  5061.5  466.17  5078.2   467.9
  5102.6  466.83  5165.5  467.51  5299.9  466.17  5788.6  468.88  6078.5  467.55
  6232.7  470.44    6287  473.51  6403.2  478.98  6515.6  481.52  6918.6  482.23
#Mann= 7 ,-1 , 0
  2730.3     .05       0  4838.4     .16       0  4990.8     .07       0
  4996.8     .16       0  5061.5     .05       0    6287      .1       0
  6403.2     .05       0
Bank Sta=4990.8,4996.8
XS Rating Curve= 0 ,0
Exp/Cntr=0.3,0.1

Type RM Length L Ch R = 1 ,4731    ,1804,1804,1804
BEGIN DESCRIPTION:
UNT0040 IN CHRS 3.0
END DESCRIPTION:
XS GIS Cut Line= 4
      3442978.96      10578047.4      3443742.87     10577170.64
      3443985.93     10575729.66      3442485.67     10574680.35
#Sta/Elev= 30
  3411.3  475.29  3722.8  473.62  4041.7   469.6  4119.6   470.2  4303.8  467.67
  4324.6   465.8  4551.6  463.24  4887.5  462.09  4968.7  463.59  4988.9   456.2
  4996.1  455.82  4998.8  455.32  5002.1  455.82  5009.2  461.41  5017.4  462.64
  5100.5  463.69  5180.1   462.4  5556.7  461.62  5698.8  462.83  5738.2  461.27
  5840.8   463.1  6424.6  463.61  6662.5  467.06    6919  474.72  6999.3  473.36
  7070.8   475.8  7279.2  476.46  7480.1  481.95  7827.3  483.62  7866.3  483.86
#Mann= 5 ,-1 , 0
  3411.3     .05       0  4996.1     .07       0  5002.1     .05       0
  5180.1     .05       0  7827.3      .1       0
Bank Sta=4996.1,5002.1
XS Rating Curve= 0 ,0
Exp/Cntr=0.3,0.1

Type RM Length L Ch R = 1 ,2927    ,2073,2073,2073
BEGIN DESCRIPTION:
UNT0040 IN CHRS 2.0
END DESCRIPTION:
XS GIS Cut Line= 4
       3443048.4     10578090.79      3445270.65     10576450.15
       3445426.9     10575799.11      3442796.73     10574314.76
#Sta/Elev= 30
  2351.9   474.2  2847.3  469.55  3047.8  464.37  3448.7  459.45  3490.4  460.01
  3525.9  464.64  3534.3  462.15  3569.8  460.94  4630.6  459.95  4956.1  460.44
  4985.4  458.11    4997  451.19  4999.8  450.69    5003  451.19  5006.3   451.8
  5014.7  460.72  5146.9  460.07    5916  461.93    6570  460.55  6753.7  462.65
  6776.7  460.74  6929.9  462.51  7296.7  461.26  7523.5  463.02  7555.3  466.36
    7592  463.27  7744.5  463.75  7906.2  465.16    8522  482.24  8803.8  484.42
#Mann= 5 ,-1 , 0
  2351.9     .05       0  4630.6     .16       0    4997     .07       0
    5003     .16       0  5146.9     .05       0
Bank Sta=4997,5003
XS Rating Curve= 0 ,0
Exp/Cntr=0.3,0.1

Type RM Length L Ch R = 1 ,854     ,0,0,0
BEGIN DESCRIPTION:
UNT0040 IN CHRS 1.0
END DESCRIPTION:
XS GIS Cut Line= 3
      3442975.93     10578627.63      3445634.32     10577607.68
      3445958.48     10577294.32
#Sta/Elev= 30
  1979.1  477.91  2199.9  470.16    2307  469.62  2435.6  465.95  2514.1  465.91
  2538.8  464.19  2628.8  463.92    2714  461.19  2746.2  461.58  2762.9  464.54
  2817.6  461.19  3101.8  458.62  4211.7  458.51  4320.1  457.19  4363.5  458.02
  4502.7  457.45    4965  459.66  4977.6  459.38  4984.8  457.22  4988.7  450.42
  4991.5  449.92  4994.7  450.42  4998.9  450.44    5013  456.94    5020  458.72
  5039.2  458.91  5091.6  459.57  5197.9  459.28  5219.2  459.42  5277.3  460.36
#Mann= 10 ,-1 , 0
  1979.1     .05       0  4320.1     .16       0  4502.7     .12       0
    4965     .16       0  4988.7     .07       0  4994.7     .16       0
  5039.2     .12       0  5091.6     .16       0  5197.9     .12       0
  5219.2     .16       0
Bank Sta=4988.7,4994.7
XS Rating Curve= 0 ,0
Exp/Cntr=0.3,0.1

Chan Stop Cuts=-1
Use User Specified Reach Order=0
Composite Channel Slope=5