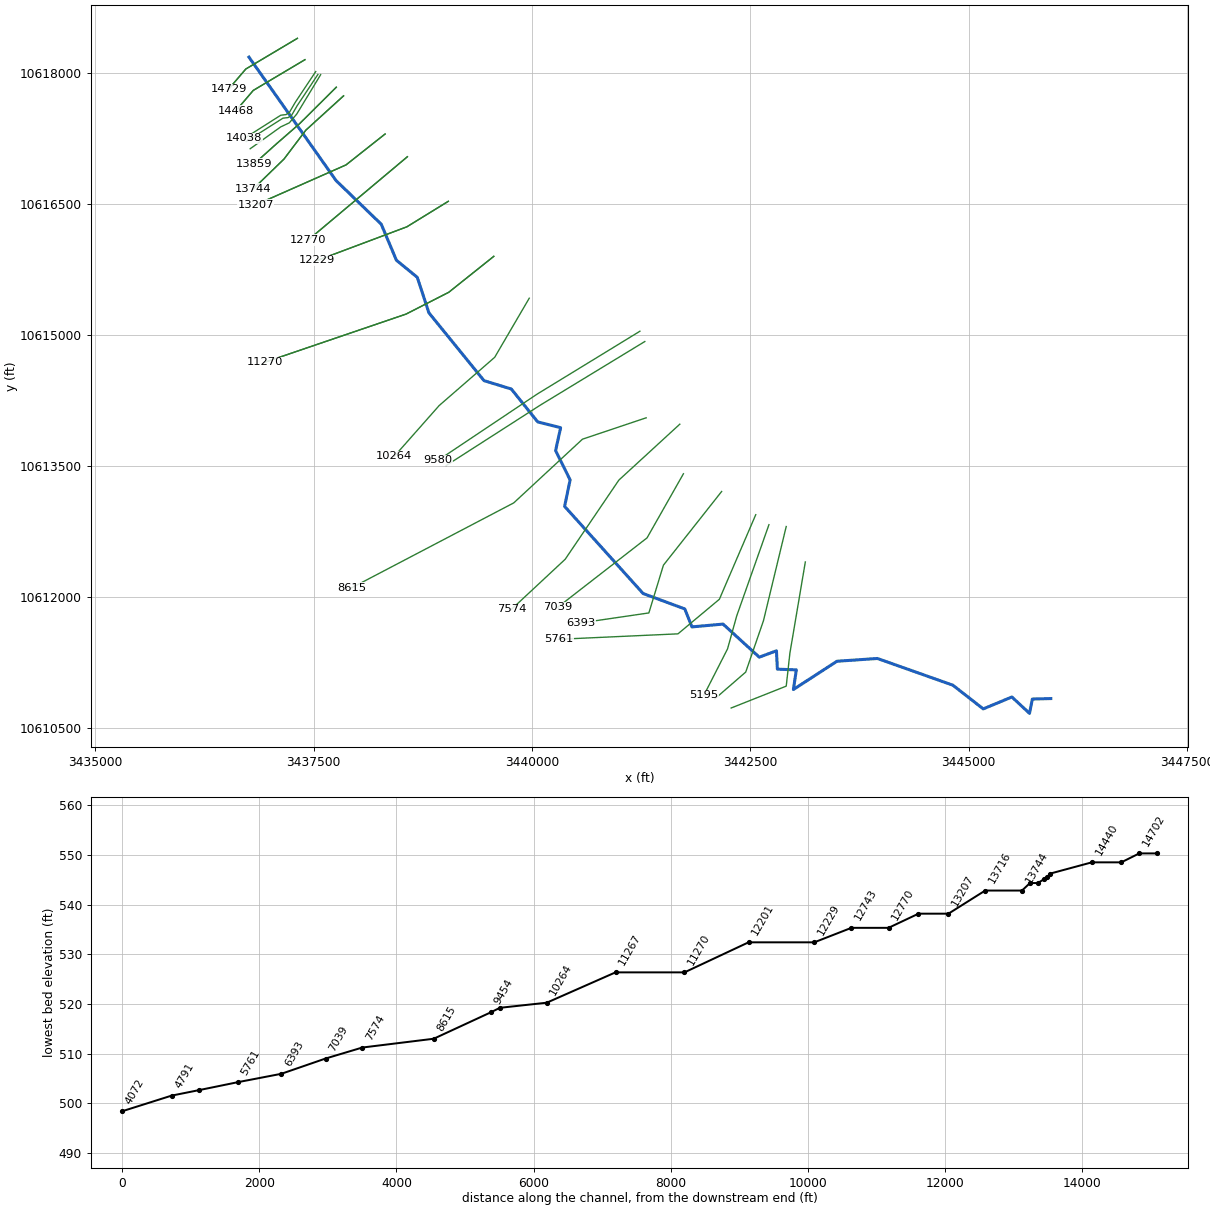
--- UNT0044 IN CHRS.prj (project) ---

Proj Title=UNT0044 IN CHRS Base Level Engineering
Current Plan=p01
Default Exp/Contr=0.3,0.1
English Units
Geom File=g01
Flow File=f01
Plan File=p01
Y Axis Title=Elevation
X Axis Title(PF)=Main Channel Distance
X Axis Title(XS)=Station
BEGIN DESCRIPTION:
UNT0044 IN CHRS
END DESCRIPTION:
DSS Export Rating Curves= 0
DSS Export Rating Curve Sorted= 0
DSS Export Volume Flow Curves= 0
DXF OffsetX= 0
DXF OffsetY= 0
DXF ScaleX= 1
DXF ScaleY= 10

--- UNT0044 IN CHRS.p01 (plan) ---

Plan Title=Multiple Run
Short Identifier=Multiple
Geom File=g01
Flow File=f01
Subcritical Flow
K Sum by GR= 0
Std Step Tol= 0.01
Critical Tol= 0.01
Num of Std Step Trials= 20
Max Error Tol= 0.3
Flow Tol Ratio= 0.001
Split Flow NTrial= 30
Split Flow Tol= 0.02
Split Flow Ratio= 0.02
Log Output Level= 0
Friction Slope Method= 1
Unsteady Friction Slope Method= 2
Unsteady Bridges Friction Slope Method= 1
Parabolic Critical Depth
Global Vel Dist=  1 , 1 , 1
Global Log Level= 0
CheckData=True
Encroach Param= -1, 0, 0, 0
BEGIN DESCRIPTION:
Multiple Run
END DESCRIPTION:

--- UNT0044 IN CHRS.f01 (steady flow) ---

Flow Title=Multiple
Program Version=4.10
Number of Profiles= 7
Profile Names=10-year,25-year,50-year,1pct_min,100-year,1pct_plu,500-year
River Rch & RM=UNT0044 IN CHRS,Reach-1         ,14729
     300     367     414     340     460     622     566
River Rch & RM=UNT0044 IN CHRS,Reach-1         ,5195
     419     521     594     493     667     902     838
Boundary for River Rch & Prof#=UNT0044 IN CHRS,Reach-1         , 1
Up Type= 0
Dn Type= 3
Dn Slope=0.005
Boundary for River Rch & Prof#=UNT0044 IN CHRS,Reach-1         , 2
Up Type= 0
Dn Type= 3
Dn Slope=0.005
Boundary for River Rch & Prof#=UNT0044 IN CHRS,Reach-1         , 3
Up Type= 0
Dn Type= 3
Dn Slope=0.005
Boundary for River Rch & Prof#=UNT0044 IN CHRS,Reach-1         , 4
Up Type= 0
Dn Type= 3
Dn Slope=0.005
Boundary for River Rch & Prof#=UNT0044 IN CHRS,Reach-1         , 5
Up Type= 0
Dn Type= 3
Dn Slope=0.005
Boundary for River Rch & Prof#=UNT0044 IN CHRS,Reach-1         , 6
Up Type= 0
Dn Type= 3
Dn Slope=0.005
Boundary for River Rch & Prof#=UNT0044 IN CHRS,Reach-1         , 7
Up Type= 0
Dn Type= 3
Dn Slope=0.005
DSS Import GetInterval= 0
DSS Import GetPeak= 0
DSS Import FillOption= 0

--- UNT0044 IN CHRS.g01 (geometry) ---

Geom Title=Existing Conditions
Program Version=4.10

River Reach=UNT0044 IN CHRS ,Reach-1
Reach XY= 30
      3436759.49     10618177.25       3437757.1     10616763.62
      3438274.68      10616263.4      3438448.29     10615851.08
      3438687.39     10615655.23      3438820.47     10615248.86
      3439451.34     10614472.34      3439764.71     10614376.09
      3440066.47     10613999.69      3440328.85     10613933.53
      3440271.34     10613671.32      3440437.55     10613335.22
      3440374.42     10613032.62      3441273.61     10612034.32
      3441750.72     10611857.93       3441832.3     10611652.28
      3442188.81     10611684.39      3442603.75     10611305.52
      3442800.45     10611378.61      3442810.93     10611168.16
       3443028.2     10611160.06      3442994.21     10610935.19
      3443493.32     10611258.86      3443956.82     10611290.58
      3444820.99     10610984.59       3445168.3     10610713.22
      3445496.65     10610849.56      3445698.26     10610661.93
      3445730.91     10610825.95      3445942.11     10610831.64

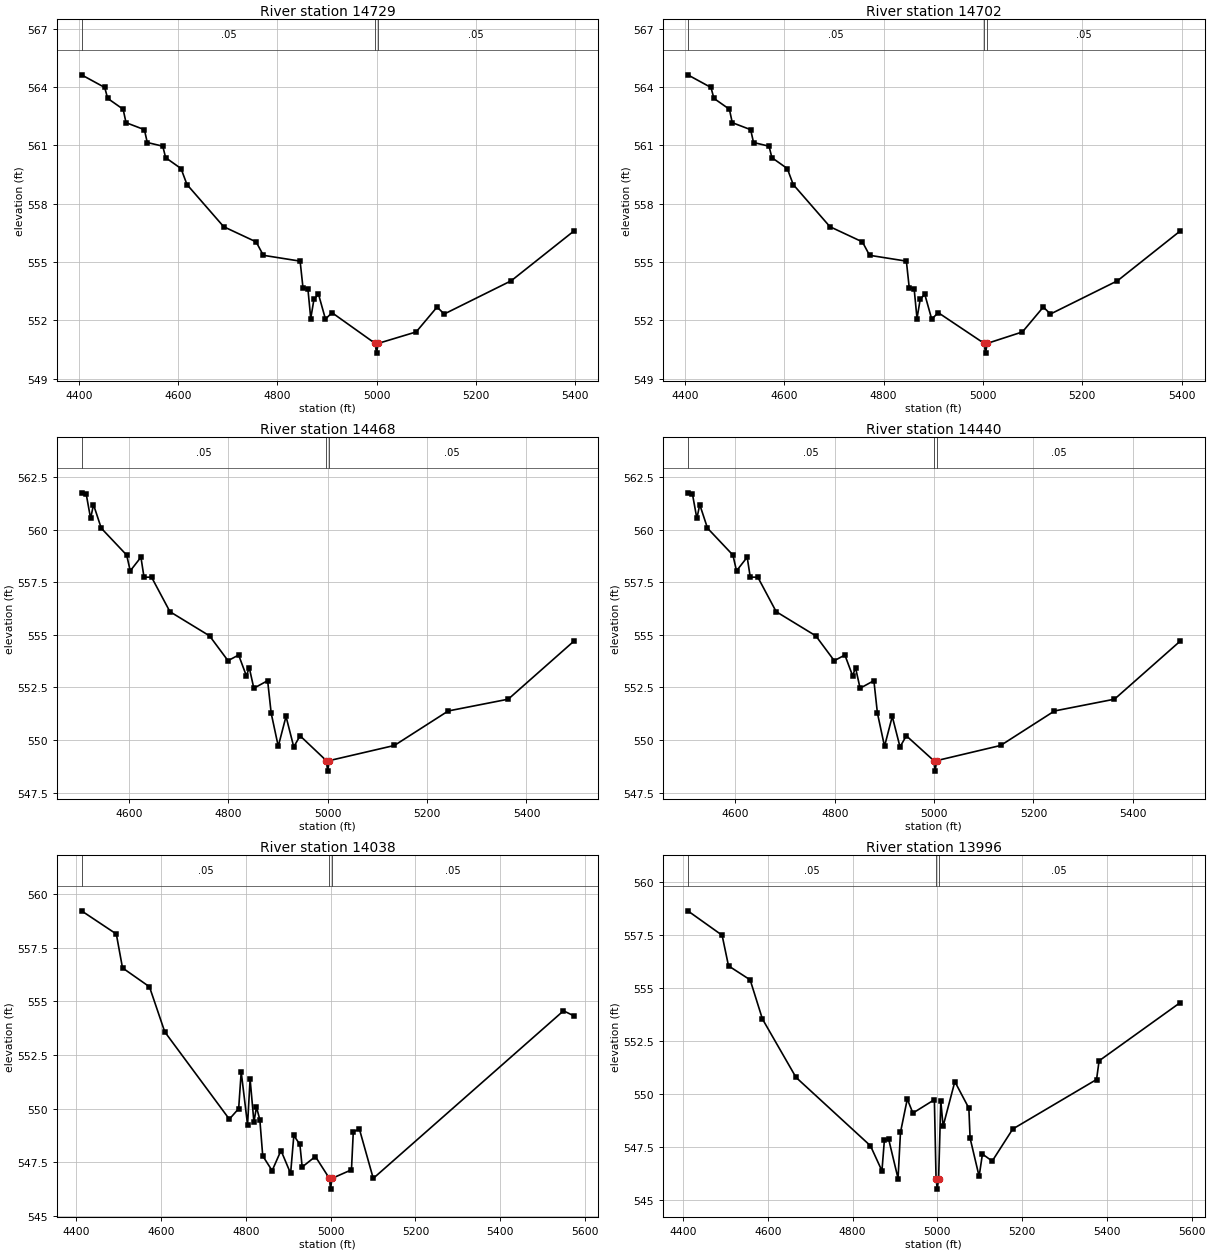
Type RM Length L Ch R = 1 ,14729   ,261,261,261
BEGIN DESCRIPTION:
UNT00685 IN CHRS 20.0
END DESCRIPTION:
XS GIS Cut Line= 3
      3437314.31     10618392.29       3436723.2     10618040.75
      3436526.21     10617810.06
#Sta/Elev= 30
  4405.7  564.63  4452.4  563.98  4458.3  563.42  4489.5  562.86  4495.3  562.17
  4532.3  561.81  4538.1  561.15  4569.3  560.96  4575.1  560.37  4606.1  559.81
    4618  558.99    4692  556.82  4757.3  556.04  4771.8  555.35  4845.9  555.05
  4851.7  553.67  4861.5  553.64  4867.3   552.1  4873.7  553.08  4882.9  553.35
  4896.9  552.07  4910.1   552.4    4997  550.82  4999.8  550.32    5003  550.82
  5079.6  551.41  5121.7  552.69    5136  552.33    5271  554.04  5396.8  556.59
#Mann= 3 ,-1 , 0
  4405.7     .05       0    4997    .035       0    5003     .05       0
Bank Sta=4997,5003
XS Rating Curve= 0 ,0
Exp/Cntr=0.3,0.1

Type RM Length L Ch R = 1 ,14702   ,262,262,262
BEGIN DESCRIPTION:
UNT00685 IN CHRS 20.0
END DESCRIPTION:
XS GIS Cut Line= 3
      3437314.31     10618392.29       3436723.2     10618040.75
      3436526.21     10617810.06
#Sta/Elev= 30
  4405.7  564.63  4452.4  563.98  4458.3  563.42  4489.5  562.86  4495.3  562.17
  4532.3  561.81  4538.1  561.15  4569.3  560.96  4575.1  560.37  4606.1  559.81
    4618  558.99    4692  556.82  4757.3  556.04  4771.8  555.35  4845.9  555.05
  4851.7  553.67  4861.5  553.64  4867.3   552.1  4873.7  553.08  4882.9  553.35
  4896.9  552.07  4910.1   552.4  5002.6  550.82  5005.3  550.32  5008.6  550.82
  5079.6  551.41  5121.7  552.69    5136  552.33    5271  554.04  5396.8  556.59
#Mann= 3 ,-1 , 0
  4405.7     .05       0  5002.6    .035       0  5008.6     .05       0
Bank Sta=5002.6,5008.6
XS Rating Curve= 0 ,0
Exp/Cntr=0.3,0.1

Type RM Length L Ch R = 1 ,14468   ,430,430,430
BEGIN DESCRIPTION:
UNT00685 IN CHRS 20.1
END DESCRIPTION:
XS GIS Cut Line= 3
      3437400.27     10618147.51      3436809.13     10617795.96
      3436612.29     10617565.44
#Sta/Elev= 30
  4504.2  561.75  4513.7  561.68  4522.5  560.53  4528.3  561.19  4543.9  560.07
  4595.1  558.79  4602.3  558.04  4623.8  558.69    4630  557.74  4645.2  557.74
  4682.2   556.1    4762  554.95  4799.1  553.77  4820.5  554.04  4836.1  553.05
  4841.9  553.44  4851.1  552.46  4878.9  552.82    4886  551.28  4900.3   549.7
  4915.9  551.12  4931.5  549.67  4944.2   550.2    4997  549.02  4999.8  548.52
    5003  549.02  5134.1  549.74  5242.5  551.38  5363.3  551.94  5495.1  554.69
#Mann= 3 ,-1 , 0
  4504.2     .05       0    4997    .035       0    5003     .05       0
Bank Sta=4997,5003
XS Rating Curve= 0 ,0
Exp/Cntr=0.3,0.1

Type RM Length L Ch R = 1 ,14440   ,608,608,608
BEGIN DESCRIPTION:
UNT00685 IN CHRS 20.1
END DESCRIPTION:
XS GIS Cut Line= 3
      3437400.27     10618147.51      3436809.13     10617795.96
      3436612.29     10617565.44
#Sta/Elev= 30
  4504.2  561.75  4513.7  561.68  4522.5  560.53  4528.3  561.19  4543.9  560.07
  4595.1  558.79  4602.3  558.04  4623.8  558.69    4630  557.74  4645.2  557.74
  4682.2   556.1    4762  554.95  4799.1  553.77  4820.5  554.04  4836.1  553.05
  4841.9  553.44  4851.1  552.46  4878.9  552.82    4886  551.28  4900.3   549.7
  4915.9  551.12  4931.5  549.67  4944.2   550.2  4999.4  549.02  5002.1  548.52
  5005.4  549.02  5134.1  549.74  5242.5  551.38  5363.3  551.94  5495.1  554.69
#Mann= 3 ,-1 , 0
  4504.2     .05       0  4999.4    .035       0  5005.4     .05       0
Bank Sta=4999.4,5005.4
XS Rating Curve= 0 ,0
Exp/Cntr=0.3,0.1

Type RM Length L Ch R = 1 ,14038   ,42,42,42
BEGIN DESCRIPTION:
UNT00685 IN CHRS 20.8
END DESCRIPTION:
XS GIS Cut Line= 6
      3437524.45     10618012.18      3437287.45     10617655.38
      3437222.35      10617543.4      3437183.29     10617518.66
      3437124.69     10617512.15      3436704.16     10617245.25
#Sta/Elev= 30
  4412.1  559.22  4494.2  558.14  4508.8  556.56  4572.4  555.68  4608.5  553.58
  4760.9  549.51  4782.9     550  4788.9  551.71  4803.9  549.25  4809.9  551.38
  4818.9  549.38    4825  550.07  4832.9  549.48  4839.7   547.8  4861.9  547.11
  4882.8  548.05  4905.5  546.98  4913.1  548.75  4927.4  548.33  4932.8  547.28
  4963.9  547.77    4997  546.75  4999.8  546.25    5003  546.75  5049.1  547.15
  5053.4  548.92  5067.8  549.05  5100.5  546.75  5549.4  554.56  5573.5  554.33
#Mann= 3 ,-1 , 0
  4412.1     .05       0    4997    .035       0    5003     .05       0
Bank Sta=4997,5003
XS Rating Curve= 0 ,0
Exp/Cntr=0.3,0.1

Type RM Length L Ch R = 1 ,13996   ,46,46,46
BEGIN DESCRIPTION:
UNT00685 IN CHRS 20.6
END DESCRIPTION:
XS GIS Cut Line= 6
      3437549.18     10617978.31      3437312.19     10617621.53
      3437247.09     10617509.55      3437208.03     10617484.81
      3437149.43      10617478.3      3436728.89     10617211.39
#Sta/Elev= 30
  4411.1  558.63  4492.1  557.48  4507.2  556.04  4558.3  555.38  4587.2  553.54
  4666.5  550.79  4842.2  547.57  4869.3  546.39    4875  547.83  4884.9   547.9
  4907.3  546.03    4913   548.2  4929.1  549.77  4942.3  549.11    4993  549.74
    4997  546.03  4999.8  545.53    5003  546.03  5008.2  549.67  5013.6  548.49
  5041.3  550.59  5074.4  549.34  5077.3  547.93  5098.6  546.13  5106.4  547.18
  5129.5  546.85    5178  548.36  5375.7  550.69  5381.7  551.57  5572.5   554.3
#Mann= 3 ,-1 , 0
  4411.1     .05       0    4997    .035       0    5003     .05       0
Bank Sta=4997,5003
XS Rating Curve= 0 ,0
Exp/Cntr=0.3,0.1

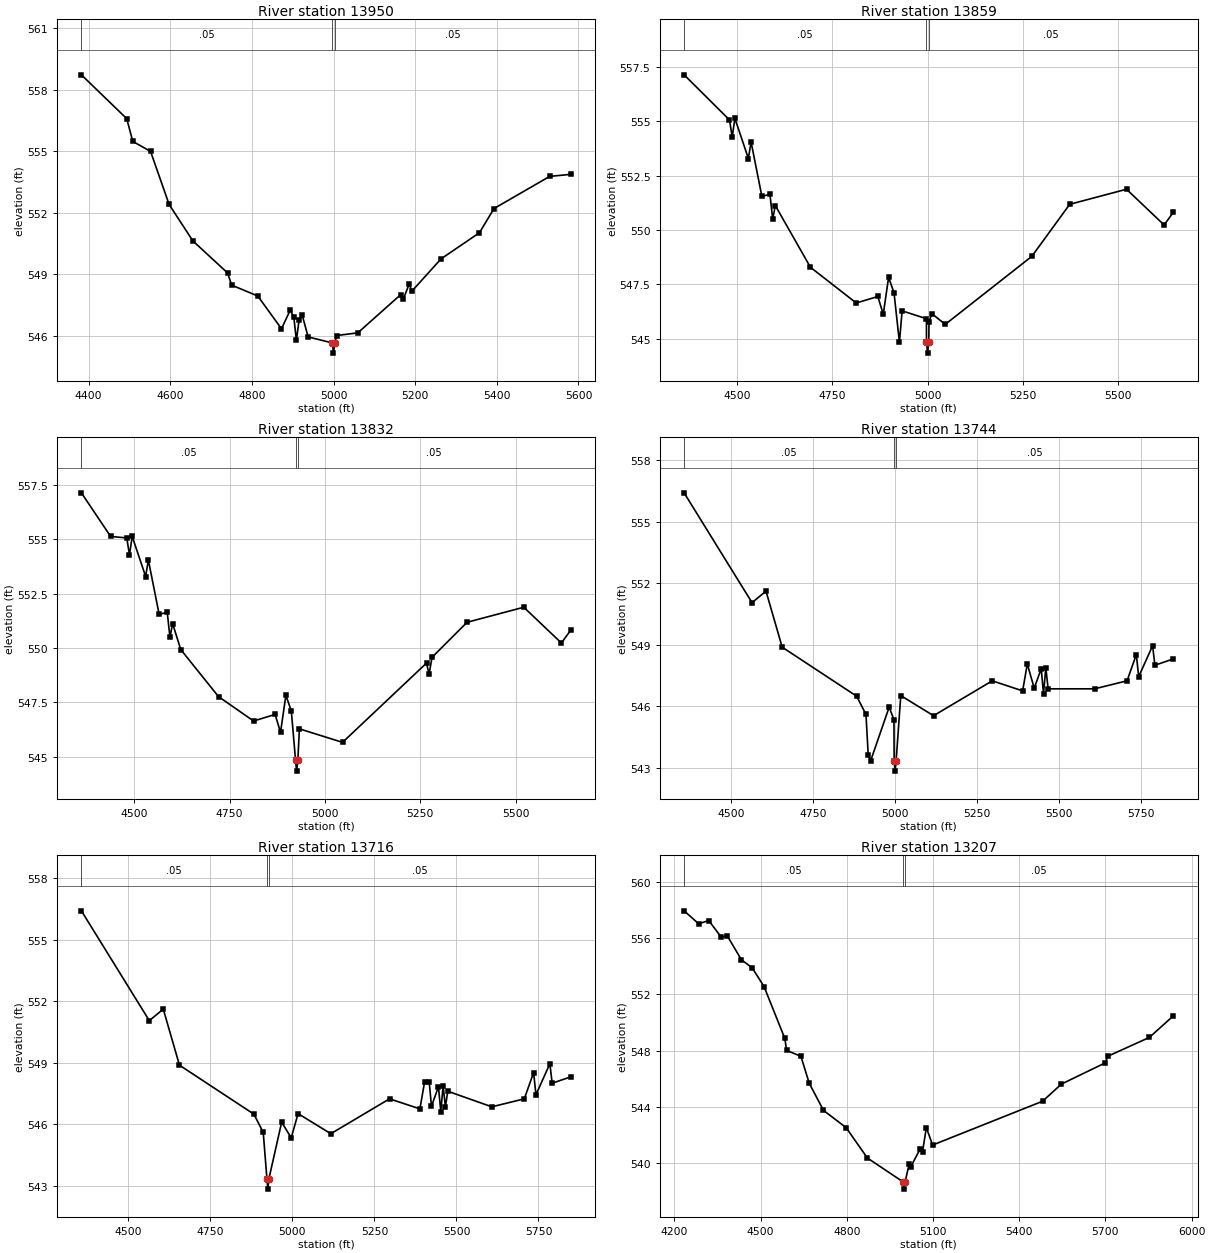
Type RM Length L Ch R = 1 ,13950   ,91,91,91
BEGIN DESCRIPTION:
UNT00685 IN CHRS 20.5
END DESCRIPTION:
XS GIS Cut Line= 5
      3437580.93     10617976.58      3437307.51     10617526.09
      3437221.57     10617424.52      3437122.61     10617377.65
      3436773.64     10617127.64
#Sta/Elev= 30
  4382.3  558.73  4493.4  556.59  4508.1  555.48  4551.8  554.99  4597.2   552.4
  4655.4  550.62  4740.7  549.05  4750.4  548.46  4814.4  547.93  4872.5  546.33
  4893.9  547.24  4902.8  546.88    4909  545.77  4915.8  546.78  4923.5  546.98
  4937.8  545.93    4997  545.64  4999.8  545.14    5003  545.64  5008.1     546
  5059.5  546.13  5164.7     548  5170.8  547.77  5185.5  548.52  5191.7  548.16
  5263.2  549.74  5357.5  551.02  5393.1   552.2  5529.5  553.77  5581.1  553.87
#Mann= 3 ,-1 , 0
  4382.3     .05       0    4997    .035       0    5003     .05       0
Bank Sta=4997,5003
XS Rating Curve= 0 ,0
Exp/Cntr=0.3,0.1

Type RM Length L Ch R = 1 ,13859   ,115,115,115
BEGIN DESCRIPTION:
UNT00685 IN CHRS 19.2
END DESCRIPTION:
XS GIS Cut Line= 4
      3437759.67     10617832.43      3437337.78     10617413.15
      3437077.36     10617186.58      3436822.14      10616957.4
#Sta/Elev= 30
  4361.5  557.12  4480.5  555.05  4487.6  554.27  4494.7  555.12    4530  553.28
  4537.1  554.04  4565.4  551.54  4586.6  551.64  4593.7  550.49  4600.7  551.12
  4692.7  548.29  4812.9  546.65  4869.4  546.95  4883.6  546.13  4897.7  547.83
  4911.9  547.11    4926  544.85  4933.1  546.29  4996.8  545.93    4997  544.85
  4999.8  544.35    5003  544.85  5003.6   545.8  5011.1  546.16  5046.2  545.67
  5273.1  548.79  5372.6  551.18  5521.4  551.87    5620  550.23  5644.5  550.82
#Mann= 3 ,-1 , 0
  4361.5     .05       0    4997    .035       0    5003     .05       0
Bank Sta=4997,5003
XS Rating Curve= 0 ,0
Exp/Cntr=0.3,0.1

Type RM Length L Ch R = 1 ,13832   ,116,116,116
BEGIN DESCRIPTION:
UNT00685 IN CHRS 19.2
END DESCRIPTION:
XS GIS Cut Line= 4
      3437759.67     10617832.43      3437337.78     10617413.15
      3437077.36     10617186.58      3436822.14      10616957.4
#Sta/Elev= 30
  4361.5  557.12  4438.1  555.12  4480.5  555.05  4487.6  554.27  4494.7  555.12
    4530  553.28  4537.1  554.04  4565.4  551.54  4586.6  551.64  4593.7  550.49
  4600.7  551.12    4622  549.93    4721  547.77  4812.9  546.65  4869.4  546.95
  4883.6  546.13  4897.7  547.83  4911.9  547.11    4923  544.85  4925.8  544.35
    4929  544.85  4933.1  546.29  5046.2  545.67  5266.5  549.31  5273.1  548.79
  5280.7  549.57  5372.6  551.18  5521.4  551.87    5620  550.23  5644.5  550.82
#Mann= 3 ,-1 , 0
  4361.5     .05       0    4923    .035       0    4929     .05       0
Bank Sta=4923,4929
XS Rating Curve= 0 ,0
Exp/Cntr=0.3,0.1

Type RM Length L Ch R = 1 ,13744   ,537,537,537
BEGIN DESCRIPTION:
UNT00685 IN CHRS 19.1
END DESCRIPTION:
XS GIS Cut Line= 4
      3437842.98     10617733.45       3437410.7     10617340.23
       3437160.7      10617009.5      3436807.26     10616666.46
#Sta/Elev= 30
  4356.8   556.4  4563.8  551.05  4606.4  551.61  4655.7  548.88  4882.8  546.49
  4911.1   545.6  4917.9  543.64  4925.3  543.34  4981.8  545.96  4996.4  545.34
    4997  543.34  4999.8  542.84    5003  543.34  5017.2  546.52  5117.1  545.54
    5296  547.24  5388.6  546.75  5402.8  548.06  5423.9  546.88  5445.2  547.83
  5452.2  546.62  5459.3  547.87  5466.3  546.85  5607.8  546.85  5706.8  547.24
  5735.1  548.52  5742.3  547.44  5784.7  548.95  5791.7     548  5848.3  548.31
#Mann= 3 ,-1 , 0
  4356.8     .05       0    4997     .04       0    5003     .05       0
Bank Sta=4997,5003
XS Rating Curve= 0 ,0
Exp/Cntr=0.3,0.1

Type RM Length L Ch R = 1 ,13716   ,536,536,536
BEGIN DESCRIPTION:
UNT00685 IN CHRS 19.1
END DESCRIPTION:
XS GIS Cut Line= 4
      3437842.98     10617733.45       3437410.7     10617340.23
       3437160.7      10617009.5      3436807.26     10616666.46
#Sta/Elev= 30
  4356.8   556.4  4563.8  551.05  4606.4  551.61  4655.7  548.88  4882.8  546.49
  4911.1   545.6  4922.3  543.34  4925.1  542.84  4928.3  543.34  4967.2   546.1
  4996.4  545.34  5017.2  546.52  5117.1  545.54    5296  547.24  5388.6  546.75
  5402.8  548.06  5416.9  548.06  5423.9  546.88  5445.2  547.83  5452.2  546.62
  5459.3  547.87  5466.3  546.85  5473.5  547.61  5607.8  546.85  5706.8  547.24
  5735.1  548.52  5742.3  547.44  5784.7  548.95  5791.7     548  5848.3  548.31
#Mann= 3 ,-1 , 0
  4356.8     .05       0  4922.3     .04       0  4928.3     .05       0
Bank Sta=4922.3,4928.3
XS Rating Curve= 0 ,0
Exp/Cntr=0.3,0.1

Type RM Length L Ch R = 1 ,13207   ,437,437,437
BEGIN DESCRIPTION:
UNT00685 IN CHRS 19.0
END DESCRIPTION:
XS GIS Cut Line= 3
      3438318.55     10617296.65      3437870.61     10616942.46
      3436835.63     10616484.79
#Sta/Elev= 30
    4234  557.94  4284.6  557.02  4319.8  557.25  4363.2  556.07    4384  556.17
  4433.6  554.46  4470.6   553.9  4512.2  552.56  4584.4  548.88  4590.8  548.03
  4640.4  547.61  4669.3   545.7    4719  543.77  4797.5  542.55  4871.7  540.39
    4997  538.68  4999.8  538.18    5003  538.68  5016.9  539.96  5022.4  539.76
  5054.9  541.01  5063.5  540.81  5076.8  542.55  5098.6  541.31  5481.3  544.42
  5546.9  545.64    5700  547.15  5707.5  547.61  5852.8  548.95  5936.7  550.49
#Mann= 3 ,-1 , 0
    4234     .05       0    4997    .035       0    5003     .05       0
Bank Sta=4997,5003
XS Rating Curve= 0 ,0
Exp/Cntr=0.3,0.1

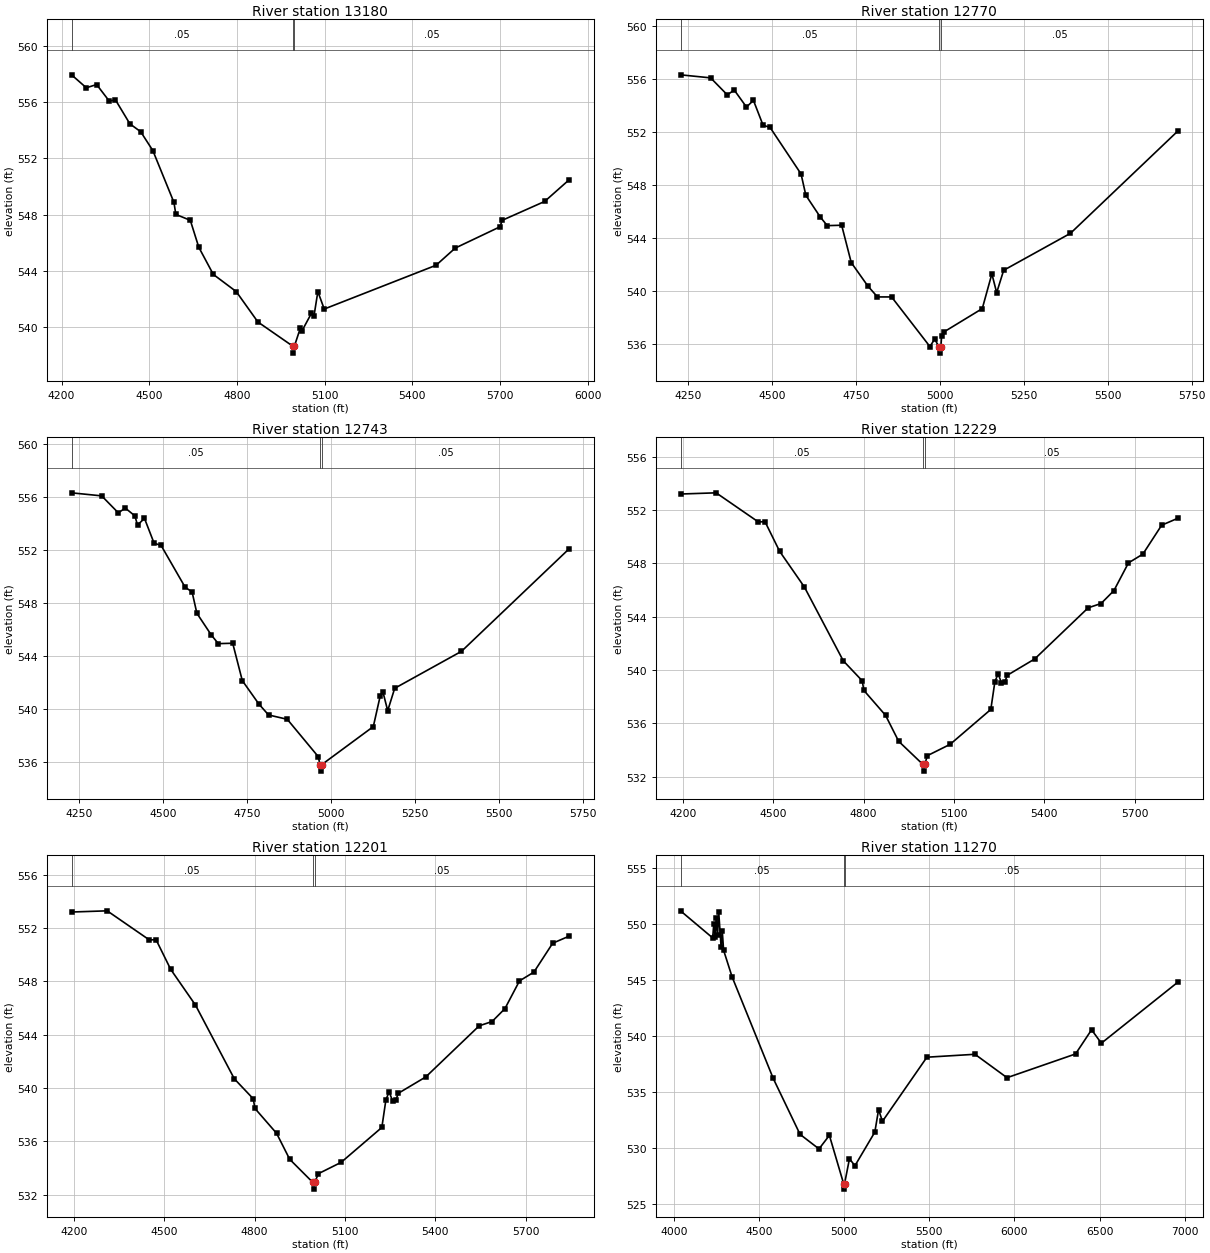
Type RM Length L Ch R = 1 ,13180   ,437,437,437
BEGIN DESCRIPTION:
UNT00685 IN CHRS 19.0
END DESCRIPTION:
XS GIS Cut Line= 3
      3438318.55     10617296.65      3437870.61     10616942.46
      3436835.63     10616484.79
#Sta/Elev= 30
    4234  557.94  4284.6  557.02  4319.8  557.25  4363.2  556.07    4384  556.17
  4433.6  554.46  4470.6   553.9  4512.2  552.56  4584.4  548.88  4590.8  548.03
  4640.4  547.61  4669.3   545.7    4719  543.77  4797.5  542.55  4871.7  540.39
  4990.6  538.68  4993.4  538.18  4996.6  538.68  5016.9  539.96  5022.4  539.76
  5054.9  541.01  5063.5  540.81  5076.8  542.55  5098.6  541.31  5481.3  544.42
  5546.9  545.64    5700  547.15  5707.5  547.61  5852.8  548.95  5936.7  550.49
#Mann= 3 ,-1 , 0
    4234     .05       0  4990.6    .035       0  4996.6     .05       0
Bank Sta=4990.6,4996.6
XS Rating Curve= 0 ,0
Exp/Cntr=0.3,0.1

Type RM Length L Ch R = 1 ,12770   ,541,541,541
BEGIN DESCRIPTION:
UNT00685 IN CHRS 16.0
END DESCRIPTION:
XS GIS Cut Line= 2
      3438573.75     10617036.22      3437438.28     10616083.06
#Sta/Elev= 30
  4227.3  556.33  4317.1   556.1  4366.6  554.82  4387.4  555.18  4423.8   553.9
  4444.6   554.4  4473.2  552.53  4494.1  552.36  4586.4  548.85  4600.7  547.24
  4643.7   545.6  4664.5  544.95  4707.4  544.98    4736  542.16  4785.5  540.39
  4814.1  539.57  4856.1  539.57  4970.2  535.83  4984.5  536.38    4997  535.83
  4999.8  535.33    5003  535.83  5005.3  536.65  5012.8  536.94  5126.3  538.69
  5154.9  541.31  5169.2  539.89    5190  541.58    5389  544.37  5709.8  552.11
#Mann= 3 ,-1 , 0
  4227.3     .05       0    4997    .035       0    5003     .05       0
Bank Sta=4997,5003
XS Rating Curve= 0 ,0
Exp/Cntr=0.3,0.1

Type RM Length L Ch R = 1 ,12743   ,542,542,542
BEGIN DESCRIPTION:
UNT00685 IN CHRS 16.0
END DESCRIPTION:
XS GIS Cut Line= 2
      3438573.75     10617036.22      3437438.28     10616083.06
#Sta/Elev= 30
  4227.3  556.33  4317.1   556.1  4366.6  554.82  4387.4  555.18    4416  554.59
  4423.8   553.9  4444.6   554.4  4473.2  552.53  4494.1  552.36  4565.6  549.21
  4586.4  548.85  4600.7  547.24  4643.7   545.6  4664.5  544.95  4707.4  544.98
    4736  542.16  4785.5  540.39  4814.1  539.57    4870  539.24  4962.4  536.42
  4967.2  535.83  4969.9  535.33  4973.2  535.83  5126.3  538.69  5147.1  541.03
  5154.9  541.31  5169.2  539.89    5190  541.58    5389  544.37  5709.8  552.11
#Mann= 3 ,-1 , 0
  4227.3     .05       0  4967.2    .035       0  4973.2     .05       0
Bank Sta=4967.2,4973.2
XS Rating Curve= 0 ,0
Exp/Cntr=0.3,0.1

Type RM Length L Ch R = 1 ,12229   ,959,959,959
BEGIN DESCRIPTION:
UNT00685 IN CHRS 15.0
END DESCRIPTION:
XS GIS Cut Line= 3
       3439042.5     10616525.81      3438568.53     10616234.13
      3437542.46     10615848.71
#Sta/Elev= 30
  4191.9  553.21  4310.2   553.3  4450.7  551.11  4472.4  551.14  4521.1  548.91
  4603.3  546.23  4732.5  540.69  4795.4  539.19  4800.8  538.47  4872.8   536.6
  4916.4  534.65    4997  532.91  4999.8  532.41    5003  532.91  5011.7  533.57
  5087.2  534.42  5222.4  537.04    5236  539.13  5246.7  539.71  5257.9  539.04
    5268  539.07  5277.5  539.61  5368.2  540.83  5545.8  544.67  5588.5  544.99
  5631.2  545.96  5679.5  548.04  5727.4   548.7  5789.8  550.87  5844.5   551.4
#Mann= 3 ,-1 , 0
  4191.9     .05       0    4997    .035       0    5003     .05       0
Bank Sta=4997,5003
XS Rating Curve= 0 ,0
Exp/Cntr=0.3,0.1

Type RM Length L Ch R = 1 ,12201   ,934,934,934
BEGIN DESCRIPTION:
UNT00685 IN CHRS 15.0
END DESCRIPTION:
XS GIS Cut Line= 3
       3439042.5     10616525.81      3438568.53     10616234.13
      3437542.46     10615848.71
#Sta/Elev= 30
  4191.9  553.21  4310.2   553.3  4450.7  551.11  4472.4  551.14  4521.1  548.91
  4603.3  546.23  4732.5  540.69  4795.4  539.19  4800.8  538.47  4872.8   536.6
  4916.4  534.65  4993.4  532.91  4996.2  532.41  4999.4  532.91  5011.7  533.57
  5087.2  534.42  5222.4  537.04    5236  539.13  5246.7  539.71  5257.9  539.04
    5268  539.07  5277.5  539.61  5368.2  540.83  5545.8  544.67  5588.5  544.99
  5631.2  545.96  5679.5  548.04  5727.4   548.7  5789.8  550.87  5844.5   551.4
#Mann= 3 ,-1 , 0
  4191.9     .05       0  4993.4    .035       0  4999.4     .05       0
Bank Sta=4993.4,4999.4
XS Rating Curve= 0 ,0
Exp/Cntr=0.3,0.1

Type RM Length L Ch R = 1 ,11270   ,1006,1006,1006
BEGIN DESCRIPTION:
UNT00685 IN CHRS 13.0
END DESCRIPTION:
XS GIS Cut Line= 4
      3439563.31     10615895.58      3439047.69     10615484.13
      3438558.11     10615234.13      3436938.29     10614682.04
#Sta/Elev= 30
  4039.9  551.21  4228.8  548.79  4235.2  550.05  4243.2  548.86  4249.6  550.59
  4257.6  549.07    4264  551.13  4278.4  547.94  4284.8  549.45  4292.8  547.69
  4342.5  545.32  4584.2  536.24  4741.6  531.25  4852.7  529.95  4913.7  531.16
    4997  526.86  4999.8  526.36    5003  526.86  5031.5  529.07  5063.7  528.45
  5180.4  531.45  5202.6  533.47  5224.9  532.41  5486.1  538.14  5768.2   538.4
  5956.3  536.31  6358.5  538.43  6452.6  540.59    6510  539.39  6960.6  544.86
#Mann= 3 ,-1 , 0
  4039.9     .05       0    4997    .035       0    5003     .05       0
Bank Sta=4997,5003
XS Rating Curve= 0 ,0
Exp/Cntr=0.3,0.1

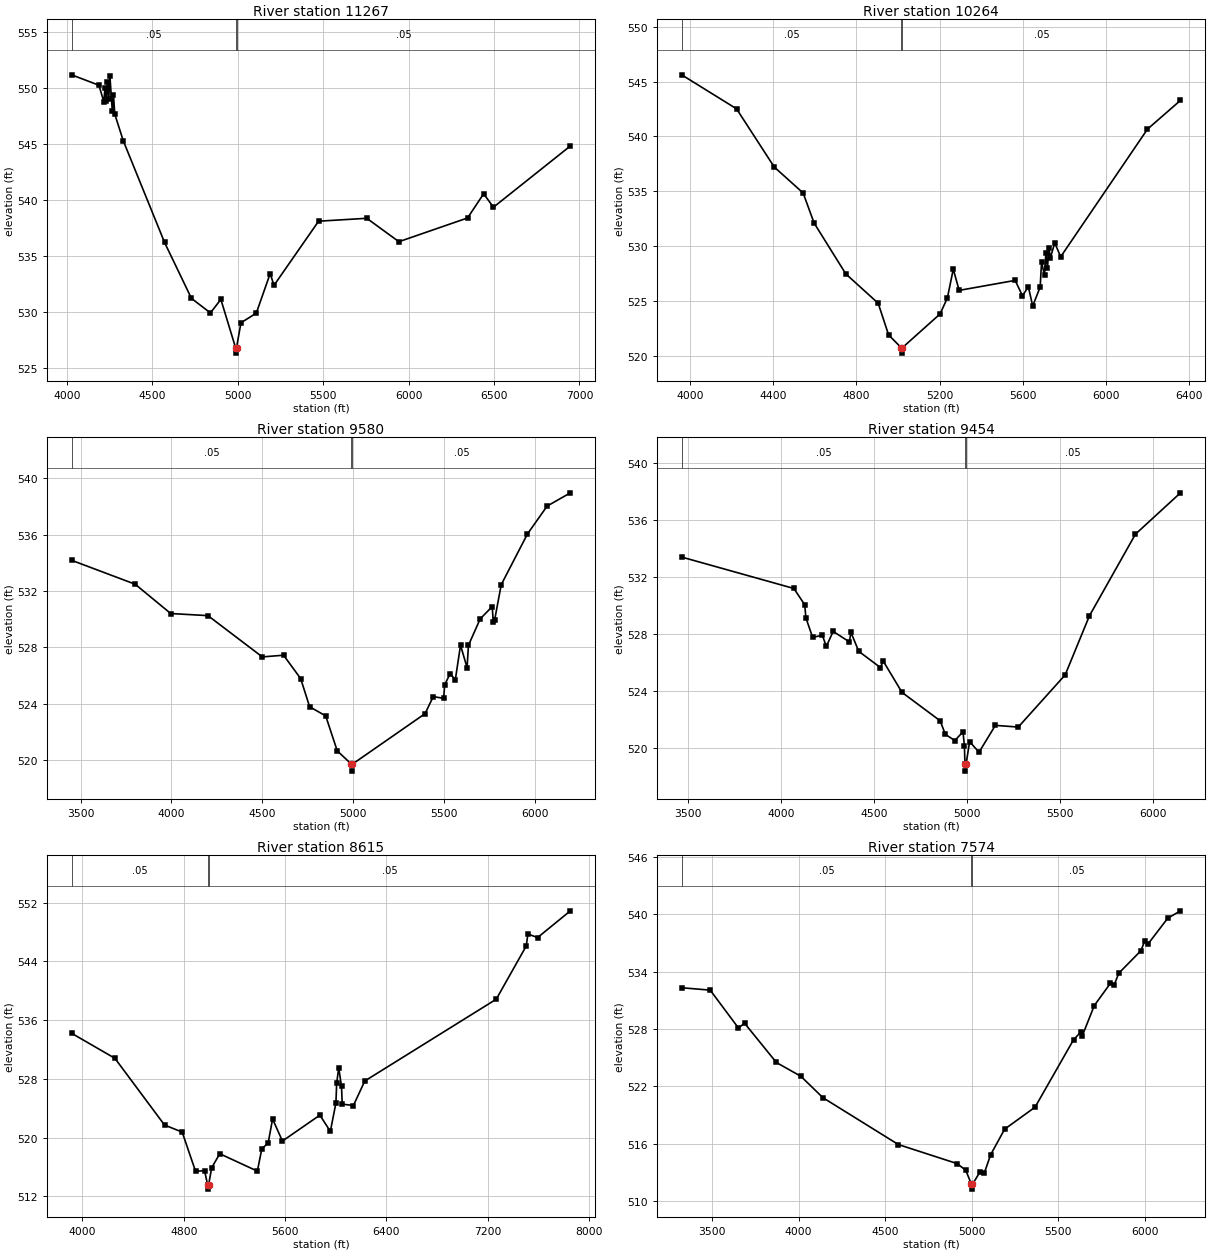
Type RM Length L Ch R = 1 ,11267   ,1003,1003,1003
BEGIN DESCRIPTION:
UNT00685 IN CHRS 13.0
END DESCRIPTION:
XS GIS Cut Line= 4
      3439563.33      10615895.6      3439047.69     10615484.13
      3438558.11     10615234.13      3436938.32     10614682.05
#Sta/Elev= 30
  4026.4  551.21  4186.5  550.28  4215.3  548.79  4221.7  550.05  4229.7  548.86
  4236.1  550.59  4244.1  549.07  4250.5  551.13  4264.9  547.94  4271.3  549.45
  4279.3  547.69    4329  545.32  4570.8  536.24  4728.1  531.25  4839.2  529.95
  4900.3  531.16  4986.2  526.86  4988.9  526.36  4992.2  526.86    5018  529.07
  5107.8  529.93  5189.2  533.47  5211.4  532.41  5472.6  538.14  5754.8   538.4
  5942.8  536.31    6345  538.43  6439.1  540.59  6496.5  539.39  6947.1  544.86
#Mann= 3 ,-1 , 0
  4026.4     .05       0  4986.2    .035       0  4992.2     .05       0
Bank Sta=4986.2,4992.2
XS Rating Curve= 0 ,0
Exp/Cntr=0.3,0.1

Type RM Length L Ch R = 1 ,10264   ,684,684,684
BEGIN DESCRIPTION:
UNT00685 IN CHRS 11.0
END DESCRIPTION:
XS GIS Cut Line= 4
      3439969.56     10615416.41      3439573.73     10614739.34
      3438938.32     10614187.25      3438423.88     10613605.27
#Sta/Elev= 30
  3957.9  545.62  4222.2  542.52    4404  537.21  4542.9  534.85  4595.8  532.11
  4748.6  527.47  4904.4   524.8  4954.7  521.91  5015.3  520.75  5018.1  520.25
  5021.3  520.75  5202.5  523.82  5237.7  525.27  5266.2   527.9  5294.6  525.97
  5564.3  526.88  5599.5  525.48  5627.9  526.29  5648.8  524.55  5684.8  526.27
  5691.5  528.55  5705.7  527.34  5712.4  529.37  5719.9     528  5726.6   529.8
  5734.2  528.96  5755.1   530.3  5783.5  529.03  6201.8  540.67  6360.7  543.29
#Mann= 3 ,-1 , 0
  3957.9     .05       0  5015.3    .035       0  5021.3     .05       0
Bank Sta=5015.3,5021.3
XS Rating Curve= 0 ,0
Exp/Cntr=0.3,0.1

Type RM Length L Ch R = 1 ,9580    ,126,126,126
BEGIN DESCRIPTION:
UNT00685 IN CHRS 9.1
END DESCRIPTION:
XS GIS Cut Line= 3
      3441237.07     10615038.23      3440056.49       10614316.
      3438925.79     10613559.88
#Sta/Elev= 30
  3450.8  534.19  3800.6  532.49  3996.1  530.41  4201.1  530.26    4500  527.33
    4617  527.45    4711  525.79  4760.3  523.79  4848.8  523.14  4912.2  520.66
    4990  519.72  4992.7  519.22    4996  519.72  5395.4   523.3  5440.4  524.51
  5497.5  524.39  5503.5  525.35  5533.5  526.15  5561.8   525.7  5590.5  528.16
  5626.6  526.56    5634  528.15  5698.7  530.03  5764.7   530.9  5770.7  529.83
  5778.4  529.97  5814.5  532.46  5958.8  536.06  6067.1  538.04    6195  538.98
#Mann= 3 ,-1 , 0
  3450.8     .05       0    4990    .035       0    4996     .05       0
Bank Sta=4990,4996
XS Rating Curve= 0 ,0
Exp/Cntr=0.3,0.1

Type RM Length L Ch R = 1 ,9454    ,839,839,839
BEGIN DESCRIPTION:
UNT00685 IN CHRS 9.0
END DESCRIPTION:
XS GIS Cut Line= 3
      3441292.59     10614920.15      3440094.69       10614191.
      3439018.26       10613500.
#Sta/Elev= 30
  3465.9  533.41  4069.1   531.2  4127.2  530.06  4133.8  529.13  4169.9  527.76
  4222.1  527.91  4243.5  527.12  4280.3  528.18  4367.9  527.44  4375.2  528.13
  4417.8  526.78    4534  525.64  4549.5  526.09  4650.3  523.89  4855.6  521.89
  4883.2  520.94  4934.3   520.5  4978.3  521.12  4985.8  520.12  4988.8  518.85
  4991.5  518.35  4994.8  518.85  5013.9  520.42  5064.4  519.68  5152.3  521.57
  5275.4  521.45  5527.5  525.12  5657.7  529.27  5905.2  535.02  6147.4  537.93
#Mann= 3 ,-1 , 0
  3465.9     .05       0  4988.8     .04       0  4994.8     .05       0
Bank Sta=4988.8,4994.8
XS Rating Curve= 0 ,0
Exp/Cntr=0.3,0.1

Type RM Length L Ch R = 1 ,8615    ,1041,1041,1041
BEGIN DESCRIPTION:
UNT00685 IN CHRS 6.0
END DESCRIPTION:
XS GIS Cut Line= 4
       3441308.1     10614046.63      3440578.94     10613801.84
      3439792.48     10613072.67      3437933.15     10612098.73
#Sta/Elev= 30
  3914.1  534.22  4256.2  530.81  4648.3  521.72  4787.5  520.76  4893.6  515.41
  4964.4  515.51  4989.6  513.49  4992.3  512.99  4995.6  513.49  5020.6   515.9
  5084.6  517.81  5381.7  515.44  5416.9   518.5  5466.7  519.26  5501.9  522.54
  5579.6  519.54  5875.6  523.07  5958.2  520.85  6002.3  524.73    6008  527.39
  6024.4  529.52  6046.5  526.97  6052.1  524.57  6140.4  524.38  6230.3  527.72
  7268.9  538.86  7505.9  546.11  7518.6  547.74  7595.6  547.26  7854.7   550.9
#Mann= 3 ,-1 , 0
  3914.1     .05       0  4989.6    .035       0  4995.6     .05       0
Bank Sta=4989.6,4995.6
XS Rating Curve= 0 ,0
Exp/Cntr=0.3,0.1

Type RM Length L Ch R = 1 ,7574    ,535,535,535
BEGIN DESCRIPTION:
UNT00685 IN CHRS 4.1
END DESCRIPTION:
XS GIS Cut Line= 4
      3441693.49     10613973.68      3440995.61     10613333.09
      3440381.03     10612426.84      3439766.45     10611853.93
#Sta/Elev= 30
  3324.4  532.32  3489.3  532.07  3652.1  528.11  3687.9   528.6  3871.6  524.49
  4013.4  523.04  4140.7   520.8  4576.7  515.89  4915.2   513.9  4966.1   513.2
    4999  511.72  5001.7  511.22    5005  511.72  5046.7  512.98  5073.9  512.94
  5109.8  514.82  5190.6   517.5  5366.7  519.81  5588.9  526.87  5631.4  527.69
  5638.6  527.25  5709.1  530.46  5801.4  532.77  5822.4  532.56  5850.7  533.85
  5978.3   536.2  5999.3  537.18  6020.8  536.94  6133.6  539.61  6206.9  540.38
#Mann= 3 ,-1 , 0
  3324.4     .05       0    4999    .035       0    5005     .05       0
Bank Sta=4999,5005
XS Rating Curve= 0 ,0
Exp/Cntr=0.3,0.1

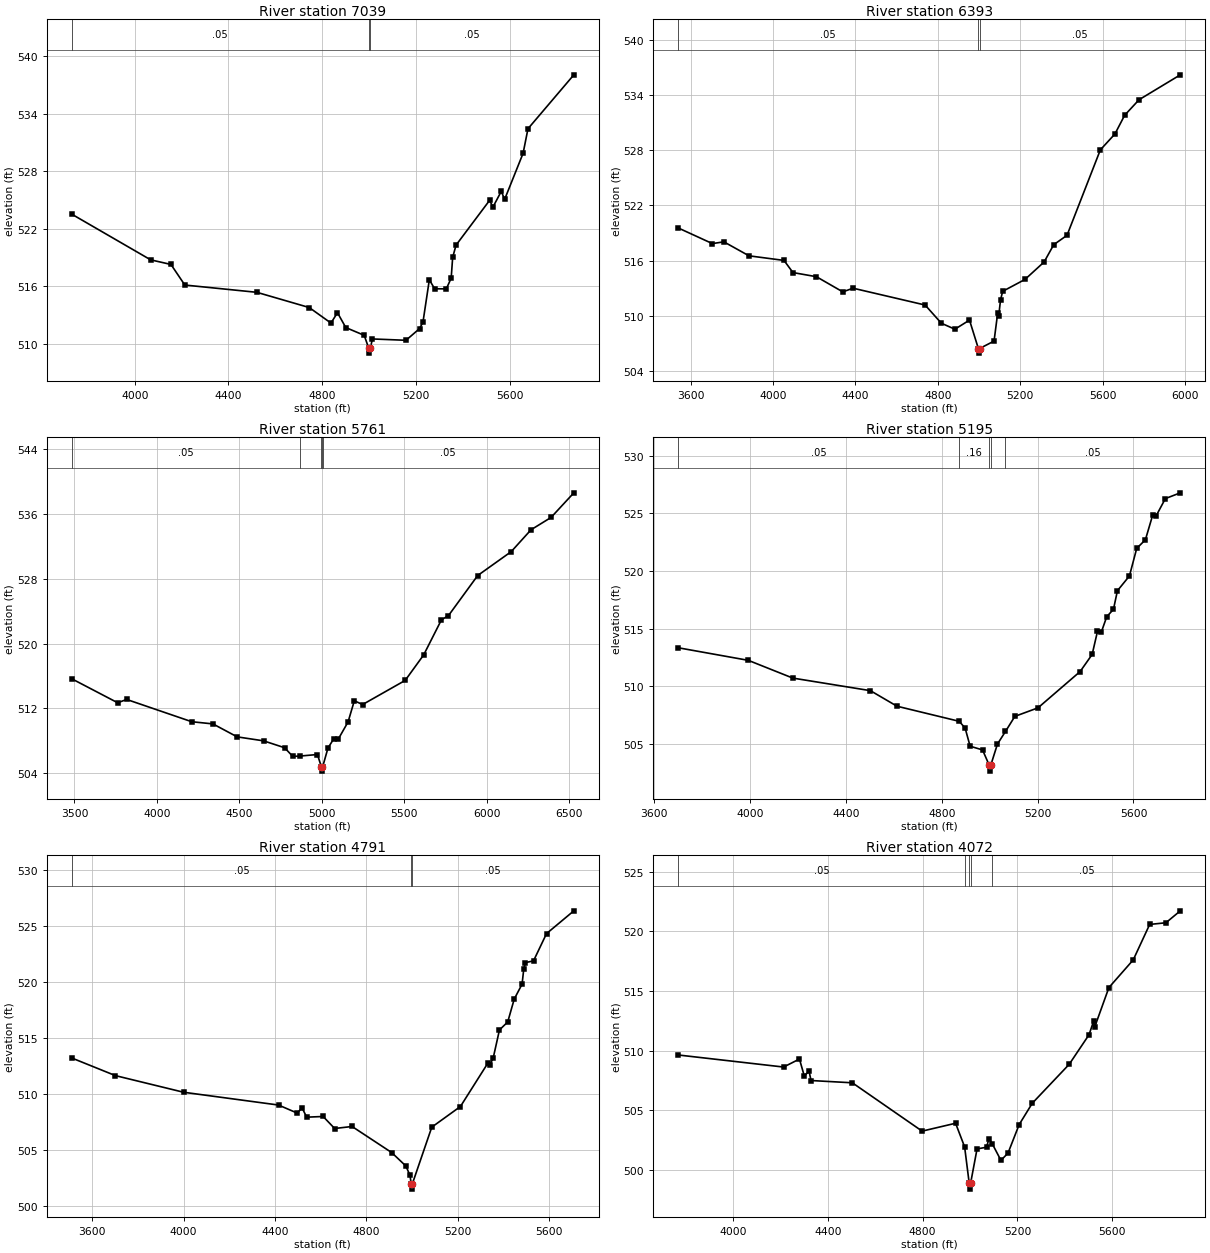
Type RM Length L Ch R = 1 ,7039    ,646,646,646
BEGIN DESCRIPTION:
UNT00685 IN CHRS 3.0
END DESCRIPTION:
XS GIS Cut Line= 3
      3441735.18     10613405.98      3441318.53     10612671.63
      3440293.72     10611875.71
#Sta/Elev= 30
  3731.4  523.52    4068  518.75  4154.5  518.27  4213.7  516.12  4520.9  515.36
  4744.5  513.77  4837.1  512.15  4864.9  513.23  4900.4  511.68  4978.9  510.87
  4998.5  509.51  5001.3  509.01  5004.5  509.51  5014.3  510.49  5157.2  510.35
  5215.1  511.57  5229.6  512.24  5256.8  516.67  5279.4  515.73  5329.2  515.72
    5350  516.84  5356.3     519  5370.8  520.29  5513.8  524.96  5528.3  524.27
  5563.6   525.9  5578.1  525.07  5656.8  529.88  5677.6  532.44  5873.3  538.07
#Mann= 3 ,-1 , 0
  3731.4     .05       0  4998.5     .03       0  5004.5     .05       0
Bank Sta=4998.5,5004.5
XS Rating Curve= 0 ,0
Exp/Cntr=0.3,0.1

Type RM Length L Ch R = 1 ,6393    ,632,632,632
BEGIN DESCRIPTION:
UNT00685 IN CHRS 6.1
END DESCRIPTION:
XS GIS Cut Line= 4
      3442172.67     10613202.85      3441506.03     10612359.13
      3441339.36     10611812.25      3440558.12     10611697.67
#Sta/Elev= 30
    3540  519.54  3705.6  517.84  3761.6  518.03  3883.5  516.51  4053.3  516.01
  4096.7  514.69  4210.5  514.24  4338.7  512.59  4388.4  512.99  4738.1  511.16
    4817  509.18  4882.6  508.53  4953.5  509.52  4996.5  506.43  4999.2  505.93
  5002.5  506.43  5072.7  507.24  5090.1  510.25  5095.3  509.97    5104   511.7
  5114.5  512.65  5222.6  513.94  5315.6  515.84  5362.3  517.72  5426.8  518.74
  5588.5  528.03  5659.3  529.76  5706.4  531.79  5776.2  533.48  5976.6  536.19
#Mann= 3 ,-1 , 0
    3540     .05       0  4996.5     .03       0  5002.5     .05       0
Bank Sta=4996.5,5002.5
XS Rating Curve= 0 ,0
Exp/Cntr=0.3,0.1

Type RM Length L Ch R = 1 ,5761    ,566,566,566
BEGIN DESCRIPTION:
UNT00685 IN CHRS 5.5
END DESCRIPTION:
XS GIS Cut Line= 4
      3442563.32     10612937.27      3442146.65      10611968.5
      3441672.69     10611572.67       3440302.9     10611510.17
#Sta/Elev= 30
  3483.7  515.65    3762  512.69  3816.4   513.1  4210.9  510.35  4339.5  510.08
  4486.2  508.48  4646.1  507.99  4773.7  507.14  4823.1  506.07  4866.5  506.11
  4972.8   506.3  4997.2  504.75    5000  504.25  5003.2  504.75  5004.4  504.78
  5036.6   507.1  5071.7  508.24  5100.4  508.25  5158.6  510.33  5196.4  512.94
  5246.5  512.47  5504.6  515.45  5616.8   518.6  5724.4  522.93    5767  523.45
  5944.2   528.4  6147.4  531.35  6267.5  534.05  6388.8  535.57    6527  538.61
#Mann= 5 ,-1 , 0
  3483.7     .05       0  4866.5     .16       0  4997.2     .07       0
  5003.2     .16       0  5004.4     .05       0
Bank Sta=4997.2,5003.2
XS Rating Curve= 0 ,0
Exp/Cntr=0.3,0.1

Type RM Length L Ch R = 1 ,5195    ,404,404,404
BEGIN DESCRIPTION:
UNT00685 IN CHRS 5.0
END DESCRIPTION:
XS GIS Cut Line= 4
      3442714.36     10612822.67      3442344.57      10611775.8
       3442240.4      10611400.8      3441969.55     10610869.52
#Sta/Elev= 30
  3699.7  513.35  3992.1  512.26    4178  510.72  4501.8  509.63  4612.9  508.28
  4872.8  506.97  4897.3  506.38  4918.1  504.81    4970  504.49  4998.1  503.15
  5000.8  502.65  5004.1  503.15  5032.2     505  5065.7  506.09  5104.9   507.4
  5201.5  508.14  5377.4  511.29  5427.5  512.77  5449.7  514.77  5466.3  514.74
  5488.5  516.05  5516.4  516.68    5533   518.3  5583.1  519.58  5613.5  521.97
  5649.8  522.72  5680.9  524.91  5694.3  524.78  5733.1  526.29  5795.5  526.79
#Mann= 5 ,-1 , 0
  3699.7     .05       0  4872.8     .16       0  4998.1     .07       0
  5004.1     .16       0  5065.7     .05       0
Bank Sta=4998.1,5004.1
XS Rating Curve= 0 ,0
Exp/Cntr=0.3,0.1

Type RM Length L Ch R = 1 ,4791    ,719,719,719
BEGIN DESCRIPTION:
UNT00685 IN CHRS 4.0
END DESCRIPTION:
XS GIS Cut Line= 4
      3442912.27     10612801.79      3442651.86     10611723.71
      3442448.73     10611135.17      3442095.84     10610828.99
#Sta/Elev= 30
  3510.6  513.21    3702  511.64  4000.2  510.16  4416.1  509.02  4498.4   508.3
  4518.9  508.78  4539.5  507.94  4611.5     508  4661.9  506.93  4738.2  507.11
  4911.5  504.79  4973.8  503.59  4992.1  502.75  4996.7  502.03  4999.5  501.53
  5002.7  502.03  5087.3  507.05  5212.8  508.89  5334.4   512.8    5342  512.62
  5356.2   513.2  5383.7  515.71  5419.9  516.42  5448.4  518.46  5482.8  519.79
  5490.1  521.13  5497.7  521.71  5532.8  521.86  5589.8  524.29  5709.5  526.32
#Mann= 3 ,-1 , 0
  3510.6     .05       0  4996.7    .035       0  5002.7     .05       0
Bank Sta=4996.7,5002.7
XS Rating Curve= 0 ,0
Exp/Cntr=0.3,0.1

Type RM Length L Ch R = 1 ,4072    ,801,801,801
BEGIN DESCRIPTION:
UNT00685 IN CHRS 3.1
END DESCRIPTION:
XS GIS Cut Line= 4
      3443131.03      10612395.6      3442953.94     10611348.71
      3442912.28     10610973.71      3442282.02      10610723.7
#Sta/Elev= 30
  3769.5  509.63  4213.7  508.62  4280.6  509.29  4300.9  507.88  4321.2  508.27
  4329.4  507.49  4503.7   507.3  4797.9  503.25    4939  503.91  4977.1  501.93
  4996.4  498.89  4999.1  498.39  5002.4  498.89  5029.5  501.76  5069.5   501.9
  5079.9  502.63  5094.2  502.17  5130.2   500.8  5160.1  501.41  5207.1   503.8
  5262.5  505.59  5418.1  508.85  5501.8  511.33  5520.7  512.45  5526.1     512
  5585.5  515.28  5688.1   517.6  5757.4  520.57  5825.9  520.71  5886.6  521.71
#Mann= 5 ,-1 , 0
  3769.5     .05       0  4977.1     .16       0  4996.4     .07       0
  5002.4     .16       0  5094.2     .05       0
Bank Sta=4996.4,5002.4
XS Rating Curve= 0 ,0
Exp/Cntr=0.3,0.1