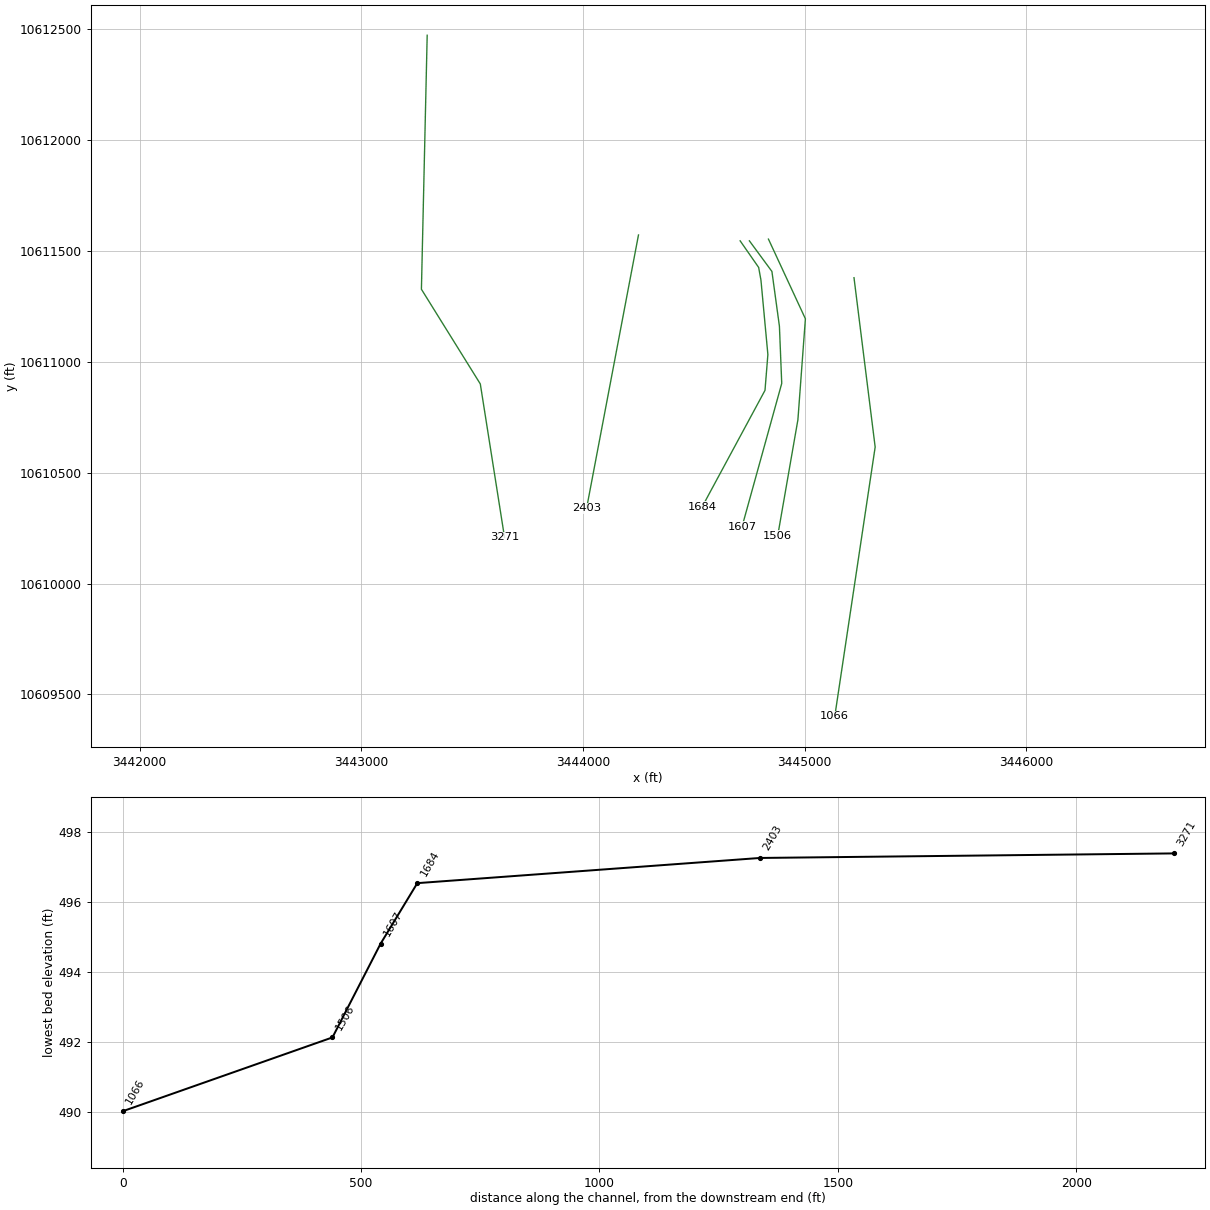
HEC-RAS study UNT0044 IN CHRS.prj: UNT0044 IN CHRS Base Level Engineering

--- UNT0044 IN CHRS.g01 (geometry) --- (continued)

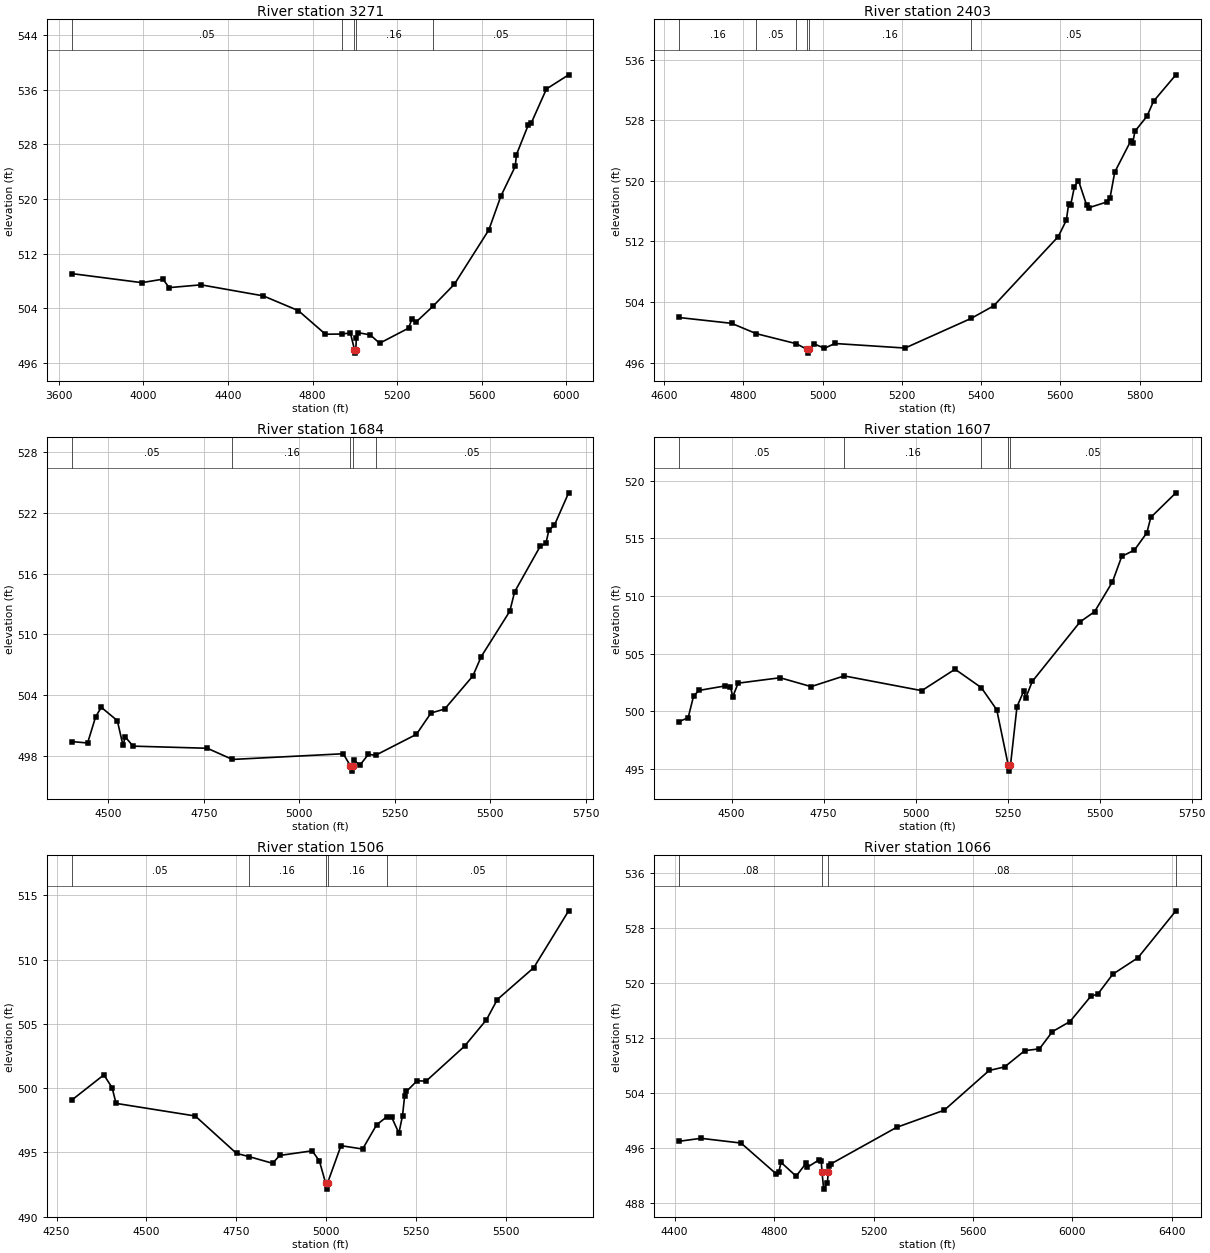
Type RM Length L Ch R = 1 ,3271    ,868,868,868
BEGIN DESCRIPTION:
UNT00685 IN CHRS 2.0
END DESCRIPTION:
XS GIS Cut Line= 4
      3443297.69     10612473.73      3443271.65     10611327.88
      3443537.28      10610900.8      3443646.65     10610208.08
#Sta/Elev= 30
  3660.1  509.06  3992.3  507.73  4092.3  508.24  4121.7     507  4272.3  507.41
  4566.8  505.79  4732.5  503.63  4860.7  500.17  4939.9   500.2  4978.5  500.37
    4998   497.9  5000.8   497.4    5004   497.9  5006.9  499.65  5013.8  500.41
  5072.7  500.07  5116.7  498.85  5253.6  501.06    5269  502.35  5290.2  501.99
  5368.3  504.25  5470.3   507.5    5633  515.45  5690.4  520.43  5757.9  524.76
  5763.9  526.51  5820.3  530.89  5834.8   531.2  5905.6  536.12  6010.5  538.19
#Mann= 5 ,-1 , 0
  3660.1     .05       0  4939.9     .16       0    4998     .07       0
    5004     .16       0  5368.3     .05       0
Bank Sta=4998,5004
XS Rating Curve= 0 ,0
Exp/Cntr=0.3,0.1

Type RM Length L Ch R = 1 ,2403    ,719,719,719
BEGIN DESCRIPTION:
UNT00685 IN CHRS 1.0
END DESCRIPTION:
XS GIS Cut Line= 2
      3444250.82      10611572.7      3444016.77     10610340.02
#Sta/Elev= 30
  4636.9  501.97  4770.3   501.2  4832.3  499.84    4933  498.52  4960.7  497.77
  4963.4  497.27  4966.7  497.77  4978.7  498.49  5004.4  497.91    5031  498.54
    5208  497.94  5374.8  501.85  5431.9  503.51  5594.8  512.65  5615.1   514.8
    5621  516.98  5626.1  516.82  5635.5  519.21  5645.7  520.04    5666  516.84
  5673.2  516.47  5716.9   517.2  5725.5  517.79  5737.3  521.15  5777.7  525.26
  5782.8  525.01  5788.2  526.53  5818.7  528.52  5835.1  530.49  5891.6  533.98
#Mann= 6 ,-1 , 0
  4636.9     .16       0  4832.3     .05       0    4933     .16       0
  4960.7     .07       0  4966.7     .16       0  5374.8     .05       0
Bank Sta=4960.7,4966.7
XS Rating Curve= 0 ,0
Exp/Cntr=0.3,0.1

Type RM Length L Ch R = 1 ,1684    ,77,77,77
BEGIN DESCRIPTION:
UNT00685 IN CHRS 1.5
END DESCRIPTION:
XS GIS Cut Line= 6
      3444709.57     10611546.21      3444792.88     10611426.44
       3444803.3     10611369.15      3444834.55     10611033.22
      3444821.52     10610871.76      3444537.92     10610346.18
#Sta/Elev= 30
    4404  499.46  4446.1  499.32  4467.1   501.9  4481.9  502.83  4523.8  501.52
  4538.6   499.1  4544.7  499.92  4564.9  499.01  4759.3   498.8  4824.9   497.7
    5115  498.26  5133.9  497.05  5136.7  496.55  5139.9  497.05  5142.6  497.61
  5158.8  497.15  5180.7   498.2  5199.5  498.11  5306.4  500.17  5344.5  502.27
  5380.3  502.66    5454  505.91  5475.8  507.81  5550.8  512.29  5563.4   514.2
  5630.3  518.68  5645.3  518.97    5653  520.27  5667.2  520.73  5704.7  523.94
#Mann= 5 ,-1 , 0
    4404     .05       0  4824.9     .16       0  5133.9     .07       0
  5139.9     .16       0  5199.5     .05       0
Bank Sta=5133.9,5139.9
XS Rating Curve= 0 ,0
Exp/Cntr=0.3,0.1

Type RM Length L Ch R = 1 ,1607    ,101,101,101
BEGIN DESCRIPTION:
UNT00685 IN CHRS 1.6
END DESCRIPTION:
XS GIS Cut Line= 5
      3444751.23     10611546.21      3444852.77     10611408.22
      3444886.63     10611160.82      3444897.05     10610903.01
      3444717.63     10610255.56
#Sta/Elev= 30
  4356.3  499.11  4381.8  499.45  4396.5  501.33  4411.1  501.82  4482.1  502.21
  4496.8  502.12    4503  501.27  4517.6  502.45  4631.7  502.92  4715.9  502.15
  4805.8  503.08  5016.7   501.8  5107.1  503.66  5178.5  502.06  5220.4  500.14
  5251.7  495.32  5254.4  494.82  5257.7  495.32  5275.4  500.41  5294.1  501.79
  5299.3  501.18  5316.9   502.6  5446.9  507.77  5486.3  508.65  5534.9  511.24
  5560.1  513.45  5594.4  513.99  5628.3  515.49    5639  516.83  5707.2  518.96
#Mann= 5 ,-1 , 0
  4356.3     .05       0  4805.8     .16       0  5178.5     .05       0
  5251.7     .07       0  5257.7     .05       0
Bank Sta=5251.7,5257.7
XS Rating Curve= 0 ,0
Exp/Cntr=0.3,0.1

Type RM Length L Ch R = 1 ,1506    ,440,440,440
BEGIN DESCRIPTION:
UNT00685 IN CHRS 1.7
END DESCRIPTION:
XS GIS Cut Line= 4
      3444837.16     10611554.02      3445003.82     10611194.67
      3444969.96     10610738.94      3444878.92     10610216.11
#Sta/Elev= 30
  4291.6  499.05  4381.7  501.03  4404.5  500.03  4415.6  498.81  4635.9  497.83
  4750.9  494.92  4785.7  494.67  4851.2  494.15  4871.2  494.76  4961.5  495.12
  4981.6  494.33  4998.6  492.64  5001.4  492.14  5004.6  492.64  5041.7  495.52
  5101.9  495.26  5140.8  497.14  5169.7  497.78  5182.6  497.74  5202.9   496.5
    5213  497.86  5218.9   499.4  5223.9  499.74  5253.6  500.57  5278.5  500.54
  5385.6  503.26  5446.5  505.31  5476.9  506.89  5578.4  509.37  5675.4  513.79
#Mann= 5 ,-1 , 0
  4291.6     .05       0  4785.7     .16       0  4998.6     .07       0
  5004.6     .16       0  5169.7     .05       0
Bank Sta=4998.6,5004.6
XS Rating Curve= 0 ,0
Exp/Cntr=0.3,0.1

Type RM Length L Ch R = 1 ,1066    ,0,0,0
BEGIN DESCRIPTION:
UNT0044 IN CHRS 1.0
END DESCRIPTION:
XS GIS Cut Line= 3
      3445223.03     10611380.01      3445318.53     10610616.07
      3445136.23     10609400.75
#Sta/Elev= 30
  4416.9  496.99    4506  497.43  4667.2  496.74  4808.3  492.26  4818.4  492.47
  4828.4  493.92  4888.9  491.91  4928.8  493.81  4933.9  493.22  4979.6  494.25
  4989.7  494.17 4992.76  492.55  4999.5  490.03  5014.5  490.93 5017.96  492.51
  5019.9  493.38    5030  493.73  5292.4  499.02  5484.5  501.53  5664.9  507.31
  5727.2  507.83  5808.1   510.2  5867.1  510.46  5919.3  512.97  5990.1  514.44
  6074.4  518.15  6101.3  518.41    6162  521.33  6263.1  523.72  6415.7  530.56
#Mann= 4 ,-1 , 0
  4416.9     .08       0 4992.76     .04       0 5017.96     .08       0
  6415.7     .05       0
Bank Sta=4992.76,5017.96
XS Rating Curve= 0 ,0
Exp/Cntr=0.3,0.1

Chan Stop Cuts=-1
Use User Specified Reach Order=0
Composite Channel Slope=5