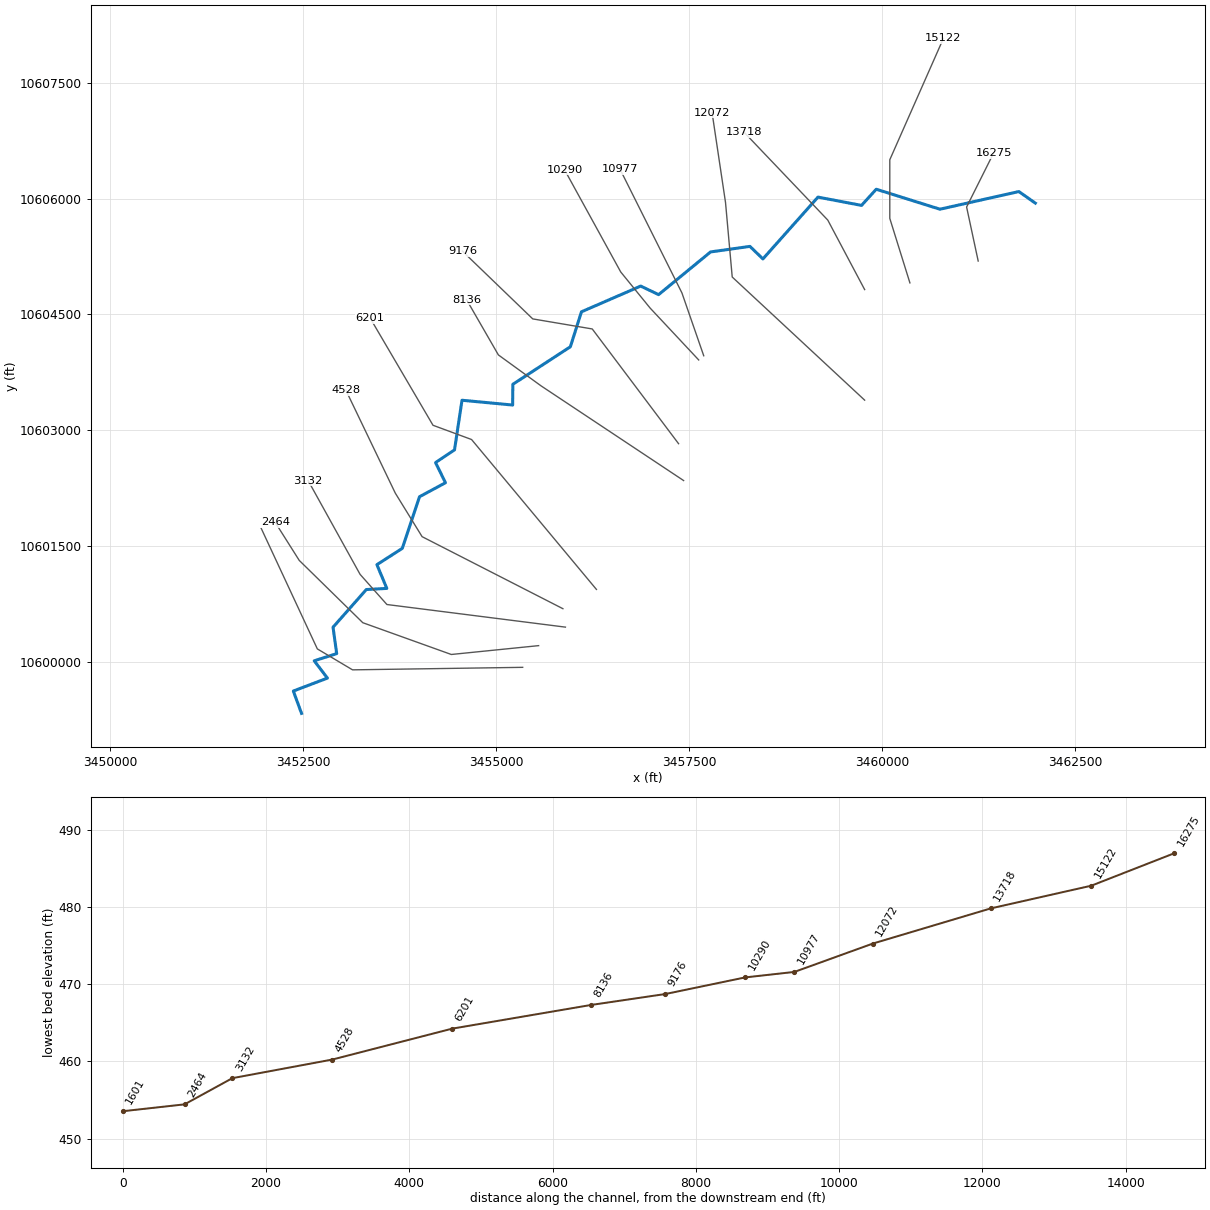
--- UNT0045 IN CHRS.prj (project) ---

Proj Title=UNT0045 IN CHRS Base Level Engineering
Current Plan=p01
Default Exp/Contr=0.3,0.1
English Units
Geom File=g01
Flow File=f01
Plan File=p01
BEGIN DESCRIPTION:
UNT0045 IN CHRS
END DESCRIPTION:

--- UNT0045 IN CHRS.p01 (plan) ---

Plan Title=Multiple Run
Short Identifier=Multiple
Geom File=g01
Flow File=f01
Subcritical Flow
K Sum by GR= 0
Std Step Tol= 0.01
Critical Tol= 0.01
Num of Std Step Trials= 20
Max Error Tol= 0.3
Flow Tol Ratio= 0.001
Split Flow NTrial= 30
Split Flow Tol= 0.02
Split Flow Ratio= 0.02
Log Output Level= 0
Friction Slope Method= 1
Unsteady Friction Slope Method= 2
Unsteady Bridges Friction Slope Method= 1
Parabolic Critical Depth
Global Vel Dist=  1 , 1 , 1
Global Log Level= 0
CheckData=True
Encroach Param= -1, 0, 0, 0
BEGIN DESCRIPTION:
Multiple Run
END DESCRIPTION:

--- UNT0045 IN CHRS.f01 (steady flow) ---

Flow Title=Multiple
Number of Profiles=7
Profile Names=10-year,25-year,50-year,1pct_min,100-year,1pct_plu,500-year
River Rch & RM= UNT0045 IN CHRS,Reach-1,16275
     429     538     617     514     696     941     884
River Rch & RM= UNT0045 IN CHRS,Reach-1,13718
     471     592     680     568     768    1039     980
River Rch & RM= UNT0045 IN CHRS,Reach-1,10977
     641     818     949     800    1082    1464    1404
River Rch & RM= UNT0045 IN CHRS,Reach-1,8136
     680     866    1005     846    1145    1548    1482
River Rch & RM= UNT0045 IN CHRS,Reach-1,1601
     832    1070    1249    1058    1430    1934    1874
Boundary for River Rch & Prof#=UNT0045 IN CHRS,Reach-1,1
Up Type=0
Dn Type=3
Dn Slope=0.005
Boundary for River Rch & Prof#=UNT0045 IN CHRS,Reach-1,2
Up Type=0
Dn Type=3
Dn Slope=0.005
Boundary for River Rch & Prof#=UNT0045 IN CHRS,Reach-1,3
Up Type=0
Dn Type=3
Dn Slope=0.005
Boundary for River Rch & Prof#=UNT0045 IN CHRS,Reach-1,4
Up Type=0
Dn Type=3
Dn Slope=0.005
Boundary for River Rch & Prof#=UNT0045 IN CHRS,Reach-1,5
Up Type=0
Dn Type=3
Dn Slope=0.005
Boundary for River Rch & Prof#=UNT0045 IN CHRS,Reach-1,6
Up Type=0
Dn Type=3
Dn Slope=0.005
Boundary for River Rch & Prof#=UNT0045 IN CHRS,Reach-1,7
Up Type=0
Dn Type=3
Dn Slope=0.005

--- UNT0045 IN CHRS.g01 (geometry) ---

Geom Title=Existing Conditions

River Reach=UNT0045 IN CHRS,Reach-1
Reach XY= 30
      3461982.11     10605941.64      3461768.55     10606091.73
      3460747.11     10605863.08      3459922.29     10606121.84
      3459731.72     10605912.40      3459167.92     10606019.93
      3458455.11     10605219.10      3458287.17     10605381.39
      3457777.57     10605309.62      3457104.79     10604756.48
      3456873.10     10604867.32      3456105.80     10604533.80
      3455962.45     10604081.09      3455217.48     10603594.68
      3455215.09     10603326.11      3454559.44     10603388.23
      3454462.79     10602745.47      3454216.96     10602580.79
      3454345.68     10602319.65      3454009.13     10602138.02
      3453786.46     10601469.33      3453458.07     10601258.03
      3453586.22     10600950.62      3453320.88     10600935.91
      3452890.08     10600447.86      3452937.18     10600105.67
      3452646.46     10600012.64      3452817.21     10599788.67
      3452375.77     10599620.86      3452482.11     10599331.64

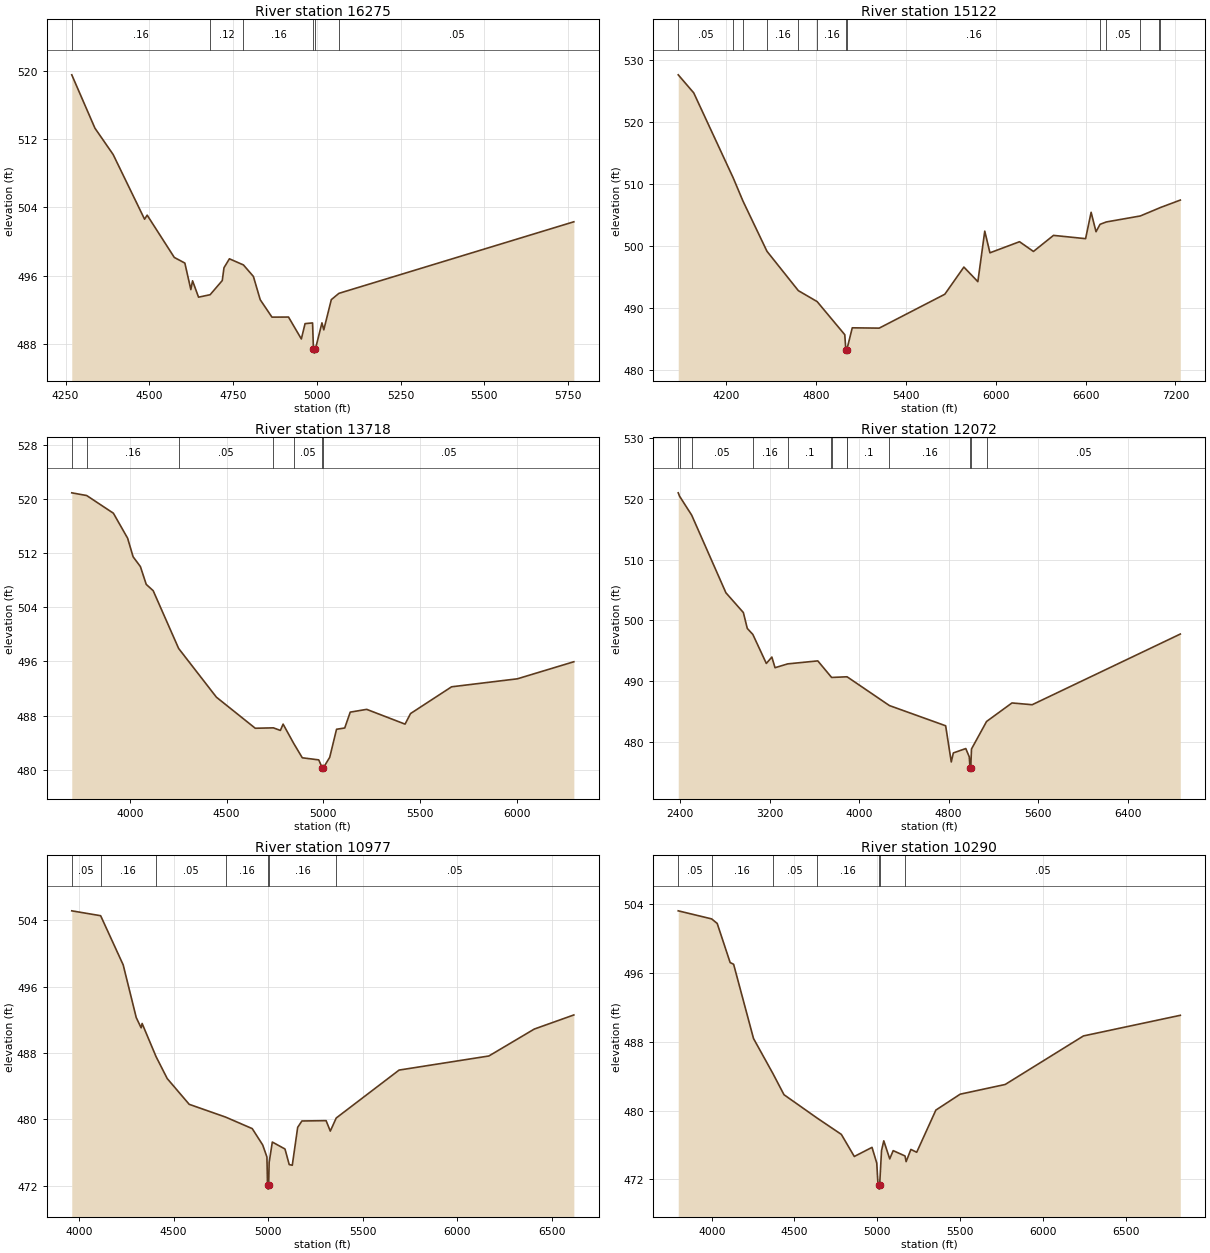
Type RM Length L Ch R = 1,16275,1153,1153,1153
BEGIN DESCRIPTION:
UNT0045 IN CHRS 19.0
END DESCRIPTION:
XS GIS Cut Line= 3
      3461242.11     10605191.62      3461092.11     10605891.64
      3461442.09     10606591.61
#Sta/Elev= 30
  4268.5  519.54  4337.6  513.29  4392.1  510.19  4485.8  502.61  4493.5  503.09
  4574.5  498.13  4606.0  497.47  4623.9  494.36  4629.0  495.39  4646.9  493.47
  4681.5  493.76  4717.7  495.42  4722.8  496.92  4739.0  497.97  4780.9  497.25
  4810.6  495.90  4831.0  493.17  4866.0  491.13  4915.4  491.14  4953.7  488.57
  4964.8  490.37  4987.2  490.45  4989.8  487.41  4992.5  486.91  4995.8  487.41
  5015.2  490.46  5020.7  489.64  5043.1  493.18  5065.9  493.92  5767.0  502.31
#Mann=6,-1,0
  4268.5    0.16       0  4681.5    0.12       0  4780.9    0.16       0
  4989.8    0.07       0  4995.8    0.16       0  5065.9    0.05       0
Bank Sta=4989.8,4995.8
Exp/Cntr=0.3,0.1

Type RM Length L Ch R = 1,15122,1404,1404,1404
BEGIN DESCRIPTION:
UNT0045 IN CHRS 18.0
END DESCRIPTION:
XS GIS Cut Line= 4
      3460358.17     10604908.56      3460097.75     10605744.08
      3460097.75     10606503.63      3460792.11     10608076.79
#Sta/Elev= 30
  3878.3  527.59  3981.9  524.68  4245.9  510.96  4310.8  507.24  4471.3  499.14
  4680.8  492.80  4806.2  491.04  4991.0  485.70  4998.0  483.23  5000.8  482.73
  5004.0  483.23  5041.0  486.81  5221.0  486.76  5659.2  492.22  5786.7  496.60
  5880.0  494.25  5926.2  502.39  5960.8  498.90  6158.3  500.69  6251.5  499.12
  6385.3  501.71  6599.8  501.18  6636.7  505.43  6669.5  502.30  6696.3  503.49
  6737.5  503.87  6965.4  504.84  7091.1  506.11  7097.5  506.18  7232.6  507.40
#Mann=13,-1,0
  3878.3    0.05       0  4245.9    0.16       0  4310.8    0.05       0
  4471.3    0.16       0  4680.8    0.05       0  4806.2    0.16       0
  4998.0    0.07       0  5004.0    0.16       0  6696.3     0.1       0
  6737.5    0.05       0  6965.4     0.1       0  7091.1    0.05       0
  7097.5     0.1       0
Bank Sta=4998,5004
Exp/Cntr=0.3,0.1

Type RM Length L Ch R = 1,13718,1646,1646,1646
BEGIN DESCRIPTION:
UNT0045 IN CHRS 16.0
END DESCRIPTION:
XS GIS Cut Line= 3
      3459772.21     10604821.81      3459294.80     10605722.38
      3458209.75     10606861.68
#Sta/Elev= 30
  3700.6  520.88  3777.7  520.48  3915.5  517.87  3989.0  514.18  4017.3  511.44
  4055.0  509.99  4085.2  507.36  4121.0  506.43  4252.5  497.90  4447.4  490.71
  4648.2  486.12  4741.7  486.18  4777.8  485.80  4791.9  486.73  4845.7  483.93
  4891.0  481.76  4975.9  481.45  4994.0  480.29  4996.8  479.79  5000.0  480.29
  5032.6  481.83  5067.8  485.97  5110.2  486.16  5138.5  488.50  5223.5  488.91
  5421.6  486.73  5450.0  488.29  5661.9  492.24  6001.6  493.42  6293.2  495.94
#Mann=7,-1,0
  3700.6    0.05       0  3777.7    0.16       0  4252.5    0.05       0
  4741.7    0.16       0  4845.7    0.05       0  4994.0   0.035       0
  5000.0    0.05       0
Bank Sta=4994,5000
Exp/Cntr=0.3,0.1

Type RM Length L Ch R = 1,12072,1095,1095,1095
BEGIN DESCRIPTION:
UNT0045 IN CHRS 15.0
END DESCRIPTION:
XS GIS Cut Line= 4
      3459772.20     10603389.51      3458057.82     10604984.53
      3457971.01     10605950.25      3457797.40     10607111.31
#Sta/Elev= 30
  2384.6  520.96  2396.3  520.41  2504.9  517.29  2810.5  504.54  2966.4  501.29
  3001.6  498.68  3051.3  497.69  3171.6  492.93  3221.0  493.98  3249.3  492.23
  3362.6  492.86  3631.4  493.35  3753.0  490.67  3755.6  490.63  3893.3  490.74
  3893.7  490.73  4271.3  486.01  4773.5  482.69  4823.7  476.75  4842.3  478.23
  4953.4  478.95  4984.4  477.59  4991.4  475.74  4994.2  475.24  4997.4  475.74
  5004.4  478.88  5139.2  483.40  5365.9  486.44  5546.6  486.15  6869.8  497.76
#Mann=13,-1,0
  2384.6    0.05       0  2396.3    0.16       0  2504.9    0.05       0
  3051.3    0.16       0  3362.6     0.1       0  3753.0    0.05       0
  3755.6     0.1       0  3893.3    0.05       0  3893.7     0.1       0
  4271.3    0.16       0  4991.4    0.07       0  4997.4    0.16       0
  5139.2    0.05       0
Bank Sta=4991.4,4997.4
Exp/Cntr=0.3,0.1

Type RM Length L Ch R = 1,10977,687,687,687
BEGIN DESCRIPTION:
UNT0045 IN CHRS 14.0
END DESCRIPTION:
XS GIS Cut Line= 3
      3457688.91     10603964.54      3457406.78     10604778.37
      3456603.83     10606384.27
#Sta/Elev= 30
  3960.7  505.14  4113.5  504.55  4232.8  498.62  4301.8  492.27  4327.7  491.03
  4333.0  491.55  4406.2  487.58  4465.7  484.91  4582.1  481.80  4774.7  480.26
  4915.7  478.87  4971.0  476.90  4993.4  475.45  4996.6  472.07  4999.3  471.57
  5002.6  472.07  5005.2  474.80  5022.0  477.25  5089.0  476.41  5111.4  474.53
  5127.6  474.45  5156.1  479.02  5178.5  479.79  5306.5  479.83  5328.8  478.57
  5360.1  480.15  5692.8  485.93  6167.9  487.63  6408.3  490.88  6617.5  492.58
#Mann=7,-1,0
  3960.7    0.05       0  4113.5    0.16       0  4406.2    0.05       0
  4774.7    0.16       0  4996.6    0.07       0  5002.6    0.16       0
  5360.1    0.05       0
Bank Sta=4996.6,5002.6
Exp/Cntr=0.3,0.1

Type RM Length L Ch R = 1,10290,1114,1114,1114
BEGIN DESCRIPTION:
UNT0045 IN CHRS 11.0
END DESCRIPTION:
XS GIS Cut Line= 4
      3457623.83     10603910.28      3456994.45     10604583.06
      3456614.68     10605049.64      3455887.66     10606373.47
#Sta/Elev= 30
  3797.7  503.25  3999.6  502.31  4033.2  501.78  4111.3  497.23  4132.3  497.03
  4252.5  488.39  4369.2  484.33  4436.6  481.85  4636.1  479.14  4783.1  477.23
  4861.4  474.66  4968.4  475.72  4997.1  473.89  5003.6  471.73  5008.5  471.36
  5011.3  470.86  5014.5  471.36  5025.9  475.35  5039.5  476.48  5075.4  474.38
  5096.2  475.34  5167.8  474.72  5174.5  474.06  5203.3  475.48  5238.4  475.15
  5354.2  480.06  5501.1  481.91  5773.0  483.04  6245.8  488.69  6830.9  491.09
#Mann=7,-1,0
  3797.7    0.05       0  3999.6    0.16       0  4369.2    0.05       0
  4636.1    0.16       0  5008.5    0.07       0  5014.5    0.16       0
  5167.8    0.05       0
Bank Sta=5008.5,5014.5
Exp/Cntr=0.3,0.1

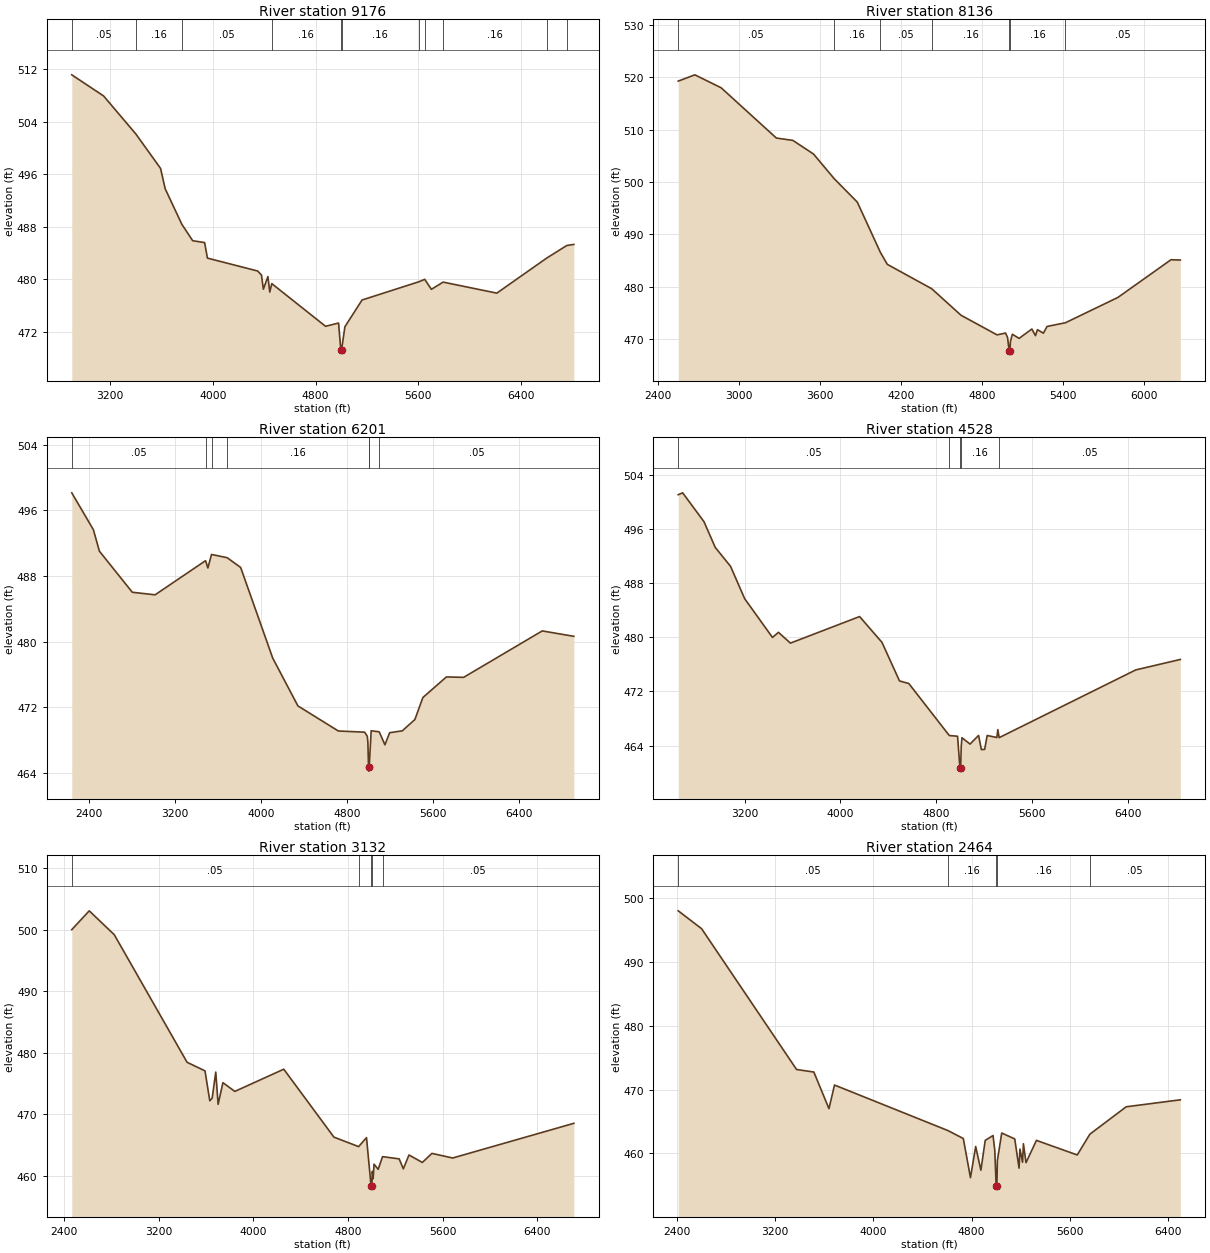
Type RM Length L Ch R = 1,9176,1040,1040,1040
BEGIN DESCRIPTION:
UNT0045 IN CHRS 10.0
END DESCRIPTION:
XS GIS Cut Line= 4
      3457363.41     10602825.21      3456245.75     10604311.79
      3455475.35     10604442.00      3454563.88     10605320.93
#Sta/Elev= 30
  2902.5  511.15  3150.2  507.93  3401.6  502.12  3593.8  496.87  3629.2  493.79
  3759.1  488.36  3843.7  485.85  3936.4  485.57  3958.3  483.20  4349.8  481.23
  4379.0  480.61  4393.6  478.46  4429.0  480.38  4443.5  478.02  4459.4  479.31
  4877.6  472.80  4979.0  473.30  4996.3  469.21  4999.1  468.71  5002.3  469.21
  5028.1  472.73  5161.6  476.81  5605.2  479.60  5649.5  479.96  5701.2  478.44
  5792.4  479.54  6210.6  477.86  6599.2  483.21  6754.8  485.12  6809.9  485.29
#Mann=11,-1,0
  2902.5    0.05       0  3401.6    0.16       0  3759.1    0.05       0
  4459.4    0.16       0  4996.3    0.07       0  5002.3    0.16       0
  5605.2    0.05       0  5649.5     0.1       0  5792.4    0.16       0
  6599.2     0.1       0  6754.8    0.16       0
Bank Sta=4996.3,5002.3
Exp/Cntr=0.3,0.1

Type RM Length L Ch R = 1,8136,1935,1935,1935
BEGIN DESCRIPTION:
UNT0045 IN CHRS 8.0
END DESCRIPTION:
XS GIS Cut Line= 4
      3457428.49     10602347.81      3455583.86     10603573.94
      3455030.48     10603975.42      3454618.15     10604691.56
#Sta/Elev= 30
  2547.3  519.31  2670.3  520.51  2865.8  518.03  3275.4  508.42  3397.9  507.97
  3551.2  505.36  3704.4  500.65  3875.8  496.17  4047.1  486.56  4098.3  484.27
  4428.3  479.60  4645.5  474.53  4912.7  470.78  4975.9  471.13  4990.6  470.28
  5002.3  467.79  5005.1  467.29  5008.3  467.79  5011.5  469.47  5026.2  470.90
  5076.4  470.11  5170.8  471.90  5197.8  470.63  5212.5  471.77  5256.6  471.11
  5283.6  472.39  5420.2  473.10  5809.3  477.94  6203.2  485.15  6272.3  485.09
#Mann=7,-1,0
  2547.3    0.05       0  3704.4    0.16       0  4047.1    0.05       0
  4428.3    0.16       0  5002.3    0.07       0  5008.3    0.16       0
  5420.2    0.05       0
Bank Sta=5002.3,5008.3
Exp/Cntr=0.3,0.1

Type RM Length L Ch R = 1,6201,1673,1673,1673
BEGIN DESCRIPTION:
UNT0045 IN CHRS 5.0
END DESCRIPTION:
XS GIS Cut Line= 4
      3456299.98     10600937.25      3454683.25     10602879.50
      3454184.12     10603063.96      3453370.30     10604452.89
#Sta/Elev= 30
  2237.2  498.15  2438.1  493.66  2494.2  491.04  2800.1  486.03  3012.3  485.72
  3481.4  489.88  3503.1  488.99  3536.9  490.64  3682.8  490.24  3807.8  489.05
  4105.9  478.01  4340.2  472.18  4716.4  469.12  4960.4  468.98  4985.4  468.48
  4990.8  467.77  4997.0  464.73  4999.8  464.23  5003.0  464.73  5021.4  469.15
  5096.3  469.02  5149.3  467.44  5193.0  468.91  5310.7  469.14  5428.0  470.52
  5502.3  473.20  5721.2  475.71  5881.5  475.66  6612.5  481.32  6906.2  480.66
#Mann=7,-1,0
  2237.2    0.05       0  3481.4    0.16       0  3536.9    0.05       0
  3682.8    0.16       0  4997.0    0.07       0  5003.0    0.16       0
  5096.3    0.05       0
Bank Sta=4997,5003
Exp/Cntr=0.3,0.1

Type RM Length L Ch R = 1,4528,1396,1396,1396
BEGIN DESCRIPTION:
UNT0045 IN CHRS 4.0
END DESCRIPTION:
XS GIS Cut Line= 4
      3455865.97     10600687.67      3454043.06     10601620.82
      3453695.84     10602185.06      3453055.66     10603519.67
#Sta/Elev= 30
  2646.5  501.02  2683.5  501.30  2861.2  497.05  2955.6  493.24  3083.3  490.45
  3201.3  485.67  3433.0  479.96  3483.0  480.71  3582.8  479.12  4160.2  483.04
  4347.2  479.23  4493.3  473.54  4570.9  473.16  4909.0  465.48  4977.9  465.38
  4997.6  460.73  5000.4  460.23  5003.6  460.73  5008.8  463.94  5014.6  465.16
  5082.1  464.22  5153.3  465.50  5176.7  463.41  5204.0  463.44  5225.2  465.49
  5305.9  465.19  5314.0  466.35  5325.1  465.17  6465.8  475.17  6837.1  476.71
#Mann=5,-1,0
  2646.5    0.05       0  4909.0    0.16       0  4997.6    0.07       0
  5003.6    0.16       0  5325.1    0.05       0
Bank Sta=4997.6,5003.6
Exp/Cntr=0.3,0.1

Type RM Length L Ch R = 1,3132,668,668,668
BEGIN DESCRIPTION:
UNT0045 IN CHRS 2.0
END DESCRIPTION:
XS GIS Cut Line= 4
      3455898.56     10600448.94      3453587.33     10600741.91
      3453240.11     10601132.54      3452567.72     10602347.19
#Sta/Elev= 30
  2467.0  500.01  2614.6  503.07  2826.3  499.18  3441.2  478.44  3592.4  477.05
  3632.7  472.19  3652.9  472.61  3683.1  476.85  3703.3  471.61  3743.6  475.13
  3844.4  473.71  4257.7  477.32  4681.0  466.28  4889.9  464.73  4956.4  466.19
  4995.2  458.32  4998.0  457.82  5001.2  458.32  5005.8  460.71  5012.5  459.52
  5020.0  461.88  5055.1  461.04  5091.8  463.10  5232.4  462.74  5267.5  461.12
  5315.4  463.37  5427.9  462.16  5509.2  463.63  5684.1  462.88  6707.7  468.52
#Mann=5,-1,0
  2467.0    0.05       0  4889.9    0.16       0  4995.2    0.07       0
  5001.2    0.16       0  5091.8    0.05       0
Bank Sta=4995.2,5001.2
Exp/Cntr=0.3,0.1

Type RM Length L Ch R = 1,2464,863,863,863
BEGIN DESCRIPTION:
UNT0045 IN CHRS 2.1
END DESCRIPTION:
XS GIS Cut Line= 5
      3455551.40     10600209.22      3454421.23     10600094.64
      3453275.39     10600506.10      3452452.48     10601313.39
      3452140.48     10601807.39
#Sta/Elev= 30
  2410.5  497.93  2600.8  495.14  3374.7  473.13  3515.4  472.73  3638.5  467.01
  3683.7  470.70  4607.0  463.59  4733.1  462.34  4791.4  456.22  4833.8  461.09
  4876.3  457.39  4911.6  462.05  4975.3  462.81  4989.4  460.53  5000.6  454.93
  5003.3  454.43  5006.6  454.93  5010.6  458.89  5046.0  463.20  5152.0  462.28
  5187.4  457.71  5194.5  460.69  5215.7  458.63  5222.7  461.53  5244.0  458.57
  5328.9  462.05  5661.2  459.77  5764.2  463.02  6060.2  467.30  6501.0  468.39
#Mann=5,-1,0
  2410.5    0.05       0  4607.0    0.16       0  5000.6    0.07       0
  5006.6    0.16       0  5764.2    0.05       0
Bank Sta=5000.6,5006.6
Exp/Cntr=0.3,0.1

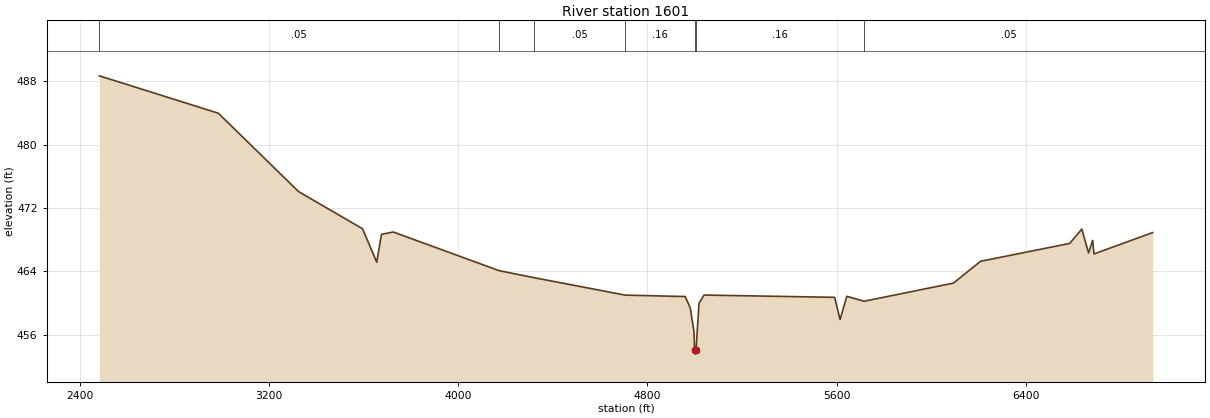
Type RM Length L Ch R = 1,1601,0,0,0
BEGIN DESCRIPTION:
UNT0045 IN CHRS 1.0
END DESCRIPTION:
XS GIS Cut Line= 4
      3455345.17     10599928.11      3453142.46     10599895.56
      3452686.73     10600166.83      3451960.34     10601728.01
#Sta/Elev= 30
  2482.3  488.68  2985.4  483.96  3325.5  474.05  3595.5  469.37  3655.5  465.15
  3675.5  468.66  3725.5  468.96  4172.9  464.08  4321.4  463.19  4706.5  460.99
  4960.1  460.81  4981.5  459.38  4997.1  456.40  4999.9  454.04  5002.7  453.54
  5005.9  454.04  5018.5  459.94  5039.9  461.00  5592.2  460.71  5615.1  457.90
  5643.5  460.84  5716.9  460.22  6094.8  462.51  6209.2  465.26  6586.3  467.52
  6637.6  469.33  6666.0  466.32  6683.4  467.90  6688.9  466.19  6937.5  468.89
#Mann=7,-1,0
  2482.3    0.05       0  4172.9     0.1       0  4321.4    0.05       0
  4706.5    0.16       0  4999.9    0.07       0  5005.9    0.16       0
  5716.9    0.05       0
Bank Sta=4999.9,5005.9
Exp/Cntr=0.3,0.1

Chan Stop Cuts=-1