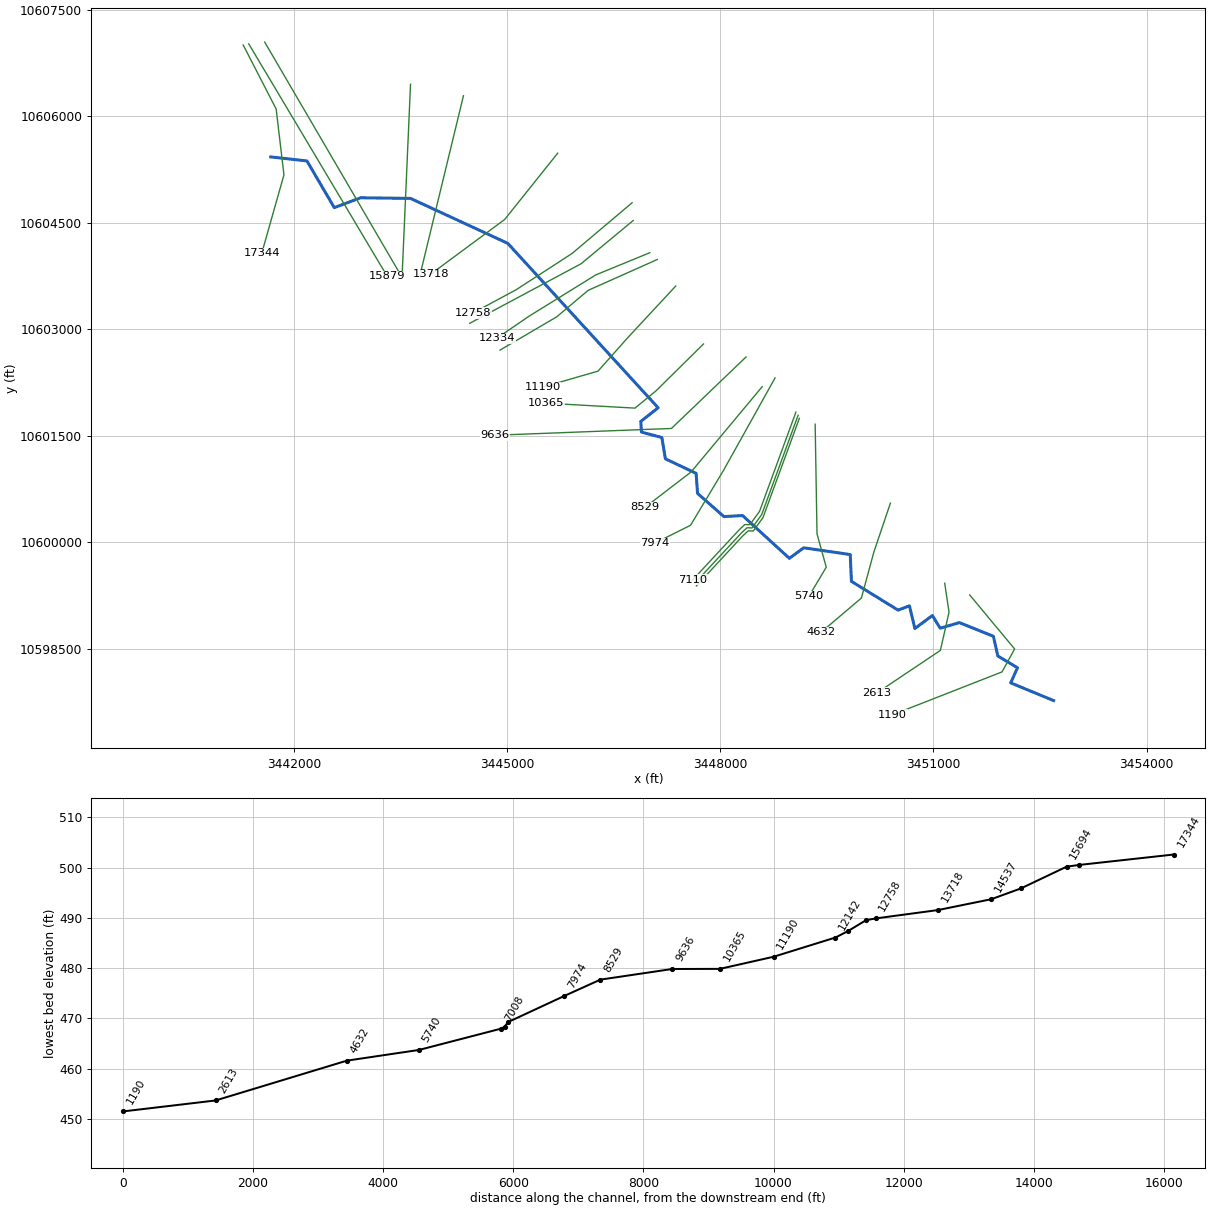
--- UNT0047 IN CHRS.prj (project) ---

Proj Title=UNT0047 IN CHRS Base Level Engineering
Current Plan=p01
Default Exp/Contr=0.3,0.1
English Units
Geom File=g01
Flow File=f01
Plan File=p01
Y Axis Title=Elevation
X Axis Title(PF)=Main Channel Distance
X Axis Title(XS)=Station
BEGIN DESCRIPTION:
UNT0047 IN CHRS
END DESCRIPTION:
DSS Export Rating Curves= 0
DSS Export Rating Curve Sorted= 0
DSS Export Volume Flow Curves= 0
DXF OffsetX= 0
DXF OffsetY= 0
DXF ScaleX= 1
DXF ScaleY= 10

--- UNT0047 IN CHRS.p01 (plan) ---

Plan Title=Multiple Run
Short Identifier=Multiple
Geom File=g01
Flow File=f01
Subcritical Flow
K Sum by GR= 0
Std Step Tol= 0.01
Critical Tol= 0.01
Num of Std Step Trials= 20
Max Error Tol= 0.3
Flow Tol Ratio= 0.001
Split Flow NTrial= 30
Split Flow Tol= 0.02
Split Flow Ratio= 0.02
Log Output Level= 0
Friction Slope Method= 1
Unsteady Friction Slope Method= 2
Unsteady Bridges Friction Slope Method= 1
Parabolic Critical Depth
Global Vel Dist=  1 , 1 , 1
Global Log Level= 0
CheckData=True
Encroach Param= -1, 0, 0, 0
BEGIN DESCRIPTION:
Multiple Run
END DESCRIPTION:

--- UNT0047 IN CHRS.f01 (steady flow) ---

Flow Title=Multiple
Number of Profiles=7
Profile Names=10-year,25-year,50-year,1pct_min,100-year,1pct_plu,500-year
River Rch & RM= UNT0047 IN CHRS,Reach-1,17344
     321     395     447     368     498     674     618
River Rch & RM= UNT0047 IN CHRS,Reach-1,15879
     449     561     643     535     724     979     917
River Rch & RM= UNT0047 IN CHRS,Reach-1,12334
     485     608     699     583     788    1066    1002
River Rch & RM= UNT0047 IN CHRS,Reach-1,8529
     613     778     900     755    1022    1382    1316
Boundary for River Rch & Prof#=UNT0047 IN CHRS,Reach-1,1
Up Type=0
Dn Type=3
Dn Slope=0.005
Boundary for River Rch & Prof#=UNT0047 IN CHRS,Reach-1,2
Up Type=0
Dn Type=3
Dn Slope=0.005
Boundary for River Rch & Prof#=UNT0047 IN CHRS,Reach-1,3
Up Type=0
Dn Type=3
Dn Slope=0.005
Boundary for River Rch & Prof#=UNT0047 IN CHRS,Reach-1,4
Up Type=0
Dn Type=3
Dn Slope=0.005
Boundary for River Rch & Prof#=UNT0047 IN CHRS,Reach-1,5
Up Type=0
Dn Type=3
Dn Slope=0.005
Boundary for River Rch & Prof#=UNT0047 IN CHRS,Reach-1,6
Up Type=0
Dn Type=3
Dn Slope=0.005
Boundary for River Rch & Prof#=UNT0047 IN CHRS,Reach-1,7
Up Type=0
Dn Type=3
Dn Slope=0.005

--- UNT0047 IN CHRS.g01 (geometry) ---

Geom Title=Existing Conditions
Program Version=4.10

River Reach=UNT0047 IN CHRS ,Reach-1
Reach XY= 30
      3441676.25     10605425.79       3442185.2     10605368.86
      3442569.75     10604711.74      3442940.81     10604850.51
      3443642.11     10604841.64      3445010.98     10604208.91
        3447127.     10601893.84      3446883.17     10601702.22
      3446892.11     10601551.64       3447179.2     10601475.11
      3447229.51     10601175.01      3447661.32     10600970.58
      3447681.58     10600688.04      3448052.79     10600361.86
       3448315.3     10600376.36      3448973.82     10599774.13
      3449175.17      10599922.4      3449830.23     10599827.39
      3449846.97     10599449.84      3450503.75     10599044.83
      3450663.48     10599105.91      3450739.61     10598786.03
      3450986.68     10598969.36      3451095.46      10598790.3
      3451366.57     10598869.18      3451844.71      10598676.4
      3451907.12     10598398.89       3452184.2     10598233.92
      3452088.04     10598020.64      3452692.11     10597771.64

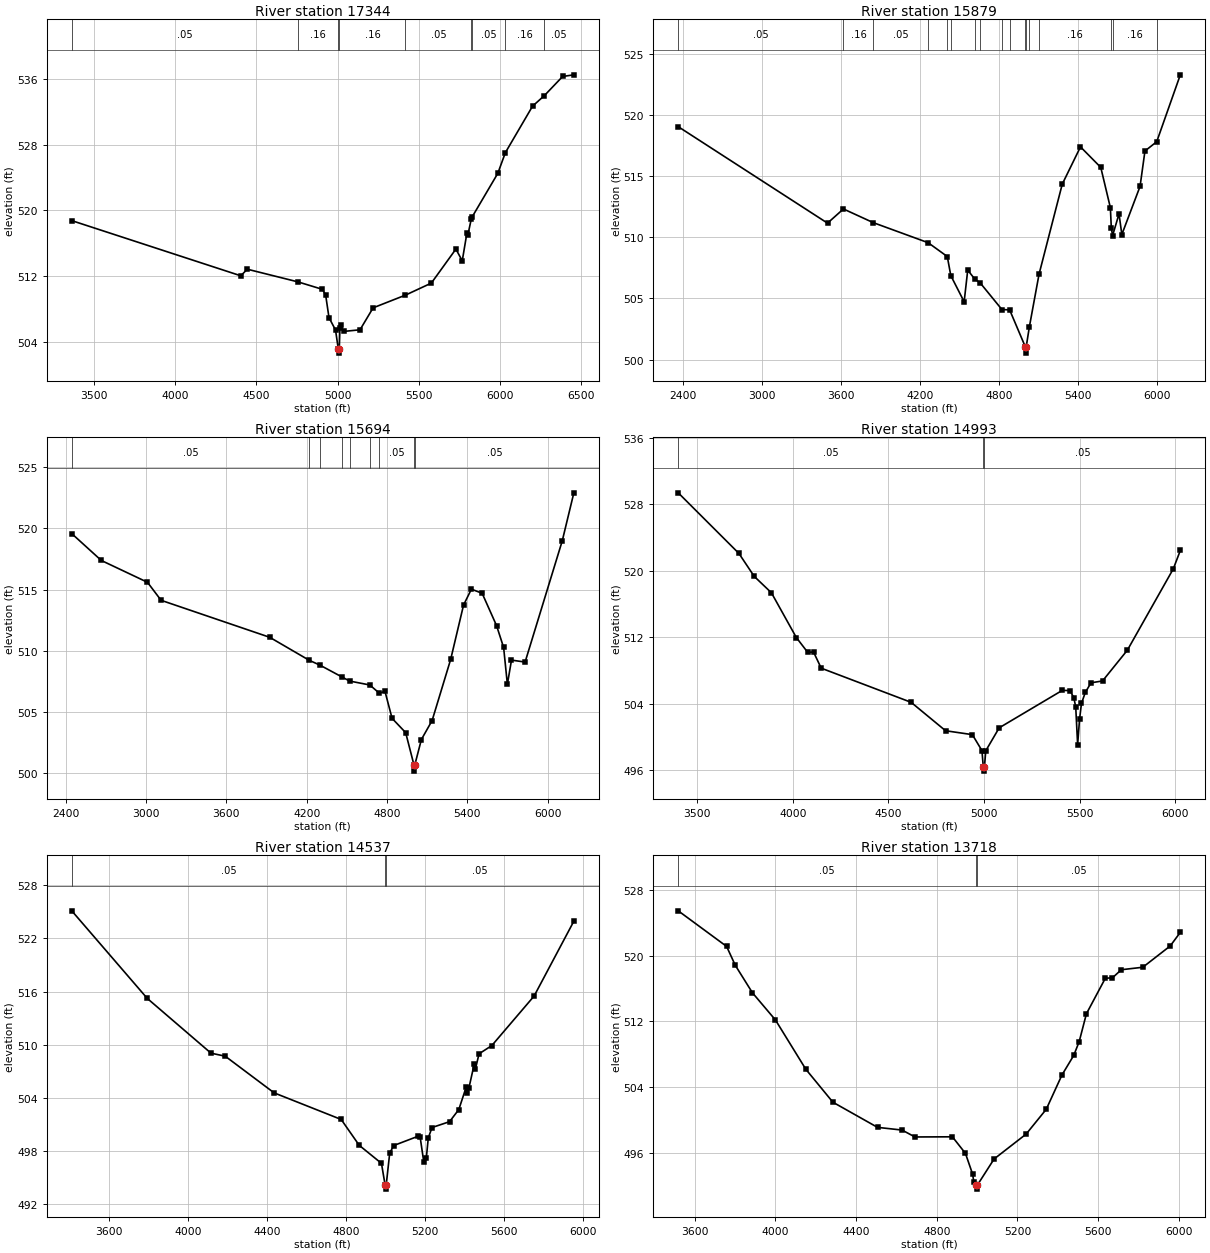
Type RM Length L Ch R = 1 ,17344   ,1465,1465,1465
BEGIN DESCRIPTION:
UNT0047 IN CHRS 31.0
END DESCRIPTION:
XS GIS Cut Line= 4
      3441288.37     10607000.76      3441751.93     10606099.68
      3441861.31      10605172.6       3441548.8     10604068.41
#Sta/Elev= 30
  3361.6  518.74  4403.2  512.03  4443.4  512.83  4755.3  511.29  4906.6  510.38
  4926.4  509.68  4946.9  506.94  4987.2  505.43  5004.3  503.12  5007.1  502.62
  5010.3  503.12  5014.4  505.72  5019.5     506  5037.5  505.26  5138.2  505.46
  5218.8  508.13  5418.4  509.68  5577.7  511.14  5729.1  515.28  5768.2  513.85
    5797  517.24  5802.2  516.94  5824.2  518.97  5829.5   519.2  5987.5   524.5
  6033.9  527.01  6201.6  532.67  6274.8  533.96  6386.9  536.28    6456  536.48
#Mann= 9 ,-1 , 0
  3361.6     .05       0  4755.3     .16       0  5004.3     .07       0
  5010.3     .16       0  5418.4     .05       0  5824.2     .16       0
  5829.5     .05       0  6033.9     .16       0  6274.8     .05       0
Bank Sta=5004.3,5010.3
XS Rating Curve= 0 ,0
Exp/Cntr=0.3,0.1

Type RM Length L Ch R = 1 ,15879   ,185,185,185
BEGIN DESCRIPTION:
UNT0047 IN CHRS 31.1
END DESCRIPTION:
XS GIS Cut Line= 2
      3441366.52     10607016.34      3443314.11     10603746.05
#Sta/Elev= 30
  2366.9  519.05  3498.6  511.16  3619.3  512.32  3845.8   511.2  4261.6  509.56
  4406.6  508.43  4433.3  506.87  4534.4  504.73  4561.6  507.32  4613.9   506.6
  4656.3  506.27  4821.2  504.09  4879.3  504.07  4998.7  501.03  5001.5  500.53
  5004.7  501.03  5028.4  502.65  5102.3  506.99  5278.2  514.35  5416.4   517.4
  5570.2  515.72  5642.9  512.43  5650.2  510.76  5659.8  510.14  5708.5  511.92
  5729.9  510.23  5868.1  514.17  5905.1  517.06  5994.3  517.82  6173.2  523.29
#Mann= 17 ,-1 , 0
  2366.9     .05       0  3619.3     .16       0  3845.8     .05       0
  4261.6     .16       0  4406.6     .05       0  4433.3     .16       0
  4613.9     .05       0  4656.3     .16       0  4821.2     .05       0
  4879.3     .16       0  4998.7     .07       0  5004.7     .16       0
  5028.4     .05       0  5102.3     .16       0  5650.2     .05       0
  5659.8     .16       0  5994.3     .05       0
Bank Sta=4998.7,5004.7
XS Rating Curve= 0 ,0
Exp/Cntr=0.3,0.1

Type RM Length L Ch R = 1 ,15694   ,701,701,701
BEGIN DESCRIPTION:
UNT0047 IN CHRS 29.0
END DESCRIPTION:
XS GIS Cut Line= 2
       3441590.5     10607042.35      3443481.12     10603802.78
#Sta/Elev= 30
  2445.4  519.57  2666.2  517.38  3010.9   515.6  3112.6  514.13  3924.5  511.11
  4220.1  509.23  4299.4  508.84  4461.2  507.89  4521.3  507.54  4671.9  507.22
  4743.2  506.55  4785.3   506.7  4838.2   504.5  4939.9  503.33    5002  500.69
  5004.8  500.19    5008  500.69  5057.3  502.77  5137.5  504.32  5276.4  509.32
  5372.3  513.74    5431  515.04  5511.3   514.7  5618.7  512.07  5671.7  510.28
  5699.7  507.27  5730.4  509.25  5832.1  509.09  6109.9  518.99  6196.3   522.9
#Mann= 9 ,-1 , 0
  2445.4     .05       0  4220.1      .1       0  4299.4     .05       0
  4461.2      .1       0  4521.3     .05       0  4671.9      .1       0
  4743.2     .05       0    5002     .04       0    5008     .05       0
Bank Sta=5002,5008
XS Rating Curve= 0 ,0
Exp/Cntr=0.3,0.1

Type RM Length L Ch R = 1 ,14993   ,456,456,456
BEGIN DESCRIPTION:
UNT0047 IN CHRS 28.0
END DESCRIPTION:
XS GIS Cut Line= 3
      3443642.56     10606448.61      3443527.97     10603834.06
      3443527.97     10603825.12
#Sta/Elev= 30
  3401.2  529.36  3718.5  522.07  3798.5  519.31  3888.6  517.33  4018.8  511.95
  4078.8  510.15  4108.8  510.21  4148.9  508.26  4619.3  504.15  4799.5  500.73
  4939.6  500.26  4989.7  498.34  4996.7  496.37  4999.5  495.87  5002.7  496.37
  5009.7  498.32  5079.8  501.08  5410.1  505.59  5450.1  505.56  5470.2  504.71
  5480.2  503.59  5490.2  499.06  5500.2  502.12  5510.2  504.01  5530.2  505.34
  5560.2   506.5  5620.3  506.72  5750.4  510.43  5990.7  520.22  6027.2  522.42
#Mann= 3 ,-1 , 0
  3401.2     .05       0  4996.7    .035       0  5002.7     .05       0
Bank Sta=4996.7,5002.7
XS Rating Curve= 0 ,0
Exp/Cntr=0.3,0.1

Type RM Length L Ch R = 1 ,14537   ,819,819,819
BEGIN DESCRIPTION:
UNT0047 IN CHRS 26.0
END DESCRIPTION:
XS GIS Cut Line= 2
      3444387.36     10606287.22      3443788.81     10603814.95
#Sta/Elev= 30
    3411  525.12  3793.4  515.24  4116.4  509.06  4188.4  508.72  4436.3  504.58
    4776  501.58  4867.5  498.66    4980  496.63  4998.2  494.22    5001  493.72
  5004.2  494.22  5021.8  497.79  5042.4  498.64  5165.9  499.69  5176.1  499.58
  5194.3   496.8    5207  497.18  5217.3   499.5  5236.1  500.67  5324.9  501.33
  5371.9   502.7  5408.6  505.19  5413.7  504.58  5423.1  505.13  5450.4  507.87
  5455.5  507.23  5474.5  508.99  5539.2  509.92  5753.5  515.51  5954.7  523.95
#Mann= 3 ,-1 , 0
    3411     .05       0  4998.2    .035       0  5004.2     .05       0
Bank Sta=4998.2,5004.2
XS Rating Curve= 0 ,0
Exp/Cntr=0.3,0.1

Type RM Length L Ch R = 1 ,13718   ,960,960,960
BEGIN DESCRIPTION:
UNT0047 IN CHRS 24.0
END DESCRIPTION:
XS GIS Cut Line= 3
      3445713.35     10605477.99      3444968.58     10604545.73
      3443928.19     10603775.84
#Sta/Elev= 30
  3519.3  525.44  3758.9  521.11  3802.1   518.8    3887  515.46    4001  512.15
  4151.2  506.16  4285.6  502.14  4506.6  499.08  4628.2  498.75  4692.2  497.91
  4877.6  497.93  4942.3  495.91  4977.8  493.38    4984   492.4  4995.6  492.06
  4998.4  491.56  5001.6  492.06  5084.2  495.23  5242.9  498.26  5342.6  501.28
  5420.3  505.45  5478.8  507.84  5505.8  509.52  5541.6  512.91  5635.3  517.23
  5670.7  517.29  5714.6  518.27    5821  518.57  5956.7  521.16  6006.8  522.82
#Mann= 3 ,-1 , 0
  3519.3     .05       0  4995.6    .035       0  5001.6     .05       0
Bank Sta=4995.6,5001.6
XS Rating Curve= 0 ,0
Exp/Cntr=0.3,0.1

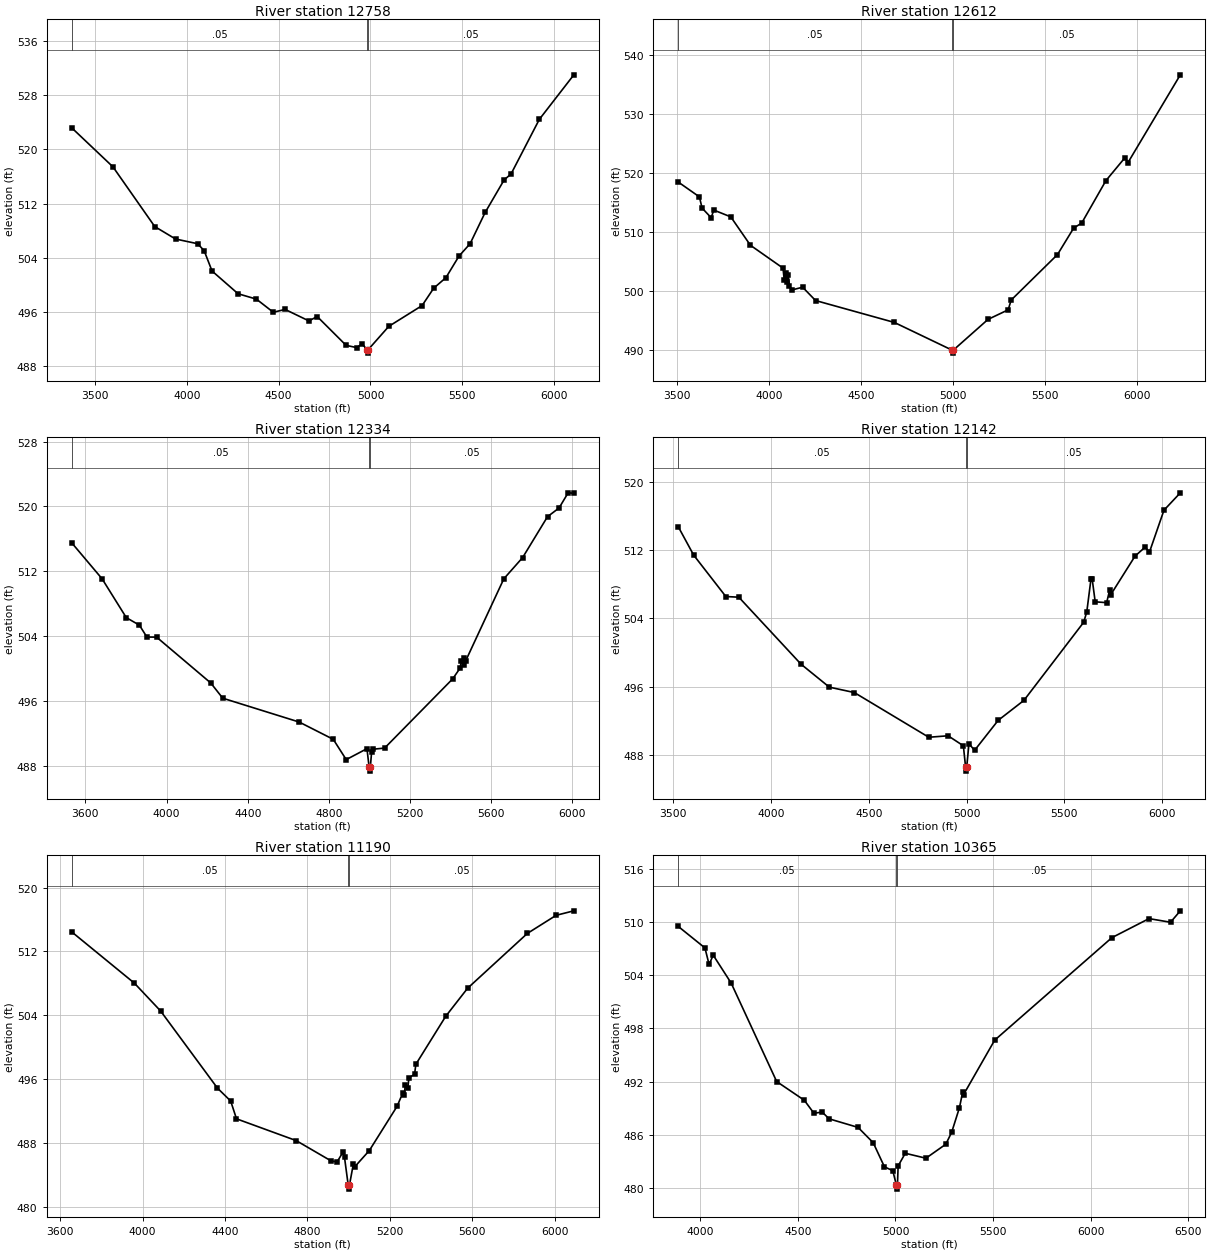
Type RM Length L Ch R = 1 ,12758   ,146,146,146
BEGIN DESCRIPTION:
UNT0047 IN CHRS 22.0
END DESCRIPTION:
XS GIS Cut Line= 4
      3446760.29     10604780.14       3445916.5     10604066.57
      3445130.04     10603556.15       3444520.7     10603228.04
#Sta/Elev= 30
    3373  523.19  3597.5  517.42    3825   508.6  3938.1  506.76    4059  506.06
  4094.1  505.03    4137  502.03  4278.7  498.67  4378.8  497.87  4470.7  495.93
    4535  496.35  4664.8  494.65  4709.8   495.3  4867.2  491.04  4924.6  490.71
  4954.9  491.27    4981  490.39  4983.8  489.89    4987  490.39  5099.9  493.85
  5281.1  496.92  5344.4  499.49    5411  501.05  5482.5  504.25  5542.5  506.06
  5624.5  510.68  5728.3  515.51  5765.4  516.36  5919.8  524.45  6107.7  531.03
#Mann= 3 ,-1 , 0
    3373     .05       0    4981    .035       0    4987     .05       0
Bank Sta=4981,4987
XS Rating Curve= 0 ,0
Exp/Cntr=0.3,0.1

Type RM Length L Ch R = 1 ,12612   ,278,278,278
BEGIN DESCRIPTION:
UNT0047 IN CHRS 21.0
END DESCRIPTION:
XS GIS Cut Line= 3
       3446775.9     10604530.13       3446041.5     10603920.73
      3444475.46     10603083.08
#Sta/Elev= 30
  3507.2  518.46  3622.4  515.95  3636.8  514.06  3686.2  512.43  3700.6  513.72
    3793  512.57  3899.8  507.77  4076.9  503.91  4083.9  501.84  4091.2  503.06
  4097.7   501.5  4105.6  502.78  4112.1  500.82  4126.4  500.23  4183.7  500.68
    4254  498.43  4682.1  494.73  4996.9  490.04  4999.6  489.54  5002.9  490.04
  5191.7  495.24  5301.4  496.86  5317.7  498.51  5569.6   506.2  5657.4  510.67
  5701.3  511.53    5833   518.7  5936.9  522.59  5953.2  521.76  6237.5  536.58
#Mann= 3 ,-1 , 0
  3507.2     .05       0  4996.9    .035       0  5002.9     .05       0
Bank Sta=4996.9,5002.9
XS Rating Curve= 0 ,0
Exp/Cntr=0.3,0.1

Type RM Length L Ch R = 1 ,12334   ,192,192,192
BEGIN DESCRIPTION:
UNT0047 IN CHRS 20.0
END DESCRIPTION:
XS GIS Cut Line= 4
      3447010.25     10604076.98      3446249.83     10603764.48
      3445307.13     10603181.15      3444859.21     10602873.86
#Sta/Elev= 30
  3532.8  515.51  3682.2  511.08  3801.6  506.29  3865.9  505.37  3902.9   503.9
  3950.8  503.89  4217.5  498.24  4276.8  496.36  4653.5  493.42  4821.3  491.29
  4885.1  488.79  4987.3  490.14  4997.9  487.87  5000.7  487.37  5003.9  487.87
  5010.4  489.77  5016.3  490.07  5074.2  490.21  5409.9  498.75  5445.9  500.06
  5452.4  500.92  5463.5  500.45  5467.5  501.26  5473.6  500.96  5661.7  511.08
  5754.4   513.7    5877  518.74  5933.8  519.81  5978.5  521.68  6006.7  521.63
#Mann= 3 ,-1 , 0
  3532.8     .05       0  4997.9    .035       0  5003.9     .05       0
Bank Sta=4997.9,5003.9
XS Rating Curve= 0 ,0
Exp/Cntr=0.3,0.1

Type RM Length L Ch R = 1 ,12142   ,952,952,952
BEGIN DESCRIPTION:
UNT0047 IN CHRS 19.0
END DESCRIPTION:
XS GIS Cut Line= 4
      3447114.37     10603981.04      3446142.19     10603547.03
      3445699.49     10603173.77      3444902.29     10602705.85
#Sta/Elev= 30
  3525.3  514.73  3604.3   511.4  3768.7  506.55  3835.2  506.47  4153.4  498.62
  4298.2  495.93  4425.8   495.3  4806.8  490.06  4905.7  490.23  4983.7  489.06
    4995  486.59  4997.8  486.09    5001  486.59  5012.3  489.32  5040.9  488.52
  5161.8  492.04  5293.5  494.38  5599.4  503.54  5615.1  504.77  5636.5   508.6
  5642.3  508.65    5658  505.93  5716.6  505.83  5732.3  507.34  5738.1  506.78
  5861.7  511.28    5914  512.35  5935.4  511.74  6009.7  516.66  6093.4   518.7
#Mann= 3 ,-1 , 0
  3525.3     .05       0    4995    .035       0    5001     .05       0
Bank Sta=4995,5001
XS Rating Curve= 0 ,0
Exp/Cntr=0.3,0.1

Type RM Length L Ch R = 1 ,11190   ,825,825,825
BEGIN DESCRIPTION:
UNT0047 IN CHRS 18.0
END DESCRIPTION:
XS GIS Cut Line= 4
      3447374.85     10603607.82      3446697.75     10602878.63
      3446281.08     10602409.88      3445499.87      10602184.2
#Sta/Elev= 30
  3656.8  514.45  3960.4  508.04  4087.9  504.55  4363.5   494.9  4427.5  493.29
  4455.8  491.06  4745.7  488.33  4915.4  485.78  4943.9  485.68  4972.3  486.88
  4979.8  486.23  4997.7  482.76  5000.5  482.26  5003.7  482.76  5022.5  485.38
  5029.2  485.05  5100.2  487.09  5234.9  492.63  5263.3  494.35    5270  494.01
  5274.5  495.33  5286.9  494.96  5292.2   496.2  5319.6  496.63  5325.8  497.88
  5470.7  503.89  5576.8   507.4  5866.6  514.26  6006.4  516.53  6092.2  517.09
#Mann= 3 ,-1 , 0
  3656.8     .05       0  4997.7     .03       0  5003.7     .05       0
Bank Sta=4997.7,5003.7
XS Rating Curve= 0 ,0
Exp/Cntr=0.3,0.1

Type RM Length L Ch R = 1 ,10365   ,729,729,729
BEGIN DESCRIPTION:
UNT0047 IN CHRS 16.0
END DESCRIPTION:
XS GIS Cut Line= 4
      3447765.48     10602791.85      3447097.06      10602132.1
      3446801.92     10601889.05      3445551.96     10601958.49
#Sta/Elev= 30
  3886.5  509.52  4023.4  507.09  4044.6  505.22  4065.8  506.27  4157.8  503.12
  4391.1     492  4532.5  489.89    4582  488.42  4624.4  488.55  4659.8  487.79
  4808.3  486.82  4885.9  485.09  4943.3  482.37  4986.3  481.93  5004.1  480.35
  5006.9  479.85  5010.1  480.35  5013.6  482.47  5050.2   483.9    5156  483.34
  5257.9  484.92    5288  486.27    5328  489.06    5344  490.77    5349  490.53
  5508.3  496.67  6109.2  508.25  6299.5   510.4  6409.7  509.99  6459.9  511.28
#Mann= 3 ,-1 , 0
  3886.5     .05       0  5004.1    .035       0  5010.1     .05       0
Bank Sta=5004.1,5010.1
XS Rating Curve= 0 ,0
Exp/Cntr=0.3,0.1

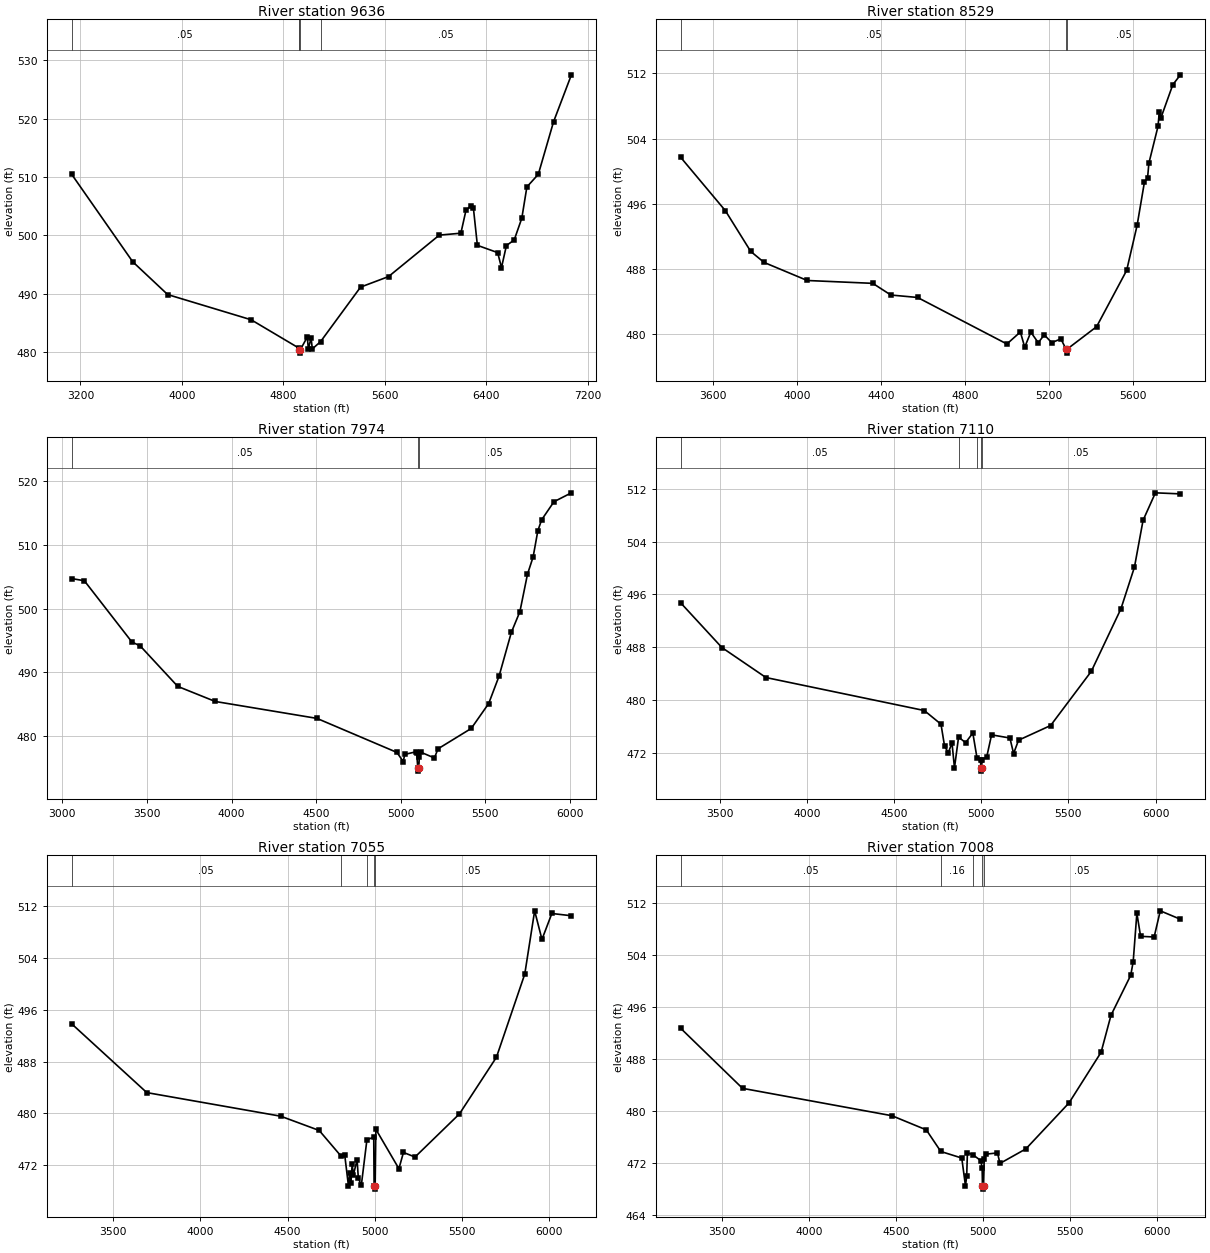
Type RM Length L Ch R = 1 ,9636    ,1107,1107,1107
BEGIN DESCRIPTION:
UNT0047 IN CHRS 14.0
END DESCRIPTION:
XS GIS Cut Line= 3
      3448364.42     10602609.54      3447314.07     10601602.59
      3444831.46     10601507.11
#Sta/Elev= 30
  3131.1  510.49  3612.2   495.5    3888  489.87  4545.9  485.55  4919.5  480.73
  4925.4  480.33  4928.1  479.83  4931.4  480.33  4988.4  482.58  4997.3  480.58
  5018.4  482.42  5028.4  480.55  5093.6  481.81  5408.7  491.15  5628.9  492.95
  6029.2  500.06  6199.3  500.39  6239.3  504.29  6279.4  505.11  6298.2  504.68
  6329.4  498.31  6489.5  497.06  6519.5  494.49  6558.4  498.28  6619.6  499.22
  6679.7  502.96  6719.7  508.32  6809.8  510.49  6929.9  519.49  7070.6  527.54
#Mann= 5 ,-1 , 0
  3131.1     .05       0  4919.5     .16       0  4925.4     .07       0
  4931.4     .16       0  5093.6     .05       0
Bank Sta=4925.4,4931.4
XS Rating Curve= 0 ,0
Exp/Cntr=0.3,0.1

Type RM Length L Ch R = 1 ,8529    ,555,555,555
BEGIN DESCRIPTION:
UNT0047 IN CHRS 12.0
END DESCRIPTION:
XS GIS Cut Line= 3
       3448592.1     10602191.63      3447592.11     10600991.64
      3446942.11     10600491.64
#Sta/Elev= 30
  3445.9   501.7  3658.7  495.17  3779.8  490.17  3843.6  488.82  4049.2  486.61
  4361.6  486.26  4447.6  484.83  4575.1  484.53  5000.8  478.83    5065   480.3
  5085.8  478.44  5114.9  480.28  5150.2  478.99  5179.2  479.95  5214.5  478.99
  5258.1  479.46  5282.5  478.21  5285.2  477.71  5288.5  478.21  5428.4  480.95
  5571.6  487.84  5621.4  493.35  5656.7  498.71  5671.2  499.14  5677.6  500.98
  5721.1  505.49  5727.4  507.29  5735.6  506.58  5791.7   510.6    5828  511.81
#Mann= 3 ,-1 , 0
  3445.9     .05       0  5282.5     .03       0  5288.5     .05       0
Bank Sta=5282.5,5288.5
XS Rating Curve= 0 ,0
Exp/Cntr=0.3,0.1

Type RM Length L Ch R = 1 ,7974    ,864,864,864
BEGIN DESCRIPTION:
UNT0047 IN CHRS 11.0
END DESCRIPTION:
XS GIS Cut Line= 4
       3448772.4     10602314.39      3448051.92     10601020.99
      3447583.17     10600239.74      3447079.71     10599988.01
#Sta/Elev= 30
  3054.7  504.73  3129.7  504.39  3410.9  494.76  3460.1  494.14  3681.9  487.78
  3903.6  485.41  4504.9  482.75  4977.8   477.4  5014.8  475.97  5024.3  477.09
  5088.6  477.49  5094.4  477.34  5101.2  474.96  5103.9  474.46  5107.2  474.96
    5110  476.75  5117.6  477.45  5199.2  476.53  5220.8  477.97  5417.1  481.17
  5520.3  485.09  5581.7  489.41  5654.4  496.29  5704.7  499.53  5749.5  505.41
  5782.9  508.13  5810.9  512.26  5833.3  513.97    5906  516.81  6009.2  518.21
#Mann= 3 ,-1 , 0
  3054.7     .05       0  5101.2    .035       0  5107.2     .05       0
Bank Sta=5101.2,5107.2
XS Rating Curve= 0 ,0
Exp/Cntr=0.3,0.1

Type RM Length L Ch R = 1 ,7110    ,55,55,55
BEGIN DESCRIPTION:
UNT0047 IN CHRS 7.0
END DESCRIPTION:
XS GIS Cut Line= 6
      3449066.33     10601833.71      3448554.16      10600436.1
      3448418.46     10600248.02      3448346.41     10600249.76
      3448270.02     10600178.58      3447616.61     10599474.25
#Sta/Elev= 30
  3275.4  494.72  3511.9  487.96  3764.7  483.42  4673.1  478.43    4769  476.36
  4789.7  473.02  4811.1  472.06  4832.2  473.53  4846.3  469.76    4870  474.42
  4909.8  473.56  4951.7  475.02  4975.7  471.25  4996.6  470.96    4997  469.76
  4999.8  469.26    5003  469.76  5004.1  470.96  5031.5  471.42  5059.2  474.75
  5164.5  474.27  5185.6  471.92    5214  473.94    5398  476.16  5631.5  484.36
  5801.5  493.82  5879.1  500.13  5928.5  507.21  5999.3  511.37  6142.9  511.21
#Mann= 5 ,-1 , 0
  3275.4     .05       0    4870     .16       0  4975.7     .05       0
    4997    .035       0    5003     .05       0
Bank Sta=4997,5003
XS Rating Curve= 0 ,0
Exp/Cntr=0.3,0.1

Type RM Length L Ch R = 1 ,7055    ,47,47,47
BEGIN DESCRIPTION:
UNT0047 IN CHRS 7.1
END DESCRIPTION:
XS GIS Cut Line= 6
       3449096.7     10601788.09      3448584.55     10600390.53
      3448448.84     10600202.45      3448376.79     10600204.19
       3448300.4     10600133.01      3447646.83      10599428.5
#Sta/Elev= 30
  3261.4  493.83  3692.6  483.22  4461.1  479.58  4681.9  477.38  4804.5  473.51
  4828.7  473.52  4849.8  468.83    4857  470.89  4863.9  469.24  4871.1  472.18
  4878.1  470.54  4899.4  472.84  4906.4  470.05  4923.5   468.9  4955.7  475.94
  4994.8  476.35    4997  468.83  4999.8  468.33    5003  468.83  5006.9  477.57
  5139.3  471.48  5165.4  473.99  5231.7  473.28  5486.5  479.93  5698.9  488.67
  5861.5   501.5  5918.2  511.26  5960.2  506.85  6016.9  510.85  6129.1   510.5
#Mann= 5 ,-1 , 0
  3261.4     .05       0  4804.5     .16       0  4955.7     .05       0
    4997    .035       0    5003     .05       0
Bank Sta=4997,5003
XS Rating Curve= 0 ,0
Exp/Cntr=0.3,0.1

Type RM Length L Ch R = 1 ,7008    ,1268,1268,1268
BEGIN DESCRIPTION:
UNT0047 IN CHRS 7.2
END DESCRIPTION:
XS GIS Cut Line= 6
      3449114.04     10601744.65      3448601.91     10600347.13
       3448466.2     10600159.05      3448394.15     10600160.78
      3448317.76      10600089.6      3447664.77     10599385.72
#Sta/Elev= 30
  3265.7  492.75  3620.4   483.5  4477.6  479.28  4674.7   477.1  4757.9  473.77
  4878.1  472.76  4899.4  468.47  4906.4     470  4910.5  473.57  4941.8  473.27
  4986.5  472.38  4994.9   471.3    4997  468.47  4999.8  467.97    5003  468.47
    5007  472.67    5017  473.36  5083.1  473.55  5097.2  471.93  5245.9  474.17
  5493.3  481.25  5677.4  489.06  5734.1  494.75  5847.4  500.92  5861.5  503.02
  5882.6  510.48    5904  506.92  5981.7  506.82  6016.9  510.85  6132.5  509.55
#Mann= 5 ,-1 , 0
  3265.7     .05       0  4757.9     .16       0  4941.8     .05       0
    4997    .035       0    5003     .05       0
Bank Sta=4997,5003
XS Rating Curve= 0 ,0
Exp/Cntr=0.3,0.1

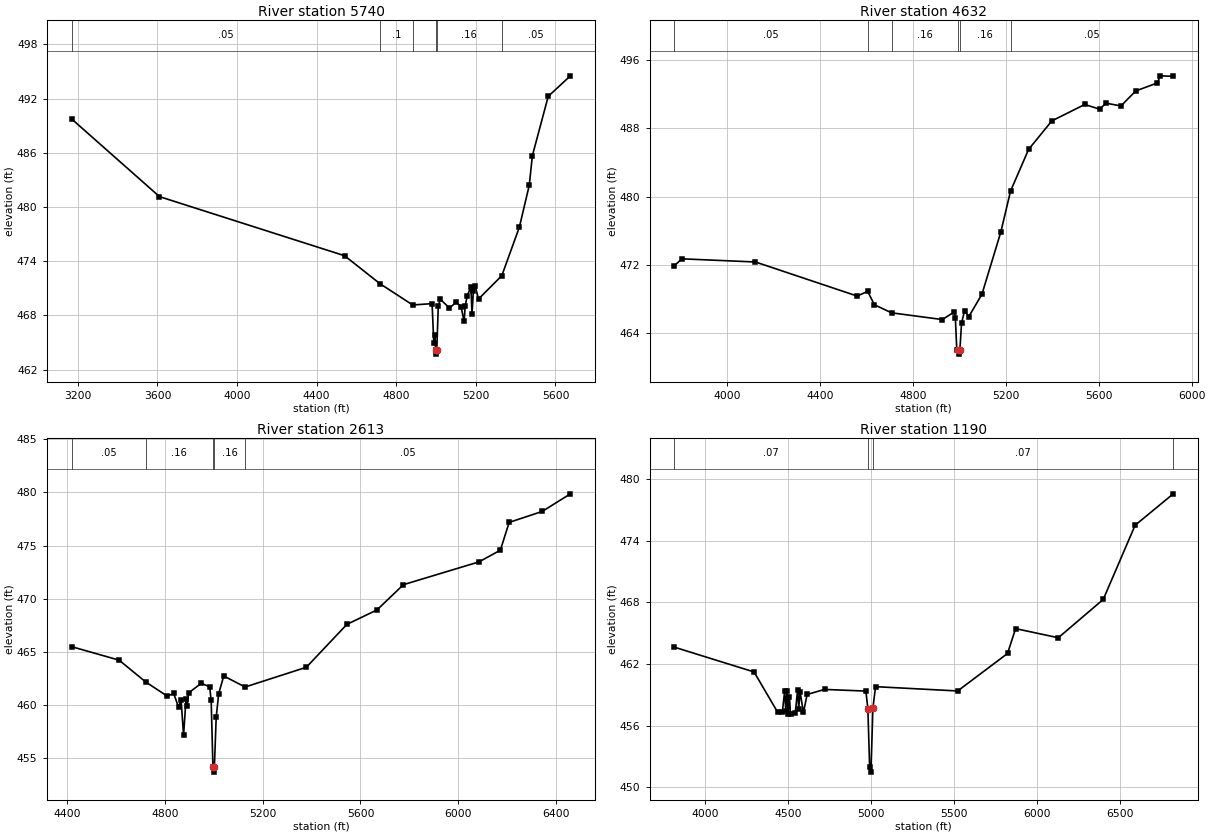
Type RM Length L Ch R = 1 ,5740    ,1108,1108,1108
BEGIN DESCRIPTION:
UNT0047 IN CHRS 6.0
END DESCRIPTION:
XS GIS Cut Line= 4
      3449336.64     10601663.31      3449362.68     10600118.22
      3449492.89     10599649.47      3449249.84     10599241.49
#Sta/Elev= 30
  3168.4  489.74  3610.1  481.14  4540.3   474.6  4717.8  471.51  4882.5  469.15
    4980   469.3  4988.5  464.98  4993.7  465.78  4997.8  464.21  5000.5  463.71
  5003.8  464.21  5011.1  469.02  5021.5  469.78  5067.4  468.81  5101.6  469.46
  5125.3  468.97  5141.1  467.33  5146.2     469  5156.4  470.15  5175.3  471.17
  5180.5  468.11  5187.6  470.69  5196.5  471.25  5213.3  469.81  5330.4  472.39
  5418.8  477.77  5468.4   482.4    5484  485.67  5563.8  492.24  5675.1  494.51
#Mann= 6 ,-1 , 0
  3168.4     .05       0  4717.8      .1       0  4882.5     .16       0
  4997.8     .07       0  5003.8     .16       0  5330.4     .05       0
Bank Sta=4997.8,5003.8
XS Rating Curve= 0 ,0
Exp/Cntr=0.3,0.1

Type RM Length L Ch R = 1 ,4632    ,2019,2019,2019
BEGIN DESCRIPTION:
UNT0047 IN CHRS 4.0
END DESCRIPTION:
XS GIS Cut Line= 4
      3450395.66     10600552.23      3450161.29      10599857.8
      3449987.68     10599215.44      3449415.97     10598730.35
#Sta/Elev= 30
  3772.6  471.93  3804.9  472.72  4121.5  472.35  4559.2  468.37  4604.7  468.91
  4633.8  467.35  4707.4  466.41  4926.2  465.62  4977.2  466.51  4982.4  465.81
  4988.4   462.1  4995.8  462.08  4998.5  461.58  5001.8  462.08  5009.1  465.21
  5022.2  466.66  5040.2  465.96  5096.8  468.58  5178.1  475.85    5220  480.64
  5297.8  485.51  5397.8  488.84  5539.5  490.76  5603.2  490.22  5631.7  490.91
  5695.4  490.59  5759.1  492.34  5851.4  493.27  5865.7  494.11  5920.7  494.05
#Mann= 6 ,-1 , 0
  3772.6     .05       0  4604.7      .1       0  4707.4     .16       0
  4995.8     .07       0  5001.8     .16       0    5220     .05       0
Bank Sta=4995.8,5001.8
XS Rating Curve= 0 ,0
Exp/Cntr=0.3,0.1

Type RM Length L Ch R = 1 ,2613    ,1423,1423,1423
BEGIN DESCRIPTION:
UNT0047 IN CHRS 2.0
END DESCRIPTION:
XS GIS Cut Line= 4
      3451159.56     10599423.75      3451220.32     10599015.78
      3451098.79     10598477.59      3450205.93     10597879.46
#Sta/Elev= 30
  4419.1  465.47  4613.3   464.2  4722.3  462.14  4810.1  460.81  4836.3  461.06
  4856.3  459.76  4866.6  460.45  4876.8  457.11  4886.8  460.56  4891.9  459.88
  4897.3  461.11  4948.6  462.01  4983.4   461.7  4989.6   460.4  4996.8  454.15
  4999.6  453.65  5002.8  454.15  5010.1   458.8  5020.3  461.03  5040.9  462.71
  5128.3  461.67  5378.7  463.53  5544.3  467.57  5667.3  468.93  5775.4  471.31
  6084.6  473.46  6171.7  474.56  6207.7  477.18  6342.8  478.21    6458  479.87
#Mann= 5 ,-1 , 0
  4419.1     .05       0  4722.3     .16       0  4996.8     .07       0
  5002.8     .16       0  5128.3     .05       0
Bank Sta=4996.8,5002.8
XS Rating Curve= 0 ,0
Exp/Cntr=0.3,0.1

Type RM Length L Ch R = 1 ,1190    ,0,0,0
BEGIN DESCRIPTION:
UNT0047 IN CHRS 1.0
END DESCRIPTION:
XS GIS Cut Line= 4
      3451511.56     10599258.43      3452143.49     10598498.03
      3451966.41     10598175.11      3450425.97     10597571.43
#Sta/Elev= 30
  3812.8  463.63  4293.5  461.22  4435.5  457.31  4464.1  457.31  4478.4  459.39
  4484.9  457.38  4492.7  459.38  4499.2  457.15  4507.1  458.81  4513.6  457.08
  4542.2  457.23  4556.5  459.47    4563  457.61  4570.9  459.29  4591.7  457.28
  4613.8  459.03  4719.3  459.52  4968.5  459.36 4980.48  457.66  4991.3  451.97
  4999.2  451.47 5010.73  457.68    5027  459.79  5522.7  459.37  5823.8  463.02
  5872.5  465.44  6130.3  464.55  6401.6  468.28  6594.1   475.5  6824.3  478.56
#Mann= 4 ,-1 , 0
  3812.8     .07       0 4980.48     .04       0 5010.73     .07       0
  6824.3     .05       0
Bank Sta=4980.48,5010.73
XS Rating Curve= 0 ,0
Exp/Cntr=0.3,0.1

Chan Stop Cuts=-1
Use User Specified Reach Order=0
Composite Channel Slope=5