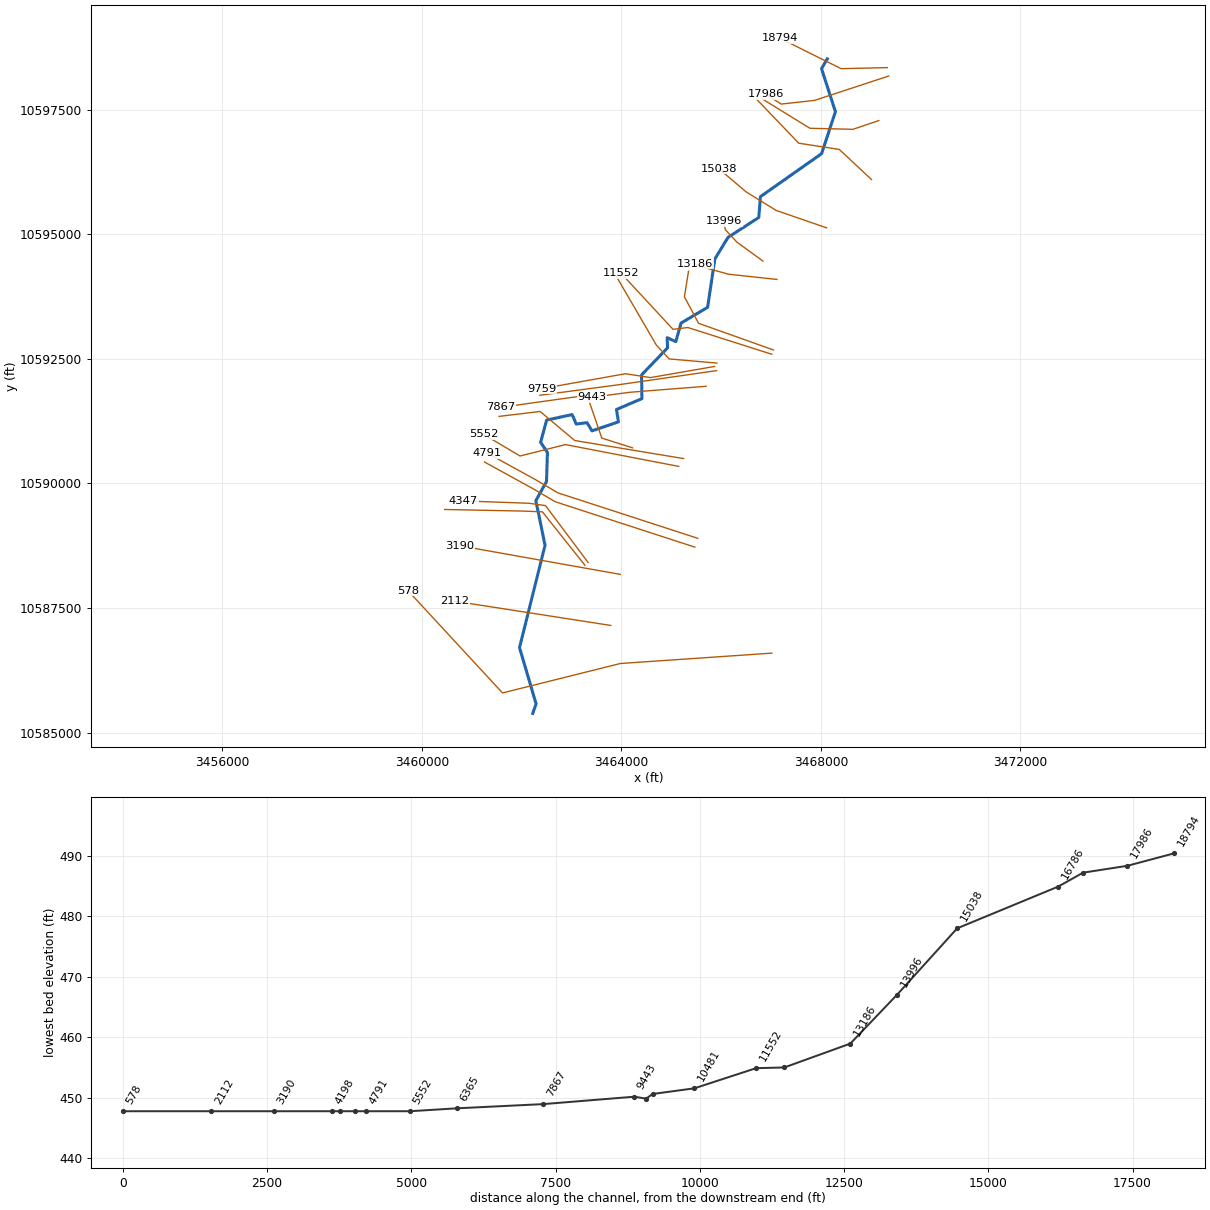
--- UNT0049 IN CHRS.prj (project) ---

Proj Title=UNT0049 IN CHRS Base Level Engineering
Current Plan=p01
Default Exp/Contr=0.3,0.1
English Units
Geom File=g01
Flow File=f01
Plan File=p01
BEGIN DESCRIPTION:
UNT0049 IN CHRS
END DESCRIPTION:

--- UNT0049 IN CHRS.p01 (plan) ---

Plan Title=Multiple Run
Short Identifier=Multiple
Geom File=g01
Flow File=f01
Subcritical Flow
K Sum by GR= 0
Std Step Tol= 0.01
Critical Tol= 0.01
Num of Std Step Trials= 20
Max Error Tol= 0.3
Flow Tol Ratio= 0.001
Split Flow NTrial= 30
Split Flow Tol= 0.02
Split Flow Ratio= 0.02
Log Output Level= 0
Friction Slope Method= 1
Unsteady Friction Slope Method= 2
Unsteady Bridges Friction Slope Method= 1
Parabolic Critical Depth
Global Vel Dist=  1 , 1 , 1
Global Log Level= 0
CheckData=True
Encroach Param= -1, 0, 0, 0
BEGIN DESCRIPTION:
Multiple Run
END DESCRIPTION:

--- UNT0049 IN CHRS.f01 (steady flow) ---

Flow Title=Multiple
Number of Profiles=7
Profile Names=10-year,25-year,50-year,1pct_min,100-year,1pct_plu,500-year
River Rch & RM= UNT0049 IN CHRS,Reach-1,18794
     440     552     635     531     718     970     915
River Rch & RM= UNT0049 IN CHRS,Reach-1,15038
     693     891    1041     883    1194    1615    1570
River Rch & RM= UNT0049 IN CHRS,Reach-1,9443
     692     888    1036     878    1187    1605    1555
River Rch & RM= UNT0049 IN CHRS,Reach-1,6365
     852    1105    1296    1105    1494    2020    1980
River Rch & RM= UNT0049 IN CHRS,Reach-1,5552
     901    1170    1375    1172    1585    2144    2105
River Rch & RM= UNT0049 IN CHRS,Reach-1,4347
     952    1234    1448    1232    1666    2253    2203
Boundary for River Rch & Prof#=UNT0049 IN CHRS,Reach-1,1
Up Type=0
Dn Type=3
Dn Slope=0.005
Boundary for River Rch & Prof#=UNT0049 IN CHRS,Reach-1,2
Up Type=0
Dn Type=3
Dn Slope=0.005
Boundary for River Rch & Prof#=UNT0049 IN CHRS,Reach-1,3
Up Type=0
Dn Type=3
Dn Slope=0.005
Boundary for River Rch & Prof#=UNT0049 IN CHRS,Reach-1,4
Up Type=0
Dn Type=3
Dn Slope=0.005
Boundary for River Rch & Prof#=UNT0049 IN CHRS,Reach-1,5
Up Type=0
Dn Type=3
Dn Slope=0.005
Boundary for River Rch & Prof#=UNT0049 IN CHRS,Reach-1,6
Up Type=0
Dn Type=3
Dn Slope=0.005
Boundary for River Rch & Prof#=UNT0049 IN CHRS,Reach-1,7
Up Type=0
Dn Type=3
Dn Slope=0.005

--- UNT0049 IN CHRS.g01 (geometry) ---

Geom Title=Existing Conditions

River Reach=UNT0049 IN CHRS,Reach-1
Reach XY= 30
      3468128.40     10598518.60      3468012.56     10598321.28
      3468291.06     10597456.71      3468013.75     10596615.24
      3466788.14     10595752.97      3466754.43     10595335.08
      3466137.05     10594934.48      3465873.07     10594501.06
      3465728.74     10593533.12      3465195.03     10593214.98
      3465091.13     10592844.48      3464917.13     10592923.62
      3464926.18     10592720.28      3464404.07     10592175.85
      3464411.69     10591701.69      3463901.01     10591481.49
      3463941.11     10591234.26      3463410.27     10591053.53
      3463310.54     10591218.39      3463095.47     10591189.66
      3463012.53     10591380.62      3462500.55     10591270.32
      3462380.41     10590823.09      3462517.22     10590619.62
      3462498.29     10590037.50      3462285.09     10589654.83
      3462469.49     10588759.09      3461957.40     10586705.61
      3462289.77     10585575.14      3462222.03     10585385.77

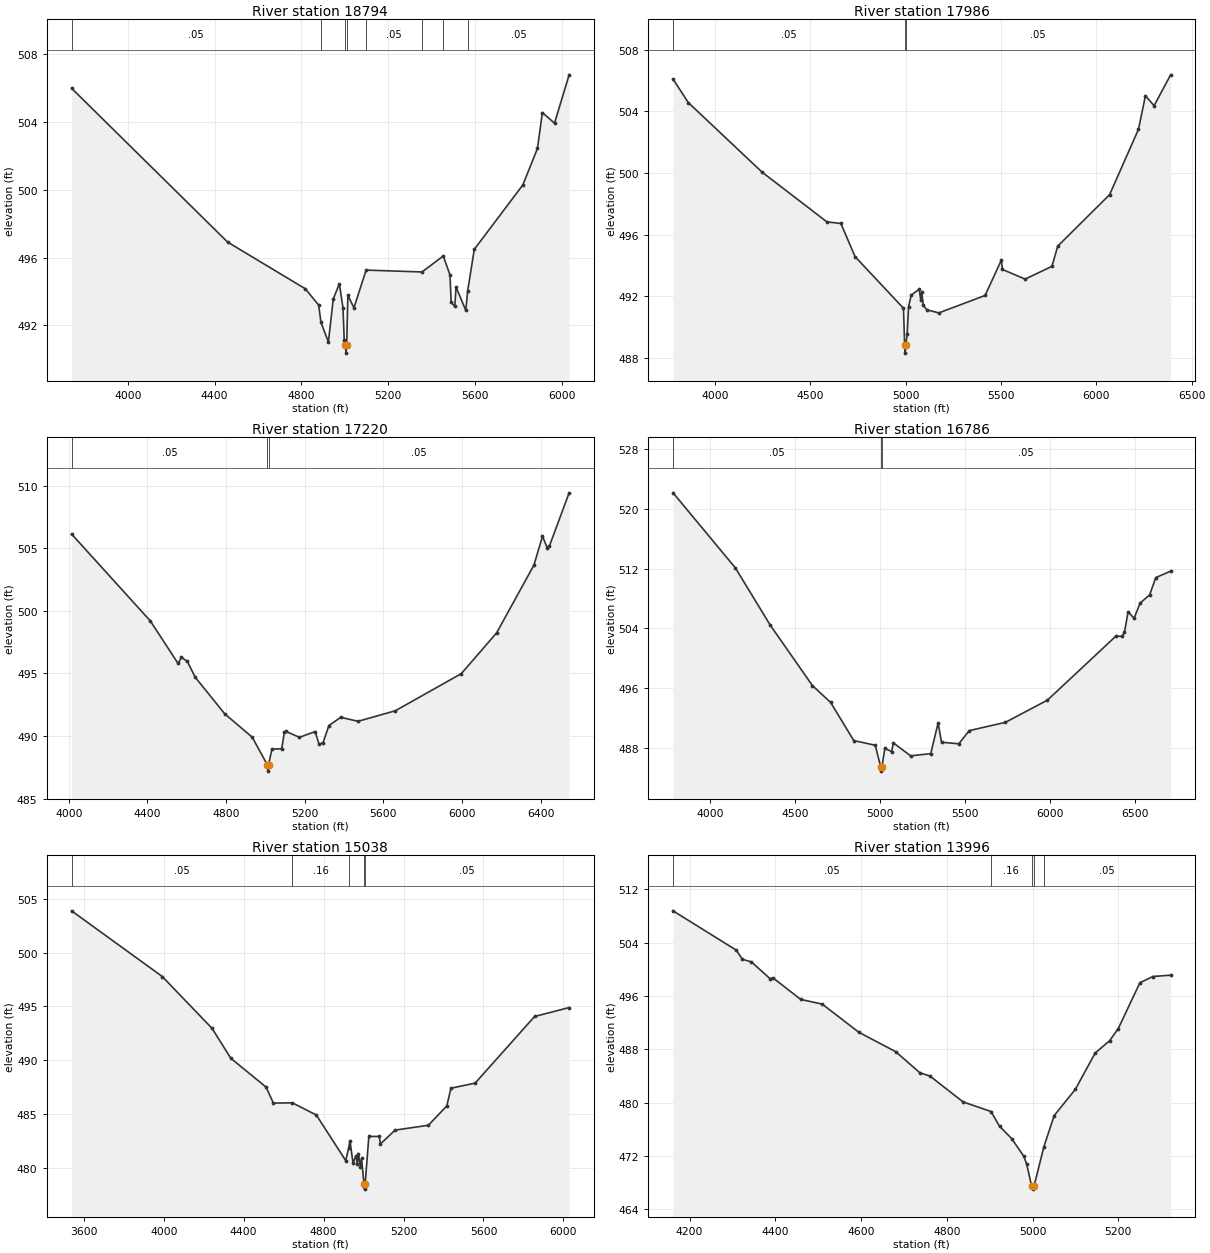
Type RM Length L Ch R = 1,18794,808,808,808
BEGIN DESCRIPTION:
UNT0049 IN CHRS 24.1
END DESCRIPTION:
XS GIS Cut Line= 3
      3469330.94     10598341.72      3468405.91     10598320.62
      3467181.89     10598929.11
#Sta/Elev= 30
  3740.8  505.97  4459.8  496.91  4817.7  494.16  4879.3  493.20  4889.7  492.18
  4924.1  491.03  4946.5  493.56  4974.5  494.45  4991.3  493.04  4996.9  491.17
  5002.3  490.87  5005.1  490.37  5008.3  490.87  5013.7  493.78  5041.7  493.04
  5097.9  495.26  5355.3  495.15  5453.2  496.09  5484.1  494.98  5489.7  493.37
  5506.5  493.12  5512.1  494.26  5556.9  492.89  5565.9  494.05  5596.1  496.48
  5820.1  500.28  5887.3  502.43  5909.7  504.54  5965.8  503.91  6033.0  506.76
#Mann=8,-1,0
  3740.8    0.05       0  4889.7     0.1       0  5002.3    0.07       0
  5008.3     0.1       0  5097.9    0.05       0  5355.3     0.1       0
  5453.2    0.12       0  5565.9    0.05       0
Bank Sta=5002.3,5008.3
Exp/Cntr=0.3,0.1

Type RM Length L Ch R = 1,17986,766,766,766
BEGIN DESCRIPTION:
UNT0049 IN CHRS 24.32
END DESCRIPTION:
XS GIS Cut Line= 4
      3469359.13     10598172.90      3467871.28     10597683.98
      3467202.99     10597610.12      3466889.97     10597810.60
#Sta/Elev= 30
  3779.4  506.09  3859.4  504.57  4246.3  500.06  4586.8  496.83  4659.8  496.73
  4734.1  494.58  4988.3  491.23  4994.3  488.82  4997.0  488.32  5000.3  488.82
  5007.8  489.58  5014.9  491.33  5028.9  492.09  5071.0  492.46  5078.5  491.79
  5083.8  492.27  5092.0  491.43  5110.3  491.13  5173.9  490.93  5416.3  492.06
  5502.0  494.36  5507.0  493.75  5626.4  493.12  5767.2  493.95  5797.4  495.26
  6069.7  498.60  6221.1  502.84  6257.4  505.01  6303.0  504.37  6389.6  506.37
#Mann=3,-1,0
  3779.4    0.05       0  4994.3    0.03       0  5000.3    0.05       0
Bank Sta=4994.3,5000.3
Exp/Cntr=0.3,0.1

Type RM Length L Ch R = 1,17220,434,434,434
BEGIN DESCRIPTION:
UNT0049 IN CHRS 24.0
END DESCRIPTION:
XS GIS Cut Line= 4
      3469162.10     10597279.48      3468641.57     10597103.63
      3467779.83     10597124.73      3466826.87     10597711.98
#Sta/Elev= 30
  4014.2  506.13  4415.3  499.18  4556.0  495.79  4573.1  496.28  4603.1  495.95
  4643.1  494.69  4793.2  491.77  4933.2  489.90  5010.2  487.69  5013.0  487.19
  5016.2  487.69  5033.2  488.94  5083.2  488.98  5096.7  490.30  5103.3  490.37
  5173.3  489.89  5253.3  490.35  5273.3  489.33  5293.3  489.46  5323.3  490.83
  5383.3  491.49  5471.6  491.17  5660.9  492.01  5996.9  494.98  6176.6  498.24
  6365.9  503.64  6409.6  505.95  6433.1  505.05  6445.1  505.18  6545.0  509.42
#Mann=3,-1,0
  4014.2    0.05       0  5010.2   0.035       0  5016.2    0.05       0
Bank Sta=5010.2,5016.2
Exp/Cntr=0.3,0.1

Type RM Length L Ch R = 1,16786,1748,1748,1748
BEGIN DESCRIPTION:
UNT0049 IN CHRS 23.0
END DESCRIPTION:
XS GIS Cut Line= 4
      3469014.32     10596096.19      3468368.49     10596700.36
      3467555.99     10596825.36      3466712.26     10597705.54
#Sta/Elev= 30
  3782.9  522.16  4149.2  512.11  4354.3  504.44  4602.0  496.35  4708.9  494.10
  4845.7  488.97  4971.9  488.35  5004.6  485.38  5007.4  484.88  5010.6  485.38
  5027.9  487.92  5068.3  487.50  5078.4  488.66  5179.6  486.93  5298.2  487.22
  5341.5  491.34  5361.5  488.75  5462.9  488.54  5524.9  490.31  5736.9  491.41
  5984.4  494.39  6387.6  502.98  6423.1  502.92  6437.3  503.47  6458.4  506.22
  6493.9  505.36  6529.1  507.39  6585.7  508.50  6621.0  510.80  6708.6  511.67
#Mann=3,-1,0
  3782.9    0.05       0  5004.6    0.03       0  5010.6    0.05       0
Bank Sta=5004.6,5010.6
Exp/Cntr=0.3,0.1

Type RM Length L Ch R = 1,15038,1042,1042,1042
BEGIN DESCRIPTION:
UNT0049 IN CHRS 19.0
END DESCRIPTION:
XS GIS Cut Line= 4
      3468113.25     10595127.45      3467102.86     10595476.40
      3466503.90     10595846.19      3465957.07     10596309.69
#Sta/Elev= 30
  3538.7  503.89  3992.6  497.78  4242.1  492.95  4335.7  490.17  4512.2  487.49
  4548.7  486.00  4643.7  486.03  4763.8  484.89  4910.4  480.66  4925.2  481.80
  4931.7  482.51  4947.1  480.43  4961.1  481.08  4968.4  480.38  4974.3  481.31
  4983.8  480.07  4989.7  480.86  5002.0  478.50  5004.8  478.00  5008.0  478.50
  5026.3  482.90  5078.4  482.90  5084.2  482.20  5157.6  483.49  5324.1  483.94
  5416.4  485.74  5437.2  487.39  5558.1  487.86  5855.7  494.06  6028.4  494.89
#Mann=5,-1,0
  3538.7    0.05       0  4643.7    0.16       0  4925.2    0.05       0
  5002.0    0.04       0  5008.0    0.05       0
Bank Sta=5002,5008
Exp/Cntr=0.3,0.1

Type RM Length L Ch R = 1,13996,810,810,810
BEGIN DESCRIPTION:
UNT0049 IN CHRS 17.0
END DESCRIPTION:
XS GIS Cut Line= 4
      3466837.23     10594460.78      3466316.40     10594840.98
      3466082.03     10595090.98      3466061.20     10595262.81
#Sta/Elev= 30
  4161.4  508.78  4308.6  502.89  4323.2  501.51  4344.1  501.12  4388.1  498.58
  4394.3  498.74  4459.2  495.49  4509.4  494.79  4595.1  490.55  4680.9  487.65
  4737.3  484.48  4760.4  484.01  4837.9  480.12  4903.0  478.68  4922.9  476.47
  4951.2  474.63  4979.6  471.96  4986.4  470.76  4997.6  467.54  5000.3  467.04
  5003.6  467.54  5026.4  473.39  5050.4  478.07  5099.7  482.00  5145.9  487.44
  5179.8  489.31  5199.9  491.12  5250.3  497.99  5280.5  498.93  5322.0  499.13
#Mann=5,-1,0
  4161.4    0.05       0  4903.0    0.16       0  4997.6    0.07       0
  5003.6    0.16       0  5026.4    0.05       0
Bank Sta=4997.6,5003.6
Exp/Cntr=0.3,0.1

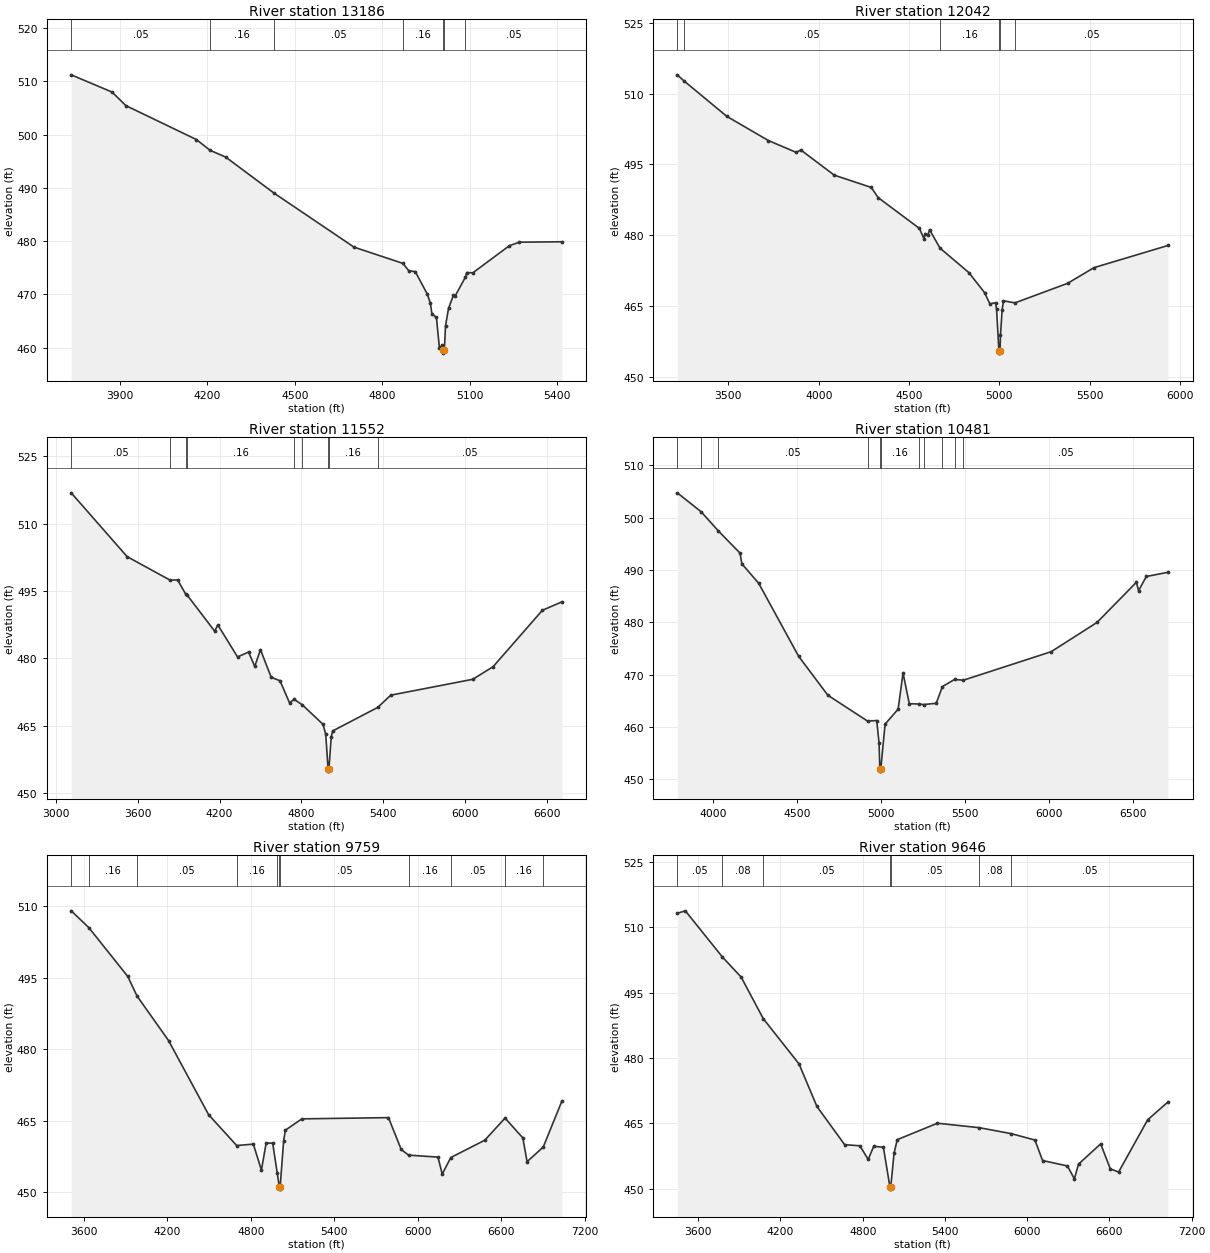
Type RM Length L Ch R = 1,13186,1144,1144,1144
BEGIN DESCRIPTION:
UNT0049 IN CHRS 16.0
END DESCRIPTION:
XS GIS Cut Line= 4
      3467118.63     10594091.78      3466147.44     10594197.14
      3465519.85     10594371.22      3465479.32     10594407.25
#Sta/Elev= 30
  3733.2  511.25  3873.3  508.01  3920.8  505.46  4162.2  499.10  4209.4  497.07
  4262.8  495.80  4428.9  489.02  4702.9  478.88  4870.3  475.83  4891.1  474.42
  4912.8  474.30  4954.3  470.03  4964.7  468.34  4970.0  466.32  4985.4  465.68
  4995.8  459.87  5004.3  460.44  5006.5  459.47  5009.2  458.97  5012.5  459.47
  5016.6  464.10  5027.0  467.41  5043.7  469.83  5048.9  469.64  5084.3  473.19
  5089.2  474.11  5110.0  474.05  5235.8  479.16  5270.1  479.81  5415.6  479.89
#Mann=7,-1,0
  3733.2    0.05       0  4209.4    0.16       0  4428.9    0.05       0
  4870.3    0.16       0  5006.5    0.07       0  5012.5    0.16       0
  5084.3    0.05       0
Bank Sta=5006.5,5012.5
Exp/Cntr=0.3,0.1

Type RM Length L Ch R = 1,12042,490,490,490
BEGIN DESCRIPTION:
UNT0049 IN CHRS 15.0
END DESCRIPTION:
XS GIS Cut Line= 4
      3467049.92     10592676.25      3465547.34     10593212.23
      3465263.32     10593743.63      3465345.77     10594256.69
#Sta/Elev= 30
  3216.9  513.97  3252.2  512.74  3490.9  505.18  3721.5  500.05  3875.5  497.55
  3901.0  498.06  4085.9  492.73  4290.9  490.12  4329.4  487.96  4557.6  481.45
  4583.1  479.25  4588.4  480.34  4605.4  480.12  4613.9  481.16  4671.7  477.27
  4831.2  472.10  4919.0  467.83  4947.6  465.48  4979.2  465.70  4984.9  464.38
  4998.1  455.53  5000.9  455.03  5004.1  455.53  5006.8  458.85  5015.6  464.09
  5023.1  466.12  5086.6  465.67  5378.5  469.81  5524.2  473.13  5934.4  477.83
#Mann=6,-1,0
  3216.9     0.1       0  3252.2    0.05       0  4671.7    0.16       0
  4998.1    0.07       0  5004.1    0.16       0  5086.6    0.05       0
Bank Sta=4998.1,5004.1
Exp/Cntr=0.3,0.1

Type RM Length L Ch R = 1,11552,1071,1071,1071
BEGIN DESCRIPTION:
UNT0049 IN CHRS 14.0
END DESCRIPTION:
XS GIS Cut Line= 4
      3467014.33     10592590.98      3465332.03     10593127.44
      3465035.15     10593090.98      3463993.47     10594216.00
#Sta/Elev= 30
  3111.9  516.87  3521.9  502.66  3837.9  497.42  3891.9  497.49  3950.8  494.35
  3963.8  494.04  4163.9  486.07  4187.0  487.45  4331.8  480.33  4412.4  481.43
  4457.7  478.24  4499.7  481.94  4578.6  475.79  4643.0  475.03  4712.7  470.12
  4746.7  470.89  4806.4  469.67  4958.2  465.34  4978.3  463.13  4995.5  455.41
  4998.2  454.91  5001.5  455.41  5018.6  462.53  5028.7  463.85  5359.7  469.10
  5455.3  471.82  6056.9  475.36  6205.4  478.16  6566.6  490.71  6710.0  492.60
#Mann=9,-1,0
  3111.9    0.05       0  3837.9    0.16       0  3950.8    0.12       0
  3963.8    0.16       0  4746.7    0.05       0  4806.4    0.16       0
  4995.5    0.07       0  5001.5    0.16       0  5359.7    0.05       0
Bank Sta=4995.5,5001.5
Exp/Cntr=0.3,0.1

Type RM Length L Ch R = 1,10481,722,722,722
BEGIN DESCRIPTION:
UNT0049 IN CHRS 13.0
END DESCRIPTION:
XS GIS Cut Line= 4
      3465915.32     10592413.90      3464957.03     10592497.23
      3464701.82     10592773.27      3463904.93     10594143.09
#Sta/Elev= 30
  3786.4  504.74  3928.2  501.13  4030.8  497.47  4160.2  493.22  4171.1  491.17
  4271.4  487.45  4509.0  473.52  4683.0  466.08  4919.8  461.13  4974.1  461.25
  4988.3  456.92  4992.6  452.08  4995.4  451.58  4998.6  452.08  5024.0  460.55
  5101.7  463.42  5130.9  470.34  5168.1  464.47  5224.4  464.39  5254.4  464.30
  5328.7  464.54  5365.3  467.73  5437.6  469.09  5490.4  468.95  6013.8  474.40
  6286.1  479.98  6521.1  487.66  6533.8  486.04  6579.8  488.76  6709.0  489.56
#Mann=11,-1,0
  3786.4    0.12       0  3928.2    0.16       0  4030.8    0.05       0
  4919.8    0.16       0  4992.6    0.07       0  4998.6    0.16       0
  5224.4    0.05       0  5254.4    0.16       0  5365.3    0.05       0
  5437.6    0.16       0  5490.4    0.05       0
Bank Sta=4992.6,4998.6
Exp/Cntr=0.3,0.1

Type RM Length L Ch R = 1,9759,113,113,113
BEGIN DESCRIPTION:
UNT0049 IN CHRS 12.0
END DESCRIPTION:
XS GIS Cut Line= 4
      3465868.50     10592346.19      3464582.03     10592122.23
      3464082.03     10592200.36      3462395.82     10591898.50
#Sta/Elev= 30
  3510.0  509.07  3636.1  505.56  3916.5  495.29  3982.6  491.20  4209.4  481.83
  4497.3  466.26  4698.8  459.80  4818.3  460.10  4876.5  454.65  4910.5  460.36
  4957.4  460.28  4989.9  454.04  5005.0  451.15  5007.8  450.65  5011.0  451.15
  5036.0  460.78  5048.5  463.02  5166.6  465.40  5789.1  465.66  5880.6  458.97
  5933.5  457.79  6144.7  457.37  6175.2  453.81  6236.8  457.28  6481.5  460.93
  6626.4  465.56  6754.2  461.41  6784.7  456.41  6900.7  459.48  7034.9  469.14
#Mann=11,-1,0
  3510.0    0.05       0  3636.1    0.16       0  3982.6    0.05       0
  4698.8    0.16       0  4989.9    0.05       0  5005.0   0.035       0
  5011.0    0.05       0  5933.5    0.16       0  6236.8    0.05       0
  6626.4    0.16       0  6900.7    0.05       0
Bank Sta=5005,5011
Exp/Cntr=0.3,0.1

Type RM Length L Ch R = 1,9646,203,203,203
BEGIN DESCRIPTION:
UNT0049 IN CHRS 11.0
END DESCRIPTION:
XS GIS Cut Line= 3
      3465910.19     10592262.86      3463925.78     10591976.40
      3462365.17     10591768.32
#Sta/Elev= 30
  3447.5  513.21  3506.2  513.78  3776.5  503.18  3913.2  498.57  4074.6  489.02
  4335.3  478.64  4465.9  468.87  4668.1  460.09  4779.2  459.83  4839.9  456.70
  4880.3  459.72  4951.0  459.50  4998.5  450.38  5001.3  449.88  5004.5  450.38
  5028.8  458.15  5052.0  461.24  5345.1  465.01  5649.8  463.99  5882.1  462.63
  6056.2  461.15  6111.9  456.45  6293.5  455.20  6344.0  452.24  6374.2  455.63
  6535.7  460.27  6606.3  454.53  6666.8  453.81  6878.7  465.80  7026.9  469.90
#Mann=7,-1,0
  3447.5    0.05       0  3776.5    0.08       0  4074.6    0.05       0
  4998.5    0.04       0  5004.5    0.05       0  5649.8    0.08       0
  5882.1    0.05       0
Bank Sta=4998.5,5004.5
Exp/Cntr=0.3,0.1

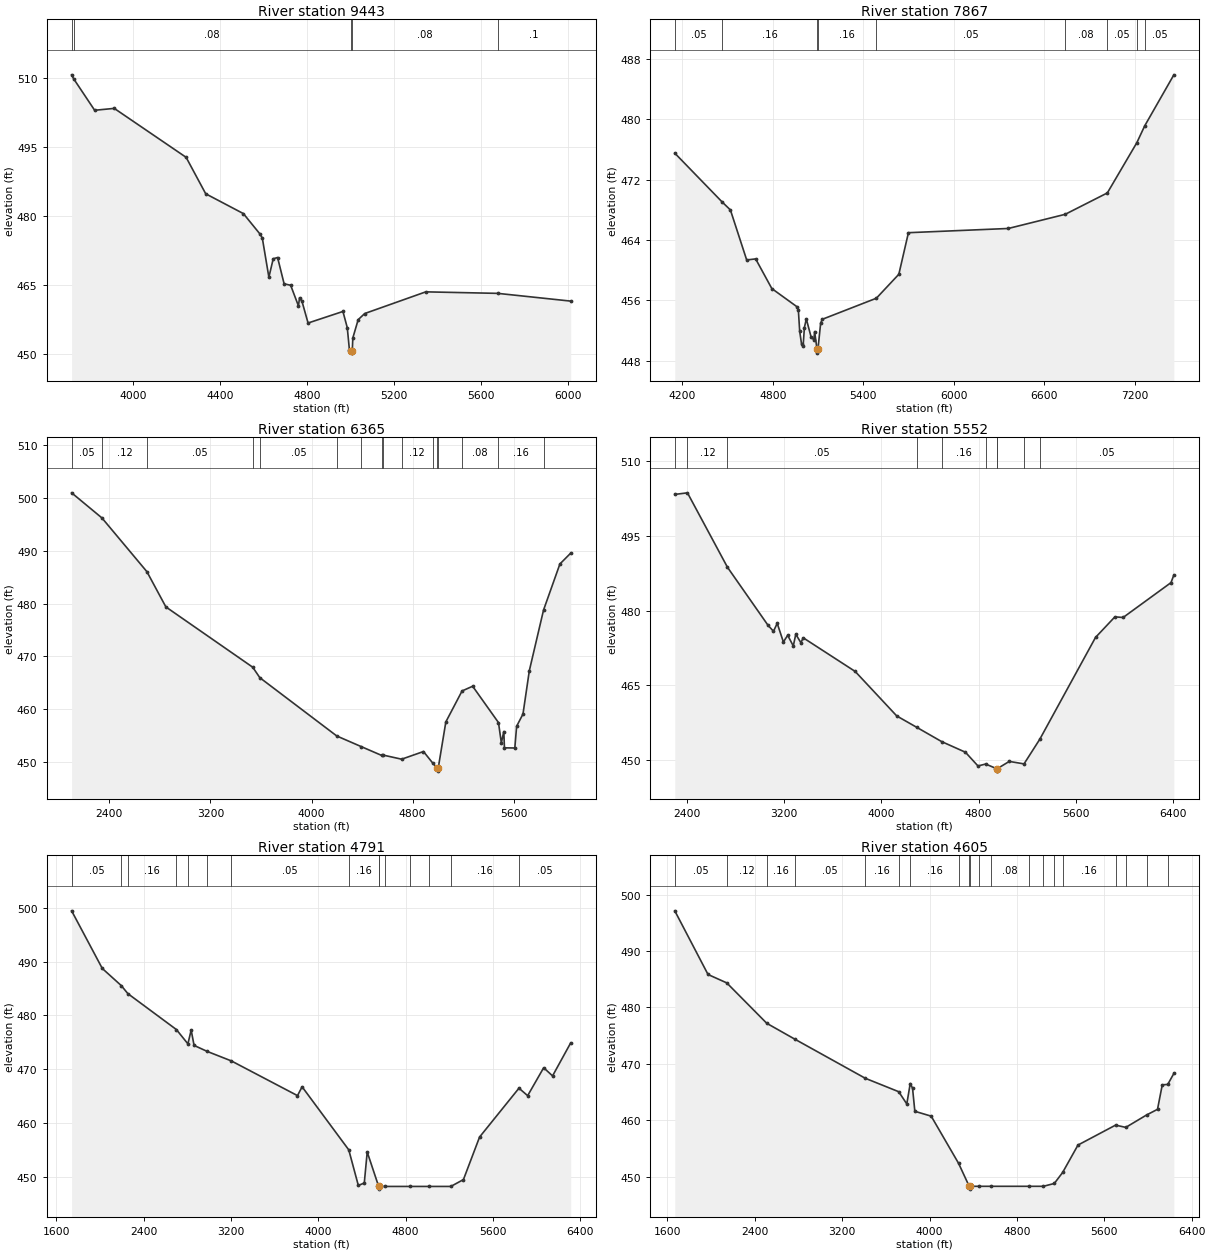
Type RM Length L Ch R = 1,9443,1576,1576,1576
BEGIN DESCRIPTION:
UNT0049 IN CHRS 10.0
END DESCRIPTION:
XS GIS Cut Line= 4
      3465697.93     10591948.14      3464643.21     10591865.68
      3464157.10     10591826.61      3463410.56     10591726.79
#Sta/Elev= 30
  3715.0  510.65  3723.8  509.83  3821.1  502.95  3911.4  503.36  4242.4  492.73
  4332.7  484.81  4506.1  480.51  4583.5  476.02  4593.5  475.16  4623.6  466.69
  4643.6  470.69  4663.7  470.97  4693.8  465.25  4723.9  464.94  4759.8  460.46
  4764.8  462.23  4776.0  461.46  4804.1  456.74  4964.7  459.25  4984.7  455.73
  4994.8  450.79  5001.8  450.70  5004.5  450.20  5007.8  450.70  5010.2  453.48
  5034.9  457.47  5065.0  458.80  5346.4  463.51  5678.0  463.18  6013.8  461.50
#Mann=5,-1,0
  3715.0     0.1       0  3723.8    0.08       0  5001.8    0.07       0
  5007.8    0.08       0  5678.0     0.1       0
Bank Sta=5001.8,5007.8
Exp/Cntr=0.3,0.1

Type RM Length L Ch R = 1,7867,1502,1502,1502
BEGIN DESCRIPTION:
UNT0049 IN CHRS 7.2
END DESCRIPTION:
XS GIS Cut Line= 4
      3464223.46     10590713.35      3463607.19     10590908.64
      3463312.05     10591768.02      3461576.50     10591525.04
#Sta/Elev= 30
  4150.1  475.53  4464.8  469.03  4518.7  467.99  4626.6  461.35  4686.0  461.49
  4793.3  457.55  4958.3  455.16  4968.9  454.74  4977.9  451.88  4990.1  450.20
  5000.6  449.92  5009.1  452.38  5021.8  453.52  5053.5  451.12  5071.6  450.75
  5076.9  451.84  5092.8  449.48  5095.6  448.98  5098.8  449.48  5116.9  452.97
  5127.5  453.47  5486.1  456.27  5635.0  459.45  5698.5  464.97  6360.4  465.53
  6737.5  467.41  7016.9  470.25  7212.0  476.91  7264.9  479.17  7457.7  485.93
#Mann=9,-1,0
  4150.1    0.05       0  4464.8    0.16       0  5092.8    0.07       0
  5098.8    0.16       0  5486.1    0.05       0  6737.5    0.08       0
  7016.9    0.05       0  7212.0     0.1       0  7264.9    0.05       0
Bank Sta=5092.8,5098.8
Exp/Cntr=0.3,0.1

Type RM Length L Ch R = 1,6365,813,813,813
BEGIN DESCRIPTION:
UNT0049 IN CHRS 7.1
END DESCRIPTION:
XS GIS Cut Line= 4
      3465247.79     10590497.62      3463065.52     10590859.60
      3462370.21     10591442.93      3461547.32     10591343.98
#Sta/Elev= 30
  2101.9  500.97  2342.0  496.21  2697.6  486.04  2847.6  479.37  3534.9  467.95
  3590.9  465.97  4200.0  454.93  4394.5  452.91  4554.0  451.26  4562.1  451.34
  4712.9  450.54  4885.7  451.99  4958.1  449.83  4995.9  448.78  4998.6  448.28
  5001.9  448.78  5062.6  457.60  5191.0  463.46  5274.7  464.35  5479.1  457.47
  5501.7  453.63  5521.2  455.78  5526.2  452.69  5608.4  452.66  5622.6  456.77
  5672.9  459.09  5723.3  467.32  5835.6  478.78  5965.0  487.50  6050.4  489.55
#Mann=16,-1,0
  2101.9    0.05       0  2342.0    0.12       0  2697.6    0.05       0
  3534.9    0.16       0  3590.9    0.05       0  4200.0     0.1       0
  4394.5    0.16       0  4554.0    0.12       0  4562.1    0.16       0
  4712.9    0.12       0  4958.1    0.16       0  4995.9    0.07       0
  5001.9    0.16       0  5191.0    0.08       0  5479.1    0.16       0
  5835.6     0.1       0
Bank Sta=4995.9,5001.9
Exp/Cntr=0.3,0.1

Type RM Length L Ch R = 1,5552,761,761,761
BEGIN DESCRIPTION:
UNT0049 IN CHRS 7.0
END DESCRIPTION:
XS GIS Cut Line= 4
      3465149.78     10590340.97      3462878.90     10590778.48
      3461967.45     10590549.31      3461233.23     10590986.72
#Sta/Elev= 30
  2299.6  503.29  2403.8  503.61  2732.9  488.69  3067.9  477.01  3111.9  475.85
  3142.5  477.44  3193.4  473.69  3228.6  475.04  3274.9  472.90  3295.3  475.25
  3337.5  473.55  3356.4  474.54  3784.1  467.79  4126.0  458.87  4291.0  456.58
  4495.9  453.72  4691.4  451.59  4794.5  448.84  4857.8  449.22  4948.1  448.30
  4950.9  447.80  4954.1  448.30  5052.3  449.75  5173.6  449.25  5303.7  454.21
  5761.9  474.61  5921.5  478.74  5989.0  478.61  6383.0  485.60  6406.7  487.14
#Mann=10,-1,0
  2299.6    0.05       0  2403.8    0.12       0  2732.9    0.05       0
  4291.0     0.1       0  4495.9    0.16       0  4857.8    0.12       0
  4948.1    0.07       0  4954.1    0.12       0  5173.6    0.16       0
  5303.7    0.05       0
Bank Sta=4948.1,4954.1
Exp/Cntr=0.3,0.1

Type RM Length L Ch R = 1,4791,186,186,186
BEGIN DESCRIPTION:
UNT0049 IN CHRS 6.0
END DESCRIPTION:
XS GIS Cut Line= 4
      3465529.92     10588898.28      3462727.86     10589809.73
      3462295.57     10590064.94      3461311.23     10590606.59
#Sta/Elev= 30
  1740.6  499.41  2021.6  488.72  2195.2  485.55  2256.1  484.05  2700.5  477.39
  2805.9  474.74  2835.8  477.29  2862.5  474.45  2983.8  473.33  3203.5  471.58
  3809.9  465.14  3852.0  466.78  4279.6  455.08  4367.2  448.48  4421.8  448.94
  4448.5  454.69  4553.5  448.30  4556.3  447.80  4559.5  448.30  4608.4  448.30
  4841.1  448.30  5011.0  448.30  5214.5  448.30  5330.1  449.57  5477.9  457.46
  5838.8  466.52  5918.3  465.13  6065.1  470.31  6146.5  468.80  6312.7  474.92
#Mann=15,-1,0
  1740.6    0.05       0  2195.2    0.12       0  2256.1    0.16       0
  2700.5     0.1       0  2805.9    0.16       0  2983.8     0.1       0
  3203.5    0.05       0  4279.6    0.16       0  4553.5   0.033       0
  4559.5    0.16       0  4608.4    0.07       0  4841.1    0.05       0
  5011.0    0.07       0  5214.5    0.16       0  5838.8    0.05       0
Bank Sta=4553.5,4559.5
Exp/Cntr=0.3,0.1

Type RM Length L Ch R = 1,4605,258,258,258
BEGIN DESCRIPTION:
UNT0049 IN CHRS 6.1
END DESCRIPTION:
XS GIS Cut Line= 4
      3465472.62     10588721.20      3462670.57     10589632.65
      3462238.28     10589887.86      3461255.50     10590428.64
#Sta/Elev= 30
  1666.9  497.11  1971.3  485.83  2143.0  484.34  2509.4  477.18  2769.0  474.34
  3411.5  467.44  3717.5  465.06  3791.6  462.89  3822.9  466.51  3844.2  465.68
  3865.2  461.59  4014.9  460.73  4265.7  452.37  4363.2  448.30  4366.0  447.80
  4369.2  448.30  4455.2  448.30  4560.6  448.30  4907.3  448.30  5041.7  448.30
  5142.1  448.80  5218.6  450.75  5359.2  455.61  5703.3  459.14  5796.9  458.74
  5986.6  460.93  6087.4  461.94  6131.0  466.28  6181.1  466.35  6237.2  468.30
#Mann=20,-1,0
  1666.9    0.05       0  2143.0    0.12       0  2509.4    0.16       0
  2769.0    0.05       0  3411.5    0.16       0  3717.5    0.05       0
  3822.9    0.16       0  4265.7    0.07       0  4363.2    0.07       0
  4369.2    0.07       0  4455.2    0.05       0  4560.6    0.08       0
  4907.3    0.08       0  5041.7    0.07       0  5142.1    0.05       0
  5218.6    0.16       0  5703.3    0.16       0  5796.9    0.05       0
  5986.6    0.05       0  6181.1     0.1       0
Bank Sta=4363.2,4369.2
Exp/Cntr=0.3,0.1

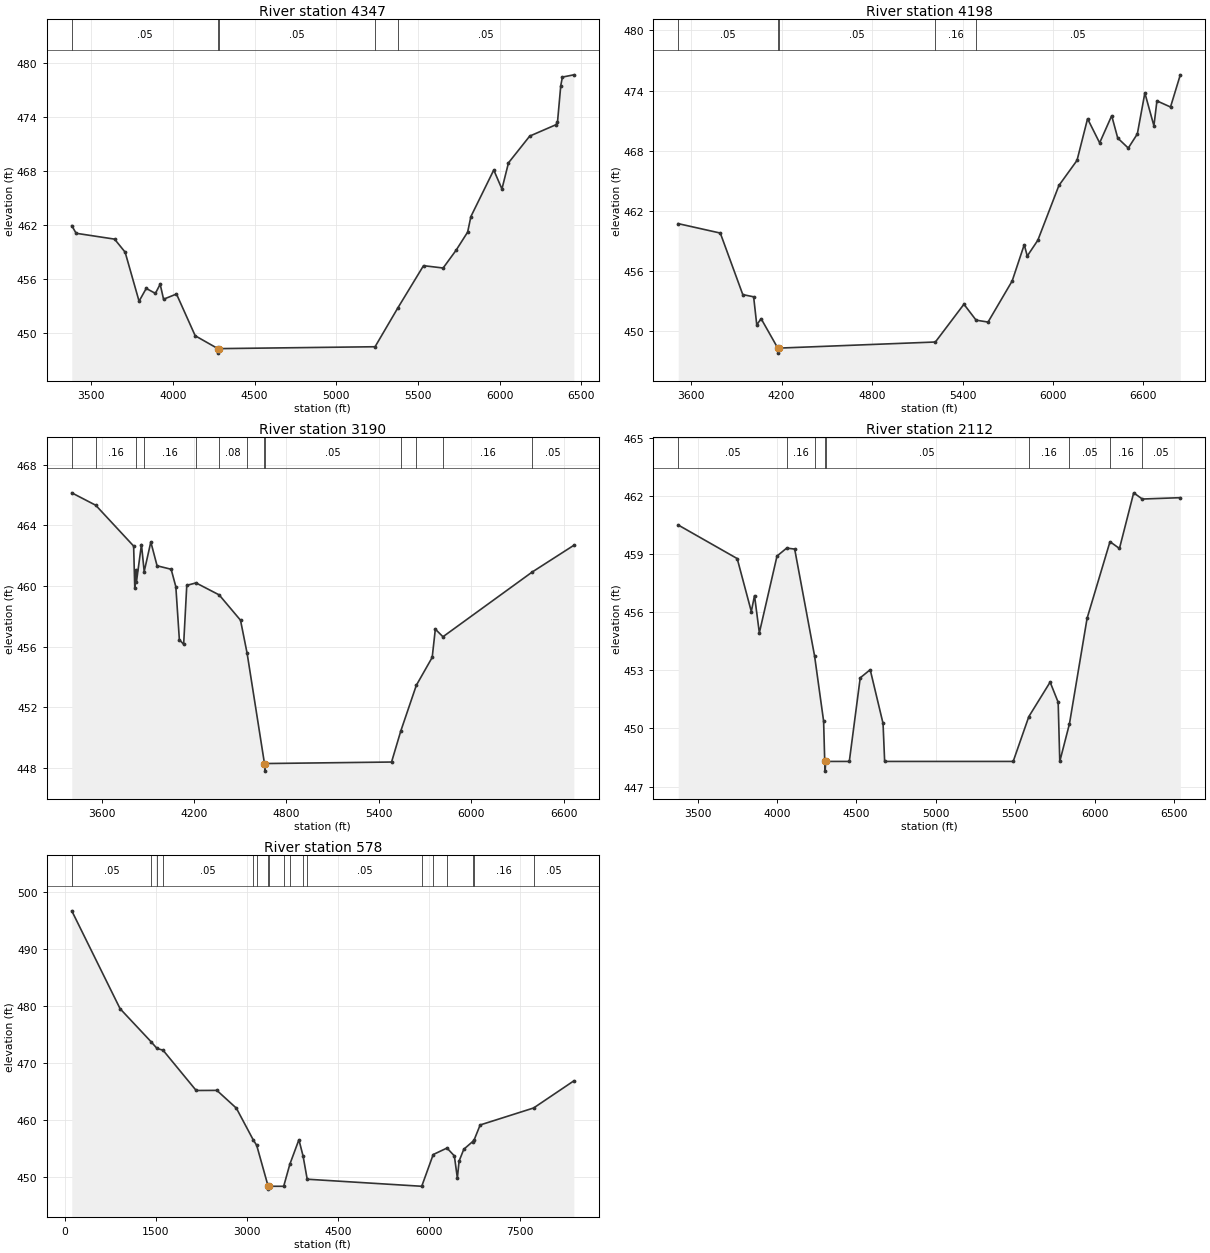
Type RM Length L Ch R = 1,4347,149,149,149
BEGIN DESCRIPTION:
UNT0049 IN CHRS 5.0
END DESCRIPTION:
XS GIS Cut Line= 4
      3463332.05     10588413.87      3462477.86     10589554.52
      3462144.53     10589601.40      3460832.01     10589648.27
#Sta/Elev= 30
  3380.3  461.97  3407.0  461.12  3642.5  460.47  3707.1  459.02  3792.5  453.57
  3836.3  454.99  3892.5  454.44  3921.7  455.46  3942.5  453.79  4021.7  454.37
  4136.3  449.73  4275.0  448.30  4277.8  447.80  4281.0  448.30  5237.9  448.51
  5376.2  452.79  5534.6  457.52  5654.7  457.26  5734.7  459.25  5804.8  461.25
  5824.8  462.98  5964.9  468.15  6014.9  466.04  6055.0  468.95  6185.0  471.92
  6345.1  473.18  6355.1  473.46  6375.2  477.53  6385.2  478.48  6455.3  478.73
#Mann=5,-1,0
  3380.3    0.05       0  4275.0   0.033       0  4281.0    0.05       0
  5237.9    0.16       0  5376.2    0.05       0
Bank Sta=4275,4281
Exp/Cntr=0.3,0.1

Type RM Length L Ch R = 1,4198,1008,1008,1008
BEGIN DESCRIPTION:
UNT0049 IN CHRS 4.0
END DESCRIPTION:
XS GIS Cut Line= 4
      3463269.52     10588356.61      3462415.36     10589429.52
      3461998.70     10589445.15      3460457.07     10589476.40
#Sta/Elev= 30
  3514.3  460.72  3793.3  459.78  3942.5  453.64  4014.4  453.42  4035.2  450.62
  4064.0  451.24  4174.7  448.30  4177.5  447.80  4180.7  448.30  5220.0  448.91
  5409.3  452.68  5490.0  451.09  5569.3  450.90  5729.3  455.00  5809.4  458.62
  5829.4  457.49  5899.4  459.06  6039.4  464.53  6159.4  467.03  6229.4  471.19
  6309.5  468.78  6389.5  471.49  6429.5  469.26  6499.5  468.26  6559.5  469.67
  6609.5  473.76  6669.5  470.48  6689.5  472.97  6779.6  472.36  6844.6  475.57
#Mann=5,-1,0
  3514.3    0.05       0  4174.7   0.033       0  4180.7    0.05       0
  5220.0    0.16       0  5490.0    0.05       0
Bank Sta=4174.7,4180.7
Exp/Cntr=0.3,0.1

Type RM Length L Ch R = 1,3190,1078,1078,1078
BEGIN DESCRIPTION:
UNT0049 IN CHRS 3.0
END DESCRIPTION:
XS GIS Cut Line= 2
      3463977.83     10588174.32      3460766.03     10588747.24
#Sta/Elev= 30
  3404.7  466.15  3560.6  465.33  3806.7  462.64  3814.1  459.88  3819.2  461.07
  3825.3  460.30  3857.5  462.74  3875.3  460.96  3918.4  462.91  3959.0  461.34
  4050.5  461.11  4080.9  459.96  4103.8  456.47  4131.7  456.16  4152.0  460.05
  4212.1  460.21  4362.5  459.42  4501.2  457.75  4544.3  455.56  4656.9  448.30
  4659.7  447.80  4662.9  448.30  5482.7  448.40  5542.5  450.44  5643.7  453.46
  5746.8  455.30  5767.1  457.16  5816.8  456.66  6396.9  460.93  6667.2  462.69
#Mann=13,-1,0
  3404.7    0.05       0  3560.6    0.16       0  3825.3    0.05       0
  3875.3    0.16       0  4212.1    0.05       0  4362.5    0.08       0
  4544.3    0.05       0  4656.9   0.033       0  4662.9    0.05       0
  5542.5    0.16       0  5643.7    0.05       0  5816.8    0.16       0
  6396.9    0.05       0
Bank Sta=4656.9,4662.9
Exp/Cntr=0.3,0.1

Type RM Length L Ch R = 1,2112,1534,1534,1534
BEGIN DESCRIPTION:
UNT0049 IN CHRS 2.0
END DESCRIPTION:
XS GIS Cut Line= 2
      3463786.90     10587150.01      3460661.89     10587636.12
#Sta/Elev= 30
  3377.7  460.49  3749.1  458.76  3838.0  456.03  3858.2  456.85  3888.6  454.93
  3999.9  458.89  4060.8  459.30  4111.2  459.25  4236.5  453.74  4293.4  450.38
  4300.5  448.30  4303.2  447.80  4306.5  448.30  4455.3  448.30  4524.0  452.61
  4586.9  453.03  4667.8  450.26  4677.9  448.30  5487.6  448.30  5586.0  450.61
  5720.3  452.39  5770.9  451.35  5781.1  448.30  5842.0  450.24  5953.1  455.68
  6097.3  459.63  6157.0  459.28  6246.6  462.15  6300.9  461.83  6540.3  461.90
#Mann=9,-1,0
  3377.7    0.05       0  4060.8    0.16       0  4236.5    0.05       0
  4300.5   0.033       0  4306.5    0.05       0  5586.0    0.16       0
  5842.0    0.05       0  6097.3    0.16       0  6300.9    0.05       0
Bank Sta=4300.5,4306.5
Exp/Cntr=0.3,0.1

Type RM Length L Ch R = 1,578,0,0,0
BEGIN DESCRIPTION:
UNT0049 IN CHRS 1.0
END DESCRIPTION:
XS GIS Cut Line= 4
      3467016.02     10586594.45      3463977.86     10586386.12
      3461616.75     10585795.84      3459724.42     10587844.42
#Sta/Elev= 30
   118.0  496.64   913.8  479.46  1423.5  473.67  1522.4  472.48  1621.2  472.18
  2166.7  465.11  2507.5  465.13  2828.3  462.01  3103.9  456.49  3163.5  455.48
  3351.8  448.30  3354.5  447.80  3357.8  448.30  3607.9  448.30  3708.8  452.16
  3858.4  456.47  3927.4  453.59  3994.9  449.54  5881.0  448.30  6069.9  453.87
  6297.0  455.01  6418.4  453.63  6467.7  449.74  6496.1  452.72  6573.8  454.80
  6717.9  456.13  6742.0  456.38  6843.1  459.06  7723.2  462.04  8385.9  466.80
#Mann=18,-1,0
   118.0    0.05       0  1423.5    0.16       0  1522.4    0.12       0
  1621.2    0.05       0  3103.9    0.16       0  3163.5    0.05       0
  3351.8   0.033       0  3357.8    0.05       0  3607.9     0.1       0
  3708.8    0.05       0  3927.4    0.07       0  3994.9    0.05       0
  5881.0    0.16       0  6069.9    0.05       0  6297.0    0.16       0
  6717.9    0.05       0  6742.0    0.16       0  7723.2    0.05       0
Bank Sta=3351.8,3357.8
Exp/Cntr=0.3,0.1

Chan Stop Cuts=-1