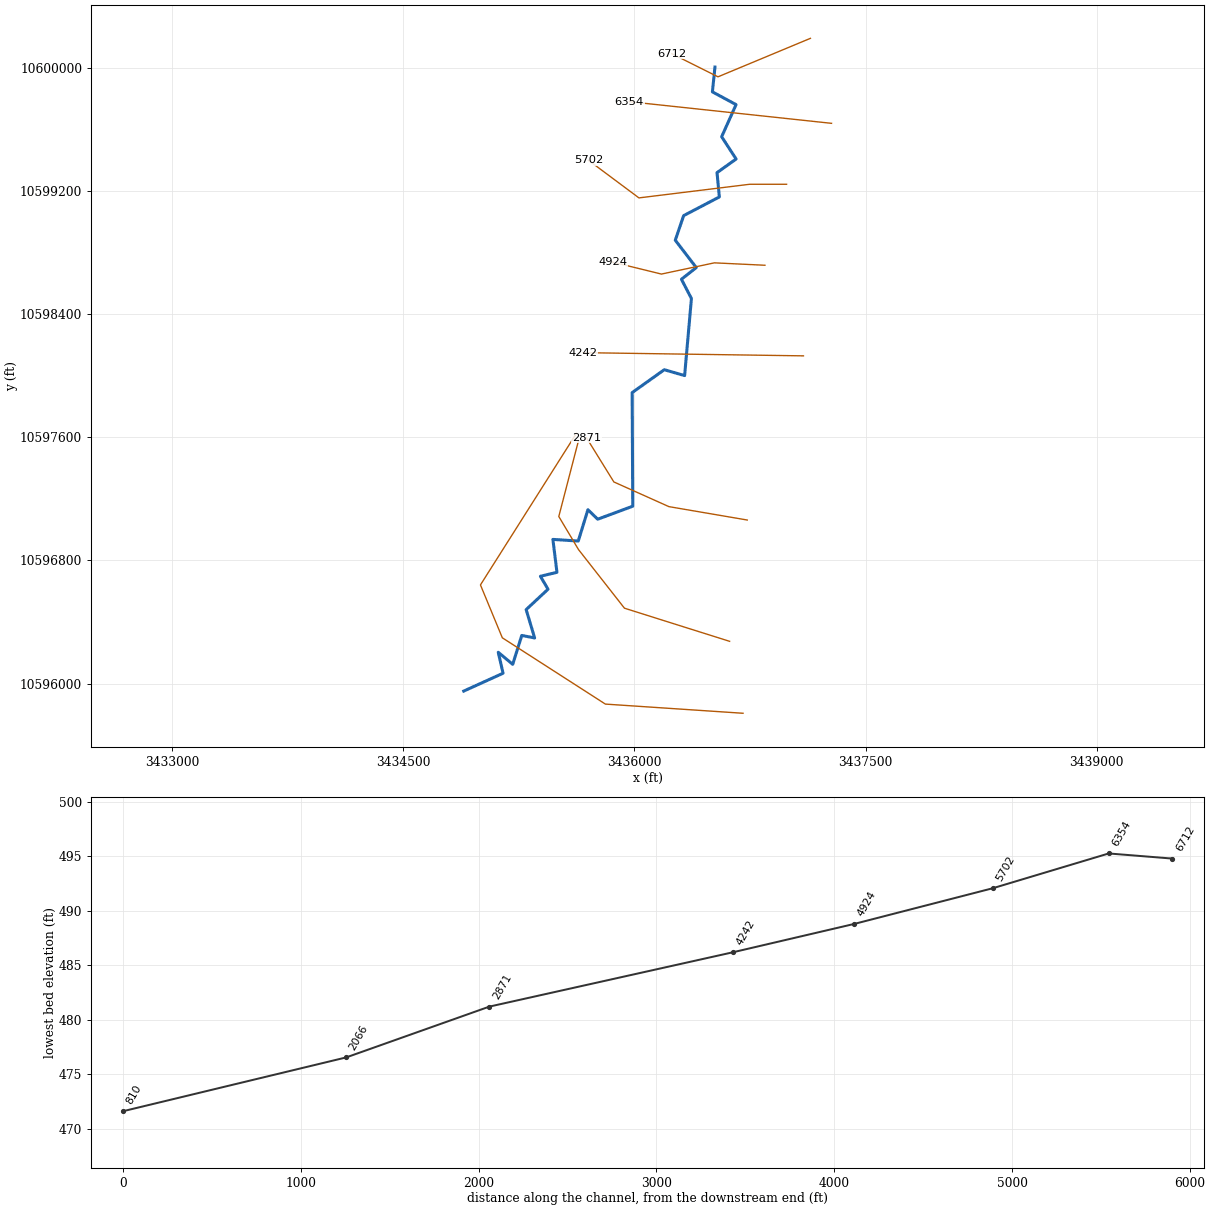
--- UNT00501 IN CHRS.prj (project) ---

Proj Title=UNT00501 IN CHRS Base Level Engineering
Current Plan=p01
Default Exp/Contr=0.3,0.1
English Units
Geom File=g01
Flow File=f01
Plan File=p01
BEGIN DESCRIPTION:
UNT00501 IN CHRS
END DESCRIPTION:

--- UNT00501 IN CHRS.p01 (plan) ---

Plan Title=Multiple Run
Short Identifier=Multiple
Geom File=g01
Flow File=f01
Subcritical Flow
K Sum by GR= 0
Std Step Tol= 0.01
Critical Tol= 0.01
Num of Std Step Trials= 20
Max Error Tol= 0.3
Flow Tol Ratio= 0.001
Split Flow NTrial= 30
Split Flow Tol= 0.02
Split Flow Ratio= 0.02
Log Output Level= 0
Friction Slope Method= 1
Unsteady Friction Slope Method= 2
Unsteady Bridges Friction Slope Method= 1
Parabolic Critical Depth
Global Vel Dist=  1 , 1 , 1
Global Log Level= 0
CheckData=True
Encroach Param= -1, 0, 0, 0
BEGIN DESCRIPTION:
Multiple Run
END DESCRIPTION:

--- UNT00501 IN CHRS.f01 (steady flow) ---

Flow Title=Multiple
Number of Profiles=7
Profile Names=10-year,25-year,50-year,1pct_min,100-year,1pct_plu,500-year
River Rch & RM= UNT00501 IN CHRS,Reach-1,6712
     294     359     405     333     450     609     553
Boundary for River Rch & Prof#=UNT00501 IN CHRS,Reach-1,1
Up Type=0
Dn Type=3
Dn Slope=0.005
Boundary for River Rch & Prof#=UNT00501 IN CHRS,Reach-1,2
Up Type=0
Dn Type=3
Dn Slope=0.005
Boundary for River Rch & Prof#=UNT00501 IN CHRS,Reach-1,3
Up Type=0
Dn Type=3
Dn Slope=0.005
Boundary for River Rch & Prof#=UNT00501 IN CHRS,Reach-1,4
Up Type=0
Dn Type=3
Dn Slope=0.005
Boundary for River Rch & Prof#=UNT00501 IN CHRS,Reach-1,5
Up Type=0
Dn Type=3
Dn Slope=0.005
Boundary for River Rch & Prof#=UNT00501 IN CHRS,Reach-1,6
Up Type=0
Dn Type=3
Dn Slope=0.005
Boundary for River Rch & Prof#=UNT00501 IN CHRS,Reach-1,7
Up Type=0
Dn Type=3
Dn Slope=0.005

--- UNT00501 IN CHRS.g01 (geometry) ---

Geom Title=Existing Conditions

River Reach=UNT00501 IN CHRS,Reach-1
Reach XY= 30
      3436522.34     10600005.17      3436505.86     10599843.92
      3436659.31     10599761.06      3436565.86     10599552.39
      3436659.62     10599407.74      3436535.85     10599319.15
      3436550.79     10599161.16      3436319.25     10599039.99
      3436264.87     10598880.24      3436401.14     10598702.43
      3436304.73     10598626.62      3436369.68     10598501.68
      3436325.53     10598001.00      3436193.49     10598039.08
      3435985.07     10597890.33      3435988.89     10597152.44
      3435761.55     10597068.03      3435697.95     10597129.59
      3435635.24     10596926.17      3435470.55     10596936.86
      3435497.05     10596723.10      3435389.65     10596697.29
      3435438.91     10596613.14      3435297.06     10596480.73
      3435352.23     10596296.60      3435268.72     10596313.09
      3435209.94     10596125.30      3435115.96     10596203.63
      3435147.24     10596067.45      3434892.11     10595951.64

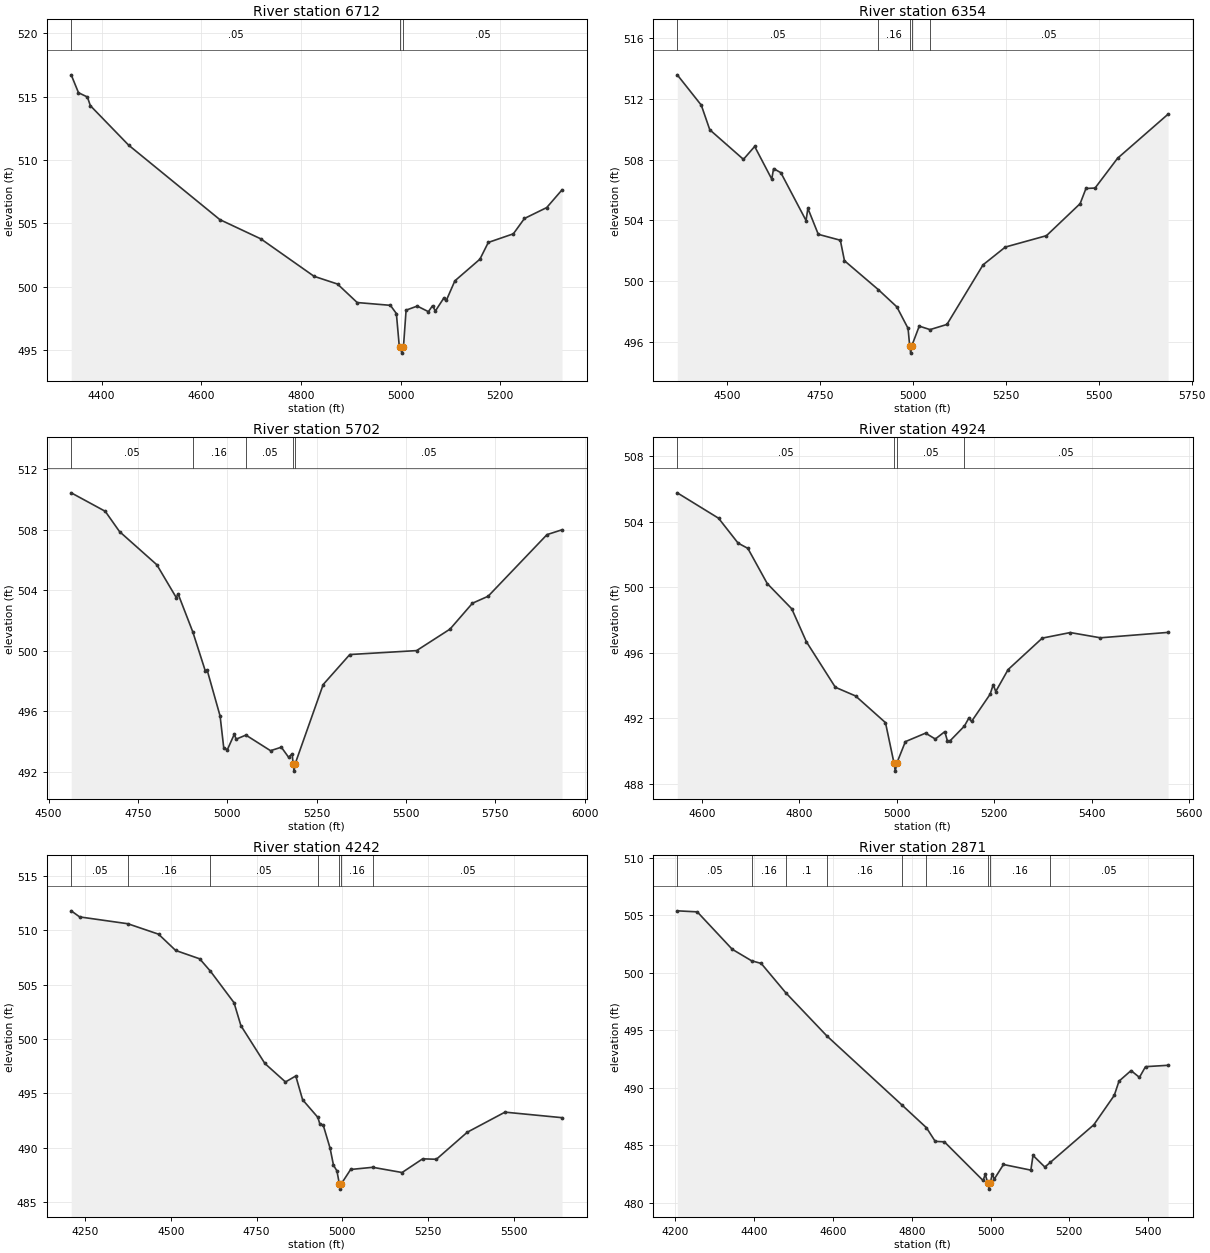
Type RM Length L Ch R = 1,6712,358,358,358
BEGIN DESCRIPTION:
UNT00501 IN CHRS 12.0
END DESCRIPTION:
XS GIS Cut Line= 3
      3437142.09     10600191.63      3436542.11     10599941.64
      3436242.10     10600091.65
#Sta/Elev= 30
  4338.9  516.72  4353.5  515.31  4371.4  514.97  4377.3  514.29  4454.3  511.17
  4637.3  505.30  4719.7  503.78  4826.4  500.83  4873.5  500.22  4913.0  498.76
  4979.7  498.54  4991.7  497.89  4997.3  495.41  4999.9  495.27  5002.6  494.77
  5005.9  495.27  5011.2  498.16  5033.6  498.48  5056.0  498.04  5064.3  498.51
  5069.9  498.09  5086.7  499.10  5092.3  498.96  5109.1  500.47  5159.4  502.18
  5176.2  503.50  5226.5  504.18  5248.8  505.39  5293.5  506.25  5324.3  507.65
#Mann=3,-1,0
  4338.9    0.05       0  4999.9   0.035       0  5005.9    0.05       0
Bank Sta=4999.9,5005.9
Exp/Cntr=0.3,0.1

Type RM Length L Ch R = 1,6354,652,652,652
BEGIN DESCRIPTION:
UNT00501 IN CHRS 11.0
END DESCRIPTION:
XS GIS Cut Line= 2
      3437279.04     10599639.51      3435966.85     10599780.11
#Sta/Elev= 30
  4367.0  513.58  4431.6  511.58  4454.4  509.96  4544.9  508.01  4575.1  508.86
  4621.0  506.71  4626.0  507.40  4645.5  507.13  4713.2  503.98  4718.2  504.78
  4746.1  503.07  4805.4  502.68  4816.5  501.33  4907.3  499.43  4957.3  498.29
  4987.5  496.87  4991.8  495.74  4994.6  495.24  4997.8  495.74  5017.6  497.02
  5046.6  496.79  5092.0  497.13  5189.2  501.06  5249.0  502.23  5359.6  502.98
  5450.1  505.09  5465.8  506.09  5490.3  506.12  5550.7  508.08  5686.7  510.99
#Mann=5,-1,0
  4367.0    0.05       0  4907.3    0.16       0  4991.8    0.07       0
  4997.8    0.16       0  5046.6    0.05       0
Bank Sta=4991.8,4997.8
Exp/Cntr=0.3,0.1

Type RM Length L Ch R = 1,5702,778,778,778
BEGIN DESCRIPTION:
UNT00501 IN CHRS 9.0
END DESCRIPTION:
XS GIS Cut Line= 4
      3436987.32     10599243.68      3436747.78     10599243.68
      3436029.03     10599155.14      3435700.91     10599399.93
#Sta/Elev= 30
  4563.3  510.43  4658.5  509.21  4698.5  507.87  4802.8  505.68  4857.2  503.51
  4862.2  503.76  4903.5  501.24  4938.4  498.67  4943.4  498.74  4979.8  495.69
  4989.9  493.61  5000.0  493.46  5019.6  494.49  5024.6  494.16  5052.0  494.43
  5120.9  493.40  5151.1  493.63  5171.3  492.97  5181.4  493.19  5184.0  492.55
  5186.7  492.05  5190.0  492.55  5268.2  497.77  5342.6  499.75  5529.5  500.01
  5623.0  501.43  5685.8  503.14  5729.6  503.60  5894.3  507.67  5936.4  507.99
#Mann=5,-1,0
  4563.3    0.05       0  4903.5    0.16       0  5052.0    0.05       0
  5184.0    0.07       0  5190.0    0.05       0
Bank Sta=5184,5190
Exp/Cntr=0.3,0.1

Type RM Length L Ch R = 1,4924,682,682,682
BEGIN DESCRIPTION:
UNT00501 IN CHRS 7.0
END DESCRIPTION:
XS GIS Cut Line= 4
      3436846.74     10598717.64      3436518.61     10598733.26
      3436174.86     10598660.35      3435857.13     10598738.48
#Sta/Elev= 30
  4549.7  505.77  4634.4  504.22  4674.5  502.70  4694.5  502.38  4734.3  500.23
  4784.6  498.69  4814.6  496.68  4874.0  493.90  4915.5  493.37  4976.9  491.74
  4994.3  489.28  4997.0  488.78  5000.3  489.28  5017.7  490.58  5059.2  491.10
  5079.1  490.74  5098.6  491.19  5103.8  490.64  5109.7  490.64  5138.8  491.53
  5148.3  492.04  5153.4  491.81  5191.5  493.47  5198.0  494.06  5203.1  493.64
  5228.5  494.98  5298.6  496.90  5356.0  497.24  5417.8  496.92  5556.8  497.25
#Mann=4,-1,0
  4549.7    0.05       0  4994.3    0.07       0  5000.3    0.05       0
  5138.8    0.05       0
Bank Sta=4994.3,5000.3
Exp/Cntr=0.3,0.1

Type RM Length L Ch R = 1,4242,1371,1371,1371
BEGIN DESCRIPTION:
UNT00501 IN CHRS 5.0
END DESCRIPTION:
XS GIS Cut Line= 2
      3437096.71     10598129.10      3435665.76     10598149.91
#Sta/Elev= 30
  4209.4  511.81  4234.0  511.25  4374.6  510.62  4464.0  509.66  4514.0  508.16
  4584.0  507.39  4615.3  506.25  4684.1  503.35  4704.1  501.24  4774.1  497.75
  4834.1  496.05  4864.1  496.60  4884.1  494.41  4928.5  492.79  4934.1  492.20
  4944.1  492.08  4964.1  489.96  4974.1  488.38  4984.1  487.86  4991.1  486.68
  4993.8  486.18  4997.1  486.68  5024.1  487.99  5088.5  488.19  5174.1  487.71
  5234.1  488.97  5274.1  488.93  5364.1  491.42  5474.1  493.27  5640.5  492.76
#Mann=7,-1,0
  4209.4    0.05       0  4374.6    0.16       0  4615.3    0.05       0
  4928.5    0.16       0  4991.1    0.07       0  4997.1    0.16       0
  5088.5    0.05       0
Bank Sta=4991.1,4997.1
Exp/Cntr=0.3,0.1

Type RM Length L Ch R = 1,2871,805,805,805
BEGIN DESCRIPTION:
UNT00501 IN CHRS 4.0
END DESCRIPTION:
XS GIS Cut Line= 4
      3436732.09     10597062.68      3436223.60     10597149.72
      3435866.28     10597310.06      3435688.23     10597597.68
#Sta/Elev= 30
  4204.9  505.37  4255.6  505.28  4344.4  502.03  4393.5  501.03  4417.9  500.80
  4480.3  498.25  4584.6  494.50  4775.1  488.50  4837.2  486.53  4859.6  485.34
  4882.8  485.30  4981.0  481.94  4986.5  482.47  4993.4  481.69  4996.2  481.19
  4999.4  481.69  5004.1  482.49  5009.6  482.07  5032.8  483.33  5102.3  482.84
  5107.8  484.12  5137.8  483.11  5151.6  483.51  5262.1  486.78  5314.1  489.34
  5326.0  490.57  5356.6  491.49  5377.9  490.90  5393.3  491.83  5450.7  491.95
#Mann=9,-1,0
  4204.9    0.05       0  4393.5    0.16       0  4480.3     0.1       0
  4584.6    0.16       0  4775.1    0.05       0  4837.2    0.16       0
  4993.4    0.07       0  4999.4    0.16       0  5151.6    0.05       0
Bank Sta=4993.4,4999.4
Exp/Cntr=0.3,0.1

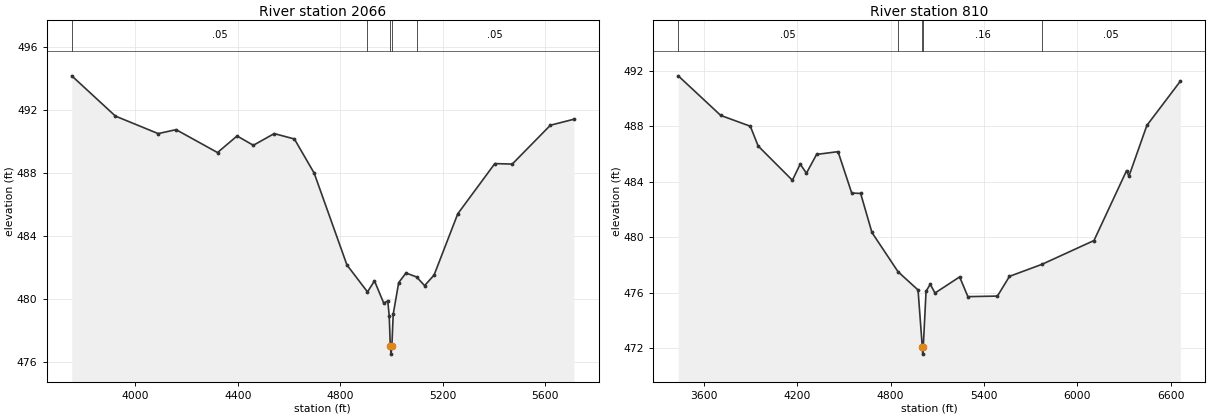
Type RM Length L Ch R = 1,2066,1256,1256,1256
BEGIN DESCRIPTION:
UNT00501 IN CHRS 2.0
END DESCRIPTION:
XS GIS Cut Line= 5
      3436617.59     10596274.75      3435934.99     10596490.06
      3435637.23     10596870.29      3435508.96     10597085.59
      3435637.23     10597580.33
#Sta/Elev= 30
  3751.9  494.16  3922.3  491.61  4089.3  490.50  4159.2  490.75  4321.0  489.30
  4397.3  490.35  4460.9  489.76  4542.4  490.50  4621.1  490.16  4698.3  488.00
  4826.3  482.18  4906.6  480.47  4933.9  481.17  4970.0  479.76  4985.6  479.90
  4991.4  478.97  4995.7  477.03  4998.5  476.53  5001.7  477.03  5007.0  479.06
  5028.4  481.06  5056.9  481.67  5098.0  481.42  5129.6  480.87  5166.6  481.54
  5259.1  485.42  5403.7  488.60  5471.8  488.57  5620.7  491.03  5712.3  491.41
#Mann=5,-1,0
  3751.9    0.05       0  4906.6    0.16       0  4995.7    0.07       0
  5001.7    0.16       0  5098.0    0.05       0
Bank Sta=4995.7,5001.7
Exp/Cntr=0.3,0.1

Type RM Length L Ch R = 1,810,0,0,0
BEGIN DESCRIPTION:
UNT00501 IN CHRS 1.0
END DESCRIPTION:
XS GIS Cut Line= 5
      3436704.60     10595807.50      3435811.31     10595867.05
      3435142.49     10596297.66      3435000.48     10596641.24
      3435623.48     10597626.14
#Sta/Elev= 30
  3434.5  491.63  3707.6  488.78  3898.0  488.00  3948.1  486.58  4168.4  484.11
  4218.7  485.27  4258.8  484.62  4323.8  485.97  4462.0  486.17  4549.8  483.19
  4607.2  483.16  4679.8  480.35  4847.9  477.52  4976.3  476.21  5003.7  472.09
  5006.4  471.59  5009.7  472.09  5027.8  476.12  5054.9  476.62  5085.2  475.99
  5243.6  477.15  5296.8  475.73  5486.6  475.77  5564.0  477.19  5773.7  478.06
  6107.4  479.77  6316.8  484.80  6332.1  484.40  6447.4  488.06  6662.4  491.24
#Mann=5,-1,0
  3434.5    0.05       0  4847.9    0.16       0  5003.7    0.07       0
  5009.7    0.16       0  5773.7    0.05       0
Bank Sta=5003.7,5009.7
Exp/Cntr=0.3,0.1

Chan Stop Cuts=-1