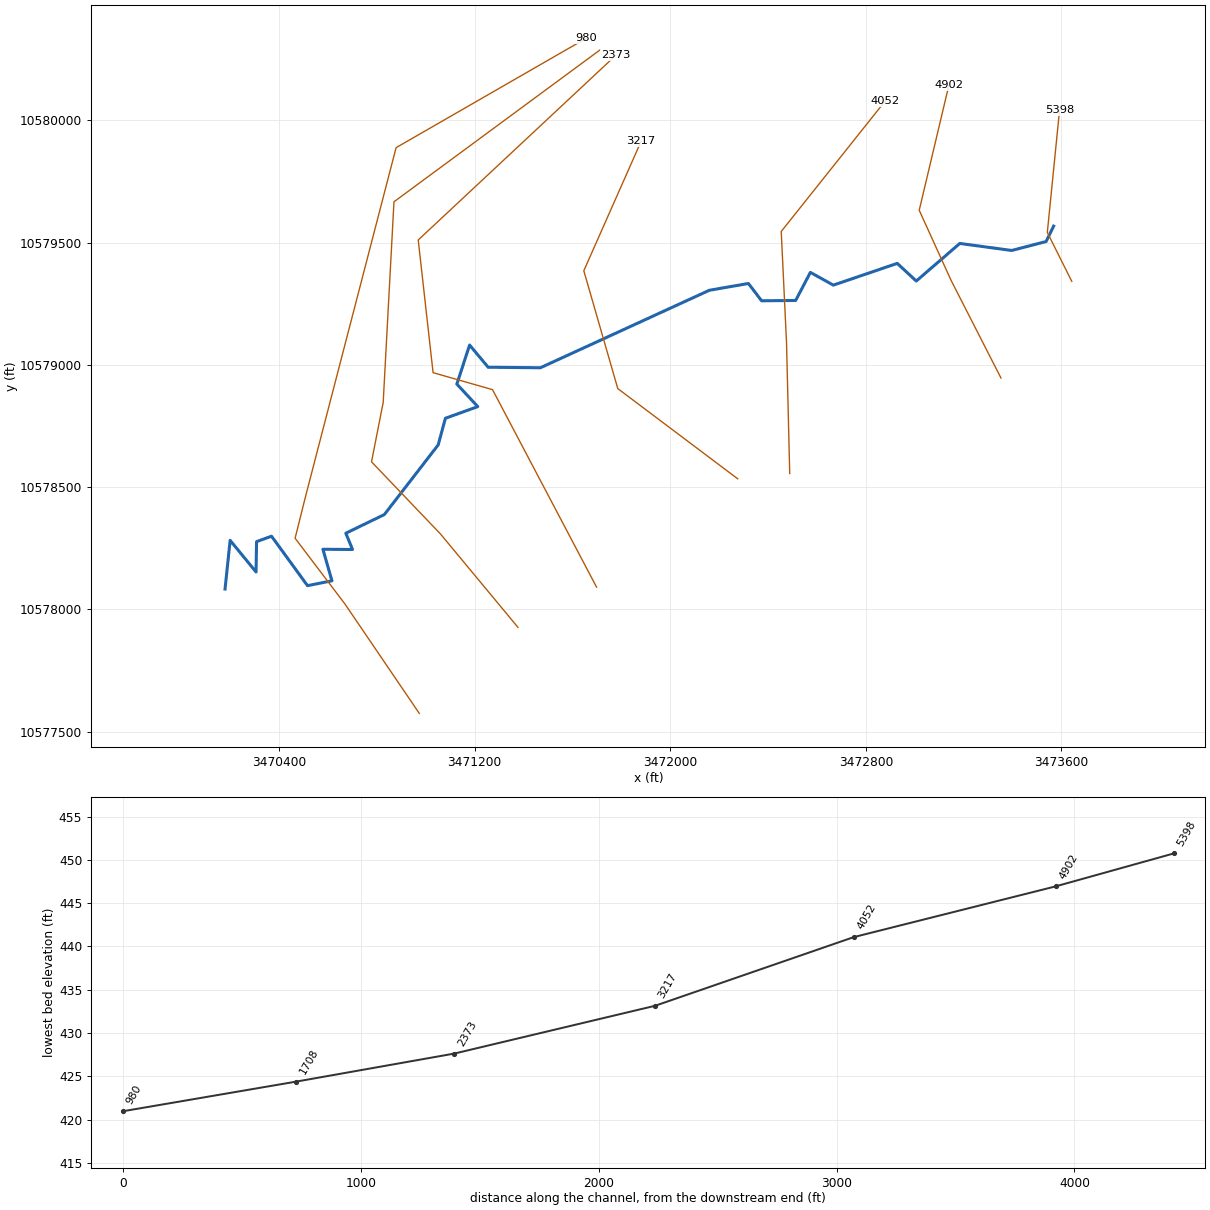
--- UNT0058 IN CHRS.prj (project) ---

Proj Title=UNT0058 IN CHRS Base Level Engineering
Current Plan=p01
Default Exp/Contr=0.3,0.1
English Units
Geom File=g01
Flow File=f01
Plan File=p01
BEGIN DESCRIPTION:
UNT0058 IN CHRS
END DESCRIPTION:

--- UNT0058 IN CHRS.p01 (plan) ---

Plan Title=Multiple Run
Short Identifier=Multiple
Geom File=g01
Flow File=f01
Subcritical Flow
K Sum by GR= 0
Std Step Tol= 0.01
Critical Tol= 0.01
Num of Std Step Trials= 20
Max Error Tol= 0.3
Flow Tol Ratio= 0.001
Split Flow NTrial= 30
Split Flow Tol= 0.02
Split Flow Ratio= 0.02
Log Output Level= 0
Friction Slope Method= 1
Unsteady Friction Slope Method= 2
Unsteady Bridges Friction Slope Method= 1
Parabolic Critical Depth
Global Vel Dist=  1 , 1 , 1
Global Log Level= 0
CheckData=True
Encroach Param= -1, 0, 0, 0
BEGIN DESCRIPTION:
Multiple Run
END DESCRIPTION:

--- UNT0058 IN CHRS.f01 (steady flow) ---

Flow Title=Multiple
Number of Profiles=7
Profile Names=10-year,25-year,50-year,1pct_min,100-year,1pct_plu,500-year
River Rch & RM= UNT0058 IN CHRS,Reach-1,5398
     516     657     762     643     870    1176    1131
Boundary for River Rch & Prof#=UNT0058 IN CHRS,Reach-1,1
Up Type=0
Dn Type=3
Dn Slope=0.005
Boundary for River Rch & Prof#=UNT0058 IN CHRS,Reach-1,2
Up Type=0
Dn Type=3
Dn Slope=0.005
Boundary for River Rch & Prof#=UNT0058 IN CHRS,Reach-1,3
Up Type=0
Dn Type=3
Dn Slope=0.005
Boundary for River Rch & Prof#=UNT0058 IN CHRS,Reach-1,4
Up Type=0
Dn Type=3
Dn Slope=0.005
Boundary for River Rch & Prof#=UNT0058 IN CHRS,Reach-1,5
Up Type=0
Dn Type=3
Dn Slope=0.005
Boundary for River Rch & Prof#=UNT0058 IN CHRS,Reach-1,6
Up Type=0
Dn Type=3
Dn Slope=0.005
Boundary for River Rch & Prof#=UNT0058 IN CHRS,Reach-1,7
Up Type=0
Dn Type=3
Dn Slope=0.005

--- UNT0058 IN CHRS.g01 (geometry) ---

Geom Title=Existing Conditions

River Reach=UNT0058 IN CHRS,Reach-1
Reach XY= 30
      3473567.88     10579567.41      3473537.08     10579504.35
      3473396.46     10579467.89      3473184.22     10579496.54
      3473006.14     10579342.86      3472928.51     10579415.06
      3472667.07     10579326.14      3472573.25     10579378.21
      3472513.04     10579263.42      3472373.72     10579262.12
      3472319.90     10579332.86      3472160.17     10579305.09
      3471469.20     10578988.25      3471255.66     10578990.42
      3471179.71     10579081.13      3471127.62     10578921.41
      3471213.13     10578829.39      3471080.75     10578781.65
      3471051.23     10578672.71      3470831.18     10578387.98
      3470673.63     10578311.60      3470700.97     10578245.19
      3470579.88     10578246.06      3470616.77     10578117.15
      3470516.95     10578097.19      3470369.81     10578299.44
      3470308.61     10578277.31      3470306.44     10578153.18
      3470200.54     10578282.52      3470179.75     10578083.74

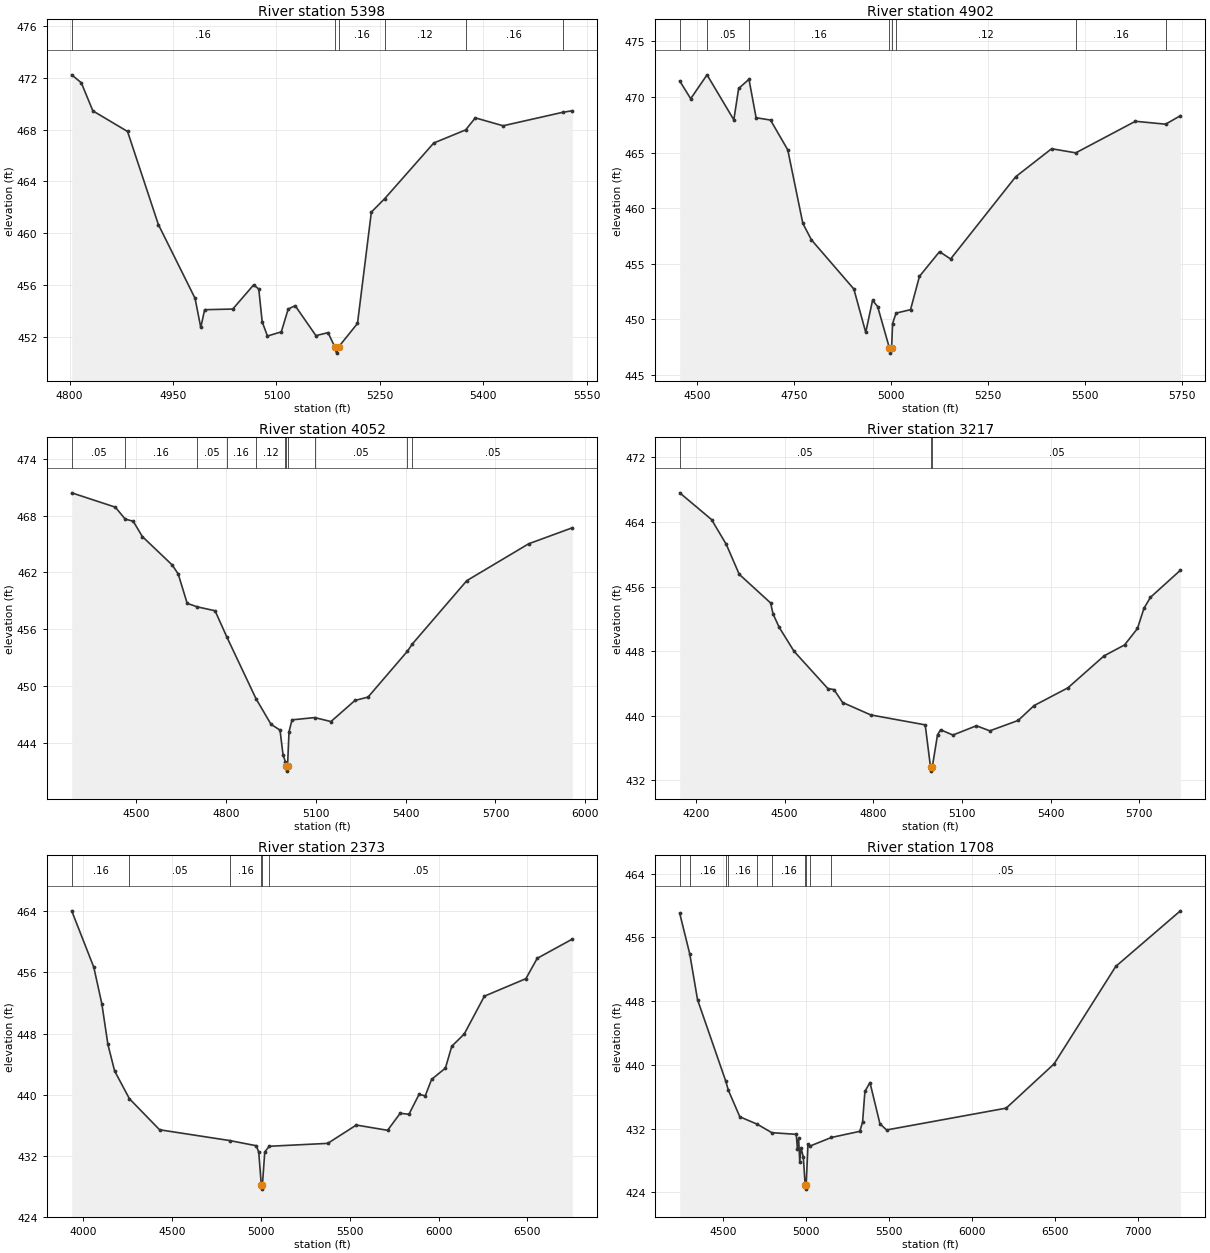
Type RM Length L Ch R = 1,5398,496,496,496
BEGIN DESCRIPTION:
UNT0058 IN CHRS 8.0
END DESCRIPTION:
XS GIS Cut Line= 3
      3473642.09     10579341.67      3473542.11     10579541.64
      3473592.11     10580041.67
#Sta/Elev= 30
  4803.0  472.22  4816.9  471.61  4833.7  469.44  4884.0  467.85  4928.7  460.67
  4981.9  454.98  4990.2  452.73  4995.8  454.10  5036.6  454.15  5066.8  456.01
  5074.3  455.70  5079.3  453.16  5086.9  452.07  5107.0  452.39  5117.0  454.15
  5127.1  454.41  5157.2  452.10  5174.8  452.33  5184.4  451.25  5187.1  450.75
  5190.4  451.25  5217.5  453.04  5237.6  461.63  5257.0  462.67  5328.1  466.96
  5374.3  467.97  5388.4  468.90  5428.6  468.29  5515.2  469.33  5529.1  469.45
#Mann=6,-1,0
  4803.0    0.16       0  5184.4    0.07       0  5190.4    0.16       0
  5257.0    0.12       0  5374.3    0.16       0  5515.2    0.12       0
Bank Sta=5184.4,5190.4
Exp/Cntr=0.3,0.1

Type RM Length L Ch R = 1,4902,850,850,850
BEGIN DESCRIPTION:
UNT0058 IN CHRS 7.0
END DESCRIPTION:
XS GIS Cut Line= 4
      3473352.45     10578946.52      3473148.46     10579345.82
      3473018.26     10579632.28      3473139.78     10580144.40
#Sta/Elev= 30
  4455.7  471.44  4483.9  469.84  4526.0  471.99  4595.0  467.94  4607.4  470.76
  4634.0  471.59  4652.4  468.13  4689.5  467.92  4733.9  465.24  4772.7  458.63
  4794.9  457.14  4904.1  452.72  4934.7  448.82  4952.3  451.70  4965.4  451.14
  4995.4  447.45  4998.1  446.95  5001.4  447.45  5003.9  449.61  5012.8  450.55
  5050.1  450.86  5073.1  453.86  5124.8  456.08  5153.3  455.42  5320.9  462.82
  5413.4  465.34  5475.7  464.97  5629.2  467.81  5707.0  467.55  5745.1  468.31
#Mann=8,-1,0
  4455.7    0.16       0  4526.0    0.05       0  4634.0    0.16       0
  4995.4    0.07       0  5001.4    0.16       0  5012.8    0.12       0
  5475.7    0.16       0  5707.0    0.05       0
Bank Sta=4995.4,5001.4
Exp/Cntr=0.3,0.1

Type RM Length L Ch R = 1,4052,835,835,835
BEGIN DESCRIPTION:
UNT0058 IN CHRS 5.0
END DESCRIPTION:
XS GIS Cut Line= 4
      3472488.74     10578555.86      3472475.72     10579089.74
      3472454.02     10579545.47      3472879.39     10580079.35
#Sta/Elev= 30
  4284.0  470.39  4429.8  468.88  4462.6  467.63  4489.8  467.39  4519.9  465.79
  4619.9  462.79  4639.9  461.84  4669.9  458.75  4703.9  458.38  4763.1  457.97
  4801.9  455.24  4900.0  448.70  4950.1  446.01  4980.1  445.40  4990.1  442.83
  4998.0  442.05  4999.2  441.58  5001.9  441.08  5005.2  441.58  5010.2  445.23
  5020.2  446.48  5096.0  446.72  5150.3  446.30  5230.4  448.52  5274.3  448.88
  5405.8  453.71  5422.2  454.47  5604.2  461.14  5810.8  465.02  5956.9  466.71
#Mann=11,-1,0
  4284.0    0.05       0  4462.6    0.16       0  4703.9    0.05       0
  4801.9    0.16       0  4900.0    0.12       0  4998.0    0.16       0
  4999.2    0.07       0  5005.2    0.16       0  5096.0    0.05       0
  5405.8    0.16       0  5422.2    0.05       0
Bank Sta=4999.2,5005.2
Exp/Cntr=0.3,0.1

Type RM Length L Ch R = 1,3217,844,844,844
BEGIN DESCRIPTION:
UNT0058 IN CHRS 4.0
END DESCRIPTION:
XS GIS Cut Line= 4
      3472276.07     10578534.18      3471785.62     10578903.11
      3471646.73     10579384.88      3471881.11     10579914.42
#Sta/Elev= 30
  4145.2  467.62  4252.8  464.31  4302.8  461.23  4346.5  457.53  4452.7  453.98
  4461.1  452.61  4481.9  450.95  4531.9  448.00  4646.4  443.38  4667.2  443.25
  4696.4  441.65  4791.7  440.11  4975.9  438.88  4993.8  433.65  4996.5  433.15
  4999.8  433.65  5017.6  437.66  5028.0  438.27  5069.6  437.62  5149.2  438.77
  5194.5  438.14  5290.5  439.43  5344.3  441.27  5459.0  443.47  5580.9  447.42
  5650.5  448.78  5694.2  450.82  5716.1  453.31  5737.9  454.67  5839.4  458.03
#Mann=3,-1,0
  4145.2    0.05       0  4993.8   0.035       0  4999.8    0.05       0
Bank Sta=4993.8,4999.8
Exp/Cntr=0.3,0.1

Type RM Length L Ch R = 1,2373,665,665,665
BEGIN DESCRIPTION:
UNT0058 IN CHRS 3.0
END DESCRIPTION:
XS GIS Cut Line= 5
      3471698.83     10578091.44      3471273.46     10578898.77
      3471030.41     10578968.21      3470969.65     10579510.75
      3471777.37     10580265.63
#Sta/Elev= 30
  3935.5  464.06  4060.1  456.66  4105.2  451.87  4139.2  446.57  4177.0  443.10
  4260.0  439.47  4430.0  435.40  4824.1  433.99  4974.2  433.31  4987.9  432.46
  5002.4  428.13  5005.2  427.63  5008.4  428.13  5021.7  432.49  5046.6  433.24
  5375.9  433.62  5536.9  436.02  5712.8  435.33  5783.7  437.56  5833.0  437.43
  5889.7  440.03  5924.8  439.85  5960.5  442.00  6038.2  443.47  6073.8  446.33
  6144.2  447.94  6257.5  452.89  6491.0  455.18  6554.5  457.84  6752.3  460.36
#Mann=6,-1,0
  3935.5    0.16       0  4260.0    0.05       0  4824.1    0.16       0
  5002.4    0.07       0  5008.4    0.16       0  5046.6    0.05       0
Bank Sta=5002.4,5008.4
Exp/Cntr=0.3,0.1

Type RM Length L Ch R = 1,1708,728,728,728
BEGIN DESCRIPTION:
UNT0058 IN CHRS 2.0
END DESCRIPTION:
XS GIS Cut Line= 6
      3471377.62     10577926.55      3471060.79     10578308.49
      3470778.67     10578603.63      3470826.42     10578846.69
      3470870.48     10579666.88      3471711.89     10580287.09
#Sta/Elev= 30
  4238.2  459.02  4298.6  453.92  4345.5  448.18  4515.7  437.95  4531.7  436.79
  4600.7  433.47  4705.8  432.54  4793.6  431.48  4940.9  431.27  4947.8  429.44
  4955.0  430.76  4962.0  427.78  4969.2  429.56  4983.4  428.43  4994.5  424.89
  4997.3  424.39  5000.5  424.89  5011.7  430.09  5021.2  429.78  5153.2  430.88
  5324.1  431.65  5340.8  432.82  5354.7  436.66  5385.3  437.77  5445.5  432.59
  5485.5  431.82  6206.6  434.56  6495.6  440.12  6867.4  452.36  7257.1  459.34
#Mann=10,-1,0
  4238.2    0.05       0  4298.6    0.16       0  4515.7    0.05       0
  4531.7    0.16       0  4705.8    0.05       0  4793.6    0.16       0
  4994.5    0.07       0  5000.5    0.16       0  5021.2    0.12       0
  5153.2    0.05       0
Bank Sta=4994.5,5000.5
Exp/Cntr=0.3,0.1

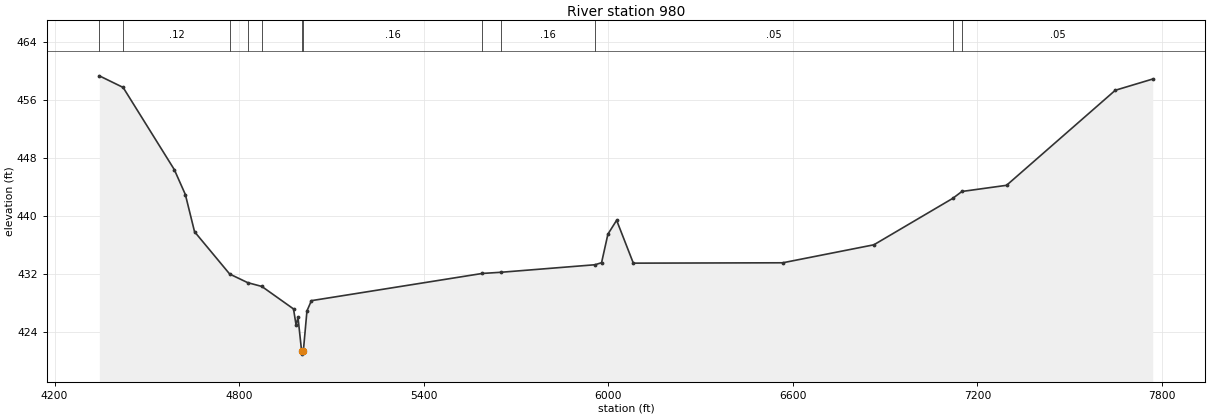
Type RM Length L Ch R = 1,980,0,0,0
BEGIN DESCRIPTION:
UNT0058 IN CHRS 1.0
END DESCRIPTION:
XS GIS Cut Line= 6
      3470973.97     10577575.00      3470670.17     10578022.03
      3470466.17     10578291.13      3470509.58     10578464.74
      3470879.16     10579888.23      3471656.10     10580335.30
#Sta/Elev= 30
  4345.5  459.33  4422.8  457.73  4589.1  446.41  4625.1  442.97  4655.0  437.84
  4769.2  432.01  4827.9  430.82  4873.7  430.30  4976.7  427.20  4985.0  424.98
  4991.3  426.03  5002.8  421.47  5005.6  420.97  5008.8  421.47  5020.4  426.93
  5034.9  428.34  5590.2  432.09  5650.3  432.25  5956.6  433.29  5978.0  433.57
  5998.7  437.51  6027.0  439.42  6081.3  433.51  6566.9  433.56  6863.2  436.04
  7119.6  442.44  7149.4  443.39  7294.5  444.24  7648.0  457.34  7769.7  458.89
#Mann=12,-1,0
  4345.5    0.16       0  4422.8    0.12       0  4769.2    0.16       0
  4827.9    0.12       0  4873.7    0.16       0  5002.8    0.07       0
  5008.8    0.16       0  5590.2    0.12       0  5650.3    0.16       0
  5956.6    0.05       0  7119.6    0.16       0  7149.4    0.05       0
Bank Sta=5002.8,5008.8
Exp/Cntr=0.3,0.1

Chan Stop Cuts=-1