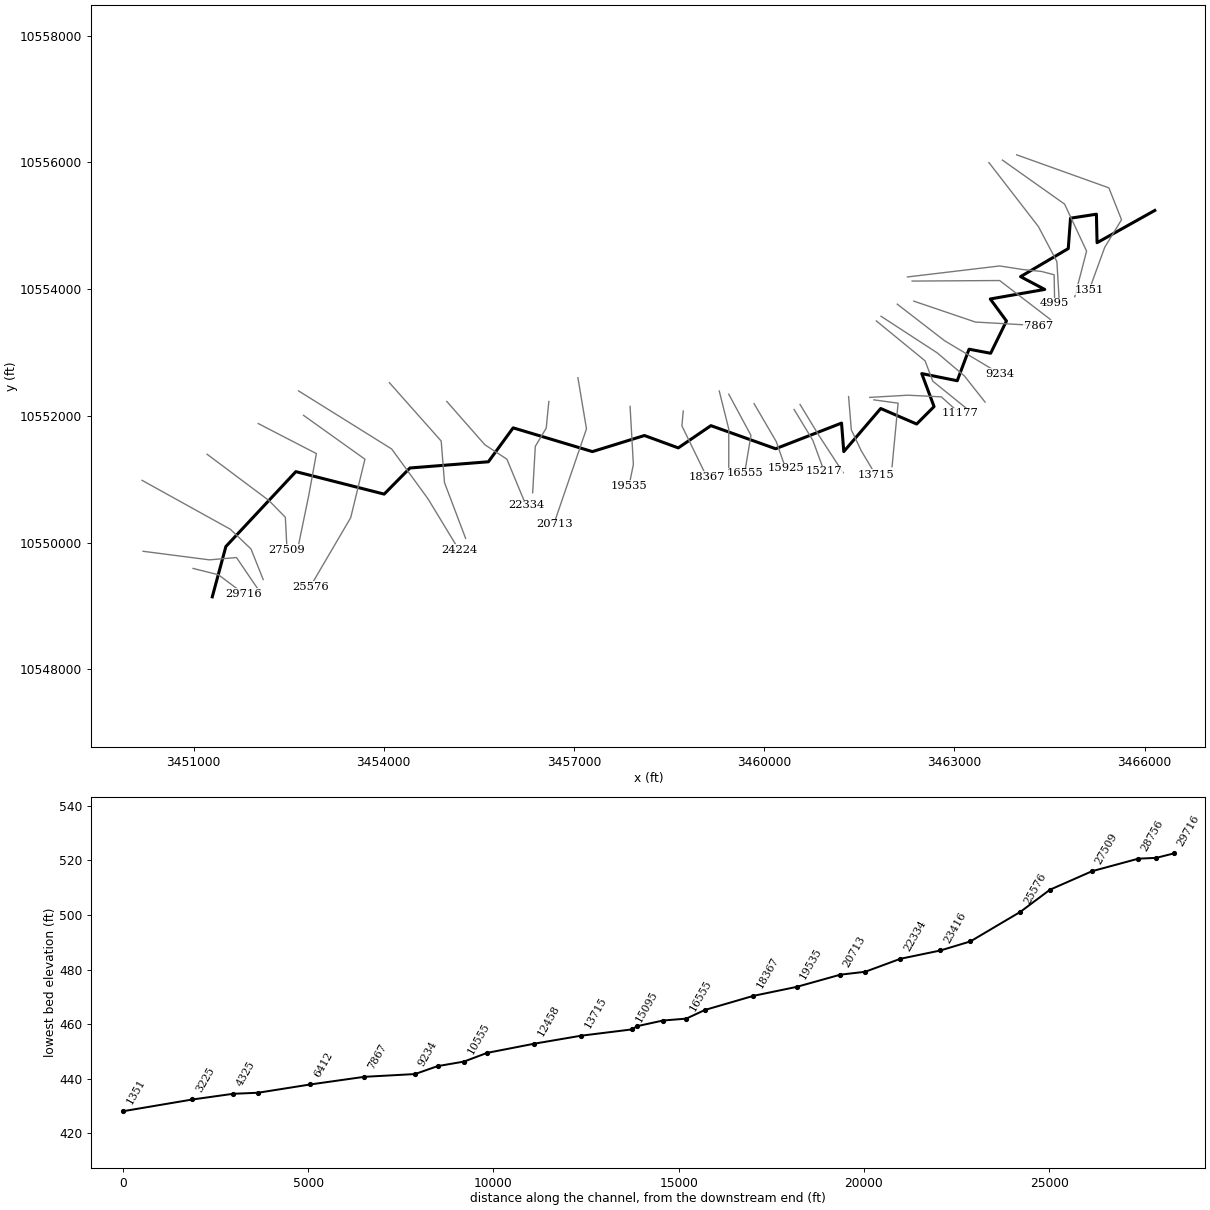
--- UNT0060 IN CHRS.prj (project) ---

Proj Title=UNT0060 IN CHRS Base Level Engineering
Current Plan=p01
Default Exp/Contr=0.3,0.1
English Units
Geom File=g01
Flow File=f01
Plan File=p01
Y Axis Title=Elevation
X Axis Title(PF)=Main Channel Distance
X Axis Title(XS)=Station
BEGIN DESCRIPTION:
UNT0060 IN CHRS
END DESCRIPTION:
DSS File=dss
DSS Export Rating Curves= 0
DSS Export Rating Curve Sorted= 0
DSS Export Volume Flow Curves= 0
DXF OffsetX= 0
DXF OffsetY= 0
DXF ScaleX= 1
DXF ScaleY= 10

--- UNT0060 IN CHRS.p01 (plan) ---

Plan Title=Multiple Run
Program Version=4.10
Short Identifier=Multiple Run
Geom File=g01
Flow File=f01
Subcritical Flow
K Sum by GR= 0
Std Step Tol= 0.01
Critical Tol= 0.01
Num of Std Step Trials= 20
Max Error Tol= 0.3
Flow Tol Ratio= 0.001
Split Flow NTrial= 30
Split Flow Tol= 0.02
Split Flow Ratio= 0.02
Log Output Level= 0
Friction Slope Method= 1
Unsteady Friction Slope Method= 2
Unsteady Bridges Friction Slope Method= 1
Parabolic Critical Depth
Global Vel Dist= 1 , 1 , 1
Global Log Level= 0
CheckData=True
Encroach Param=-1 ,0,0, 0
BEGIN DESCRIPTION:
Multiple Run
END DESCRIPTION:
Computation Interval=1HOUR
Output Interval=1HOUR
Run HTab= 0
Run UNet= 0
Run PostProcess= 0
Run WQNet= 0
UNET Theta= 1
UNET Theta Warmup= 1
UNET ZTol= 0.02
UNET ZSATol= 0.05
UNET MxIter= 20
UNET MaxInSteps= 0
UNET DtIC= 0
UNET DtMin= 0
UNET MaxCRTS= 20
UNET WFStab= 2
UNET SFStab= 1
UNET WFX= 1
UNET SFX= 1
UNET DSS MLevel= 4
UNET DZMax Abort= 100
UNET Convert EG Bridges= 0
UNET Use Existing IB Tables=-1
UNET Froude Reduction=False
UNET Froude Limit= 1
UNET Froude Power= 10
UNET Time Slicing=0,0, 5
UNET Junction Losses=0
Instantaneous Interval=1HOUR
DSS File=dss
Write IC File= 0
Write IC File at Sim End=0
Echo Input=False
Echo Parameters=False
Echo Output=False
Write Detailed= 0
WQ AD Non Conservative
WQ ULTIMATE=-1
WQ Max Comp Step=1HOUR
WQ Output Interval=15MIN
WQ Output Selected Increments= 0
WQ Output face flow=0
WQ Output face velocity=0
WQ Output face area=0
WQ Output face dispersion=0
WQ Output cell volume=0
WQ Output cell surface area=0
WQ Output cell continuity=0
WQ Output cumulative cell continuity=0
WQ Output face conc=0
WQ Output face dconc_dx=0
WQ Output face courant=0
WQ Output face peclet=0
WQ Output face adv mass=0
WQ Output face disp mass=0
WQ Output cell mass=0
WQ Output cell source sink temp=0
WQ Output cell source sink nsm=0
WQ Output MaxMinRange=-1
WQ Daily Max Min Mean=-1
WQ Daily Range=0
WQ Daily Time=0
WQ Create Restart=0
WQ Fixed Restart=0
WQ System Summary=0
WQ Use Fixed Temperature=0
Sorting and Armoring Iterations= 10
XS Update Threshold= 0.02
Hydraulics Update Threshold= 0.02
Energy Slope Method= 1
Volume Change Method= 0
XS Weighting Method= 0
Number of US Weighted Cross Sections= 1
Number of DS Weighted Cross Sections= 1
Upstream XS Weight=0.25
Main XS Weight=0.5
Downstream XS Weight=0.25
Number of DS XS's Weighted with US Boundary= 1
Upstream Boundary Weight= 1
Weight of XSs Associated with US Boundary= 0
Number of US XS's Weighted with DS Boundary= 1
Downstream Boundary Weight= 0.5
Weight of XSs Associated with DS Boundary= 0.5
Sediment Output Level= 4
Mass or Volume Output= 0
Output Increment Type= 1
Profile and TS Output Increment= 10
XS Output Flag= 0
XS Output Increment= 10
Disregard all LS=0
Disregard all Conn=0
Disregard all Breaches=0
Disregard all Pumps=0

--- UNT0060 IN CHRS.f01 (steady flow) ---

Flow Title=Multiple
Number of Profiles=7
Profile Names=10-year,25-year,50-year,1pct_min,100-year,1pct_plu,500-year
River Rch & RM= UNT0060 IN CHRS,Reach-1,29716
     771    1004    1183    1013    1370    1852    1834
River Rch & RM= UNT0060 IN CHRS,Reach-1,22334
     849    1107    1304    1117    1510    2043    2021
River Rch & RM= UNT0060 IN CHRS,Reach-1,10555
    1183    1563    1860    1606    2172    2938    2957
River Rch & RM= UNT0060 IN CHRS,Reach-1,4325
    1372    1825    2180    1889    2555    3455    3502
Boundary for River Rch & Prof#=UNT0060 IN CHRS,Reach-1,1
Up Type=0
Dn Type=3
Dn Slope=0.005
Boundary for River Rch & Prof#=UNT0060 IN CHRS,Reach-1,2
Up Type=0
Dn Type=3
Dn Slope=0.005
Boundary for River Rch & Prof#=UNT0060 IN CHRS,Reach-1,3
Up Type=0
Dn Type=3
Dn Slope=0.005
Boundary for River Rch & Prof#=UNT0060 IN CHRS,Reach-1,4
Up Type=0
Dn Type=3
Dn Slope=0.005
Boundary for River Rch & Prof#=UNT0060 IN CHRS,Reach-1,5
Up Type=0
Dn Type=3
Dn Slope=0.005
Boundary for River Rch & Prof#=UNT0060 IN CHRS,Reach-1,6
Up Type=0
Dn Type=3
Dn Slope=0.005
Boundary for River Rch & Prof#=UNT0060 IN CHRS,Reach-1,7
Up Type=0
Dn Type=3
Dn Slope=0.005

--- UNT0060 IN CHRS.g01 (geometry) ---

Geom Title=Existing Conditions
Program Version=4.10

River Reach=UNT0060 IN CHRS ,Reach-1
Reach XY= 30
      3451295.26     10549142.85      3451509.71     10549937.63
      3452613.31     10551119.19      3454006.49     10550764.56
        3454413.     10551176.88      3455650.74     10551274.99
      3456041.08     10551810.41      3457291.27     10551435.56
      3458111.97     10551689.38      3458645.88     10551494.05
      3459160.86     10551845.11      3460181.39     10551480.65
      3461220.98     10551885.51      3461256.65     10551435.62
      3461839.08     10552115.57      3462405.82     10551870.76
       3462680.4     10552146.05      3462486.33     10552666.65
      3463046.33     10552553.86      3463232.38     10553051.47
      3463572.94     10552987.33      3463822.63     10553496.76
      3463567.11      10553844.4      3464426.04     10553995.04
      3464044.78      10554196.7      3464797.59     10554640.02
      3464832.83      10555119.5       3465241.2     10555182.31
      3465251.86     10554732.64      3466162.11     10555241.64

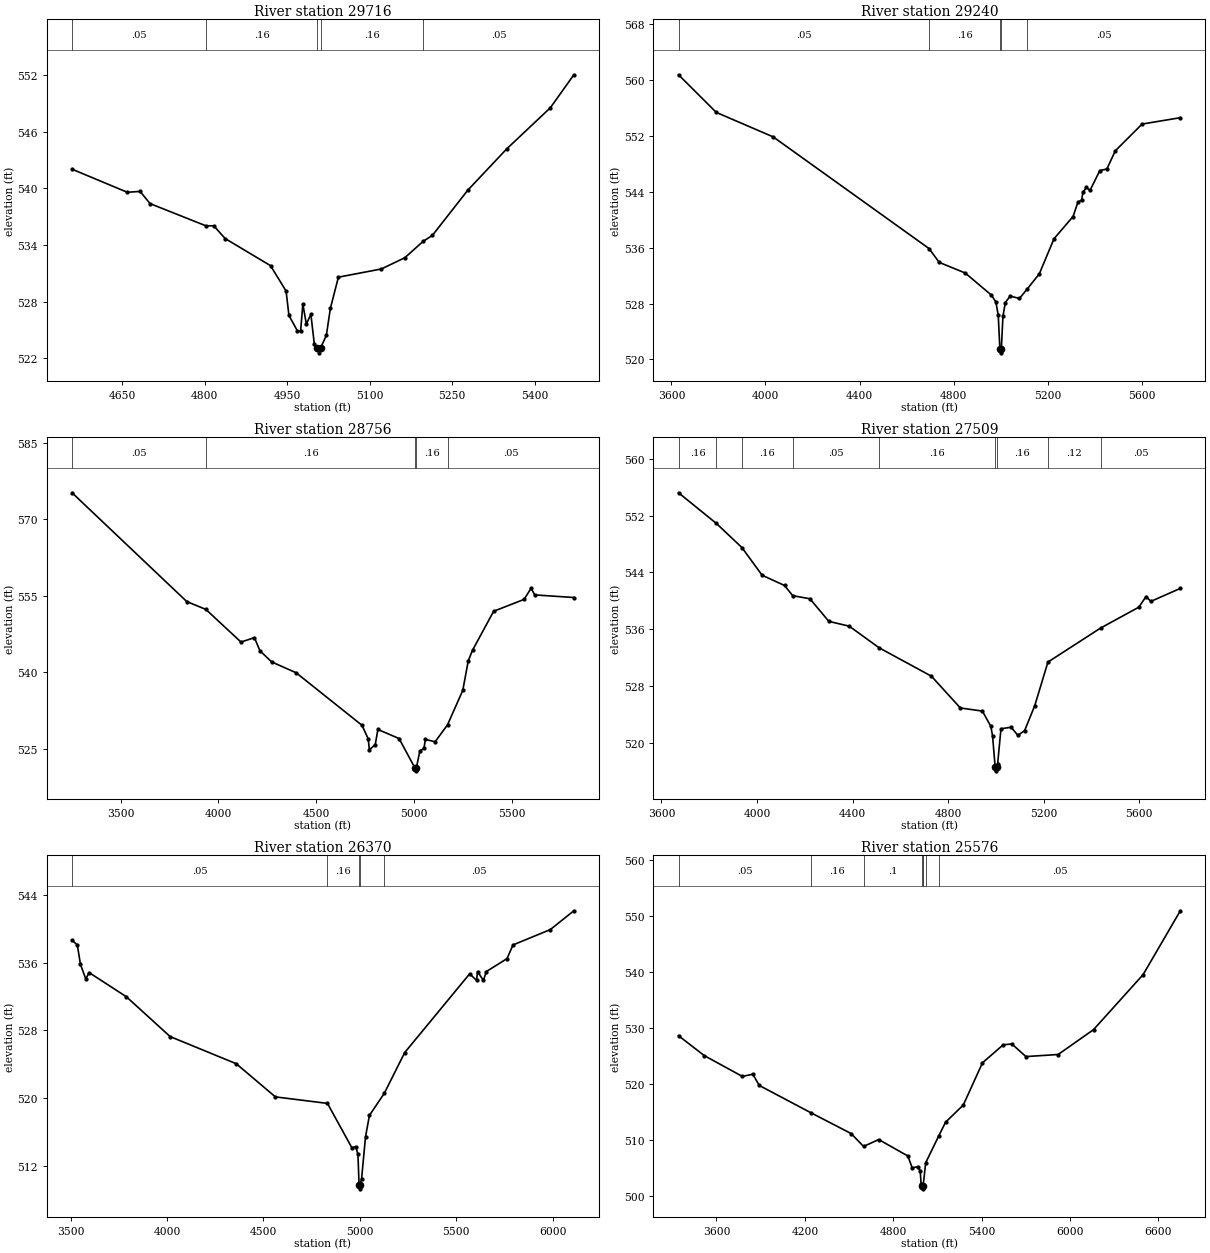
Type RM Length L Ch R = 1 ,29716   ,476,476,476
BEGIN DESCRIPTION:
UNT0060 IN CHRS 44.0
END DESCRIPTION:
XS GIS Cut Line= 3
      3450992.08     10549591.65      3451392.11     10549491.64
      3451792.07     10549191.67
#Sta/Elev= 30
  4559.1  542.02  4659.6  539.58  4682.8  539.67  4700.9  538.38  4802.4  536.03
  4816.8  536.03  4837.4  534.68  4919.9  531.81  4948.2  529.12  4953.4  526.54
  4968.9  524.89  4974.6  524.89  4978.7  527.74    4985  525.63  4993.3  526.65
  4999.6  523.47  5004.9  523.08  5007.6  522.58  5010.9  523.08  5021.4  524.43
  5028.7  527.28  5043.3  530.59  5121.4  531.46  5164.1  532.65  5197.3  534.38
  5214.1  535.01  5278.7  539.81  5349.6  544.19  5428.7  548.53  5471.4  552.02
#Mann= 5 ,-1 , 0
  4559.1     .05       0  4802.4     .16       0  5004.9     .07       0
  5010.9     .16       0  5197.3     .05       0
Bank Sta=5004.9,5010.9
XS Rating Curve= 0 ,0
Exp/Cntr=0.3,0.1

Type RM Length L Ch R = 1 ,29240   ,484,484,484
BEGIN DESCRIPTION:
UNT0060 IN CHRS 43.0
END DESCRIPTION:
XS GIS Cut Line= 4
      3450203.06     10549862.31      3451249.93      10549726.9
      3451677.02     10549763.36      3452041.57     10549226.94
#Sta/Elev= 30
  3630.4  560.79  3790.8   555.4  4032.8  551.89  4695.2  535.89  4738.4  533.91
  4848.8  532.39  4959.2  529.25  4979.2  528.25  4989.3  526.34  4996.3  521.45
    4999  520.95  5002.3  521.45  5009.3  526.18  5019.4  528.16  5040.1  529.08
  5079.6  528.74  5112.9  530.12  5163.6  532.25  5226.5  537.31  5307.3  540.48
  5328.3  542.57  5343.2   542.8  5349.3  543.95  5364.2  544.65  5379.1  544.21
  5421.1  547.07    5451  547.29  5486.9   549.9  5600.8  553.73  5763.2  554.64
#Mann= 5 ,-1 , 0
  3630.4     .05       0  4695.2     .16       0  4996.3     .07       0
  5002.3     .16       0  5112.9     .05       0
Bank Sta=4996.3,5002.3
XS Rating Curve= 0 ,0
Exp/Cntr=0.3,0.1

Type RM Length L Ch R = 1 ,28756   ,1247,1247,1247
BEGIN DESCRIPTION:
UNT0060 IN CHRS 41.0
END DESCRIPTION:
XS GIS Cut Line= 4
      3450187.47     10550982.09      3451578.06     10550211.27
      3451906.18     10549898.77      3452098.46     10549415.48
#Sta/Elev= 30
  3252.2  575.21  3837.9  553.87  3935.9  552.32    4115  545.92  4183.6  546.78
  4212.2  544.19  4271.8  542.02  4396.5   539.9    4733  529.59  4765.1  526.91
  4770.8  524.77    4801   525.8  4814.3  528.77  4922.5  526.99  5004.4  521.15
  5007.2  520.65  5010.4  521.15  5028.5  524.49  5049.9  525.08  5056.8  526.82
  5106.5  526.35    5170  529.67  5248.1  536.45    5276  542.25  5297.7  544.31
  5405.6  551.96  5561.2  554.29  5597.1  556.49    5615  555.17  5815.4  554.66
#Mann= 5 ,-1 , 0
  3252.2     .05       0  3935.9     .16       0  5004.4     .07       0
  5010.4     .16       0    5170     .05       0
Bank Sta=5004.4,5010.4
XS Rating Curve= 0 ,0
Exp/Cntr=0.3,0.1

Type RM Length L Ch R = 1 ,27509   ,1139,1139,1139
BEGIN DESCRIPTION:
UNT0060 IN CHRS 39.0
END DESCRIPTION:
XS GIS Cut Line= 4
      3451213.48     10551393.56      3452187.43      10550664.4
      3452447.85     10550398.77      3452473.89     10549888.38
#Sta/Elev= 30
  3671.8  555.21  3830.3  550.89    3937   547.5  4021.6   543.6  4115.4  542.16
  4149.5  540.73  4221.6  540.29  4300.8  537.11  4386.3  536.43  4510.6   533.4
  4730.1  529.39    4851  524.92  4943.2  524.48  4978.5  522.34  4985.7  521.02
  4996.8  516.57  4999.6  516.07  5002.8  516.57  5006.8  516.97    5021  521.99
  5063.4  522.21  5091.7  521.07    5120  521.73  5162.4  525.25  5217.5  531.38
  5437.5  536.16    5598  539.11  5628.1  540.61  5648.1  539.92  5771.5  541.75
#Mann= 9 ,-1 , 0
  3671.8     .16       0  3830.3     .05       0    3937     .16       0
  4149.5     .05       0  4510.6     .16       0  4996.8     .07       0
  5002.8     .16       0  5217.5     .12       0  5437.5     .05       0
Bank Sta=4996.8,5002.8
XS Rating Curve= 0 ,0
Exp/Cntr=0.3,0.1

Type RM Length L Ch R = 1 ,26370   ,794,794,794
BEGIN DESCRIPTION:
UNT0060 IN CHRS 37.0
END DESCRIPTION:
XS GIS Cut Line= 4
      3452020.74     10551877.95      3452937.43     10551403.98
      3452817.64     10550747.73      3452635.34     10549862.27
#Sta/Elev= 30
  3507.2  538.65  3534.4  538.11  3550.9  535.79  3578.6  534.07  3595.2  534.84
  3788.8  531.98  4015.9  527.27  4358.9  524.06  4561.9  520.14  4832.2  519.37
  4958.3  514.14  4978.7  514.26  4990.2  513.35    4996  509.77  4998.7  509.27
    5002  509.77  5009.2  510.47  5029.5  515.42  5049.8  517.95  5127.3  520.58
  5232.9  525.38  5569.8  534.69  5605.6  533.91  5610.7  534.95  5641.3   533.9
  5655.9  534.95  5763.8  536.49  5794.4   538.1  5988.4  539.92  6110.3  542.14
#Mann= 5 ,-1 , 0
  3507.2     .05       0  4832.2     .16       0    4996     .07       0
    5002     .16       0  5127.3     .05       0
Bank Sta=4996,5002
XS Rating Curve= 0 ,0
Exp/Cntr=0.3,0.1

Type RM Length L Ch R = 1 ,25576   ,1352,1352,1352
BEGIN DESCRIPTION:
UNT0060 IN CHRS 35.0
END DESCRIPTION:
XS GIS Cut Line= 4
      3452734.31     10552008.15      3453703.06     10551315.44
       3453479.1     10550393.57      3452838.46     10549299.79
#Sta/Elev= 30
  3342.5   528.6  3517.5  525.04  3775.6  521.32  3846.8  521.71    3891   519.7
  4238.8  514.85    4514   511.1  4598.7  508.79    4702  510.02  4900.1  507.07
  4928.4  504.99  4969.6  505.13  4983.6  504.35  4990.1  501.98  4997.4   501.7
  5000.2   501.2  5003.4   501.7  5004.2  501.94  5020.6  505.86  5108.4  510.62
  5155.8  513.13  5275.9  516.19  5406.4  523.76  5546.8  526.97  5605.4  527.13
  5701.2  524.87  5920.1  525.24  6160.5  529.69  6496.8  539.53  6749.7  550.96
#Mann= 8 ,-1 , 0
  3342.5     .05       0  4238.8     .16       0  4598.7      .1       0
  4997.4     .07       0  5003.4      .1       0  5004.2     .16       0
  5020.6      .1       0  5108.4     .05       0
Bank Sta=4997.4,5003.4
XS Rating Curve= 0 ,0
Exp/Cntr=0.3,0.1

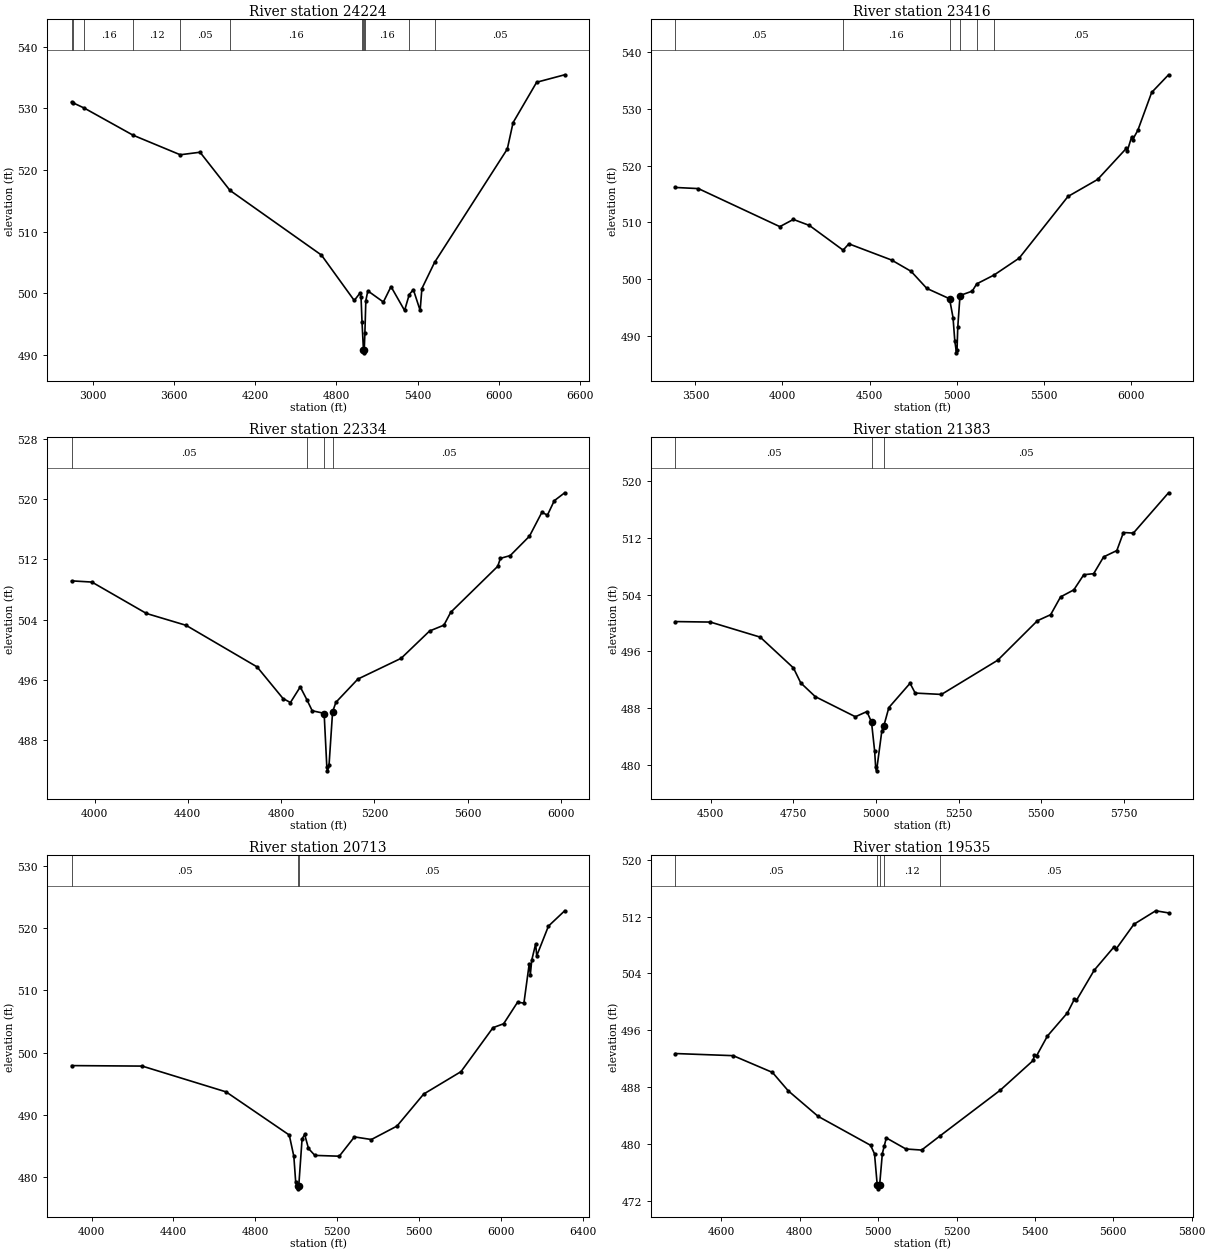
Type RM Length L Ch R = 1 ,24224   ,808,808,808
BEGIN DESCRIPTION:
UNT0060 IN CHRS 33.0
END DESCRIPTION:
XS GIS Cut Line= 4
      3452656.18     10552393.57      3454124.93      10551476.9
      3454697.85     10550690.44      3455187.28      10549883.4
#Sta/Elev= 30
  2840.8  531.01  2850.7  530.89  2935.9  530.01  3294.6  525.64  3644.3  522.46
  3790.8  522.87  4011.9  516.69  4689.3  506.19  4931.9  498.83  4974.5  500.03
  4982.1  499.35  4989.4  495.33  4999.9  490.84  5002.7  490.34  5005.9  490.84
  5010.6  493.57  5017.6   498.8  5032.3  500.39  5147.4  498.58  5203.8  501.08
  5304.3  497.21  5338.9   499.8  5369.2  500.59  5419.4  497.21  5432.3  500.76
  5525.8  504.99  6064.3  523.39    6107  527.67  6281.5  534.22    6489  535.43
#Mann= 12 ,-1 , 0
  2840.8     .16       0  2850.7     .05       0  2935.9     .16       0
  3294.6     .12       0  3644.3     .05       0  4011.9     .16       0
  4989.4      .1       0  4999.9     .07       0  5005.9      .1       0
  5010.6     .16       0  5338.9      .1       0  5525.8     .05       0
Bank Sta=4999.9,5005.9
XS Rating Curve= 0 ,0
Exp/Cntr=0.3,0.1

Type RM Length L Ch R = 1 ,23416   ,1082,1082,1082
BEGIN DESCRIPTION:
UNT0060 IN CHRS 31.0
END DESCRIPTION:
XS GIS Cut Line= 4
      3454088.47     10552523.77      3454906.18      10551601.9
      3454958.27     10550945.65      3455291.39       10550066.
#Sta/Elev= 30
  3385.7  516.15  3517.4  515.95  3984.9  509.25  4062.7  510.52  4154.7  509.46
  4348.2  505.11  4381.3  506.22  4626.4  503.37  4738.6  501.38  4828.9  498.37
  4959.3  496.55  4979.4  493.24  4989.4  489.19  4999.2  487.02  5002.4  487.52
  5006.6  491.52  5019.5  497.12  5089.7  497.89  5115.5  499.17  5215.2  500.73
  5359.2   503.7  5639.4  514.56  5809.7  517.56  5974.6  523.04  5979.9  522.57
  6004.8  525.04  6010.1  524.54  6040.3   526.2    6120  532.89  6216.9     536
#Mann= 6 ,-1 , 0
  3385.7     .05       0  4348.2     .16       0  4959.3     .07       0
  5019.5     .16       0  5115.5      .1       0  5215.2     .05       0
Bank Sta=4959.3,5019.5
XS Rating Curve= 0 ,0
Exp/Cntr=0.3,0.1

Type RM Length L Ch R = 1 ,22334   ,951,951,951
BEGIN DESCRIPTION:
UNT0060 IN CHRS 29.0
END DESCRIPTION:
XS GIS Cut Line= 4
      3454994.71     10552226.91      3455593.68     10551544.61
      3455942.64     10551315.44      3456244.66     10550586.42
#Sta/Elev= 30
  3901.9  509.14  3988.8  508.98  4222.7  504.82  4392.6  503.25  4697.2  497.74
  4808.5  493.55  4840.2  493.02  4882.3  495.09  4911.6  493.34  4933.6  491.93
  4984.3  491.59  4984.8  491.56  4996.3  484.47  4999.1  483.97  5005.9  484.79
    5021  491.79  5035.2  493.05  5129.5  496.13    5315  498.88  5437.1   502.5
  5498.4  503.27  5527.7  504.98  5729.3  511.07  5740.5  512.12  5782.8  512.49
  5865.3  515.06  5918.5  518.22  5942.4  517.85  5971.7  519.76  6016.4  520.81
#Mann= 4 ,-1 , 0
  3901.9     .05       0  4911.6     .16       0  4984.3     .07       0
    5021     .05       0
Bank Sta=4984.8,5021
XS Rating Curve= 0 ,0
Exp/Cntr=0.3,0.1

Type RM Length L Ch R = 1 ,21383   ,670,670,670
BEGIN DESCRIPTION:
UNT0060 IN CHRS 27.0
END DESCRIPTION:
XS GIS Cut Line= 4
       3456604.1     10552226.87      3456562.43     10551805.02
      3456390.56     10551518.57      3456348.96     10550785.41
#Sta/Elev= 30
  4393.4  500.21  4499.1  500.14  4649.9  498.02  4750.4  493.69  4772.6  491.58
  4816.5  489.65  4937.9  486.82  4972.8  487.55  4986.7  486.07  4996.2  481.99
  4999.3  479.71    5002  479.21  5017.8  484.77  5023.7  485.48  5039.2  488.11
  5103.4  491.53  5118.9  490.15  5198.4  489.96  5368.6  494.77  5488.8  500.33
  5528.9  501.18  5558.9  503.68    5599  504.67  5629.1   506.8  5659.1  506.95
  5689.2  509.31  5729.2   510.2  5749.2  512.74  5779.3  512.66  5885.7  518.33
#Mann= 3 , 0 , 0
  4393.4     .05       0  4986.7    .035       0  5023.7     .05       0
Bank Sta=4986.7,5023.7
XS Rating Curve= 0 ,0
Exp/Cntr=0.3,0.1

Type RM Length L Ch R = 1 ,20713   ,1178,1178,1178
BEGIN DESCRIPTION:
UNT0060 IN CHRS 25.0
END DESCRIPTION:
XS GIS Cut Line= 4
      3457062.43     10552601.91      3457197.85     10551794.61
      3456687.43     10550305.02      3456692.66     10550289.36
#Sta/Elev= 30
  3902.7  497.94  4247.7  497.86  4657.4  493.72  4966.3  486.79  4988.7  483.36
  4997.6  479.28  5006.8  478.65  5009.6  478.15  5012.8  478.65  5028.9  486.17
  5041.5  486.89  5060.2  484.63  5091.4  483.52  5210.7  483.39  5284.7  486.49
  5367.7  486.07  5492.8  488.23  5623.2  493.37  5805.6  496.97    5962  504.03
    6014  504.66  6081.9  508.11  6113.1  507.98  6139.1   514.3  6144.4  512.54
  6151.5  514.89  6170.4  517.48  6175.7  515.57    6233  520.34  6312.4   522.8
#Mann= 3 ,-1 , 0
  3902.7     .05       0  5006.8    .035       0  5012.8     .05       0
Bank Sta=5006.8,5012.8
XS Rating Curve= 0 ,0
Exp/Cntr=0.3,0.1

Type RM Length L Ch R = 1 ,19535   ,1168,1168,1168
BEGIN DESCRIPTION:
UNT0060 IN CHRS 23.0
END DESCRIPTION:
XS GIS Cut Line= 4
      3457885.35     10552148.73      3457906.18     10551784.19
      3457937.43     10551232.11      3457869.73     10550898.82
#Sta/Elev= 30
  4482.8  492.73  4630.1  492.43  4730.3  490.07  4770.4  487.49  4846.7  483.89
  4980.7  479.81  4990.7  478.61  4997.7  474.18  5000.5  473.68  5003.7  474.18
  5010.7  478.65  5015.7  479.74  5020.8  480.85  5070.8  479.29  5110.9  479.14
    5158  481.14  5311.2  487.55  5395.7  491.76  5398.6  492.53  5404.5  492.44
    5432   495.2    5483  498.46  5500.7  500.37  5505.8   500.2  5551.3  504.46
  5601.9  507.75    5607  507.43  5652.6  510.93  5708.3  512.83    5741  512.53
#Mann= 5 ,-1 , 0
  4482.8     .05       0  4997.7    .035       0  5003.7     .05       0
  5015.7     .12       0    5158     .05       0
Bank Sta=4997.7,5003.7
XS Rating Curve= 0 ,0
Exp/Cntr=0.3,0.1

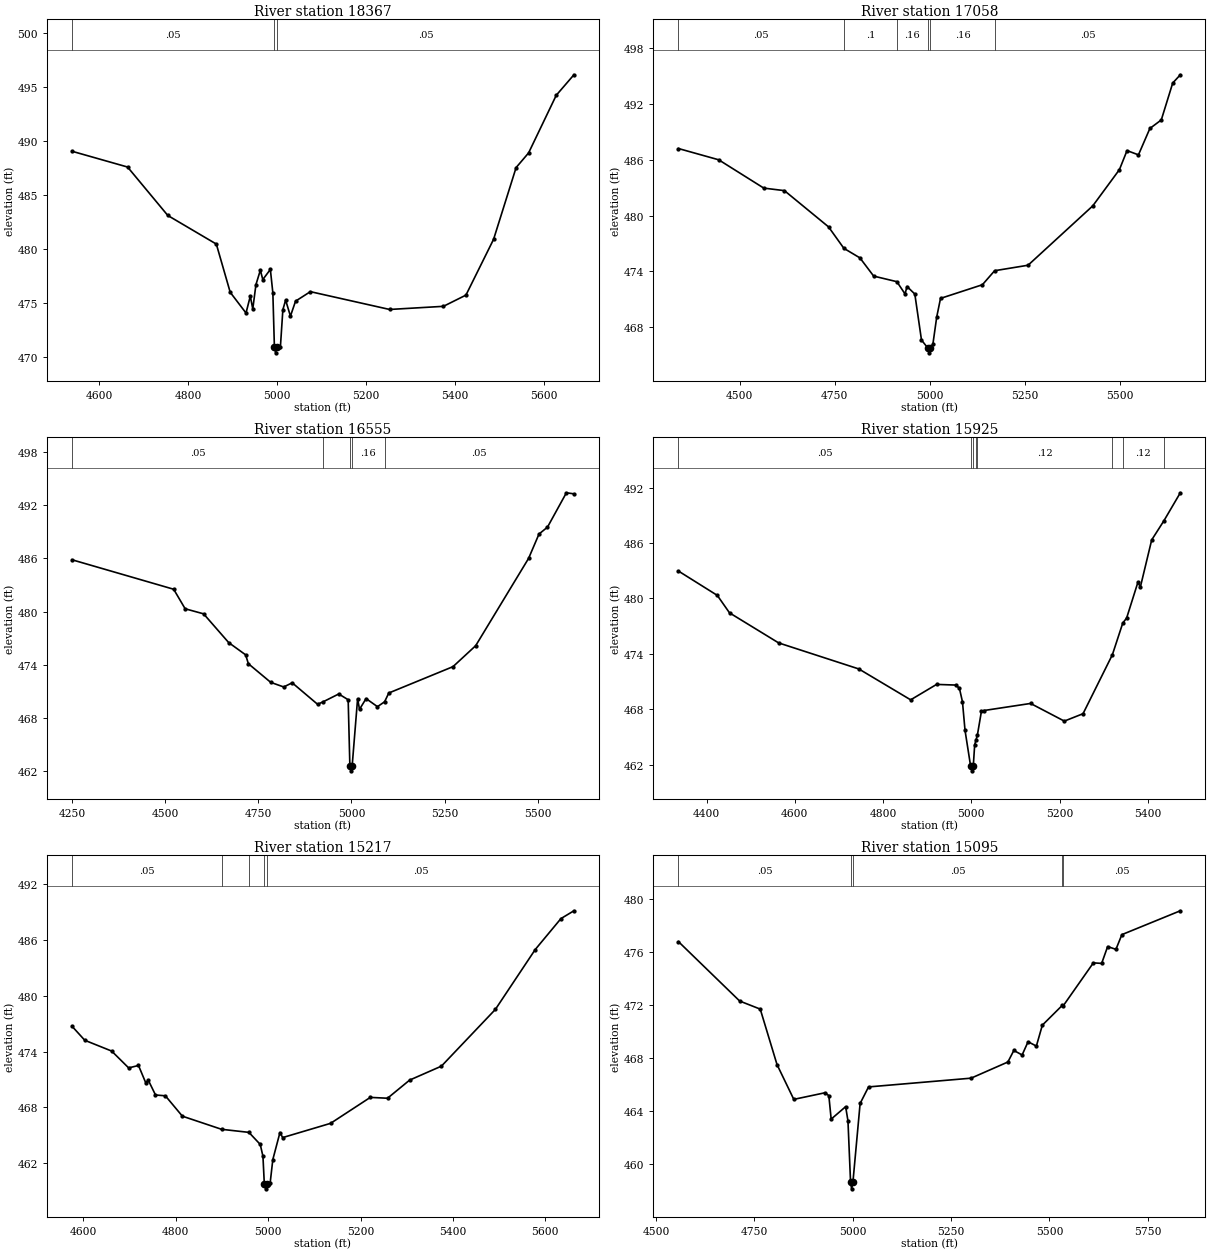
Type RM Length L Ch R = 1 ,18367   ,1309,1309,1309
BEGIN DESCRIPTION:
UNT0060 IN CHRS 20.0
END DESCRIPTION:
XS GIS Cut Line= 3
      3458723.89     10552075.87      3458703.06     10551841.48
       3459093.7     10551039.36
#Sta/Elev= 30
  4539.4  489.07  4664.1  487.61  4754.5  483.12  4863.5  480.47  4894.7     476
  4930.2  474.08  4939.8  475.64  4945.4  474.46  4952.5  476.71  4962.4  478.05
  4967.9  477.18  4984.9  478.12  4990.5  475.95    4994  470.89  4996.7  470.39
    5000  470.89  5007.4   470.9    5013  474.39  5019.2  475.28    5030  473.79
  5041.5  475.18  5074.8  476.06  5252.8  474.41  5373.7   474.7  5424.3  475.74
  5486.4  480.91    5537  487.56  5565.1  488.92  5627.2  494.26  5666.9  496.16
#Mann= 3 ,-1 , 0
  4539.4     .05       0    4994    .035       0    5000     .05       0
Bank Sta=4994,5000
XS Rating Curve= 0 ,0
Exp/Cntr=0.3,0.1

Type RM Length L Ch R = 1 ,17058   ,503,503,503
BEGIN DESCRIPTION:
UNT0060 IN CHRS 19.0
END DESCRIPTION:
XS GIS Cut Line= 3
      3459292.12      10552391.6      3459442.11     10551791.64
      3459442.11     10551091.67
#Sta/Elev= 30
  4339.6  487.21  4445.2     486  4563.8  482.95  4617.9  482.68  4733.8  478.78
  4774.1  476.47  4816.3  475.44  4852.4  473.48  4913.3  472.88  4934.8  471.56
    4940  472.36  4960.5  471.55    4978   466.6    4995  465.72  4997.8  465.22
    5001  465.72    5008  466.16    5018  469.07    5028  471.08    5138  472.55
  5170.2  474.06    5258  474.65    5428  481.04    5498  484.94    5518  486.99
    5548  486.53    5578  489.37    5608  490.29    5638  494.26    5658  495.15
#Mann= 6 ,-1 , 0
  4339.6     .05       0  4774.1      .1       0  4913.3     .16       0
    4995     .07       0    5001     .16       0  5170.2     .05       0
Bank Sta=4995,5001
XS Rating Curve= 0 ,0
Exp/Cntr=0.3,0.1

Type RM Length L Ch R = 1 ,16555   ,630,630,630
BEGIN DESCRIPTION:
UNT0060 IN CHRS 18.0
END DESCRIPTION:
XS GIS Cut Line= 3
       3459442.1     10552341.65      3459792.11     10551691.64
      3459692.11     10551091.67
#Sta/Elev= 30
  4250.6  485.83  4523.2  482.51    4554  480.31  4603.5  479.74  4670.8   476.5
  4716.3  475.12  4723.6  474.12  4783.6  472.02  4818.5   471.5  4841.2  471.97
  4909.3  469.55  4923.3  469.81  4966.1  470.71  4991.4  470.06    4996  462.55
  4998.7  462.05    5002  462.55  5016.7  470.18  5021.8  468.98  5039.5  470.19
    5070  469.28  5089.1  469.83  5100.4  470.82  5272.7  473.79  5333.5  476.15
  5475.5  485.99  5503.4  488.73  5526.2  489.51  5576.9  493.38  5597.1  493.26
#Mann= 5 ,-1 , 0
  4250.6     .05       0  4923.3     .16       0    4996     .07       0
    5002     .16       0  5089.1     .05       0
Bank Sta=4996,5002
XS Rating Curve= 0 ,0
Exp/Cntr=0.3,0.1

Type RM Length L Ch R = 1 ,15925   ,708,708,708
BEGIN DESCRIPTION:
UNT0060 IN CHRS 17.0
END DESCRIPTION:
XS GIS Cut Line= 3
      3459842.12     10552191.62      3460192.11     10551591.64
      3460337.73     10551173.36
#Sta/Elev= 30
  4336.3  482.96  4424.3  480.33    4452  478.44  4563.3  475.19  4745.2  472.37
  4862.6  469.03  4921.3   470.7  4964.3  470.63    4973   470.3    4980  468.82
  4985.8  465.73  4998.5  461.85  5001.3  461.35  5004.5  461.85  5007.7  464.17
  5010.9  464.72  5013.9  465.24    5023   467.8    5028  467.87  5134.4  468.64
  5210.9  466.73  5253.3  467.53  5319.8  473.91  5343.3  477.33  5352.1  477.88
  5377.8  481.77  5383.1  481.21  5408.9  486.33  5436.3  488.38  5473.8  491.43
#Mann= 8 ,-1 , 0
  4336.3     .05       0  4998.5    .035       0  5004.5     .05       0
  5010.9     .16       0  5013.9     .12       0  5319.8     .16       0
  5343.3     .12       0  5436.3     .05       0
Bank Sta=4998.5,5004.5
XS Rating Curve= 0 ,0
Exp/Cntr=0.3,0.1

Type RM Length L Ch R = 1 ,15217   ,122,122,122
BEGIN DESCRIPTION:
UNT0060 IN CHRS 15.0
END DESCRIPTION:
XS GIS Cut Line= 3
      3460472.73       10552100.      3460767.87     10551613.88
      3460945.84     10551127.73
#Sta/Elev= 30
  4575.5  476.72    4603  475.22  4661.2  474.06    4698  472.25  4719.3  472.51
  4734.8  470.67  4740.6  470.92  4756.1  469.34  4777.5  469.25  4814.3  467.06
  4899.1  465.65  4958.3  465.32  4982.9  464.02  4988.7  462.75  4991.7  459.75
  4994.5  459.25  4997.7  459.75  5004.2  459.83  5010.1   462.4  5025.5   465.3
  5031.4  464.76  5135.1  466.29  5221.1  469.08  5258.4  468.99  5306.3  470.94
  5375.1  472.44  5491.9  478.54  5578.1  484.97  5633.8   488.3  5661.9  489.14
#Mann= 5 ,-1 , 0
  4575.5     .05       0  4899.1      .1       0  4958.3     .05       0
  4991.7     .04       0  4997.7     .05       0
Bank Sta=4991.7,4997.7
XS Rating Curve= 0 ,0
Exp/Cntr=0.3,0.1

Type RM Length L Ch R = 1 ,15095   ,1380,1380,1380
BEGIN DESCRIPTION:
UNT0060 IN CHRS 14.5
END DESCRIPTION:
XS GIS Cut Line= 3
      3460566.49     10552179.85      3460861.62     10551693.74
      3461247.58     10551101.13
#Sta/Elev= 30
  4556.9  476.76  4712.5  472.28  4764.8  471.67  4807.5  467.48  4850.1  464.86
  4929.6  465.36  4939.2  465.14  4945.1  463.37  4981.9  464.31  4987.8  463.24
  4994.4  458.61  4997.1  458.11  5000.4  458.61  5018.7  464.55  5040.1   465.8
  5300.8  466.46  5394.4  467.68  5409.5  468.55  5430.6  468.21  5445.7  469.21
  5466.8  468.88    5482  470.46  5532.6  471.95  5535.1  471.92  5611.7  475.16
  5632.8  475.12    5648  476.39  5669.1  476.18  5684.2  477.29  5832.8  479.09
#Mann= 5 ,-1 , 0
  4556.9     .05       0  4994.4     .04       0  5000.4     .05       0
  5532.6      .1       0  5535.1     .05       0
Bank Sta=4994.4,5000.4
XS Rating Curve= 0 ,0
Exp/Cntr=0.3,0.1

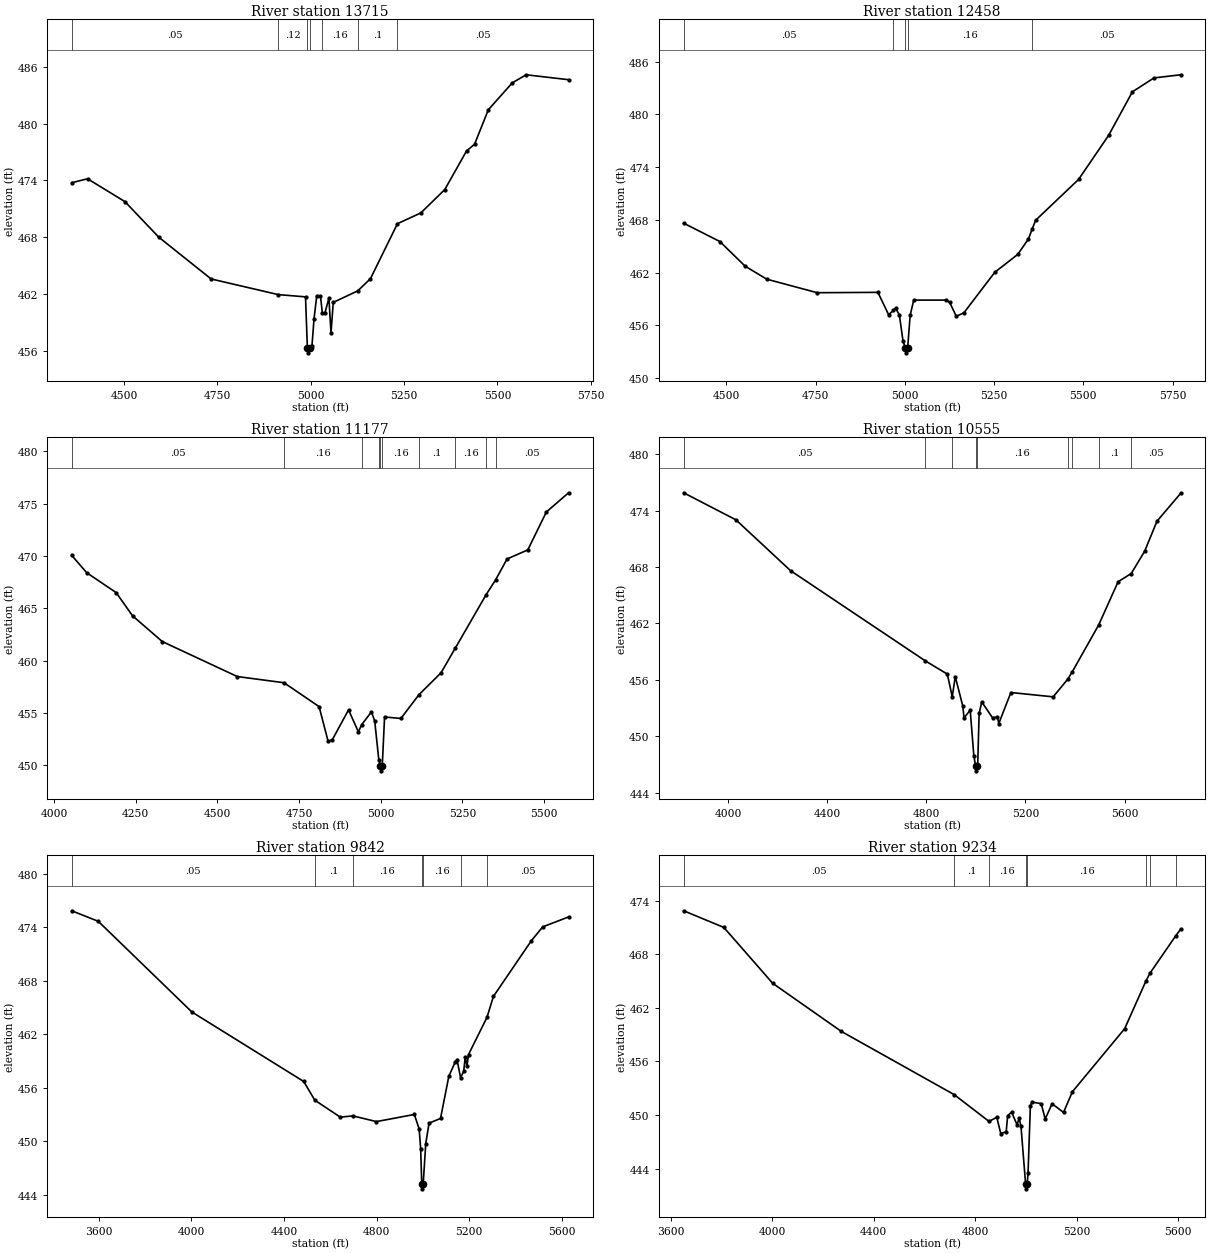
Type RM Length L Ch R = 1 ,13715   ,1257,1257,1257
BEGIN DESCRIPTION:
UNT0060 IN CHRS 14.0
END DESCRIPTION:
XS GIS Cut Line= 4
      3461332.11     10552303.99      3461375.51     10551778.81
      3461531.76     10551448.95      3461757.26     10551071.67
#Sta/Elev= 30
  4359.4  473.75  4401.9  474.17  4502.2  471.75  4592.5  468.01    4733  463.59
  4912.7  461.94  4985.9   461.7  4990.9  456.29  4993.6  455.79  4996.9  456.29
  5003.2  456.53  5008.7  459.37    5016  461.82  5025.9  461.81  5031.1  459.97
  5038.2  460.04  5048.6  461.57  5054.2   457.9  5060.3  461.12  5125.8  462.33
  5159.9  463.62  5232.3  469.43  5294.8  470.56  5359.1  473.03  5417.4  477.11
  5438.8  477.81  5475.8  481.46    5540   484.3    5577  485.15  5690.9  484.63
#Mann= 7 ,-1 , 0
  4359.4     .05       0  4912.7     .12       0  4990.9     .07       0
  4996.9     .12       0  5031.1     .16       0  5125.8      .1       0
  5232.3     .05       0
Bank Sta=4990.9,4996.9
XS Rating Curve= 0 ,0
Exp/Cntr=0.3,0.1

Type RM Length L Ch R = 1 ,12458   ,1281,1281,1281
BEGIN DESCRIPTION:
UNT0060 IN CHRS 12.0
END DESCRIPTION:
XS GIS Cut Line= 3
      3461731.41      10552251.9      3462113.36     10552199.82
      3462017.88     10551197.24
#Sta/Elev= 30
    4380  467.63  4481.6  465.54  4552.3  462.74  4612.8  461.26  4754.1  459.72
  4924.4  459.76  4954.5  457.21    4968  457.72  4974.6  457.93  4984.6  457.18
  4994.7  454.24  5001.7  453.38  5004.5  452.88  5007.7  453.38  5014.8  457.15
  5024.8  458.88  5115.2  458.88  5125.3  458.64  5144.1  457.03  5165.5  457.44
  5252.1  462.05  5316.1  464.07  5346.3  465.83  5357.1     467  5366.4  467.96
  5486.9  472.61    5571  477.62  5637.6  482.57  5697.9  484.15  5772.6  484.51
#Mann= 5 ,-1 , 0
    4380     .05       0    4968     .16       0  5001.7     .07       0
  5007.7     .16       0  5357.1     .05       0
Bank Sta=5001.7,5007.7
XS Rating Curve= 0 ,0
Exp/Cntr=0.3,0.1

Type RM Length L Ch R = 1 ,11177   ,622,622,622
BEGIN DESCRIPTION:
UNT0060 IN CHRS 11.0
END DESCRIPTION:
XS GIS Cut Line= 4
      3461666.26     10552290.96      3462269.61     10552325.68
      3462794.78     10552299.64      3463085.57     10552039.24
#Sta/Elev= 30
  4054.3  470.06  4100.2   468.4  4190.4   466.5  4240.4  464.29  4331.4  461.83
    4561  458.49  4703.8   457.9  4811.3  455.62  4838.8  452.32  4851.4  452.44
  4901.4  455.31  4931.5  453.21  4941.7   453.9  4971.5  455.12  4981.5  454.24
  4993.9  450.57  4998.6  449.99  5001.3  449.49  5004.6  449.99  5011.6  454.63
  5061.6  454.49  5116.6  456.75  5184.5  458.85    5228   461.2  5322.5  466.31
  5351.4  467.72  5386.4  469.71  5449.9  470.58  5506.7   474.2  5574.8  476.03
#Mann= 10 ,-1 , 0
  4054.3     .05       0  4703.8     .16       0  4941.7      .1       0
  4993.9     .16       0  4998.6     .07       0  5004.6     .16       0
  5116.6      .1       0    5228     .16       0  5322.5      .1       0
  5351.4     .05       0
Bank Sta=4998.6,5004.6
XS Rating Curve= 0 ,0
Exp/Cntr=0.3,0.1

Type RM Length L Ch R = 1 ,10555   ,713,713,713
BEGIN DESCRIPTION:
UNT0060 IN CHRS 10.0
END DESCRIPTION:
XS GIS Cut Line= 4
      3461770.49     10553497.55      3462538.71     10552868.22
      3462660.23     10552547.04      3463180.68     10552126.34
#Sta/Elev= 30
  3820.3  475.92  4031.3  473.04  4251.6  467.63  4795.7  458.02  4884.6  456.61
  4904.4  454.19  4916.6  456.34  4946.8  453.23  4952.1  451.95  4976.9  452.77
  4991.5  447.94  4998.7  446.81  5001.5  446.31  5004.7  446.81  5007.1  446.83
  5012.9  452.42  5023.6  453.65  5067.4  451.94  5086.9  452.07  5092.2  451.35
  5141.2  454.65  5311.8  454.19  5370.3  456.06  5388.3  456.83  5495.4  461.84
    5574  466.45  5626.8  467.32  5681.2   469.7  5730.7  472.89    5826  475.85
#Mann= 9 ,-1 , 0
  3820.3     .05       0  4795.7      .1       0  4904.4     .16       0
  4998.7     .07       0  5004.7     .16       0  5370.3      .1       0
  5388.3     .16       0  5495.4      .1       0  5626.8     .05       0
Bank Sta=4998.7,5004.7
XS Rating Curve= 0 ,0
Exp/Cntr=0.3,0.1

Type RM Length L Ch R = 1 ,9842    ,608,608,608
BEGIN DESCRIPTION:
UNT0060 IN CHRS 9.0
END DESCRIPTION:
XS GIS Cut Line= 4
      3461844.26     10553571.34      3462729.68     10552994.09
      3463159.37      10552629.5      3463484.87      10552217.2
#Sta/Elev= 30
  3483.2  475.82  3597.9  474.64  4002.2  464.47    4485  456.68    4533  454.58
  4643.1  452.68  4697.5  452.82    4799  452.18  4962.7  452.98  4983.6  451.36
  4990.1  449.12  4994.9  445.14  4997.6  444.64  5000.9  445.14  5012.1  449.72
  5026.4  452.01  5075.8  452.53  5111.8  457.27  5139.2  458.85    5147  459.14
  5162.3  457.12  5175.9   457.8  5182.3  459.37  5190.2  458.43  5196.7   459.7
  5276.7  463.88  5304.1  466.21  5467.7  472.45  5517.3  474.02    5629  475.13
#Mann= 7 ,-1 , 0
  3483.2     .05       0    4533      .1       0  4697.5     .16       0
  4994.9     .07       0  5000.9     .16       0  5162.3      .1       0
  5276.7     .05       0
Bank Sta=4994.9,5000.9
XS Rating Curve= 0 ,0
Exp/Cntr=0.3,0.1

Type RM Length L Ch R = 1 ,9234    ,1367,1367,1367
BEGIN DESCRIPTION:
UNT0060 IN CHRS 7.0
END DESCRIPTION:
XS GIS Cut Line= 3
      3462100.32     10553762.33      3462846.87     10553185.06
       3463718.2     10552664.86
#Sta/Elev= 30
  3651.5  472.85  3809.8  470.99  4002.7  464.73  4273.2  459.35  4717.8  452.28
  4854.9  449.29  4885.7  449.74  4901.3  447.93  4922.7  448.13  4928.5  449.93
  4944.1  450.32  4965.5  448.91    4974  449.66    4981  448.72  4999.4  442.24
  5002.2  441.74  5005.4  442.24  5008.9  443.52    5018  451.01  5023.8  451.45
  5060.8  451.27  5076.4  449.55  5103.6  451.26  5148.7  450.29  5183.6   452.6
  5389.7  459.66  5473.8  465.01  5489.5  465.87  5590.2  470.02    5610  470.78
#Mann= 8 ,-1 , 0
  3651.5     .05       0  4717.8      .1       0  4854.9     .16       0
  4999.4     .07       0  5005.4     .16       0  5473.8     .12       0
  5489.5     .05       0  5590.2      .1       0
Bank Sta=4999.4,5005.4
XS Rating Curve= 0 ,0
Exp/Cntr=0.3,0.1

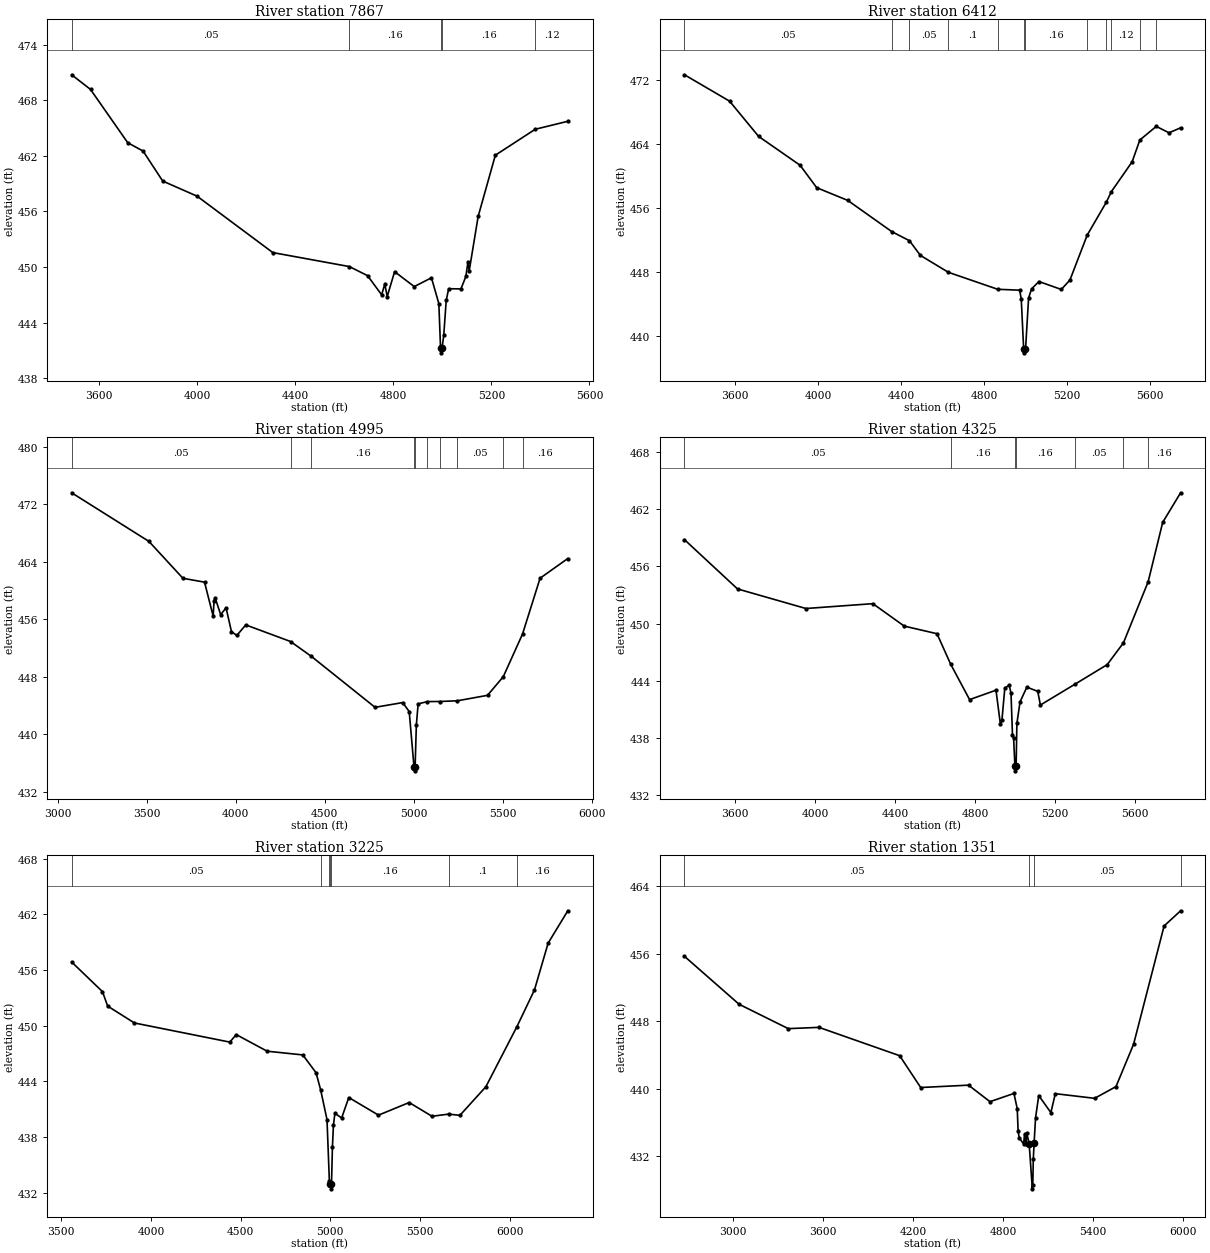
Type RM Length L Ch R = 1 ,7867    ,1455,1455,1455
BEGIN DESCRIPTION:
UNT0060 IN CHRS 6.0
END DESCRIPTION:
XS GIS Cut Line= 3
      3462360.72     10553810.07      3463332.98      10553480.2
      3464326.88     10553423.77
#Sta/Elev= 30
  3489.4  470.74  3566.2  469.16  3717.9  463.41  3780.7   462.5  3860.5  459.27
  4000.5  457.64  4309.3  451.55  4621.4  450.04  4695.5  449.06  4752.9  446.99
  4765.6  448.15  4775.6  446.81  4805.7  449.49  4885.8  447.88  4955.9  448.83
    4986  446.04    4993  441.23  4995.7  440.73    4999  441.23    5006  442.62
    5016  446.38    5026  447.65  5076.1  447.63  5096.2  448.98  5104.6  450.52
  5109.7  449.57  5146.2  455.45  5216.3  462.06  5378.9  464.86  5511.6  465.72
#Mann= 5 ,-1 , 0
  3489.4     .05       0  4621.4     .16       0    4993     .07       0
    4999     .16       0  5378.9     .12       0
Bank Sta=4993,4999
XS Rating Curve= 0 ,0
Exp/Cntr=0.3,0.1

Type RM Length L Ch R = 1 ,6412    ,1417,1417,1417
BEGIN DESCRIPTION:
UNT0060 IN CHRS 5.0
END DESCRIPTION:
XS GIS Cut Line= 3
      3462334.74      10554126.9      3463714.92     10554135.58
      3464517.45     10553519.58
#Sta/Elev= 30
  3355.2  472.64  3572.6  469.35  3712.6  464.95  3912.6  461.35  3992.6  458.55
  4142.6  456.96  4354.4  453.07    4440  451.93  4492.6   450.1  4627.4  447.99
  4865.5  445.87  4971.4  445.76  4978.9  444.62  4990.4  438.44  4993.1  437.94
  4996.4  438.44  4999.7  438.46  5014.2  444.79  5028.7  445.92    5064  446.84
  5171.9  445.85  5213.6  447.03  5296.9  452.64  5389.4  456.76  5413.4  458.06
  5513.4  461.78  5550.6   464.5  5629.7   466.2  5691.2   465.4  5747.1  466.02
#Mann= 12 ,-1 , 0
  3355.2     .05       0  4354.4      .1       0    4440     .05       0
  4627.4      .1       0  4865.5     .16       0  4990.4     .07       0
  4996.4     .16       0  5296.9     .12       0  5389.4     .16       0
  5413.4     .12       0  5550.6     .16       0  5629.7     .12       0
Bank Sta=4990.4,4996.4
XS Rating Curve= 0 ,0
Exp/Cntr=0.3,0.1

Type RM Length L Ch R = 1 ,4995    ,670,670,670
BEGIN DESCRIPTION:
UNT0060 IN CHRS 4.0
END DESCRIPTION:
XS GIS Cut Line= 6
      3462260.94       10554192.      3463714.92     10554365.61
      3464079.51     10554309.19      3464374.64     10554278.81
       3464574.3     10554226.72      3464582.97     10553775.97
#Sta/Elev= 30
  3079.5  473.59  3513.7  466.82  3704.5  461.69  3825.9  461.15  3874.5  456.41
  3879.5  458.59  3886.4  458.91  3916.6  456.62  3946.8  457.58    3977  454.28
  4007.2  453.73  4057.6   455.2  4309.1  452.89  4426.7  450.81  4783.8  443.73
    4939  444.39  4975.7  443.14  5002.8  435.39  5005.6  434.89  5008.8  435.39
  5015.9  441.31  5025.9  444.21  5078.2  444.53  5146.8  444.54  5246.2  444.64
  5415.8   445.4  5504.3     448  5612.3  453.93  5710.9   461.7  5866.6  464.44
#Mann= 10 ,-1 , 0
  3079.5     .05       0  4309.1      .1       0  4426.7     .16       0
  5002.8     .07       0  5008.8     .16       0  5078.2     .05       0
  5146.8     .16       0  5246.2     .05       0  5504.3     .12       0
  5612.3     .16       0
Bank Sta=5002.8,5008.8
XS Rating Curve= 0 ,0
Exp/Cntr=0.3,0.1

Type RM Length L Ch R = 1 ,4325    ,1100,1100,1100
BEGIN DESCRIPTION:
UNT0060 IN CHRS 3.0
END DESCRIPTION:
XS GIS Cut Line= 4
      3463545.67     10555997.54       3464326.9     10554986.27
       3464617.7     10554435.06      3464652.32     10553855.09
#Sta/Elev= 30
  3345.9  458.82  3611.2  453.64  3953.5  451.58  4288.4  452.09  4445.3  449.73
  4609.2  448.93  4677.5  445.73  4772.3     442  4904.4  442.99  4926.4  439.42
  4934.3  439.88  4948.5  443.22  4970.5  443.51  4979.5  442.67  4986.9  438.25
  4992.5  437.96  4999.1  435.01  5001.9  434.51  5005.1  435.01  5008.9  439.49
  5024.7  441.76  5058.7  443.31  5113.3  442.87  5126.5  441.43  5297.8   443.6
  5460.8  445.68    5542  447.97  5665.6  454.39  5738.4  460.64    5828  463.75
#Mann= 7 ,-1 , 0
  3345.9     .05       0  4677.5     .16       0  4999.1     .07       0
  5005.1     .16       0  5297.8     .05       0    5542     .12       0
  5665.6     .16       0
Bank Sta=4999.1,5005.1
XS Rating Curve= 0 ,0
Exp/Cntr=0.3,0.1

Type RM Length L Ch R = 1 ,3225    ,1874,1874,1874
BEGIN DESCRIPTION:
UNT0060 IN CHRS 2.0
END DESCRIPTION:
XS GIS Cut Line= 4
      3463758.31     10556036.63      3464739.23     10555342.18
      3465086.45     10554599.99      3464899.82     10553879.52
#Sta/Elev= 30
    3558  456.86  3729.6  453.67  3758.7  452.11    3908  450.29  4439.7  448.23
  4475.3  449.04  4647.6  447.25  4846.2  446.85  4920.3  444.93  4945.9  443.08
  4981.3  439.88  4994.5  433.25  5000.3  432.92  5003.1  432.42  5006.3  432.92
  5011.6  436.94  5017.2   439.3  5025.4  440.57  5062.8  440.05  5102.7  442.26
  5268.3  440.36  5439.3  441.72  5566.4  440.24  5659.2  440.47  5722.2  440.34
  5866.8  443.42    6040   449.9  6137.7  453.85  6213.8  458.89  6323.5  462.38
#Mann= 7 ,-1 , 0
    3558     .05       0  4945.9     .12       0  4994.5     .16       0
  5000.3     .07       0  5006.3     .16       0  5659.2      .1       0
    6040     .16       0
Bank Sta=5000.3,5006.3
XS Rating Curve= 0 ,0
Exp/Cntr=0.3,0.1

Type RM Length L Ch R = 1 ,1351    ,0,0,0
BEGIN DESCRIPTION:
UNT0060 IN CHRS 1.0
END DESCRIPTION:
XS GIS Cut Line= 5
      3463983.99      10556119.1      3465438.01     10555598.25
      3465637.66     10555094.78      3465372.91     10554660.75
      3465129.87     10553992.39
#Sta/Elev= 30
  2678.1  455.68  3041.9     450  3369.6  447.11  3574.3  447.26  4112.1   443.9
  4251.9  440.13  4570.7  440.41  4713.8  438.45  4873.3  439.43  4895.3  437.62
  4901.1  434.98  4908.4  434.16  4937.9  433.43  4943.8  434.57  4953.4  433.39
  4959.2  434.68  4974.7  433.49  4995.8  428.12    4999  428.62  5002.2   431.6
 5007.64  433.54  5017.3  436.54  5038.6  439.18  5119.3  437.16    5149   439.4
    5411  438.85  5553.3  440.24  5670.3  445.25  5873.8  459.28  5983.8  461.08
#Mann= 4 ,-1 , 0
  2678.1     .05       0  4974.7    .035       0 5007.64     .05       0
  5983.8     .16       0
Bank Sta=4974.7,5007.64
XS Rating Curve= 0 ,0
Exp/Cntr=0.3,0.1

Chan Stop Cuts=-1
Use User Specified Reach Order=0
Composite Channel Slope=5