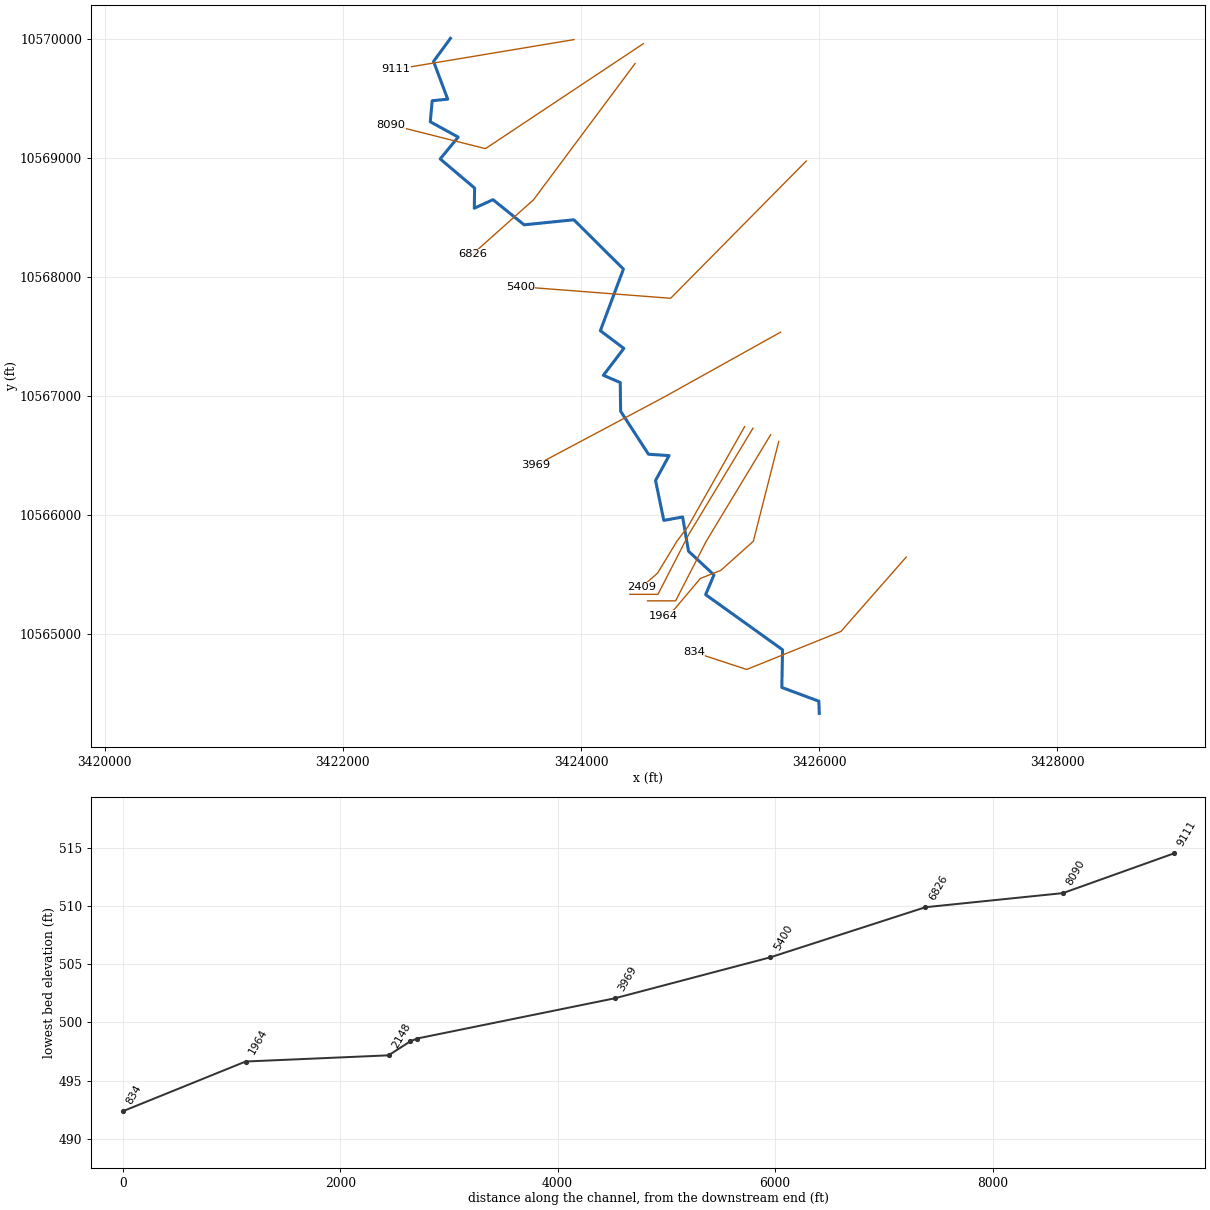
--- UNT00603 IN CHRS.prj (project) ---

Proj Title=UNT00603 IN CHRS Base Level Engineering
Current Plan=p01
Default Exp/Contr=0.3,0.1
English Units
Geom File=g01
Flow File=f01
Plan File=p01
Y Axis Title=Elevation
X Axis Title(PF)=Main Channel Distance
X Axis Title(XS)=Station
BEGIN DESCRIPTION:
UNT00603 IN CHRS
END DESCRIPTION:
DSS Export Rating Curves= 0
DSS Export Rating Curve Sorted= 0
DSS Export Volume Flow Curves= 0
DXF OffsetX= 0
DXF OffsetY= 0
DXF ScaleX= 1
DXF ScaleY= 10

--- UNT00603 IN CHRS.p01 (plan) ---

Plan Title=Multiple Run
Short Identifier=Multiple
Geom File=g01
Flow File=f01
Subcritical Flow
K Sum by GR= 0
Std Step Tol= 0.01
Critical Tol= 0.01
Num of Std Step Trials= 20
Max Error Tol= 0.3
Flow Tol Ratio= 0.001
Split Flow NTrial= 30
Split Flow Tol= 0.02
Split Flow Ratio= 0.02
Log Output Level= 0
Friction Slope Method= 1
Unsteady Friction Slope Method= 2
Unsteady Bridges Friction Slope Method= 1
Parabolic Critical Depth
Global Vel Dist=  1 , 1 , 1
Global Log Level= 0
CheckData=True
Encroach Param= -1, 0, 0, 0
BEGIN DESCRIPTION:
Multiple Run
END DESCRIPTION:

--- UNT00603 IN CHRS.f01 (steady flow) ---

Flow Title=Multiple
Number of Profiles=7
Profile Names=10-year,25-year,50-year,1pct_min,100-year,1pct_plu,500-year
River Rch & RM= UNT00603 IN CHRS,Reach-1,9111
     308     378     427     352     476     643     588
River Rch & RM= UNT00603 IN CHRS,Reach-1,8090
     395     490     557     461     624     844     781
Boundary for River Rch & Prof#=UNT00603 IN CHRS,Reach-1,1
Up Type=0
Dn Type=3
Dn Slope=0.005
Boundary for River Rch & Prof#=UNT00603 IN CHRS,Reach-1,2
Up Type=0
Dn Type=3
Dn Slope=0.005
Boundary for River Rch & Prof#=UNT00603 IN CHRS,Reach-1,3
Up Type=0
Dn Type=3
Dn Slope=0.005
Boundary for River Rch & Prof#=UNT00603 IN CHRS,Reach-1,4
Up Type=0
Dn Type=3
Dn Slope=0.005
Boundary for River Rch & Prof#=UNT00603 IN CHRS,Reach-1,5
Up Type=0
Dn Type=3
Dn Slope=0.005
Boundary for River Rch & Prof#=UNT00603 IN CHRS,Reach-1,6
Up Type=0
Dn Type=3
Dn Slope=0.005
Boundary for River Rch & Prof#=UNT00603 IN CHRS,Reach-1,7
Up Type=0
Dn Type=3
Dn Slope=0.005

--- UNT00603 IN CHRS.g01 (geometry) ---

Geom Title=Existing Conditions
Program Version=4.10

River Reach=UNT00603 IN CHRS,Reach-1
Reach XY= 30
      3422903.87     10570002.16      3422761.73     10569808.07
      3422880.93     10569491.13      3422750.46     10569478.14
      3422734.26     10569301.37      3422968.59     10569172.44
      3422817.65     10568989.31      3423106.78     10568744.42
      3423104.13     10568575.06      3423261.16     10568646.97
      3423522.78     10568435.75      3423940.63     10568477.87
      3424356.85     10568063.81       3424162.9     10567546.11
      3424360.51     10567397.39      3424188.42     10567171.61
      3424330.09     10567111.09      3424333.43     10566869.51
      3424567.46      10566508.4      3424740.29     10566496.94
      3424626.58     10566287.74      3424696.02     10565952.67
      3424854.01     10565981.31      3424903.49     10565693.99
      3425117.36     10565494.88      3425047.33     10565329.21
      3425693.45     10564866.17      3425687.53     10564549.26
      3425998.49     10564433.77      3426002.11     10564331.64

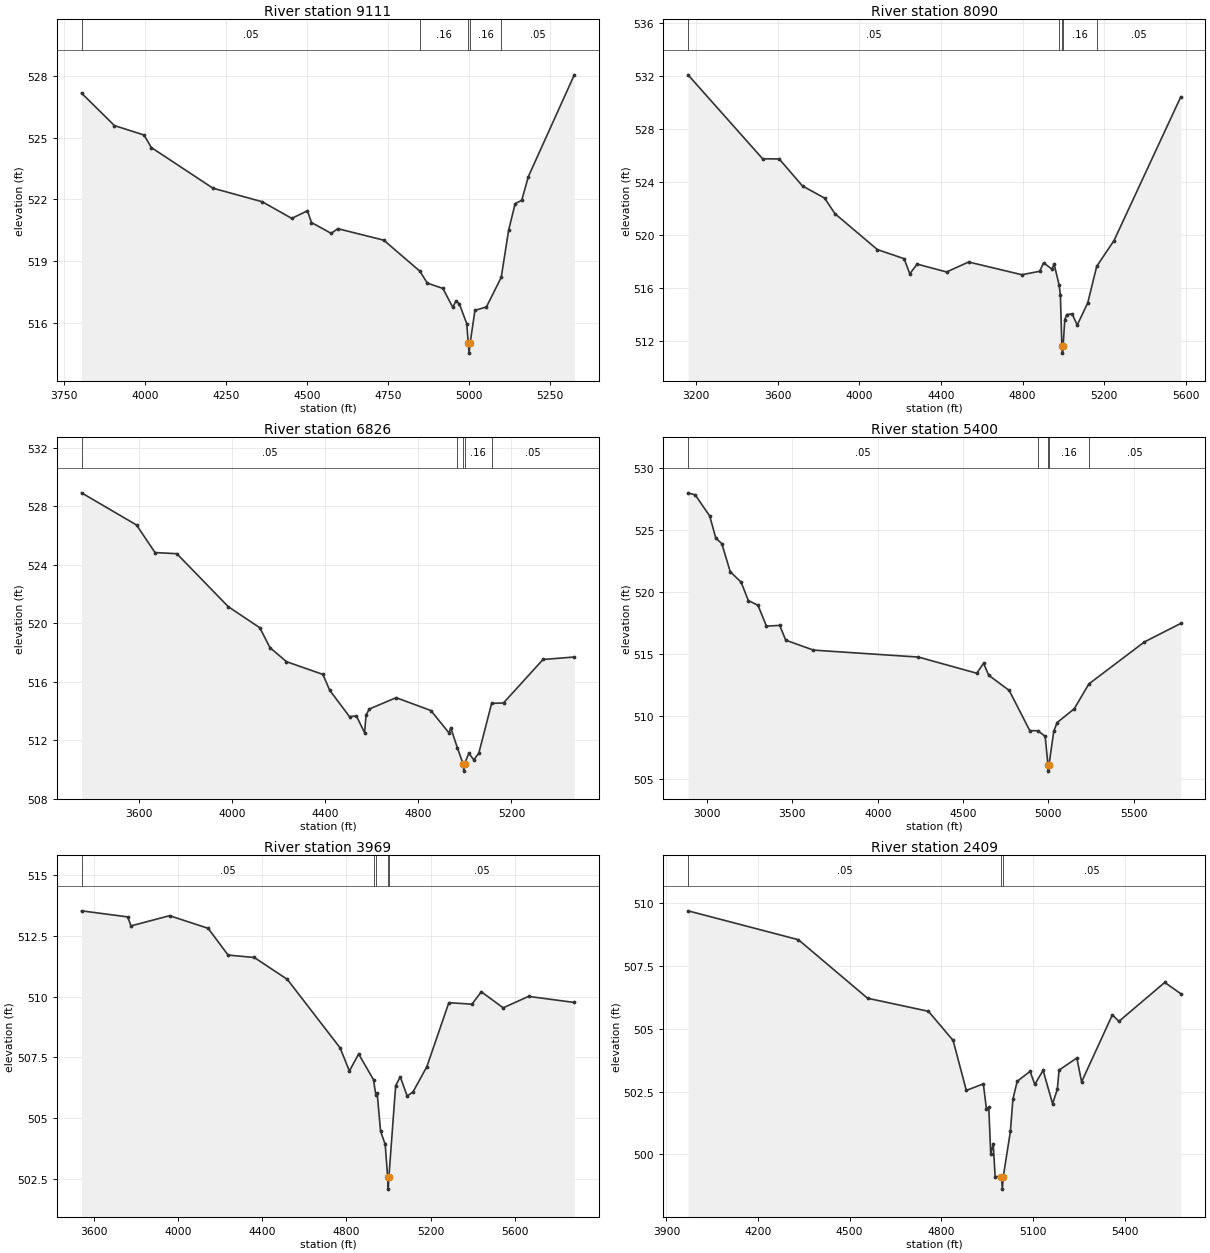
Type RM Length L Ch R = 1 ,9111    ,1021,1021,1021
BEGIN DESCRIPTION:
UNT00603 IN CHRS 7.0
END DESCRIPTION:
XS GIS Cut Line= 3
      3423942.09     10569991.64      3422742.11     10569791.64
      3422442.08     10569741.64
#Sta/Elev= 30
  3803.6  527.18    3905   525.6  3996.2  525.14    4019  524.53  4209.1  522.55
  4361.2  521.89  4452.4  521.08  4500.6  521.45  4513.2  520.88  4574.1  520.35
  4594.3  520.58  4736.3  520.02  4847.7  518.51  4870.6  517.93  4918.8  517.67
  4949.2  516.75  4959.3  517.07  4969.4  516.92  4992.3  515.96  4996.9  515.02
  4999.6  514.52  5002.9  515.02  5017.6   516.6  5053.1  516.77  5098.8  518.21
  5121.5   520.5  5141.8   521.8  5162.1  521.96  5182.3  523.11  5324.3  528.07
#Mann= 5 ,-1 , 0
  3803.6     .05       0  4847.7     .16       0  4996.9     .07       0
  5002.9     .16       0  5098.8     .05       0
Bank Sta=4996.9,5002.9
XS Rating Curve= 0 ,0
Exp/Cntr=0.3,0.1

Type RM Length L Ch R = 1 ,8090    ,1264,1264,1264
BEGIN DESCRIPTION:
UNT00603 IN CHRS 6.0
END DESCRIPTION:
XS GIS Cut Line= 3
      3424524.39     10569957.48      3423197.97     10569075.51
      3422399.84     10569276.78
#Sta/Elev= 30
  3159.8  532.09  3525.7  525.76  3606.8  525.75  3721.1  523.71  3829.3   522.8
  3880.4  521.62  4087.8  518.92  4219.3  518.23  4247.1  517.09  4283.2  517.82
  4427.5  517.23  4535.7  517.98  4796.5  517.02  4883.8  517.28  4903.1  517.92
  4944.4  517.44  4954.7  517.83  4979.3  516.24  4985.6  515.48  4992.9  511.61
  4995.7  511.11  4998.9  511.61    5007  513.64  5016.6  514.02    5043  514.07
  5068.1  513.23  5119.7   514.9  5163.7  517.66  5248.3  519.59  5575.8  530.43
#Mann= 5 ,-1 , 0
  3159.8     .05       0  4979.3     .16       0  4992.9     .07       0
  4998.9     .16       0  5163.7     .05       0
Bank Sta=4992.9,4998.9
XS Rating Curve= 0 ,0
Exp/Cntr=0.3,0.1

Type RM Length L Ch R = 1 ,6826    ,1426,1426,1426
BEGIN DESCRIPTION:
UNT00603 IN CHRS 5.0
END DESCRIPTION:
XS GIS Cut Line= 3
      3424454.93     10569790.81      3423600.75     10568644.96
      3423086.99     10568186.74
#Sta/Elev= 30
  3352.5  528.92  3588.9  526.72  3668.1  524.84    3762  524.76    3983  521.14
  4118.5   519.7  4162.2  518.34  4233.2  517.38  4389.6  516.51  4418.8  515.43
  4504.3  513.62  4533.5  513.68  4568.9  512.52  4575.2  513.75  4589.8  514.15
  4704.4  514.92  4853.9  514.04  4931.7  512.51  4939.2  512.86  4967.2  511.51
  4992.2   510.4    4995   509.9  4998.2   510.4    5017  511.12  5037.9  510.67
  5059.6  511.12  5114.8  514.53  5165.8  514.56  5335.5  517.53  5470.1   517.7
#Mann= 5 ,-1 , 0
  3352.5     .05       0  4967.2     .16       0  4992.2     .07       0
  4998.2     .16       0  5114.8     .05       0
Bank Sta=4992.2,4998.2
XS Rating Curve= 0 ,0
Exp/Cntr=0.3,0.1

Type RM Length L Ch R = 1 ,5400    ,1431,1431,1431
BEGIN DESCRIPTION:
UNT00603 IN CHRS 4.0
END DESCRIPTION:
XS GIS Cut Line= 3
      3425892.43     10568971.36      3424753.53     10567818.57
      3423489.67     10567915.79
#Sta/Elev= 30
  2888.2     528  2930.6  527.83  3015.5  526.13  3050.9  524.36  3086.2  523.91
  3135.7  521.65  3199.3  520.81  3241.8  519.33  3298.3  518.95  3347.9  517.27
  3425.6  517.33    3461  516.14  3623.6  515.34  4238.8  514.78  4580.3  513.48
  4620.5  514.28  4650.5  513.32  4770.9  512.09  4891.3  508.86  4939.2  508.85
  4981.5   508.4  4997.8   506.1  5000.6   505.6  5003.8   506.1  5031.7   508.8
  5051.7  509.51    5152  510.62  5237.7  512.62  5563.2     516  5776.3  517.49
#Mann= 5 ,-1 , 0
  2888.2     .05       0  4939.2     .16       0  4997.8     .07       0
  5003.8     .16       0  5237.7     .05       0
Bank Sta=4997.8,5003.8
XS Rating Curve= 0 ,0
Exp/Cntr=0.3,0.1

Type RM Length L Ch R = 1 ,3969    ,1821,1821,1821
BEGIN DESCRIPTION:
UNT00603 IN CHRS 3.0
END DESCRIPTION:
XS GIS Cut Line= 3
      3425677.15     10567533.86      3424704.92     10566992.18
      3423622.35      10566416.2
#Sta/Elev= 30
  3543.2  513.53  3762.1  513.28  3777.9  512.91  3961.1  513.33  4144.2  512.81
  4238.8  511.71  4363.4  511.61    4520  510.71  4770.7  507.89  4814.6  506.94
  4858.6  507.64  4929.2  506.58  4940.3  505.94  4946.4  506.04  4962.8  504.46
  4984.7  503.92  4996.2  502.58  4998.9  502.08  5002.2  502.58  5034.3  506.34
  5056.3   506.7  5088.9  505.91  5116.6  506.08  5182.5  507.12  5286.7  509.75
  5396.5  509.69  5440.9   510.2  5544.7  509.54  5665.2  510.01  5882.4  509.76
#Mann= 5 ,-1 , 0
  3543.2     .05       0  4929.2      .1       0  4940.3     .05       0
  4996.2     .03       0  5002.2     .05       0
Bank Sta=4996.2,5002.2
XS Rating Curve= 0 ,0
Exp/Cntr=0.3,0.1

Type RM Length L Ch R = 1 ,2409    ,61,61,61
BEGIN DESCRIPTION:
UNT00603 IN CHRS 2.3
END DESCRIPTION:
XS GIS Cut Line= 5
      3425375.25     10566740.95      3424898.67     10565899.78
      3424807.53     10565779.98      3424643.47     10565509.15
      3424508.02     10565391.93
#Sta/Elev= 30
  3970.9   509.7  4332.2  508.55  4558.7  506.22  4757.9   505.7  4838.7  504.54
  4881.9  502.55  4937.7  502.81  4947.9   501.8  4955.5  501.88  4961.8  500.02
    4970  500.43  4976.3  499.12    4997  499.12  4999.8  498.62    5003  499.12
  5026.2  500.92  5034.5   502.2  5048.4  502.91  5090.6  503.31  5106.1  502.79
  5133.3  503.35  5164.3  502.02  5179.8  502.59  5185.6  503.36  5243.8  503.84
  5259.3  502.89  5360.1  505.56  5381.5   505.3  5531.6  506.85    5584   506.4
#Mann= 3 ,-1 , 0
  3970.9     .05       0    4997     .03       0    5003     .05       0
Bank Sta=4997,5003
XS Rating Curve= 0 ,0
Exp/Cntr=0.3,0.1

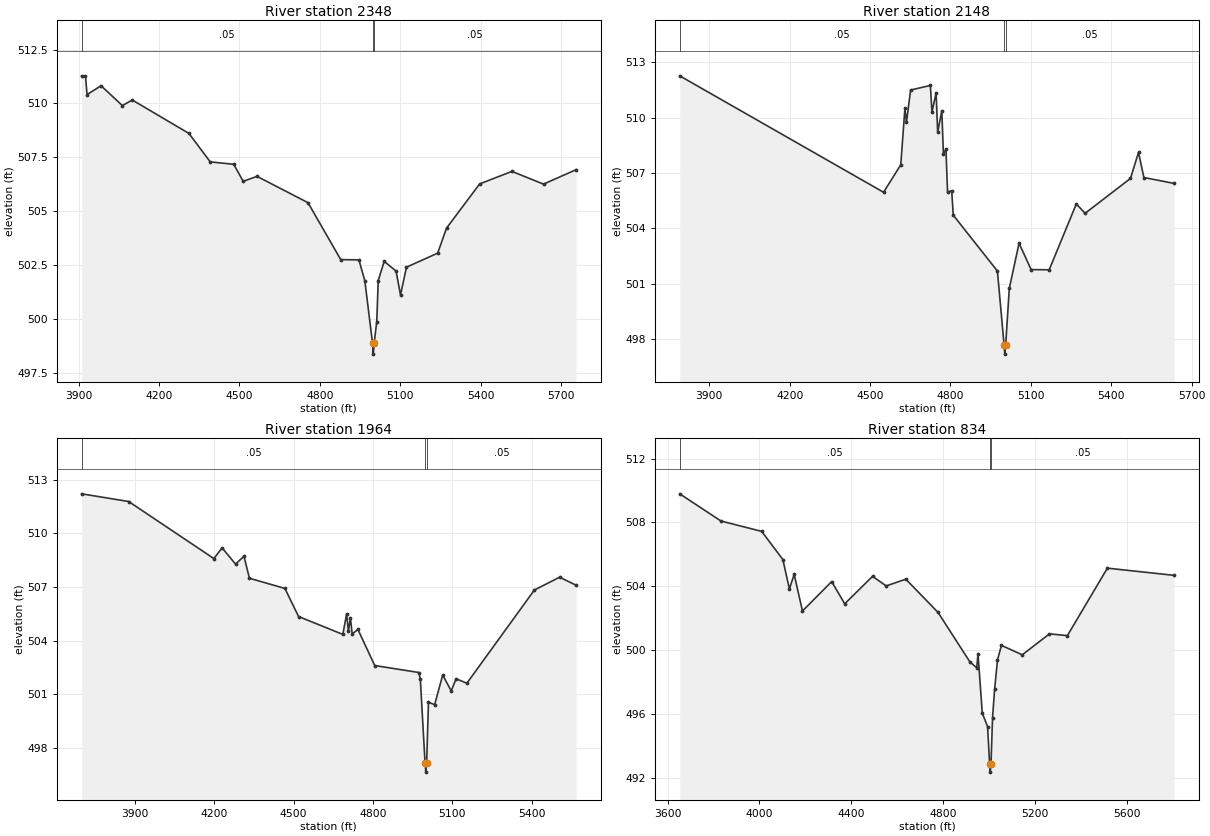
Type RM Length L Ch R = 1 ,2348    ,200,200,200
BEGIN DESCRIPTION:
UNT00603 IN CHRS 2.2
END DESCRIPTION:
XS GIS Cut Line= 4
      3425445.39     10566727.46       3424903.7     10565831.59
      3424646.76     10565331.59      3424410.62     10565331.59
#Sta/Elev= 30
  3911.4  511.28  3925.7  511.28  3931.6  510.41  3983.9  510.82  4063.5   509.9
  4100.3  510.16  4311.8  508.61  4391.4  507.29  4479.1  507.18  4514.2  506.39
    4566  506.62  4756.1   505.4  4878.4  502.76  4946.2  502.75  4968.3  501.78
    4997  498.88  4999.8  498.38    5003  498.88  5012.7  499.89  5018.3  501.79
  5040.5  502.68  5084.8  502.23  5101.4  501.12  5123.6  502.41  5240.1  503.06
  5273.1  504.22  5396.7  506.27  5517.2  506.85  5635.1  506.26  5756.6  506.93
#Mann= 3 ,-1 , 0
  3911.4     .05       0    4997    .035       0    5003     .05       0
Bank Sta=4997,5003
XS Rating Curve= 0 ,0
Exp/Cntr=0.3,0.1

Type RM Length L Ch R = 1 ,2148    ,1314,1314,1314
BEGIN DESCRIPTION:
UNT00603 IN CHRS 2.0
END DESCRIPTION:
XS GIS Cut Line= 4
      3425593.78     10566672.69      3425052.14      10565776.9
      3424795.19      10565276.9      3424559.06      10565276.9
#Sta/Elev= 30
  3789.6  512.26  4550.4  505.95  4614.5  507.44    4630   510.5  4635.8  509.75
  4651.3  511.49    4725  511.74  4730.9   510.3  4746.4  511.34  4752.2  509.21
  4767.7  510.36  4773.6  508.05  4783.2  508.27  4789.1  505.96  4804.6  506.03
  4810.4  504.71  4975.2  501.68    5000  497.68  5002.7  497.18    5006  497.68
  5019.5  500.74  5055.9  503.19  5100.9  501.76  5168.4  501.75  5269.6  505.32
  5302.3  504.81  5471.7   506.7  5501.7  508.11  5521.7  506.75  5634.7  506.43
#Mann= 3 ,-1 , 0
  3789.6     .05       0    5000    .035       0    5006     .05       0
Bank Sta=5000,5006
XS Rating Curve= 0 ,0
Exp/Cntr=0.3,0.1

Type RM Length L Ch R = 1 ,1964    ,1130,1130,1130
BEGIN DESCRIPTION:
UNT00603 IN CHRS 2.1
END DESCRIPTION:
XS GIS Cut Line= 6
       3425661.7     10566615.94      3425448.15     10565777.38
      3425174.72     10565532.59      3425002.84     10565464.88
      3424781.49     10565201.86      3424687.71     10565149.76
#Sta/Elev= 30
  3699.5  512.21  3877.2  511.78  4199.2  508.59  4230.2  509.19    4281  508.28
  4312.8  508.72  4333.4  507.49  4467.5  506.92  4519.1  505.35  4686.4  504.35
  4700.7   505.5  4707.4  504.53  4714.9  505.29  4721.6  504.37  4743.3  504.63
  4806.8  502.61  4973.8  502.22  4979.2  501.84    4997  497.15  4999.8  496.65
    5003  497.15  5009.9  500.56  5033.3  500.42  5063.6  502.08  5095.8  501.19
  5114.3  501.87    5155  501.62  5409.9  506.83  5505.4  507.55  5567.6   507.1
#Mann= 3 ,-1 , 0
  3699.5     .05       0    4997     .03       0    5003     .05       0
Bank Sta=4997,5003
XS Rating Curve= 0 ,0
Exp/Cntr=0.3,0.1

Type RM Length L Ch R = 1 ,834     ,0,0,0
BEGIN DESCRIPTION:
UNT00603 IN CHRS 1.0
END DESCRIPTION:
XS GIS Cut Line= 4
      3426732.68     10565644.94      3426184.08     10565019.96
      3425392.42     10564700.51      3424948.02     10564846.33
#Sta/Elev= 30
  3652.6  509.79  3832.2  508.09  4009.6  507.44  4101.7  505.68  4130.2  503.84
    4151  504.75  4187.1  502.46  4314.3   504.3  4371.2  502.91  4492.4  504.63
  4551.5  504.03  4637.3  504.45  4777.5  502.37  4916.5  499.27    4946  498.91
  4951.4  499.79  4970.1  496.07  4993.2  495.22  5002.1  492.88  5004.8  492.38
  5008.1  492.88  5014.7  495.77  5023.8  497.55  5036.3  499.39  5053.4  500.31
  5144.1  499.72  5262.7  501.03  5340.7  500.92  5514.9  505.14  5805.6  504.69
#Mann= 3 ,-1 , 0
  3652.6     .05       0  5002.1     .03       0  5008.1     .05       0
Bank Sta=5002.1,5008.1
XS Rating Curve= 0 ,0
Exp/Cntr=0.3,0.1

Chan Stop Cuts=-1
Use User Specified Reach Order=0
Composite Channel Slope=5