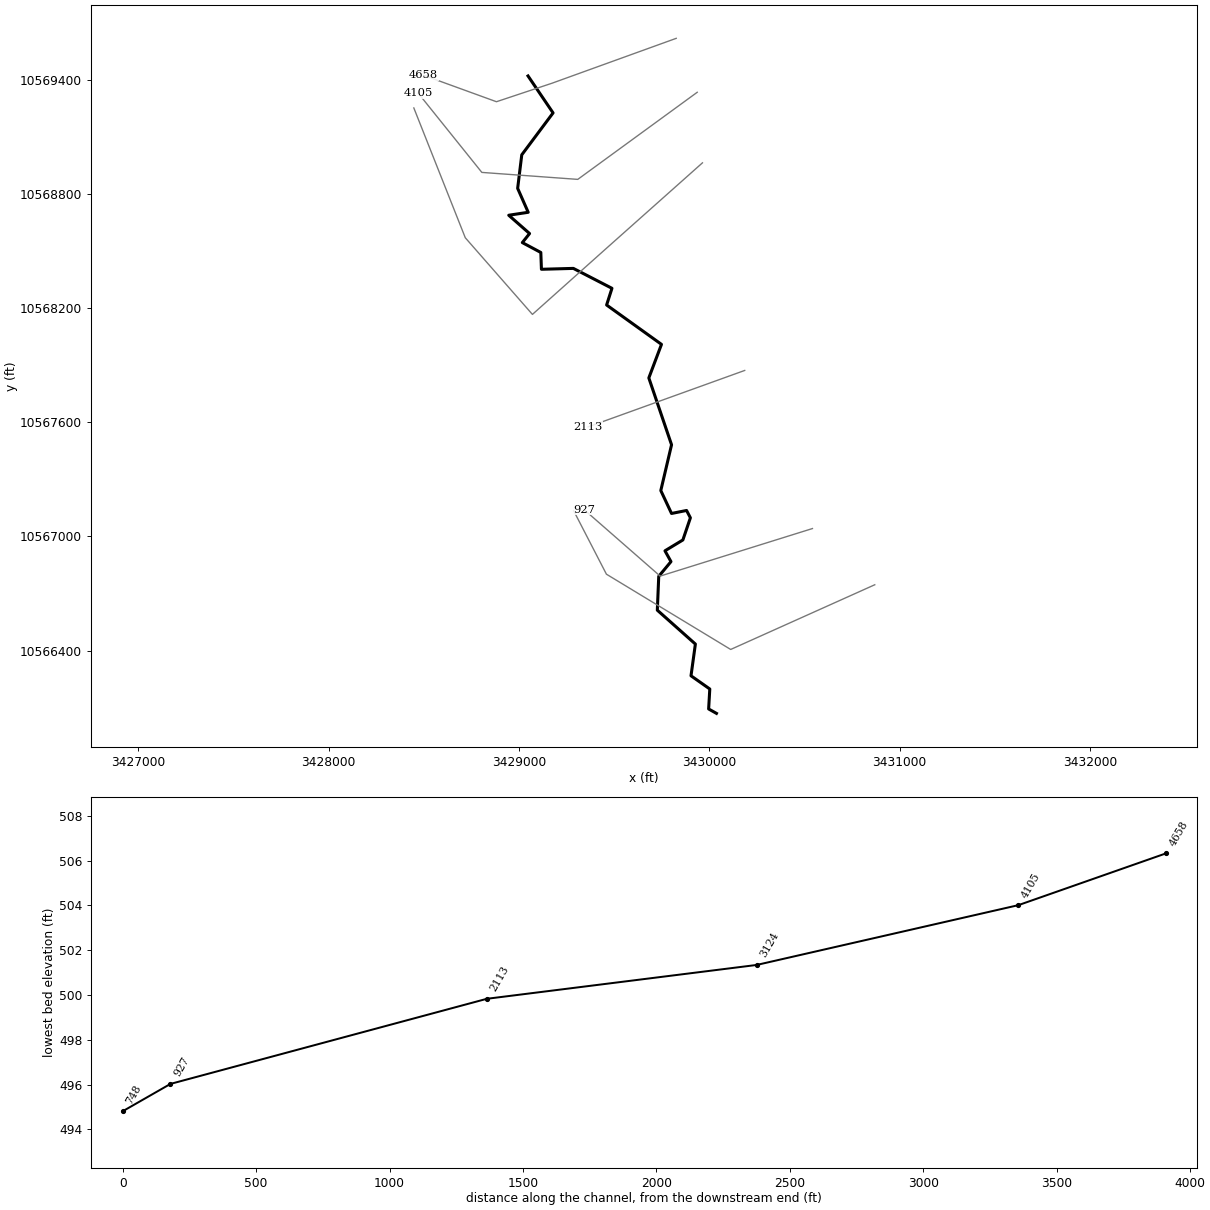
--- UNT00608 IN CHRS.prj (project) ---

Proj Title=UNT00608 IN CHRS Base Level Engineering
Current Plan=p01
Default Exp/Contr=0.3,0.1
English Units
Geom File=g01
Flow File=f01
Plan File=p01
BEGIN DESCRIPTION:
UNT00608 IN CHRS
END DESCRIPTION:

--- UNT00608 IN CHRS.p01 (plan) ---

Plan Title=Multiple Run
Short Identifier=Multiple
Geom File=g01
Flow File=f01
Subcritical Flow
K Sum by GR= 0
Std Step Tol= 0.01
Critical Tol= 0.01
Num of Std Step Trials= 20
Max Error Tol= 0.3
Flow Tol Ratio= 0.001
Split Flow NTrial= 30
Split Flow Tol= 0.02
Split Flow Ratio= 0.02
Log Output Level= 0
Friction Slope Method= 1
Unsteady Friction Slope Method= 2
Unsteady Bridges Friction Slope Method= 1
Parabolic Critical Depth
Global Vel Dist=  1 , 1 , 1
Global Log Level= 0
CheckData=True
Encroach Param= -1, 0, 0, 0
BEGIN DESCRIPTION:
Multiple Run
END DESCRIPTION:

--- UNT00608 IN CHRS.f01 (steady flow) ---

Flow Title=Multiple
Number of Profiles=7
Profile Names=10-year,25-year,50-year,1pct_min,100-year,1pct_plu,500-year
River Rch & RM= UNT00608 IN CHRS,Reach-1,4658
     253     309     347     285     386     522     474
Boundary for River Rch & Prof#=UNT00608 IN CHRS,Reach-1,1
Up Type=0
Dn Type=3
Dn Slope=0.005
Boundary for River Rch & Prof#=UNT00608 IN CHRS,Reach-1,2
Up Type=0
Dn Type=3
Dn Slope=0.005
Boundary for River Rch & Prof#=UNT00608 IN CHRS,Reach-1,3
Up Type=0
Dn Type=3
Dn Slope=0.005
Boundary for River Rch & Prof#=UNT00608 IN CHRS,Reach-1,4
Up Type=0
Dn Type=3
Dn Slope=0.005
Boundary for River Rch & Prof#=UNT00608 IN CHRS,Reach-1,5
Up Type=0
Dn Type=3
Dn Slope=0.005
Boundary for River Rch & Prof#=UNT00608 IN CHRS,Reach-1,6
Up Type=0
Dn Type=3
Dn Slope=0.005
Boundary for River Rch & Prof#=UNT00608 IN CHRS,Reach-1,7
Up Type=0
Dn Type=3
Dn Slope=0.005

--- UNT00608 IN CHRS.g01 (geometry) ---

Geom Title=Existing Conditions
Program Version=4.10

River Reach=UNT00608 IN CHRS,Reach-1
Reach XY= 30
      3429047.99     10569421.59      3429179.57      10569227.3
      3429015.12     10569006.89      3428993.48     10568830.56
      3429048.94     10568704.69      3428946.62     10568689.17
      3429056.13     10568592.94      3429018.04     10568545.33
      3429115.21     10568493.38      3429118.43       10568405.
      3429286.11     10568409.67      3429488.92     10568304.97
      3429460.82     10568217.17      3429749.06     10568010.15
      3429682.58     10567833.65      3429802.02     10567482.16
       3429745.5      10567241.5      3429801.84     10567120.98
      3429880.91     10567136.72      3429900.92     10567098.03
      3429861.47     10566981.59      3429767.32     10566924.62
      3429798.95     10566867.75      3429734.67      10566790.4
      3429727.21     10566612.32      3429927.15     10566434.27
      3429904.18     10566267.36      3430002.84      10566197.9
      3429996.82     10566092.93      3430037.86     10566069.73

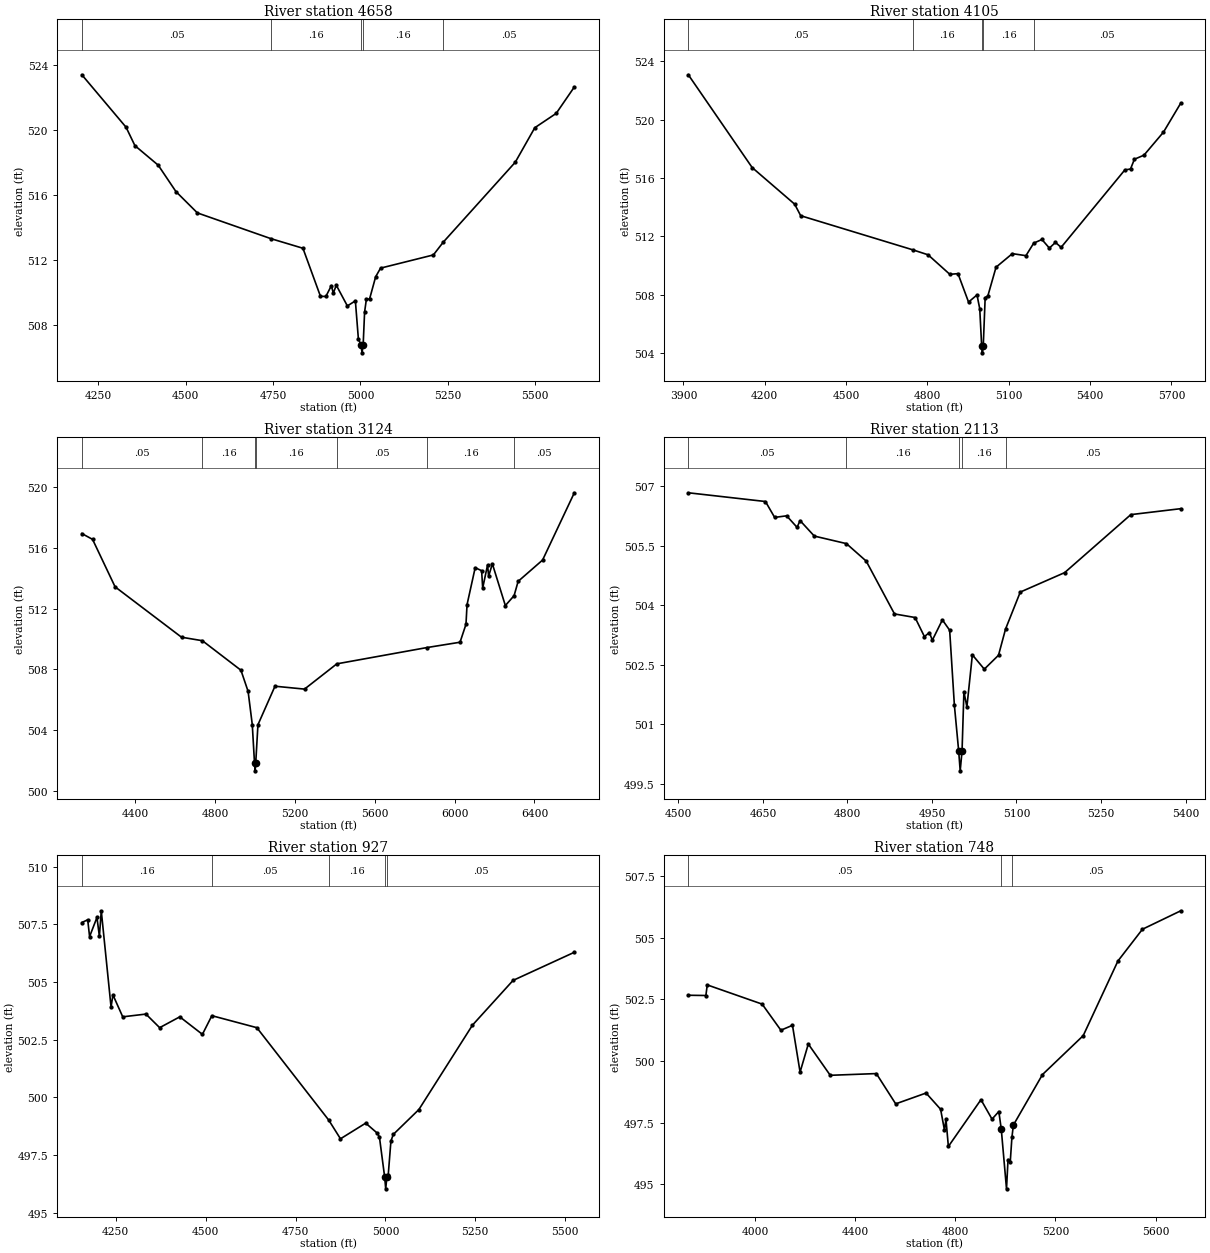
Type RM Length L Ch R = 1 ,4658    ,553,553,553
BEGIN DESCRIPTION:
UNT00608 IN CHRS 4.5
END DESCRIPTION:
XS GIS Cut Line= 4
      3429826.51     10569619.43      3429173.76     10569383.33
      3428882.09      10569286.1      3428500.14     10569424.99
#Sta/Elev= 30
  4203.5  523.39  4329.9  520.17  4355.2  519.04  4421.8  517.84  4472.5  516.22
  4533.8  514.91    4744  513.33  4835.6  512.74  4885.7  509.79  4901.1  509.78
    4917  510.45  4922.3  509.98    4931  510.47  4962.6   509.2  4985.5  509.51
  4994.2  507.15  5001.8  506.82  5004.5  506.32  5007.8  506.82  5011.9  508.83
  5017.1  509.63  5025.9  509.61  5043.5  510.99  5057.5  511.52  5208.5  512.33
    5237  513.12  5442.6  518.02  5498.5  520.14  5559.7  521.02  5611.5  522.64
#Mann= 5 ,-1 , 0
  4203.5     .05       0    4744     .16       0  5001.8     .07       0
  5007.8     .16       0    5237     .05       0
Bank Sta=5001.8,5007.8
XS Rating Curve= 0 ,0
Exp/Cntr=0.3,0.1

Type RM Length L Ch R = 1 ,4105    ,981,981,981
BEGIN DESCRIPTION:
UNT00608 IN CHRS 4.0
END DESCRIPTION:
XS GIS Cut Line= 4
      3429936.87     10569335.82      3429309.31     10568877.75
      3428805.41     10568914.39      3428471.01     10569331.25
#Sta/Elev= 30
  3918.1  523.07  4153.6  516.71  4310.4   514.2  4332.6  513.41  4746.3  511.07
  4802.5  510.73  4882.8  509.39  4912.8  509.44  4951.8  507.49    4983  507.98
  4993.1  507.03  5000.1  504.51  5002.8  504.01  5006.1  504.51  5013.1  507.79
  5023.1  507.92  5053.2  509.88  5113.4  510.81  5163.5  510.67  5192.2  511.53
  5222.4  511.78    5250  511.19  5272.4  511.58  5293.2  511.24  5528.4  516.55
  5549.2  516.61  5563.6  517.28  5598.9  517.56  5670.9  519.14  5734.7  521.13
#Mann= 5 ,-1 , 0
  3918.1     .05       0  4746.3     .16       0  5000.1     .07       0
  5006.1     .16       0  5192.2     .05       0
Bank Sta=5000.1,5006.1
XS Rating Curve= 0 ,0
Exp/Cntr=0.3,0.1

Type RM Length L Ch R = 1 ,3124    ,1011,1011,1011
BEGIN DESCRIPTION:
UNT00608 IN CHRS 3.0
END DESCRIPTION:
XS GIS Cut Line= 5
      3429964.35     10568964.75      3429460.48     10568515.85
       3429071.1      10568167.7      3428718.37     10568570.82
      3428448.11     10569253.34
#Sta/Elev= 30
  4132.7  516.93  4186.3  516.55  4299.2  513.43  4631.9  510.12  4736.5  509.89
  4929.6  507.95  4965.5  506.56  4986.4  504.38  4997.6  501.84  5000.4  501.34
  5003.6  501.84  5014.8  504.37  5100.1   506.9  5248.1  506.71  5409.9  508.37
  5861.2  509.44  6027.1  509.79  6056.9  510.97  6062.2  512.26    6103  514.69
  6135.2  514.49  6140.6  513.35    6165  514.87  6170.3  514.13  6189.1  514.94
  6254.1   512.2  6297.9  512.85  6318.1  513.79  6440.6  515.19  6599.6  519.61
#Mann= 7 ,-1 , 0
  4132.7     .05       0  4736.5     .16       0  4997.6     .07       0
  5003.6     .16       0  5409.9     .05       0  5861.2     .16       0
  6297.9     .05       0
Bank Sta=4997.6,5003.6
XS Rating Curve= 0 ,0
Exp/Cntr=0.3,0.1

Type RM Length L Ch R = 1 ,2113    ,1186,1186,1186
BEGIN DESCRIPTION:
UNT00608 IN CHRS 2.0
END DESCRIPTION:
XS GIS Cut Line= 2
      3430186.25     10567872.98      3429364.11     10567576.38
#Sta/Elev= 30
  4517.6  506.83  4654.5  506.61  4670.8  506.21  4692.1  506.25  4710.6  505.96
  4715.9  506.13  4741.2  505.74  4798.2  505.55  4833.3  505.11  4883.5  503.78
    4920  503.69  4936.6  503.21  4945.4  503.31  4950.7  503.12  4968.5  503.63
  4981.4  503.37  4989.8  501.48  4997.4  500.33  5000.1  499.83  5003.4  500.33
  5006.7  501.82    5012  501.44  5021.7  502.75  5042.9  502.39  5068.1  502.74
  5080.6   503.4  5106.7  504.33  5185.5  504.82  5302.9  506.28  5391.6  506.43
#Mann= 5 ,-1 , 0
  4517.6     .05       0  4798.2     .16       0  4997.4     .07       0
  5003.4     .16       0  5080.6     .05       0
Bank Sta=4997.4,5003.4
XS Rating Curve= 0 ,0
Exp/Cntr=0.3,0.1

Type RM Length L Ch R = 1 ,927     ,179,179,179
BEGIN DESCRIPTION:
UNT00608 IN CHRS 1.0
END DESCRIPTION:
XS GIS Cut Line= 3
      3430542.15     10567041.66      3429742.11     10566791.64
      3429342.11     10567141.64
#Sta/Elev= 30
  4155.7  507.58    4172   507.7  4177.2  506.97  4197.7   507.8  4204.5  506.98
  4209.7  508.09  4236.9  503.92  4242.2  504.44  4269.4  503.49  4333.9  503.61
  4372.1  503.02  4428.1  503.49    4491  502.73  4517.3  503.54  4642.4  503.02
  4842.4  499.01    4875   498.2  4945.2  498.88  4977.7  498.44  4983.4  498.27
    4998  496.53  5000.8  496.03    5004  496.53  5007.7  496.61  5015.3   498.1
  5021.9  498.39  5093.1  499.47  5242.1  503.13    5355  505.07  5525.4  506.29
#Mann= 5 ,-1 , 0
  4155.7     .16       0  4517.3     .05       0  4842.4     .16       0
    4998     .07       0    5004     .05       0
Bank Sta=4998,5004
XS Rating Curve= 0 ,0
Exp/Cntr=0.3,0.1

Type RM Length L Ch R = 1 ,748     ,0,0,0
BEGIN DESCRIPTION:
UNT00608 IN CHRS 1.9
END DESCRIPTION:
XS GIS Cut Line= 4
      3430869.56     10566746.12      3430112.59     10566405.82
      3429459.81     10566801.66      3429287.93     10567134.99
#Sta/Elev= 30
  3732.4  502.67  3802.6  502.66  3808.1  503.09  4027.5  502.31  4102.4  501.25
  4148.7  501.45  4179.1  499.55    4212  500.69  4299.7  499.42  4483.9  499.49
  4561.3  498.26  4682.7   498.7  4740.8  498.04  4756.3  497.19  4762.2  497.64
  4771.8  496.53  4902.1  498.43  4946.3  497.64  4973.5  497.95  4983.2  497.24
  5004.2  494.81  5010.3     496    5019  495.88  5025.8   496.9  5031.7   497.4
    5148  499.45  5310.8  501.03  5449.5  504.06  5547.5  505.35  5700.8   506.1
#Mann= 3 ,-1 , 0
  3732.4     .05       0  4983.2     .07       0  5025.8     .05       0
Bank Sta=4983.2,5031.7
XS Rating Curve= 0 ,0
Exp/Cntr=0.3,0.1

Chan Stop Cuts=-1
Use User Specified Reach Order=0
Composite Channel Slope=5