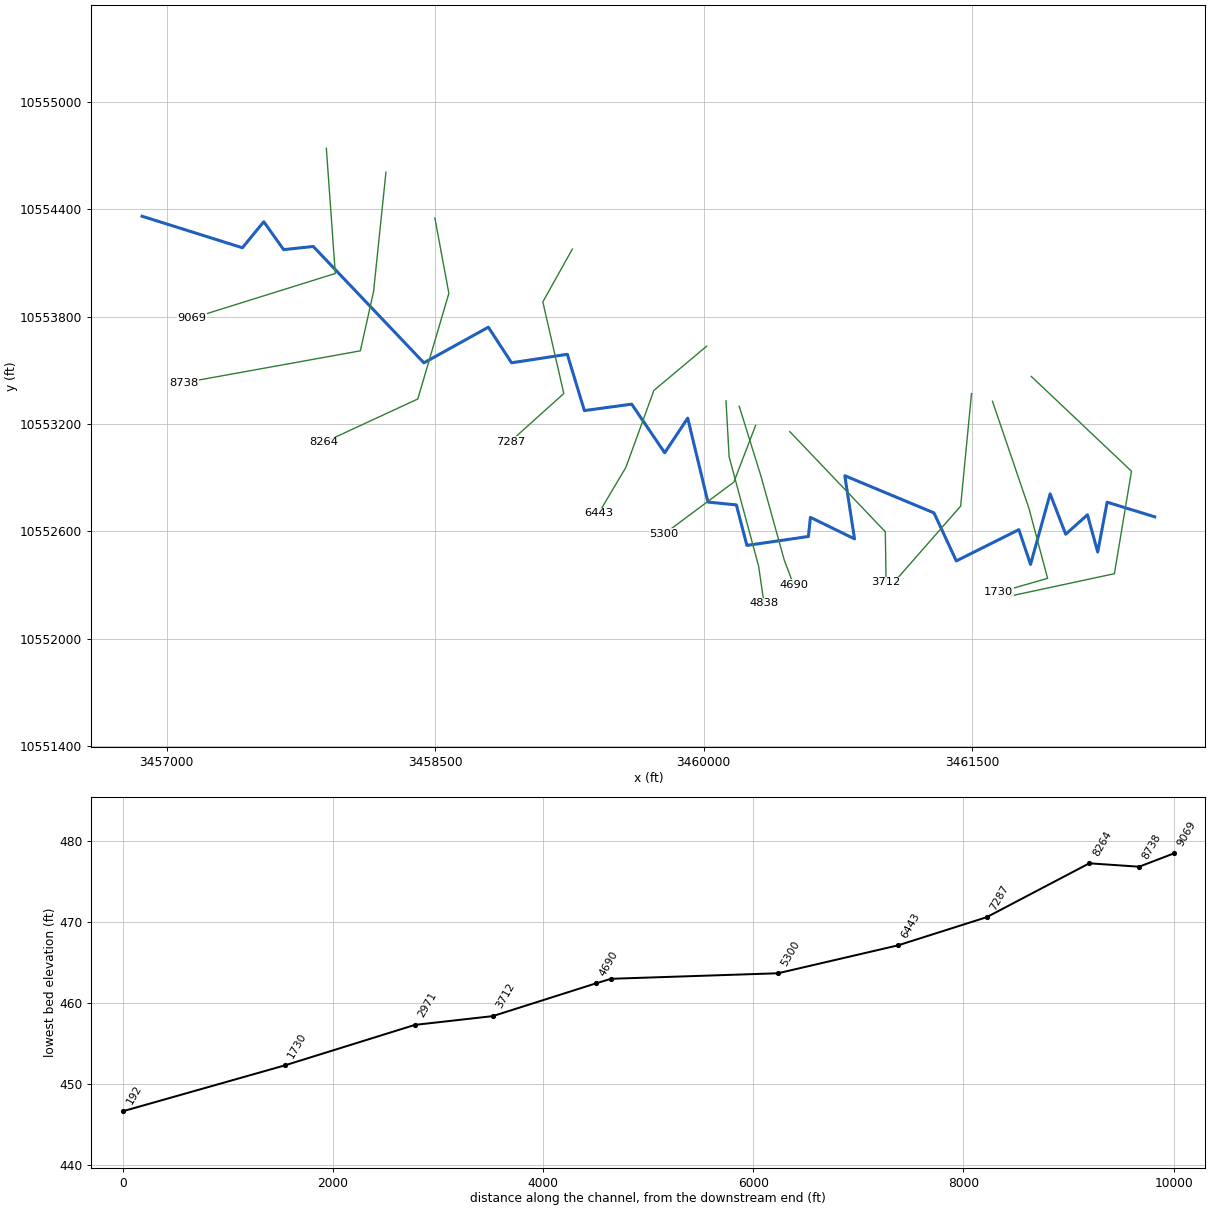
--- UNT0061 IN CHRS.prj (project) ---

Proj Title=UNT0061 IN CHRS Base Level Engineering
Current Plan=p01
Default Exp/Contr=0.3,0.1
English Units
Geom File=g01
Flow File=f01
Plan File=p01
Y Axis Title=Elevation
X Axis Title(PF)=Main Channel Distance
X Axis Title(XS)=Station
BEGIN DESCRIPTION:
UNT0061 IN CHRS
END DESCRIPTION:
DSS Export Rating Curves= 0
DSS Export Rating Curve Sorted= 0
DSS Export Volume Flow Curves= 0
DXF OffsetX= 0
DXF OffsetY= 0
DXF ScaleX= 1
DXF ScaleY= 10

--- UNT0061 IN CHRS.p01 (plan) ---

Plan Title=Multiple Run
Short Identifier=Multiple
Geom File=g01
Flow File=f01
Subcritical Flow
K Sum by GR= 0
Std Step Tol= 0.01
Critical Tol= 0.01
Num of Std Step Trials= 20
Max Error Tol= 0.3
Flow Tol Ratio= 0.001
Split Flow NTrial= 30
Split Flow Tol= 0.02
Split Flow Ratio= 0.02
Log Output Level= 0
Friction Slope Method= 1
Unsteady Friction Slope Method= 2
Unsteady Bridges Friction Slope Method= 1
Parabolic Critical Depth
Global Vel Dist=  1 , 1 , 1
Global Log Level= 0
CheckData=True
Encroach Param= -1, 0, 0, 0
BEGIN DESCRIPTION:
Multiple Run
END DESCRIPTION:

--- UNT0061 IN CHRS.f01 (steady flow) ---

Flow Title=Multiple
Number of Profiles=7
Profile Names=10-year,25-year,50-year,1pct_min,100-year,1pct_plu,500-year
River Rch & RM= UNT0061 IN CHRS,Reach-1,9069
     542     696     811     689     932    1261    1227
River Rch & RM= UNT0061 IN CHRS,Reach-1,7287
     590     758     884     751    1015    1373    1335
Boundary for River Rch & Prof#=UNT0061 IN CHRS,Reach-1,1
Up Type=0
Dn Type=3
Dn Slope=0.005
Boundary for River Rch & Prof#=UNT0061 IN CHRS,Reach-1,2
Up Type=0
Dn Type=3
Dn Slope=0.005
Boundary for River Rch & Prof#=UNT0061 IN CHRS,Reach-1,3
Up Type=0
Dn Type=3
Dn Slope=0.005
Boundary for River Rch & Prof#=UNT0061 IN CHRS,Reach-1,4
Up Type=0
Dn Type=3
Dn Slope=0.005
Boundary for River Rch & Prof#=UNT0061 IN CHRS,Reach-1,5
Up Type=0
Dn Type=3
Dn Slope=0.005
Boundary for River Rch & Prof#=UNT0061 IN CHRS,Reach-1,6
Up Type=0
Dn Type=3
Dn Slope=0.005
Boundary for River Rch & Prof#=UNT0061 IN CHRS,Reach-1,7
Up Type=0
Dn Type=3
Dn Slope=0.005

--- UNT0061 IN CHRS.g01 (geometry) ---

Geom Title=Existing Conditions
Program Version=4.10

River Reach=UNT0061 IN CHRS ,Reach-1
Reach XY= 30
      3456862.11     10554361.64      3457422.98     10554185.52
      3457542.37     10554330.97       3457653.5     10554175.05
      3457819.07     10554192.69      3458437.33     10553542.24
      3458797.46      10553741.5      3458927.28     10553542.56
      3459238.85     10553590.04      3459334.16     10553275.45
      3459598.74     10553311.39      3459783.12     10553039.52
      3459911.77     10553233.27      3460024.79       10552764.
      3460183.64     10552748.37      3460242.49     10552521.81
      3460586.24     10552571.81      3460597.49     10552678.67
      3460844.06     10552558.39      3460789.85     10552911.38
      3461288.07     10552703.77      3461412.89     10552435.38
      3461762.42     10552609.82      3461827.84     10552415.91
      3461937.21       10552810.      3462024.23     10552584.45
      3462145.85     10552692.92      3462203.23     10552484.81
      3462255.84     10552763.49      3462522.11     10552681.64

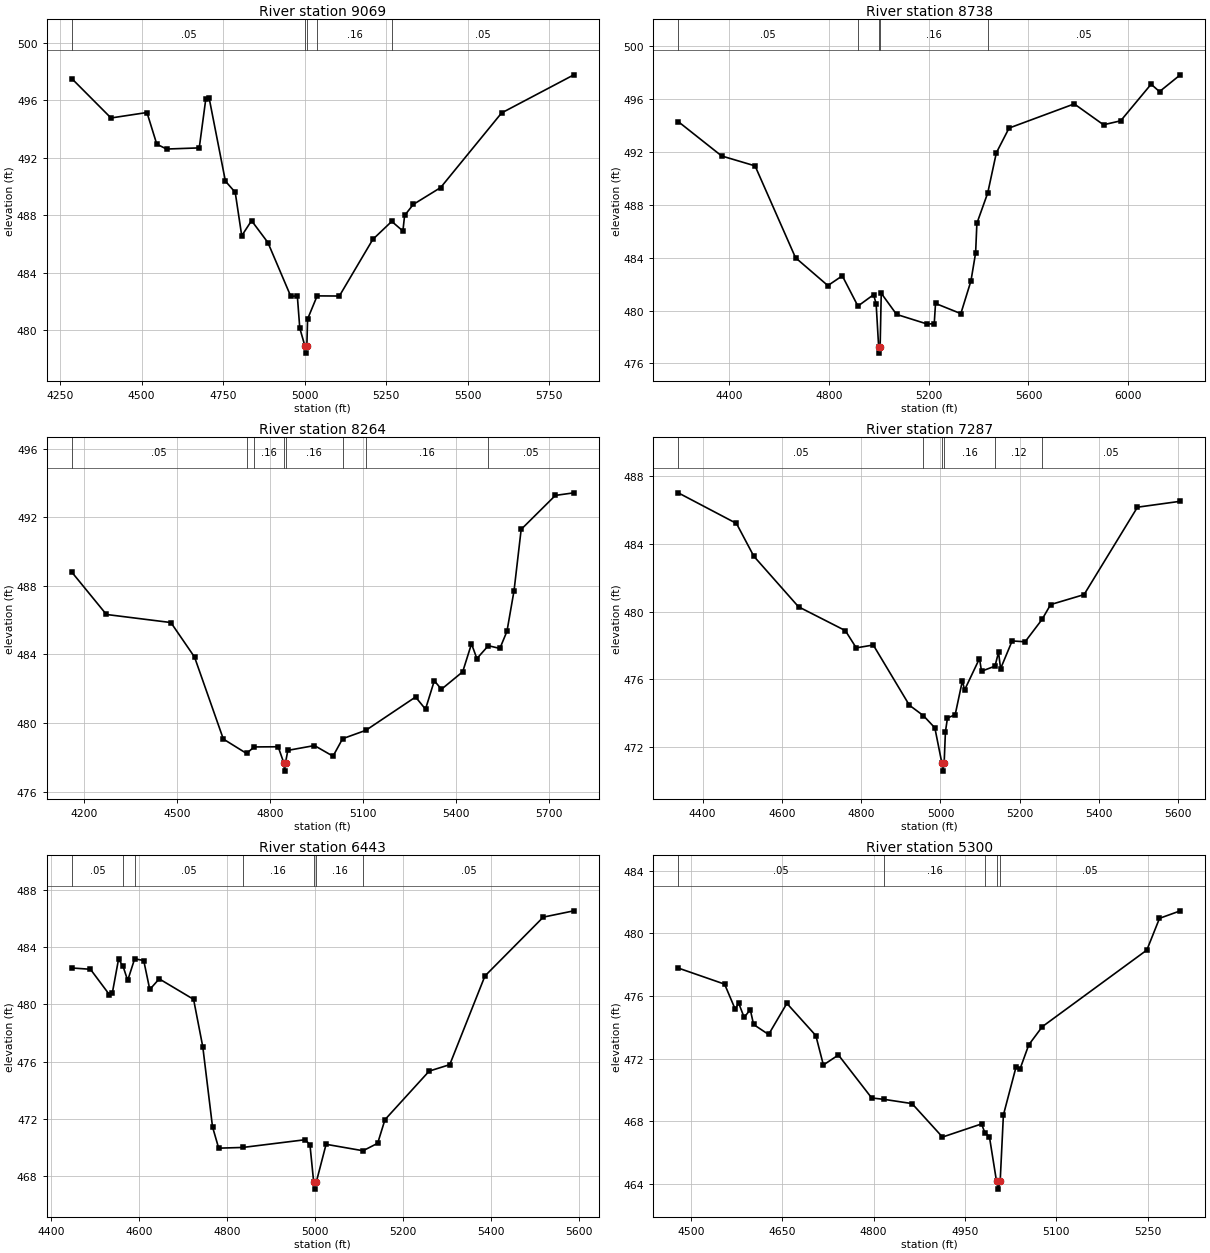
Type RM Length L Ch R = 1 ,9069    ,331,331,331
BEGIN DESCRIPTION:
UNT0061 IN CHRS 12.0
END DESCRIPTION:
XS GIS Cut Line= 3
      3457892.11     10554741.64      3457942.11     10554041.64
      3457142.13     10553791.65
#Sta/Elev= 30
  4286.1  497.51  4406.4  494.77  4516.7  495.15  4546.8  492.95  4576.8  492.61
  4677.1  492.69  4697.1  496.08  4707.2  496.18  4757.3  490.38  4787.4   489.6
  4807.4  486.58  4837.5  487.63  4887.6  486.11  4957.8  482.37  4977.9   482.4
  4985.4  480.16  5001.1  478.92  5003.9  478.42  5007.1  478.92  5009.4  480.79
  5038.7   482.4  5106.8  482.39  5209.5  486.33  5267.5  487.58  5301.7  486.91
  5306.9  487.99  5333.6  488.76  5417.4  489.93  5604.4  495.12    5826  497.77
#Mann= 5 ,-1 , 0
  4286.1     .05       0  5001.1    .035       0  5007.1     .05       0
  5038.7     .16       0  5267.5     .05       0
Bank Sta=5001.1,5007.1
XS Rating Curve= 0 ,0
Exp/Cntr=0.3,0.1

Type RM Length L Ch R = 1 ,8738    ,474,474,474
BEGIN DESCRIPTION:
UNT0061 IN CHRS 11.0
END DESCRIPTION:
XS GIS Cut Line= 4
      3458225.27     10554607.69      3458155.82     10553939.28
      3458082.04     10553609.42        3457097.     10553431.51
#Sta/Elev= 30
  4197.1   494.3    4371   491.7  4504.8  490.95  4666.9     484  4796.4  481.89
  4854.2  482.63  4916.8  480.34  4979.4   481.2  4989.7  480.53  4999.8  477.28
  5002.6  476.78  5005.8  477.28  5010.2  481.31  5071.6  479.71  5194.6  478.98
  5222.5  479.01  5227.6  480.54    5329  479.77  5369.6  482.25  5388.2  484.36
  5393.3   486.6  5436.7   488.9  5471.3  491.94  5522.1  493.81  5783.3  495.64
  5900.5  494.06  5969.2  494.36  6091.1  497.13  6124.8  496.57  6208.1  497.84
#Mann= 5 ,-1 , 0
  4197.1     .05       0  4916.8     .16       0  4999.8     .07       0
  5005.8     .16       0  5436.7     .05       0
Bank Sta=4999.8,5005.8
XS Rating Curve= 0 ,0
Exp/Cntr=0.3,0.1

Type RM Length L Ch R = 1 ,8264    ,977,977,977
BEGIN DESCRIPTION:
UNT0061 IN CHRS 10.0
END DESCRIPTION:
XS GIS Cut Line= 4
       3458498.7     10554351.63      3458576.83      10553930.6
      3458403.22     10553340.32      3457878.03     10553097.26
#Sta/Elev= 30
  4159.6   488.8  4271.5  486.33  4479.8  485.86  4556.2  483.85  4649.3  479.07
  4724.3  478.23  4748.9  478.61  4826.5  478.62  4844.3   477.7  4847.1   477.2
  4850.3   477.7  4857.7  478.41  4943.8  478.69  5003.7  478.07  5034.7  479.09
    5110  479.58  5270.4  481.52  5302.5  480.81    5331  482.47  5353.9  481.97
  5422.7  482.99  5451.1  484.62  5468.5  483.76  5505.5  484.51  5542.8  484.35
  5565.7  485.35  5588.6  487.72  5611.6  491.29  5722.2  493.27  5781.8  493.42
#Mann= 8 ,-1 , 0
  4159.6     .05       0  4724.3     .12       0  4748.9     .16       0
  4844.3     .07       0  4850.3     .16       0  5034.7     .12       0
    5110     .16       0  5505.5     .05       0
Bank Sta=4844.3,4850.3
XS Rating Curve= 0 ,0
Exp/Cntr=0.3,0.1

Type RM Length L Ch R = 1 ,7287    ,844,844,844
BEGIN DESCRIPTION:
UNT0061 IN CHRS 8.0
END DESCRIPTION:
XS GIS Cut Line= 4
      3459266.95     10554178.03        3459102.     10553882.86
      3459219.19     10553370.71      3458919.74     10553101.63
#Sta/Elev= 30
  4338.7  487.02  4485.5  485.21  4529.3  483.27    4642  480.28  4760.1  478.87
  4787.6  477.85  4830.5  478.02  4921.5  474.46    4957  473.84  4985.8  473.12
  5003.3  471.06  5006.1  470.56  5009.3  471.06  5012.5  472.89  5017.6   473.7
  5037.1   473.9  5055.4  475.92  5060.6  475.35  5098.4  477.22  5103.5  476.47
  5137.5  476.77  5146.4  477.59  5151.6  476.62  5180.7  478.26  5213.4  478.21
  5256.1  479.53  5277.7  480.41  5362.1     481  5496.7  486.17  5604.8  486.52
#Mann= 6 ,-1 , 0
  4338.7     .05       0    4957     .16       0  5003.3     .07       0
  5009.3     .16       0  5137.5     .12       0  5256.1     .05       0
Bank Sta=5003.3,5009.3
XS Rating Curve= 0 ,0
Exp/Cntr=0.3,0.1

Type RM Length L Ch R = 1 ,6443    ,1143,1143,1143
BEGIN DESCRIPTION:
UNT0061 IN CHRS 6.0
END DESCRIPTION:
XS GIS Cut Line= 4
      3460017.79     10553635.46      3459722.66     10553388.07
      3459566.41     10552958.38      3459414.48     10552702.27
#Sta/Elev= 30
  4447.4  482.53  4489.8  482.44  4532.8  480.67  4539.3  480.75  4553.6  483.14
  4563.7  482.66  4574.4  481.66  4590.2  483.17  4610.8  483.05  4624.5  481.03
    4646  481.77    4724  480.34  4744.9  477.03    4767  471.44    4781  469.95
  4835.9     470  4977.7  470.54  4988.3  470.18  4996.7  467.59  4999.4  467.09
  5002.7  467.59  5024.9  470.22  5108.7  469.77    5142  470.29  5158.6  471.94
    5259  475.33  5305.7  475.78  5385.6  481.97  5518.1  486.08  5587.5  486.52
#Mann= 7 ,-1 , 0
  4447.4     .05       0  4563.7      .1       0  4590.2     .05       0
  4835.9     .16       0  4996.7     .07       0  5002.7     .16       0
  5108.7     .05       0
Bank Sta=4996.7,5002.7
XS Rating Curve= 0 ,0
Exp/Cntr=0.3,0.1

Type RM Length L Ch R = 1 ,5300    ,1588,1588,1588
BEGIN DESCRIPTION:
UNT0061 IN CHRS 5.0
END DESCRIPTION:
XS GIS Cut Line= 3
      3460291.23     10553192.74      3460169.71     10552875.91
      3459780.14      10552585.9
#Sta/Elev= 30
  4478.9  477.79  4555.1  476.76  4572.7  475.14    4578  475.57  4587.2  474.63
  4597.3  475.13  4602.7  474.18  4627.4  473.54  4657.4  475.53    4705  473.47
  4717.4  471.59  4742.1  472.23  4796.8  469.48  4817.5  469.39  4863.1  469.12
  4913.1  466.98  4977.3  467.82  4982.6  467.27  4990.2  467.01  5001.9  464.15
  5004.6  463.65  5007.9  464.15  5013.2  468.39  5034.1  471.48  5040.3  471.31
  5054.9  472.88  5077.1  474.04  5248.9  478.94  5269.7  480.97  5303.9  481.45
#Mann= 5 ,-1 , 0
  4478.9     .05       0  4817.5     .16       0  4982.6     .05       0
  5001.9    .035       0  5007.9     .05       0
Bank Sta=5001.9,5007.9
XS Rating Curve= 0 ,0
Exp/Cntr=0.3,0.1

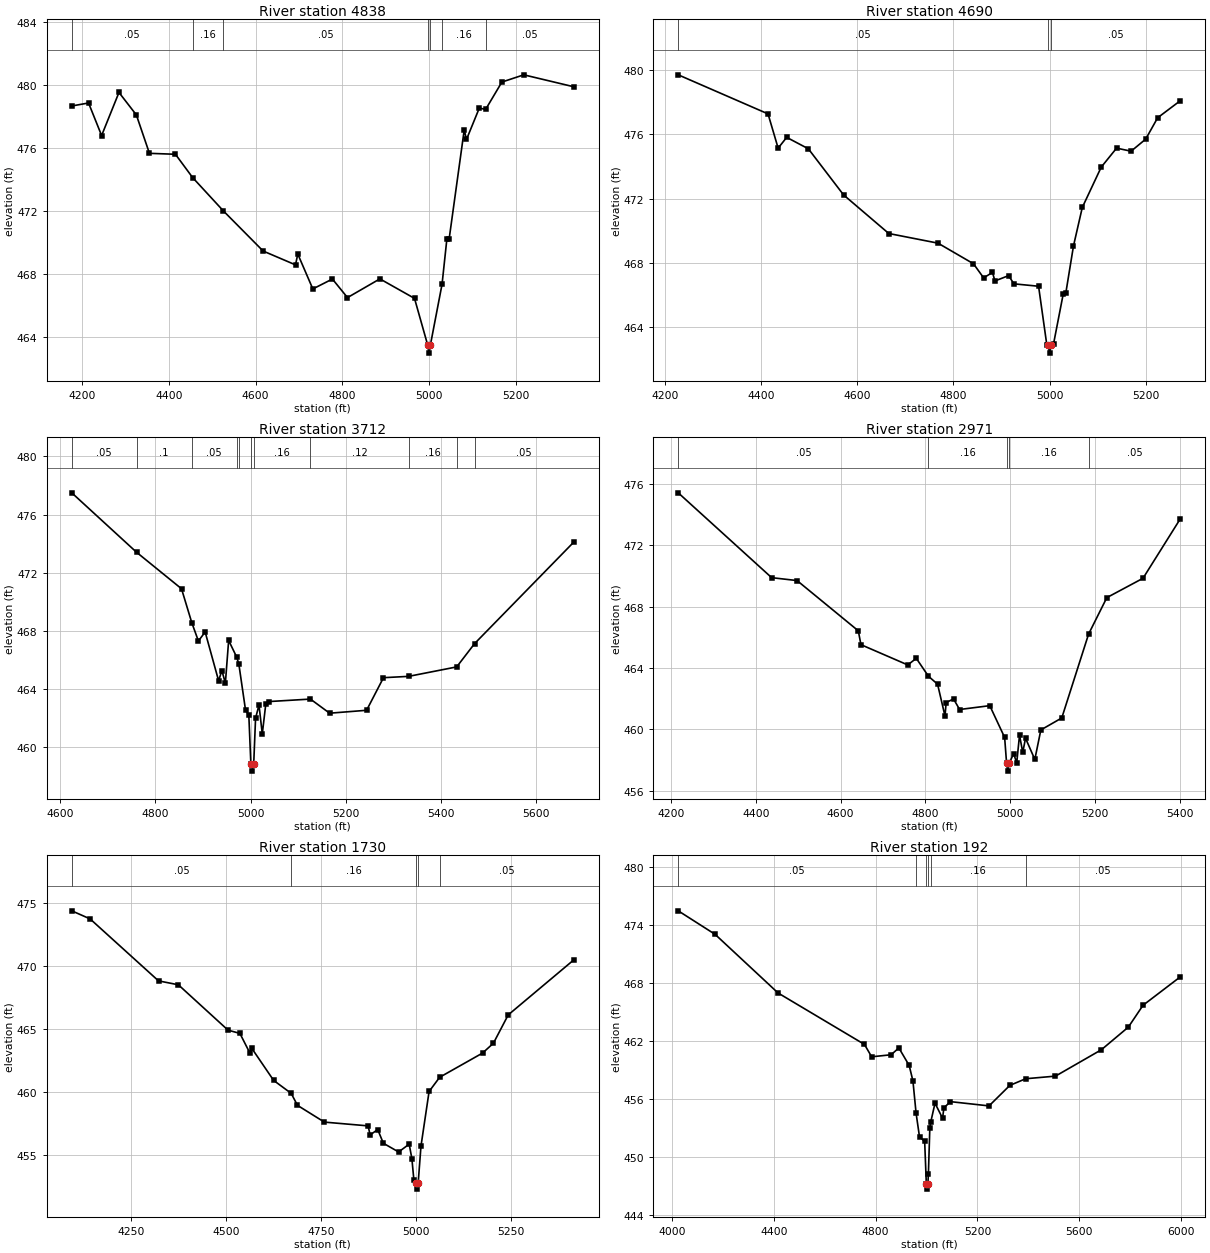
Type RM Length L Ch R = 1 ,4838    ,148,148,148
BEGIN DESCRIPTION:
UNT0061 IN CHRS 5.0
END DESCRIPTION:
XS GIS Cut Line= 4
      3460125.72     10553330.32      3460143.08     10553017.78
      3460308.01      10552405.8       3460338.4     10552197.44
#Sta/Elev= 30
  4176.4  478.68  4215.1  478.87  4245.2   476.8  4285.2  479.54  4325.3  478.11
  4355.4  475.67  4415.4  475.61    4455  474.13  4525.9  472.01  4617.5  469.46
  4692.2  468.58  4697.4  469.27  4732.1  467.05  4777.2  467.68    4812   466.5
  4886.7  467.69  4966.5  466.45    4997  463.47  4999.8  462.97    5003  463.47
    5030  467.35  5041.2  470.25  5046.4  470.24  5081.1  477.16  5086.3  476.55
  5115.9  478.55  5130.4  478.46  5167.9   480.2  5218.4  480.66  5333.8   479.9
#Mann= 7 ,-1 , 0
  4176.4     .05       0    4455     .16       0  4525.9     .05       0
    4997     .04       0    5003     .05       0    5030     .16       0
  5130.4     .05       0
Bank Sta=4997,5003
XS Rating Curve= 0 ,0
Exp/Cntr=0.3,0.1

Type RM Length L Ch R = 1 ,4690    ,978,978,978
BEGIN DESCRIPTION:
UNT0061 IN CHRS 5.6
END DESCRIPTION:
XS GIS Cut Line= 4
       3460199.5     10553299.92      3460321.03     10552909.27
      3460451.24     10552440.52      3460503.31     10552301.68
#Sta/Elev= 30
  4227.8   479.7  4414.5  477.27  4435.5  475.14  4453.3  475.81  4498.3   475.1
  4571.6  472.23  4665.6  469.83  4767.9  469.23  4841.6  467.95  4862.8  467.07
  4881.1  467.41  4886.3  466.88  4914.7  467.21  4925.7   466.7    4977  466.55
  4994.2  462.89    4997  462.89  4999.8  462.39    5003  462.89  5008.1  462.96
  5028.4  466.09  5033.6  466.12  5049.6  469.06  5067.9  471.45  5107.3  473.96
  5139.2  475.14  5169.4  474.95  5199.7   475.7  5224.6  477.03  5271.7  478.09
#Mann= 3 ,-1 , 0
  4227.8     .05       0    4997     .04       0    5003     .05       0
Bank Sta=4997,5003
XS Rating Curve= 0 ,0
Exp/Cntr=0.3,0.1

Type RM Length L Ch R = 1 ,3712    ,741,741,741
BEGIN DESCRIPTION:
UNT0061 IN CHRS 4.0
END DESCRIPTION:
XS GIS Cut Line= 3
      3460482.18     10553158.07      3461016.06     10552598.14
       3461020.4     10552316.33
#Sta/Elev= 30
    4624  477.49  4760.1  473.41  4854.7   470.9  4876.2  468.58  4890.2  467.31
  4904.4  467.93  4932.7  464.58  4939.6  465.28  4946.9  464.41  4953.8  467.35
  4970.9  466.19  4975.3  465.71  4989.3  462.56  4996.2  462.23  5000.5  458.87
  5003.2  458.37  5006.5  458.87  5010.4  462.01  5017.6  462.91  5024.5  460.92
  5031.8  462.96  5038.7  463.15  5125.7  463.32  5166.1  462.35  5243.8  462.55
  5279.3  464.79    5332  464.88  5433.2  465.53  5470.8  467.13  5679.5  474.11
#Mann= 11 ,-1 , 0
    4624     .05       0  4760.1      .1       0  4876.2     .05       0
  4970.9      .1       0  4975.3     .16       0  5000.5     .07       0
  5006.5     .16       0  5125.7     .12       0    5332     .16       0
  5433.2     .12       0  5470.8     .05       0
Bank Sta=5000.5,5006.5
XS Rating Curve= 0 ,0
Exp/Cntr=0.3,0.1

Type RM Length L Ch R = 1 ,2971    ,1241,1241,1241
BEGIN DESCRIPTION:
UNT0061 IN CHRS 3.0
END DESCRIPTION:
XS GIS Cut Line= 3
      3461497.84     10553370.73      3461437.07     10552741.37
      3461073.31     10552325.64
#Sta/Elev= 30
  4216.7   475.4  4437.1  469.88  4497.1  469.69  4641.6  466.42  4647.8  465.52
  4758.3   464.2  4778.4  464.63  4807.2  463.46  4828.6  462.95  4846.2  460.87
  4848.8  461.75  4866.3  461.99  4880.6   461.3  4951.8  461.55  4986.9  459.48
  4991.5  457.79  4994.2  457.29  4997.5  457.79  5008.1  458.43  5015.4  457.83
    5022  459.63  5029.6  458.51  5036.2  459.43  5058.1  458.05  5072.3  459.97
  5121.7  460.75    5185  466.21    5228  468.58  5313.4  469.84  5401.4  473.71
#Mann= 5 ,-1 , 0
  4216.7     .05       0  4807.2     .16       0  4991.5     .07       0
  4997.5     .16       0    5185     .05       0
Bank Sta=4991.5,4997.5
XS Rating Curve= 0 ,0
Exp/Cntr=0.3,0.1

Type RM Length L Ch R = 1 ,1730    ,1538,1538,1538
BEGIN DESCRIPTION:
UNT0061 IN CHRS 2.0
END DESCRIPTION:
XS GIS Cut Line= 4
      3461615.03     10553327.27      3461819.02     10552728.35
      3461923.18     10552337.72      3461649.71     10552259.59
#Sta/Elev= 30
  4093.4  474.38  4141.6  473.74  4321.7  468.82  4373.9  468.51  4504.6  464.91
  4535.9  464.65    4562   463.1  4567.3  463.46  4624.7  460.92  4670.9  459.89
  4687.4  458.94  4758.2  457.61  4873.4  457.31  4878.5  456.59  4898.6  457.02
  4913.5  455.93  4953.6  455.24  4981.4  455.86  4988.5  454.72  4993.7  453.04
  4999.1  452.79  5001.9  452.29  5005.1  452.79  5012.5  455.71  5033.8  460.04
  5061.7  461.17  5174.5  463.09  5203.1  463.87  5242.1  466.12  5414.8  470.49
#Mann= 5 ,-1 , 0
  4093.4     .05       0  4670.9     .16       0  4999.1     .07       0
  5005.1     .16       0  5061.7     .05       0
Bank Sta=4999.1,5005.1
XS Rating Curve= 0 ,0
Exp/Cntr=0.3,0.1

Type RM Length L Ch R = 1 ,192     ,0,0,0
BEGIN DESCRIPTION:
UNT0061 IN CHRS 1.0
END DESCRIPTION:
XS GIS Cut Line= 4
      3461832.06     10553466.17      3462391.93     10552936.68
      3462296.45     10552363.76      3461688.85     10552233.56
#Sta/Elev= 30
  4024.3  475.44    4169  473.01  4416.6  466.94    4756  461.62  4784.3  460.34
  4860.8  460.55  4891.2  461.26  4931.8  459.44  4946.5  457.84  4958.9   454.5
  4972.3  452.06  4992.6  451.59  4999.2  447.15    5002  446.65  5005.2  447.15
  5007.3  448.26  5012.9     453  5016.3  453.57  5033.2  455.54    5063  453.98
  5068.1  455.06    5094   455.7  5245.5  455.26  5327.2  457.38  5389.5  458.07
  5506.6  458.34    5687  461.07  5792.9  463.41  5850.6  465.67  5997.1  468.61
#Mann= 6 ,-1 , 0
  4024.3     .05       0  4958.9      .1       0  4999.2     .07       0
  5005.2      .1       0  5016.3     .16       0  5389.5     .05       0
Bank Sta=4999.2,5005.2
XS Rating Curve= 0 ,0
Exp/Cntr=0.3,0.1

Chan Stop Cuts=-1
Use User Specified Reach Order=0
Composite Channel Slope=5