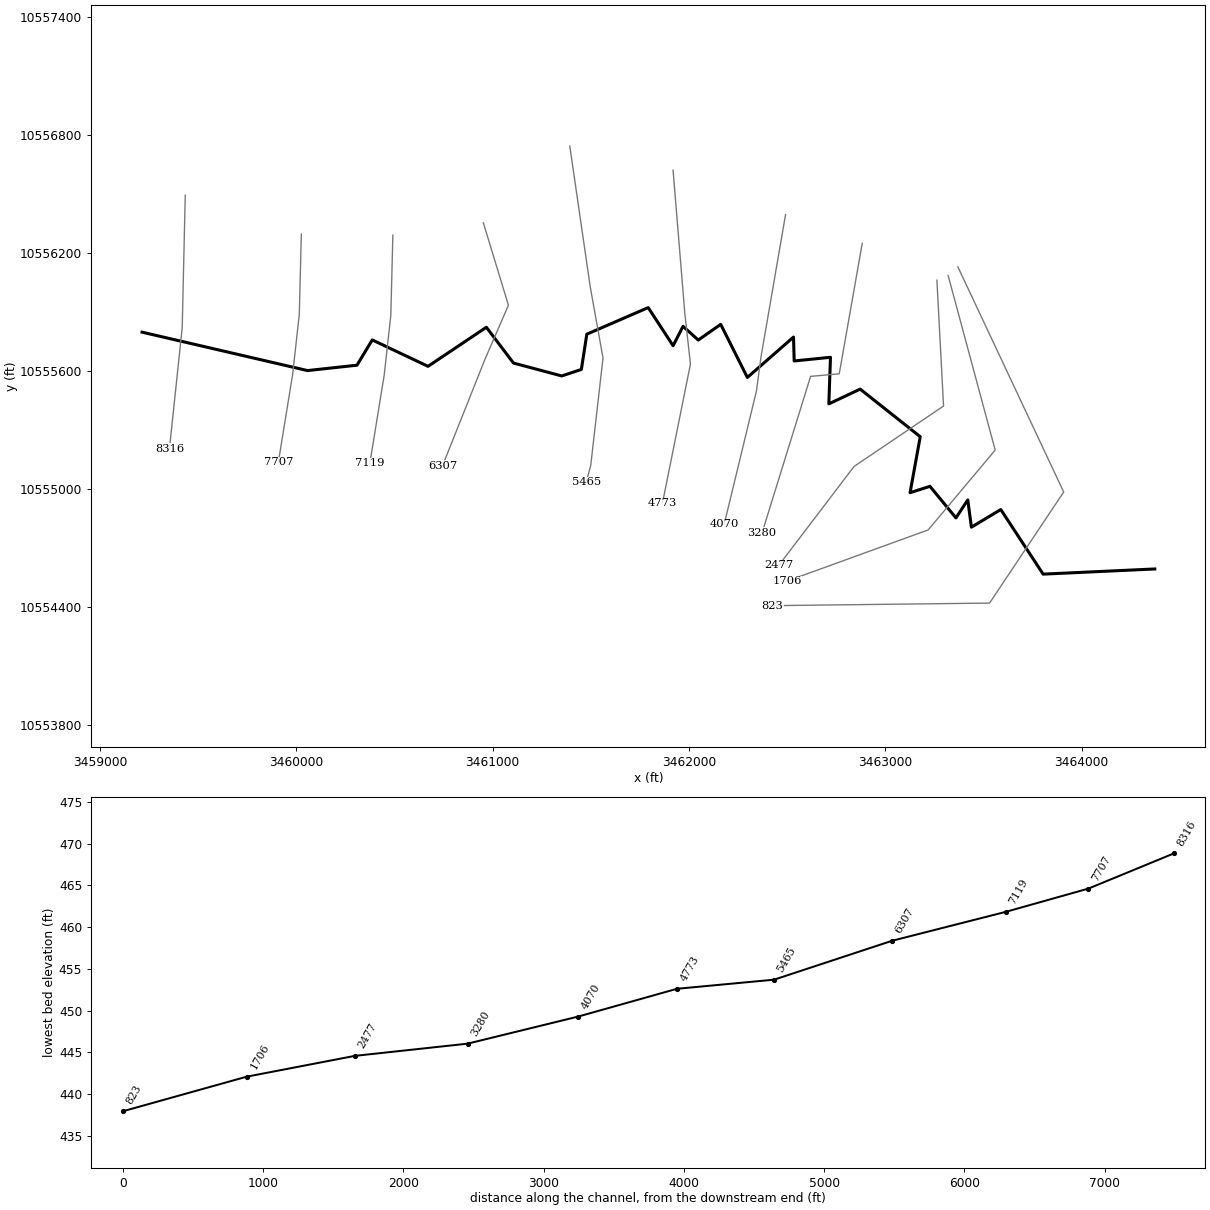
--- UNT0062 IN CHRS.prj (project) ---

Proj Title=UNT0062 IN CHRS Base Level Engineering
Current Plan=p01
Default Exp/Contr=0.3,0.1
English Units
Geom File=g01
Flow File=f01
Plan File=p01
BEGIN DESCRIPTION:
UNT0062 IN CHRS
END DESCRIPTION:

--- UNT0062 IN CHRS.p01 (plan) ---

Plan Title=Multiple Run
Short Identifier=Multiple
Geom File=g01
Flow File=f01
Subcritical Flow
K Sum by GR= 0
Std Step Tol= 0.01
Critical Tol= 0.01
Num of Std Step Trials= 20
Max Error Tol= 0.3
Flow Tol Ratio= 0.001
Split Flow NTrial= 30
Split Flow Tol= 0.02
Split Flow Ratio= 0.02
Log Output Level= 0
Friction Slope Method= 1
Unsteady Friction Slope Method= 2
Unsteady Bridges Friction Slope Method= 1
Parabolic Critical Depth
Global Vel Dist=  1 , 1 , 1
Global Log Level= 0
CheckData=True
Encroach Param= -1, 0, 0, 0
BEGIN DESCRIPTION:
Multiple Run
END DESCRIPTION:

--- UNT0062 IN CHRS.f01 (steady flow) ---

Flow Title=Multiple
Number of Profiles=7
Profile Names=10-year,25-year,50-year,1pct_min,100-year,1pct_plu,500-year
River Rch & RM= UNT0062 IN CHRS,Reach-1,8316
     378     469     535     444     601     812     756
Boundary for River Rch & Prof#=UNT0062 IN CHRS,Reach-1,1
Up Type=0
Dn Type=3
Dn Slope=0.005
Boundary for River Rch & Prof#=UNT0062 IN CHRS,Reach-1,2
Up Type=0
Dn Type=3
Dn Slope=0.005
Boundary for River Rch & Prof#=UNT0062 IN CHRS,Reach-1,3
Up Type=0
Dn Type=3
Dn Slope=0.005
Boundary for River Rch & Prof#=UNT0062 IN CHRS,Reach-1,4
Up Type=0
Dn Type=3
Dn Slope=0.005
Boundary for River Rch & Prof#=UNT0062 IN CHRS,Reach-1,5
Up Type=0
Dn Type=3
Dn Slope=0.005
Boundary for River Rch & Prof#=UNT0062 IN CHRS,Reach-1,6
Up Type=0
Dn Type=3
Dn Slope=0.005
Boundary for River Rch & Prof#=UNT0062 IN CHRS,Reach-1,7
Up Type=0
Dn Type=3
Dn Slope=0.005

--- UNT0062 IN CHRS.g01 (geometry) ---

Geom Title=Existing Conditions

River Reach=UNT0062 IN CHRS,Reach-1
Reach XY= 30
      3459214.21     10555796.67      3460056.90     10555601.17
      3460308.78     10555628.50      3460386.63     10555757.11
      3460670.73     10555622.77      3460967.92     10555821.63
      3461105.75     10555639.45      3461351.73     10555573.82
      3461451.71     10555606.97      3461479.40     10555786.28
      3461792.11     10555921.64      3461918.89     10555727.62
      3461969.55     10555826.42      3462047.03     10555756.45
      3462161.40     10555836.34      3462297.07     10555566.25
      3462532.20     10555771.69      3462535.51     10555650.04
      3462720.41     10555668.79      3462712.08     10555431.76
      3462871.64     10555506.81      3463177.58     10555264.63
      3463125.78     10554979.69      3463227.02     10555012.21
      3463359.42     10554851.44      3463419.57     10554942.85
      3463438.25     10554804.32      3463587.81     10554894.03
      3463803.47     10554565.37      3464372.11     10554591.64

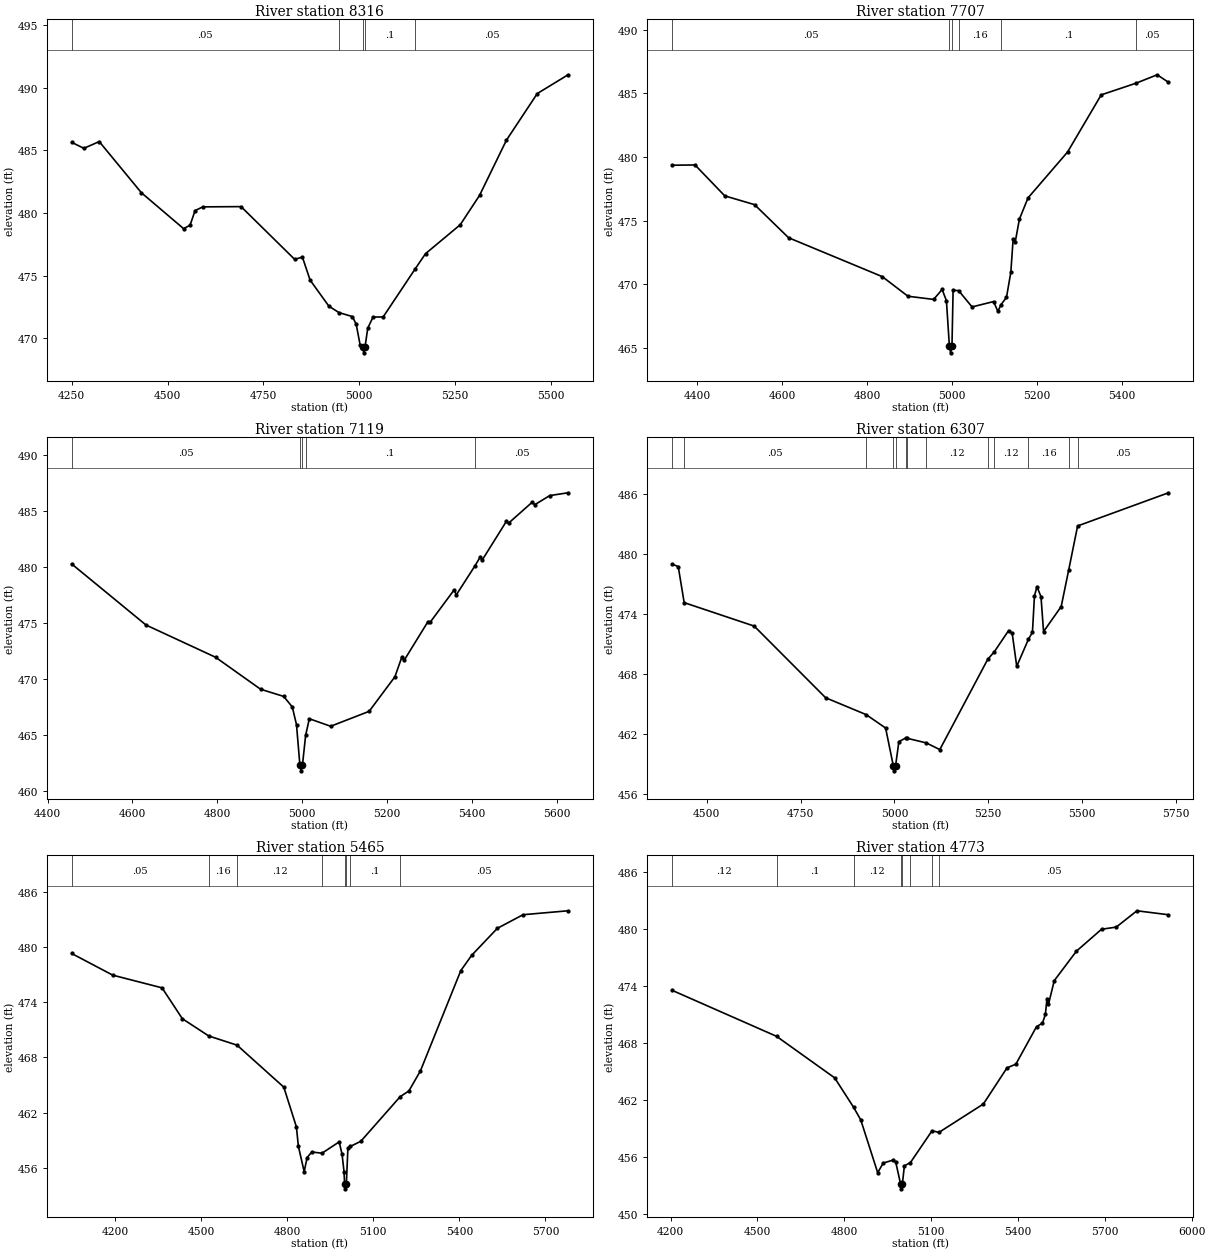
Type RM Length L Ch R = 1,8316,609,609,609
BEGIN DESCRIPTION:
UNT0062 IN CHRS 12.0
END DESCRIPTION:
XS GIS Cut Line= 3
      3459434.31     10556493.53      3459418.68     10555819.06
      3459353.57     10555201.83
#Sta/Elev= 30
  4249.9  485.65  4281.8  485.17  4321.8  485.71  4431.8  481.62  4541.9  478.75
  4558.8  479.02  4571.9  480.19  4591.9  480.49  4691.9  480.51  4831.9  476.29
  4851.9  476.48  4872.0  474.64  4920.8  472.56  4947.2  472.04  4982.3  471.72
  4992.3  471.11  5002.4  469.48  5009.5  469.32  5012.2  468.82  5015.5  469.32
  5022.5  470.79  5036.2  471.68  5062.7  471.69  5145.3  475.49  5173.3  476.75
  5263.8  479.06  5314.1  481.40  5384.5  485.83  5464.9  489.55  5545.2  491.05
#Mann=5,-1,0
  4249.9    0.05       0  4947.2     0.1       0  5009.5    0.07       0
  5015.5     0.1       0  5145.3    0.05       0
Bank Sta=5009.5,5015.5
Exp/Cntr=0.3,0.1

Type RM Length L Ch R = 1,7707,588,588,588
BEGIN DESCRIPTION:
UNT0062 IN CHRS 11.1
END DESCRIPTION:
XS GIS Cut Line= 4
      3460025.45     10556295.64      3460015.03     10555886.77
      3459981.18     10555582.08      3459908.47     10555135.43
#Sta/Elev= 30
  4340.7  479.36  4394.7  479.38  4464.7  476.95  4534.8  476.26  4614.8  473.66
  4835.4  470.60  4895.7  469.06  4956.1  468.81  4976.2  469.59  4986.3  468.71
  4993.3  465.11  4996.1  464.61  4999.3  465.11  5002.0  469.53  5015.0  469.50
  5046.6  468.22  5097.2  468.64  5107.4  467.87  5114.7  468.40  5127.6  468.97
  5137.8  470.94  5143.3  473.56  5148.4  473.36  5158.0  475.12  5178.3  476.79
  5271.4  480.40  5350.5  484.89  5432.6  485.81  5482.2  486.47  5508.8  485.88
#Mann=6,-1,0
  4340.7    0.05       0  4993.3   0.035       0  4999.3    0.05       0
  5015.0    0.16       0  5114.7     0.1       0  5432.6    0.05       0
Bank Sta=4993.3,4999.3
Exp/Cntr=0.3,0.1

Type RM Length L Ch R = 1,7119,812,812,812
BEGIN DESCRIPTION:
UNT0062 IN CHRS 11.0
END DESCRIPTION:
XS GIS Cut Line= 4
      3460491.60     10556290.39      3460481.18     10555881.56
      3460447.33     10555576.88      3460374.42     10555128.99
#Sta/Elev= 30
  4456.8  480.26  4631.9  474.82  4795.7  471.95  4901.8  469.10  4956.2  468.46
  4976.4  467.53  4986.4  465.94  4994.4  462.33  4997.1  461.83  5000.4  462.33
  5007.9  464.99  5016.6  466.47  5066.9  465.80  5157.5  467.13  5218.2  470.21
  5234.6  471.97  5239.7  471.66  5296.2  475.13  5301.2  475.06  5357.7  477.95
  5362.7  477.50  5406.6  480.08  5419.2  480.88  5424.2  480.63  5480.7  484.05
  5485.8  483.89  5542.2  485.78  5547.3  485.53  5582.9  486.35  5626.1  486.60
#Mann=5,-1,0
  4456.8    0.05       0  4994.4    0.03       0  5000.4    0.05       0
  5007.9     0.1       0  5406.6    0.05       0
Bank Sta=4994.4,5000.4
Exp/Cntr=0.3,0.1

Type RM Length L Ch R = 1,6307,842,842,842
BEGIN DESCRIPTION:
UNT0062 IN CHRS 10.0
END DESCRIPTION:
XS GIS Cut Line= 4
      3460952.52     10556352.96      3461080.14     10555933.65
      3460960.35     10555657.60      3460744.36     10555116.33
#Sta/Elev= 30
  4407.9  478.98  4424.3  478.74  4440.1  475.14  4626.6  472.80  4816.9  465.65
  4924.7  463.97  4976.6  462.63  4997.1  458.86  4999.8  458.36  5003.1  458.86
  5011.9  461.27  5031.2  461.66  5033.6  461.61  5084.7  461.15  5120.9  460.48
  5248.5  469.48  5266.1  470.24  5304.3  472.36  5313.7  472.08  5325.8  468.79
  5357.1  471.50  5367.6  472.18  5373.0  475.81  5379.6  476.74  5390.4  475.73
  5397.2  472.25  5444.2  474.75  5464.4  478.44  5487.9  482.79  5729.9  486.10
#Mann=13,-1,0
  4407.9    0.16       0  4440.1    0.05       0  4924.7     0.1       0
  4997.1    0.07       0  5003.1     0.1       0  5031.2    0.12       0
  5033.6    0.16       0  5084.7    0.12       0  5248.5    0.16       0
  5266.1    0.12       0  5357.1    0.16       0  5464.4    0.12       0
  5487.9    0.05       0
Bank Sta=4997.1,5003.1
Exp/Cntr=0.3,0.1

Type RM Length L Ch R = 1,5465,692,692,692
BEGIN DESCRIPTION:
UNT0062 IN CHRS 8.0
END DESCRIPTION:
XS GIS Cut Line= 5
      3461392.64     10556743.57      3461496.81     10556027.40
      3461561.91     10555665.42      3461499.41     10555118.54
      3461475.97     10555032.61
#Sta/Elev= 30
  4048.0  479.32  4191.4  476.96  4363.2  475.58  4433.9  472.22  4526.1  470.34
  4624.7  469.34  4787.7  464.77  4831.7  460.44  4838.5  458.34  4858.8  455.57
  4869.0  457.11  4885.3  457.71  4921.0  457.58  4980.8  458.81  4990.9  457.46
  4997.7  455.58  4999.8  454.20  5002.5  453.70  5005.8  454.20  5011.2  458.10
  5019.9  458.32  5056.4  458.88  5193.7  463.74  5223.8  464.35  5264.1  466.54
  5405.0  477.46  5443.1  479.13  5532.4  482.06  5621.8  483.54  5779.0  483.97
#Mann=8,-1,0
  4048.0    0.05       0  4526.1    0.16       0  4624.7    0.12       0
  4921.0    0.16       0  4999.8    0.07       0  5005.8    0.16       0
  5019.9     0.1       0  5193.7    0.05       0
Bank Sta=4999.8,5005.8
Exp/Cntr=0.3,0.1

Type RM Length L Ch R = 1,4773,703,703,703
BEGIN DESCRIPTION:
UNT0062 IN CHRS 6.0
END DESCRIPTION:
XS GIS Cut Line= 4
      3461918.68     10556621.11      3461978.58     10555891.98
      3462007.22     10555634.17      3461864.33     10554924.91
#Sta/Elev= 30
  4205.4  473.55  4566.1  468.70  4766.8  464.32  4832.2  461.22  4857.1  459.88
  4915.6  454.31  4934.6  455.33  4967.5  455.63  4977.6  455.47  4994.7  453.11
  4997.4  452.61  5000.7  453.11  5007.8  455.04  5028.6  455.38  5103.4  458.74
  5126.9  458.56  5280.6  461.56  5362.2  465.37  5392.8  465.76  5464.2  469.72
  5484.6  470.08  5494.8  471.02  5500.3  472.68  5505.4  472.07  5525.4  474.57
  5602.0  477.68  5688.6  479.99  5739.6  480.22  5811.0  481.94  5919.9  481.52
#Mann=8,-1,0
  4205.4    0.12       0  4566.1     0.1       0  4832.2    0.12       0
  4994.7    0.07       0  5000.7    0.12       0  5028.6    0.05       0
  5103.4    0.16       0  5126.9    0.05       0
Bank Sta=4994.7,5000.7
Exp/Cntr=0.3,0.1

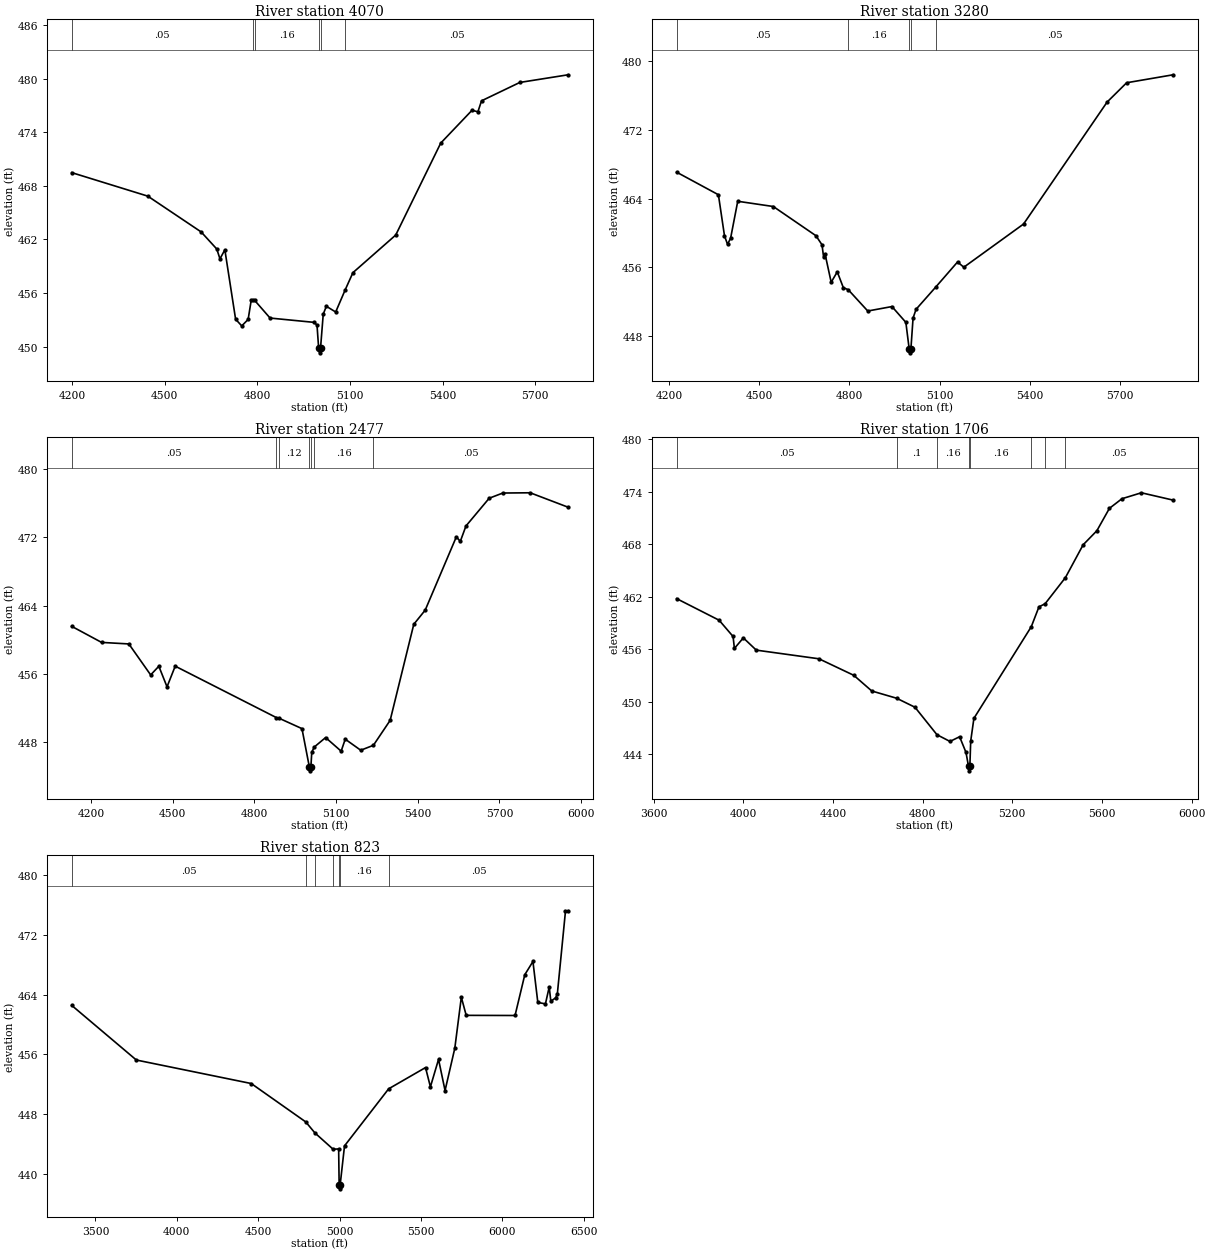
Type RM Length L Ch R = 1,4070,790,790,790
BEGIN DESCRIPTION:
UNT0062 IN CHRS 5.0
END DESCRIPTION:
XS GIS Cut Line= 4
      3462491.60     10556394.59      3462366.60     10555670.63
      3462343.16     10555496.15      3462179.10     10554819.07
#Sta/Elev= 30
  4199.5  469.50  4446.0  466.86  4618.6  462.85  4669.3  460.93  4679.5  459.83
  4695.4  460.84  4730.2  453.06  4750.1  452.31  4770.8  453.04  4780.9  455.23
  4785.6  455.22  4791.4  455.19  4841.8  453.19  4983.6  452.71  4993.7  452.42
  4999.1  449.79  5001.9  449.29  5005.1  449.79  5013.9  453.63  5024.0  454.51
  5054.2  453.87  5085.2  456.37  5110.0  458.28  5248.6  462.50  5394.3  472.81
  5495.6  476.49  5514.6  476.32  5526.4  477.55  5650.3  479.61  5806.9  480.47
#Mann=6,-1,0
  4199.5    0.05       0  4785.6    0.12       0  4791.4    0.16       0
  4999.1    0.07       0  5005.1    0.16       0  5085.2    0.05       0
Bank Sta=4999.1,5005.1
Exp/Cntr=0.3,0.1

Type RM Length L Ch R = 1,3280,803,803,803
BEGIN DESCRIPTION:
UNT0062 IN CHRS 4.0
END DESCRIPTION:
XS GIS Cut Line= 4
      3462882.21     10556248.71      3462765.03     10555584.69
      3462619.20     10555571.67      3462372.10     10554775.74
#Sta/Elev= 30
  4224.2  467.08  4363.4  464.45  4383.7  459.66  4393.8  458.68  4404.0  459.38
  4427.8  463.69  4546.3  463.08  4688.3  459.68  4708.6  458.62  4713.8  457.20
  4718.9  457.52  4739.1  454.26  4759.4  455.47  4779.7  453.62  4795.7  453.40
  4861.0  450.91  4941.6  451.43  4987.9  449.59  4998.8  446.54  5001.6  446.04
  5004.8  446.54  5011.9  450.09  5021.9  451.11  5087.2  453.69  5160.1  456.62
  5181.0  456.01  5380.0  461.04  5658.3  475.24  5723.4  477.49  5878.3  478.42
#Mann=5,-1,0
  4224.2    0.05       0  4795.7    0.16       0  4998.8    0.07       0
  5004.8    0.16       0  5087.2    0.05       0
Bank Sta=4998.8,5004.8
Exp/Cntr=0.3,0.1

Type RM Length L Ch R = 1,2477,771,771,771
BEGIN DESCRIPTION:
UNT0062 IN CHRS 3.0
END DESCRIPTION:
XS GIS Cut Line= 4
      3463262.43     10556061.24      3463296.28     10555420.63
      3462840.56     10555113.33      3462457.71     10554610.69
#Sta/Elev= 30
  4129.6  461.56  4239.4  459.67  4339.5  459.49  4419.6  455.85  4449.6  456.87
  4479.7  454.45  4509.7  456.88  4881.5  450.83  4889.0  450.79  4975.1  449.54
  5002.0  445.08  5004.8  444.58  5008.0  445.08  5011.1  446.76  5020.3  447.38
  5062.0  448.49  5119.0  446.89  5134.0  448.30  5190.9  447.00  5237.4  447.58
  5298.9  450.51  5385.7  461.80  5427.6  463.46  5541.9  472.07  5556.5  471.54
  5577.3  473.35  5662.6  476.61  5712.6  477.22  5813.1  477.25  5952.6  475.55
#Mann=7,-1,0
  4129.6    0.05       0  4881.5     0.1       0  4889.0    0.12       0
  5002.0    0.07       0  5008.0    0.12       0  5020.3    0.16       0
  5237.4    0.05       0
Bank Sta=5002,5008
Exp/Cntr=0.3,0.1

Type RM Length L Ch R = 1,1706,883,883,883
BEGIN DESCRIPTION:
UNT0062 IN CHRS 2.0
END DESCRIPTION:
XS GIS Cut Line= 4
      3463319.71     10556084.72      3463559.31     10555196.67
      3463218.16     10554790.42      3462499.38     10554529.99
#Sta/Elev= 30
  3702.6  461.78  3892.2  459.31  3954.4  457.45  3960.4  456.09  4000.3  457.29
  4057.9  455.89  4337.6  454.90  4493.0  453.01  4573.1  451.22  4684.0  450.39
  4765.9  449.36  4863.9  446.22  4922.0  445.45  4964.9  445.99  4993.5  444.19
  5004.7  442.59  5007.4  442.09  5010.7  442.59  5014.4  445.49  5028.7  448.09
  5284.7  458.57  5318.9  460.84  5346.2  461.19  5436.9  464.18  5515.9  467.93
  5577.2  469.54  5633.2  472.10  5689.1  473.20  5775.7  473.88  5917.4  473.04
#Mann=8,-1,0
  3702.6    0.05       0  4684.0     0.1       0  4863.9    0.16       0
  5004.7    0.07       0  5010.7    0.16       0  5284.7    0.05       0
  5346.2    0.16       0  5436.9    0.05       0
Bank Sta=5004.7,5010.7
Exp/Cntr=0.3,0.1

Type RM Length L Ch R = 1,823,0,0,0
BEGIN DESCRIPTION:
UNT0062 IN CHRS 1.0
END DESCRIPTION:
XS GIS Cut Line= 4
      3463369.20     10556128.96      3463908.26     10554983.13
      3463530.66     10554418.02      3462425.49     10554405.02
#Sta/Elev= 30
  3353.8  462.55  3751.2  455.22  4457.2  452.07  4792.4  446.92  4848.4  445.45
  4960.4  443.26  4994.4  443.30  4997.5  438.45  5000.2  437.95  5003.5  438.45
  5030.5  443.71  5301.7  451.36  5528.3  454.21  5558.3  451.62  5608.3  455.31
  5648.3  451.13  5708.3  456.81  5748.3  463.64  5778.3  461.21  6078.4  461.19
  6138.4  466.66  6188.4  468.43  6218.4  462.94  6265.2  462.75  6288.4  465.01
  6298.4  463.10  6328.4  463.57  6338.4  464.10  6388.4  475.19  6405.0  475.23
#Mann=7,-1,0
  3353.8    0.05       0  4792.4     0.1       0  4848.4    0.12       0
  4960.4    0.16       0  4997.5    0.07       0  5003.5    0.16       0
  5301.7    0.05       0
Bank Sta=4997.5,5003.5
Exp/Cntr=0.3,0.1

Chan Stop Cuts=-1