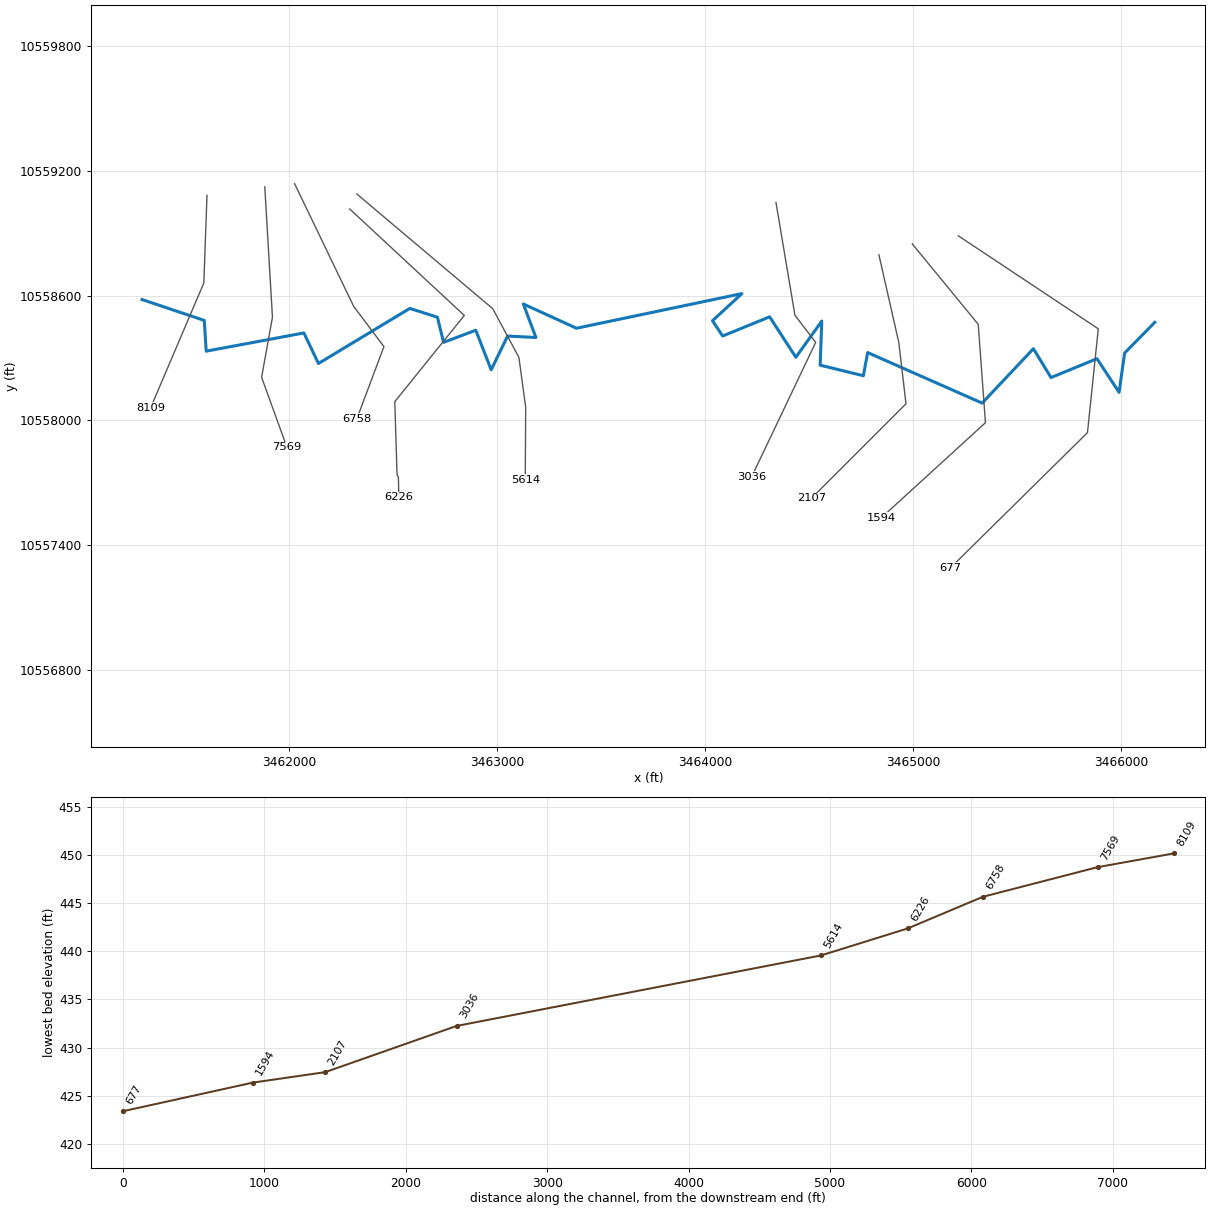
--- UNT0064 IN CHRS.prj (project) ---

Proj Title=UNT0064 IN CHRS Base Level Engineering
Current Plan=p01
Default Exp/Contr=0.3,0.1
English Units
Geom File=g01
Flow File=f01
Plan File=p01
BEGIN DESCRIPTION:
UNT0064 IN CHRS
END DESCRIPTION:

--- UNT0064 IN CHRS.p01 (plan) ---

Plan Title=Multiple Run
Short Identifier=Multiple
Geom File=g01
Flow File=f01
Subcritical Flow
K Sum by GR= 0
Std Step Tol= 0.01
Critical Tol= 0.01
Num of Std Step Trials= 20
Max Error Tol= 0.3
Flow Tol Ratio= 0.001
Split Flow NTrial= 30
Split Flow Tol= 0.02
Split Flow Ratio= 0.02
Log Output Level= 0
Friction Slope Method= 1
Unsteady Friction Slope Method= 2
Unsteady Bridges Friction Slope Method= 1
Parabolic Critical Depth
Global Vel Dist=  1 , 1 , 1
Global Log Level= 0
CheckData=True
Encroach Param= -1, 0, 0, 0
BEGIN DESCRIPTION:
Multiple Run
END DESCRIPTION:

--- UNT0064 IN CHRS.f01 (steady flow) ---

Flow Title=Multiple
Number of Profiles=7
Profile Names=10-year,25-year,50-year,1pct_min,100-year,1pct_plu,500-year
River Rch & RM= UNT0064 IN CHRS,Reach-1,8109
     423     532     612     513     694     938     889
River Rch & RM= UNT0064 IN CHRS,Reach-1,3036
     448     563     648     543     735     994     941
Boundary for River Rch & Prof#=UNT0064 IN CHRS,Reach-1,1
Up Type=0
Dn Type=3
Dn Slope=0.005
Boundary for River Rch & Prof#=UNT0064 IN CHRS,Reach-1,2
Up Type=0
Dn Type=3
Dn Slope=0.005
Boundary for River Rch & Prof#=UNT0064 IN CHRS,Reach-1,3
Up Type=0
Dn Type=3
Dn Slope=0.005
Boundary for River Rch & Prof#=UNT0064 IN CHRS,Reach-1,4
Up Type=0
Dn Type=3
Dn Slope=0.005
Boundary for River Rch & Prof#=UNT0064 IN CHRS,Reach-1,5
Up Type=0
Dn Type=3
Dn Slope=0.005
Boundary for River Rch & Prof#=UNT0064 IN CHRS,Reach-1,6
Up Type=0
Dn Type=3
Dn Slope=0.005
Boundary for River Rch & Prof#=UNT0064 IN CHRS,Reach-1,7
Up Type=0
Dn Type=3
Dn Slope=0.005

--- UNT0064 IN CHRS.g01 (geometry) ---

Geom Title=Existing Conditions

River Reach=UNT0064 IN CHRS,Reach-1
Reach XY= 30
      3461293.67     10558581.16      3461592.67     10558481.01
      3461602.08     10558333.15      3462071.76     10558420.66
      3462141.62     10558273.83      3462580.91     10558538.64
      3462713.48     10558496.35      3462743.38     10558375.50
      3462897.88     10558433.80      3462972.07     10558243.41
      3463050.92     10558405.76      3463187.03     10558398.88
      3463126.51     10558559.99      3463381.87     10558443.32
      3464177.09     10558609.73      3464036.00     10558479.39
      3464084.67     10558406.03      3464310.61     10558498.15
      3464436.68     10558303.89      3464561.25     10558477.48
      3464553.58     10558265.83      3464761.12     10558215.00
      3464781.90     10558326.33      3465332.23     10558083.36
      3465578.62     10558344.98      3465663.27     10558206.20
      3465884.40     10558296.92      3465990.54     10558135.18
      3466017.00     10558323.97      3466162.11     10558471.64

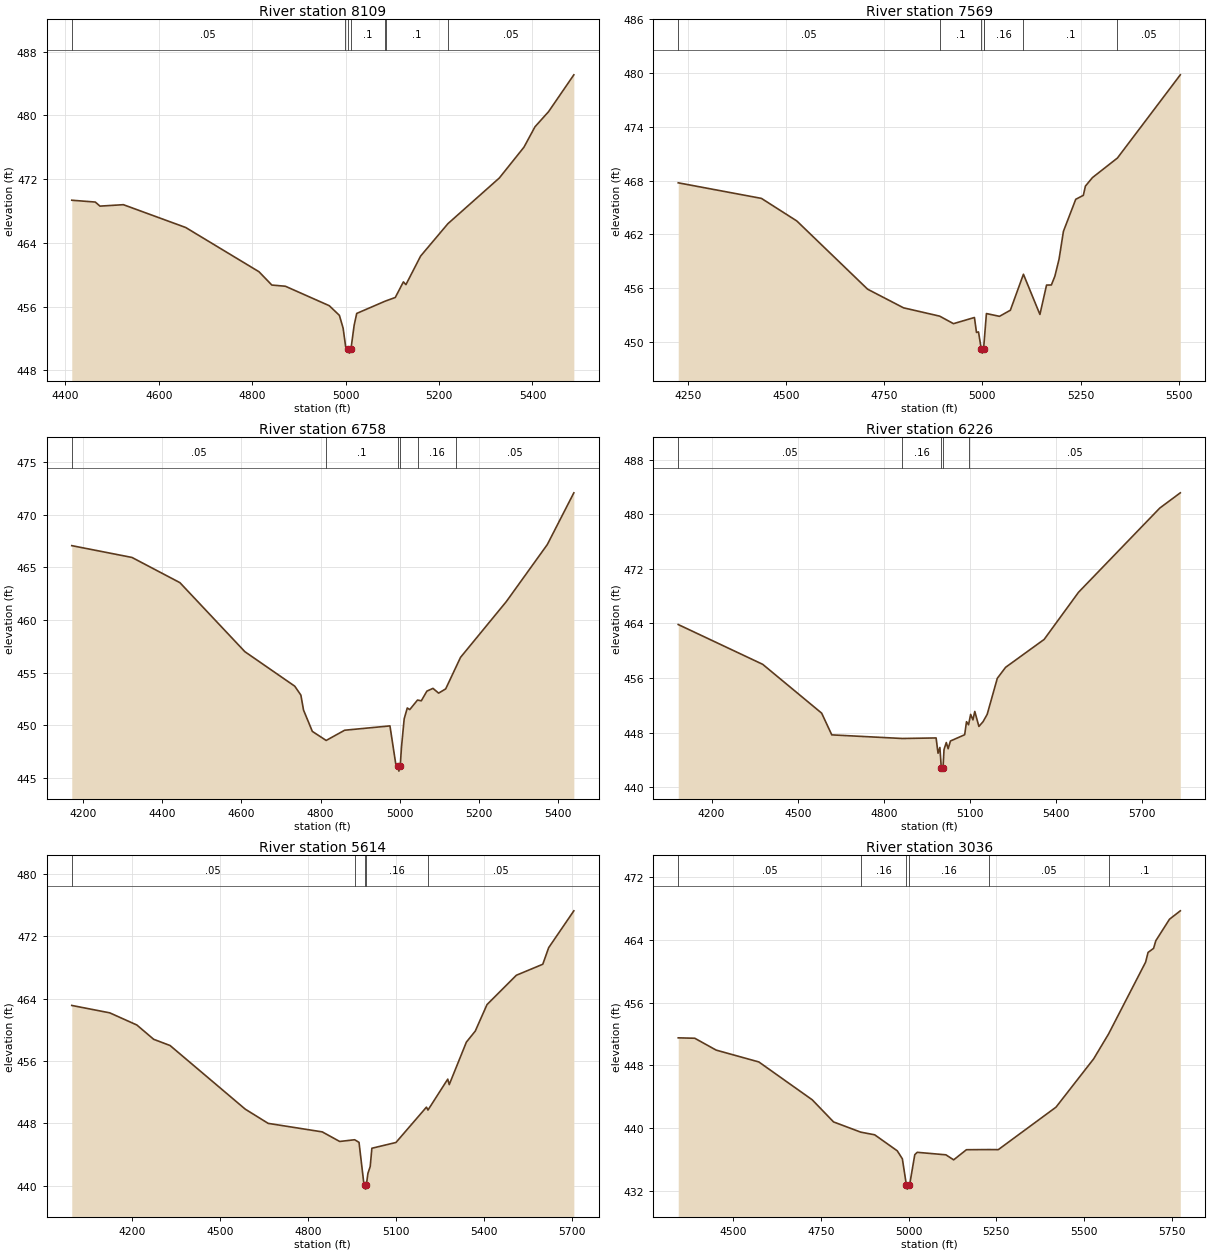
Type RM Length L Ch R = 1,8109,540,540,540
BEGIN DESCRIPTION:
UNT0064 IN CHRS 4.0
END DESCRIPTION:
XS GIS Cut Line= 3
      3461605.83     10559082.04      3461590.65     10558661.07
      3461334.58     10558059.98
#Sta/Elev= 30
  4413.9  469.35  4464.3  469.12  4474.3  468.61  4524.4  468.79  4657.7  465.93
  4814.6  460.38  4842.1  458.71  4871.1  458.56  4965.0  456.12  4986.7  454.91
  4994.7  453.30  4998.1  451.84  5000.1  450.98  5005.4  450.67  5008.2  450.17
  5011.4  450.67  5018.3  453.67  5023.8  455.15  5083.5  456.66  5086.6  456.73
  5106.3  457.15  5123.7  459.11  5129.1  458.76  5160.6  462.35  5219.0  466.41
  5329.0  472.14  5381.7  476.00  5405.3  478.56  5434.4  480.46  5488.5  485.08
#Mann=7,-1,0
  4413.9    0.05       0  4998.1     0.1       0  5005.4    0.07       0
  5011.4     0.1       0  5083.5    0.16       0  5086.6     0.1       0
  5219.0    0.05       0
Bank Sta=5005.4,5011.4
Exp/Cntr=0.3,0.1

Type RM Length L Ch R = 1,7569,811,811,811
BEGIN DESCRIPTION:
UNT0064 IN CHRS 3.0
END DESCRIPTION:
XS GIS Cut Line= 4
      3461883.62     10559123.27      3461920.51     10558496.14
      3461868.42     10558207.51      3461989.97     10557871.10
#Sta/Elev= 30
  4225.1  467.76  4437.1  466.02  4527.2  463.50  4707.6  455.88  4799.1  453.80
  4891.2  452.87  4926.4  452.03  4979.8  452.72  4985.0  451.05  4990.1  451.11
  4997.1  449.24  4999.9  448.74  5003.1  449.24  5004.2  449.84  5010.3  453.16
  5043.6  452.85  5071.3  453.53  5104.6  457.55  5146.6  453.06  5163.5  456.34
  5175.8  456.35  5184.7  457.33  5195.4  459.24  5206.5  462.34  5237.9  465.92
  5257.2  466.36  5262.5  467.39  5280.4  468.34  5344.1  470.53  5504.3  479.82
#Mann=7,-1,0
  4225.1    0.05       0  4891.2     0.1       0  4997.1    0.07       0
  5003.1     0.1       0  5004.2    0.16       0  5104.6     0.1       0
  5344.1    0.05       0
Bank Sta=4997.1,5003.1
Exp/Cntr=0.3,0.1

Type RM Length L Ch R = 1,6758,532,532,532
BEGIN DESCRIPTION:
UNT0064 IN CHRS 3.1
END DESCRIPTION:
XS GIS Cut Line= 4
      3462026.86     10559138.47      3462311.13     10558548.22
      3462456.53     10558355.08      3462326.72     10558008.91
#Sta/Elev= 30
  4172.3  467.05  4324.2  465.93  4445.1  463.54  4609.0  456.99  4734.8  453.72
  4750.3  452.87  4757.0  451.45  4779.2  449.43  4814.1  448.57  4860.7  449.54
  4975.0  449.95  4989.6  446.35  4994.9  446.16  4997.6  445.66  5000.9  446.16
  5004.1  447.94  5010.9  450.62  5018.7  451.65  5025.0  451.50  5044.5  452.40
  5054.1  452.33  5068.2  453.25  5083.5  453.51  5097.8  453.06  5115.6  453.46
  5141.9  455.56  5153.0  456.45  5268.7  461.75  5371.9  467.15  5438.9  472.06
#Mann=6,-1,0
  4172.3    0.05       0  4814.1     0.1       0  4994.9    0.07       0
  5000.9     0.1       0  5044.5    0.16       0  5141.9    0.05       0
Bank Sta=4994.9,5000.9
Exp/Cntr=0.3,0.1

Type RM Length L Ch R = 1,6226,612,612,612
BEGIN DESCRIPTION:
UNT0064 IN CHRS 2.0
END DESCRIPTION:
XS GIS Cut Line= 6
      3462291.61     10559016.97      3462842.82     10558504.82
      3462508.61     10558090.32      3462519.46     10557738.76
      3462525.98     10557727.91      3462528.15     10557630.22
#Sta/Elev= 30
  4084.1  463.84  4378.3  458.01  4583.5  450.86  4618.7  447.68  4864.1  447.15
  4981.9  447.23  4988.7  444.99  4995.1  445.84  5000.0  442.87  5002.8  442.37
  5006.0  442.87  5009.5  445.53  5017.4  446.56  5023.9  445.65  5031.8  446.78
  5081.4  447.70  5087.8  449.61  5094.9  449.16  5102.2  450.68  5110.2  449.88
  5116.6  451.11  5131.0  448.92  5145.4  449.61  5159.8  450.69  5195.0  455.96
  5223.8  457.57  5358.1  461.66  5477.7  468.56  5760.8  480.90  5832.2  483.13
#Mann=5,-1,0
  4084.1    0.05       0  4864.1    0.16       0  5000.0    0.07       0
  5006.0    0.16       0  5094.9    0.05       0
Bank Sta=5000,5006
Exp/Cntr=0.3,0.1

Type RM Length L Ch R = 1,5614,2578,2578,2578
BEGIN DESCRIPTION:
UNT0064 IN CHRS 1.1
END DESCRIPTION:
XS GIS Cut Line= 5
      3462326.34     10559088.57      3462979.53     10558537.37
      3463105.40     10558303.00      3463137.95     10558062.11
      3463135.79     10557715.81
#Sta/Elev= 30
  3995.2  463.12  4124.6  462.17  4217.0  460.61  4274.1  458.78  4330.1  457.98
  4586.2  449.82  4664.2  448.00  4848.3  446.91  4907.8  445.68  4958.7  445.90
  4973.6  445.57  4989.8  440.36  4992.5  440.07  4995.2  439.57  4998.5  440.07
  5003.9  441.59  5011.7  442.47  5017.4  444.81  5099.4  445.55  5203.2  450.08
  5208.5  449.71  5275.8  453.67  5280.9  452.97  5339.3  458.42  5369.5  459.83
  5409.5  463.23  5509.5  466.99  5599.5  468.40  5619.5  470.52  5705.3  475.25
#Mann=5,-1,0
  3995.2    0.05       0  4958.7    0.16       0  4992.5    0.07       0
  4998.5    0.16       0  5208.5    0.05       0
Bank Sta=4992.5,4998.5
Exp/Cntr=0.3,0.1

Type RM Length L Ch R = 1,3036,929,929,929
BEGIN DESCRIPTION:
UNT0064 IN CHRS 5.0
END DESCRIPTION:
XS GIS Cut Line= 4
      3464341.12     10559048.12      3464432.26     10558505.59
      3464532.09     10558375.38      3464223.92     10557728.66
#Sta/Elev= 30
  4343.8  451.51  4390.9  451.46  4451.8  449.95  4573.5  448.44  4725.6  443.62
  4786.4  440.80  4863.7  439.50  4903.6  439.16  4967.9  437.12  4982.4  436.10
  4994.0  432.74  4996.7  432.24  5000.0  432.74  5003.3  432.83  5017.8  436.63
  5024.9  436.93  5106.5  436.61  5128.6  435.97  5165.0  437.26  5230.3  437.28
  5255.8  437.27  5420.2  442.68  5527.4  448.83  5569.9  452.00  5675.5  461.15
  5682.5  462.39  5698.2  462.91  5704.6  463.88  5743.6  466.62  5774.4  467.69
#Mann=6,-1,0
  4343.8    0.05       0  4863.7    0.16       0  4994.0    0.07       0
  5000.0    0.16       0  5230.3    0.05       0  5569.9     0.1       0
Bank Sta=4994,5000
Exp/Cntr=0.3,0.1

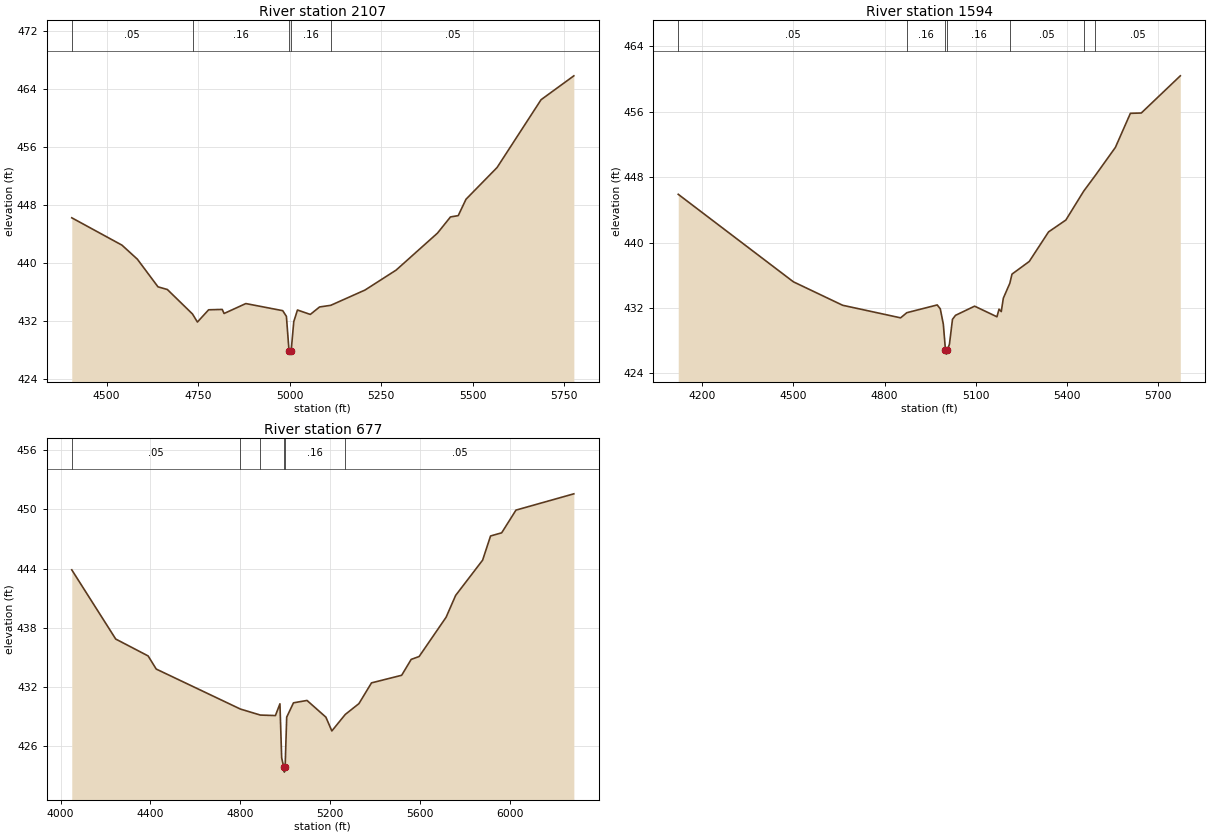
Type RM Length L Ch R = 1,2107,513,513,513
BEGIN DESCRIPTION:
UNT0064 IN CHRS 4.1
END DESCRIPTION:
XS GIS Cut Line= 4
      3464835.91     10558796.39      3464931.40     10558375.38
      3464966.12     10558080.24      3464511.43     10557625.56
#Sta/Elev= 30
  4404.8  446.26  4541.8  442.49  4584.0  440.55  4640.4  436.73  4666.0  436.36
  4734.7  432.98  4748.1  431.87  4778.8  433.56  4815.9  433.61  4821.0  433.05
  4880.4  434.42  4981.2  433.44  4991.3  432.65  4998.4  427.94  5001.1  427.44
  5004.4  427.94  5011.4  431.92  5021.5  433.53  5056.6  432.92  5081.9  433.95
  5112.6  434.18  5206.2  436.29  5291.1  439.04  5404.2  444.15  5439.6  446.38
  5460.8  446.56  5482.0  448.82  5566.9  453.20  5687.1  462.56  5776.7  465.86
#Mann=5,-1,0
  4404.8    0.05       0  4734.7    0.16       0  4998.4    0.07       0
  5004.4    0.16       0  5112.6    0.05       0
Bank Sta=4998.4,5004.4
Exp/Cntr=0.3,0.1

Type RM Length L Ch R = 1,1594,917,917,917
BEGIN DESCRIPTION:
UNT0064 IN CHRS 2.1
END DESCRIPTION:
XS GIS Cut Line= 4
      3464996.53     10558848.44      3465313.34     10558462.19
      3465348.06     10557989.10      3464848.94     10557533.38
#Sta/Elev= 30
  4122.2  445.91  4500.6  435.20  4662.4  432.33  4852.9  430.79  4873.3  431.42
  4973.2  432.37  4983.3  431.89  4993.3  430.01  5000.3  426.85  5003.1  426.35
  5006.3  426.85  5013.4  427.57  5023.4  430.61  5033.4  431.10  5096.1  432.22
  5169.5  430.92  5176.3  431.85  5183.7  431.56  5190.5  433.20  5211.8  435.02
  5218.9  436.14  5275.6  437.69  5339.1  441.31  5395.9  442.76  5454.4  446.29
  5492.6  448.21  5558.7  451.65  5608.0  455.82  5643.8  455.86  5772.0  460.41
#Mann=7,-1,0
  4122.2    0.05       0  4873.3    0.16       0  5000.3    0.07       0
  5006.3    0.16       0  5211.8    0.05       0  5454.4     0.1       0
  5492.6    0.05       0
Bank Sta=5000.3,5006.3
Exp/Cntr=0.3,0.1

Type RM Length L Ch R = 1,677,0,0,0
BEGIN DESCRIPTION:
UNT0064 IN CHRS 1.0
END DESCRIPTION:
XS GIS Cut Line= 4
      3465217.82     10558887.56      3465890.60     10558440.49
      3465838.51     10557941.36      3465178.78     10557290.30
#Sta/Elev= 30
  4049.4  443.87  4245.2  436.86  4389.5  435.15  4425.6  433.82  4800.4  429.77
  4889.3  429.16  4956.6  429.11  4976.7  430.30  4984.4  424.82  4993.8  423.88
  4996.5  423.38  4999.8  423.88  5006.8  428.95  5037.0  430.40  5097.3  430.64
  5181.3  428.95  5207.9  427.55  5267.6  429.22  5328.6  430.32  5384.5  432.42
  5518.9  433.19  5561.4  434.80  5596.7  435.09  5716.9  439.07  5759.4  441.28
  5879.5  444.85  5914.9  447.30  5964.4  447.62  6028.1  449.92  6285.9  451.57
#Mann=6,-1,0
  4049.4    0.05       0  4800.4     0.1       0  4889.3    0.16       0
  4993.8    0.07       0  4999.8    0.16       0  5267.6    0.05       0
Bank Sta=4993.8,4999.8
Exp/Cntr=0.3,0.1

Chan Stop Cuts=-1