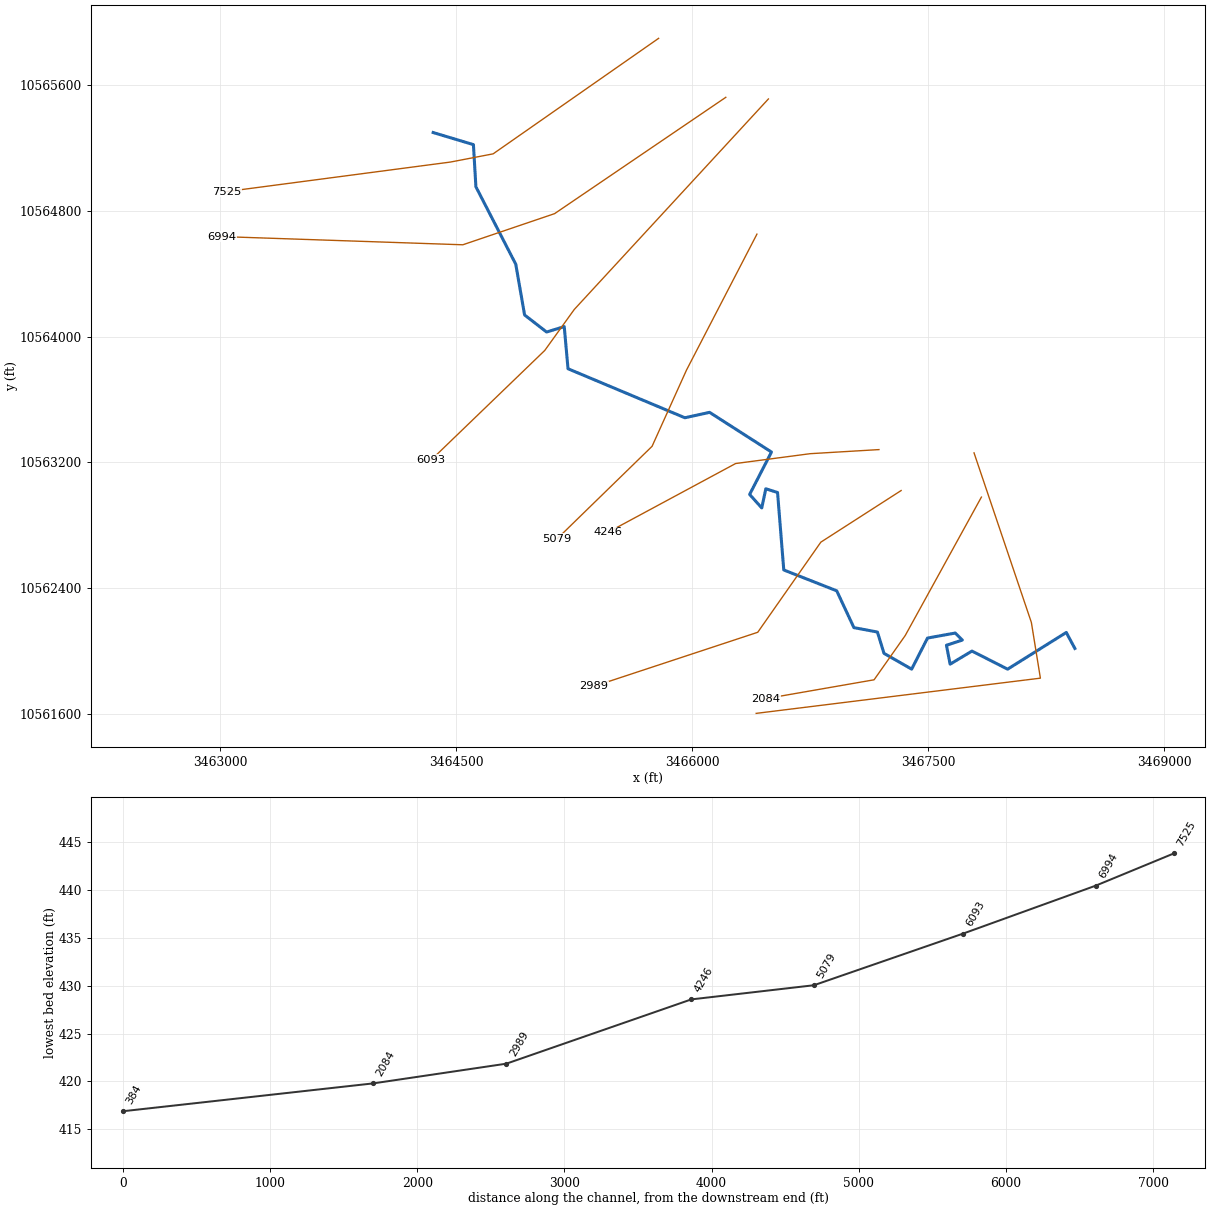
--- UNT0065 IN CHRS.prj (project) ---

Proj Title=UNT0065 IN CHRS Base Level Engineering
Current Plan=p01
Default Exp/Contr=0.3,0.1
English Units
Geom File=g01
Flow File=f01
Plan File=p01
BEGIN DESCRIPTION:
UNT0065 IN CHRS
END DESCRIPTION:

--- UNT0065 IN CHRS.p01 (plan) ---

Plan Title=Multiple Run
Short Identifier=Multiple
Geom File=g01
Flow File=f01
Subcritical Flow
K Sum by GR= 0
Std Step Tol= 0.01
Critical Tol= 0.01
Num of Std Step Trials= 20
Max Error Tol= 0.3
Flow Tol Ratio= 0.001
Split Flow NTrial= 30
Split Flow Tol= 0.02
Split Flow Ratio= 0.02
Log Output Level= 0
Friction Slope Method= 1
Unsteady Friction Slope Method= 2
Unsteady Bridges Friction Slope Method= 1
Parabolic Critical Depth
Global Vel Dist=  1 , 1 , 1
Global Log Level= 0
CheckData=True
Encroach Param= -1, 0, 0, 0
BEGIN DESCRIPTION:
Multiple Run
END DESCRIPTION:

--- UNT0065 IN CHRS.f01 (steady flow) ---

Flow Title=Multiple
Number of Profiles=7
Profile Names=10-year,25-year,50-year,1pct_min,100-year,1pct_plu,500-year
River Rch & RM= UNT0065 IN CHRS,Reach-1,7525
     522     665     772     652     882    1193    1149
River Rch & RM= UNT0065 IN CHRS,Reach-1,4246
     567     724     841     711     961    1300    1252
Boundary for River Rch & Prof#=UNT0065 IN CHRS,Reach-1,1
Up Type=0
Dn Type=3
Dn Slope=0.005
Boundary for River Rch & Prof#=UNT0065 IN CHRS,Reach-1,2
Up Type=0
Dn Type=3
Dn Slope=0.005
Boundary for River Rch & Prof#=UNT0065 IN CHRS,Reach-1,3
Up Type=0
Dn Type=3
Dn Slope=0.005
Boundary for River Rch & Prof#=UNT0065 IN CHRS,Reach-1,4
Up Type=0
Dn Type=3
Dn Slope=0.005
Boundary for River Rch & Prof#=UNT0065 IN CHRS,Reach-1,5
Up Type=0
Dn Type=3
Dn Slope=0.005
Boundary for River Rch & Prof#=UNT0065 IN CHRS,Reach-1,6
Up Type=0
Dn Type=3
Dn Slope=0.005
Boundary for River Rch & Prof#=UNT0065 IN CHRS,Reach-1,7
Up Type=0
Dn Type=3
Dn Slope=0.005

--- UNT0065 IN CHRS.g01 (geometry) ---

Geom Title=Existing Conditions

River Reach=UNT0065 IN CHRS,Reach-1
Reach XY= 30
      3464353.17     10565297.49      3464609.10     10565220.65
      3464624.76     10564952.87      3464878.29     10564460.16
      3464934.38     10564137.74      3465074.30     10564029.23
      3465186.42     10564063.64      3465210.41     10563795.84
      3465953.31     10563484.18      3466110.52     10563518.59
      3466503.90     10563266.27      3466365.11     10562996.72
      3466442.16     10562910.92      3466468.00     10563032.69
      3466542.52     10563008.91      3466582.14     10562516.54
      3466918.63     10562384.08      3467028.05     10562150.01
      3467177.39     10562122.04      3467219.31     10561986.39
      3467395.18     10561886.08      3467495.99     10562083.66
      3467672.25     10562115.54      3467717.39     10562070.83
      3467616.26     10562037.85      3467639.69     10561917.62
      3467778.58     10562000.96      3468005.15     10561885.94
      3468378.09     10562119.25      3468432.79     10562017.66

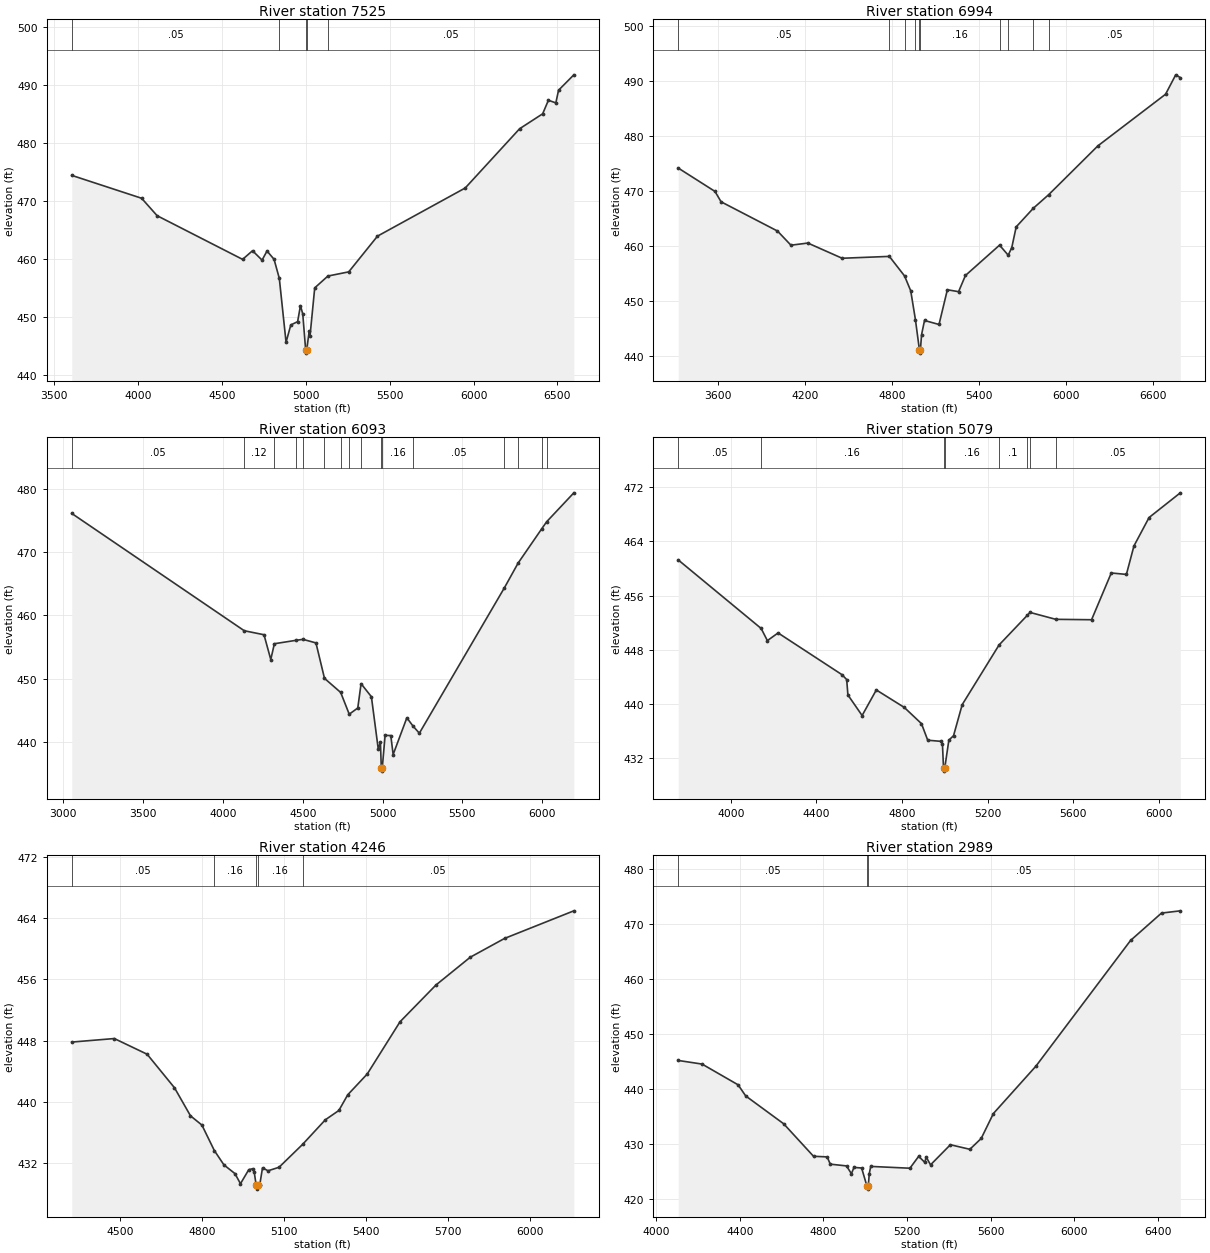
Type RM Length L Ch R = 1,7525,531,531,531
BEGIN DESCRIPTION:
UNT0065 IN CHRS 11.0
END DESCRIPTION:
XS GIS Cut Line= 4
      3465786.46     10565896.42      3464734.39     10565162.06
      3464463.56     10565109.97      3463041.68     10564922.48
#Sta/Elev= 30
  3604.6  474.43  4021.0  470.49  4113.4  467.49  4622.9  459.97  4682.2  461.46
  4738.9  459.84  4768.5  461.41  4810.4  459.99  4841.8  456.70  4882.0  445.70
  4910.3  448.68  4951.0  449.25  4967.8  452.00  4981.6  450.58  4999.0  444.33
  5001.7  443.83  5005.0  444.33  5019.7  447.58  5024.8  446.77  5052.9  455.06
  5131.5  457.10  5255.7  457.82  5427.1  463.97  5950.2  472.26  6274.4  482.46
  6411.7  485.03  6445.9  487.36  6490.3  486.91  6506.4  489.09  6597.6  491.74
#Mann=5,-1,0
  3604.6    0.05       0  4841.8    0.16       0  4999.0    0.07       0
  5005.0    0.16       0  5131.5    0.05       0
Bank Sta=4999,5005
Exp/Cntr=0.3,0.1

Type RM Length L Ch R = 1,6994,901,901,901
BEGIN DESCRIPTION:
UNT0065 IN CHRS 10.0
END DESCRIPTION:
XS GIS Cut Line= 4
      3466213.56     10565521.43      3465125.02     10564781.85
      3464541.68     10564583.93      3463010.38     10564636.02
#Sta/Elev= 30
  3326.9  474.19  3580.5  469.93  3622.5  468.04  4011.7  462.71  4104.5  460.13
  4221.2  460.52  4457.8  457.75  4783.5  458.09  4888.6  454.52  4931.1  451.81
  4963.5  446.55  4991.5  440.96  4994.2  440.46  4997.5  440.96  5005.9  443.84
  5026.2  446.41  5126.2  445.68  5183.8  452.01  5261.2  451.66  5308.5  454.61
  5543.9  460.14  5603.6  458.31  5628.2  459.69  5658.7  463.47  5776.8  466.86
  5883.8  469.36  6222.6  478.24  6689.3  487.64  6759.4  491.18  6791.1  490.67
#Mann=10,-1,0
  3326.9    0.05       0  4783.5    0.16       0  4888.6    0.12       0
  4963.5    0.16       0  4991.5    0.07       0  4997.5    0.16       0
  5543.9    0.12       0  5603.6    0.05       0  5776.8    0.12       0
  5883.8    0.05       0
Bank Sta=4991.5,4997.5
Exp/Cntr=0.3,0.1

Type RM Length L Ch R = 1,6093,1014,1014,1014
BEGIN DESCRIPTION:
UNT0065 IN CHRS 8.0
END DESCRIPTION:
XS GIS Cut Line= 4
      3466484.37     10565511.00      3465250.02     10564172.47
      3465062.52     10563912.06      3464339.83     10563215.37
#Sta/Elev= 30
  3053.1  476.09  4133.8  457.59  4257.4  456.96  4299.9  453.05  4322.3  455.54
  4460.8  456.09  4501.8  456.23  4582.9  455.67  4636.4  450.08  4737.8  447.86
  4791.4  444.43  4844.9  445.40  4865.6  449.24  4930.3  447.18  4973.5  438.88
  4986.8  440.08  4992.3  435.95  4995.1  435.45  4998.3  435.95  5016.2  441.09
  5051.8  441.06  5066.5  438.07  5152.4  443.86  5190.5  442.57  5230.7  441.43
  5763.7  464.37  5849.2  468.25  5996.6  473.64  6028.3  474.78  6198.6  479.34
#Mann=16,-1,0
  3053.1    0.05       0  4133.8    0.12       0  4322.3    0.16       0
  4460.8    0.12       0  4501.8    0.16       0  4636.4    0.12       0
  4737.8    0.16       0  4791.4    0.12       0  4865.6    0.16       0
  4992.3    0.07       0  4998.3    0.16       0  5190.5    0.05       0
  5763.7     0.1       0  5849.2    0.12       0  5996.6     0.1       0
  6028.3    0.16       0
Bank Sta=4992.3,4998.3
Exp/Cntr=0.3,0.1

Type RM Length L Ch R = 1,5079,833,833,833
BEGIN DESCRIPTION:
UNT0065 IN CHRS 6.0
END DESCRIPTION:
XS GIS Cut Line= 4
      3466411.49     10564651.66      3465963.56     10563787.06
      3465744.81     10563302.68      3465141.91     10562715.38
#Sta/Elev= 30
  3754.2  461.27  4141.8  451.14  4170.9  449.34  4220.9  450.48  4519.5  444.31
  4541.6  443.59  4547.3  441.31  4613.7  438.27  4680.1  442.05  4810.7  439.47
  4891.2  437.07  4920.4  434.62  4983.7  434.45  4989.2  434.07  4994.2  430.55
  4997.0  430.05  5000.2  430.55  5019.2  434.63  5041.1  435.29  5081.6  439.88
  5253.9  448.70  5386.1  453.09  5398.6  453.51  5519.0  452.49  5686.3  452.43
  5778.4  459.34  5849.1  459.13  5884.4  463.34  5955.1  467.54  6101.1  471.19
#Mann=8,-1,0
  3754.2    0.05       0  4141.8    0.16       0  4994.2    0.07       0
  5000.2    0.16       0  5253.9     0.1       0  5386.1    0.16       0
  5398.6    0.12       0  5519.0    0.05       0
Bank Sta=4994.2,5000.2
Exp/Cntr=0.3,0.1

Type RM Length L Ch R = 1,4246,1257,1257,1257
BEGIN DESCRIPTION:
UNT0065 IN CHRS 4.0
END DESCRIPTION:
XS GIS Cut Line= 4
      3467187.51     10563281.85      3466750.02     10563255.81
      3466276.06     10563193.31      3465464.29     10562756.20
#Sta/Elev= 30
  4322.1  447.81  4477.8  448.27  4598.0  446.22  4698.2  441.83  4756.8  438.16
  4798.6  436.95  4844.2  433.61  4879.3  431.74  4919.6  430.60  4939.8  429.28
  4970.1  431.11  4984.3  431.24  4990.3  430.77  4997.3  429.07  5000.1  428.57
  5003.3  429.07  5010.4  429.14  5020.5  431.36  5040.7  430.97  5081.0  431.43
  5167.1  434.42  5250.5  437.64  5300.0  438.86  5332.5  440.91  5403.9  443.63
  5523.9  450.46  5655.4  455.27  5781.1  458.91  5906.8  461.37  6160.4  464.98
#Mann=5,-1,0
  4322.1    0.05       0  4844.2    0.16       0  4997.3    0.07       0
  5003.3    0.16       0  5167.1    0.05       0
Bank Sta=4997.3,5003.3
Exp/Cntr=0.3,0.1

Type RM Length L Ch R = 1,2989,905,905,905
BEGIN DESCRIPTION:
UNT0065 IN CHRS 3.0
END DESCRIPTION:
XS GIS Cut Line= 4
      3467328.17     10563021.45      3466817.72     10562693.31
      3466416.68     10562120.39      3465376.04     10561776.98
#Sta/Elev= 30
  4105.1  445.24  4219.2  444.58  4391.5  440.81  4427.9  438.79  4609.5  433.73
  4752.3  427.82  4817.7  427.71  4832.5  426.39  4910.1  426.07  4933.6  424.65
  4945.9  425.80  4982.5  425.69  5008.2  422.35  5011.0  421.85  5014.2  422.35
  5019.1  424.68  5026.1  425.98  5213.5  425.65  5255.4  427.81  5285.0  426.70
  5291.1  427.71  5312.1  426.26  5407.1  429.92  5500.3  429.09  5554.5  431.06
  5612.8  435.59  5816.2  444.20  6269.0  467.05  6417.1  472.03  6507.1  472.44
#Mann=3,-1,0
  4105.1    0.05       0  5008.2    0.03       0  5014.2    0.05       0
Bank Sta=5008.2,5014.2
Exp/Cntr=0.3,0.1

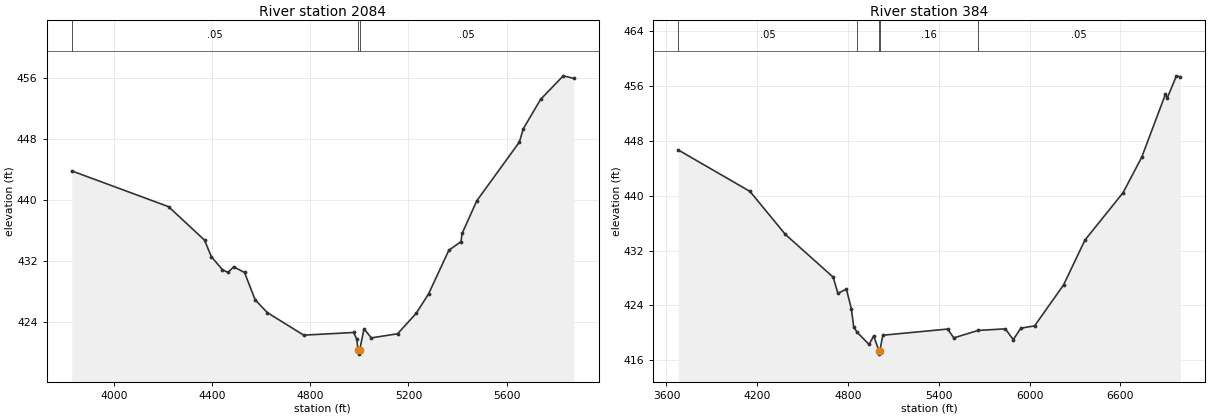
Type RM Length L Ch R = 1,2084,1700,1700,1700
BEGIN DESCRIPTION:
UNT0065 IN CHRS 2.0
END DESCRIPTION:
XS GIS Cut Line= 4
      3467838.57     10562979.80      3467354.18     10562099.56
      3467156.27     10561818.31      3466468.75     10561698.51
#Sta/Elev= 30
  3827.5  443.82  4221.9  439.13  4368.7  434.74  4396.2  432.58  4441.8  430.86
  4464.6  430.50  4487.4  431.24  4531.6  430.50  4575.1  426.91  4624.4  425.24
  4772.8  422.28  4976.4  422.63  4989.1  421.74  4994.8  420.29  4997.6  419.79
  5000.8  420.29  5018.7  423.11  5048.3  421.92  5155.5  422.46  5231.1  425.13
  5281.9  427.69  5364.4  433.41  5413.8  434.54  5418.9  435.64  5478.4  439.90
  5652.1  447.61  5667.6  449.33  5738.6  453.21  5830.9  456.29  5874.0  455.95
#Mann=3,-1,0
  3827.5    0.05       0  4994.8   0.035       0  5000.8    0.05       0
Bank Sta=4994.8,5000.8
Exp/Cntr=0.3,0.1

Type RM Length L Ch R = 1,384,0,0,0
BEGIN DESCRIPTION:
UNT0065 IN CHRS 1.0
END DESCRIPTION:
XS GIS Cut Line= 4
      3467791.67     10563261.05      3468156.27     10562182.89
      3468213.56     10561828.72      3466406.68     10561604.82
#Sta/Elev= 30
  3678.0  446.69  4152.4  440.63  4385.8  434.36  4701.3  428.13  4733.0  425.76
  4789.3  426.36  4821.9  423.49  4837.7  420.85  4858.7  420.11  4939.0  418.29
  4969.4  419.54  5004.0  417.38  5006.8  416.88  5010.0  417.38  5030.1  419.64
  5458.5  420.54  5498.8  419.25  5659.2  420.34  5839.4  420.57  5891.8  419.00
  5942.2  420.67  6032.9  421.01  6224.3  426.99  6365.4  433.53  6617.3  440.45
  6740.0  445.60  6896.9  454.79  6909.5  454.28  6970.0  457.51  6995.6  457.35
#Mann=5,-1,0
  3678.0    0.05       0  4858.7    0.16       0  5004.0    0.07       0
  5010.0    0.16       0  5659.2    0.05       0
Bank Sta=5004,5010
Exp/Cntr=0.3,0.1

Chan Stop Cuts=-1