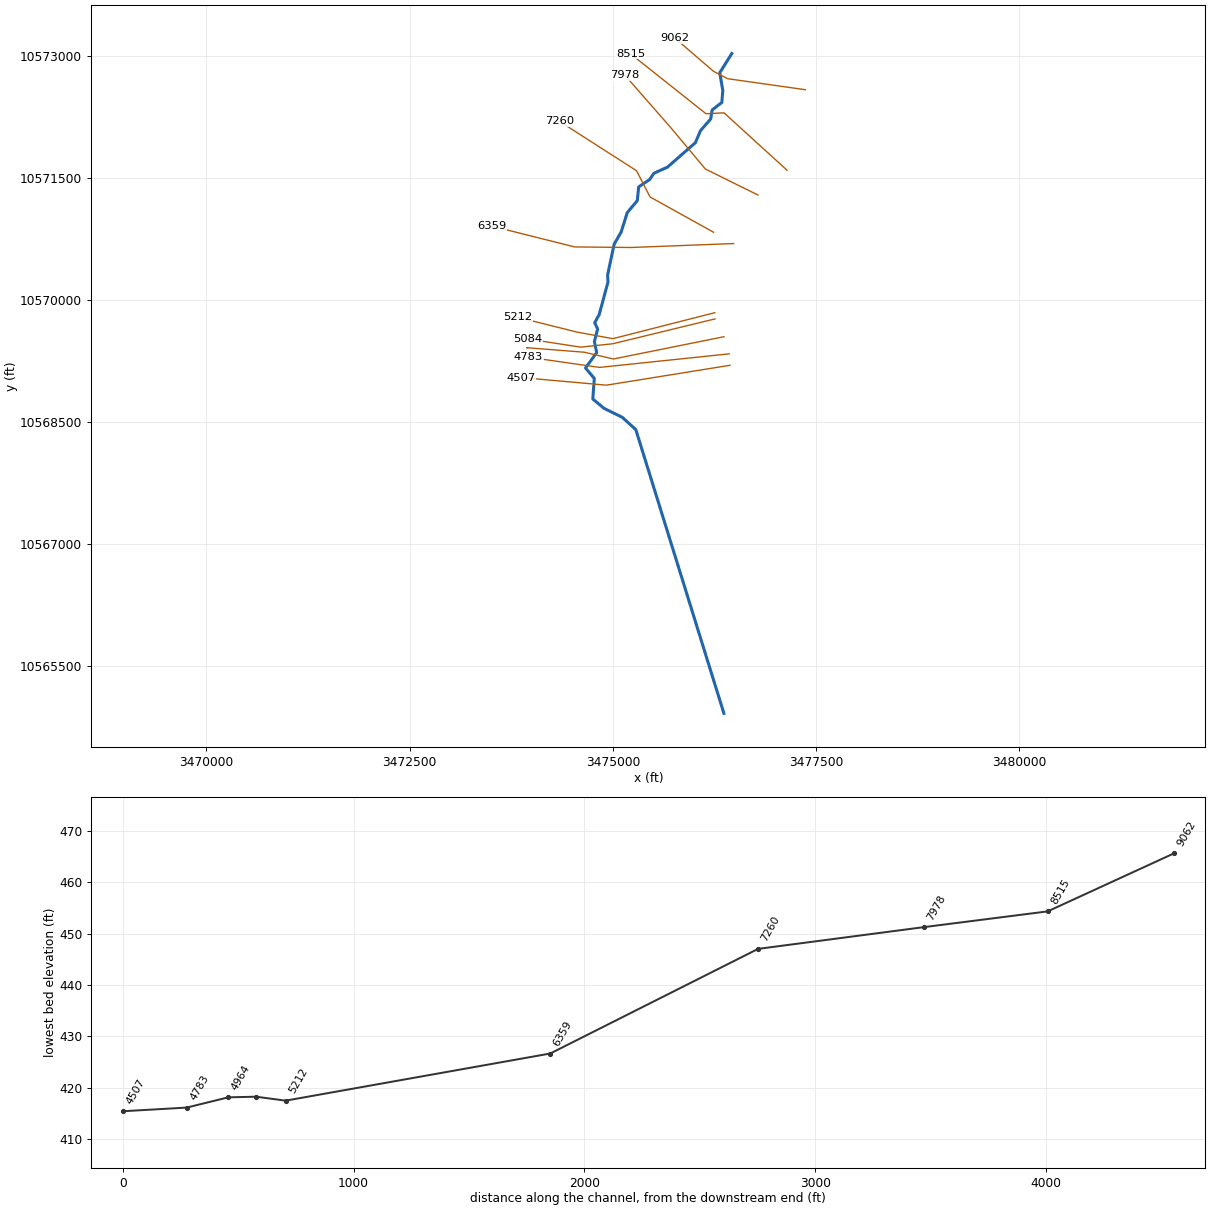
--- UNT0066 IN CHRS.prj (project) ---

Proj Title=UNT0066 IN CHRS Base Level Engineering
Current Plan=p01
Default Exp/Contr=0.3,0.1
English Units
Geom File=g01
Flow File=f01
Plan File=p01
BEGIN DESCRIPTION:
UNT0066 IN CHRS
END DESCRIPTION:

--- UNT0066 IN CHRS.p01 (plan) ---

Plan Title=Multiple Run
Short Identifier=Multiple
Geom File=g01
Flow File=f01
Subcritical Flow
K Sum by GR= 0
Std Step Tol= 0.01
Critical Tol= 0.01
Num of Std Step Trials= 20
Max Error Tol= 0.3
Flow Tol Ratio= 0.001
Split Flow NTrial= 30
Split Flow Tol= 0.02
Split Flow Ratio= 0.02
Log Output Level= 0
Friction Slope Method= 1
Unsteady Friction Slope Method= 2
Unsteady Bridges Friction Slope Method= 1
Parabolic Critical Depth
Global Vel Dist=  1 , 1 , 1
Global Log Level= 0
CheckData=True
Encroach Param= -1, 0, 0, 0
BEGIN DESCRIPTION:
Multiple Run
END DESCRIPTION:

--- UNT0066 IN CHRS.f01 (steady flow) ---

Flow Title=Multiple
Number of Profiles=7
Profile Names=10-year,25-year,50-year,1pct_min,100-year,1pct_plu,500-year
River Rch & RM= UNT0066 IN CHRS,Reach-1,9062
     467     591     682     574     777    1050    1003
River Rch & RM= UNT0066 IN CHRS,Reach-1,7260
     694     895    1047     891    1204    1629    1590
Boundary for River Rch & Prof#=UNT0066 IN CHRS,Reach-1,1
Up Type=0
Dn Type=3
Dn Slope=0.005
Boundary for River Rch & Prof#=UNT0066 IN CHRS,Reach-1,2
Up Type=0
Dn Type=3
Dn Slope=0.005
Boundary for River Rch & Prof#=UNT0066 IN CHRS,Reach-1,3
Up Type=0
Dn Type=3
Dn Slope=0.005
Boundary for River Rch & Prof#=UNT0066 IN CHRS,Reach-1,4
Up Type=0
Dn Type=3
Dn Slope=0.005
Boundary for River Rch & Prof#=UNT0066 IN CHRS,Reach-1,5
Up Type=0
Dn Type=3
Dn Slope=0.005
Boundary for River Rch & Prof#=UNT0066 IN CHRS,Reach-1,6
Up Type=0
Dn Type=3
Dn Slope=0.005
Boundary for River Rch & Prof#=UNT0066 IN CHRS,Reach-1,7
Up Type=0
Dn Type=3
Dn Slope=0.005

--- UNT0066 IN CHRS.g01 (geometry) ---

Geom Title=Existing Conditions

River Reach=UNT0066 IN CHRS,Reach-1
Reach XY= 30
      3476462.11     10573031.64      3476313.72     10572796.18
      3476351.32     10572576.48      3476338.99     10572429.60
      3476220.38     10572338.22      3476202.05     10572226.63
      3476077.18     10572084.26      3476014.21     10571935.41
      3475670.45     10571634.15      3475503.55     10571559.10
      3475451.81     10571482.53      3475315.66     10571390.28
      3475299.87     10571222.68      3475175.79     10571074.83
      3475099.34     10570832.76      3475014.32     10570686.01
      3474933.98     10570306.21      3474939.23     10570222.79
      3474829.49     10569817.26      3474774.98     10569720.58
      3474811.51     10569643.83      3474771.90     10569488.17
      3474799.66     10569352.83      3474662.21     10569163.64
      3474770.08     10569035.89      3474752.34     10568781.90
      3474889.94     10568667.31      3475114.99     10568556.54
      3475281.21     10568405.44      3476364.79     10564915.01

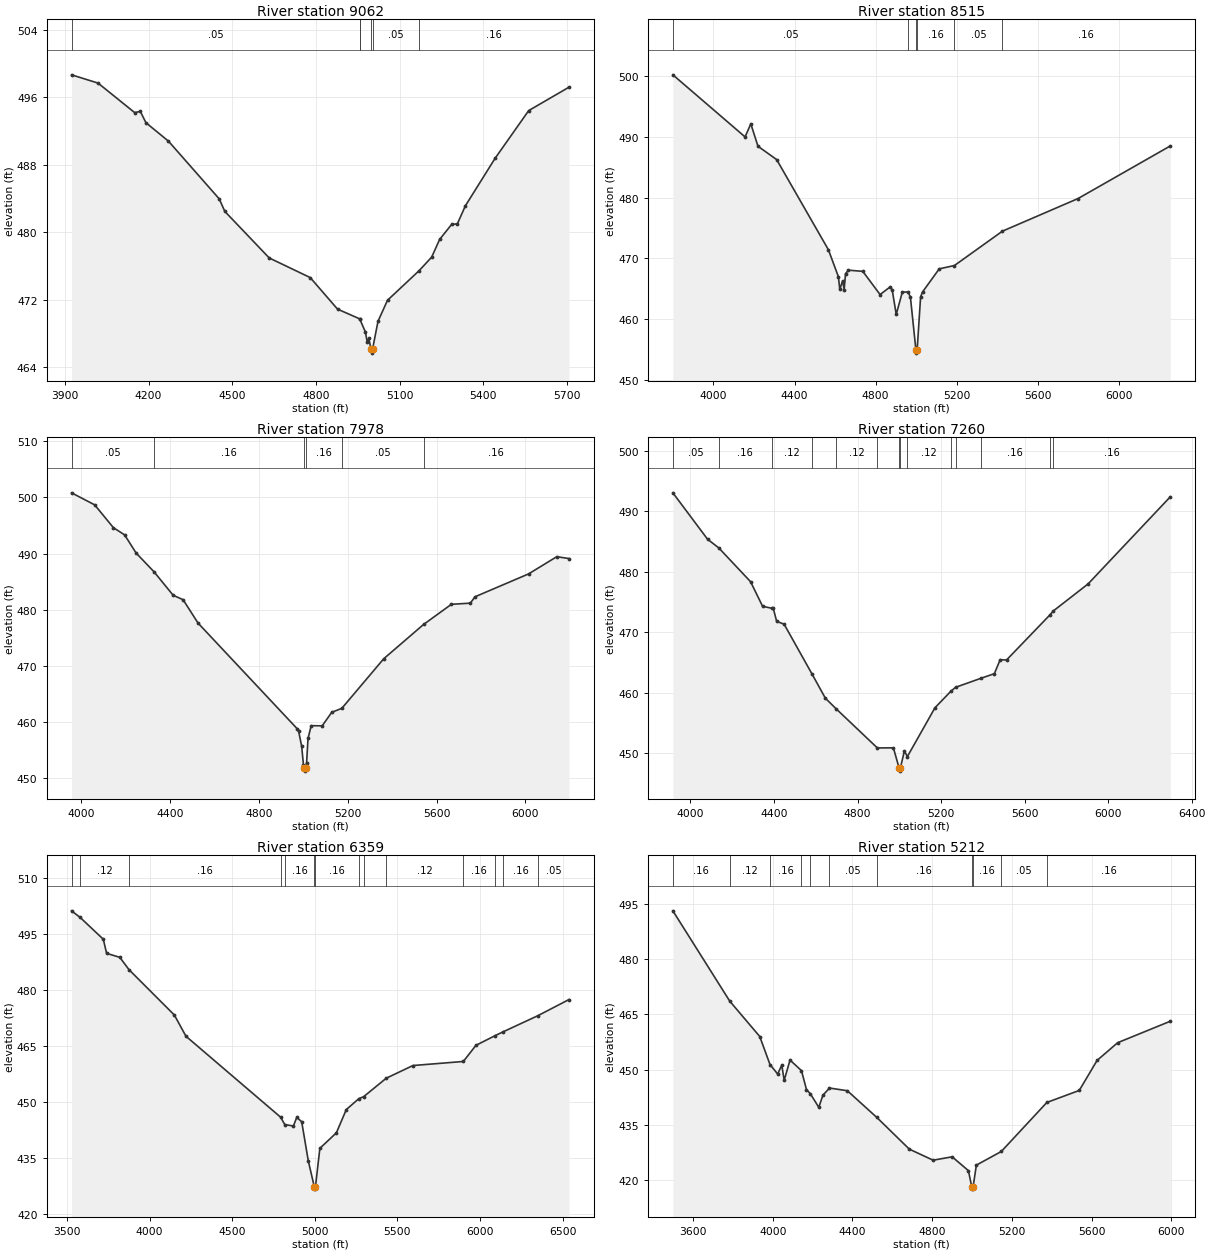
Type RM Length L Ch R = 1,9062,547,547,547
BEGIN DESCRIPTION:
UNT0066 IN CHRS 14.0
END DESCRIPTION:
XS GIS Cut Line= 4
      3477366.16     10572586.77      3476411.34     10572722.19
      3476237.73     10572812.46      3475765.49     10573218.73
#Sta/Elev= 30
  3924.1  498.65  4019.1  497.67  4150.4  494.17  4170.6  494.31  4190.8  492.97
  4271.6  490.78  4453.4  483.94  4473.6  482.45  4632.7  476.93  4779.7  474.60
  4877.6  470.86  4956.7  469.71  4957.1  469.70  4977.8  468.12  4984.1  466.92
  4989.8  467.39  4997.3  466.14  5000.1  465.64  5003.3  466.14  5022.7  469.42
  5056.7  471.91  5170.0  475.42  5215.1  477.03  5243.6  479.13  5286.4  480.90
  5307.2  480.98  5335.8  483.11  5442.2  488.74  5562.9  494.41  5707.1  497.18
#Mann=6,-1,0
  3924.1    0.05       0  4956.7    0.16       0  4957.1    0.05       0
  4997.3   0.035       0  5003.3    0.05       0  5170.0    0.16       0
Bank Sta=4997.3,5003.3
Exp/Cntr=0.3,0.1

Type RM Length L Ch R = 1,8515,537,537,537
BEGIN DESCRIPTION:
UNT0066 IN CHRS 13.0
END DESCRIPTION:
XS GIS Cut Line= 4
      3477140.51     10571597.19      3476366.20     10572302.05
      3476143.98     10572291.63      3475217.70     10573027.10
#Sta/Elev= 30
  3800.3  500.25  4156.3  490.01  4184.6  492.17  4219.8  488.47  4312.0  486.27
  4567.1  471.40  4616.4  466.95  4623.2  464.86  4637.3  466.30  4644.8  464.82
  4651.5  467.45  4665.7  468.03  4736.7  467.84  4821.8  464.01  4871.5  465.27
  4881.5  464.81  4901.5  460.74  4931.6  464.42  4960.3  464.43  4971.6  463.54
  4998.6  454.85  5001.4  454.35  5004.6  454.85  5021.7  463.65  5031.7  464.46
  5113.5  468.25  5188.6  468.80  5424.8  474.46  5797.6  479.84  6252.6  488.52
#Mann=6,-1,0
  3800.3    0.05       0  4960.3    0.16       0  4998.6    0.07       0
  5004.6    0.16       0  5188.6    0.05       0  5424.8    0.16       0
Bank Sta=4998.6,5004.6
Exp/Cntr=0.3,0.1

Type RM Length L Ch R = 1,7978,718,718,718
BEGIN DESCRIPTION:
UNT0066 IN CHRS 12.0
END DESCRIPTION:
XS GIS Cut Line= 4
      3476782.89     10571291.62      3476137.03     10571611.07
      3475709.95     10572121.49      3475147.45     10572763.85
#Sta/Elev= 30
  3956.3  500.83  4060.5  498.69  4144.7  494.63  4195.1  493.35  4247.2  490.11
  4328.4  486.74  4413.9  482.59  4458.7  481.80  4526.0  477.64  4971.9  458.85
  4978.4  458.50  4992.7  455.68  5000.5  452.46  5004.0  451.78  5006.8  451.28
  5010.0  451.78  5014.8  452.78  5021.3  457.12  5035.6  459.37  5085.1  459.35
  5128.0  461.75  5173.4  462.46  5362.2  471.29  5541.4  477.39  5666.8  480.98
  5752.3  481.19  5773.1  482.32  6014.2  486.39  6141.4  489.46  6196.2  489.13
#Mann=6,-1,0
  3956.3    0.05       0  4328.4    0.16       0  5004.0    0.07       0
  5010.0    0.16       0  5173.4    0.05       0  5541.4    0.16       0
Bank Sta=5004,5010
Exp/Cntr=0.3,0.1

Type RM Length L Ch R = 1,7260,901,901,901
BEGIN DESCRIPTION:
UNT0066 IN CHRS 10.0
END DESCRIPTION:
XS GIS Cut Line= 4
      3476237.73     10570833.29      3475456.48     10571267.32
      3475289.81     10571590.24      3474342.88     10572197.25
#Sta/Elev= 30
  3915.7  493.03  4081.9  485.36  4135.6  483.93  4287.9  478.34  4345.4  474.28
  4388.0  473.97  4396.5  473.95  4412.6  471.80  4448.4  471.33  4582.0  463.10
  4645.9  459.10  4699.2  457.29  4895.0  450.88  4971.8  450.90  4999.1  447.55
  5001.9  447.05  5005.1  447.55  5024.3  450.37  5038.8  449.46  5170.8  457.52
  5247.0  460.25  5269.6  460.90  5390.2  462.38  5455.2  463.15  5483.0  465.46
  5513.4  465.41  5720.4  472.83  5737.0  473.50  5904.0  477.98  6297.6  492.37
#Mann=14,-1,0
  3915.7    0.05       0  4135.6    0.16       0  4388.0    0.12       0
  4582.0    0.16       0  4699.2    0.12       0  4895.0    0.16       0
  4999.1    0.07       0  5005.1    0.16       0  5038.8    0.12       0
  5247.0    0.16       0  5269.6    0.12       0  5390.2    0.16       0
  5720.4    0.12       0  5737.0    0.16       0
Bank Sta=4999.1,5005.1
Exp/Cntr=0.3,0.1

Type RM Length L Ch R = 1,6359,1147,1147,1147
BEGIN DESCRIPTION:
UNT0066 IN CHRS 8.0
END DESCRIPTION:
XS GIS Cut Line= 4
      3476484.23     10570694.41      3475220.37     10570645.80
      3474529.40     10570652.74      3473506.10     10570909.43
#Sta/Elev= 30
  3528.0  501.16  3580.2  499.39  3720.3  493.55  3740.3  489.78  3820.3  488.71
  3875.7  485.42  4150.6  473.26  4220.6  467.59  4793.8  445.92  4818.6  443.95
  4871.1  443.57  4891.1  445.86  4921.1  444.72  4961.1  434.23  4998.1  427.17
  5000.8  426.67  5004.1  427.17  5031.1  437.59  5131.1  441.74  5191.1  447.96
  5267.0  450.89  5296.0  451.41  5433.0  456.36  5594.4  459.75  5899.7  460.84
  5975.9  465.16  6089.1  467.69  6141.1  468.79  6350.6  473.09  6538.8  477.41
#Mann=14,-1,0
  3528.0    0.16       0  3580.2    0.12       0  3875.7    0.16       0
  4793.8    0.12       0  4818.6    0.16       0  4998.1    0.07       0
  5004.1    0.16       0  5267.0    0.12       0  5296.0    0.16       0
  5433.0    0.12       0  5899.7    0.16       0  6089.1    0.12       0
  6141.1    0.16       0  6350.6    0.05       0
Bank Sta=4998.1,5004.1
Exp/Cntr=0.3,0.1

Type RM Length L Ch R = 1,5212,128,128,128
BEGIN DESCRIPTION:
UNT0066 IN CHRS 7.0
END DESCRIPTION:
XS GIS Cut Line= 4
      3476251.66     10569843.72      3474998.15     10569524.27
      3474546.76     10569607.60      3473825.84     10569787.83
#Sta/Elev= 30
  3499.1  493.20  3784.5  468.63  3935.0  459.01  3986.5  451.38  4024.9  448.80
  4045.6  451.22  4057.6  447.08  4086.9  452.60  4144.4  449.72  4169.4  444.59
  4188.6  443.46  4231.3  439.74  4251.7  443.02  4284.9  444.99  4374.4  444.26
  4522.1  437.01  4685.4  428.37  4804.8  425.36  4900.5  426.28  4981.9  422.52
  4999.2  417.99  5002.0  417.49  5005.2  417.99  5021.8  424.02  5147.0  427.73
  5375.5  441.07  5538.2  444.34  5627.6  452.51  5730.7  457.32  5994.8  463.16
#Mann=11,-1,0
  3499.1    0.16       0  3784.5    0.12       0  3986.5    0.16       0
  4144.4    0.12       0  4188.6    0.16       0  4284.9    0.05       0
  4522.1    0.16       0  4999.2    0.07       0  5005.2    0.16       0
  5147.0    0.05       0  5375.5    0.16       0
Bank Sta=4999.2,5005.2
Exp/Cntr=0.3,0.1

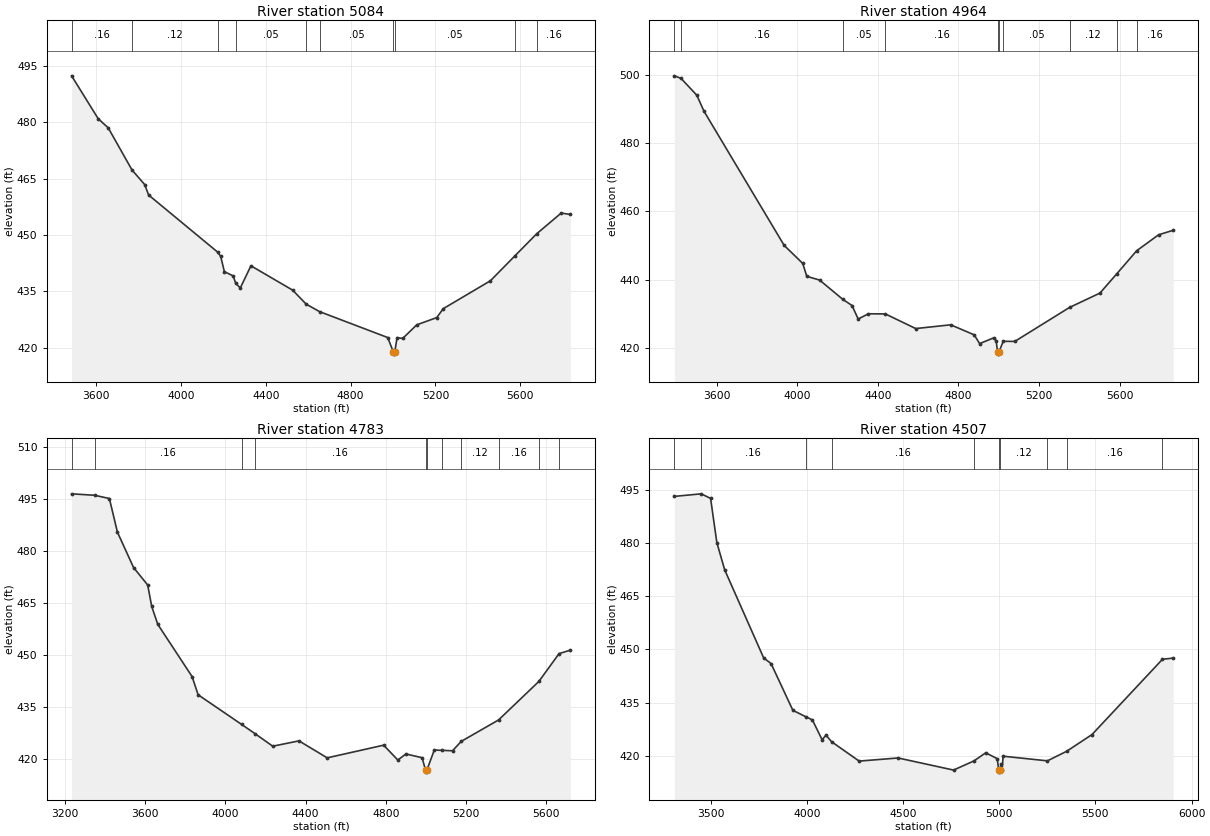
Type RM Length L Ch R = 1,5084,120,120,120
BEGIN DESCRIPTION:
UNT0066 IN CHRS 6.0
END DESCRIPTION:
XS GIS Cut Line= 4
      3476255.12     10569767.33      3474998.15     10569461.77
      3474602.31     10569420.10      3473949.53     10569520.80
#Sta/Elev= 30
  3484.2  492.39  3609.9  480.94  3656.8  478.54  3769.3  467.29  3828.9  463.42
  3847.5  460.64  4172.6  445.45  4187.1  444.32  4204.7  440.23  4246.4  439.09
  4258.0  437.14  4279.7  435.88  4329.9  441.79  4526.7  435.30  4590.4  431.58
  4654.0  429.57  4974.9  422.68  5002.1  418.76  5004.8  418.26  5008.1  418.76
  5019.0  422.66  5045.3  422.43  5112.0  426.06  5206.4  428.00  5236.7  430.36
  5459.3  437.80  5576.3  444.52  5677.0  450.29  5793.2  455.84  5836.3  455.46
#Mann=10,-1,0
  3484.2    0.16       0  3769.3    0.12       0  4172.6    0.16       0
  4258.0    0.05       0  4590.4    0.16       0  4654.0    0.05       0
  5002.1    0.04       0  5008.1    0.05       0  5576.3    0.12       0
  5677.0    0.16       0
Bank Sta=5002.1,5008.1
Exp/Cntr=0.3,0.1

Type RM Length L Ch R = 1,4964,181,181,181
BEGIN DESCRIPTION:
UNT0066 IN CHRS 5.0
END DESCRIPTION:
XS GIS Cut Line= 5
      3476366.25     10569548.58      3475005.09     10569274.27
      3474647.45     10569357.60      3473939.12     10569413.16
      3473948.36     10569413.16
#Sta/Elev= 30
  3390.8  499.79  3423.9  499.03  3502.0  494.09  3537.8  489.38  3935.7  450.03
  4027.5  444.77  4047.9  440.97  4111.7  439.86  4226.2  434.23  4272.3  432.40
  4302.9  428.44  4353.9  429.98  4438.0  429.93  4588.6  425.64  4762.0  426.74
  4878.9  423.80  4905.6  421.22  4977.5  422.96  4987.7  422.10  4995.0  418.64
  4997.8  418.14  5001.0  418.64  5022.6  421.90  5080.2  421.87  5352.3  431.85
  5503.0  436.05  5585.3  441.63  5684.8  448.45  5793.9  453.15  5866.3  454.47
#Mann=10,-1,0
  3390.8    0.05       0  3423.9    0.16       0  4226.2    0.05       0
  4438.0    0.16       0  4995.0    0.07       0  5001.0    0.16       0
  5022.6    0.05       0  5352.3    0.12       0  5585.3    0.05       0
  5684.8    0.16       0
Bank Sta=4995,5001
Exp/Cntr=0.3,0.1

Type RM Length L Ch R = 1,4783,276,276,276
BEGIN DESCRIPTION:
UNT0066 IN CHRS 2.0
END DESCRIPTION:
XS GIS Cut Line= 3
      3476429.34     10569337.62      3474835.63     10569170.96
      3473960.61     10569295.96
#Sta/Elev= 30
  3233.7  496.45  3348.4  496.03  3422.0  495.10  3462.2  485.37  3542.6  475.18
  3613.0  470.14  3633.1  463.94  3663.3  458.78  3834.2  443.72  3864.4  438.46
  4081.4  429.90  4148.0  427.24  4236.4  423.62  4367.1  425.16  4507.8  420.26
  4789.4  423.92  4859.9  419.63  4900.3  421.38  4981.1  420.30  4998.3  416.64
  5001.0  416.14  5004.3  416.64  5041.7  422.51  5079.8  422.43  5132.6  422.30
  5175.7  425.00  5362.2  431.20  5563.2  442.32  5663.7  450.34  5720.0  451.34
#Mann=11,-1,0
  3233.7    0.05       0  3348.4    0.16       0  4081.4    0.05       0
  4148.0    0.16       0  4998.3    0.07       0  5004.3    0.16       0
  5079.8    0.05       0  5175.7    0.12       0  5362.2    0.16       0
  5563.2    0.05       0  5663.7    0.16       0
Bank Sta=4998.3,5004.3
Exp/Cntr=0.3,0.1

Type RM Length L Ch R = 1,4507,0,0,0
BEGIN DESCRIPTION:
UNT0066 IN CHRS 1.0
END DESCRIPTION:
XS GIS Cut Line= 3
      3476439.79     10569197.00      3474918.96     10568952.21
      3473872.06     10569045.96
#Sta/Elev= 30
  3312.4  493.15  3451.7  493.87  3500.4  492.58  3532.9  480.13  3573.4  472.47
  3776.0  447.64  3814.7  446.02  3927.9  432.85  3993.6  431.08  4029.2  430.16
  4079.8  424.56  4100.1  425.85  4129.1  424.00  4272.3  418.54  4474.9  419.42
  4762.8  416.01  4868.8  418.59  4930.0  420.88  4990.2  419.21  4997.2  415.93
  5000.0  415.43  5003.2  415.93  5010.0  417.61  5015.0  416.04  5020.3  419.92
  5250.5  418.61  5350.1  421.29  5482.2  426.02  5848.4  447.24  5903.9  447.57
#Mann=10,-1,0
  3312.4    0.05       0  3451.7    0.16       0  3993.6    0.05       0
  4129.1    0.16       0  4868.8    0.12       0  4997.2    0.07       0
  5003.2    0.12       0  5250.5    0.05       0  5350.1    0.16       0
  5848.4    0.05       0
Bank Sta=4997.2,5003.2
Exp/Cntr=0.3,0.1

Chan Stop Cuts=-1