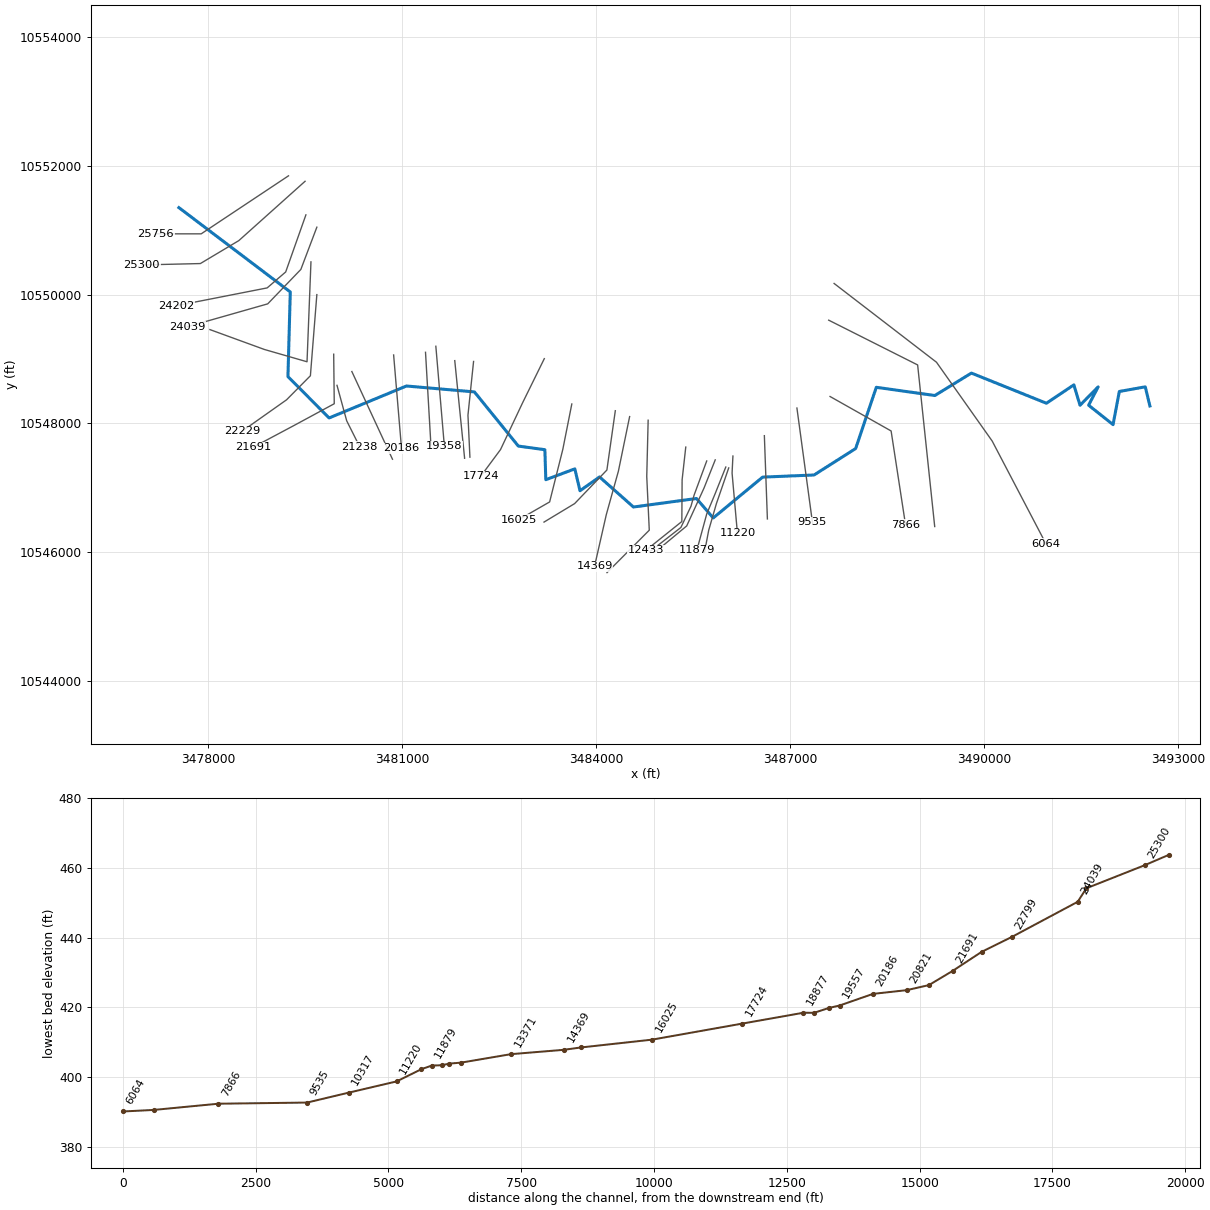
--- UNT0068 IN CHRS.prj (project) ---

Proj Title=UNT0068 IN CHRS Base Level Engineering
Current Plan=p01
Default Exp/Contr=0.3,0.1
English Units
Geom File=g01
Flow File=f01
Plan File=p01
Y Axis Title=Elevation
X Axis Title(PF)=Main Channel Distance
X Axis Title(XS)=Station
BEGIN DESCRIPTION:
UNT0068 IN CHRS
END DESCRIPTION:
DSS Export Rating Curves= 0
DSS Export Rating Curve Sorted= 0
DSS Export Volume Flow Curves= 0
DXF OffsetX= 0
DXF OffsetY= 0
DXF ScaleX= 1
DXF ScaleY= 10

--- UNT0068 IN CHRS.p01 (plan) ---

Plan Title=Multiple Run
Short Identifier=Multiple
Geom File=g01
Flow File=f01
Subcritical Flow
K Sum by GR= 0
Std Step Tol= 0.01
Critical Tol= 0.01
Num of Std Step Trials= 20
Max Error Tol= 0.3
Flow Tol Ratio= 0.001
Split Flow NTrial= 30
Split Flow Tol= 0.02
Split Flow Ratio= 0.02
Log Output Level= 0
Friction Slope Method= 1
Unsteady Friction Slope Method= 2
Unsteady Bridges Friction Slope Method= 1
Parabolic Critical Depth
Global Vel Dist=  1 , 1 , 1
Global Log Level= 0
CheckData=True
Encroach Param= -1, 0, 0, 0
BEGIN DESCRIPTION:
Multiple Run
END DESCRIPTION:

--- UNT0068 IN CHRS.f01 (steady flow) ---

Flow Title=Multiple
Number of Profiles=7
Profile Names=10-year,25-year,50-year,1pct_min,100-year,1pct_plu,500-year
River Rch & RM= UNT0068 IN CHRS,Reach-1,25756
     407     508     581     485     655     886     830
River Rch & RM= UNT0068 IN CHRS,Reach-1,24039
     448     562     646     540     731     988     932
River Rch & RM= UNT0068 IN CHRS,Reach-1,22229
     892    1162    1370    1173    1587    2146    2124
River Rch & RM= UNT0068 IN CHRS,Reach-1,21238
    1048    1375    1628    1400    1893    2560    2554
River Rch & RM= UNT0068 IN CHRS,Reach-1,19077
    1073    1403    1657    1421    1922    2599    2578
River Rch & RM= UNT0068 IN CHRS,Reach-1,11879
    1146    1496    1764    1509    2041    2760    2726
Boundary for River Rch & Prof#=UNT0068 IN CHRS,Reach-1,1
Up Type=0
Dn Type=3
Dn Slope=0.005
Boundary for River Rch & Prof#=UNT0068 IN CHRS,Reach-1,2
Up Type=0
Dn Type=3
Dn Slope=0.005
Boundary for River Rch & Prof#=UNT0068 IN CHRS,Reach-1,3
Up Type=0
Dn Type=3
Dn Slope=0.005
Boundary for River Rch & Prof#=UNT0068 IN CHRS,Reach-1,4
Up Type=0
Dn Type=3
Dn Slope=0.005
Boundary for River Rch & Prof#=UNT0068 IN CHRS,Reach-1,5
Up Type=0
Dn Type=3
Dn Slope=0.005
Boundary for River Rch & Prof#=UNT0068 IN CHRS,Reach-1,6
Up Type=0
Dn Type=3
Dn Slope=0.005
Boundary for River Rch & Prof#=UNT0068 IN CHRS,Reach-1,7
Up Type=0
Dn Type=3
Dn Slope=0.005

--- UNT0068 IN CHRS.g01 (geometry) ---

Geom Title=Existing Conditions
Program Version=4.10

River Reach=UNT0068 IN CHRS ,Reach-1
Reach XY= 30
       3477547.7     10551348.04      3479269.79     10550040.13
      3479233.47     10548727.18      3479870.13      10548085.9
      3481065.93     10548581.39      3482116.95     10548489.65
      3482796.55     10547649.34      3483206.42     10547593.49
      3483220.74     10547127.97      3483669.63     10547296.28
      3483749.63     10546956.69      3484051.62     10547170.77
      3484576.18     10546704.38      3485550.29     10546836.55
      3485809.88      10546534.7      3486573.71     10547168.04
      3487368.53      10547201.1      3488012.04     10547611.37
      3488331.31     10548561.22      3489236.63     10548433.78
      3489802.07      10548781.8        3490962.       10548314.
      3491385.94     10548599.35      3491481.54     10548282.78
      3491761.43     10548567.25      3491614.34     10548283.43
       3491992.3     10547982.12      3492089.03     10548496.47
      3492490.42     10548568.52      3492562.11     10548271.64

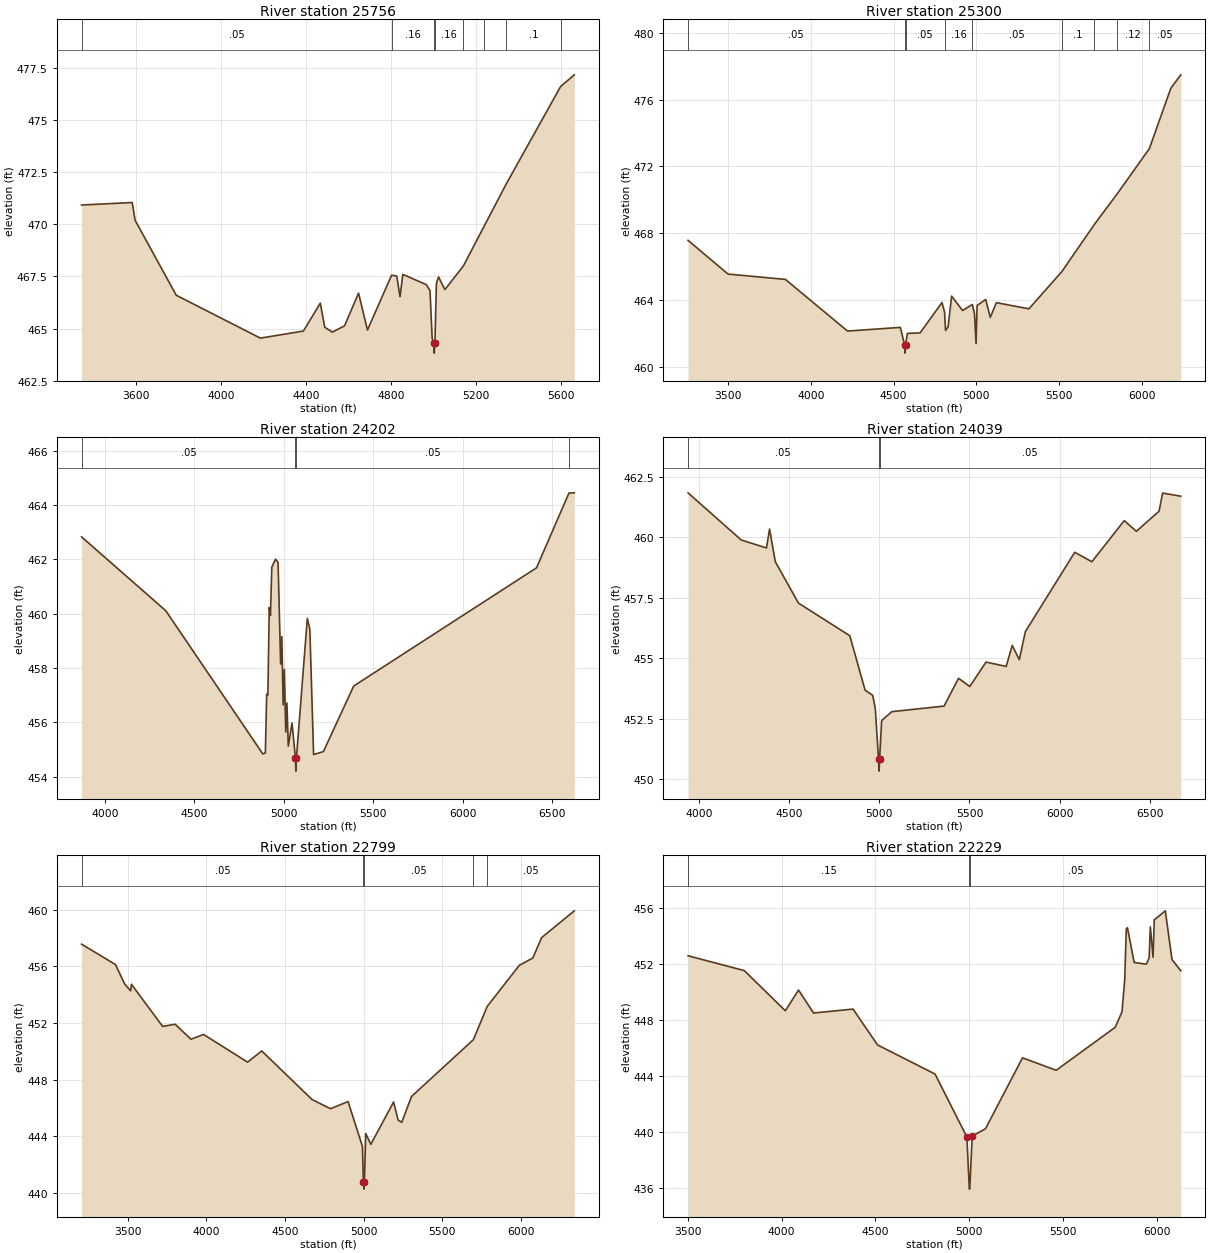
Type RM Length L Ch R = 1 ,25756   ,456,456,456
BEGIN DESCRIPTION:
UNT0068 IN CHRS 36.0
END DESCRIPTION:
XS GIS Cut Line= 3
      3479242.14     10551841.67      3477892.11     10550941.64
      3477192.15     10550941.64
#Sta/Elev= 30
  3341.7  470.93  3580.6  471.05  3594.1   470.2  3787.9   466.6  4184.5  464.54
  4387.4  464.88    4467  466.22    4488  465.06  4524.1  464.83  4581.2  465.13
  4647.3   466.7  4689.3  464.93    4803  467.56  4827.5  467.52  4842.6  466.53
  4856.1   467.6  4966.7  467.11  4984.2  466.81  4994.2  464.53  5001.2  464.32
    5004  463.82  5007.2  464.32  5014.2  467.16  5024.2  467.48  5054.2  466.87
  5141.7  468.01  5240.6  469.94  5342.8  471.93  5599.7  476.62  5664.2  477.18
#Mann= 8 ,-1 , 0
  3341.7     .05       0    4803     .16       0  5001.2     .07       0
  5007.2     .16       0  5141.7      .1       0  5240.6     .05       0
  5342.8      .1       0  5599.7     .05       0
Bank Sta=5001.2,5007.2
XS Rating Curve= 0 ,0
Exp/Cntr=0.3,0.1

Type RM Length L Ch R = 1 ,25300   ,1098,1098,1098
BEGIN DESCRIPTION:
UNT0068 IN CHRS 35.2
END DESCRIPTION:
XS GIS Cut Line= 4
      3479498.28     10551756.84      3478473.97     10550836.69
      3477879.35     10550480.79      3476972.21     10550459.09
#Sta/Elev= 30
  3258.2  467.58  3499.8  465.56  3846.7  465.24  4221.9  462.15  4541.1  462.37
  4566.5  461.33  4569.3  460.83  4572.5  461.33  4583.7  462.01  4660.6  462.04
  4792.8  463.86  4808.4  463.28  4814.2  462.19  4829.7  462.41  4851.1  464.24
    4917  463.38  4976.2  463.74  4989.2  463.18  4998.6   461.4  5004.8  463.68
  5056.8  464.04  5084.5  462.97  5121.5  463.85  5317.9  463.48  5517.1  465.71
  5713.6  468.53  5851.3  470.36  6045.5  473.06  6175.6  476.68  6235.5  477.48
#Mann= 9 ,-1 , 0
  3258.2     .05       0  4566.5    .035       0  4572.5     .05       0
  4808.4     .16       0  4976.2     .05       0  5517.1      .1       0
  5713.6     .05       0  5851.3     .12       0  6045.5     .05       0
Bank Sta=4566.5,4572.5
XS Rating Curve= 0 ,0
Exp/Cntr=0.3,0.1

Type RM Length L Ch R = 1 ,24202   ,163,163,163
BEGIN DESCRIPTION:
UNT0068 IN CHRS 35.1
END DESCRIPTION:
XS GIS Cut Line= 4
      3479511.29     10551235.98      3479198.79     10550350.58
      3478912.33     10550103.19      3477501.76     10549825.41
#Sta/Elev= 30
    3869  462.83  4340.2  460.11  4882.8  454.84  4896.6  454.88  4904.2  457.04
  4910.8  457.01  4918.5  460.23  4925.1  459.94  4932.7  461.71  4953.6  462.01
  4967.8  461.89  4982.1  458.15  4988.7  459.16  4996.3  456.65    5003  457.95
  5010.6  455.65  5017.2  456.72  5024.9  455.13  5045.7  455.98  5064.6  454.71
  5067.4  454.21  5070.6  454.71  5131.3  459.83  5145.5  459.42  5166.4  454.82
  5221.3  454.93  5390.5  457.34  6412.8  461.69  6594.1  464.44  6624.1  464.45
#Mann= 4 ,-1 , 0
    3869     .05       0  5064.6     .03       0  5070.6     .05       0
  6594.1     .12       0
Bank Sta=5064.6,5070.6
XS Rating Curve= 0 ,0
Exp/Cntr=0.3,0.1

Type RM Length L Ch R = 1 ,24039   ,1240,1240,1240
BEGIN DESCRIPTION:
UNT0068 IN CHRS 35.0
END DESCRIPTION:
XS GIS Cut Line= 4
      3479680.56       10551045.      3479433.17     10550389.65
      3478921.02     10549855.79      3477676.22     10549500.14
#Sta/Elev= 30
    3938  461.84  4233.2  459.89  4373.5  459.56  4390.5  460.34  4422.6  458.99
  4550.9  457.28  4835.9  455.93  4920.8  453.68  4963.2  453.46  4977.4  452.92
  4995.4  450.83  4998.2  450.33  5001.4  450.83  5012.6  452.42  5069.2  452.79
  5359.2  453.02  5439.6  454.17    5502  453.83    5592  454.84  5703.8  454.66
  5737.6  455.53  5776.6  454.94  5810.4   456.1  6084.4  459.38  6179.6  458.99
    6359  460.69  6426.6  460.25  6552.4  461.08  6572.2  461.83  6672.9   461.7
#Mann= 3 ,-1 , 0
    3938     .05       0  4995.4    .035       0  5001.4     .05       0
Bank Sta=4995.4,5001.4
XS Rating Curve= 0 ,0
Exp/Cntr=0.3,0.1

Type RM Length L Ch R = 1 ,22799   ,570,570,570
BEGIN DESCRIPTION:
UNT0068 IN CHRS 34.0
END DESCRIPTION:
XS GIS Cut Line= 4
      3479589.42     10550506.86      3479528.65     10548957.35
      3478868.93     10549148.33      3478027.05     10549456.44
#Sta/Elev= 30
  3205.5  457.58  3420.9  456.14  3480.9  454.74  3517.8  454.28  3522.9  454.74
  3721.1  451.76  3801.2  451.91  3901.3  450.85  3981.3  451.19  4261.5  449.23
  4351.6  450.02  4671.8  446.58  4789.3  445.93  4900.5  446.44    4992  443.26
  4998.3  440.74  5001.1  440.24  5004.3  440.74  5012.9  444.18  5045.3  443.41
  5190.1  446.41  5218.5  445.14  5241.9  444.97  5304.4   446.8  5697.7  450.82
  5785.5  453.17  5989.5  456.08  6075.7   456.6  6131.4  458.04  6339.5  459.94
#Mann= 5 ,-1 , 0
  3205.5     .05       0  4998.3    .035       0  5004.3     .05       0
  5697.7     .16       0  5785.5     .05       0
Bank Sta=4998.3,5004.3
XS Rating Curve= 0 ,0
Exp/Cntr=0.3,0.1

Type RM Length L Ch R = 1 ,22229   ,538,538,538
BEGIN DESCRIPTION:
UNT0068 IN CHRS 33.0
END DESCRIPTION:
XS GIS Cut Line= 4
      3479680.56       10549999.      3479580.74     10548740.34
      3479211.81     10548367.08      3478526.54     10547881.31
#Sta/Elev= 30
  3500.6  452.62  3800.6  451.56  4019.6  448.69  4089.8  450.17    4170  448.53
  4380.7  448.81  4511.1  446.25  4817.9  444.17  4987.6  439.67  4998.7  436.45
  5001.5  435.95  5004.7  436.45  5015.8  439.74  5086.6  440.26  5284.3  445.33
  5463.5  444.44  5778.5  447.51  5814.7  448.62    5829   450.9  5837.6  454.55
  5843.8  454.62  5879.4  452.14  5944.7  452.02  5959.4  452.47  5965.6  454.69
  5980.3  452.51  5986.5  455.18  6045.6  455.83  6081.2  452.35    6128  451.55
#Mann= 3 ,-1 , 0
  3500.6     .15       0  4998.7    .035       0  5004.7     .05       0
Bank Sta=4987.6,5015.8
XS Rating Curve= 0 ,0
Exp/Cntr=0.3,0.1

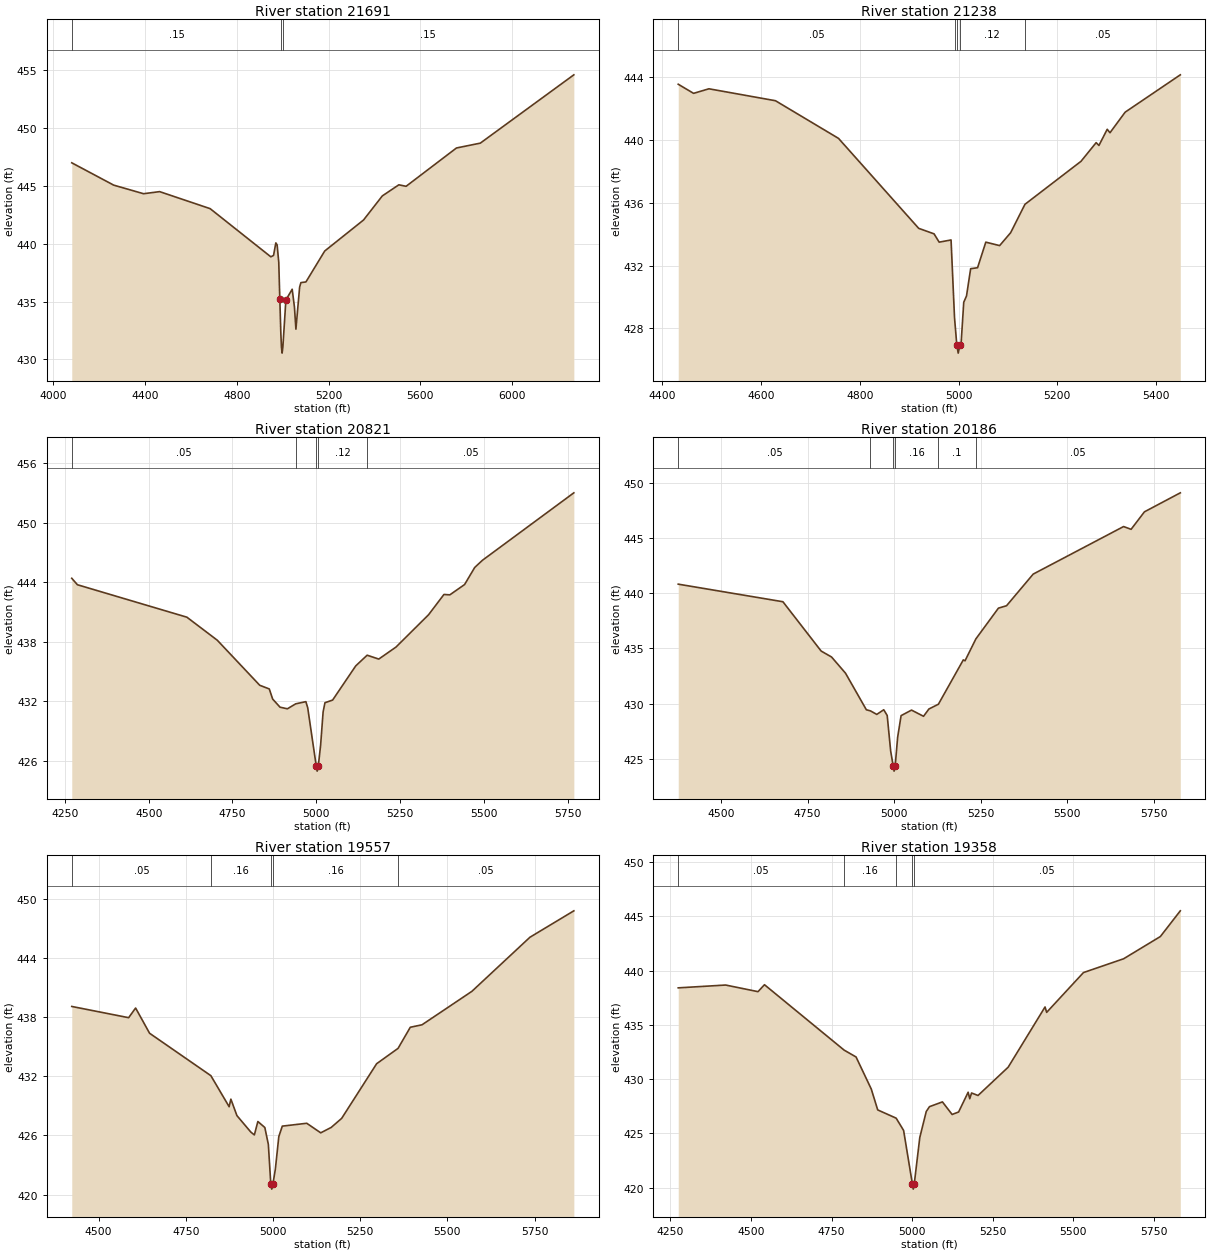
Type RM Length L Ch R = 1 ,21691   ,453,453,453
BEGIN DESCRIPTION:
UNT0068 IN CHRS 32.0
END DESCRIPTION:
XS GIS Cut Line= 4
      3479940.98     10549074.57      3479949.66     10548306.31
      3479333.34     10547972.11       3478699.7     10547633.59
#Sta/Elev= 30
    4081  446.99  4263.9  445.06  4393.9  444.32  4463.9   444.5    4684  443.03
  4948.4  438.87  4960.3  438.99  4970.2  440.07  4975.9   439.9    4983  438.39
 4987.54  435.24  4992.1  432.22  4994.8  431.05  4997.5  430.55  5000.8  431.05
    5014  435.14  5041.5  436.07  5051.3  434.53  5057.7  432.62  5073.9  436.25
  5079.5  436.64  5101.4   436.7  5183.2  439.37  5352.4  442.05  5434.2  444.13
  5506.3  445.09  5537.8  444.96  5757.3  448.27  5861.3  448.69  6268.8  454.59
#Mann= 3 ,-1 , 0
    4081     .15       0  4994.8    .035       0  5000.8     .15       0
Bank Sta=4987.54,5014
XS Rating Curve= 0 ,0
Exp/Cntr=0.3,0.1

Type RM Length L Ch R = 1 ,21238   ,417,417,417
BEGIN DESCRIPTION:
UNT0068 IN CHRS 31.0
END DESCRIPTION:
XS GIS Cut Line= 3
       3479992.1     10548591.67      3480142.11     10548041.64
      3480342.09     10547641.67
#Sta/Elev= 30
  4431.9  443.55    4463  442.97  4494.1  443.26  4628.9   442.5  4756.7   440.1
  4919.1  434.37  4950.2  434.02  4960.6  433.49  4984.7  433.63  4991.7  428.68
  4993.6  427.97  4996.4  426.92  4999.2  426.42  5002.4  426.92  5004.8  426.92
  5010.4  429.66    5016  430.06  5024.4   431.8  5038.4  431.86  5055.1  433.49
  5083.1  433.27  5105.4  434.09  5134.4   435.9    5248  438.64  5278.7  439.83
  5284.3  439.65  5301.1  440.68  5306.7  440.46  5337.4  441.77  5449.2  444.15
#Mann= 5 ,-1 , 0
  4431.9     .05       0  4993.6     .12       0  4996.4     .07       0
  5002.4     .12       0  5134.4     .05       0
Bank Sta=4996.4,5002.4
XS Rating Curve= 0 ,0
Exp/Cntr=0.3,0.1

Type RM Length L Ch R = 1 ,20821   ,635,635,635
BEGIN DESCRIPTION:
UNT0068 IN CHRS 30.0
END DESCRIPTION:
XS GIS Cut Line= 2
      3480221.94     10548805.88      3480849.99     10547445.68
#Sta/Elev= 30
  4270.4   444.4  4287.2  443.75  4613.9  440.48  4704.6  438.16  4831.3  433.62
  4859.8  433.25  4869.9  432.23  4891.9  431.41  4913.9  431.25  4938.6  431.75
    4969  431.97  4974.5  431.35    5000  425.47  5002.7  424.97    5006  425.47
    5013   427.6  5020.4  430.93  5025.9  431.86  5048.8  432.13  5117.7  435.57
  5151.8  436.65  5186.5  436.26  5237.9  437.47  5335.2  440.73    5381  442.77
  5398.5  442.73  5442.6  443.77  5472.8  445.49  5495.7  446.21  5768.6  453.01
#Mann= 5 ,-1 , 0
  4270.4     .05       0  4938.6     .12       0    5000     .07       0
    5006     .12       0  5151.8     .05       0
Bank Sta=5000,5006
XS Rating Curve= 0 ,0
Exp/Cntr=0.3,0.1

Type RM Length L Ch R = 1 ,20186   ,629,629,629
BEGIN DESCRIPTION:
UNT0068 IN CHRS 29.0
END DESCRIPTION:
XS GIS Cut Line= 2
      3480867.78     10549062.81       3480989.3     10547618.41
#Sta/Elev= 30
  4376.7  440.81  4678.9  439.22  4789.3  434.76  4819.4  434.22  4859.6  432.76
  4919.8  429.45  4931.5  429.35  4949.9  429.03    4970  429.45    4980  428.93
    4990  425.72  4997.1   424.4  4999.8   423.9  5003.1   424.4  5010.1  426.95
  5020.1  428.92  5050.2  429.42  5084.9  428.86  5100.4  429.52  5127.8  429.95
  5199.7  433.96  5204.7  433.88    5236  435.86  5301.1  438.64  5324.6  438.86
  5401.5  441.72  5662.4  446.02  5684.1  445.77  5722.6  447.35  5826.2  449.07
#Mann= 6 ,-1 , 0
  4376.7     .05       0  4931.5     .16       0  4997.1     .07       0
  5003.1     .16       0  5127.8      .1       0    5236     .05       0
Bank Sta=4997.1,5003.1
XS Rating Curve= 0 ,0
Exp/Cntr=0.3,0.1

Type RM Length L Ch R = 1 ,19557   ,199,199,199
BEGIN DESCRIPTION:
UNT0068 IN CHRS 28.0
END DESCRIPTION:
XS GIS Cut Line= 2
      3481360.83     10549104.45      3481444.16     10547666.96
#Sta/Elev= 30
  4422.9  439.09    4586  437.95    4606  438.93  4646.1  436.37  4821.8  432.07
  4874.2  428.92  4879.2  429.69  4896.5  428.02  4936.6  426.34  4946.6  426.06
  4956.6  427.42  4976.6  426.81  4986.7  425.09  4993.7  421.06  4996.4  420.56
  4999.7  421.06  5006.7  422.57  5016.7  425.89  5026.7  426.95  5096.8  427.24
  5136.9  426.27    5167  426.82    5197  427.74  5297.2  433.28  5358.7  434.84
  5393.8  436.98  5427.4  437.23  5570.3  440.62  5736.9  446.11  5862.8  448.79
#Mann= 5 ,-1 , 0
  4422.9     .05       0  4821.8     .16       0  4993.7     .07       0
  4999.7     .16       0  5358.7     .05       0
Bank Sta=4993.7,4999.7
XS Rating Curve= 0 ,0
Exp/Cntr=0.3,0.1

Type RM Length L Ch R = 1 ,19358   ,281,281,281
BEGIN DESCRIPTION:
UNT0068 IN CHRS 27.0
END DESCRIPTION:
XS GIS Cut Line= 2
      3481520.55     10549198.22      3481652.47     10547646.42
#Sta/Elev= 30
  4274.4  438.42  4421.5  438.68  4521.9  438.07  4541.9  438.71  4789.1  432.68
    4826  432.05  4873.1   429.1  4893.2  427.17  4950.4  426.41  4973.5  425.28
  5000.6  420.37  5003.4  419.87  5006.6  420.37  5023.7  424.63  5043.7  427.02
  5053.8  427.47  5093.9  427.91    5124  426.75  5144.1  426.98  5173.7   428.8
  5178.7   428.2  5184.3  428.73  5204.3   428.5  5297.9  431.11  5412.2  436.66
  5417.2  436.16  5531.4  439.83  5655.9   441.1  5769.9  443.15  5831.8  445.52
#Mann= 5 ,-1 , 0
  4274.4     .05       0  4789.1     .16       0  4950.4     .05       0
  5000.6    .035       0  5006.6     .05       0
Bank Sta=5000.6,5006.6
XS Rating Curve= 0 ,0
Exp/Cntr=0.3,0.1

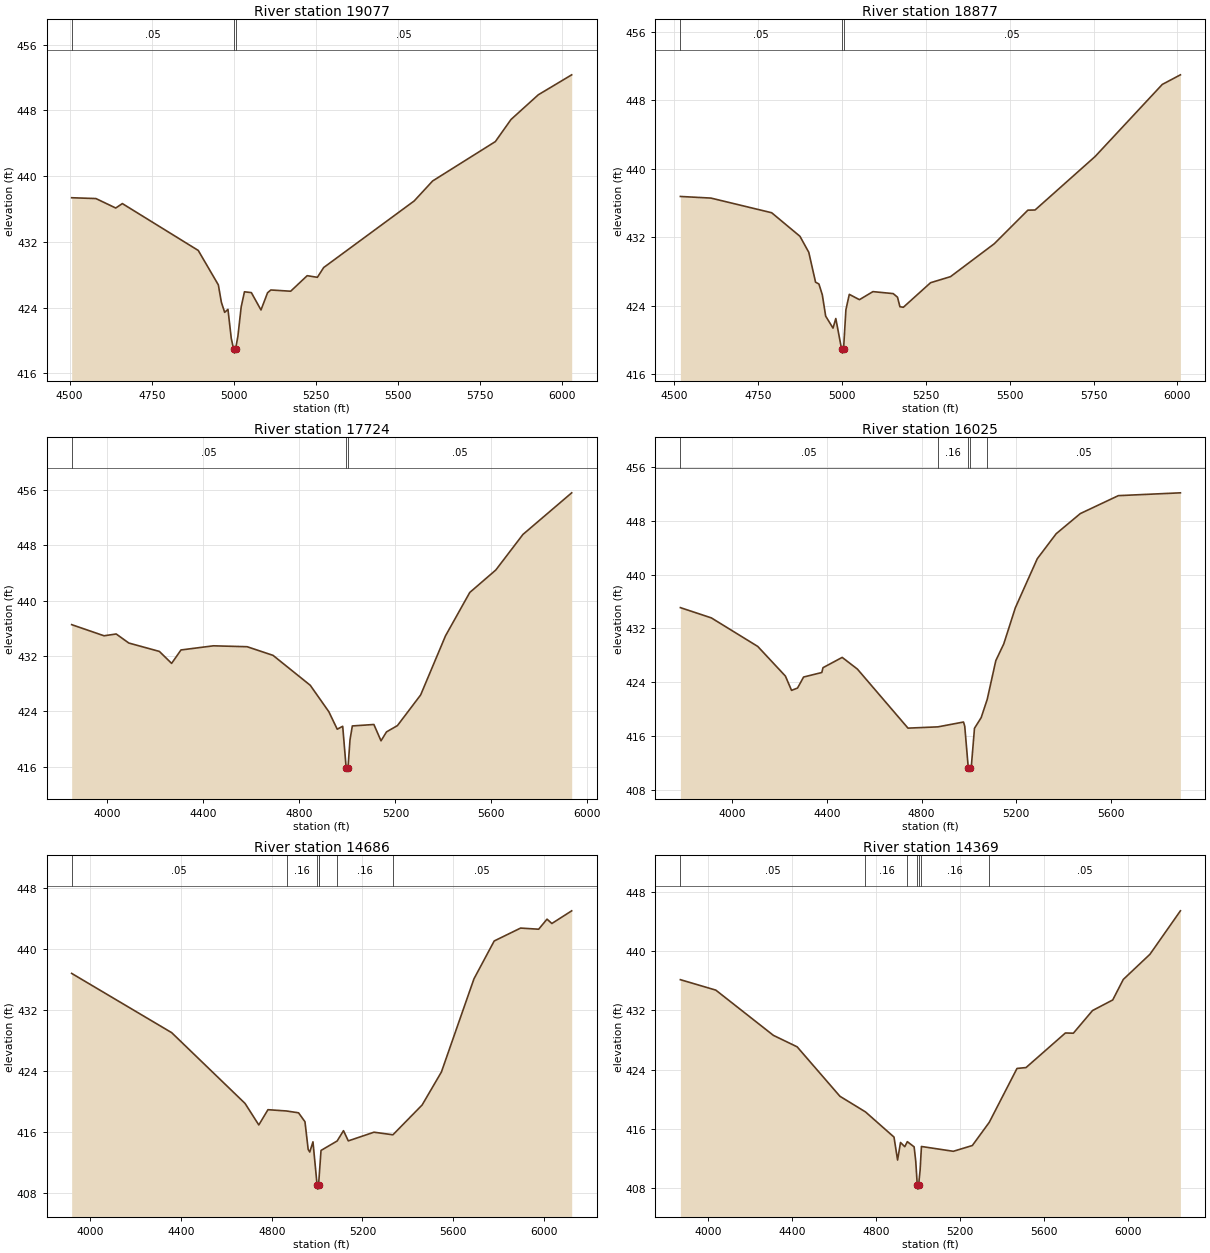
Type RM Length L Ch R = 1 ,19077   ,200,200,200
BEGIN DESCRIPTION:
UNT0068 IN CHRS 26.0
END DESCRIPTION:
XS GIS Cut Line= 4
      3481813.08     10548975.17      3481886.87      10548237.3
        3481965.     10547464.73        3481965.     10547460.39
#Sta/Elev= 30
  4506.1  437.37    4580  437.27  4640.3  436.12  4660.4  436.66  4891.5  430.96
  4952.7  426.77  4961.9  424.66  4971.9  423.43    4982  423.79    4992  420.27
  4999.1  418.97  5001.8  418.47  5005.1  418.97  5012.1  420.49  5022.2  424.08
  5032.2  425.93  5053.2  425.83  5082.5  423.72  5102.6  425.82  5112.6  426.15
  5172.9     426  5223.2  427.89  5254.2  427.69  5273.4  428.88    5549  436.98
  5605.1  439.41  5796.1   444.2  5843.8  446.89  5926.8  449.89  6028.5  452.32
#Mann= 3 ,-1 , 0
  4506.1     .05       0  4999.1     .04       0  5005.1     .05       0
Bank Sta=4999.1,5005.1
XS Rating Curve= 0 ,0
Exp/Cntr=0.3,0.1

Type RM Length L Ch R = 1 ,18877   ,1153,1153,1153
BEGIN DESCRIPTION:
UNT0068 IN CHRS 25.0
END DESCRIPTION:
XS GIS Cut Line= 3
      3482103.89     10548962.13      3482017.08     10548128.79
      3482047.46     10547477.74
#Sta/Elev= 30
  4519.3  436.78  4610.3  436.59  4791.2  434.88  4875.5  432.13  4901.8  430.26
    4922  426.77    4932  426.56  4942.1   425.3  4952.1  422.81    4974  421.41
  4982.3  422.53  4999.4  418.99  5002.1  418.49  5005.4  418.99  5012.4  423.56
  5022.5  425.35  5052.7  424.73  5092.9  425.67  5153.2  425.44  5166.1  425.02
  5173.3  423.91  5183.4  423.84  5264.6  426.71  5324.1  427.42  5454.4  431.26
  5554.5  435.18  5575.9   435.2  5754.7  441.44  5954.9  449.86  6008.9  450.98
#Mann= 3 ,-1 , 0
  4519.3     .05       0  4999.4     .03       0  5005.4     .05       0
Bank Sta=4999.4,5005.4
XS Rating Curve= 0 ,0
Exp/Cntr=0.3,0.1

Type RM Length L Ch R = 1 ,17724   ,1699,1699,1699
BEGIN DESCRIPTION:
UNT0068 IN CHRS 23.0
END DESCRIPTION:
XS GIS Cut Line= 4
      3483197.64     10549005.53      3482863.43     10548324.11
      3482520.55     10547594.94      3482212.37     10547178.25
#Sta/Elev= 30
  3851.4  436.54  3986.3  434.93  4036.9  435.19  4089.6  433.88  4216.8  432.67
  4267.8  430.94  4306.8  432.88  4441.8  433.48  4582.3  433.35  4690.3   432.1
  4845.2  427.78  4922.5  423.97  4957.7  421.43  4980.5  421.85  4994.8  415.87
  4997.5  415.37  5000.8  415.87  5003.3   416.2  5010.9  419.89  5020.6   421.9
  5110.4  422.11  5140.1  419.75  5162.9  421.04  5208.5  421.95  5305.2  426.38
  5408.7  434.92  5509.8  441.19  5618.4  444.44  5731.2  449.57  5934.4  455.59
#Mann= 3 ,-1 , 0
  3851.4     .05       0  4994.8    .035       0  5000.8     .05       0
Bank Sta=4994.8,5000.8
XS Rating Curve= 0 ,0
Exp/Cntr=0.3,0.1

Type RM Length L Ch R = 1 ,16025   ,1339,1339,1339
BEGIN DESCRIPTION:
UNT0068 IN CHRS 20.0
END DESCRIPTION:
XS GIS Cut Line= 4
      3483622.98     10548302.41      3483484.09     10547599.28
       3483280.1     10546783.31       3482799.3     10546506.09
#Sta/Elev= 30
  3780.6   435.1  3911.5  433.57  4107.6  429.32  4224.3  424.91  4250.3  422.78
  4275.6  423.13  4301.2  424.77  4378.1  425.44  4383.2  426.16  4464.3  427.69
  4528.5  425.95  4742.3  417.16  4868.9  417.35  4976.9  418.07  4982.1  417.45
    4997  411.26  4999.7  410.76    5003  411.26  5010.3  411.63  5023.3  417.14
  5051.5  418.72    5077  421.43  5113.4  427.21    5147   429.7  5195.8  435.07
  5288.6  442.38  5368.4   446.1  5470.4   449.1  5631.2  451.77  5893.4  452.19
#Mann= 5 ,-1 , 0
  3780.6     .05       0  4868.9     .16       0    4997     .07       0
    5003     .16       0    5077     .05       0
Bank Sta=4997,5003
XS Rating Curve= 0 ,0
Exp/Cntr=0.3,0.1

Type RM Length L Ch R = 1 ,14686   ,317,317,317
BEGIN DESCRIPTION:
UNT0068 IN CHRS 18.0
END DESCRIPTION:
XS GIS Cut Line= 4
      3484295.73     10548198.28      3484165.52      10547278.1
      3483666.39     10546757.27      3483193.29     10546470.81
#Sta/Elev= 30
  3918.2  436.79  4359.2  429.02  4682.4  419.75    4743  416.93  4783.4  418.93
  4865.4  418.76  4918.2  418.52  4946.5  417.35  4960.6  413.72  4967.6  413.38
  4981.7  414.72  5000.1  409.02  5002.8  408.52  5006.1  409.02  5006.6  409.16
  5017.2  413.59  5088.3  414.83  5116.3  416.18  5137.4  414.84  5250.6  415.98
  5334.1  415.64  5462.9  419.55  5547.8  423.87  5691.3  436.08  5780.5  441.04
  5896.9  442.73  5976.4  442.58  6013.3   443.9  6034.6  443.33    6122  444.99
#Mann= 7 ,-1 , 0
  3918.2     .05       0  4865.4     .16       0  5000.1     .07       0
  5006.1     .16       0  5006.6     .12       0  5088.3     .16       0
  5334.1     .05       0
Bank Sta=5000.1,5006.1
XS Rating Curve= 0 ,0
Exp/Cntr=0.3,0.1

Type RM Length L Ch R = 1 ,14369   ,998,998,998
BEGIN DESCRIPTION:
UNT0068 IN CHRS 17.0
END DESCRIPTION:
XS GIS Cut Line= 4
      3484517.07     10548107.05      3484343.47     10547260.74
      3484156.84       10546588.      3483974.74     10545785.89
#Sta/Elev= 30
  3866.3  436.14  4035.2  434.73  4309.8  428.62  4423.1  427.07  4627.2  420.39
    4749  418.28    4885  414.88  4902.1  411.78  4916.1  414.15  4936.4  413.58
  4948.6  414.26    4981  413.56  4988.7  411.63  4996.1  408.35  4998.9  407.85
  5002.1  408.35  5009.5   410.4  5015.9  413.61  5167.9  412.96  5258.6  413.74
  5339.2  416.87  5471.6  424.15  5514.7  424.27  5702.4  428.94  5740.4  428.91
  5831.7  431.97  5928.1   433.4  5978.4  436.17  6105.6  439.57  6250.9  445.44
#Mann= 7 ,-1 , 0
  3866.3     .05       0    4749     .16       0  4948.6     .12       0
  4996.1     .07       0  5002.1     .12       0  5015.9     .16       0
  5339.2     .05       0
Bank Sta=4996.1,5002.1
XS Rating Curve= 0 ,0
Exp/Cntr=0.3,0.1

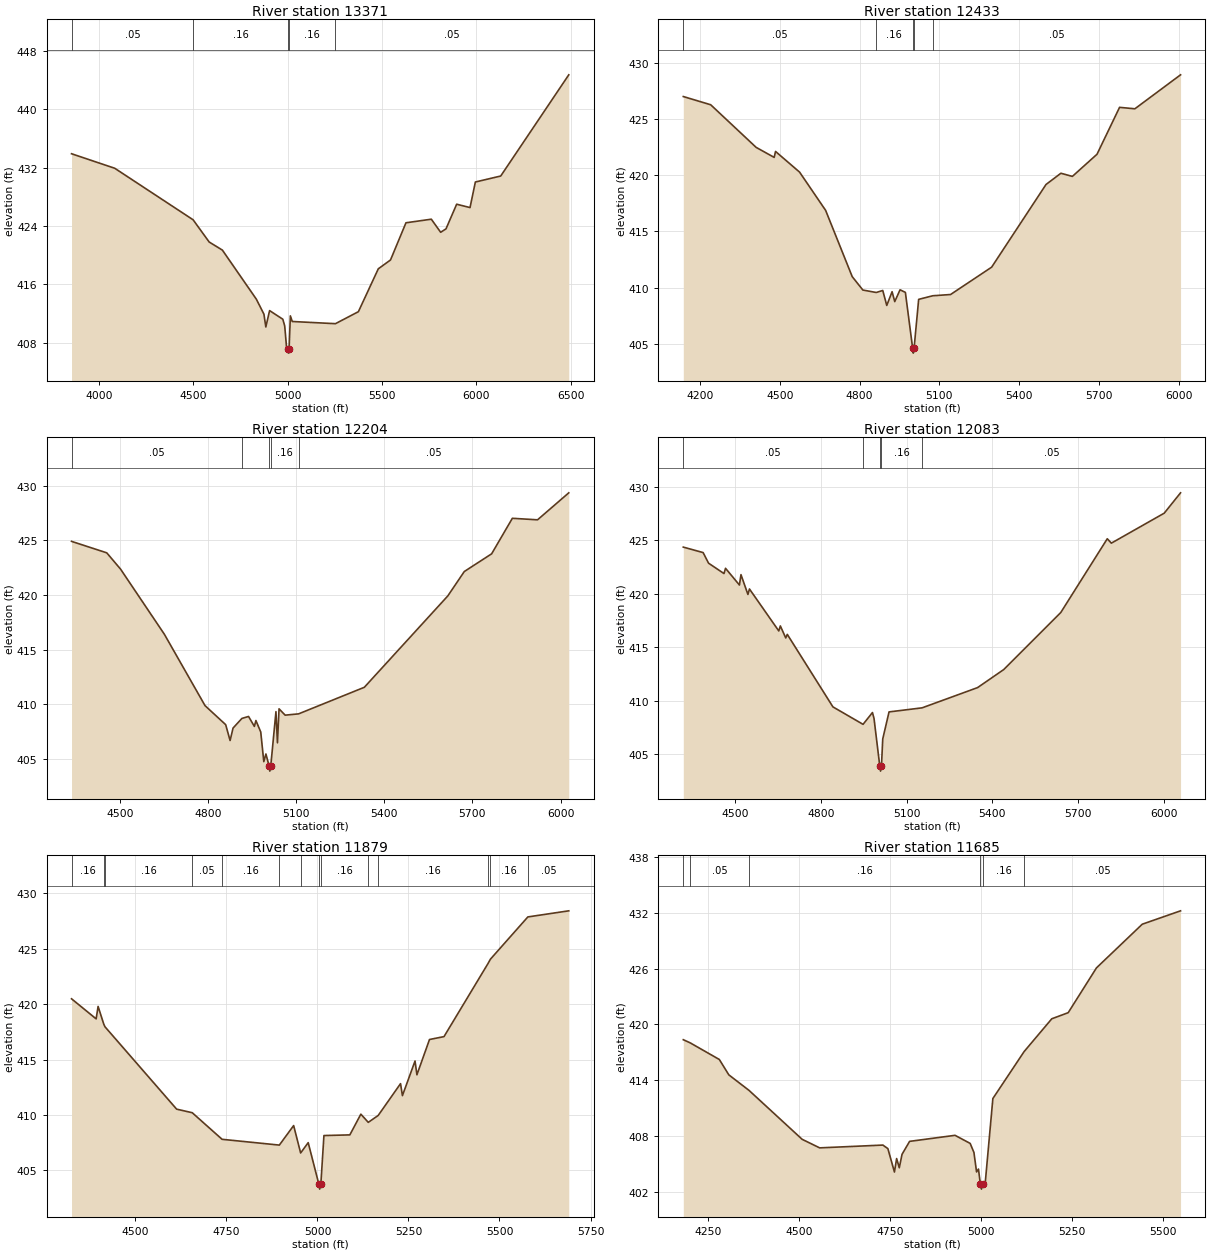
Type RM Length L Ch R = 1 ,13371   ,938,938,938
BEGIN DESCRIPTION:
UNT0068 IN CHRS 16.0
END DESCRIPTION:
XS GIS Cut Line= 4
      3484803.54     10548050.69      3484781.84     10547178.27
       3484820.9     10546344.94      3484167.04     10545686.75
#Sta/Elev= 30
  3855.2  433.89  4084.3   431.9  4499.4  424.85  4584.5  421.81  4654.5   420.7
  4834.6  413.98  4874.7  411.93  4884.7  410.18  4904.7  412.42  4974.8  411.24
  4984.8  410.32  4994.8  407.31  5001.8   407.1  5004.6   406.6  5007.8   407.1
  5014.8   411.7  5024.8  410.93  5253.5  410.63  5375.2  412.27  5480.7  418.14
  5545.4  419.35  5627.2  424.44  5761.6  424.93  5811.1  423.14  5839.4  423.61
  5895.9  426.98  5966.7  426.52  5994.9  430.02  6129.3  430.84  6489.9  444.69
#Mann= 5 ,-1 , 0
  3855.2     .05       0  4499.4     .16       0  5001.8     .07       0
  5007.8     .16       0  5253.5     .05       0
Bank Sta=5001.8,5007.8
XS Rating Curve= 0 ,0
Exp/Cntr=0.3,0.1

Type RM Length L Ch R = 1 ,12433   ,229,229,229
BEGIN DESCRIPTION:
UNT0068 IN CHRS 15.0
END DESCRIPTION:
XS GIS Cut Line= 4
      3485385.14     10547634.04      3485328.71     10547126.19
      3485324.37     10546479.49       3484768.8     10546032.43
#Sta/Elev= 30
  4136.9  426.98  4239.9  426.25    4411  422.46  4478.8  421.57  4483.9   422.1
  4574.4  420.26  4672.4  416.86  4772.4  410.97  4812.4  409.78  4862.6  409.56
  4887.3  409.74  4902.4  408.41  4922.4  409.63  4932.4  408.75  4952.4   409.8
  4972.4  409.57  4999.4  404.67  5002.2  404.17  5005.4  404.67  5022.4  408.95
  5075.6  409.27  5142.4  409.38  5296.9  411.81  5501.5  419.16  5557.5  420.16
  5600.7  419.88  5693.4  421.85  5778.3  426.02  5835.8  425.89  6007.7  428.91
#Mann= 5 ,-1 , 0
  4136.9     .05       0  4862.6     .16       0  4999.4     .07       0
  5005.4     .16       0  5075.6     .05       0
Bank Sta=4999.4,5005.4
XS Rating Curve= 0 ,0
Exp/Cntr=0.3,0.1

Type RM Length L Ch R = 1 ,12204   ,121,121,121
BEGIN DESCRIPTION:
UNT0068 IN CHRS 14.1
END DESCRIPTION:
XS GIS Cut Line= 5
      3485708.95     10547418.34       3485514.5     10546890.55
      3485465.89     10546716.93      3485309.64     10546387.07
       3484848.3     10546026.32
#Sta/Elev= 30
  4334.7   424.9  4454.7  423.85  4501.7  422.36  4650.9   416.4  4789.4  409.87
  4859.7  408.13  4874.7  406.68  4884.8  407.82  4914.9   408.7  4937.6  408.88
  4957.4  407.97  4962.6  408.51  4979.1  407.46  4989.5  404.75  4996.7  405.45
  5007.3  404.38    5010  403.88  5013.3  404.38  5030.9  409.32    5036  406.47
  5041.4  409.58  5062.2     409  5108.1  409.12  5331.9  411.55  5616.2  419.91
  5672.3  422.14  5765.4  423.76    5836  427.01  5921.7  426.87  6028.1  429.34
#Mann= 5 ,-1 , 0
  4334.7     .05       0  4914.9     .16       0  5007.3     .07       0
  5013.3     .16       0  5108.1     .05       0
Bank Sta=5007.3,5013.3
XS Rating Curve= 0 ,0
Exp/Cntr=0.3,0.1

Type RM Length L Ch R = 1 ,12083   ,204,204,204
BEGIN DESCRIPTION:
UNT0068 IN CHRS 14.0
END DESCRIPTION:
XS GIS Cut Line= 4
      3485840.88     10547435.65      3485667.28     10546998.18
      3485399.92     10546411.38      3484920.77     10546012.09
#Sta/Elev= 30
  4319.3  424.36  4388.6  423.85  4407.6  422.86  4461.6  421.89    4467  422.38
  4515.6  420.82    4521  421.79  4545.3  419.94  4550.7  420.45  4653.3  416.53
  4658.7     417  4677.6  415.88    4683  416.21  4842.6  409.44    4948  407.81
  4980.9  408.91  4986.4  408.35  5006.4  403.94  5009.2  403.44  5012.4  403.94
  5016.9  406.45  5038.9  408.97  5154.6  409.35  5348.6  411.24  5440.3  412.93
  5639.5  418.25  5802.2  425.14  5816.5  424.73  6001.4  427.53  6058.5  429.43
#Mann= 5 ,-1 , 0
  4319.3     .05       0    4948     .16       0  5006.4     .07       0
  5012.4     .16       0  5154.6     .05       0
Bank Sta=5006.4,5012.4
XS Rating Curve= 0 ,0
Exp/Cntr=0.3,0.1

Type RM Length L Ch R = 1 ,11879   ,194,194,194
BEGIN DESCRIPTION:
UNT0068 IN CHRS 13.0
END DESCRIPTION:
XS GIS Cut Line= 4
      3486004.08     10547324.56      3485840.89     10546914.85
      3485708.95     10546595.41      3485557.14     10546036.49
#Sta/Elev= 30
  4324.5  420.48  4392.1  418.67  4397.5  419.79    4413   418.2  4416.3  417.96
  4613.2  410.53    4656  410.21  4738.1  407.81  4895.3  407.29  4934.6  409.05
  4953.8  406.58  4974.6  407.51  5003.4  403.82  5006.1  403.32  5009.4  403.82
  5017.8  408.15    5089  408.21  5119.2  410.08  5139.6  409.34  5166.8  409.96
  5228.2  412.83  5233.4  411.75    5268  414.87  5273.2  413.63  5307.8  416.81
  5347.6  417.07  5468.7  423.67  5475.1  424.05  5577.9  427.86  5690.3  428.41
#Mann= 14 ,-1 , 0
  4324.5     .16       0    4413     .08       0  4416.3     .16       0
    4656     .05       0  4738.1     .16       0  4895.3     .08       0
  4953.8     .16       0  5003.4     .07       0  5009.4     .16       0
  5139.6     .05       0  5166.8     .16       0  5468.7     .05       0
  5475.1     .16       0  5577.9     .05       0
Bank Sta=5003.4,5009.4
XS Rating Curve= 0 ,0
Exp/Cntr=0.3,0.1

Type RM Length L Ch R = 1 ,11685   ,465,465,465
BEGIN DESCRIPTION:
UNT0068 IN CHRS 13.1
END DESCRIPTION:
XS GIS Cut Line= 4
      3486049.22     10547310.67      3485858.25     10546755.13
       3485740.2     10546345.41      3485674.22     10545998.16
#Sta/Elev= 30
  4182.3  418.36  4201.3  418.02  4281.4  416.23  4307.4  414.58  4362.9  412.91
  4509.1  407.64  4557.3  406.72  4731.1  407.02  4744.8  406.64  4762.9  404.12
  4768.9  405.57  4776.2  404.58  4783.8  406.03  4804.6  407.42  4929.5  408.07
  4971.1   407.2  4981.5  406.22  4988.7  404.13  4993.9  404.44  4999.3  402.78
  5002.1  402.28  5005.3  402.78  5012.7  403.03  5033.5  412.03  5119.6  417.09
  5195.5  420.61  5240.7  421.27  5318.4  426.09  5444.3  430.79  5549.6  432.23
#Mann= 6 ,-1 , 0
  4182.3     .16       0  4201.3     .05       0  4362.9     .16       0
  4999.3     .07       0  5005.3     .16       0  5119.6     .05       0
Bank Sta=4999.3,5005.3
XS Rating Curve= 0 ,0
Exp/Cntr=0.3,0.1

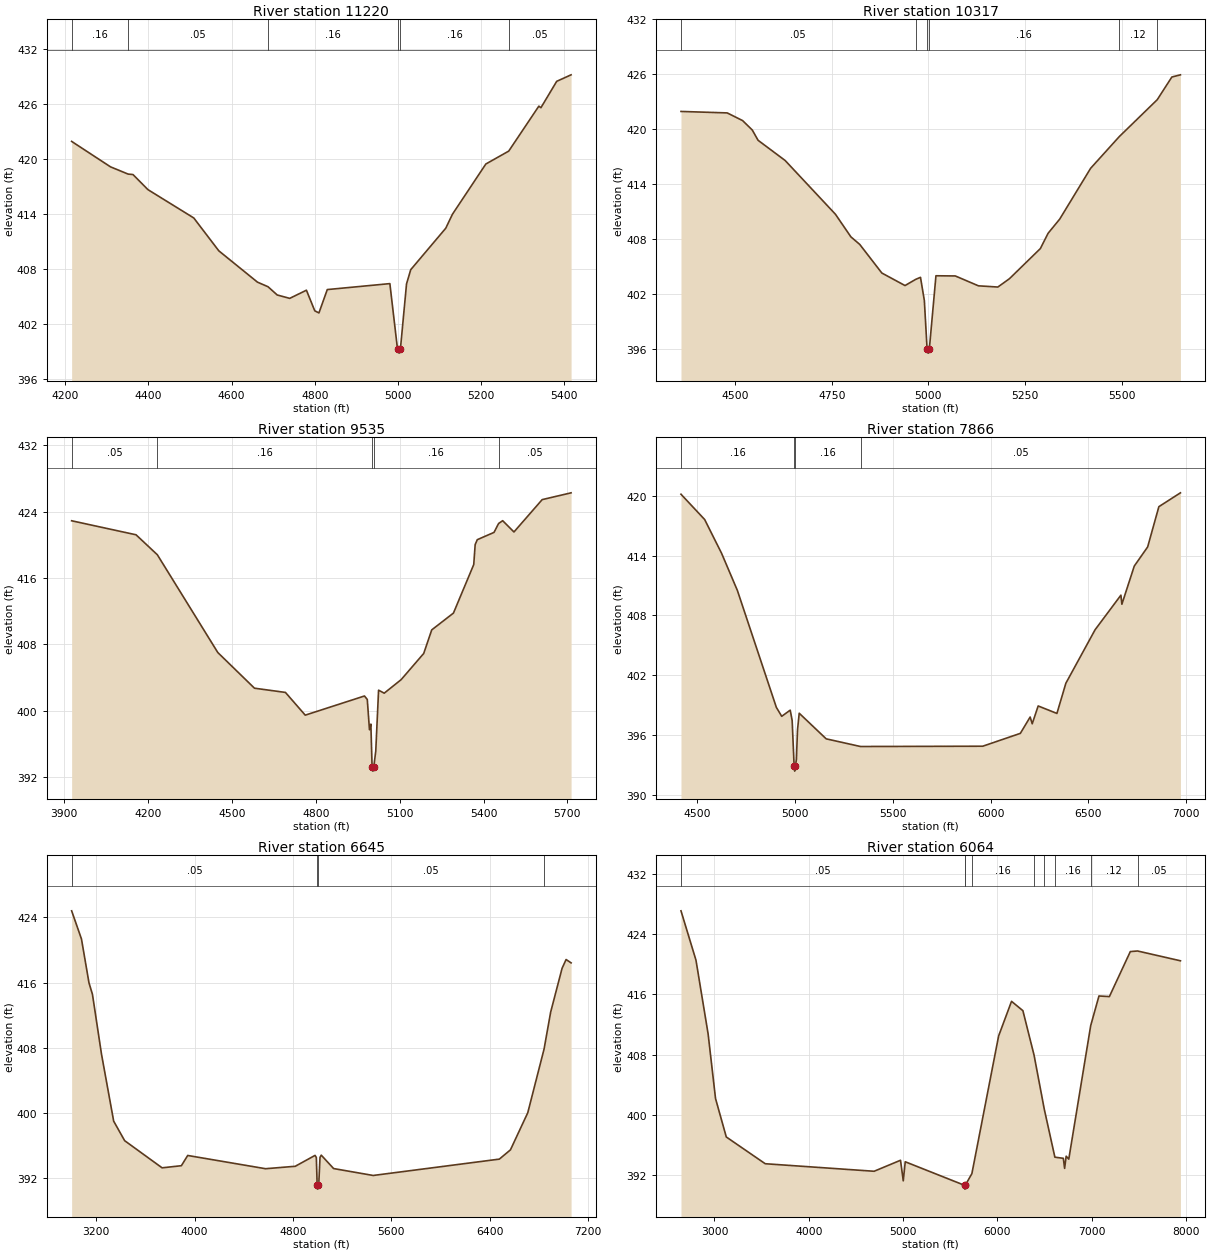
Type RM Length L Ch R = 1 ,11220   ,903,903,903
BEGIN DESCRIPTION:
UNT0068 IN CHRS 12.0
END DESCRIPTION:
XS GIS Cut Line= 3
       3486114.3     10547495.14      3486101.28     10547230.36
      3486183.75      10546297.2
#Sta/Elev= 30
  4215.1   421.9  4308.7  419.12  4351.1  418.33  4362.7  418.28  4398.8  416.63
    4509  413.54  4569.3  409.95  4662.3  406.53  4687.7  406.03  4709.8  405.13
  4739.9  404.76  4780.1  405.65  4800.2   403.4  4810.2  403.17  4830.3  405.72
  4980.9  406.37  4998.3   399.6  5000.4  399.28  5003.1  398.78  5006.4  399.28
    5021  406.34  5031.1  407.89  5115.4  412.42  5131.4  413.94  5211.8  419.43
  5266.9  420.84  5339.4  425.75  5344.4  425.58  5382.4  428.46    5417  429.17
#Mann= 6 ,-1 , 0
  4215.1     .16       0  4351.1     .05       0  4687.7     .16       0
  5000.4     .07       0  5006.4     .16       0  5266.9     .05       0
Bank Sta=5000.4,5006.4
XS Rating Curve= 0 ,0
Exp/Cntr=0.3,0.1

Type RM Length L Ch R = 1 ,10317   ,782,782,782
BEGIN DESCRIPTION:
UNT0068 IN CHRS 11.0
END DESCRIPTION:
XS GIS Cut Line= 2
      3486600.41     10547811.06      3486647.29     10546519.41
#Sta/Elev= 30
  4359.7  421.95  4479.2  421.79  4519.2  420.95  4544.2  419.92  4559.2   418.8
  4629.3  416.59  4759.4  410.72  4799.4  408.25  4822.2  407.43  4879.5   404.3
  4939.5  402.93  4966.7   403.6  4979.5  403.83  4989.5  401.29  4996.5  396.05
  4999.3  395.55  5002.5  396.05  5019.5     404  5069.6  403.98  5129.6   402.9
  5179.7  402.77  5209.7  403.68  5289.7  406.97  5309.7  408.64  5339.8  410.19
  5419.8  415.74  5494.1  419.21  5592.1  423.23    5630  425.71  5652.2  425.95
#Mann= 6 ,-1 , 0
  4359.7     .05       0  4966.7     .16       0  4996.5     .07       0
  5002.5     .16       0  5494.1     .12       0  5592.1     .16       0
Bank Sta=4996.5,5002.5
XS Rating Curve= 0 ,0
Exp/Cntr=0.3,0.1

Type RM Length L Ch R = 1 ,9535    ,1669,1669,1669
BEGIN DESCRIPTION:
UNT0068 IN CHRS 9.0
END DESCRIPTION:
XS GIS Cut Line= 2
      3487103.88     10548239.92      3487343.47     10546469.06
#Sta/Elev= 30
  3926.2   422.9  4156.6  421.21  4232.9   418.8  4449.2  407.01  4580.4  402.71
  4691.2   402.2    4762  399.46  4973.9  401.77    4984  401.35  4991.8   397.7
  4996.8  398.38  5001.2  393.21    5004  392.71  5007.2  393.21  5014.3  395.12
  5024.4  402.47  5044.6  402.11  5105.1  403.74  5185.9   406.9  5214.6  409.74
  5292.3  411.77  5364.9  417.62    5370  420.03  5377.6  420.62  5437.5   421.5
  5453.8  422.57  5468.4  422.91  5508.8  421.55  5609.7  425.45  5713.2  426.27
#Mann= 5 ,-1 , 0
  3926.2     .05       0  4232.9     .16       0  5001.2     .07       0
  5007.2     .16       0  5453.8     .05       0
Bank Sta=5001.2,5007.2
XS Rating Curve= 0 ,0
Exp/Cntr=0.3,0.1

Type RM Length L Ch R = 1 ,7866    ,1221,1221,1221
BEGIN DESCRIPTION:
UNT0068 IN CHRS 6.0
END DESCRIPTION:
XS GIS Cut Line= 3
      3487616.06     10548418.71      3488560.48       10547884.
      3488782.71      10546432.6
#Sta/Elev= 30
  4417.2  420.17  4538.3  417.63  4624.8  414.24  4705.6  410.51  4904.8  398.78
  4932.2  397.88  4975.7   398.5  4985.6  397.46  4995.7  392.88  4998.5  392.38
  5001.7  392.88  5007.2  393.52    5013  396.53  5021.7  398.19  5159.6  395.62
  5335.1  394.85  5960.1  394.88  6152.3  396.17  6202.4  397.81    6213  397.13
  6243.4  398.92  6339.3  398.17    6385   401.2  6534.5  406.57  6666.4  410.04
  6671.4  409.13  6734.8  412.96  6803.2  414.88  6860.5  418.92  6970.8  420.31
#Mann= 4 ,-1 , 0
  4417.2     .16       0  4995.7     .07       0  5001.7     .16       0
  5335.1     .05       0
Bank Sta=4995.7,5001.7
XS Rating Curve= 0 ,0
Exp/Cntr=0.3,0.1

Type RM Length L Ch R = 1 ,6645    ,581,581,581
BEGIN DESCRIPTION:
UNT0068 IN CHRS 2.0
END DESCRIPTION:
XS GIS Cut Line= 3
      3487595.59      10549602.6      3488970.59     10548908.15
      3489234.48     10546401.23
#Sta/Elev= 30
  3000.3  424.82  3080.2  421.36  3141.5  415.95  3169.4  414.56  3242.9  407.21
  3342.2  398.95  3431.3  396.55  3735.8  393.21  3892.6  393.47  3944.1  394.73
  4577.4   393.1  4818.8   393.4  4979.6  394.74  4989.9  394.48  4996.8  391.09
  4999.5  390.59  5002.8  391.09  5009.8  391.21  5019.9   394.5  5029.9  394.77
  5130.5  393.12  5452.2  392.27  6477.9  394.28  6568.4  395.42  6709.3  399.99
  6841.8  407.82  6895.3  412.36  6988.4  417.76  7020.9  418.83  7061.5  418.42
#Mann= 4 ,-1 , 0
  3000.3     .05       0  4996.8     .03       0  5002.8     .05       0
  6841.8     .16       0
Bank Sta=4996.8,5002.8
XS Rating Curve= 0 ,0
Exp/Cntr=0.3,0.1

Type RM Length L Ch R = 1 ,6064    ,0,0,0
BEGIN DESCRIPTION:
UNT0068 IN CHRS 1.0
END DESCRIPTION:
XS GIS Cut Line= 4
      3487678.96     10550172.01      3489262.26     10548949.82
      3490123.37      10547727.6      3490956.71     10546130.37
#Sta/Elev= 30
    2645  427.08    2804  420.53  2932.6  410.76  3011.4  402.17  3125.5  397.07
  3538.5  393.52  4693.1  392.52  4973.2  393.98  5002.3  391.25  5023.2  393.78
  5653.3  390.65  5656.1  390.15  5659.3  390.65  5730.1  392.21  6013.5  410.47
  6150.5  415.07    6271  413.83  6389.2  407.94  6497.6  400.77  6610.2  394.39
  6699.7  394.24  6713.5   392.9  6729.9  394.52  6757.7  394.13  6990.2  411.85
  7077.7  415.78  7188.2   415.7  7410.2  421.67  7487.1  421.75  7941.8  420.45
#Mann= 9 ,-1 , 0
    2645     .05       0  5653.3    .035       0  5659.3     .05       0
  5730.1     .16       0  6389.2     .12       0  6497.6     .05       0
  6610.2     .16       0  6990.2     .12       0  7487.1     .05       0
Bank Sta=5653.3,5659.3
XS Rating Curve= 0 ,0
Exp/Cntr=0.3,0.1

Chan Stop Cuts=-1
Use User Specified Reach Order=0
Composite Channel Slope=5