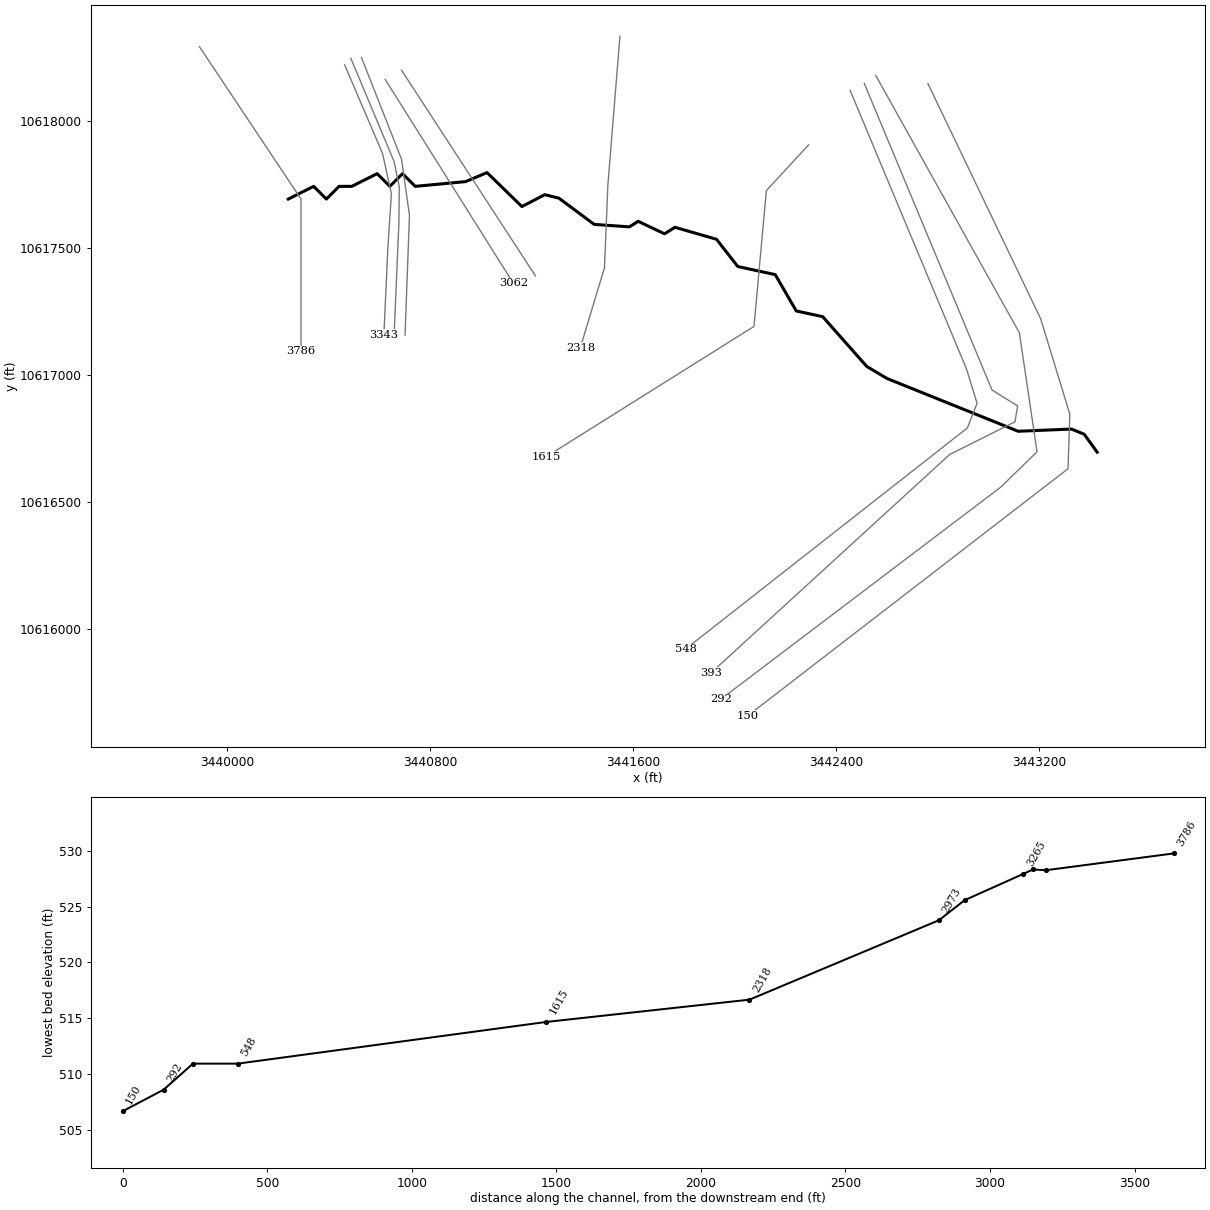
--- UNT00680 IN CHRS.prj (project) ---

Proj Title=UNT00680 IN CHRS Base Level Engineering
Current Plan=p01
Default Exp/Contr=0.3,0.1
English Units
Geom File=g01
Flow File=f01
Plan File=p01
Y Axis Title=Elevation
X Axis Title(PF)=Main Channel Distance
X Axis Title(XS)=Station
BEGIN DESCRIPTION:
UNT00680 IN CHRS
END DESCRIPTION:
DSS Export Rating Curves= 0
DSS Export Rating Curve Sorted= 0
DSS Export Volume Flow Curves= 0
DXF OffsetX= 0
DXF OffsetY= 0
DXF ScaleX= 1
DXF ScaleY= 10

--- UNT00680 IN CHRS.p01 (plan) ---

Plan Title=Multiple Run
Short Identifier=Multiple
Geom File=g01
Flow File=f01
Subcritical Flow
K Sum by GR= 0
Std Step Tol= 0.01
Critical Tol= 0.01
Num of Std Step Trials= 20
Max Error Tol= 0.3
Flow Tol Ratio= 0.001
Split Flow NTrial= 30
Split Flow Tol= 0.02
Split Flow Ratio= 0.02
Log Output Level= 0
Friction Slope Method= 1
Unsteady Friction Slope Method= 2
Unsteady Bridges Friction Slope Method= 1
Parabolic Critical Depth
Global Vel Dist=  1 , 1 , 1
Global Log Level= 0
CheckData=True
Encroach Param= -1, 0, 0, 0
BEGIN DESCRIPTION:
Multiple Run
END DESCRIPTION:

--- UNT00680 IN CHRS.f01 (steady flow) ---

Flow Title=Multiple
Number of Profiles=7
Profile Names=10-year,25-year,50-year,1pct_min,100-year,1pct_plu,500-year
River Rch & RM= UNT00680 IN CHRS,Reach-1,3786
     175     208     231     187     253     342     302
River Rch & RM= UNT00680 IN CHRS,Reach-1,292
     598     757     873     732     989    1338    1268
Boundary for River Rch & Prof#=UNT00680 IN CHRS,Reach-1,1
Up Type=0
Dn Type=3
Dn Slope=0.005
Boundary for River Rch & Prof#=UNT00680 IN CHRS,Reach-1,2
Up Type=0
Dn Type=3
Dn Slope=0.005
Boundary for River Rch & Prof#=UNT00680 IN CHRS,Reach-1,3
Up Type=0
Dn Type=3
Dn Slope=0.005
Boundary for River Rch & Prof#=UNT00680 IN CHRS,Reach-1,4
Up Type=0
Dn Type=3
Dn Slope=0.005
Boundary for River Rch & Prof#=UNT00680 IN CHRS,Reach-1,5
Up Type=0
Dn Type=3
Dn Slope=0.005
Boundary for River Rch & Prof#=UNT00680 IN CHRS,Reach-1,6
Up Type=0
Dn Type=3
Dn Slope=0.005
Boundary for River Rch & Prof#=UNT00680 IN CHRS,Reach-1,7
Up Type=0
Dn Type=3
Dn Slope=0.005

--- UNT00680 IN CHRS.g01 (geometry) ---

Geom Title=Existing Conditions
Program Version=4.10

River Reach=UNT00680 IN CHRS,Reach-1
Reach XY= 30
      3440242.11     10617691.64      3440342.11     10617741.64
      3440392.11     10617691.64      3440442.11     10617741.64
      3440492.11     10617741.64      3440592.11     10617791.64
      3440642.11     10617741.64      3440692.11     10617791.64
      3440742.11     10617741.64      3440940.28     10617760.32
      3441024.98     10617795.76      3441162.13     10617662.08
      3441252.41     10617708.96      3441307.97     10617695.07
      3441446.95     10617591.84      3441585.49     10617582.12
      3441620.21     10617603.99      3441724.03     10617554.69
        3441765.     10617580.38      3441928.89     10617533.16
      3442012.57     10617425.87      3442160.14     10617393.93
      3442242.86     10617250.91      3442347.03     10617228.35
      3442520.64     10617032.16      3442601.37     10616984.42
        3443117.     10616776.96      3443327.07     10616785.64
      3443377.08     10616765.24      3443428.04     10616694.61

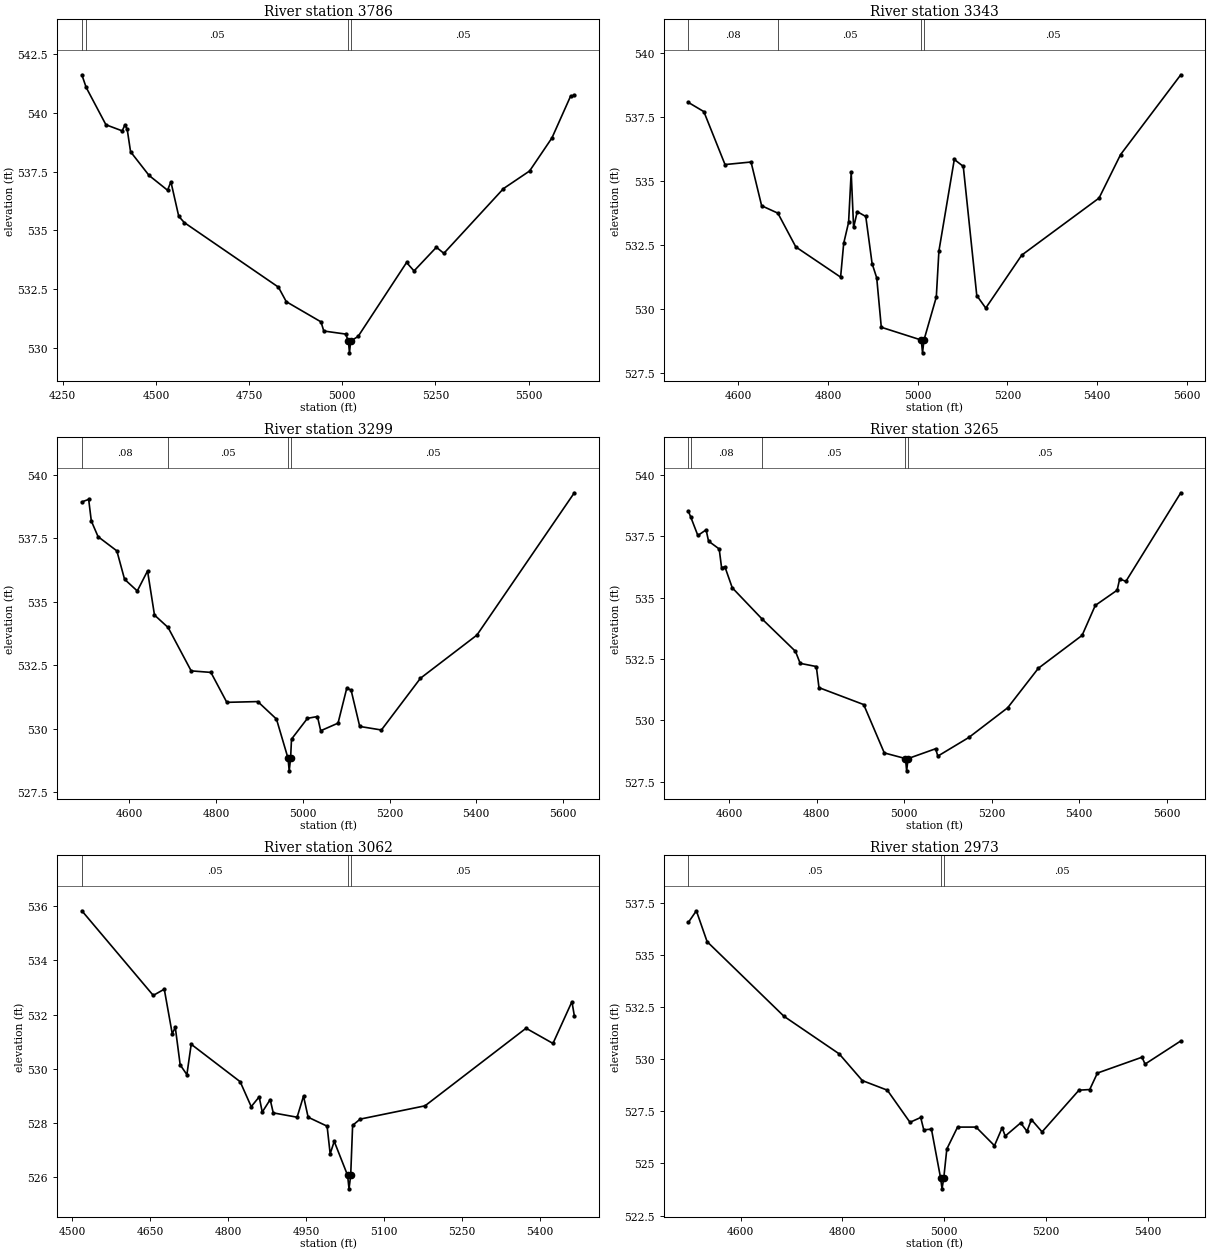
Type RM Length L Ch R = 1 ,3786    ,443,443,443
BEGIN DESCRIPTION:
UNT00680 IN CHRS 7.0
END DESCRIPTION:
XS GIS Cut Line= 3
      3439892.09     10618291.66      3440292.11     10617691.64
      3440292.11     10617091.68
#Sta/Elev= 30
  4301.4  541.63    4313  541.09    4366   539.5  4409.6  539.24  4417.1   539.5
  4423.1   539.3  4432.1  538.35  4481.7  537.34  4531.3  536.71  4540.3  537.07
  4561.3   535.6  4576.3  535.33  4828.7  532.58  4849.8  531.96  4942.9   531.1
  4950.4  530.71    5009  530.58  5016.5  530.28  5019.3  529.78  5022.5  530.28
  5042.5  530.48  5172.5  533.63  5192.5  533.27  5252.5  534.28  5272.5  534.02
  5432.5  536.78  5502.5  537.53  5562.5  538.94  5612.5  540.72  5622.5  540.75
#Mann= 4 ,-1 , 0
  4301.4     .08       0    4313     .05       0  5016.5    .035       0
  5022.5     .05       0
Bank Sta=5016.5,5022.5
XS Rating Curve= 0 ,0
Exp/Cntr=0.3,0.1

Type RM Length L Ch R = 1 ,3343    ,44,44,44
BEGIN DESCRIPTION:
UNT00680 IN CHRS 6.2
END DESCRIPTION:
XS GIS Cut Line= 5
      3440464.15     10618220.01      3440613.44     10617871.08
      3440648.17     10617711.36      3440634.28     10617499.55
      3440618.65     10617157.54
#Sta/Elev= 30
  4488.7  538.06  4523.3   537.7  4570.5  535.63  4628.5  535.73  4652.1  534.02
  4688.3  533.73  4728.3  532.41  4828.1  531.23    4835  532.55  4845.9  533.37
  4851.7  535.33  4857.1  533.17  4865.2  533.79  4884.2   533.6  4898.3  531.76
  4908.6   531.2  4918.8  529.27  5007.9  528.77  5010.7  528.27  5013.9  528.77
  5041.4  530.45  5047.2  532.25  5081.5  535.83  5101.5  535.56  5131.6  530.51
  5151.6  530.02  5231.8  532.09  5404.1  534.32  5452.1  536.02  5586.3  539.14
#Mann= 4 ,-1 , 0
  4488.7     .08       0  4688.3     .05       0  5007.9    .035       0
  5013.9     .05       0
Bank Sta=5007.9,5013.9
XS Rating Curve= 0 ,0
Exp/Cntr=0.3,0.1

Type RM Length L Ch R = 1 ,3299    ,34,34,34
BEGIN DESCRIPTION:
UNT00680 IN CHRS 6.0
END DESCRIPTION:
XS GIS Cut Line= 5
      3440488.44      10618246.1      3440658.58     10617839.83
      3440679.42     10617739.14      3440677.68     10617596.78
      3440658.58     10617147.14
#Sta/Elev= 30
  4490.4  538.94  4506.1  539.04  4512.2  538.19  4527.8  537.57  4571.1  537.01
  4588.9  535.89  4618.2  535.43  4641.9  536.22  4657.9  534.48  4689.3  533.99
  4742.5  532.28    4788  532.22  4824.7  531.04  4896.1  531.07  4939.2  530.38
  4965.8  528.84  4968.6  528.34  4971.8  528.84  4973.9  529.59  5010.7  530.41
  5033.7  530.48  5041.2  529.92  5081.2  530.22  5101.2  531.59  5111.2  531.53
  5131.2  530.09  5181.2  529.95  5271.3  531.99  5401.4  533.69  5626.1   539.3
#Mann= 4 ,-1 , 0
  4490.4     .08       0  4689.3     .05       0  4965.8    .035       0
  4971.8     .05       0
Bank Sta=4965.8,4971.8
XS Rating Curve= 0 ,0
Exp/Cntr=0.3,0.1

Type RM Length L Ch R = 1 ,3265    ,203,203,203
BEGIN DESCRIPTION:
UNT00680 IN CHRS 6.1
END DESCRIPTION:
XS GIS Cut Line= 4
      3440530.13     10618249.51       3440688.1     10617848.51
      3440719.35     10617628.03        3440702.     10617156.23
#Sta/Elev= 30
  4506.8  538.52  4512.4  538.28  4528.6  537.53  4547.5  537.76    4553   537.3
  4577.4  536.98  4582.8  536.22  4590.5  536.25  4607.2   535.4  4674.7  534.14
  4751.7  532.81  4762.5  532.32  4799.4  532.19  4805.5  531.33  4907.7  530.64
  4954.8  528.67  5003.2  528.44  5005.9  527.94  5009.2  528.44  5072.1  528.84
  5077.2  528.54  5148.1   529.3  5236.9  530.51    5307  532.12    5407  533.46
  5437.1  534.68  5487.1   535.3  5492.9  535.76  5507.1  535.66  5632.6  539.27
#Mann= 5 ,-1 , 0
  4506.8     .05       0  4512.4     .08       0  4674.7     .05       0
  5003.2    .035       0  5009.2     .05       0
Bank Sta=5003.2,5009.2
XS Rating Curve= 0 ,0
Exp/Cntr=0.3,0.1

Type RM Length L Ch R = 1 ,3062    ,89,89,89
BEGIN DESCRIPTION:
UNT00680 IN CHRS 5.1
END DESCRIPTION:
XS GIS Cut Line= 2
      3440623.85     10618162.76       3441128.1     10617360.47
#Sta/Elev= 30
    4518  535.83  4655.4  532.71  4676.6  532.94  4691.9   531.3  4697.8  531.53
  4707.2  530.15  4720.1  529.79  4728.4  530.91  4822.6  529.53  4843.9  528.61
  4859.2  528.97  4865.1  528.41  4880.4  528.87  4886.3  528.38  4932.2  528.22
  4944.5     529  4953.4  528.22  4989.9  527.89  4995.8  526.87  5003.6  527.33
  5029.3  526.08  5032.1  525.58  5035.3  526.08    5039  527.92  5053.5  528.15
  5178.3  528.64  5372.7   531.5  5424.5  530.94    5461  532.48  5465.6  531.96
#Mann= 3 ,-1 , 0
    4518     .05       0  5029.3    .035       0  5035.3     .05       0
Bank Sta=5029.3,5035.3
XS Rating Curve= 0 ,0
Exp/Cntr=0.3,0.1

Type RM Length L Ch R = 1 ,2973    ,655,655,655
BEGIN DESCRIPTION:
UNT00680 IN CHRS 5.0
END DESCRIPTION:
XS GIS Cut Line= 2
      3440688.08     10618199.23      3441215.85     10617388.48
#Sta/Elev= 30
  4497.2  536.55    4513  537.11  4534.1  535.63  4685.2  532.05  4793.6  530.25
    4839  528.97  4888.1  528.51  4932.6  526.97  4953.7   527.2  4959.7  526.61
  4974.8  526.64  4992.9  524.28  4995.6  523.78  4998.9  524.28    5005  525.69
  5026.1  526.74  5062.4  526.74  5098.6  525.85  5113.7  526.71  5119.7  526.31
    5150  526.94  5162.5  526.54  5171.1   527.1  5192.1  526.51  5264.6  528.51
  5285.7  528.54  5300.8  529.33  5388.4  530.09  5394.4  529.76  5464.6  530.87
#Mann= 3 ,-1 , 0
  4497.2     .05       0  4992.9     .04       0  4998.9     .05       0
Bank Sta=4992.9,4998.9
XS Rating Curve= 0 ,0
Exp/Cntr=0.3,0.1

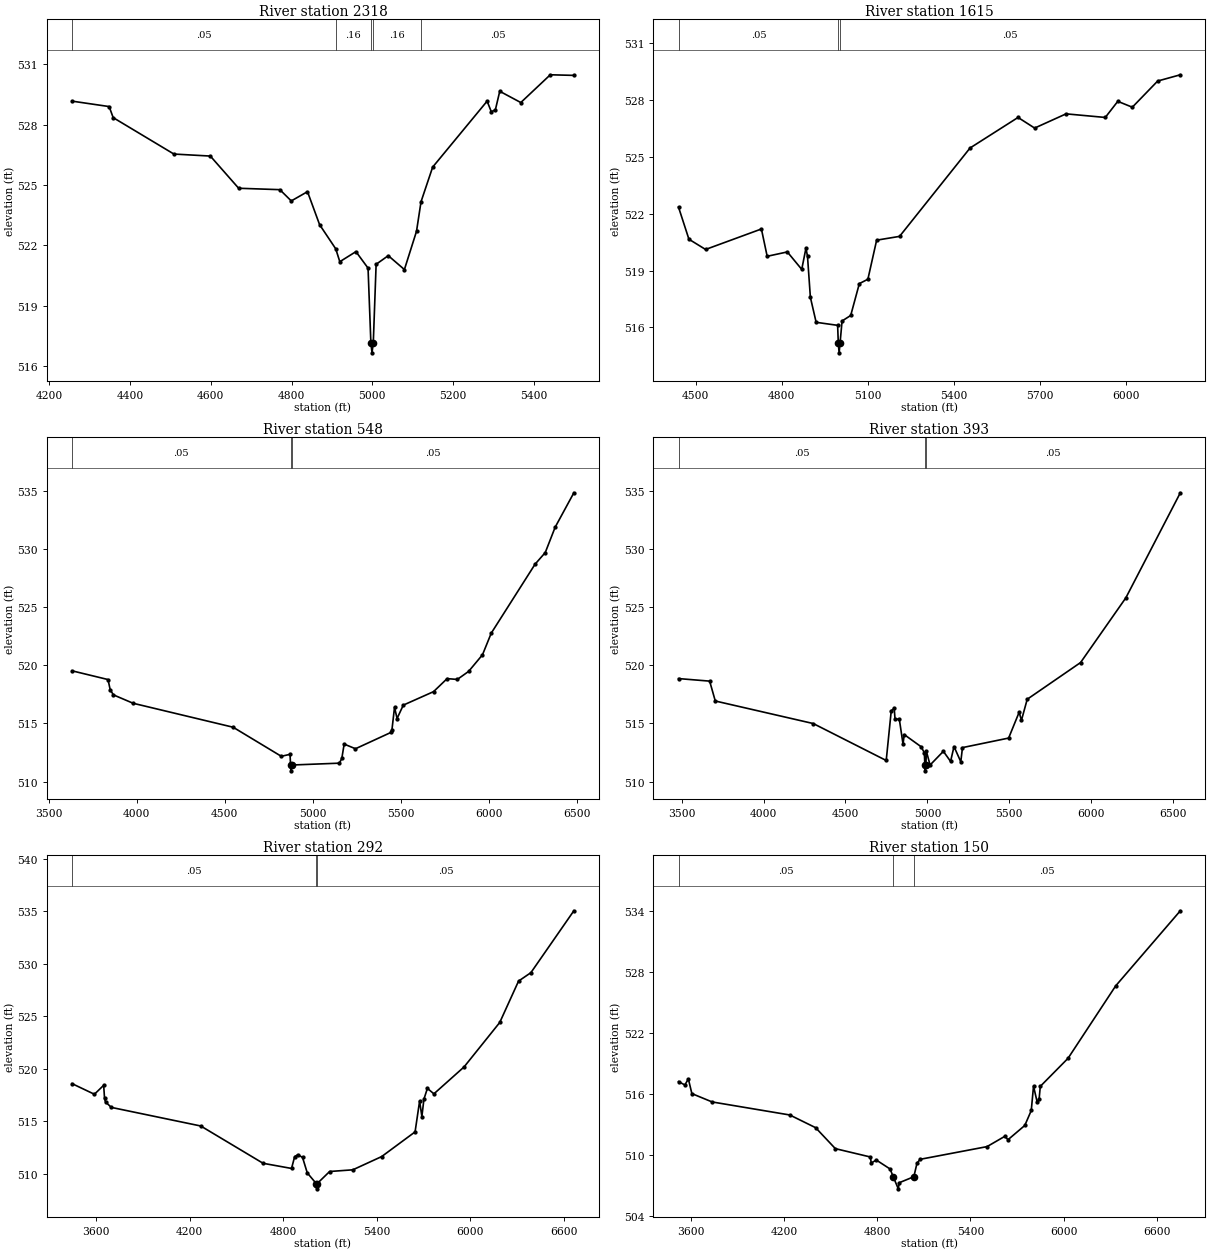
Type RM Length L Ch R = 1 ,2318    ,703,703,703
BEGIN DESCRIPTION:
UNT00680 IN CHRS 3.0
END DESCRIPTION:
XS GIS Cut Line= 4
      3441548.36     10618333.22      3441500.62     10617742.94
       3441487.6     10617421.76      3441392.36     10617105.75
#Sta/Elev= 30
    4256  529.17  4347.9   528.9  4357.9  528.35  4508.4  526.54  4598.7  526.44
  4668.9  524.84    4771  524.77  4799.3  524.21  4839.5  524.67  4869.5  523.03
  4909.5  521.83  4919.6  521.19  4959.6  521.69  4989.6  520.87  4996.6  517.16
  4999.4  516.66  5002.6  517.16  5009.6  521.06  5039.7  521.49  5079.7   520.8
  5109.7   522.7  5120.9  524.17  5149.7  525.89  5284.7  529.17  5295.1  528.64
  5305.2  528.74    5316  529.66  5368.2   529.1  5441.3  530.48  5499.7  530.45
#Mann= 5 ,-1 , 0
    4256     .05       0  4909.5     .16       0  4996.6     .07       0
  5002.6     .16       0  5120.9     .05       0
Bank Sta=4996.6,5002.6
XS Rating Curve= 0 ,0
Exp/Cntr=0.3,0.1

Type RM Length L Ch R = 1 ,1615    ,1067,1067,1067
BEGIN DESCRIPTION:
UNT00680 IN CHRS 2.0
END DESCRIPTION:
XS GIS Cut Line= 4
      3442291.68     10617905.23      3442125.04     10617724.71
      3442076.43     10617189.99      3441257.46     10616676.39
#Sta/Elev= 30
  4440.3  522.34  4476.5  520.65  4534.6  520.11  4729.2  521.19  4749.3  519.75
  4819.6  519.98  4869.8  519.06  4884.5  520.18  4889.9  519.75  4899.9  517.59
    4920  516.27  4994.9  516.11  4997.3  515.16  5000.1  514.66  5003.3  515.16
  5010.4  516.34  5040.5  516.63  5070.6  518.31  5100.4  518.54  5130.9   520.6
  5210.8   520.8  5456.6  525.46  5623.9  527.07  5681.7  526.51  5791.3  527.26
    5928  527.07  5971.6  527.92  6022.2  527.61  6110.6  528.99  6189.6  529.32
#Mann= 3 ,-1 , 0
  4440.3     .05       0  4997.3    .035       0  5003.3     .05       0
Bank Sta=4997.3,5003.3
XS Rating Curve= 0 ,0
Exp/Cntr=0.3,0.1

Type RM Length L Ch R = 1 ,548     ,155,155,155
BEGIN DESCRIPTION:
UNT00680 IN CHRS 1.2
END DESCRIPTION:
XS GIS Cut Line= 5
      3442455.05      10618119.8      3442913.38     10617022.59
      3442955.05     10616887.17      3442916.85     10616789.95
      3441806.42     10615918.96
#Sta/Elev= 30
  3633.5  519.52  3837.4  518.77    3850  517.88  3868.4  517.45  3979.9  516.73
  4547.1  514.67  4820.4  512.17    4870  512.34  4872.9  511.42  4875.6  510.92
  4878.9  511.42  5149.9  511.58  5163.7  511.99    5177  513.22  5241.2  512.82
  5441.9  514.22  5448.2  514.46  5462.7  516.39  5477.1  515.42  5512.4  516.57
  5684.1  517.73  5761.1  518.85  5818.8  518.78    5883  519.47  5961.7   520.9
  6011.4  522.76    6260  528.69  6317.8  529.69  6373.9  531.87    6480  534.83
#Mann= 3 ,-1 , 0
  3633.5     .05       0  4872.9    .033       0  4878.9     .05       0
Bank Sta=4872.9,4878.9
XS Rating Curve= 0 ,0
Exp/Cntr=0.3,0.1

Type RM Length L Ch R = 1 ,393     ,101,101,101
BEGIN DESCRIPTION:
UNT00680 IN CHRS 1.1
END DESCRIPTION:
XS GIS Cut Line= 6
      3442510.59     10618147.61      3443014.08     10616939.26
      3443114.77     10616876.76      3443104.35     10616814.26
      3442847.41     10616685.78      3441907.83     10615825.95
#Sta/Elev= 30
  3481.4  518.86  3671.3  518.64  3705.7  516.93  4303.5  514.99  4748.7  511.81
  4779.3  516.08  4797.4  516.31  4802.7  515.35  4828.4  515.39  4851.3  513.22
  4858.6  514.04  4962.1  512.99  4981.4  512.47  4984.5  511.42  4987.3  510.92
  4990.5  511.42  4993.9   512.6  5016.3  511.42  5097.4   512.6  5141.4  511.73
  5162.3  513.01  5203.8   511.7  5214.1  512.92  5495.7  513.74  5559.8  515.96
    5574  515.27  5609.1  517.08  5934.7  520.24    6211  525.81  6543.4  534.85
#Mann= 3 ,-1 , 0
  3481.4     .05       0  4984.5    .033       0  4990.5     .05       0
Bank Sta=4984.5,4990.5
XS Rating Curve= 0 ,0
Exp/Cntr=0.3,0.1

Type RM Length L Ch R = 1 ,292     ,142,142,142
BEGIN DESCRIPTION:
UNT00680 IN CHRS 1.9
END DESCRIPTION:
XS GIS Cut Line= 5
      3442555.75     10618178.83      3443121.71     10617164.95
      3443191.16      10616696.2       3443048.8     10616557.31
      3441945.85     10615721.43
#Sta/Elev= 30
  3445.9   518.6  3589.1  517.59  3648.5  518.44  3654.2  517.19  3660.3  516.86
  3697.6  516.34  4271.2  514.57    4671  511.02  4853.3  510.53  4873.2  511.65
  4893.4  511.84  4923.8  511.58  4954.1  510.11  5011.8  509.09  5014.5  508.59
  5017.8  509.09  5097.6  510.24  5246.2   510.4  5431.2  511.66  5645.5  514.01
  5674.6  516.95  5689.1  515.47  5702.3  517.13  5724.5  518.15  5766.2  517.63
  5959.6  520.19  6188.4  524.42  6309.1  528.36  6388.1  529.16  6663.7  535.05
#Mann= 3 ,-1 , 0
  3445.9     .05       0  5011.8    .035       0  5017.8     .05       0
Bank Sta=5011.8,5017.8
XS Rating Curve= 0 ,0
Exp/Cntr=0.3,0.1

Type RM Length L Ch R = 1 ,150     ,0,0,0
BEGIN DESCRIPTION:
UNT00680 IN CHRS 1.0
END DESCRIPTION:
XS GIS Cut Line= 5
      3442761.31     10618146.81      3443205.75     10617219.74
      3443320.33     10616844.74      3443313.39     10616629.46
      3442052.98     10615657.25
#Sta/Elev= 30
  3522.4  517.19  3562.9  516.86  3585.6  517.45  3608.2  516.01  3738.6  515.19
  4237.9  513.91  4404.2  512.66  4531.1   510.6  4756.4  509.78  4761.7  509.19
  4794.5  509.48  4883.1   508.6    4904  507.81  4935.8  506.65  4941.6  507.25
  5035.8  507.84  5055.8  509.15  5075.8  509.55  5506.7   510.8  5620.8  511.81
  5641.6  511.48  5749.5  512.88  5791.1  514.35  5805.6  516.74  5828.3  515.23
  5841.6  515.47  5849.1  516.72  6027.6  519.48  6334.1   526.6  6749.8  533.98
#Mann= 3 , 0 , 0
  3522.4     .05       0    4904    .035       0  5035.8     .05       0
Bank Sta=4904,5035.8
XS Rating Curve= 0 ,0
Exp/Cntr=0.3,0.1

Chan Stop Cuts=-1
Use User Specified Reach Order=0
Composite Channel Slope=5