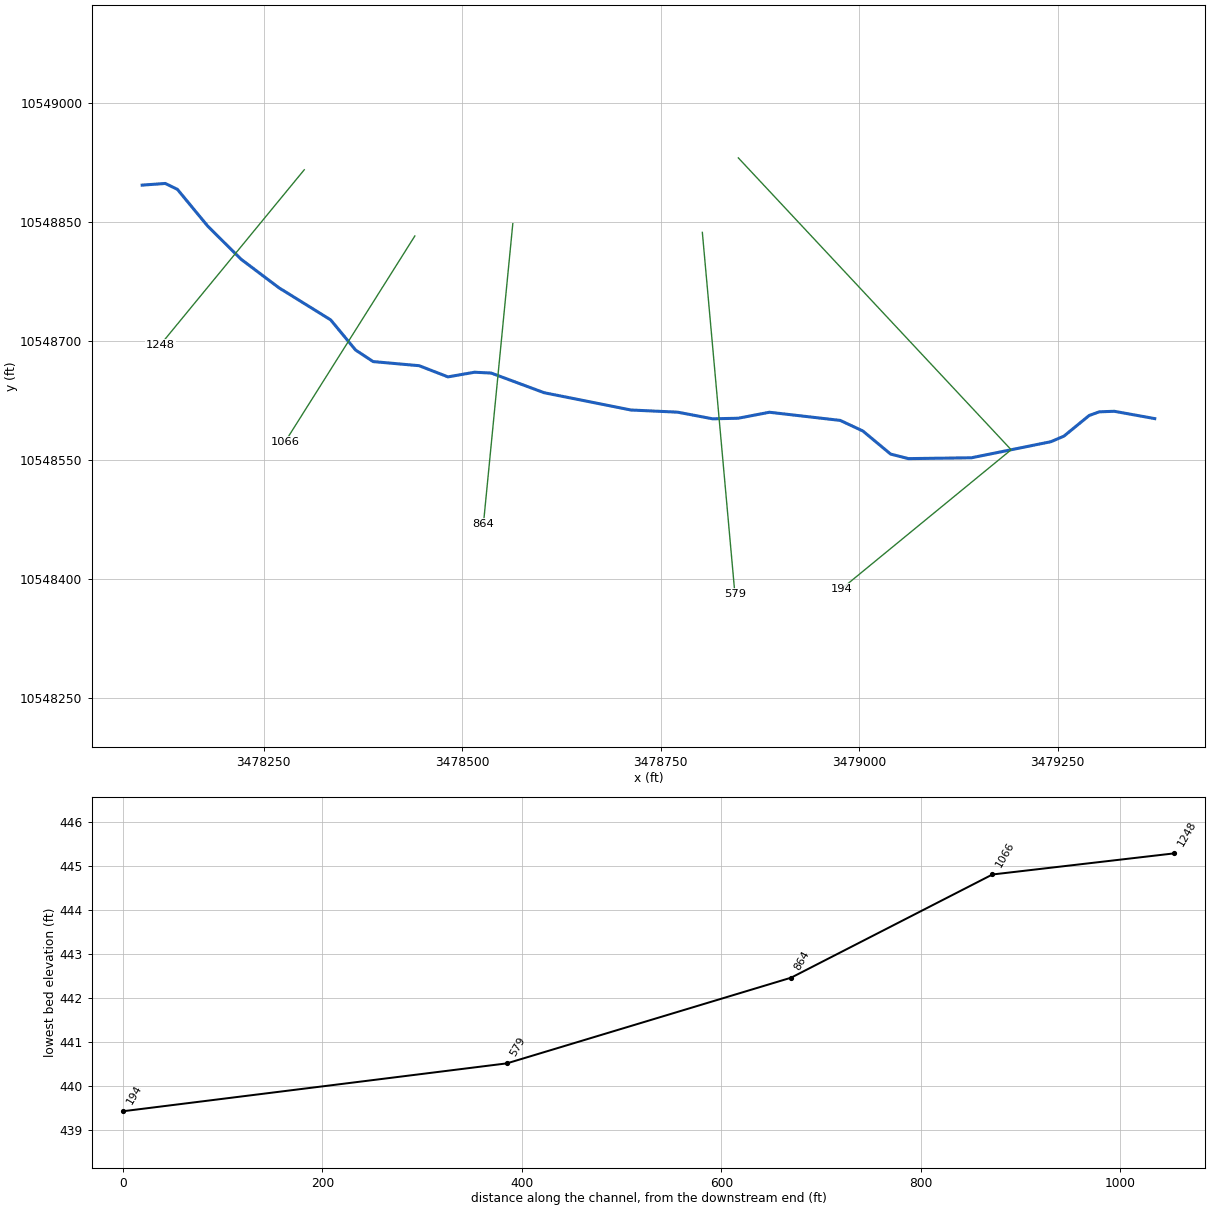
--- UNT0069 IN CHRS.prj (project) ---

Proj Title=UNT0069 IN CHRS Base Level Engineering
Current Plan=p01
Default Exp/Contr=0.3,0.1
English Units
Geom File=g01
Flow File=f01
Plan File=p01
Y Axis Title=Elevation
X Axis Title(PF)=Main Channel Distance
X Axis Title(XS)=Station
BEGIN DESCRIPTION:
UNT0069 IN CHRS
END DESCRIPTION:
DSS Export Rating Curves= 0
DSS Export Rating Curve Sorted= 0
DSS Export Volume Flow Curves= 0
DXF OffsetX= 0
DXF OffsetY= 0
DXF ScaleX= 1
DXF ScaleY= 10

--- UNT0069 IN CHRS.p01 (plan) ---

Plan Title=Multiple Run
Short Identifier=Multiple
Geom File=g01
Flow File=f01
Subcritical Flow
K Sum by GR= 0
Std Step Tol= 0.01
Critical Tol= 0.01
Num of Std Step Trials= 20
Max Error Tol= 0.3
Flow Tol Ratio= 0.001
Split Flow NTrial= 30
Split Flow Tol= 0.02
Split Flow Ratio= 0.02
Log Output Level= 0
Friction Slope Method= 1
Unsteady Friction Slope Method= 2
Unsteady Bridges Friction Slope Method= 1
Parabolic Critical Depth
Global Vel Dist=  1 , 1 , 1
Global Log Level= 0
CheckData=True
Encroach Param= -1, 0, 0, 0
BEGIN DESCRIPTION:
Multiple Run
END DESCRIPTION:

--- UNT0069 IN CHRS.f01 (steady flow) ---

Flow Title=Multiple
Number of Profiles=7
Profile Names=10-year,25-year,50-year,1pct_min,100-year,1pct_plu,500-year
River Rch & RM= UNT0069 IN CHRS,Reach-1,1248
     431     539     618     516     697     943     886
Boundary for River Rch & Prof#=UNT0069 IN CHRS,Reach-1,1
Up Type=0
Dn Type=3
Dn Slope=0.005
Boundary for River Rch & Prof#=UNT0069 IN CHRS,Reach-1,2
Up Type=0
Dn Type=3
Dn Slope=0.005
Boundary for River Rch & Prof#=UNT0069 IN CHRS,Reach-1,3
Up Type=0
Dn Type=3
Dn Slope=0.005
Boundary for River Rch & Prof#=UNT0069 IN CHRS,Reach-1,4
Up Type=0
Dn Type=3
Dn Slope=0.005
Boundary for River Rch & Prof#=UNT0069 IN CHRS,Reach-1,5
Up Type=0
Dn Type=3
Dn Slope=0.005
Boundary for River Rch & Prof#=UNT0069 IN CHRS,Reach-1,6
Up Type=0
Dn Type=3
Dn Slope=0.005
Boundary for River Rch & Prof#=UNT0069 IN CHRS,Reach-1,7
Up Type=0
Dn Type=3
Dn Slope=0.005

--- UNT0069 IN CHRS.g01 (geometry) ---

Geom Title=Existing Conditions
Program Version=4.10

River Reach=UNT0069 IN CHRS ,Reach-1
Reach XY= 30
      3478097.12     10548896.16      3478126.27     10548898.24
      3478141.54     10548890.75      3478179.82     10548844.35
      3478221.79      10548802.7      3478269.52     10548766.75
      3478334.47     10548726.47      3478365.88     10548688.47
      3478387.98     10548673.89      3478445.99     10548668.71
      3478482.26     10548654.63      3478515.75     10548660.49
       3478536.7     10548659.44      3478603.35      10548634.7
      3478712.63     10548612.91      3478771.54     10548610.18
      3478815.62     10548601.82      3478847.74     10548602.53
      3478887.12     10548610.08      3478976.32     10548599.79
      3479004.71     10548586.55      3479039.78     10548557.38
      3479062.17     10548551.68      3479141.59     10548552.73
      3479241.58     10548572.97       3479258.1     10548580.03
      3479289.84       10548606.      3479302.56     10548610.62
      3479321.43      10548611.3      3479372.48     10548602.07

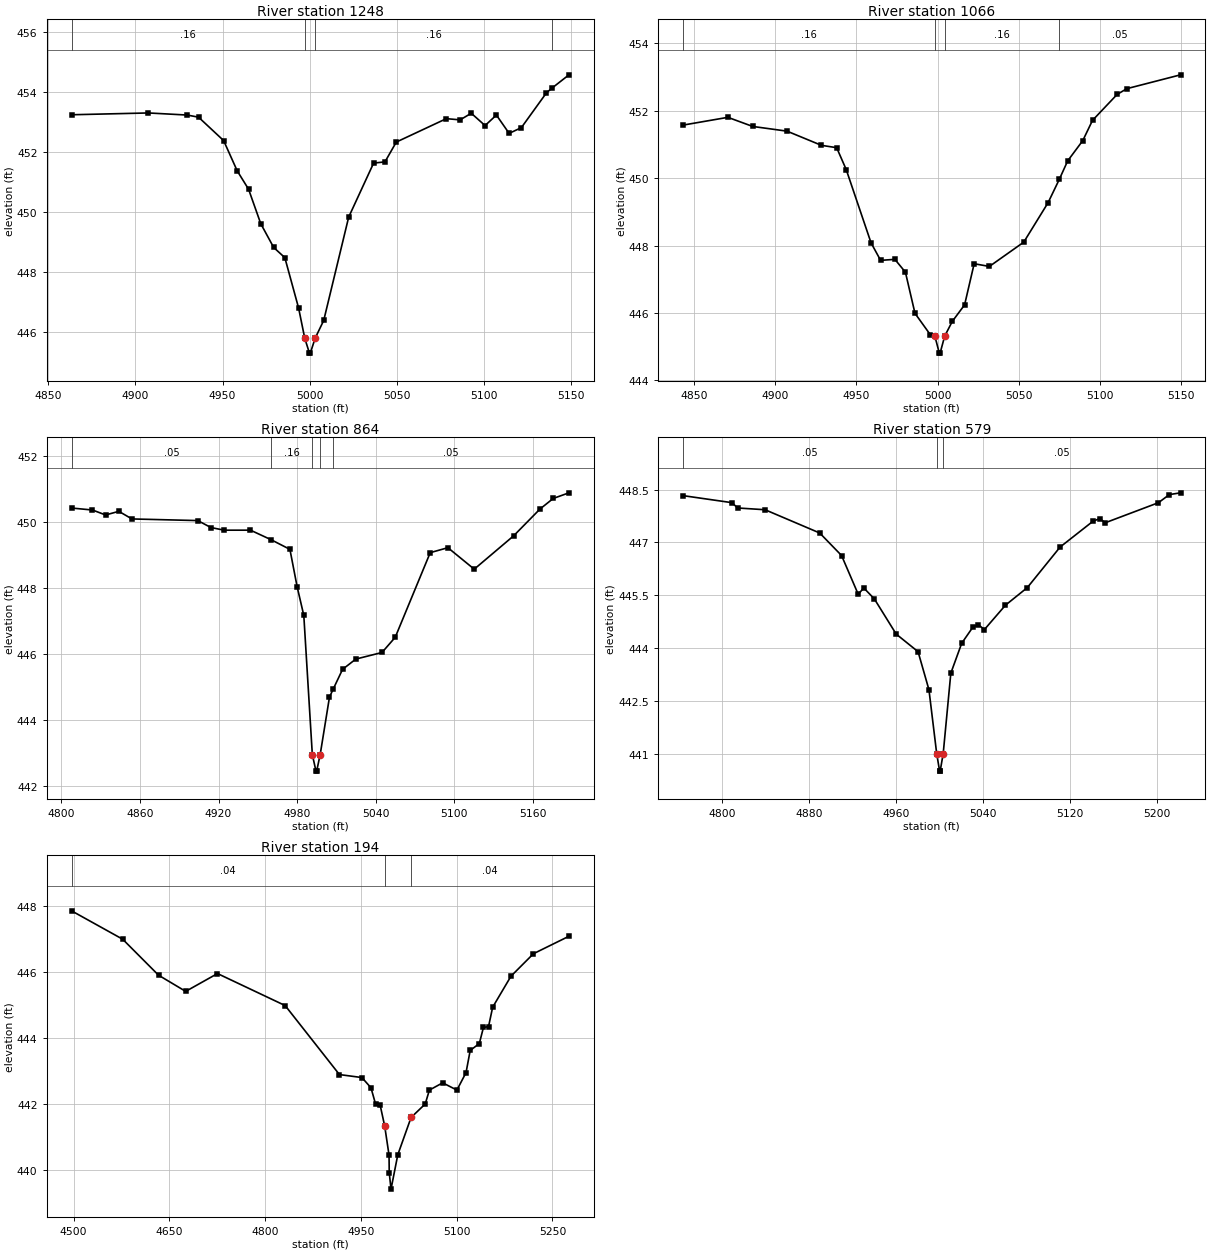
Type RM Length L Ch R = 1 ,1248    ,182,182,182
BEGIN DESCRIPTION:
UNT0069 IN CHRS 1.4
END DESCRIPTION:
XS GIS Cut Line= 2
      3478301.24     10548915.46      3478120.16     10548695.12
#Sta/Elev= 30
  4863.4  453.23  4907.5  453.29  4929.7  453.22  4936.2  453.15  4950.6  452.37
  4958.4  451.36  4964.9  450.75  4971.9   449.6  4979.3  448.81  4985.7  448.47
  4993.6  446.79  4997.1  445.79  4999.8  445.29  5000.3  445.29  5003.1  445.79
    5008  446.38  5022.3  449.82  5036.6  451.62  5043.1  451.66  5049.6  452.32
  5078.3   453.1  5086.2  453.06  5092.6  453.28  5100.5  452.87    5107  453.22
  5114.3  452.61  5121.3   452.8  5135.7  453.96  5138.7  454.11  5148.6  454.56
#Mann= 4 ,-1 , 0
  4863.4     .16       0  4997.1     .07       0  5003.1     .16       0
  5138.7     .05       0
Bank Sta=4997.1,5003.1
XS Rating Curve= 0 ,0
Exp/Cntr=0.3,0.1

Type RM Length L Ch R = 1 ,1066    ,202,202,202
BEGIN DESCRIPTION:
UNT0069 IN CHRS 1.3
END DESCRIPTION:
XS GIS Cut Line= 2
      3478440.54      10548832.1      3478276.94     10548572.55
#Sta/Elev= 30
  4843.1  451.57  4870.7   451.8    4886  451.53  4907.2  451.39  4928.4  450.97
  4937.8   450.9  4943.7  450.25    4959  448.08  4964.9  447.56  4973.7  447.59
  4980.2  447.21  4986.1  445.99  4995.5  445.36  4998.4  445.31  5001.1  444.81
  5001.6  444.81  5004.4  445.31  5009.1  445.75  5016.7  446.24  5022.6  447.46
    5032  447.38  5053.2   448.1  5068.2  449.27  5075.1  449.96  5080.3  450.51
  5089.6  451.11  5095.6  451.71  5110.8  452.48  5116.8  452.65  5149.9  453.06
#Mann= 4 ,-1 , 0
  4843.1     .16       0  4998.4     .07       0  5004.4     .16       0
  5075.1     .05       0
Bank Sta=4998.4,5004.4
XS Rating Curve= 0 ,0
Exp/Cntr=0.3,0.1

Type RM Length L Ch R = 1 ,864     ,285,285,285
BEGIN DESCRIPTION:
UNT0069 IN CHRS 1.2
END DESCRIPTION:
XS GIS Cut Line= 2
      3478563.92     10548847.57      3478526.96     10548469.67
#Sta/Elev= 30
  4807.8  450.42  4823.8  450.36  4833.8  450.21  4843.9  450.32  4853.9  450.09
  4904.2  450.04  4914.2  449.83  4924.3  449.75  4944.4  449.75  4960.2  449.46
  4974.5  449.17    4980  448.04  4985.1  447.17  4991.6  442.96  4994.4  442.46
  4994.9  442.46  4997.6  442.96  5004.7   444.7  5007.4  444.93  5014.7  445.54
  5024.8  445.85  5044.8  446.05  5054.9  446.51  5081.6  449.07  5095.1  449.22
  5115.2  448.57  5145.3  449.58  5165.4  450.39  5175.5  450.71  5187.5  450.88
#Mann= 5 ,-1 , 0
  4807.8     .05       0  4960.2     .16       0  4991.6     .07       0
  4997.6     .16       0  5007.4     .05       0
Bank Sta=4991.6,4997.6
XS Rating Curve= 0 ,0
Exp/Cntr=0.3,0.1

Type RM Length L Ch R = 1 ,579     ,385,385,385
BEGIN DESCRIPTION:
UNT0069 IN CHRS 1.1
END DESCRIPTION:
XS GIS Cut Line= 2
      3478802.64     10548836.65      3478843.65     10548381.39
#Sta/Elev= 30
  4764.4  448.33  4809.4  448.13  4814.4  447.98  4839.7  447.93  4889.9  447.27
    4910  446.63  4925.3  445.53  4930.4  445.71  4940.1   445.4  4960.2   444.4
  4980.3   443.9  4990.3  442.82  4997.4  441.01  5000.1  440.51  5000.6  440.51
  5003.4  441.01  5010.4  443.29  5020.4  444.14  5030.5  444.59  5035.5  444.67
  5041.3  444.53  5060.6  445.22  5080.7  445.72  5110.8  446.87  5140.9   447.6
  5147.2  447.68  5152.3  447.56  5201.2  448.13  5211.2  448.36  5221.5  448.41
#Mann= 3 ,-1 , 0
  4764.4     .05       0  4997.4    .035       0  5003.4     .05       0
Bank Sta=4997.4,5003.4
XS Rating Curve= 0 ,0
Exp/Cntr=0.3,0.1

Type RM Length L Ch R = 1 ,194     ,0,0,0
BEGIN DESCRIPTION:
UNT0069 IN CHRS 1.0
END DESCRIPTION:
XS GIS Cut Line= 3
      3478847.96     10548930.45      3479191.58     10548562.85
      3478978.23     10548387.91
#Sta/Elev= 30
  4496.8  447.85  4576.9  446.99  4633.1   445.9  4675.6  445.41  4725.4  445.95
  4831.4  444.98  4916.4  442.89  4951.6   442.8  4965.8  442.49  4973.1  441.99
    4980  441.98  4987.3  441.33  4994.1  440.45  4994.4  439.92  4997.2  439.42
  5007.8  440.46  5028.6  441.59  5050.8     442  5057.3  442.42  5078.1  442.64
  5100.4  442.42  5114.7  442.95  5121.2  443.62  5135.5  443.83    5142  444.32
  5149.9  444.34  5156.4  444.93  5185.1  445.87  5220.2  446.55  5275.9  447.08
#Mann= 3 , 0 , 0
  4496.8     .04       0  4987.3     .03       0  5028.6     .04       0
Bank Sta=4987.3,5028.6
XS Rating Curve= 0 ,0
Exp/Cntr=0.3,0.1

Chan Stop Cuts=-1
Use User Specified Reach Order=0
Composite Channel Slope=5