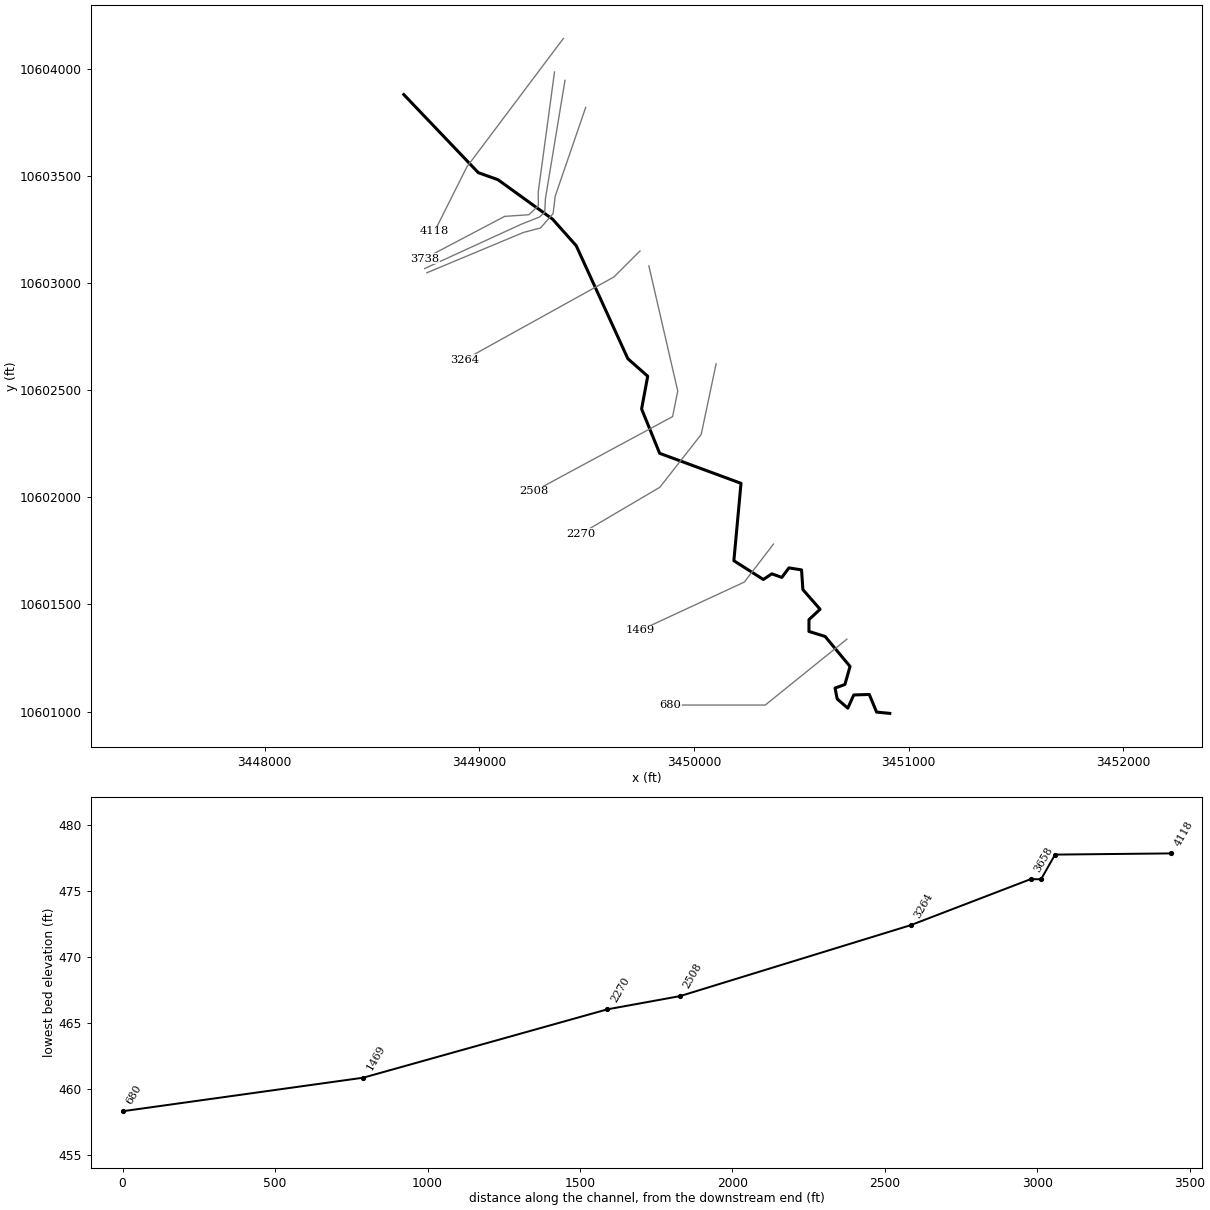
--- UNT00695 IN CHRS.prj (project) ---

Proj Title=UNT00695 IN CHRS Base Level Engineering
Current Plan=p01
Default Exp/Contr=0.3,0.1
English Units
Geom File=g01
Flow File=f01
Plan File=p01
Y Axis Title=Elevation
X Axis Title(PF)=Main Channel Distance
X Axis Title(XS)=Station
BEGIN DESCRIPTION:
UNT00695 IN CHRS
END DESCRIPTION:
DSS Export Rating Curves= 0
DSS Export Rating Curve Sorted= 0
DSS Export Volume Flow Curves= 0
DXF OffsetX= 0
DXF OffsetY= 0
DXF ScaleX= 1
DXF ScaleY= 10

--- UNT00695 IN CHRS.p01 (plan) ---

Plan Title=Multiple Run
Short Identifier=Multiple
Geom File=g01
Flow File=f01
Subcritical Flow
K Sum by GR= 0
Std Step Tol= 0.01
Critical Tol= 0.01
Num of Std Step Trials= 20
Max Error Tol= 0.3
Flow Tol Ratio= 0.001
Split Flow NTrial= 30
Split Flow Tol= 0.02
Split Flow Ratio= 0.02
Log Output Level= 0
Friction Slope Method= 1
Unsteady Friction Slope Method= 2
Unsteady Bridges Friction Slope Method= 1
Parabolic Critical Depth
Global Vel Dist=  1 , 1 , 1
Global Log Level= 0
CheckData=True
Encroach Param= -1, 0, 0, 0
BEGIN DESCRIPTION:
Multiple Run
END DESCRIPTION:

--- UNT00695 IN CHRS.f01 (steady flow) ---

Flow Title=Multiple
Number of Profiles=7
Profile Names=10-year,25-year,50-year,1pct_min,100-year,1pct_plu,500-year
River Rch & RM= UNT00695 IN CHRS,Reach-1,4118
     277     338     381     313     423     572     520
Boundary for River Rch & Prof#=UNT00695 IN CHRS,Reach-1,1
Up Type=0
Dn Type=3
Dn Slope=0.005
Boundary for River Rch & Prof#=UNT00695 IN CHRS,Reach-1,2
Up Type=0
Dn Type=3
Dn Slope=0.005
Boundary for River Rch & Prof#=UNT00695 IN CHRS,Reach-1,3
Up Type=0
Dn Type=3
Dn Slope=0.005
Boundary for River Rch & Prof#=UNT00695 IN CHRS,Reach-1,4
Up Type=0
Dn Type=3
Dn Slope=0.005
Boundary for River Rch & Prof#=UNT00695 IN CHRS,Reach-1,5
Up Type=0
Dn Type=3
Dn Slope=0.005
Boundary for River Rch & Prof#=UNT00695 IN CHRS,Reach-1,6
Up Type=0
Dn Type=3
Dn Slope=0.005
Boundary for River Rch & Prof#=UNT00695 IN CHRS,Reach-1,7
Up Type=0
Dn Type=3
Dn Slope=0.005

--- UNT00695 IN CHRS.g01 (geometry) ---

Geom Title=Existing Conditions
Program Version=4.10

River Reach=UNT00695 IN CHRS,Reach-1
Reach XY= 30
      3448648.26     10603879.26       3448995.4     10603514.84
      3449087.03     10603481.98      3449341.37     10603297.95
      3449451.62     10603173.82      3449692.15     10602646.57
      3449784.55     10602564.85      3449756.11     10602412.27
       3449840.2     10602205.21      3450219.14     10602065.18
      3450185.94       10601704.      3450323.09     10601616.54
      3450362.78     10601642.79       3450409.4     10601626.08
      3450442.44     10601670.54      3450501.21     10601661.16
      3450507.42     10601569.21      3450587.54     10601477.43
      3450535.85     10601429.15       3450535.6     10601374.05
      3450610.98     10601350.61      3450727.07     10601210.58
      3450703.16      10601126.5      3450657.22     10601109.58
      3450667.29     10601059.04      3450716.57     10601015.97
      3450744.48     10601077.65      3450816.84     10601079.84
      3450850.76      10600997.6      3450912.11     10600991.64

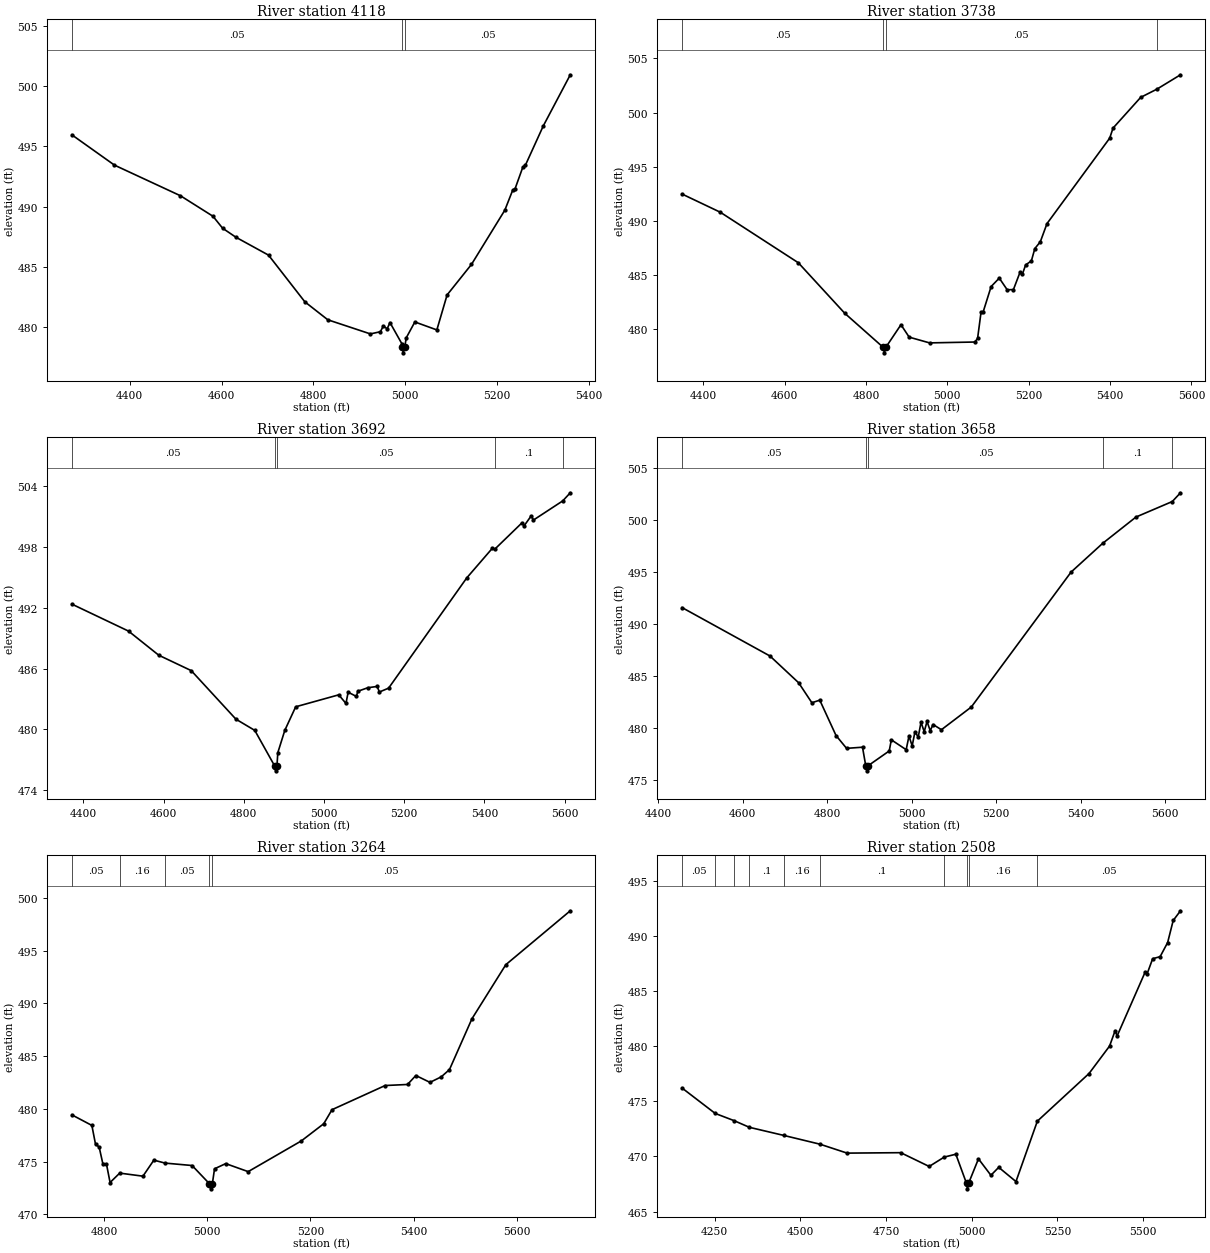
Type RM Length L Ch R = 1 ,4118    ,380,380,380
BEGIN DESCRIPTION:
UNT00695 IN CHRS 3.0
END DESCRIPTION:
XS GIS Cut Line= 3
      3449392.13     10604141.67      3448942.11     10603541.64
      3448792.13     10603241.68
#Sta/Elev= 30
  4273.9  495.94  4366.6  493.43  4510.4  490.89  4581.2  489.19  4602.1   488.2
  4631.2  487.45  4702.1  485.97  4781.2   482.1  4831.2  480.61  4923.9  479.44
  4945.8  479.62  4952.1   480.1  4960.4  479.86  4966.6  480.38  4992.7  478.61
  4992.8  478.37  4995.6  477.87  4998.8  478.37  5002.1  479.12  5020.8  480.43
  5068.7  479.77    5091  482.67  5144.1   485.2  5216.8   489.7  5233.6  491.33
  5239.2  491.49  5255.9  493.26  5261.5  493.42  5300.6  496.69  5359.3  500.92
#Mann= 3 ,-1 , 0
  4273.9     .05       0  4992.8    .035       0  4998.8     .05       0
Bank Sta=4992.8,4998.8
XS Rating Curve= 0 ,0
Exp/Cntr=0.3,0.1

Type RM Length L Ch R = 1 ,3738    ,46,46,46
BEGIN DESCRIPTION:
UNT00695 IN CHRS 2.6
END DESCRIPTION:
XS GIS Cut Line= 6
      3449350.37     10603984.69      3449274.42     10603422.64
       3449275.5      10603360.8      3449231.01     10603318.48
      3449118.17     10603310.88      3448745.47     10603114.27
#Sta/Elev= 30
  4348.1  492.46    4442  490.78  4633.7  486.11  4747.8  481.44  4842.6  478.28
  4845.4  477.78  4848.6  478.28    4886  480.38  4906.2  479.23  4956.3   478.7
  5067.5  478.78  5074.3  479.11  5082.8  481.54  5087.8  481.54  5107.6  483.91
  5127.6  484.69  5147.1  483.61  5162.4  483.63  5178.8  485.25  5184.4  485.05
  5192.4  485.91  5206.5  486.28    5215  487.42  5228.5  488.05  5244.9  489.73
    5399  497.63  5407.2  498.56  5475.1   501.4    5515  502.16    5573  503.49
#Mann= 4 ,-1 , 0
  4348.1     .05       0  4842.6    .035       0  4848.6     .05       0
    5515      .1       0
Bank Sta=4842.6,4848.6
XS Rating Curve= 0 ,0
Exp/Cntr=0.3,0.1

Type RM Length L Ch R = 1 ,3692    ,34,34,34
BEGIN DESCRIPTION:
UNT00695 IN CHRS 2.5
END DESCRIPTION:
XS GIS Cut Line= 6
       3449399.2     10603945.62      3449308.05     10603393.35
       3449304.8     10603329.33      3449279.84     10603307.63
      3449195.21     10603273.99       3448745.5     10603067.52
#Sta/Elev= 30
  4371.3  492.36  4512.5   489.7  4587.9  487.32  4668.9   485.8  4780.3  481.01
  4827.4   479.9  4876.7  476.41  4879.4  475.91  4882.7  476.41  4884.8   477.7
  4902.3  479.91  4929.4  482.23  5036.7  483.41  5054.8  482.56  5060.2  483.67
  5080.9  483.25  5084.2  483.76  5109.2  484.11  5132.6  484.24  5138.1  483.69
  5161.1  484.07    5356  494.95  5419.5  497.86  5425.8  497.78  5493.9  500.39
  5499.4  500.11  5516.9  501.08  5522.4  500.66  5595.4  502.55  5614.2  503.35
#Mann= 5 ,-1 , 0
  4371.3     .05       0  4876.7    .035       0  4882.7     .05       0
  5425.8      .1       0  5595.4     .05       0
Bank Sta=4876.7,4882.7
XS Rating Curve= 0 ,0
Exp/Cntr=0.3,0.1

Type RM Length L Ch R = 1 ,3658    ,394,394,394
BEGIN DESCRIPTION:
UNT00695 IN CHRS 2.4
END DESCRIPTION:
XS GIS Cut Line= 6
      3449495.75     10603819.73      3449353.63     10603405.28
      3449343.86      10603323.9      3449285.27     10603256.63
      3449206.06     10603236.01      3448755.92     10603047.73
#Sta/Elev= 30
  4457.1   491.6    4665  486.95  4732.8  484.38  4764.1  482.46  4782.8  482.71
  4821.3  479.31  4846.2  478.08  4883.9  478.19  4891.5  476.42  4894.3  475.92
  4897.5  476.42  4947.1  477.83  4952.1   478.9  4987.2  477.95  4993.8  479.26
  5001.4  478.32    5008  479.67  5015.7  479.16  5022.3  480.59  5029.9  479.68
  5036.5  480.66  5044.1  479.78  5050.8  480.37  5070.6  479.87  5141.3  482.05
  5377.3  495.01  5451.7  497.76  5530.9   500.3  5616.8  501.79  5636.2  502.63
#Mann= 5 ,-1 , 0
  4457.1     .05       0  4891.5    .035       0  4897.5     .05       0
  5451.7      .1       0  5616.8     .05       0
Bank Sta=4891.5,4897.5
XS Rating Curve= 0 ,0
Exp/Cntr=0.3,0.1

Type RM Length L Ch R = 1 ,3264    ,756,756,756
BEGIN DESCRIPTION:
UNT00695 IN CHRS 2.3
END DESCRIPTION:
XS GIS Cut Line= 3
      3449748.81     10603149.65      3449627.26     10603028.11
      3448932.83      10602642.7
#Sta/Elev= 30
  4737.5  479.44  4776.2  478.44  4783.3  476.65  4790.3   476.4  4797.4  474.83
  4804.5  474.78  4811.5  473.03  4830.2  473.92  4875.2  473.63  4896.4  475.15
    4918  474.87  4970.5  474.64  5003.8  472.93  5006.5  472.43  5009.8  472.93
    5014  474.33  5035.7  474.82  5079.2  474.06  5182.2  476.97  5225.7   478.6
  5241.7  479.93  5344.7  482.22  5388.1  482.32  5404.2  483.17  5431.6  482.52
  5453.4  483.04  5469.4  483.73  5512.9  488.54  5578.6  493.67  5703.6  498.78
#Mann= 5 ,-1 , 0
  4737.5     .05       0  4830.2     .16       0    4918     .05       0
  5003.8    .035       0  5009.8     .05       0
Bank Sta=5003.8,5009.8
XS Rating Curve= 0 ,0
Exp/Cntr=0.3,0.1

Type RM Length L Ch R = 1 ,2508    ,238,238,238
BEGIN DESCRIPTION:
UNT00695 IN CHRS 2.2
END DESCRIPTION:
XS GIS Cut Line= 4
      3449789.89     10603079.74      3449924.44     10602495.96
      3449900.57      10602376.6      3449255.51     10602028.09
#Sta/Elev= 30
  4155.1   476.2  4251.6   473.9  4306.3  473.25  4351.4  472.64  4451.1  471.91
  4557.3  471.11  4636.5   470.3  4792.9  470.34  4875.9  469.09  4919.8  469.94
  4953.7   470.2  4984.8  467.56  4987.6  467.06  4990.8  467.56  5019.7  469.78
    5056  468.29  5078.8  469.01  5129.1  467.72  5191.5   473.2  5342.3  477.52
  5402.2  480.01  5418.4  481.41  5424.1  480.92    5506  486.72  5511.7  486.56
  5527.9  487.93  5549.7  488.12  5571.6   489.4  5587.8   491.4  5609.1  492.28
#Mann= 10 ,-1 , 0
  4155.1     .05       0  4251.6      .1       0  4306.3     .05       0
  4351.4      .1       0  4451.1     .16       0  4557.3      .1       0
  4919.8     .16       0  4984.8     .07       0  4990.8     .16       0
  5191.5     .05       0
Bank Sta=4984.8,4990.8
XS Rating Curve= 0 ,0
Exp/Cntr=0.3,0.1

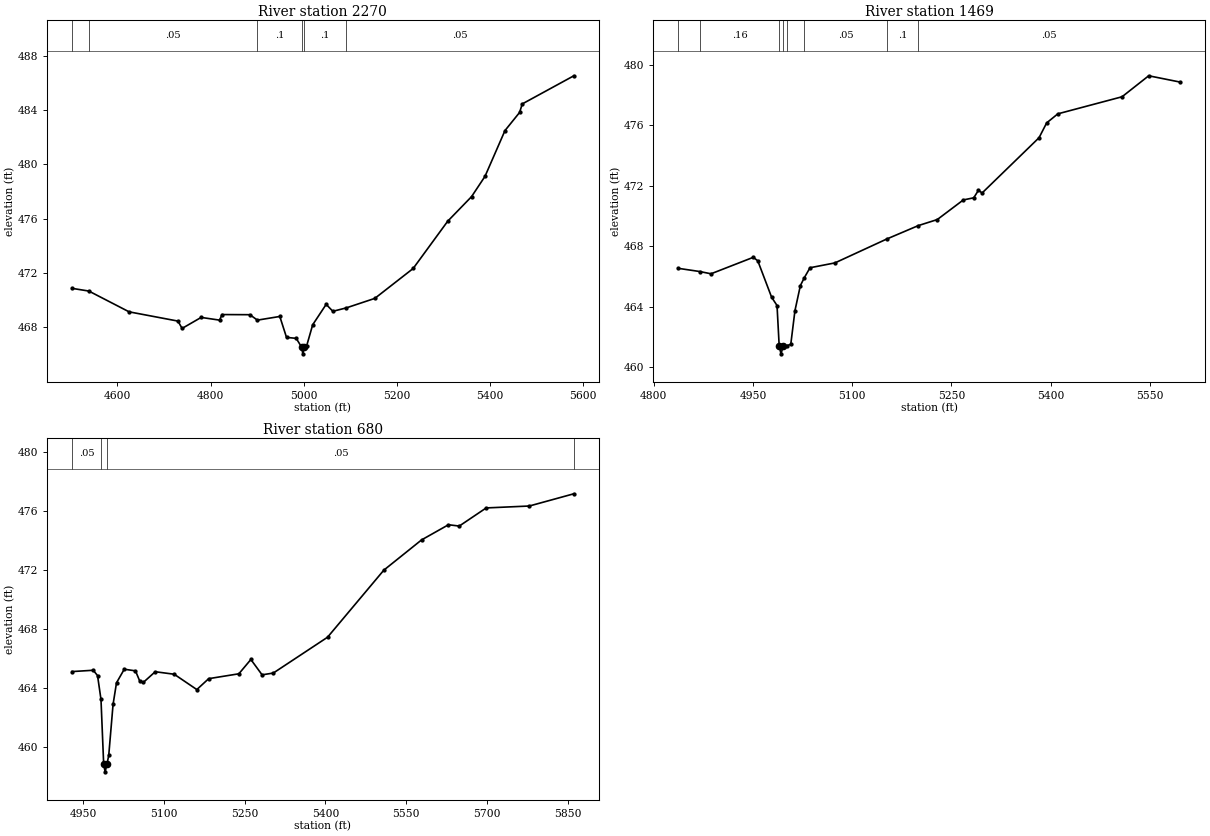
Type RM Length L Ch R = 1 ,2270    ,801,801,801
BEGIN DESCRIPTION:
UNT00695 IN CHRS 2.9
END DESCRIPTION:
XS GIS Cut Line= 4
      3450103.17     10602623.01      3450033.73     10602293.17
      3449841.02     10602046.65        3449473.     10601829.65
#Sta/Elev= 30
  4502.4  470.88  4538.6  470.68  4625.1  469.15  4729.9  468.47  4738.8  467.93
  4779.7  468.74  4819.3  468.54  4824.4  468.95  4884.3  468.94  4900.4  468.54
  4948.5  468.81  4962.9  467.27  4983.7   467.2  4995.2  466.56    4998  466.06
  5001.2  466.56  5006.3  466.67  5019.1   468.2    5048   469.7  5062.4  469.19
  5091.1  469.44  5152.4  470.14  5234.7  472.34  5308.9  475.82  5360.1  477.63
  5388.9  479.12  5431.8  482.49  5463.1  483.82  5468.9  484.45  5579.6  486.52
#Mann= 6 ,-1 , 0
  4502.4     .16       0  4538.6     .05       0  4900.4      .1       0
  4995.2     .07       0  5001.2      .1       0  5091.1     .05       0
Bank Sta=4995.2,5001.2
XS Rating Curve= 0 ,0
Exp/Cntr=0.3,0.1

Type RM Length L Ch R = 1 ,1469    ,789,789,789
BEGIN DESCRIPTION:
UNT00695 IN CHRS 2.0
END DESCRIPTION:
XS GIS Cut Line= 3
      3450370.33      10601781.6       3450234.9      10601604.5
      3449748.78      10601378.8
#Sta/Elev= 30
  4837.3  466.54  4869.5  466.33  4886.6  466.18  4950.5  467.27  4957.3  467.04
  4978.2  464.63  4986.4  464.08  4989.7  461.38  4992.4  460.88  4995.7  461.38
  5001.2  461.42  5007.2  461.51  5013.5  463.74  5021.7   465.4  5027.8  465.93
  5036.3  466.58  5073.9   466.9  5152.2  468.48    5200  469.37  5228.7  469.77
  5268.1  471.07  5283.8  471.21    5291  471.71  5296.5  471.53  5382.6  475.19
  5394.1  476.17    5411  476.77  5508.1   477.9  5548.4  479.29  5596.2  478.87
#Mann= 8 ,-1 , 0
  4837.3     .05       0  4869.5     .16       0  4989.7     .07       0
  4995.7     .16       0  5001.2      .1       0  5027.8     .05       0
  5152.2      .1       0    5200     .05       0
Bank Sta=4989.7,4995.7
XS Rating Curve= 0 ,0
Exp/Cntr=0.3,0.1

Type RM Length L Ch R = 1 ,680     ,0,0,0
BEGIN DESCRIPTION:
UNT00695 IN CHRS 1.0
END DESCRIPTION:
XS GIS Cut Line= 3
      3450712.36     10601337.85      3450332.13     10601030.54
      3449889.42     10601030.54
#Sta/Elev= 30
  4929.4  465.14  4968.9  465.23  4976.9  464.87  4983.3  463.25  4988.3  458.84
    4991  458.34  4994.3  458.84  4997.7  459.46  5005.7  462.91  5012.1  464.38
  5026.5   465.3  5047.3  465.19  5055.2   464.5  5061.7   464.4    5084  465.13
  5119.2  464.96  5161.2  463.92  5183.2  464.66  5239.2  464.99  5261.5  465.96
  5282.3  464.92  5303.1  465.04  5403.8  467.47  5508.3  472.02  5578.3  474.07
  5628.3   475.1  5648.3  475.01  5698.3  476.24  5778.3  476.37    5861   477.2
#Mann= 4 ,-1 , 0
  4929.4     .05       0  4983.3    .035       0  4994.3     .05       0
    5861     .05       0
Bank Sta=4988.3,4994.3
XS Rating Curve= 0 ,0
Exp/Cntr=0.3,0.1

Chan Stop Cuts=-1
Use User Specified Reach Order=0
Composite Channel Slope=5