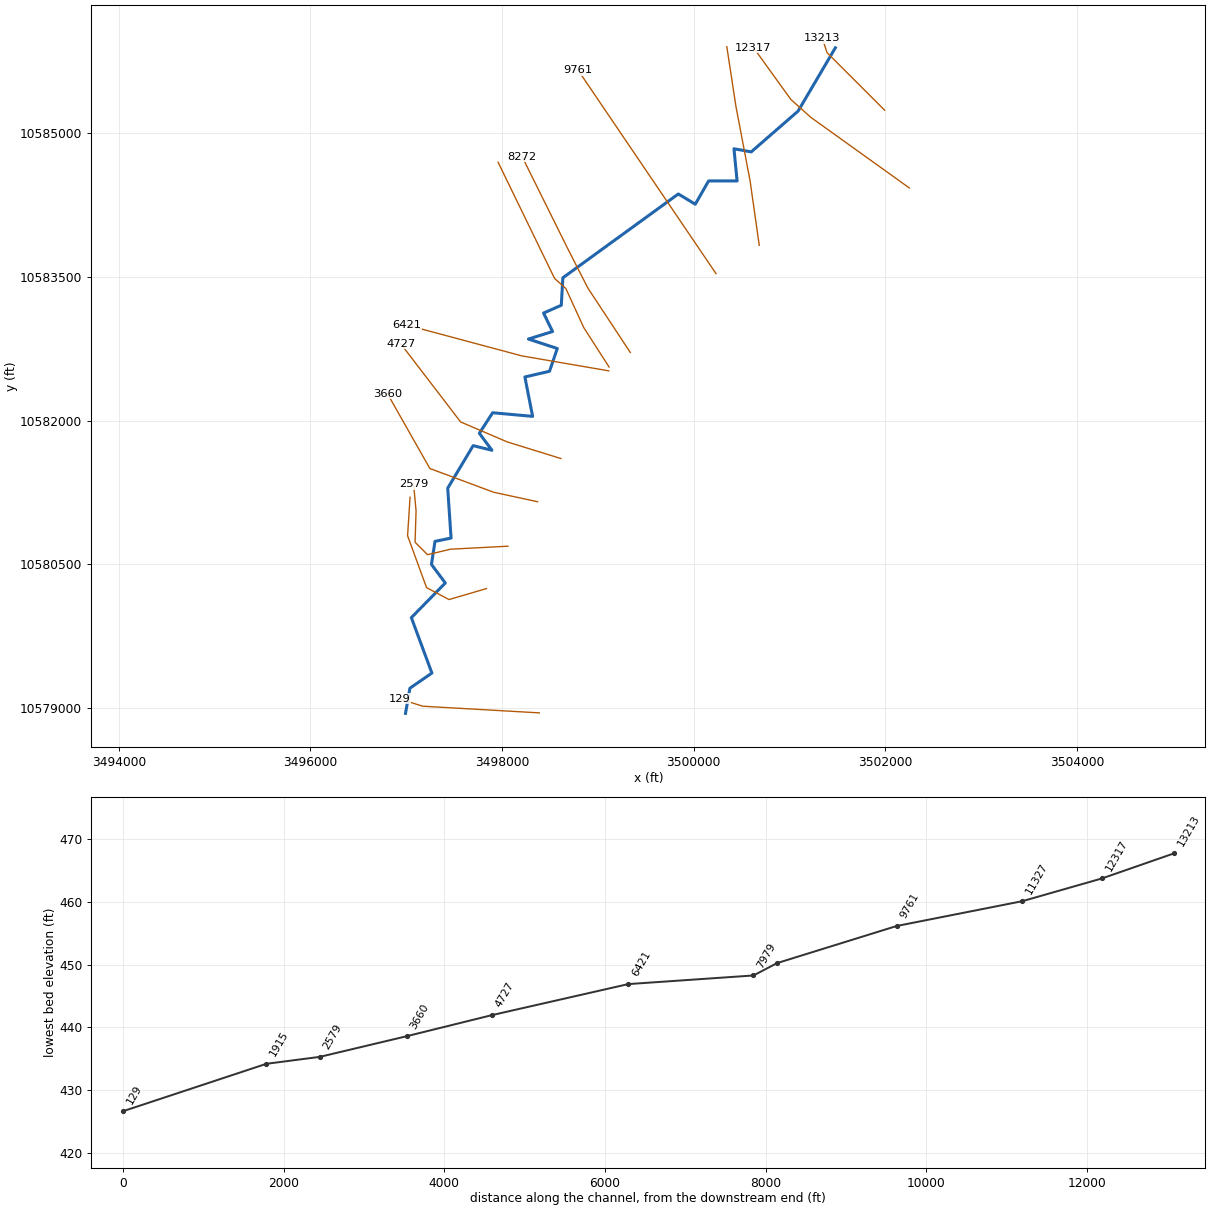
--- UNT0074 IN CHRS.prj (project) ---

Proj Title=UNT0074 IN CHRS Base Level Engineering
Current Plan=p01
Default Exp/Contr=0.3,0.1
English Units
Geom File=g01
Flow File=f01
Plan File=p01
BEGIN DESCRIPTION:
UNT0074 IN CHRS
END DESCRIPTION:

--- UNT0074 IN CHRS.p01 (plan) ---

Plan Title=Multiple Run
Short Identifier=Multiple
Geom File=g01
Flow File=f01
Subcritical Flow
K Sum by GR= 0
Std Step Tol= 0.01
Critical Tol= 0.01
Num of Std Step Trials= 20
Max Error Tol= 0.3
Flow Tol Ratio= 0.001
Split Flow NTrial= 30
Split Flow Tol= 0.02
Split Flow Ratio= 0.02
Log Output Level= 0
Friction Slope Method= 1
Unsteady Friction Slope Method= 2
Unsteady Bridges Friction Slope Method= 1
Parabolic Critical Depth
Global Vel Dist=  1 , 1 , 1
Global Log Level= 0
CheckData=True
Encroach Param= -1, 0, 0, 0
BEGIN DESCRIPTION:
Multiple Run
END DESCRIPTION:

--- UNT0074 IN CHRS.f01 (steady flow) ---

Flow Title=Multiple
Number of Profiles=7
Profile Names=10-year,25-year,50-year,1pct_min,100-year,1pct_plu,500-year
River Rch & RM= UNT0074 IN CHRS,Reach-1,13213
     382     476     544     453     613     829     776
River Rch & RM= UNT0074 IN CHRS,Reach-1,9761
     613     782     909     768    1038    1404    1352
River Rch & RM= UNT0074 IN CHRS,Reach-1,3660
     634     810     941     795    1075    1453    1399
Boundary for River Rch & Prof#=UNT0074 IN CHRS,Reach-1,1
Up Type=0
Dn Type=3
Dn Slope=0.005
Boundary for River Rch & Prof#=UNT0074 IN CHRS,Reach-1,2
Up Type=0
Dn Type=3
Dn Slope=0.005
Boundary for River Rch & Prof#=UNT0074 IN CHRS,Reach-1,3
Up Type=0
Dn Type=3
Dn Slope=0.005
Boundary for River Rch & Prof#=UNT0074 IN CHRS,Reach-1,4
Up Type=0
Dn Type=3
Dn Slope=0.005
Boundary for River Rch & Prof#=UNT0074 IN CHRS,Reach-1,5
Up Type=0
Dn Type=3
Dn Slope=0.005
Boundary for River Rch & Prof#=UNT0074 IN CHRS,Reach-1,6
Up Type=0
Dn Type=3
Dn Slope=0.005
Boundary for River Rch & Prof#=UNT0074 IN CHRS,Reach-1,7
Up Type=0
Dn Type=3
Dn Slope=0.005

--- UNT0074 IN CHRS.g01 (geometry) ---

Geom Title=Existing Conditions

River Reach=UNT0074 IN CHRS,Reach-1
Reach XY= 30
      3501478.38     10585892.84      3501090.00     10585232.19
      3500600.25     10584805.77      3500420.16     10584838.52
      3500452.84     10584502.07      3500155.56     10584502.29
      3500016.29     10584259.27      3499839.68     10584366.20
      3498634.22     10583490.78      3498618.17     10583204.02
      3498433.11     10583122.19      3498526.81     10582929.34
      3498274.79     10582851.11      3498576.22     10582752.32
      3498495.16     10582514.54      3498238.11     10582454.96
      3498318.67     10582043.66      3497901.72     10582081.32
      3497762.99     10581866.51      3497894.34     10581689.72
      3497698.21     10581737.83      3497432.67     10581293.26
      3497467.68     10580772.62      3497299.70     10580737.75
      3497263.00     10580496.83      3497407.74     10580303.34
      3497053.17     10579941.55      3497267.65     10579362.51
      3497037.94     10579204.45      3496992.11     10578941.64

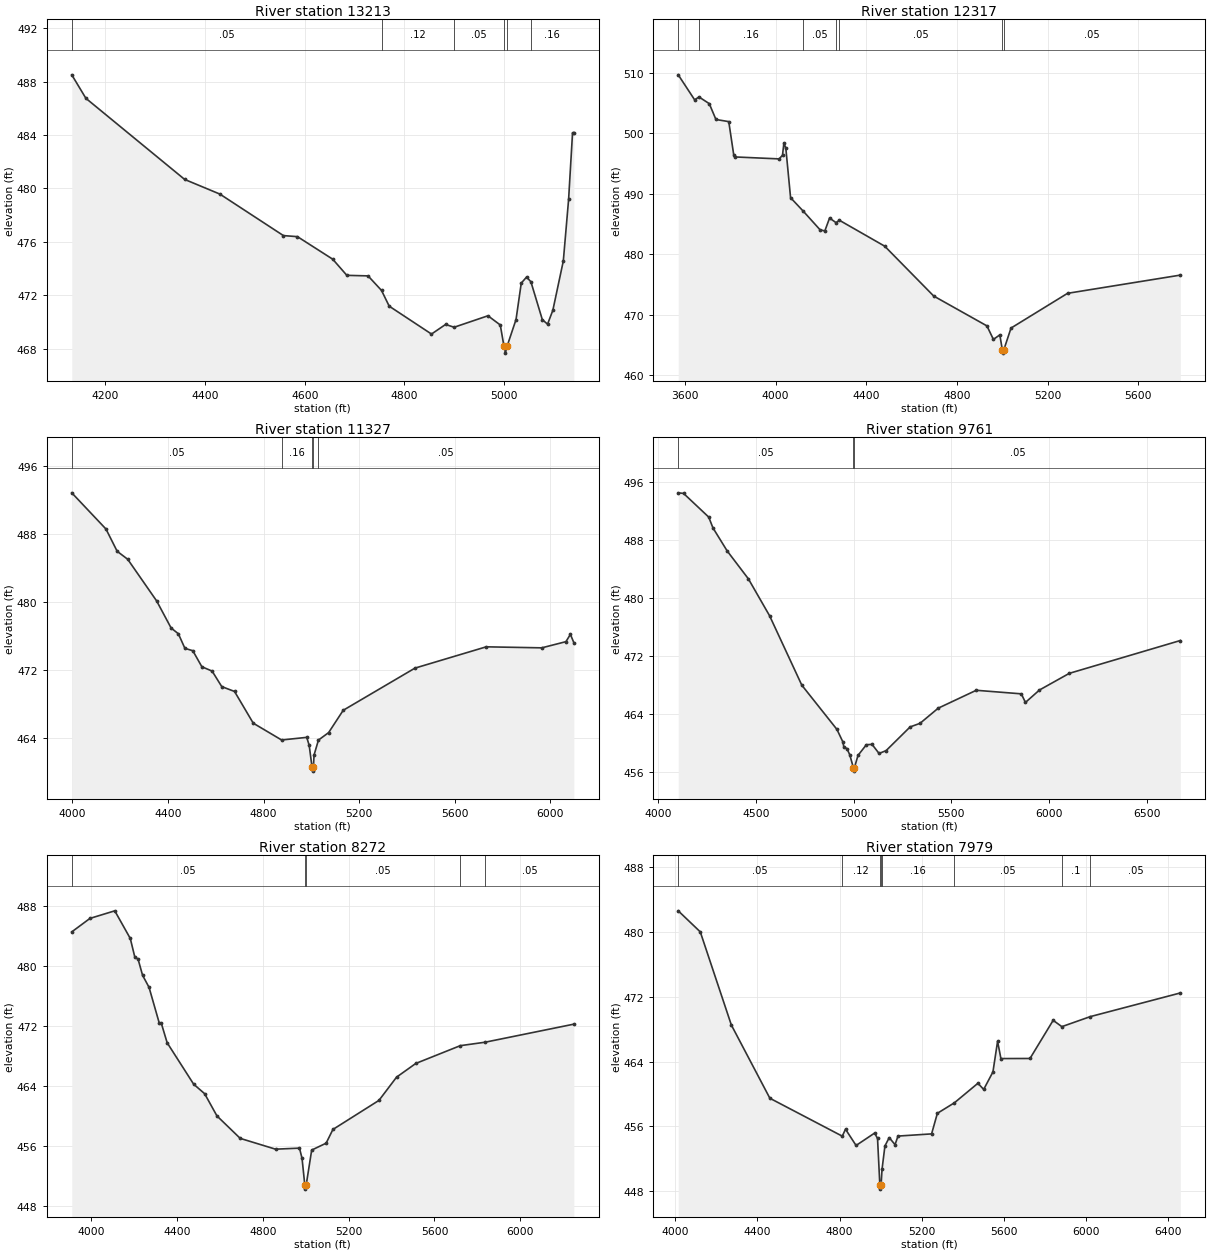
Type RM Length L Ch R = 1,13213,896,896,896
BEGIN DESCRIPTION:
UNT0074 IN CHRS 17.0
END DESCRIPTION:
XS GIS Cut Line= 3
      3501992.10     10585241.65      3501392.11     10585841.64
      3501342.12     10585991.61
#Sta/Elev= 30
  4133.0  488.52  4161.3  486.76  4359.3  480.68  4430.0  479.58  4557.3  476.47
  4585.5  476.39  4656.2  474.70  4684.5  473.49  4727.0  473.45  4754.0  472.36
  4769.4  471.18  4854.2  469.09  4882.5  469.81  4899.6  469.60  4967.4  470.46
  4992.1  469.77  4999.6  468.16  5002.4  467.66  5005.6  468.16  5023.7  470.18
  5034.2  472.91  5044.8  473.36  5053.5  473.01  5076.4  470.17  5086.9  469.83
  5097.5  470.87  5118.5  474.57  5129.1  479.18  5137.0  484.18  5139.6  484.18
#Mann=6,-1,0
  4133.0    0.05       0  4754.0    0.12       0  4899.6    0.05       0
  4999.6    0.04       0  5005.6    0.05       0  5053.5    0.16       0
Bank Sta=4999.6,5005.6
Exp/Cntr=0.3,0.1

Type RM Length L Ch R = 1,12317,990,990,990
BEGIN DESCRIPTION:
UNT0074 IN CHRS 15.0
END DESCRIPTION:
XS GIS Cut Line= 4
      3502250.85     10584428.71      3501222.21     10585166.55
      3501013.88     10585353.18      3500623.27     10585895.69
#Sta/Elev= 30
  3571.0  509.66  3643.3  505.53  3662.6  506.00  3707.8  504.90  3737.3  502.28
  3793.8  501.93  3815.6  496.47  3823.3  496.09  4016.1  495.77  4030.8  496.38
  4037.1  498.42  4045.6  497.50  4066.4  489.36  4122.4  487.13  4196.6  484.05
  4217.5  483.87  4238.4  486.00  4266.7  485.24  4281.8  485.63  4481.5  481.35
  4697.7  473.11  4932.3  468.18  4960.8  465.95  4989.2  466.69  5000.4  464.18
  5003.1  463.68  5006.4  464.18  5038.5  467.82  5287.8  473.56  5785.1  476.57
#Mann=7,-1,0
  3571.0    0.05       0  3662.6    0.16       0  4122.4    0.05       0
  4266.7    0.12       0  4281.8    0.05       0  5000.4    0.04       0
  5006.4    0.05       0
Bank Sta=5000.4,5006.4
Exp/Cntr=0.3,0.1

Type RM Length L Ch R = 1,11327,1566,1566,1566
BEGIN DESCRIPTION:
UNT0074 IN CHRS 13.0
END DESCRIPTION:
XS GIS Cut Line= 4
      3500684.01     10583829.76      3500588.53     10584502.49
      3500440.96     10585279.40      3500345.48     10585904.37
#Sta/Elev= 30
  3997.1  492.87  4140.4  488.60  4187.2  485.98  4231.3  485.04  4352.5  480.13
  4413.1  476.94  4443.4  476.26  4470.9  474.54  4504.0  474.26  4541.9  472.37
  4584.8  471.86  4625.2  470.03  4678.7  469.46  4757.1  465.72  4875.8  463.74
  4981.1  464.05  4991.3  463.11  5003.1  460.57  5005.9  460.07  5009.1  460.57
  5011.6  461.96  5030.1  463.73  5072.7  464.61  5133.8  467.24  5434.2  472.21
  5732.7  474.72  5965.3  474.60  6066.5  475.33  6085.2  476.19  6099.6  475.21
#Mann=5,-1,0
  3997.1    0.05       0  4875.8    0.16       0  5003.1    0.07       0
  5009.1    0.16       0  5030.1    0.05       0
Bank Sta=5003.1,5009.1
Exp/Cntr=0.3,0.1

Type RM Length L Ch R = 1,9761,1489,1489,1489
BEGIN DESCRIPTION:
UNT0074 IN CHRS 11.0
END DESCRIPTION:
XS GIS Cut Line= 2
      3500232.64     10583534.58      3498791.63     10585661.38
#Sta/Elev= 30
  4102.3  494.54  4129.5  494.46  4258.3  491.19  4279.9  489.70  4352.4  486.53
  4461.1  482.67  4569.7  477.57  4734.5  467.99  4914.3  461.88  4944.2  460.18
  4950.2  459.41  4965.2  459.24  4980.1  458.37  4998.1  456.62  5000.9  456.12
  5004.1  456.62  5022.1  458.29  5065.1  459.77  5094.0  459.81  5129.9  458.56
  5165.9  458.95  5288.7  462.22  5339.6  462.72  5432.5  464.81  5627.2  467.28
  5857.8  466.79  5878.8  465.60  5950.7  467.32  6103.4  469.62  6671.3  474.15
#Mann=3,-1,0
  4102.3    0.05       0  4998.1   0.035       0  5004.1    0.05       0
Bank Sta=4998.1,5004.1
Exp/Cntr=0.3,0.1

Type RM Length L Ch R = 1,8272,293,293,293
BEGIN DESCRIPTION:
UNT0074 IN CHRS 10.0
END DESCRIPTION:
XS GIS Cut Line= 4
      3499338.21     10582710.78      3498895.50     10583383.52
      3498678.48     10583808.87      3498209.72     10584755.07
#Sta/Elev= 30
  3910.5  484.54  3995.3  486.34  4110.8  487.35  4183.1  483.66  4204.2  481.18
  4219.3  480.91  4240.3  478.75  4270.5  477.14  4318.6  472.32  4327.7  472.34
  4354.8  469.75  4478.3  464.22  4529.5  462.95  4586.7  459.99  4695.2  456.99
  4859.7  455.55  4971.3  455.69  4983.2  454.32  4996.2  450.72  4998.9  450.22
  5002.2  450.72  5028.1  455.43  5095.4  456.35  5126.9  458.18  5341.5  462.06
  5423.5  465.16  5513.2  466.99  5720.3  469.36  5835.9  469.82  6249.3  472.23
#Mann=5,-1,0
  3910.5    0.05       0  4996.2   0.035       0  5002.2    0.05       0
  5720.3    0.08       0  5835.9    0.05       0
Bank Sta=4996.2,5002.2
Exp/Cntr=0.3,0.1

Type RM Length L Ch R = 1,7979,1558,1558,1558
BEGIN DESCRIPTION:
UNT0074 IN CHRS 8.0
END DESCRIPTION:
XS GIS Cut Line= 5
      3499116.84     10582558.89      3498852.10     10582971.20
      3498665.46     10583379.18      3498548.28     10583483.35
      3497958.47     10584697.66
#Sta/Elev= 30
  4014.2  482.62  4121.6  480.02  4272.9  468.52  4460.5  459.48  4813.2  454.80
  4828.9  455.66  4880.4  453.65  4970.7  455.18  4984.9  454.52  4996.2  448.76
  4998.9  448.26  5002.2  448.76  5006.8  450.70  5020.9  453.59  5041.8  454.62
  5070.2  453.75  5084.5  454.81  5248.2  455.08  5276.3  457.62  5359.4  458.92
  5473.8  461.33  5501.9  460.57  5547.0  462.73  5569.6  466.51  5585.8  464.38
  5727.5  464.39  5840.3  469.10  5882.7  468.32  6021.3  469.56  6459.6  472.48
#Mann=8,-1,0
  4014.2    0.05       0  4813.2    0.12       0  4996.2    0.07       0
  5002.2    0.12       0  5006.8    0.16       0  5359.4    0.05       0
  5882.7     0.1       0  6021.3    0.05       0
Bank Sta=4996.2,5002.2
Exp/Cntr=0.3,0.1

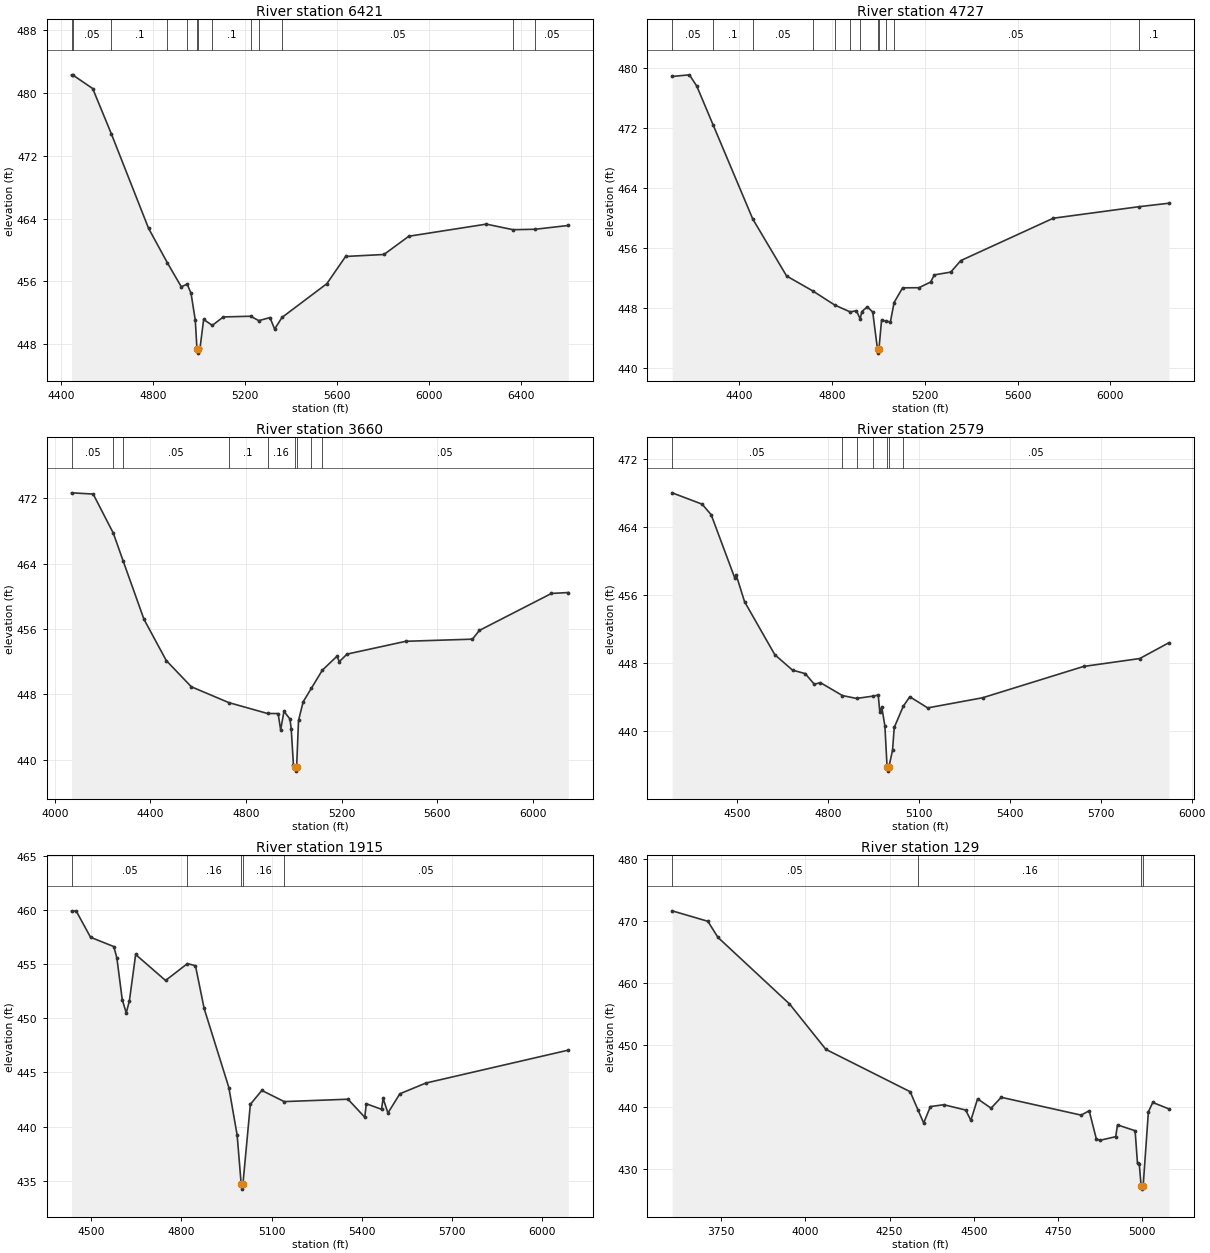
Type RM Length L Ch R = 1,6421,1694,1694,1694
BEGIN DESCRIPTION:
UNT0074 IN CHRS 4.0
END DESCRIPTION:
XS GIS Cut Line= 3
      3499112.82     10582518.98      3498205.72     10582675.23
      3497007.79     10582996.41
#Sta/Elev= 30
  4445.9  482.27  4451.9  482.24  4538.0  480.53  4619.6  474.74  4781.0  462.76
  4863.1  458.36  4923.5  455.32  4948.8  455.66  4965.8  454.50  4984.4  451.05
  4991.6  447.39  4994.3  446.89  4997.6  447.39  5004.7  447.49  5020.6  451.17
  5058.3  450.42  5106.2  451.49  5225.3  451.58  5260.4  451.02  5309.1  451.41
  5329.4  449.95  5361.5  451.43  5556.5  455.72  5638.1  459.18  5804.9  459.43
  5913.0  461.75  6250.1  463.29  6366.3  462.58  6463.1  462.64  6606.6  463.12
#Mann=13,-1,0
  4445.9    0.08       0  4451.9    0.05       0  4619.6     0.1       0
  4863.1    0.05       0  4948.8    0.12       0  4991.6    0.07       0
  4997.6    0.12       0  5058.3     0.1       0  5225.3    0.16       0
  5260.4     0.1       0  5361.5    0.05       0  6366.3     0.1       0
  6463.1    0.05       0
Bank Sta=4991.6,4997.6
Exp/Cntr=0.3,0.1

Type RM Length L Ch R = 1,4727,1067,1067,1067
BEGIN DESCRIPTION:
UNT0074 IN CHRS 2.0
END DESCRIPTION:
XS GIS Cut Line= 4
      3498613.67     10581603.19      3498053.81     10581776.79
      3497567.70     10581985.13      3496942.68     10582801.12
#Sta/Elev= 30
  4109.7  478.88  4184.1  479.10  4216.0  477.59  4287.2  472.36  4457.3  459.87
  4603.4  452.26  4715.1  450.29  4811.3  448.38  4877.7  447.47  4904.4  447.63
  4920.8  446.54  4927.8  447.51  4951.4  448.15  4974.9  447.45  4995.5  442.47
  4998.3  441.97  5001.5  442.47  5013.2  446.43  5030.3  446.23  5051.1  446.14
  5067.0  448.72  5103.7  450.68  5174.4  450.70  5224.7  451.46  5240.7  452.41
  5311.4  452.78  5354.9  454.32  5753.8  459.97  6121.3  461.50  6252.6  461.97
#Mann=12,-1,0
  4109.7    0.05       0  4287.2     0.1       0  4457.3    0.05       0
  4715.1     0.1       0  4811.3    0.12       0  4877.7    0.16       0
  4920.8    0.12       0  4995.5    0.07       0  5001.5    0.12       0
  5030.3     0.1       0  5067.0    0.05       0  6121.3     0.1       0
Bank Sta=4995.5,5001.5
Exp/Cntr=0.3,0.1

Type RM Length L Ch R = 1,3660,1081,1081,1081
BEGIN DESCRIPTION:
UNT0074 IN CHRS 7.0
END DESCRIPTION:
XS GIS Cut Line= 4
      3498370.62     10581151.80      3497910.58     10581251.62
      3497246.52     10581499.01      3496803.79     10582280.30
#Sta/Elev= 30
  4070.2  472.68  4160.8  472.53  4244.8  467.76  4285.9  464.36  4373.3  457.19
  4466.5  452.14  4571.3  448.93  4728.1  446.99  4889.8  445.66  4934.2  445.65
  4944.8  443.65  4958.6  445.92  4983.6  444.99  4988.9  443.82  4998.2  439.38
  5005.6  439.10  5008.3  438.60  5011.6  439.10  5019.5  444.80  5038.9  447.09
  5072.7  448.72  5119.0  450.96  5179.6  452.65  5190.6  452.02  5222.3  452.93
  5468.4  454.50  5746.9  454.76  5775.7  455.83  6077.2  460.36  6147.6  460.47
#Mann=9,-1,0
  4070.2    0.05       0  4244.8     0.1       0  4285.9    0.05       0
  4728.1     0.1       0  4889.8    0.16       0  5005.6    0.07       0
  5011.6    0.16       0  5072.7     0.1       0  5119.0    0.05       0
Bank Sta=5005.6,5011.6
Exp/Cntr=0.3,0.1

Type RM Length L Ch R = 1,2579,664,664,664
BEGIN DESCRIPTION:
UNT0074 IN CHRS 5.0
END DESCRIPTION:
XS GIS Cut Line= 6
      3498060.73     10580687.51      3497461.78     10580656.26
      3497222.20     10580598.97      3497091.99     10580729.18
      3497102.41     10581057.30      3497076.46     10581337.57
#Sta/Elev= 30
  4285.0  468.02  4383.8  466.69  4413.8  465.45  4491.2  458.06  4496.3  458.38
  4524.0  455.23  4624.1  448.99  4682.3  447.19  4724.2  446.78  4754.3  445.53
  4774.3  445.72  4847.1  444.20  4893.6  443.86  4947.1  444.13  4965.3  444.25
  4970.5  442.25  4977.0  442.85  4987.3  440.62  4994.5  435.82  4997.3  435.32
  5000.5  435.82  5012.5  437.77  5018.1  440.45  5047.9  442.94  5069.5  444.06
  5128.6  442.75  5309.8  443.94  5643.2  447.62  5828.7  448.55  5925.0  450.41
#Mann=7,-1,0
  4285.0    0.05       0  4847.1    0.12       0  4893.6    0.16       0
  4947.1    0.12       0  4994.5    0.07       0  5000.5    0.12       0
  5047.9    0.05       0
Bank Sta=4994.5,5000.5
Exp/Cntr=0.3,0.1

Type RM Length L Ch R = 1,1915,1786,1786,1786
BEGIN DESCRIPTION:
UNT0074 IN CHRS 3.0
END DESCRIPTION:
XS GIS Cut Line= 5
      3497836.77     10580244.80      3497446.16     10580130.22
      3497211.78     10580255.22      3497013.87     10580796.89
      3497039.78     10581198.56
#Sta/Elev= 30
  4434.9  459.86  4450.2  459.91  4498.2  457.47  4575.5  456.61  4585.7  455.57
  4603.6  451.71  4616.9  450.49  4627.3  451.59  4648.2  455.88  4747.6  453.48
  4820.5  455.04  4847.1  454.84  4875.9  450.90  4958.1  443.60  4985.7  439.20
  4999.0  434.72  5001.7  434.22  5005.0  434.72  5029.6  442.05  5067.8  443.33
  5142.2  442.30  5354.2  442.52  5409.9  440.86  5415.2  442.10  5465.7  441.59
  5471.0  442.59  5487.1  441.25  5526.7  443.02  5613.0  444.01  6086.8  447.05
#Mann=5,-1,0
  4434.9    0.05       0  4820.5    0.16       0  4999.0    0.07       0
  5005.0    0.16       0  5142.2    0.05       0
Bank Sta=4999,5005
Exp/Cntr=0.3,0.1

Type RM Length L Ch R = 1,129,0,0,0
BEGIN DESCRIPTION:
UNT0074 IN CHRS 1.0
END DESCRIPTION:
XS GIS Cut Line= 3
      3498387.97     10578946.93      3497172.73     10579016.38
      3496926.25     10579094.21
#Sta/Elev= 30
  3604.1  471.62  3710.1  469.93  3740.2  467.33  3952.6  456.59  4060.7  449.25
  4311.1  442.41  4334.1  439.50  4351.2  437.36  4371.2  440.01  4411.3  440.31
  4475.9  439.45  4491.4  437.79  4511.4  441.26  4551.5  439.75  4581.6  441.51
  4819.1  438.63  4842.9  439.34  4863.9  434.82  4874.4  434.56  4921.7  435.15
  4927.0  437.05  4979.3  436.11  4986.4  430.82  4991.6  430.79  4997.2  427.18
  5000.0  426.68  5003.2  427.18  5018.7  439.15  5031.7  440.68  5079.8  439.63
#Mann=4,-1,0
  3604.1    0.05       0  4334.1    0.16       0  4997.2    0.07       0
  5003.2    0.16       0
Bank Sta=4997.2,5003.2
Exp/Cntr=0.3,0.1

Chan Stop Cuts=-1