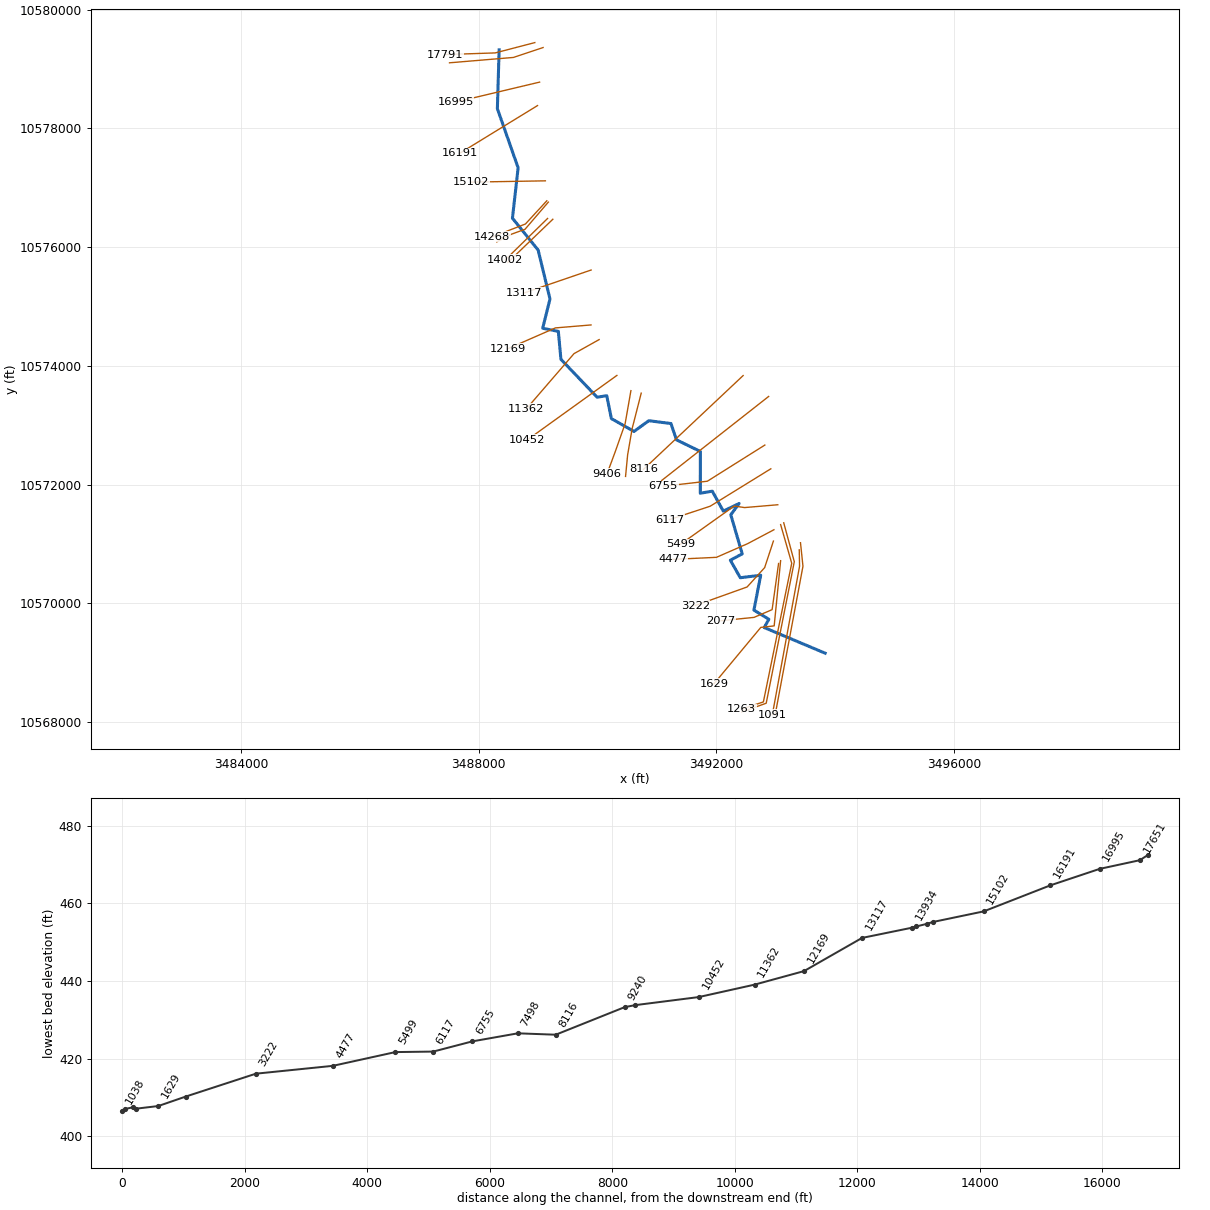
--- UNT0075 IN CHRS.prj (project) ---

Proj Title=UNT0075 IN CHRS Base Level Engineering
Current Plan=p01
Default Exp/Contr=0.3,0.1
English Units
Geom File=g01
Flow File=f01
Plan File=p01
Y Axis Title=Elevation
X Axis Title(PF)=Main Channel Distance
X Axis Title(XS)=Station
BEGIN DESCRIPTION:
UNT0075 IN CHRS
END DESCRIPTION:
DSS Export Rating Curves= 0
DSS Export Rating Curve Sorted= 0
DSS Export Volume Flow Curves= 0
DXF OffsetX= 0
DXF OffsetY= 0
DXF ScaleX= 1
DXF ScaleY= 10

--- UNT0075 IN CHRS.p01 (plan) ---

Plan Title=Multiple Run
Short Identifier=Multiple
Geom File=g01
Flow File=f01
Subcritical Flow
K Sum by GR= 0
Std Step Tol= 0.01
Critical Tol= 0.01
Num of Std Step Trials= 20
Max Error Tol= 0.3
Flow Tol Ratio= 0.001
Split Flow NTrial= 30
Split Flow Tol= 0.02
Split Flow Ratio= 0.02
Log Output Level= 0
Friction Slope Method= 1
Unsteady Friction Slope Method= 2
Unsteady Bridges Friction Slope Method= 1
Parabolic Critical Depth
Global Vel Dist=  1 , 1 , 1
Global Log Level= 0
CheckData=True
Encroach Param= -1, 0, 0, 0
BEGIN DESCRIPTION:
Multiple Run
END DESCRIPTION:

--- UNT0075 IN CHRS.f01 (steady flow) ---

Flow Title=Multiple
Number of Profiles=7
Profile Names=10-year,25-year,50-year,1pct_min,100-year,1pct_plu,500-year
River Rch & RM= UNT0075 IN CHRS,Reach-1,17791
     471     594     685     575     778    1052     999
River Rch & RM= UNT0075 IN CHRS,Reach-1,14002
     655     839     977     827    1119    1513    1464
River Rch & RM= UNT0075 IN CHRS,Reach-1,5499
     957    1248    1472    1260    1704    2304    2279
Boundary for River Rch & Prof#=UNT0075 IN CHRS,Reach-1,1
Up Type=0
Dn Type=3
Dn Slope=0.005
Boundary for River Rch & Prof#=UNT0075 IN CHRS,Reach-1,2
Up Type=0
Dn Type=3
Dn Slope=0.005
Boundary for River Rch & Prof#=UNT0075 IN CHRS,Reach-1,3
Up Type=0
Dn Type=3
Dn Slope=0.005
Boundary for River Rch & Prof#=UNT0075 IN CHRS,Reach-1,4
Up Type=0
Dn Type=3
Dn Slope=0.005
Boundary for River Rch & Prof#=UNT0075 IN CHRS,Reach-1,5
Up Type=0
Dn Type=3
Dn Slope=0.005
Boundary for River Rch & Prof#=UNT0075 IN CHRS,Reach-1,6
Up Type=0
Dn Type=3
Dn Slope=0.005
Boundary for River Rch & Prof#=UNT0075 IN CHRS,Reach-1,7
Up Type=0
Dn Type=3
Dn Slope=0.005

--- UNT0075 IN CHRS.g01 (geometry) ---

Geom Title=Existing Conditions
Program Version=4.10

River Reach=UNT0075 IN CHRS ,Reach-1
Reach XY= 30
      3488342.11     10579321.64      3488312.47      10578331.3
      3488661.98     10577335.98      3488566.33     10576487.11
      3488999.02     10575950.37      3489198.53     10575126.44
      3489075.65     10574633.51      3489339.46     10574580.31
       3489382.6     10574110.79      3489991.95     10573472.21
      3490154.65      10573497.8      3490232.22     10573112.09
      3490612.98     10572895.92      3490862.97     10573076.59
      3491236.11     10573028.73      3491328.44     10572754.22
      3491731.04     10572558.74      3491729.47     10571855.34
      3491931.36     10571890.32      3492117.28     10571554.04
      3492383.72      10571682.6      3492243.27     10571492.69
      3492435.62     10570834.03      3492235.83     10570727.27
      3492403.32     10570432.55      3492746.84     10570474.31
      3492632.72     10569886.83      3492884.61      10569732.7
      3492805.54     10569593.71      3493832.11     10569161.64

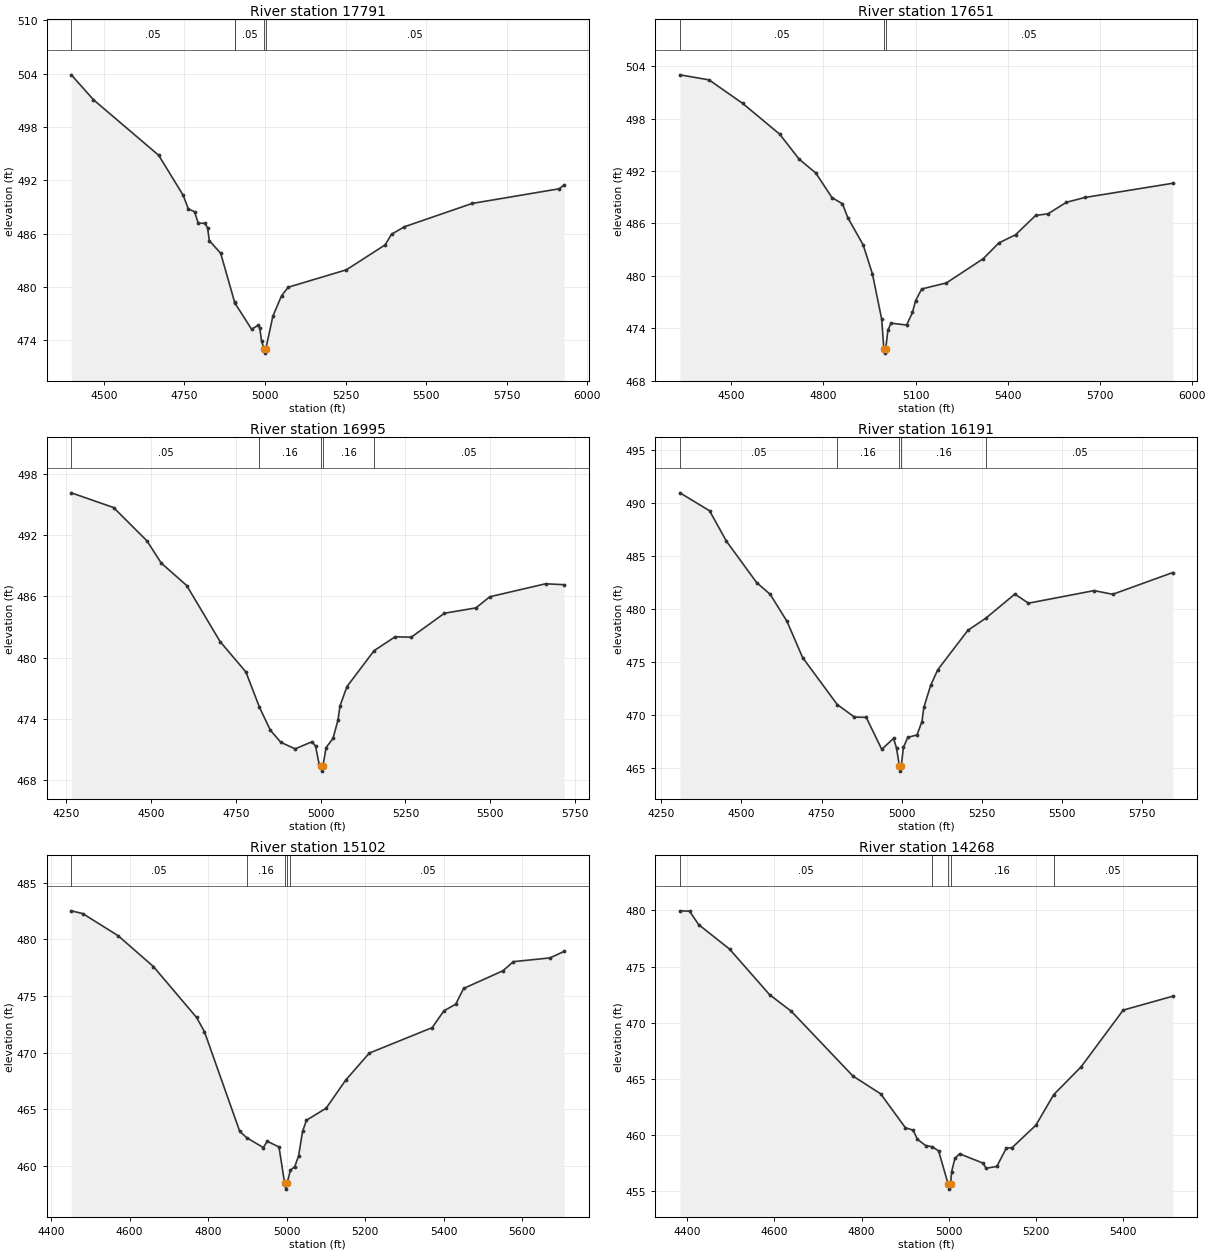
Type RM Length L Ch R = 1 ,17791   ,140,140,140
BEGIN DESCRIPTION:
UNT0075 IN CHRS 27.1
END DESCRIPTION:
XS GIS Cut Line= 3
      3488943.34     10579444.01      3488276.65     10579270.39
      3487436.73     10579242.62
#Sta/Elev= 30
  4398.9  503.86  4467.6  501.06  4670.1  494.81    4746  490.32  4761.8   488.8
  4781.3  488.46  4792.8  487.18  4813.5  487.17  4821.8  486.64    4827  485.22
  4862.3   483.8  4905.5  478.31  4906.1  478.22  4958.2  475.26  4978.7   475.7
  4983.8  475.34  4989.2  473.93  4996.5  473.07  4999.3  472.57  5002.5  473.07
  5024.3  476.73  5051.2  479.02  5071.9  479.98  5252.5  481.94  5372.5  484.74
  5392.5  485.94  5432.6  486.78  5642.7   489.4  5912.8  491.05  5928.2  491.49
#Mann= 5 ,-1 , 0
  4398.9     .05       0  4905.5     .12       0  4906.1     .05       0
  4996.5    .035       0  5002.5     .05       0
Bank Sta=4996.5,5002.5
XS Rating Curve= 0 ,0
Exp/Cntr=0.3,0.1

Type RM Length L Ch R = 1 ,17651   ,656,656,656
BEGIN DESCRIPTION:
UNT0075 IN CHRS 27.0
END DESCRIPTION:
XS GIS Cut Line= 3
      3489082.16     10579360.65       3488582.2       10579194.
      3487506.48     10579103.78
#Sta/Elev= 30
  4332.2  503.02  4427.1  502.44  4536.2  499.76  4657.4  496.22  4720.7  493.36
    4775  491.77  4827.7  488.96  4861.8  488.25  4879.4  486.65  4929.5  483.53
  4959.7   480.2  4989.8  475.02  4996.8  471.64  4999.5  471.14  5002.8  471.64
  5009.8  473.74  5019.9  474.57    5071  474.36  5090.1  475.81  5100.1  477.14
  5120.2  478.49  5200.5  479.18  5320.9  481.96  5371.1  483.75  5426.1   484.7
  5491.5  486.91  5531.7   487.1  5591.9  488.42  5652.1  488.97  5938.7   490.6
#Mann= 3 ,-1 , 0
  4332.2     .05       0  4996.8    .035       0  5002.8     .05       0
Bank Sta=4996.8,5002.8
XS Rating Curve= 0 ,0
Exp/Cntr=0.3,0.1

Type RM Length L Ch R = 1 ,16995   ,804,804,804
BEGIN DESCRIPTION:
UNT0075 IN CHRS 25.0
END DESCRIPTION:
XS GIS Cut Line= 2
      3489023.38     10578778.45      3487608.42     10578442.07
#Sta/Elev= 30
  4264.2  496.13  4388.9  494.69  4487.4  491.43  4529.5  489.26  4604.7  487.06
  4703.4  481.57  4779.4   478.6  4819.4  475.15  4851.4  472.91  4882.4  471.72
  4924.5  471.08  4974.7  471.78    4985  471.33  4995.3   469.6  5000.7   469.4
  5003.5   468.9  5006.7   469.4  5015.9   471.2  5036.4   472.1  5051.1  473.91
    5057  475.28  5077.5  477.17  5157.4  480.68  5219.8  482.05  5267.1     482
  5365.3  484.35  5457.8  484.87    5499  485.96  5663.4  487.23  5718.6  487.14
#Mann= 5 ,-1 , 0
  4264.2     .05       0  4819.4     .16       0  5000.7     .07       0
  5006.7     .16       0  5157.4     .05       0
Bank Sta=5000.7,5006.7
XS Rating Curve= 0 ,0
Exp/Cntr=0.3,0.1

Type RM Length L Ch R = 1 ,16191   ,1089,1089,1089
BEGIN DESCRIPTION:
UNT0075 IN CHRS 23.0
END DESCRIPTION:
XS GIS Cut Line= 2
      3488988.64     10578383.49      3487676.42     10577578.81
#Sta/Elev= 30
  4307.9  490.99  4400.5  489.29  4452.7  486.43  4547.4   482.5    4590  481.38
  4642.2  478.83  4690.9  475.41  4799.1  470.96    4853  469.77  4889.7  469.75
  4938.1  466.72  4974.9  467.76  4984.2  466.85  4993.2  465.16  4995.9  464.66
  4999.2  465.16  5005.7   466.9  5019.4  467.85  5048.3  468.09  5063.7  469.35
  5069.6  470.69  5090.9  472.78  5113.2  474.26  5207.1  477.98  5263.2  479.13
  5353.8  481.41  5396.4  480.55  5601.4  481.74  5659.4  481.39  5847.2  483.45
#Mann= 5 ,-1 , 0
  4307.9     .05       0  4799.1     .16       0  4993.2     .07       0
  4999.2     .16       0  5263.2     .05       0
Bank Sta=4993.2,4999.2
XS Rating Curve= 0 ,0
Exp/Cntr=0.3,0.1

Type RM Length L Ch R = 1 ,15102   ,834,834,834
BEGIN DESCRIPTION:
UNT0075 IN CHRS 22.0
END DESCRIPTION:
XS GIS Cut Line= 2
      3489121.04     10577116.12      3487865.82     10577094.44
#Sta/Elev= 30
  4451.5  482.53  4480.4  482.29  4570.4  480.34  4660.5  477.61  4770.5  473.11
  4790.5  471.86  4880.5  463.04  4898.1  462.49  4940.5  461.61  4950.5  462.17
  4980.5  461.66  4994.9  458.44  4997.7  457.94  5000.9  458.44  5009.6  459.62
  5020.5  459.92  5030.5  460.89  5040.5  463.05  5050.5  464.03  5100.5  465.09
  5150.5  467.58  5210.5  469.96  5370.6  472.21  5400.6   473.7  5430.6  474.28
  5450.6  475.67  5550.6  477.23  5577.5  478.04  5670.6  478.37  5706.9  478.95
#Mann= 5 ,-1 , 0
  4451.5     .05       0  4898.1     .16       0  4994.9     .07       0
  5000.9     .16       0  5009.6     .05       0
Bank Sta=4994.9,5000.9
XS Rating Curve= 0 ,0
Exp/Cntr=0.3,0.1

Type RM Length L Ch R = 1 ,14268   ,88,88,88
BEGIN DESCRIPTION:
UNT0075 IN CHRS 21.0
END DESCRIPTION:
XS GIS Cut Line= 3
      3489144.86     10576779.73      3488784.63     10576389.12
      3488225.89     10576172.56
#Sta/Elev= 30
  4383.4  479.97  4405.4  479.94  4426.4  478.74  4497.3  476.56  4589.1   472.5
    4639  471.02  4780.2  465.26  4843.7  463.68  4900.4  460.66  4918.2  460.44
  4928.2  459.63  4946.8  459.07  4962.4  458.96  4976.7  458.59  4998.3  455.69
    5001  455.19  5004.3  455.69  5006.6  456.75    5014  457.92  5024.7  458.34
  5078.3  457.51  5085.7  457.05  5110.2  457.21    5132  458.84  5145.5  458.89
    5200  460.89  5240.6   463.6  5303.6  466.08  5400.1  471.13    5514  472.37
#Mann= 5 ,-1 , 0
  4383.4     .05       0  4962.4     .16       0  4998.3     .07       0
  5004.3     .16       0  5240.6     .05       0
Bank Sta=4998.3,5004.3
XS Rating Curve= 0 ,0
Exp/Cntr=0.3,0.1

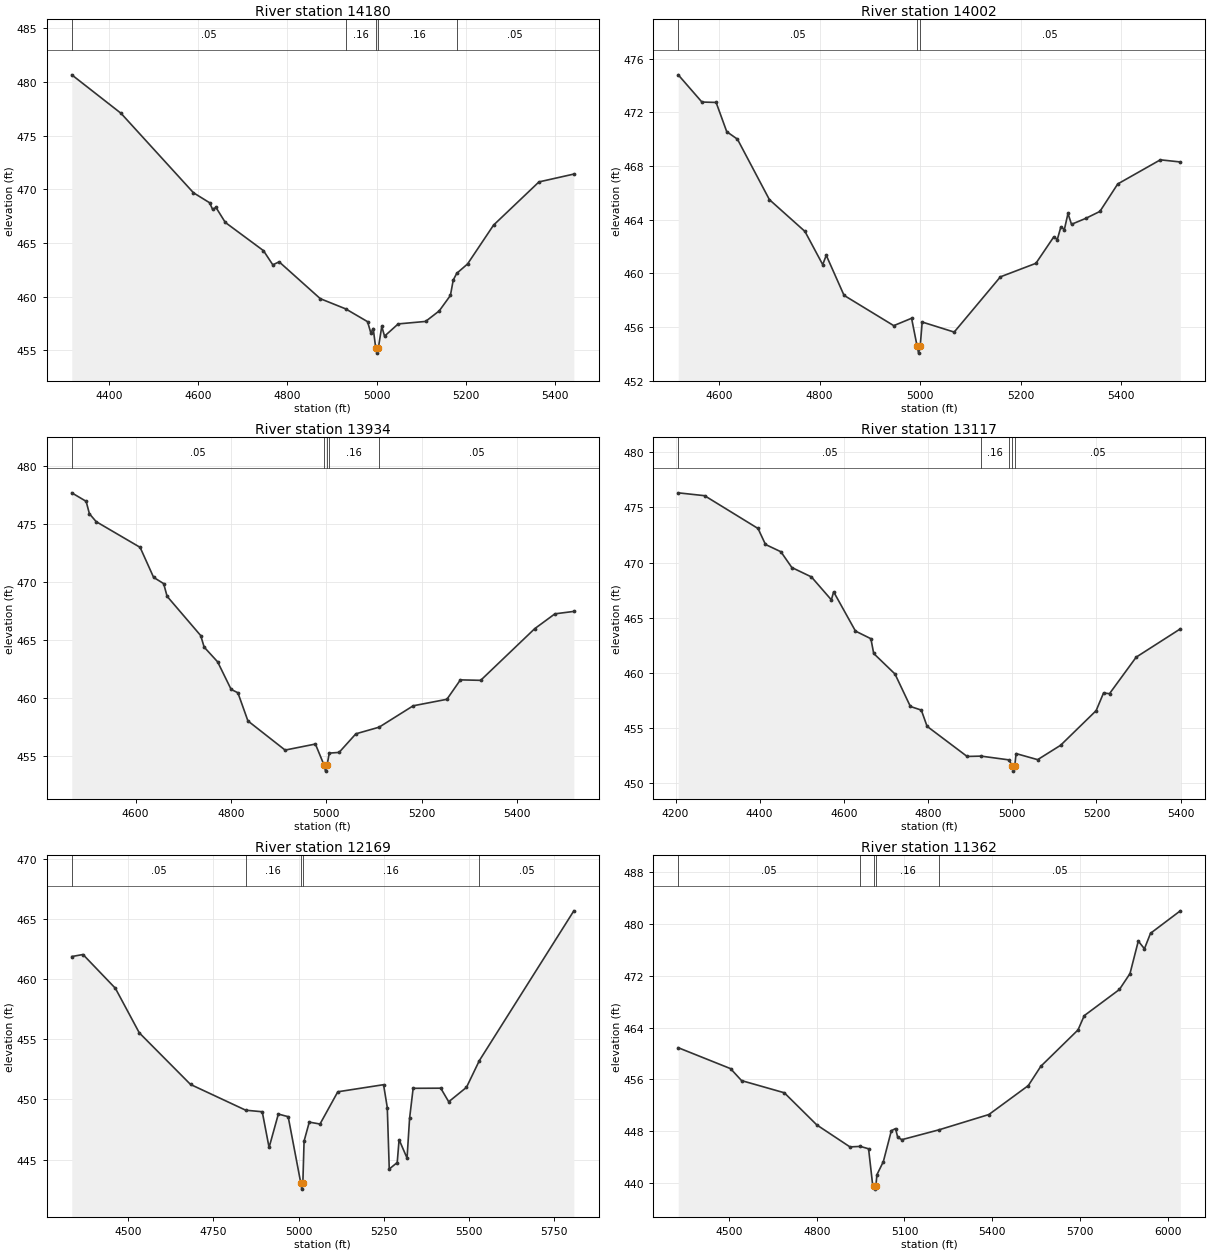
Type RM Length L Ch R = 1 ,14180   ,178,178,178
BEGIN DESCRIPTION:
UNT0075 IN CHRS 20.0
END DESCRIPTION:
XS GIS Cut Line= 4
      3489170.88     10576758.01      3488778.12     10576300.15
      3488550.25     10576217.68      3488302.89     10576087.49
#Sta/Elev= 30
  4316.6  480.66  4426.9  477.08  4589.3  469.68  4625.5  468.75  4632.1  468.14
  4639.8  468.31  4660.6  466.92  4746.2  464.29  4767.1  462.97  4781.3  463.25
  4873.5  459.82  4930.4  458.87  4979.4  457.68  4986.8  456.63  4992.1  457.04
  4997.7  455.25  5000.4  454.75  5003.7  455.25  5011.3  457.24  5017.5  456.33
  5048.1  457.47  5109.4   457.7    5140  458.68  5165.1  460.12  5171.4  461.55
  5179.3  462.18  5203.5  463.05  5261.8  466.67  5363.5  470.69  5441.7  471.42
#Mann= 5 ,-1 , 0
  4316.6     .05       0  4930.4     .16       0  4997.7     .07       0
  5003.7     .16       0  5179.3     .05       0
Bank Sta=4997.7,5003.7
XS Rating Curve= 0 ,0
Exp/Cntr=0.3,0.1

Type RM Length L Ch R = 1 ,14002   ,68,68,68
BEGIN DESCRIPTION:
UNT0075 IN CHRS 19.0
END DESCRIPTION:
XS GIS Cut Line= 2
      3489157.86     10576482.41      3488443.91     10575783.65
#Sta/Elev= 30
  4518.7  474.81  4565.8  472.78  4594.1  472.75  4615.2  470.57  4636.5  470.01
  4700.1   465.5  4770.8  463.13  4806.2  460.65  4813.2  461.35  4848.6  458.36
  4947.5   456.1    4983  456.65  4994.1  454.55  4996.9  454.05  5000.1  454.55
  5004.1  456.37  5067.8  455.62  5159.7  459.74  5230.4  460.75  5265.9  462.72
  5272.9  462.52    5280  463.46    5287  463.27  5294.2  464.47  5301.2  463.66
  5329.4   464.1  5357.7  464.62  5393.2  466.67    5478  468.47  5517.7  468.31
#Mann= 3 ,-1 , 0
  4518.7     .05       0  4994.1     .04       0  5000.1     .05       0
Bank Sta=4994.1,5000.1
XS Rating Curve= 0 ,0
Exp/Cntr=0.3,0.1

Type RM Length L Ch R = 1 ,13934   ,817,817,817
BEGIN DESCRIPTION:
UNT0075 IN CHRS 18.0
END DESCRIPTION:
XS GIS Cut Line= 2
      3489246.84     10576469.39      3488487.29     10575740.22
#Sta/Elev= 30
  4466.1  477.68  4496.2  476.95  4503.1  475.88  4517.3   475.2  4609.4  472.99
  4637.7  470.41  4658.8  469.87    4666  468.78  4736.5   465.4  4743.7  464.41
    4772  463.14  4800.3  460.77  4814.5  460.48  4835.5  458.06  4913.5  455.55
    4977  456.07  4995.4  454.24  4998.2  453.74  5001.4  454.24  5006.1  455.29
  5026.7  455.35  5061.9  456.95  5110.6  457.52  5182.1  459.36  5252.8  459.92
  5281.1  461.59  5323.6  461.55  5436.8  465.99  5479.3  467.27    5519  467.48
#Mann= 5 ,-1 , 0
  4466.1     .05       0  4995.4     .04       0  5001.4     .05       0
  5006.1     .16       0  5110.6     .05       0
Bank Sta=4995.4,5001.4
XS Rating Curve= 0 ,0
Exp/Cntr=0.3,0.1

Type RM Length L Ch R = 1 ,13117   ,948,948,948
BEGIN DESCRIPTION:
UNT0075 IN CHRS 16.0
END DESCRIPTION:
XS GIS Cut Line= 2
      3489891.44      10575614.4      3488762.92      10575228.1
#Sta/Elev= 30
  4206.5  476.32  4269.2  476.06    4396  473.09  4413.8  471.64  4450.4  470.98
  4476.4  469.55  4522.9   468.7  4570.3  466.62  4575.7  467.35  4627.6  463.79
  4664.2   463.1  4670.9  461.76  4721.5   459.9    4758  456.96    4784  456.63
  4797.7  455.16  4892.8  452.43  4926.1  452.46  4991.9  452.12  5000.1   451.6
  5002.8   451.1  5006.1   451.6  5009.1  452.69  5060.4  452.14  5114.8  453.44
  5199.3  456.58  5216.9  458.18  5231.1  458.12  5294.5  461.43  5399.3  463.99
#Mann= 5 ,-1 , 0
  4206.5     .05       0  4926.1     .16       0  4991.9     .05       0
  5000.1    .035       0  5006.1     .05       0
Bank Sta=5000.1,5006.1
XS Rating Curve= 0 ,0
Exp/Cntr=0.3,0.1

Type RM Length L Ch R = 1 ,12169   ,807,807,807
BEGIN DESCRIPTION:
UNT0075 IN CHRS 15.0
END DESCRIPTION:
XS GIS Cut Line= 3
      3489889.87     10574689.39      3489289.85     10574639.39
      3488489.86     10574289.39
#Sta/Elev= 30
  4333.6  461.87  4366.6  462.04  4461.8  459.23    4532  455.53  4682.6  451.24
  4844.7   449.1  4893.3  448.97  4913.4     446  4940.6  448.78  4969.5  448.56
  5006.6  443.04  5009.4  442.54  5012.6  443.04  5016.2  446.53  5031.5  448.11
    5063  447.95  5115.3  450.63  5249.8  451.22  5260.7  449.32  5266.5  444.21
  5289.9  444.75  5295.4  446.65  5318.8  445.12  5326.2  448.41  5336.7  450.92
  5417.8  450.93  5441.2   449.8  5493.4     451  5531.2  453.22  5808.9  465.67
#Mann= 5 ,-1 , 0
  4333.6     .05       0  4844.7     .16       0  5006.6     .07       0
  5012.6     .16       0  5531.2     .05       0
Bank Sta=5006.6,5012.6
XS Rating Curve= 0 ,0
Exp/Cntr=0.3,0.1

Type RM Length L Ch R = 1 ,11362   ,910,910,910
BEGIN DESCRIPTION:
UNT0075 IN CHRS 13.0
END DESCRIPTION:
XS GIS Cut Line= 3
      3490025.91     10574442.49      3489602.77     10574205.96
      3488797.68     10573272.83
#Sta/Elev= 30
  4326.2  460.89  4505.1  457.66  4542.8  455.81    4689  453.93  4800.3  448.96
  4913.6  445.57    4949  445.65  4977.2  445.28  4991.5  439.57  4996.1  439.55
  4998.9  439.05  5002.1  439.55  5005.8  441.28  5027.7   443.3  5055.1  448.07
  5069.4   448.4    5077  447.03  5091.3  446.69  5218.1  448.21  5388.6  450.57
  5523.5  455.04  5566.3  458.02  5693.6  463.64  5714.8  465.84  5835.1  469.88
  5871.3  472.34  5899.7  477.36  5920.7  476.17  5941.5  478.56  6043.4  482.03
#Mann= 5 ,-1 , 0
  4326.2     .05       0    4949     .16       0  4996.1     .07       0
  5002.1     .16       0  5218.1     .05       0
Bank Sta=4996.1,5002.1
XS Rating Curve= 0 ,0
Exp/Cntr=0.3,0.1

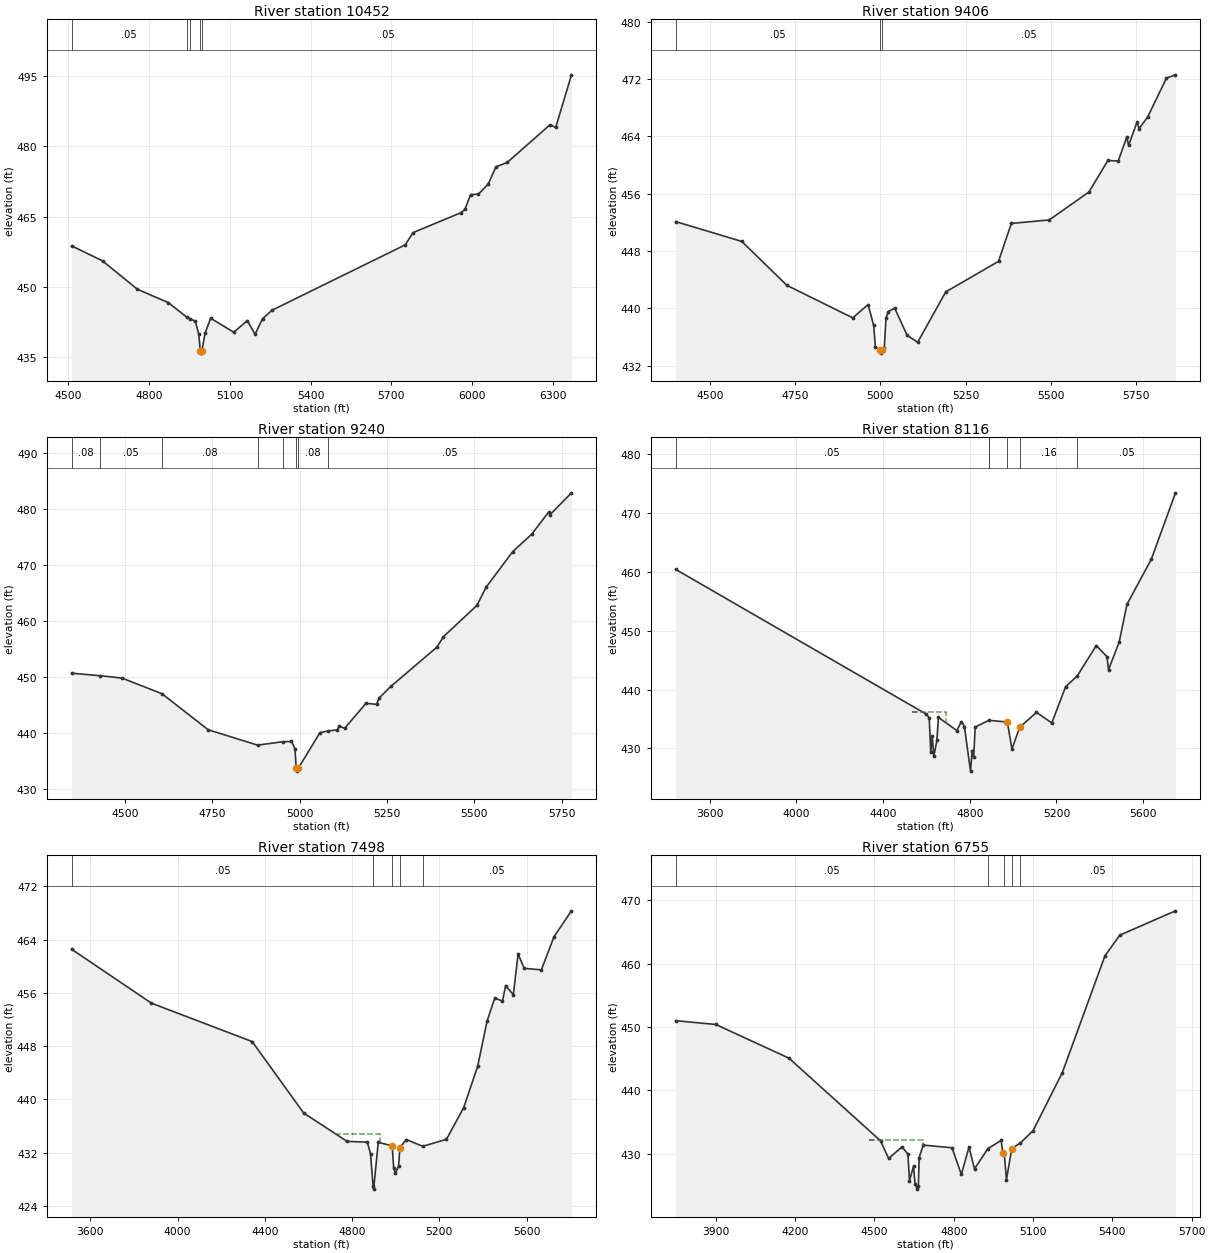
Type RM Length L Ch R = 1 ,10452   ,1046,1046,1046
BEGIN DESCRIPTION:
UNT0075 IN CHRS 11.0
END DESCRIPTION:
XS GIS Cut Line= 2
      3490325.47     10573839.24      3488817.14     10572754.11
#Sta/Elev= 30
  4512.1  458.77  4627.1  455.55  4756.4   449.5  4871.7  446.63  4939.5  443.56
  4953.7  443.17    4972  442.67  4984.7  439.89  4990.3  436.35    4993  435.85
  4996.3  436.35    5008  440.09  5028.9   443.3  5114.8  440.31  5165.1  442.81
  5193.8  439.87  5221.6   443.2  5257.2  445.02  5751.9  458.98  5781.3   461.6
  5959.3  465.85    5974  466.56  5994.9  469.69  6024.4  469.84    6060  471.91
  6089.4  475.65  6131.2  476.58  6290.2  484.63  6311.6  484.07  6370.2  495.31
#Mann= 5 ,-1 , 0
  4512.1     .05       0  4939.5     .12       0  4953.7     .05       0
  4990.3    .035       0  4996.3     .05       0
Bank Sta=4990.3,4996.3
XS Rating Curve= 0 ,0
Exp/Cntr=0.3,0.1

Type RM Length L Ch R = 1 ,9406    ,166,166,166
BEGIN DESCRIPTION:
UNT0075 IN CHRS 9.0
END DESCRIPTION:
XS GIS Cut Line= 4
      3490561.36     10573582.85      3490464.15     10573027.33
      3490297.48     10572555.11       3490158.6     10572180.13
#Sta/Elev= 30
    4400   452.1  4593.9  449.33  4726.1   443.2    4919  438.67    4964  440.53
  4980.2  437.63  4985.5  434.54  4998.8  434.25  5001.6  433.75  5004.8  434.25
  5011.1   434.4  5016.4  438.61    5023  439.55  5042.1  440.01  5078.3  436.22
  5109.2  435.27  5191.4  442.29  5346.1  446.55  5383.6  451.84  5494.8  452.33
  5611.1  456.23  5666.5  460.62  5696.9  460.55    5722   463.9  5727.3  462.73
  5752.4  466.03  5757.7  465.07  5782.8  466.66  5838.2  472.11  5864.6  472.57
#Mann= 3 ,-1 , 0
    4400     .05       0  4998.8    .035       0  5004.8     .05       0
Bank Sta=4998.8,5004.8
XS Rating Curve= 0 ,0
Exp/Cntr=0.3,0.1

Type RM Length L Ch R = 1 ,9240    ,1124,1124,1124
BEGIN DESCRIPTION:
UNT0075 IN CHRS 8.0
END DESCRIPTION:
XS GIS Cut Line= 4
      3490734.98     10573541.23       3490582.2       10572944.
      3490505.81     10572499.55      3490471.09     10572138.44
#Sta/Elev= 30
    4348  450.72  4428.6  450.27  4492.1  449.85  4606.4  447.05  4738.8  440.62
  4879.9  437.88  4951.8  438.48    4977  438.53  4987.1  437.22  4990.4  433.74
  4993.1  433.24  4996.4  433.74  5058.4  440.11  5082.1  440.42  5108.2   440.6
  5113.3  441.26  5129.2  440.89  5190.1  445.33  5220.5  445.17  5228.1  446.31
  5261.1  448.35    5393  455.36  5411.8  457.23  5507.6  462.82  5533.9  466.06
  5610.1  472.42  5664.5  475.53  5712.5  479.45  5717.5  479.04  5778.2  482.91
#Mann= 8 ,-1 , 0
    4348     .08       0  4428.6     .05       0  4606.4     .08       0
  4879.9     .05       0  4951.8     .08       0  4990.4     .07       0
  4996.4     .08       0  5082.1     .05       0
Bank Sta=4990.4,4996.4
XS Rating Curve= 0 ,0
Exp/Cntr=0.3,0.1

Type RM Length L Ch R = 1 ,8116    ,618,618,618
BEGIN DESCRIPTION:
UNT0075 IN CHRS 6.3
END DESCRIPTION:
XS GIS Cut Line= 2
      3492451.27     10573836.86       3490771.2     10572255.85
#Sta/Elev= 30
  3442.5   460.4  4598.6  435.83  4612.8  435.22  4620.1  429.38  4626.9  432.11
  4634.2  428.66  4648.4  431.39  4655.3  435.27  4740.2  433.03  4761.3  434.54
  4775.4  433.71  4803.5  426.14  4811.1  429.48  4817.9  428.56  4825.2  433.63
  4888.7  434.77  4973.7  434.47  4994.7  429.89  5030.3  433.59    5108  436.11
  5178.8  434.32  5242.3  440.46  5295.9   442.3    5384  447.46  5433.3  445.58
  5440.6  443.37    5490  448.11  5525.6  454.46  5638.4  462.15  5749.5   473.4
#Mann= 6 ,-1 , 0
  3442.5     .05       0  4888.7     .12       0  4888.7     .16       0
  4973.7     .07       0  5030.3     .16       0  5295.9     .05       0
#XS Ineff= 1 ,-1
 4533.25 4691.02  436.19
Permanent Ineff=
       F
Bank Sta=4973.7,5030.3
XS Rating Curve= 0 ,0
Exp/Cntr=0.3,0.1

Type RM Length L Ch R = 1 ,7498    ,743,743,743
BEGIN DESCRIPTION:
UNT0075 IN CHRS 6.2
END DESCRIPTION:
XS GIS Cut Line= 2
      3492880.92     10573485.27      3491079.71     10572070.34
#Sta/Elev= 30
  3514.9  462.56  3880.4  454.46  4342.3  448.68  4578.2  437.94    4777  433.68
  4870.1  433.56  4884.5  431.79    4896     427  4898.7   426.5  4919.8  433.54
    4984  433.01  4990.3  429.71  4998.4  428.86  5012.9  429.94  5019.2  432.72
  5048.1  433.96    5124  432.94  5232.5  433.99  5311.2  438.74  5375.3  444.94
  5418.7  451.77  5453.9  455.23  5489.2  454.77  5503.7   457.1  5538.9  455.72
  5560.7  461.85  5588.6  459.69  5667.3  459.47  5725.1  464.43  5805.4  468.34
#Mann= 5 ,-1 , 0
  3514.9     .05       0    4896     .07       0    4984     .05       0
  5019.2     .16       0    5124     .05       0
#XS Ineff= 1 ,-1
 4723.83 4926.39  434.75
Permanent Ineff=
       F
Bank Sta=4984,5019.2
XS Rating Curve= 0 ,0
Exp/Cntr=0.3,0.1

Type RM Length L Ch R = 1 ,6755    ,638,638,638
BEGIN DESCRIPTION:
UNT0075 IN CHRS 6.1
END DESCRIPTION:
XS GIS Cut Line= 3
      3492817.08     10572666.63      3491847.95     10572057.33
       3491106.9     10571972.91
#Sta/Elev= 30
  3748.2  451.01  3900.1  450.41  4176.9  445.09  4523.1  432.05  4553.7  429.26
  4604.6  431.09  4626.7  429.95  4632.7  425.77    4648  428.04  4653.9  425.18
    4663  424.42  4666.3  424.92  4669.2  429.39  4684.5  431.37  4793.5  430.95
    4829  426.73  4857.6  431.05  4878.8  427.63    4929   430.8  4979.4  432.11
  4985.9  430.11  4990.9  430.23  4999.5  425.91  5019.6  430.83  5052.2  431.71
  5100.1  433.65  5210.8  442.81  5371.9  461.23  5428.2  464.51  5638.8  468.35
#Mann= 5 ,-1 , 0
  3748.2     .05       0    4929     .16       0  4990.9     .07       0
  5019.6     .16       0  5052.2     .05       0
#XS Ineff= 1 ,-1
 4480.21 4683.71  432.18
Permanent Ineff=
       F
Bank Sta=4985.9,5019.6
XS Rating Curve= 0 ,0
Exp/Cntr=0.3,0.1

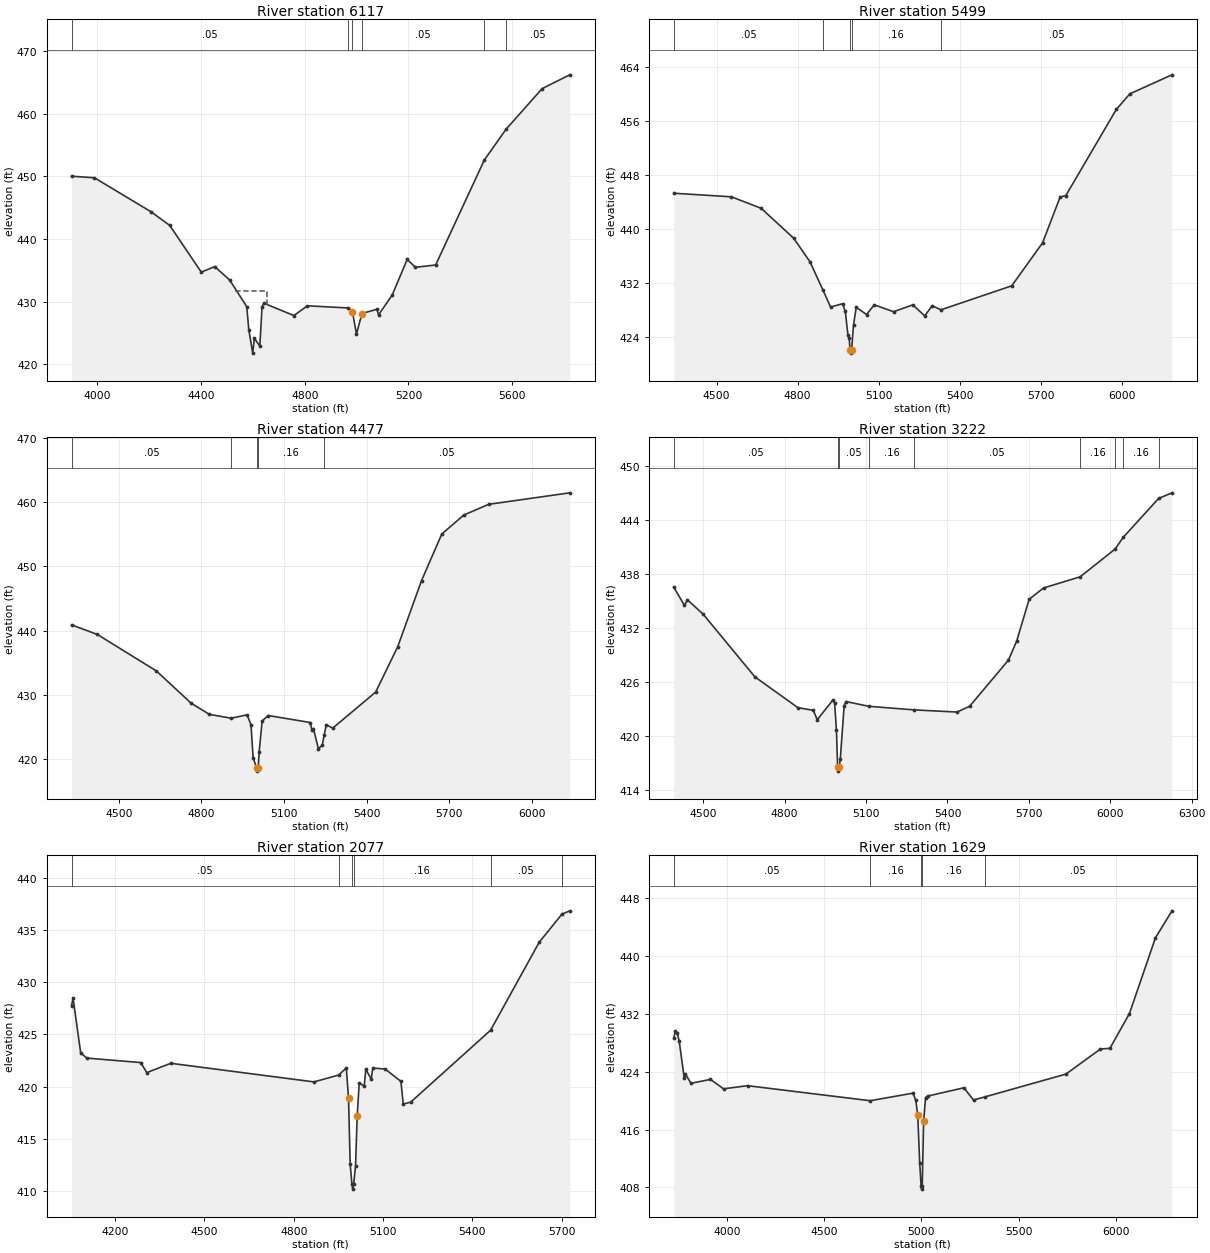
Type RM Length L Ch R = 1 ,6117    ,618,618,618
BEGIN DESCRIPTION:
UNT0075 IN CHRS 6.0
END DESCRIPTION:
XS GIS Cut Line= 3
      3492917.07     10572266.62      3491895.69     10571636.32
      3491210.86     10571410.83
#Sta/Elev= 30
  3900.8  450.01  3988.9  449.76  4205.9  444.37  4279.2  442.17  4400.9  434.71
    4453  435.59  4510.9  433.43  4576.4  429.19  4584.3   425.5  4599.4  421.79
  4605.6  424.15  4626.8  422.92  4635.2   429.1  4642.2  429.76  4758.1  427.78
  4810.2  429.34  4968.6  428.99    4984  428.37  4999.4  424.83  5020.7  428.11
  5078.6  428.79  5084.5  427.89  5136.8  431.02  5195.1  436.73  5226.9  435.48
  5304.8  435.85  5492.6   452.6  5576.3   457.5  5715.4  463.98    5822  466.18
#Mann= 6 ,-1 , 0
  3900.8     .05       0  4968.6     .16       0    4984    .035       0
  5020.7     .05       0  5492.6     .16       0  5576.3     .05       0
#XS Ineff= 1 ,-1
 4529.78    4656  431.75
Permanent Ineff=
       F
Bank Sta=4984,5020.7
XS Rating Curve= 0 ,0
Exp/Cntr=0.3,0.1

Type RM Length L Ch R = 1 ,5499    ,1022,1022,1022
BEGIN DESCRIPTION:
UNT0075 IN CHRS 7.0
END DESCRIPTION:
XS GIS Cut Line= 4
      3493034.75      10571661.4      3492474.88     10571613.66
      3492301.27      10571639.7      3491398.53     10570997.37
#Sta/Elev= 30
  4341.3  445.32  4554.7  444.79  4665.1  443.09  4785.6  438.66  4845.8  435.18
  4894.5  430.94  4922.2  428.48  4966.7  428.97  4976.8  427.82  4986.3  424.38
  4991.3  423.86    4994  422.16  4996.8  421.66    5000  422.16  5007.1  425.83
  5017.2  428.44  5055.4  427.37    5084  428.81  5155.3  427.79  5226.6   428.8
  5270.9  427.17  5298.6  428.68  5331.1  428.07  5593.2  431.62  5707.4  437.98
  5772.6  444.77  5793.5  444.97  5980.4  457.71  6030.8  460.03  6186.7  462.84
#Mann= 5 ,-1 , 0
  4341.3     .05       0  4894.5     .16       0    4994     .07       0
    5000     .16       0  5331.1     .05       0
Bank Sta=4994,5000
XS Rating Curve= 0 ,0
Exp/Cntr=0.3,0.1

Type RM Length L Ch R = 1 ,4477    ,1255,1255,1255
BEGIN DESCRIPTION:
UNT0075 IN CHRS 5.0
END DESCRIPTION:
XS GIS Cut Line= 4
      3492969.67     10571240.39      3492526.96     10571006.02
      3492001.79     10570775.99      3491268.27     10570741.26
#Sta/Elev= 30
  4328.5  440.88    4422  439.39  4636.3  433.71  4762.7  428.68  4828.7  426.95
  4907.5  426.35  4965.7  426.87  4979.8  425.33  4987.6   420.2  5000.1  418.61
  5002.9  418.11  5006.1  418.61  5009.4  421.09  5020.3  425.92  5042.1  426.77
    5195  425.68  5201.1  424.45  5206.5  424.74  5224.5   421.6  5238.7  422.15
  5245.8  423.79  5253.3  425.32  5276.7  424.81  5432.5  430.42  5512.6  437.49
    5599  447.78  5672.7  455.04  5752.8  457.99  5842.9  459.65  6137.1  461.44
#Mann= 5 ,-1 , 0
  4328.5     .05       0  4907.5     .16       0  5000.1     .07       0
  5006.1     .16       0  5245.8     .05       0
Bank Sta=5000.1,5006.1
XS Rating Curve= 0 ,0
Exp/Cntr=0.3,0.1

Type RM Length L Ch R = 1 ,3222    ,1145,1145,1145
BEGIN DESCRIPTION:
UNT0075 IN CHRS 4.0
END DESCRIPTION:
XS GIS Cut Line= 4
      3492960.99     10571049.43      3492813.42     10570602.37
      3492518.28     10570276.85      3491646.51     10569964.58
#Sta/Elev= 30
  4391.2  436.55  4430.6  434.51  4441.5  435.14  4499.4  433.55  4689.9  426.58
  4848.6  423.15  4905.7  422.85  4919.9   421.8  4976.7  423.96  4984.1  423.69
  4990.8  420.62    4995  416.59  4997.7  416.09    5001  416.59    5005  417.44
  5019.2  423.38    5026  423.83  5109.7   423.3  5277.2   422.9  5435.4  422.66
  5481.6   423.3  5624.8  428.44  5655.5  430.59    5701   435.2  5754.1  436.46
    5889   437.7  6017.6  440.78    6048   442.1  6178.3  446.42  6227.4  447.04
#Mann= 9 ,-1 , 0
  4391.2     .05       0    4995     .07       0    5001     .05       0
  5109.7     .16       0  5277.2     .05       0    5889     .16       0
  6017.6     .12       0    6048     .16       0  6178.3     .12       0
Bank Sta=4995,5001
XS Rating Curve= 0 ,0
Exp/Cntr=0.3,0.1

Type RM Length L Ch R = 1 ,2077    ,448,448,448
BEGIN DESCRIPTION:
UNT0075 IN CHRS 4.1
END DESCRIPTION:
XS GIS Cut Line= 4
      3493047.79     10570671.82      3492939.29     10569894.91
      3492635.47      10569764.7      3492079.92     10569708.28
#Sta/Elev= 30
  4053.9  427.76    4059  428.46  4084.4  423.25  4104.6  422.73  4286.3   422.3
  4306.5  421.34  4387.3  422.23  4867.9  420.45  4951.4  421.11  4976.7  421.79
  4984.2  418.87  4989.7   412.6  4995.5  410.69  4998.2  410.19  5001.5  410.69
  5007.8  412.43  5013.2  417.19  5020.2  420.37  5036.8  420.03  5042.2  421.67
  5060.4  420.72  5065.8  421.78  5107.3  421.68  5160.1   420.5    5168  418.34
  5192.4   418.5  5461.2  425.39  5624.6  433.81  5700.8   436.5  5727.3  436.82
#Mann= 6 ,-1 , 0
  4053.9     .05       0  4951.4     .16       0  4995.5     .07       0
  5001.5     .16       0  5461.2     .05       0  5700.8     .16       0
Bank Sta=4984.2,5013.2
XS Rating Curve= 0 ,0
Exp/Cntr=0.3,0.1

Type RM Length L Ch R = 1 ,1629    ,366,366,366
BEGIN DESCRIPTION:
UNT0075 IN CHRS 3.0
END DESCRIPTION:
XS GIS Cut Line= 4
      3493082.52     10570719.57      3492974.01     10569621.47
      3492748.32     10569595.43      3491959.12      10568645.8
#Sta/Elev= 30
  3724.7  428.66  3732.7  429.62  3742.7  429.32  3752.8  428.22  3778.8  423.09
  3783.8  423.74  3813.1   422.4  3913.5  422.94    3981  421.64  4104.5  422.07
  4736.3  419.99  4956.7  421.04    4971  420.03  4981.1  417.97  4991.1  411.36
  4998.2  408.25  5000.9  407.75  5004.2  408.25  5011.3  417.14  5021.3  420.43
  5031.4  420.63  5218.2  421.78  5268.3  420.09  5325.6  420.51  5744.3  423.68
  5921.3  427.14  5970.8  427.25  6071.1  432.06  6205.2  442.55  6290.1  446.28
#Mann= 5 ,-1 , 0
  3724.7     .05       0  4736.3     .16       0  4998.2     .07       0
  5004.2     .16       0  5325.6     .05       0
Bank Sta=4981.1,5011.3
XS Rating Curve= 0 ,0
Exp/Cntr=0.3,0.1

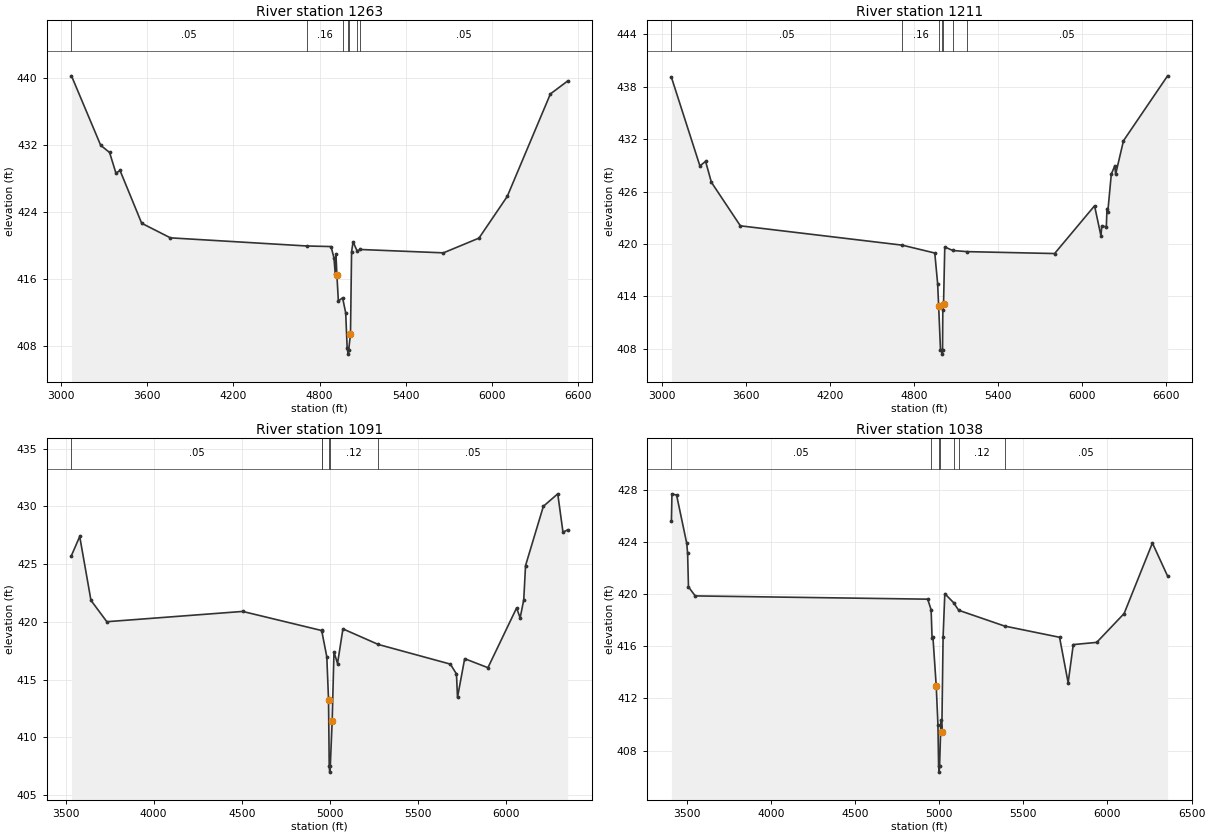
Type RM Length L Ch R = 1 ,1263    ,52,52,52
BEGIN DESCRIPTION:
UNT0075 IN CHRS 2.0
END DESCRIPTION:
XS GIS Cut Line= 4
      3493082.84     10571326.83      3493269.47     10570675.81
      3492792.04     10568340.74      3492423.16     10568219.23
#Sta/Elev= 30
  3075.8  440.28  3278.8  431.99  3340.7  431.13  3384.8  428.67  3413.4  428.98
    3564  422.68  3763.6  420.94  4710.3  419.97  4880.1   419.9  4900.5  418.55
  4909.3  416.65  4914.4  418.96  4920.9   416.5  4931.1   413.4  4960.5  413.78
  4982.1  411.98  4992.3  407.77    4997  407.56  4999.8  407.06    5003  407.56
  5015.4  409.52  5022.9  419.27  5033.2  420.46  5061.5  419.38  5084.5  419.55
  5661.4  419.15  5908.6  420.91  6104.9  425.88    6405  438.12  6524.8  439.66
#Mann= 7 ,-1 , 0
  3075.8     .05       0  4710.3     .16       0  4960.5     .12       0
    4997     .07       0    5003     .12       0  5061.5     .16       0
  5084.5     .05       0
Bank Sta=4920.9,5015.4
XS Rating Curve= 0 ,0
Exp/Cntr=0.3,0.1

Type RM Length L Ch R = 1 ,1211    ,120,120,120
BEGIN DESCRIPTION:
UNT0075 IN CHRS 2.9
END DESCRIPTION:
XS GIS Cut Line= 4
      3493134.91     10571357.27      3493312.87     10570701.85
      3492839.78     10568319.04      3492427.46     10568171.47
#Sta/Elev= 30
  3065.1  439.06  3268.6  428.93  3309.3  429.45  3350.7  427.06  3557.9  422.08
  4714.5  419.87  4947.5  418.97  4967.9  415.47  4975.1  412.91  4988.3  407.91
    4997  407.91  4999.8  407.41    5003  407.91  5004.9  412.51    5010  413.12
  5018.9  419.66  5075.9  419.26  5176.7  419.13  5803.9  418.91  6089.5  424.37
  6135.6   420.9  6140.7  422.06  6173.6  421.97  6178.5  424.05  6183.9  423.64
  6209.3     428  6234.8  428.96  6240.1  427.97  6296.3  431.81  6611.5  439.23
#Mann= 7 ,-1 , 0
  3065.1     .05       0  4714.5     .16       0  4975.1     .12       0
    4997     .07       0    5003     .12       0  5075.9     .16       0
  5176.7     .05       0
Bank Sta=4975.1,5010
XS Rating Curve= 0 ,0
Exp/Cntr=0.3,0.1

Type RM Length L Ch R = 1 ,1091    ,53,53,53
BEGIN DESCRIPTION:
UNT0075 IN CHRS 1.9
END DESCRIPTION:
XS GIS Cut Line= 3
       3493396.2     10570902.37      3493401.41     10570626.33
      3492943.11     10568126.48
#Sta/Elev= 30
  3533.3  425.75  3580.1   427.4    3644  421.87  3734.1  420.02  4505.5  420.91
  4953.3  419.26  4955.1  419.19  4983.3  416.98  4993.1  413.27    4997   407.5
  4999.8     407    5003   407.5  5013.8  411.44    5024   417.4  5044.3   416.4
  5074.8   419.4    5276  418.05  5684.8  416.35  5719.6   415.5  5725.5  413.47
  5766.2  416.82  5898.3  416.04    6061  421.21  6081.3  420.35  6101.7  421.92
  6111.9  424.88  6213.1  430.01  6294.8  431.09  6324.5  427.77  6350.9  427.97
#Mann= 6 ,-1 , 0
  3533.3     .05       0  4953.3     .16       0  4955.1     .12       0
    4997     .07       0    5003     .12       0    5276     .05       0
Bank Sta=4993.1,5013.8
XS Rating Curve= 0 ,0
Exp/Cntr=0.3,0.1

Type RM Length L Ch R = 1 ,1038    ,0,0,0
BEGIN DESCRIPTION:
UNT0075 IN CHRS 1.0
END DESCRIPTION:
XS GIS Cut Line= 4
      3493417.03     10571022.18       3493458.7     10570626.33
      3493187.87     10569178.41      3492989.96     10568121.15
#Sta/Elev= 30
  3410.3  425.61  3413.4  427.67    3441  427.57  3501.3  423.87  3506.4  423.11
  3511.5  420.54  3551.6  419.85  4932.2   419.6  4952.6  418.79  4958.4  416.59
  4963.5  416.68  4983.1  412.92  4993.2  409.95    4997  406.85  4999.8  406.35
    5003  406.85    5011  410.32  5016.1   409.4  5023.7  416.69  5033.9  420.02
  5085.6  419.34  5116.3  418.75    5389  417.54  5715.4  416.68  5766.4   413.2
  5796.9  416.12    5936  416.29  6098.9   418.5  6266.9   423.9    6357  421.37
#Mann= 7 ,-1 , 0
  3410.3     .05       0  4952.6     .12       0    4997     .07       0
    5003     .12       0  5085.6     .16       0  5116.3     .12       0
    5389     .05       0
Bank Sta=4983.1,5016.1
XS Rating Curve= 0 ,0
Exp/Cntr=0.3,0.1

Chan Stop Cuts=-1
Use User Specified Reach Order=0
Composite Channel Slope=5