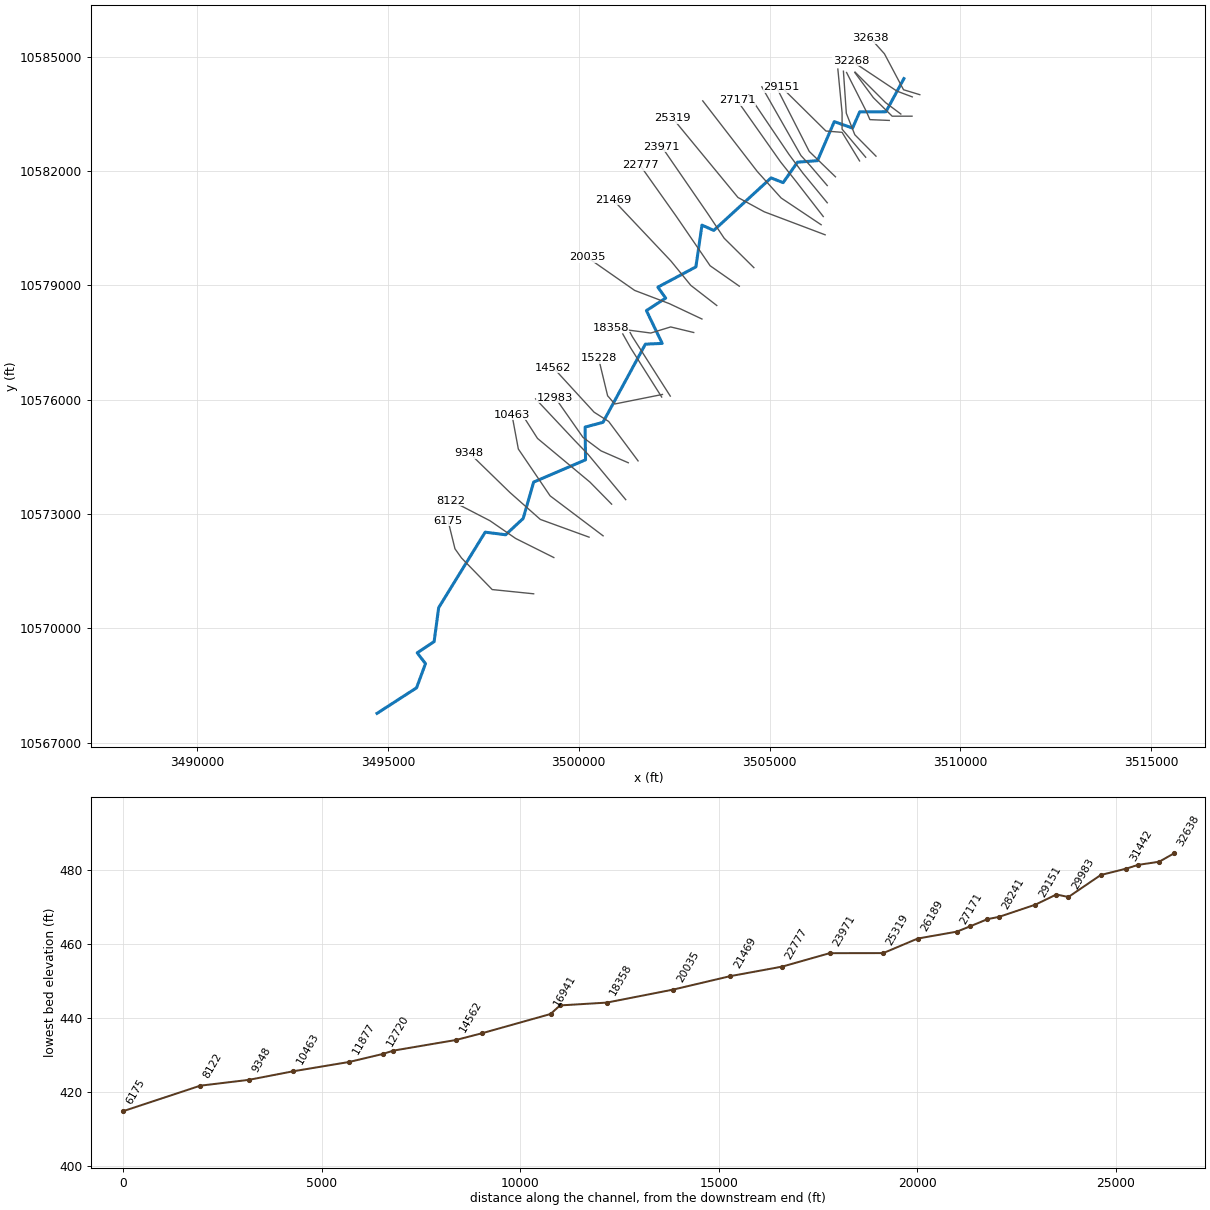
--- UNT0076 IN CHRS.prj (project) ---

Proj Title=UNT0076 IN CHRS Base Level Engineering
Current Plan=p01
Default Exp/Contr=0.3,0.1
English Units
Geom File=g01
Flow File=f01
Plan File=p01
Y Axis Title=Elevation
X Axis Title(PF)=Main Channel Distance
X Axis Title(XS)=Station
BEGIN DESCRIPTION:
UNT0076 IN CHRS
END DESCRIPTION:
DSS Export Rating Curves= 0
DSS Export Rating Curve Sorted= 0
DSS Export Volume Flow Curves= 0
DXF OffsetX= 0
DXF OffsetY= 0
DXF ScaleX= 1
DXF ScaleY= 10

--- UNT0076 IN CHRS.p01 (plan) ---

Plan Title=Multiple Run
Short Identifier=Multiple
Geom File=g01
Flow File=f01
Subcritical Flow
K Sum by GR= 0
Std Step Tol= 0.01
Critical Tol= 0.01
Num of Std Step Trials= 20
Max Error Tol= 0.3
Flow Tol Ratio= 0.001
Split Flow NTrial= 30
Split Flow Tol= 0.02
Split Flow Ratio= 0.02
Log Output Level= 0
Friction Slope Method= 1
Unsteady Friction Slope Method= 2
Unsteady Bridges Friction Slope Method= 1
Parabolic Critical Depth
Global Vel Dist=  1 , 1 , 1
Global Log Level= 0
CheckData=True
Encroach Param= -1, 0, 0, 0
BEGIN DESCRIPTION:
Multiple Run
END DESCRIPTION:

--- UNT0076 IN CHRS.f01 (steady flow) ---

Flow Title=Multiple
Program Version=4.10
Number of Profiles= 7
Profile Names=10-year,25-year,50-year,1pct_min,100-year,1pct_plu,500-year
River Rch & RM=UNT0076 IN CHRS,Reach-1         ,32638
     407     509     583     486     658     890     835
River Rch & RM=UNT0076 IN CHRS,Reach-1         ,32268
     707     909    1062     901    1219    1648    1602
River Rch & RM=UNT0076 IN CHRS,Reach-1         ,29151
     825    1065    1246    1058    1431    1936    1886
River Rch & RM=UNT0076 IN CHRS,Reach-1         ,22777
     921    1191    1396    1186    1604    2170    2116
River Rch & RM=UNT0076 IN CHRS,Reach-1         ,14562
    1228    1604    1893    1619    2190    2961    2925
River Rch & RM=UNT0076 IN CHRS,Reach-1         ,8122
    1314    1723    2038    1746    2362    3194    3168
River Rch & RM=UNT0076 IN CHRS,Reach-1         ,1423
    1554    2051    2436    2095    2834    3832    3829
Boundary for River Rch & Prof#=UNT0076 IN CHRS,Reach-1         , 1
Up Type= 0
Dn Type= 3
Dn Slope=0.002
Boundary for River Rch & Prof#=UNT0076 IN CHRS,Reach-1         , 2
Up Type= 0
Dn Type= 3
Dn Slope=0.002
Boundary for River Rch & Prof#=UNT0076 IN CHRS,Reach-1         , 3
Up Type= 0
Dn Type= 3
Dn Slope=0.002
Boundary for River Rch & Prof#=UNT0076 IN CHRS,Reach-1         , 4
Up Type= 0
Dn Type= 3
Dn Slope=0.002
Boundary for River Rch & Prof#=UNT0076 IN CHRS,Reach-1         , 5
Up Type= 0
Dn Type= 3
Dn Slope=0.002
Boundary for River Rch & Prof#=UNT0076 IN CHRS,Reach-1         , 6
Up Type= 0
Dn Type= 3
Dn Slope=0.002
Boundary for River Rch & Prof#=UNT0076 IN CHRS,Reach-1         , 7
Up Type= 0
Dn Type= 3
Dn Slope=0.002
DSS Import GetInterval= 0
DSS Import GetPeak= 0
DSS Import FillOption= 0

--- UNT0076 IN CHRS.g01 (geometry) ---

Geom Title=Existing Conditions
Program Version=4.10

River Reach=UNT0076 IN CHRS ,Reach-1
Reach XY= 30
      3508522.11     10584421.64      3508052.05     10583551.85
      3507363.49     10583548.83       3507176.6     10583123.26
       3506697.6      10583291.9      3506258.26     10582269.53
      3505733.46     10582229.27      3505356.46     10581692.89
      3505039.54      10581816.5      3503538.37     10580438.97
      3503229.95     10580578.17      3503069.78      10579482.6
      3502072.74     10578950.95       3502278.2     10578664.14
      3501772.94     10578336.04      3502187.12     10577475.74
       3501746.2     10577455.73      3500634.46      10575405.6
      3500165.72      10575280.5      3500178.32     10574423.01
      3498818.65     10573838.93      3498541.71     10572882.39
      3498083.62     10572456.71      3497546.64     10572524.48
      3496328.19     10570544.24       3496208.6     10569653.08
      3495765.41     10569360.03      3495982.96     10569076.78
       3495748.8     10568442.46      3494712.11     10567771.64

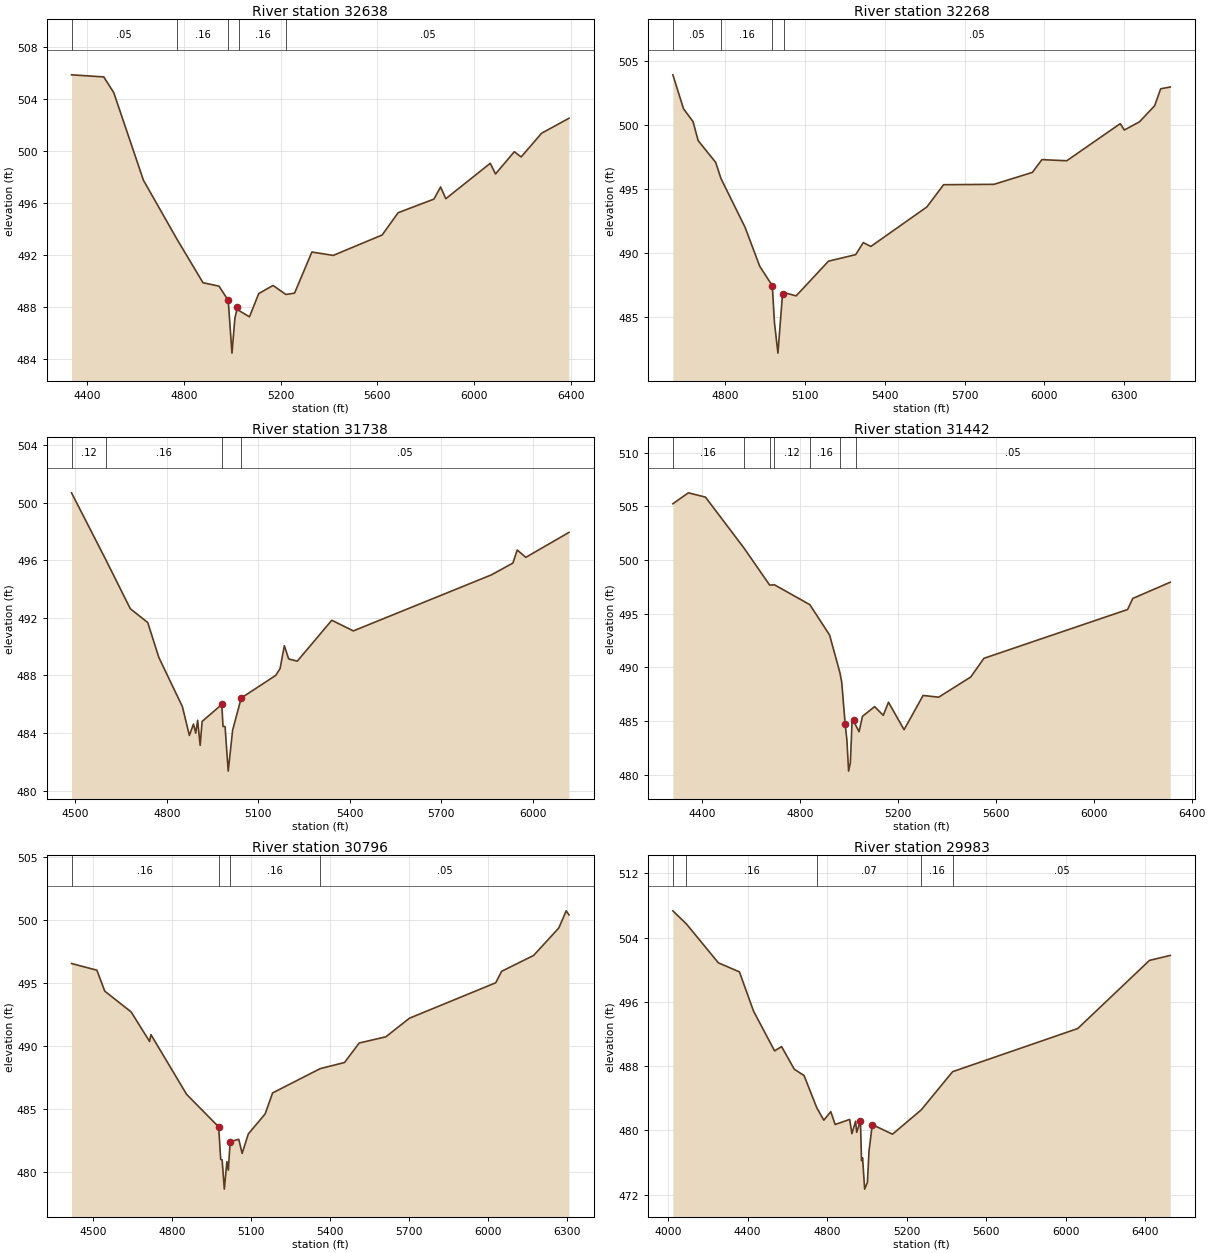
Type RM Length L Ch R = 1 ,32638   ,370,370,370
BEGIN DESCRIPTION:
UNT0076 IN CHRS 50.1
END DESCRIPTION:
XS GIS Cut Line= 4
      3508939.34     10583999.15      3508512.29     10584129.35
      3508012.29     10585072.06      3507648.45     10585477.48
#Sta/Elev= 30
    4335  505.83  4468.4  505.67  4509.8  504.46  4632.5  497.73    4770  493.24
  4879.1  489.85  4945.1  489.59  4983.4   488.5  4998.9  484.44    5011  487.13
  5021.7  487.97  5027.4  487.72  5071.3  487.23  5109.7  489.02  5168.9  489.64
  5222.1  488.95  5257.9  489.05  5329.6  492.21  5417.9  491.95  5620.4  493.52
  5686.4  495.23  5834.7  496.28  5862.2  497.21  5883.9  496.31  6067.8  499.03
  6089.5  498.21  6167.2  499.92  6195.7  499.52  6280.1  501.34  6393.3  502.49
#Mann= 5 ,-1 , 0
    4335     .05       0    4770     .16       0  4983.4     .07       0
  5027.4     .16       0  5222.1     .05       0
Bank Sta=4983.4,5021.7
XS Rating Curve= 0 ,0
Exp/Cntr=0.3,0.1

Type RM Length L Ch R = 1 ,32268   ,530,530,530
BEGIN DESCRIPTION:
UNT0076 IN CHRS 50.0
END DESCRIPTION:
XS GIS Cut Line= 3
      3508742.11     10583941.64      3508342.11     10584091.64
      3507142.12     10584891.63
#Sta/Elev= 30
  4603.6  503.92  4643.7  501.27  4679.3  500.27  4698.8  498.78  4764.7  497.08
  4784.3  495.83  4875.1  492.01  4930.2  488.97  4977.4  487.45  4985.4  484.59
  4998.5  482.19  5015.7  486.79    5021  486.92  5066.9  486.66  5188.5  489.37
  5290.7  489.88  5319.2  490.82  5347.8  490.52  5558.1   493.6  5621.2  495.34
  5810.5  495.37  5954.7   496.3  5990.8   497.3  6083.9  497.21  6285.2  500.11
  6300.3  499.61  6357.3  500.25  6414.4  501.51    6437  502.83    6473  502.97
#Mann= 4 ,-1 , 0
  4603.6     .05       0  4784.3     .16       0  4977.4     .07       0
    5021     .05       0
Bank Sta=4977.4,5015.7
XS Rating Curve= 0 ,0
Exp/Cntr=0.3,0.1

Type RM Length L Ch R = 1 ,31738   ,296,296,296
BEGIN DESCRIPTION:
UNT0076 IN CHRS 49.2
END DESCRIPTION:
XS GIS Cut Line= 3
      3508442.14     10583491.61      3508042.11     10583791.64
      3507242.12     10584591.63
#Sta/Elev= 30
  4487.1  500.68  4599.4  496.04  4679.9  492.63  4737.1  491.67  4773.6  489.24
  4850.7  485.83  4873.6  483.83  4887.1  484.62  4894.4  483.99  4900.7  484.88
    4909  483.14  4915.3   484.8  4979.9  485.98    4984  484.45  4990.7  484.45
    5001  481.35  5015.4  484.19  5043.7  486.43  5156.9     488    5171  488.47
  5185.1  490.06  5199.3  489.14  5227.6  488.99  5340.7  491.83  5411.4  491.09
    5864  494.98  5934.7   495.8  5948.8  496.71  5977.1   496.2  6118.5  497.93
#Mann= 4 ,-1 , 0
  4487.1     .12       0  4599.4     .16       0  4979.9     .07       0
  5043.7     .05       0
Bank Sta=4979.9,5043.7
XS Rating Curve= 0 ,0
Exp/Cntr=0.3,0.1

Type RM Length L Ch R = 1 ,31442   ,646,646,646
BEGIN DESCRIPTION:
UNT0076 IN CHRS 49.1
END DESCRIPTION:
XS GIS Cut Line= 4
      3508735.35      10583435.4      3508214.53      10583435.4
      3507721.48     10583921.51      3507236.25     10584580.03
#Sta/Elev= 30
  4281.4  505.25  4344.6  506.27  4414.6  505.87  4571.4  501.14  4676.9  497.67
  4696.4   497.7  4840.7  495.85  4921.5  493.02  4963.9  489.48    4971  488.62
  4985.2  484.69  4992.2  483.22  4999.1  480.34  5006.3  481.13  5013.4  485.08
  5020.5  485.07  5027.6  484.64  5041.7  484.01  5055.9  485.45  5105.3  486.35
  5140.7  485.54  5161.9  486.76  5225.6   484.2  5303.3  487.39    5367  487.23
  5497.8  489.11  5551.6  490.85  6138.5   495.4  6159.4  496.43  6312.6  497.94
#Mann= 7 ,-1 , 0
  4281.4     .16       0  4571.4     .12       0  4676.9     .16       0
  4696.4     .12       0  4840.7     .16       0  4963.9     .07       0
  5027.6     .05       0
Bank Sta=4985.2,5020.5
XS Rating Curve= 0 ,0
Exp/Cntr=0.3,0.1

Type RM Length L Ch R = 1 ,30796   ,813,813,813
BEGIN DESCRIPTION:
UNT0076 IN CHRS 49.0
END DESCRIPTION:
XS GIS Cut Line= 4
      3508138.16     10583324.28       3507631.2     10583345.12
      3507540.92     10583553.45      3507020.07     10584581.27
#Sta/Elev= 30
  4419.3  496.55  4515.4  496.02  4545.5  494.35  4645.5   492.7  4715.4  490.35
  4720.4   490.9  4855.7  486.15  4977.4  483.56  4985.1  480.97  4990.5  480.94
  4998.9  478.61  5008.5   480.8    5014  480.12    5021  482.39  5053.7  482.57
  5066.4  481.45  5089.9     483  5153.7  484.59    5182  486.26  5362.4  488.19
  5454.9  488.68  5510.5  490.23  5611.4  490.72    5701   492.2  6028.4  495.02
  6050.6  495.93  6171.9  497.19  6267.7  499.38  6295.6  500.74    6306  500.42
#Mann= 4 ,-1 , 0
  4419.3     .16       0  4977.4     .07       0    5021     .16       0
  5362.4     .05       0
Bank Sta=4977.4,5021
XS Rating Curve= 0 ,0
Exp/Cntr=0.3,0.1

Type RM Length L Ch R = 1 ,29983   ,305,305,305
BEGIN DESCRIPTION:
UNT0076 IN CHRS 48.0
END DESCRIPTION:
XS GIS Cut Line= 4
      3507790.91     10582386.79      3507235.36     10582949.28
      3507013.14     10583511.78      3506936.75     10584615.95
#Sta/Elev= 30
  4024.1  507.33  4092.2   505.7    4253  500.86    4359  499.73  4429.7  494.86
  4535.8   489.9  4571.2  490.43  4634.8  487.62  4684.3  486.82  4747.9  482.83
  4783.3  481.27  4818.6  482.33  4840.6  480.73  4913.7  481.37  4924.7  479.59
  4943.5  481.15  4948.8  479.76  4967.8  481.16  4973.2  476.23  4978.6  476.58
    4989  472.69  5002.9  473.54  5010.8   477.4  5027.3  480.72    5129  479.53
  5273.4  482.55  5431.5  487.31  6060.9  492.68  6421.7  501.16  6526.3  501.78
#Mann= 5 ,-1 , 0
  4024.1     .05       0  4092.2     .16       0  4747.9     .07       0
  5273.4     .16       0  5431.5     .05       0
Bank Sta=4967.8,5027.3
XS Rating Curve= 0 ,0
Exp/Cntr=0.3,0.1

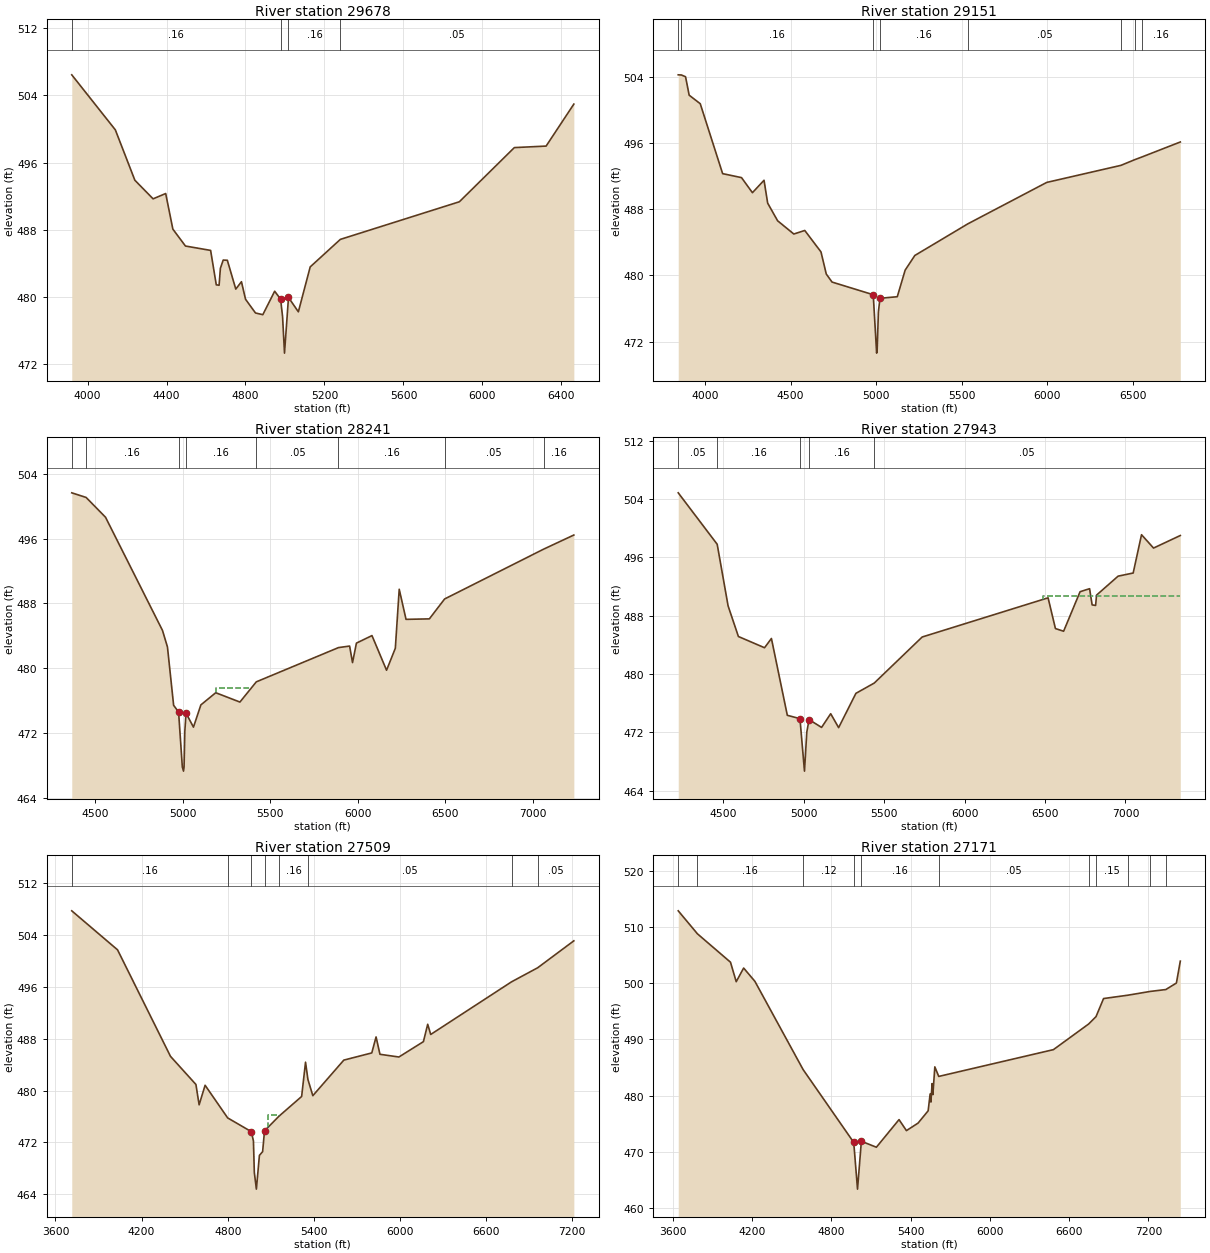
Type RM Length L Ch R = 1 ,29678   ,527,527,527
BEGIN DESCRIPTION:
UNT0076 IN CHRS 47.0
END DESCRIPTION:
XS GIS Cut Line= 4
      3507520.12     10582358.97      3506902.03     10583095.12
      3506902.03     10583525.67      3506790.92     10584671.52
#Sta/Elev= 30
  3920.1  506.43  4140.8  499.89  4239.7   493.9    4332  491.69  4395.8  492.32
  4432.1  488.09  4495.9  486.08  4623.4  485.56    4652  481.47  4666.3  481.42
  4672.8  483.43  4687.1  484.41    4708  484.39  4750.9  480.96  4779.5  481.84
  4800.3  479.75  4850.7  478.12  4887.8  477.92  4947.8  480.71  4977.8  479.77
  4987.8  477.69  4997.6  473.35  5017.8  479.97  5067.8  478.26  5127.8   483.6
  5280.5  486.87  5883.2  491.34  6161.8  497.78  6322.6  497.96  6463.1  502.95
#Mann= 4 ,-1 , 0
  3920.1     .16       0  4977.8     .07       0  5017.8     .16       0
  5280.5     .05       0
#XS Ineff= 1 ,-1
 4597.98 4699.87482.9239
Permanent Ineff=
       F
Bank Sta=4977.8,5017.8
XS Rating Curve= 0 ,0
Exp/Cntr=0.3,0.1

Type RM Length L Ch R = 1 ,29151   ,910,910,910
BEGIN DESCRIPTION:
UNT0076 IN CHRS 46.0
END DESCRIPTION:
XS GIS Cut Line= 4
      3507360.35     10582261.81      3506902.03     10583011.78
      3506478.42     10583046.51      3505318.67     10584192.37
#Sta/Elev= 30
  3843.6  504.22  3862.1   504.2  3886.3  503.99  3907.6  501.76  3972.3  500.73
  4103.1  492.29  4213.4  491.81  4277.3  489.99    4345  491.49  4366.3  488.73
  4424.3   486.6  4519.1     485  4583.1  485.43  4677.9  482.84  4708.8  480.17
  4742.5   479.2  4983.3  477.67  5003.1  470.62  5006.4  471.12  5013.4  475.59
  5022.6  477.24  5123.8  477.43  5169.8  480.64  5226.4  482.41  5536.2  486.23
  5997.2  491.23    6431  493.29  6512.2  493.98  6552.1  494.29  6777.9  496.11
#Mann= 8 ,-1 , 0
  3843.6     .05       0  3862.1     .16       0  4983.3     .07       0
  5022.6     .16       0  5536.2     .05       0    6431     .16       0
  6512.2     .05       0  6552.1     .16       0
Bank Sta=4983.3,5022.6
XS Rating Curve= 0 ,0
Exp/Cntr=0.3,0.1

Type RM Length L Ch R = 1 ,28241   ,298,298,298
BEGIN DESCRIPTION:
UNT0076 IN CHRS 45.0
END DESCRIPTION:
XS GIS Cut Line= 3
      3506728.42     10581845.12      3506040.92     10582511.78
      3505172.86     10584213.18
#Sta/Elev= 30
  4365.8  501.63  4447.9  501.06  4558.7  498.62  4884.1  484.67  4912.4  482.63
  4947.6  475.45  4975.9  474.63  4997.3  467.85    5004  467.34  5007.2  467.84
  5011.4  472.17  5018.4  474.49  5060.8  472.76  5103.2   475.5  5188.1     477
  5326.2  475.85  5419.8  478.34  5889.2  482.56  5952.8  482.75  5969.4  480.71
  5991.6  483.11  6080.5  484.04  6163.8  479.77  6213.9  482.48  6236.1  489.75
    6275  486.04  6408.3   486.1  6495.3  488.55  7060.9  494.69  7233.5  496.43
#Mann= 8 ,-1 , 0
  4365.8     .05       0  4447.9     .16       0  4975.9     .07       0
  5018.4     .16       0  5419.8     .05       0  5889.2     .16       0
  6495.3     .05       0  7060.9     .16       0
#XS Ineff= 1 ,-1
 5188.97 5388.16  477.58
Permanent Ineff=
       F
Bank Sta=4975.9,5018.4
XS Rating Curve= 0 ,0
Exp/Cntr=0.3,0.1

Type RM Length L Ch R = 1 ,27943   ,434,434,434
BEGIN DESCRIPTION:
UNT0076 IN CHRS 44.0
END DESCRIPTION:
XS GIS Cut Line= 4
      3506513.15     10581615.94       3506068.7     10582136.78
      3505825.64     10582400.67      3504797.84     10584206.27
#Sta/Elev= 30
  4220.1  504.84  4462.3  497.79    4530  489.35  4594.1  485.15  4756.6  483.61
  4799.4  484.88  4898.2  474.35  4976.8  473.89  5004.9   466.7  5019.3  472.05
  5033.5  473.76  5111.2  472.69  5167.9  474.57  5217.2  472.66  5324.6  477.36
  5438.7  478.77  5736.5  485.08  6519.3  490.45  6564.9  486.24  6615.8  485.87
  6718.2  491.29  6777.2   491.7  6793.1  489.48  6814.7  489.41  6820.5  490.82
  6954.5  493.42  7048.2  493.85  7100.1   499.1  7174.8  497.27  7341.2  498.99
#Mann= 5 ,-1 , 0
  4220.1     .05       0  4462.3     .16       0  4976.8     .07       0
  5033.5     .16       0  5438.7     .05       0
#XS Ineff= 1 ,-1
 6485.22 7446.28490.7297
Permanent Ineff=
       F
Bank Sta=4976.8,5033.5
XS Rating Curve= 0 ,0
Exp/Cntr=0.3,0.1

Type RM Length L Ch R = 1 ,27509   ,338,338,338
BEGIN DESCRIPTION:
UNT0076 IN CHRS 43.0
END DESCRIPTION:
XS GIS Cut Line= 4
      3506513.14     10581164.56      3505874.25     10581942.34
      3505513.14     10582428.45      3504457.61     10583990.92
#Sta/Elev= 30
  3713.8  507.73  4032.7  501.71  4401.6  485.27  4578.8  480.93    4601  477.79
  4642.7  480.81  4799.9  475.77  4964.7  473.65  4979.4  472.21  4985.6  467.35
  4999.9  464.78    5021  469.99  5043.4  470.56  5056.5  473.77  5156.6  476.02
  5315.2  479.08  5342.3  484.37  5359.1  481.69  5393.2   479.2    5609  484.69
  5803.8   485.8  5833.7  488.27  5860.8  485.59  5992.6  485.17  6163.5  487.54
  6193.4  490.22  6214.4  488.65  6777.3  496.77  6959.3  498.94  7211.5   503.1
#Mann= 8 ,-1 , 0
  3713.8     .16       0  4799.9     .12       0  4964.7     .07       0
  5056.5     .12       0  5156.6     .16       0  5359.1     .05       0
  6777.3     .15       0  6959.3     .05       0
#XS Ineff= 1 ,-1
 5079.22  5156.2476.2255
Permanent Ineff=
       F
Bank Sta=4964.7,5056.5
XS Rating Curve= 0 ,0
Exp/Cntr=0.3,0.1

Type RM Length L Ch R = 1 ,27171   ,982,982,982
BEGIN DESCRIPTION:
UNT0076 IN CHRS 42.0
END DESCRIPTION:
XS GIS Cut Line= 4
      3506408.97     10580803.46       3505693.7     10581727.06
      3505290.92     10582234.01      3504146.94     10583856.38
#Sta/Elev= 30
  3640.7  512.89  3785.9   508.8  4036.3  503.74  4079.7  500.27  4135.9   502.7
  4220.9  500.34  4585.8  484.63  4969.3  471.65  4997.9  463.33    5027  471.86
  5140.7  470.79  5312.1  475.71  5368.2  473.75  5456.4  475.09  5532.7  477.28
  5547.5  480.28  5553.6  478.83  5562.3  482.12  5568.4  480.16  5583.2   485.1
  5612.8   483.4    6481  488.17  6747.8  492.74  6803.5  494.05  6860.6  497.27
  7043.4  497.86  7214.8  498.54  7331.6  498.87  7411.9  500.03  7441.5  503.93
#Mann= 11 ,-1 , 0
  3640.7     .05       0  3785.9     .16       0  4585.8     .12       0
  4969.3     .07       0    5027     .16       0  5612.8     .05       0
  6747.8      .1       0  6803.5     .15       0  7043.4      .1       0
  7214.8     .15       0  7331.6     .05       0
#XS Ineff= 1 ,-1
  5311.1 5467.24  475.36
Permanent Ineff=
       F
Bank Sta=4969.3,5027
XS Rating Curve= 0 ,0
Exp/Cntr=0.3,0.1

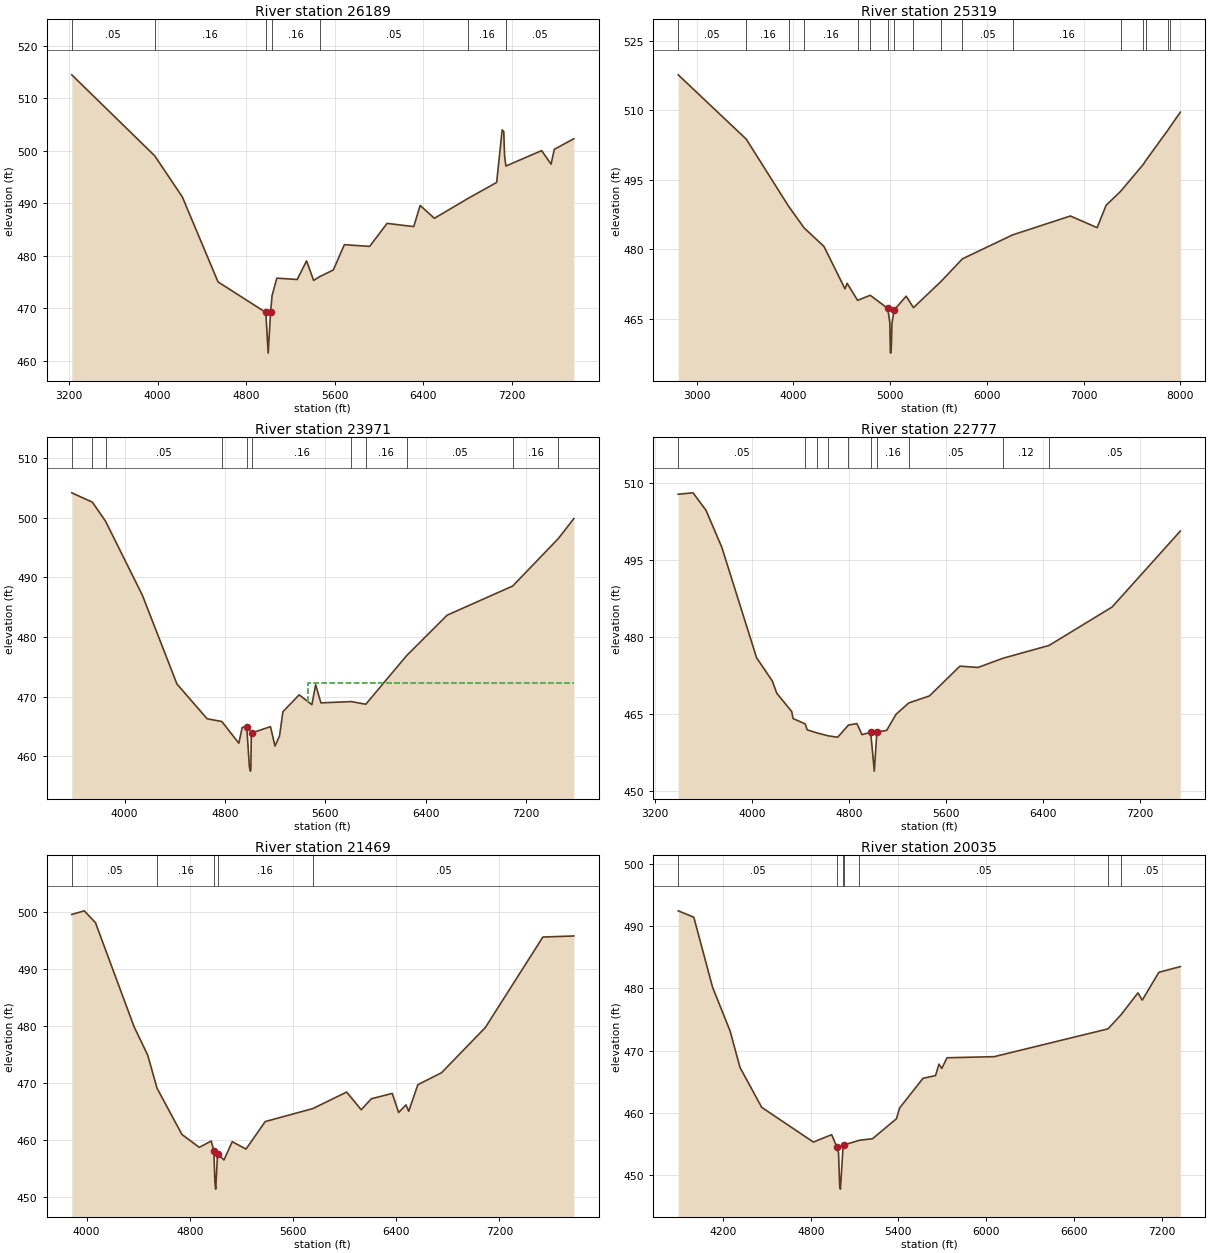
Type RM Length L Ch R = 1 ,26189   ,870,870,870
BEGIN DESCRIPTION:
UNT0076 IN CHRS 40.0
END DESCRIPTION:
XS GIS Cut Line= 4
      3506353.46     10580588.15      3505304.81     10581289.56
      3504679.81     10581984.01      3503249.84     10583837.41
#Sta/Elev= 30
  3223.8  514.44  3973.9  499.02  4223.2  491.19  4545.3  475.04  4977.3  469.22
  4998.7  461.48  5019.9  469.23  5034.1  472.46  5076.7  475.75  5260.5  475.49
  5345.7  479.03  5409.3  475.32  5463.3  476.03  5587.5  477.31  5687.1  482.12
  5915.4  481.79    6073  486.17  6313.9  485.56  6371.9  489.58  6500.6  487.14
  6807.2  490.95  7063.1  493.96  7112.9  503.96  7127.4  503.65  7134.4  499.16
  7146.3  497.08  7469.8  500.02  7554.9  497.44  7583.9  500.26  7760.6  502.28
#Mann= 7 ,-1 , 0
  3223.8     .05       0  3973.9     .16       0  4977.3     .07       0
  5034.1     .16       0  5463.3     .05       0  6807.2     .16       0
  7146.3     .05       0
Bank Sta=4977.3,5019.9
XS Rating Curve= 0 ,0
Exp/Cntr=0.3,0.1

Type RM Length L Ch R = 1 ,25319   ,1348,1348,1348
BEGIN DESCRIPTION:
UNT0076 IN CHRS 38.0
END DESCRIPTION:
XS GIS Cut Line= 4
      3506457.57     10580324.29      3504860.36     10580928.45
      3504172.86     10581303.45      3502457.63     10583386.73
#Sta/Elev= 30
  2809.5  517.68  3512.2  503.79  3950.8  489.26  4110.8   484.6  4315.8   480.6
  4533.3  471.43  4555.1  472.64  4663.4  468.95  4793.8  470.05  4974.7  467.22
  4996.5  464.12    5002  458.05  5004.7  457.55  5012.6  459.24  5018.3  463.96
  5040.1  466.83  5165.4  469.85  5240.8  467.38  5525.8  473.04  5746.5  477.92
    6266   483.1  6862.8  487.18  7139.1  484.66  7231.6  489.48  7381.5   492.5
  7616.2  498.33  7639.8  499.09    7872  505.78    7896  506.52  7998.8  509.61
#Mann= 17 ,-1 , 0
  2809.5     .05       0  3512.2     .16       0  3950.8      .1       0
  4110.8     .16       0  4663.4     .05       0  4793.8     .16       0
  4974.7     .07       0  5040.1     .16       0  5240.8     .12       0
  5525.8     .16       0  5746.5     .05       0    6266     .16       0
  7381.5     .12       0  7616.2     .16       0  7639.8     .12       0
    7872     .16       0    7896     .05       0
Bank Sta=4974.7,5040.1
XS Rating Curve= 0 ,0
Exp/Cntr=0.3,0.1

Type RM Length L Ch R = 1 ,23971   ,1194,1194,1194
BEGIN DESCRIPTION:
UNT0076 IN CHRS 36.0
END DESCRIPTION:
XS GIS Cut Line= 4
       3504589.5     10579463.21      3503811.75     10580234.01
       3503381.2     10580879.84      3502172.89     10582636.75
#Sta/Elev= 30
  3578.1  504.18  3742.6  502.61  3847.2  499.43  4140.8  487.03  4416.6  472.14
  4657.1  466.31  4774.6  465.85  4910.2  462.21  4937.3  464.86  4973.3  464.97
  4994.8   458.2  5003.1  457.53  5006.4  458.03  5009.4   463.4  5018.4  463.96
  5162.6  464.99  5198.7  461.73  5234.7  463.42  5261.8  467.49  5391.4  470.32
  5492.9  468.67  5522.7  472.02  5564.6  468.97    5808  469.19  5922.7  468.74
    6248  476.89  6571.2  483.67  7094.1  488.56  7458.1  496.52  7581.6  499.86
#Mann= 11 ,-1 , 0
  3578.1     .05       0  3742.6      .1       0  3847.2     .05       0
  4774.6     .16       0  4973.3     .07       0  5018.4     .16       0
    5808     .12       0  5922.7     .16       0    6248     .05       0
  7094.1     .16       0  7458.1     .12       0
#XS Ineff= 1 ,-1
 5461.63 7704.38472.2255
Permanent Ineff=
       F
Bank Sta=4973.3,5018.4
XS Rating Curve= 0 ,0
Exp/Cntr=0.3,0.1

Type RM Length L Ch R = 1 ,22777   ,1308,1308,1308
BEGIN DESCRIPTION:
UNT0076 IN CHRS 33.0
END DESCRIPTION:
XS GIS Cut Line= 4
      3504207.58     10578977.07       3503443.7     10579511.78
      3502554.81      10580810.4      3501610.34     10582143.76
#Sta/Elev= 30
  3391.9  507.73  3513.9     508  3621.1   504.6  3751.9  497.37  4037.9  475.95
  4167.6  471.43  4204.2  469.05  4327.3  465.51  4339.2  464.12  4438.5   463.1
  4455.7  461.93  4540.1  461.31  4628.8  460.77  4706.8   460.5  4795.2  462.86
  4865.3  463.15  4907.2     461 4978.89  461.46  5008.6  453.91  5029.8   461.5
  5110.4  461.83  5188.2  464.96  5292.4  467.16  5463.1  468.52  5714.3  474.31
  5863.9  474.06  6069.9  475.85  6449.9  478.34  6969.3   485.8    7532  500.57
#Mann= 10 ,-1 , 0
  3391.9     .05       0  4438.5     .12       0  4540.1     .05       0
  4628.8     .12       0  4795.2     .16       0 4978.89     .07       0
  5029.8     .16       0  5292.4     .05       0  6069.9     .12       0
  6449.9     .05       0
Bank Sta=4978.89,5029.8
XS Rating Curve= 0 ,0
Exp/Cntr=0.3,0.1

Type RM Length L Ch R = 1 ,21469   ,1434,1434,1434
BEGIN DESCRIPTION:
UNT0076 IN CHRS 30.0
END DESCRIPTION:
XS GIS Cut Line= 4
      3503617.32     10578470.11      3502936.75      10578997.9
      3502415.92     10579636.78      3500902.06     10581240.92
#Sta/Elev= 30
  3885.5  499.52  3982.4  500.16  4069.3  498.08    4368  479.85  4474.2  474.84
  4546.3  469.05  4739.2  460.93  4873.5  458.67  4966.1  459.77  4986.9   458.1
  4994.8   452.5    5001  451.34  5015.6  457.58  5065.2  456.45  5129.1  459.66
  5236.1  458.37  5384.7  463.19  5754.1  465.47  6015.9  468.37  6128.8  465.26
  6206.8  467.19  6369.5  468.13  6418.8  464.78  6475.5  466.12  6496.9     465
  6567.7  469.66  6751.4  471.76  7090.8  479.69  7536.6  495.56  7776.7  495.75
#Mann= 5 ,-1 , 0
  3885.5     .05       0  4546.3     .16       0  4986.9     .07       0
  5015.6     .16       0  5754.1     .05       0
Bank Sta=4986.9,5015.6
XS Rating Curve= 0 ,0
Exp/Cntr=0.3,0.1

Type RM Length L Ch R = 1 ,20035   ,1677,1677,1677
BEGIN DESCRIPTION:
UNT0076 IN CHRS 27.0
END DESCRIPTION:
XS GIS Cut Line= 4
       3503228.4     10578115.96      3502374.25     10578518.73
      3501464.53     10578865.95       3500221.5     10579733.99
#Sta/Elev= 30
  3893.9  492.49  4000.4  491.46  4128.7   480.2  4248.2  473.19  4316.5  467.29
  4464.7  460.88  4818.5  455.29  4943.4  456.48  4979.7  454.46  4990.4  453.56
  4998.2  448.24  5003.3  447.72  5022.5  454.98  5028.3  454.83  5133.3  455.58
  5222.8  455.83  5386.4  459.04  5407.8  460.76  5568.4  465.55    5654  465.99
  5677.2  467.83  5696.6  467.13    5732  468.85  6055.2  469.03  6833.6   473.5
    6923  475.78  7038.3  479.29  7067.9  478.13  7181.3   482.6  7328.1  483.52
#Mann= 7 ,-1 , 0
  3893.9     .05       0  4979.7    .035       0  5022.5     .05       0
  5028.3      .1       0  5133.3     .05       0  6833.6     .08       0
    6923     .05       0
Bank Sta=4979.7,5028.3
XS Rating Curve= 0 ,0
Exp/Cntr=0.3,0.1

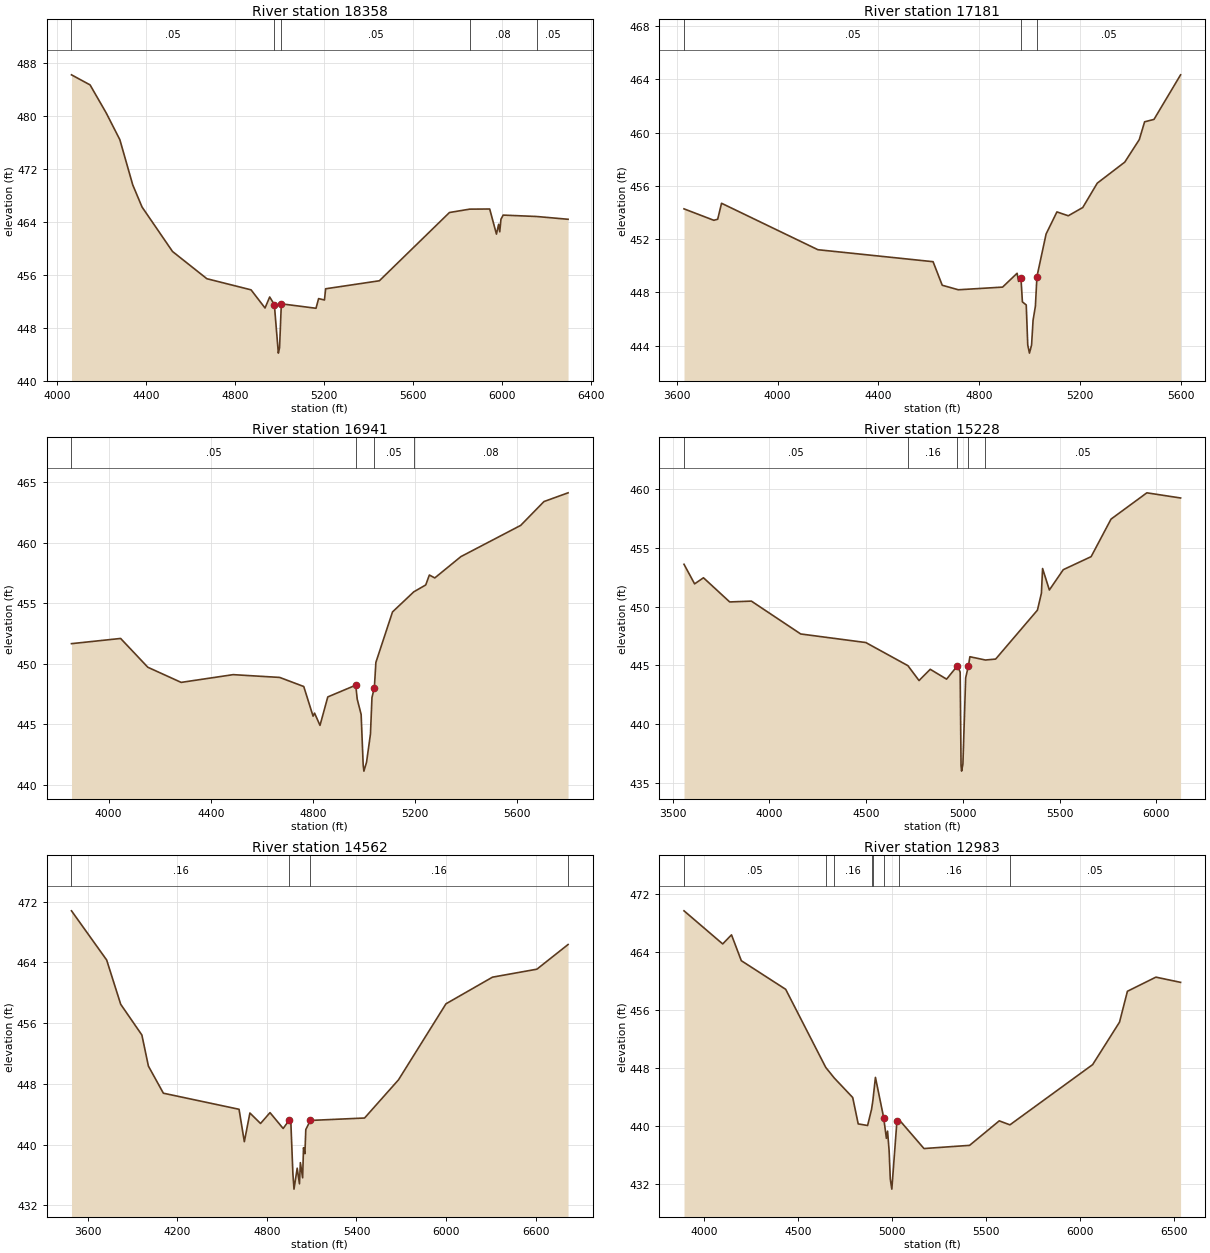
Type RM Length L Ch R = 1 ,18358   ,1177,1177,1177
BEGIN DESCRIPTION:
UNT0076 IN CHRS 25.0
END DESCRIPTION:
XS GIS Cut Line= 4
      3503013.15     10577761.78      3502408.98     10577907.62
      3501888.14      10577747.9      3500833.13     10577886.71
#Sta/Elev= 30
  4065.5   486.2  4148.9  484.68  4220.9  480.48  4282.6  476.42  4340.6  469.59
  4382.4  466.25  4519.2  459.54  4673.5  455.43    4872  453.75  4934.8  451.01
  4955.7  452.67  4976.6  451.53  4994.6   444.2    5000     445    5008  451.64
  5163.8  450.97  5175.4  452.43  5201.7  452.22    5207  453.91  5448.4  455.12
  5763.1  465.42  5853.8  465.93  5943.9  465.95  5974.2  462.16    5984  463.64
    5989  462.51  5994.4   464.4  6004.4  465.03  6154.7  464.82  6295.9   464.4
#Mann= 5 ,-1 , 0
  4065.5     .05       0  4976.6    .035       0    5008     .05       0
  5853.8     .08       0  6154.7     .05       0
Bank Sta=4976.6,5008
XS Rating Curve= 0 ,0
Exp/Cntr=0.3,0.1

Type RM Length L Ch R = 1 ,17181   ,240,240,240
BEGIN DESCRIPTION:
UNT0076 IN CHRS 23.0
END DESCRIPTION:
XS GIS Cut Line= 3
      3502398.83      10576093.6      3501409.24      10577645.7
      3501346.91     10577759.97
#Sta/Elev= 30
  3628.7  454.28  3747.2  453.42  3762.4   453.5  3777.7   454.7  4160.1  451.21
  4617.2  450.31  4653.6  448.54  4717.5   448.2  4893.1   448.4  4950.7  449.44
  4956.6  448.83  4965.9  449.12  4971.8  447.29    4987  447.06    4993  444.05
  4999.8  443.44  5008.2  444.05  5014.1  445.91  5023.4  446.97  5029.4  449.18
  5065.8  452.39  5108.8  454.05  5153.8  453.76  5211.3  454.38  5268.9  456.21
    5378  457.79  5435.6  459.48  5456.8  460.82    5494     461  5599.6  464.35
#Mann= 3 , 0 , 0
  3628.7     .05       0  4965.9     .04       0  5029.4     .05       0
Bank Sta=4965.9,5029.4
XS Rating Curve= 0 ,0
Exp/Cntr=0.3,0.1

Type RM Length L Ch R = 1 ,16941   ,1713,1713,1713
BEGIN DESCRIPTION:
UNT0076 IN CHRS 23.9
END DESCRIPTION:
XS GIS Cut Line= 3
      3502173.47     10576068.95      3501358.54     10577359.25
      3501153.68     10577723.84
#Sta/Elev= 30
  3854.9  451.65  4047.3  452.08  4153.8   449.7  4284.3  448.45  4487.8  449.09
  4670.2  448.86  4764.3  448.11  4800.8  445.66  4806.7  445.91  4827.9   444.9
  4858.4  447.25  4967.8  448.22  4973.7  447.06    4989   445.8    4997  441.62
  4999.8  441.12  5010.2  441.86  5025.5  444.19  5031.4   447.2  5040.8  448.02
  5046.7   450.1  5111.8  454.27    5195  455.93  5241.9   456.5  5256.1  457.32
  5277.4  457.08  5379.5  458.84  5613.7  461.42  5704.9  463.39  5799.2  464.11
#Mann= 4 ,-1 , 0
  3854.9     .05       0  4967.8     .04       0  5040.8     .05       0
    5195     .08       0
Bank Sta=4967.8,5040.8
XS Rating Curve= 0 ,0
Exp/Cntr=0.3,0.1

Type RM Length L Ch R = 1 ,15228   ,666,666,666
BEGIN DESCRIPTION:
UNT0076 IN CHRS 21.0
END DESCRIPTION:
XS GIS Cut Line= 4
      3502193.73     10576136.79       3500943.7     10575886.78
       3500756.2     10576102.06      3500520.09     10577081.22
#Sta/Elev= 30
  3558.4   453.6  3613.2  451.93    3659  452.45  3794.6  450.39  3906.8  450.46
  4161.7  447.66  4498.3  446.93    4716  444.96  4773.6  443.69  4831.5  444.65
    4916  443.81  4972.2  444.95  4986.2  444.41  4990.8  436.47  4993.6  435.97
  5000.4  436.57  5014.7  443.92  5028.9  444.94  5036.5  445.72  5116.7  445.44
  5169.7  445.52  5385.7  449.69  5406.3  451.13  5412.4  453.24  5447.4  451.41
  5519.4  453.14  5663.4  454.25  5766.3  457.45  5951.5  459.69  6125.9  459.25
#Mann= 5 ,-1 , 0
  3558.4     .05       0    4716     .16       0  4972.2     .07       0
  5028.9     .16       0  5116.7     .05       0
Bank Sta=4972.2,5028.9
XS Rating Curve= 0 ,0
Exp/Cntr=0.3,0.1

Type RM Length L Ch R = 1 ,14562   ,1579,1579,1579
BEGIN DESCRIPTION:
UNT0076 IN CHRS 20.0
END DESCRIPTION:
XS GIS Cut Line= 4
       3501554.8     10574393.73      3500783.98     10575428.45
      3500402.03     10575671.51       3499333.3     10576837.39
#Sta/Elev= 30
  3492.2  470.79  3727.7  464.31  3821.6  458.48  3963.4  454.43  4007.2  450.33
  4107.3  446.76    4614  444.64  4649.4  440.37  4686.7  444.15  4757.9  442.77
  4821.3   444.2  4909.3  442.11  4951.7  443.26    4961  442.85  4974.3  436.23
  4981.9  434.12  5003.3  436.88  5018.5  434.82  5024.5  437.61  5039.7  435.61
  5045.6  439.58  5054.9  438.79  5060.9  441.97  5091.4  443.17  5454.4  443.49
  5681.4  448.52  5999.5  458.54  6310.9  462.05  6608.1   463.1  6816.8  466.35
#Mann= 4 ,-1 , 0
  3492.2     .16       0  4951.7     .07       0  5091.4     .16       0
  6816.8     .05       0
Bank Sta=4951.7,5091.4
XS Rating Curve= 0 ,0
Exp/Cntr=0.3,0.1

Type RM Length L Ch R = 1 ,12983   ,263,263,263
BEGIN DESCRIPTION:
UNT0076 IN CHRS 19.0
END DESCRIPTION:
XS GIS Cut Line= 4
      3501297.84     10574345.13      3500582.59     10574657.62
      3500110.36     10575011.78      3499381.21     10576053.43
#Sta/Elev= 30
  3891.4  469.65  4097.3  465.08  4144.1  466.34  4196.3  462.77  4432.4  458.82
  4645.7  448.04    4691  446.58  4789.1  443.89  4818.3  440.25  4868.3  440.03
  4889.4  442.27  4896.4  443.48    4910  446.67  4953.7  441.13  4968.3  438.26
  4974.5  439.25  4982.9  436.51  4989.1  432.63  4997.2  431.25  5024.5  440.69
  5032.9  440.92  5168.3  436.85    5411  437.29  5568.8  440.67  5625.6  440.12
  6065.8  448.43  6208.8  454.29  6250.8  458.55  6402.4   460.5  6533.7  459.78
#Mann= 8 ,-1 , 0
  3891.4     .05       0  4645.7     .12       0    4691     .16       0
  4889.4     .07       0  4896.4     .16       0  4953.7     .07       0
  5032.9     .16       0  5625.6     .05       0
Bank Sta=4953.7,5024.5
XS Rating Curve= 0 ,0
Exp/Cntr=0.3,0.1

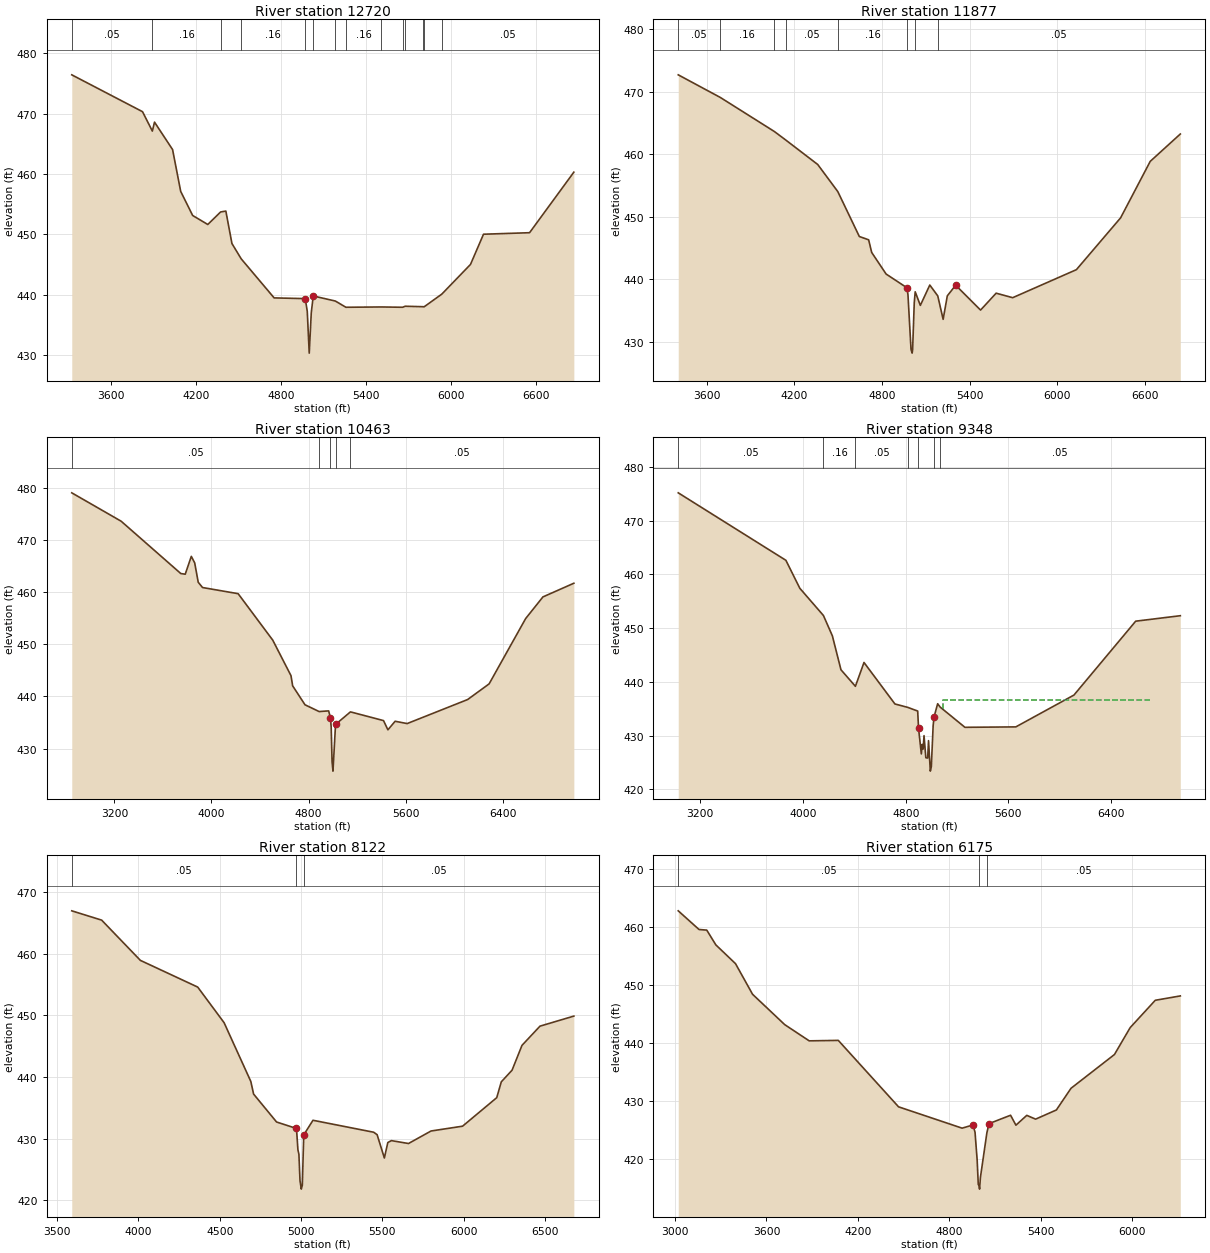
Type RM Length L Ch R = 1 ,12720   ,843,843,843
BEGIN DESCRIPTION:
UNT0076 IN CHRS 16.0
END DESCRIPTION:
XS GIS Cut Line= 4
      3501230.91     10573377.35      3500239.37     10574570.49
      3499887.81     10574935.08      3498869.57     10576021.03
#Sta/Elev= 30
  3323.2  476.41  3822.9  470.31  3892.4   467.1  3907.7  468.58  4035.3  464.04
  4092.6  457.12  4177.2  453.13    4284  451.64  4374.4  453.71  4411.6  453.86
  4454.6  448.49  4519.9  445.96  4752.7  439.49  4972.6  439.37  4986.7  437.25
  5000.6  430.35    5015  437.05    5029  439.81  5185.2  438.97  5259.6  437.94
  5509.2  437.99  5660.2  437.94  5678.1  438.11  5807.7  438.03  5811.2     438
  5937.3  440.12  6139.7  445.03  6231.6  450.03  6556.9  450.28  6869.7   460.3
#Mann= 14 ,-1 , 0
  3323.2     .05       0  3892.4     .16       0  4374.4     .12       0
  4519.9     .16       0  4972.6     .07       0    5029     .16       0
  5185.2     .05       0  5259.6     .16       0  5509.2      .1       0
  5660.2     .05       0  5678.1      .1       0  5807.7     .05       0
  5811.2      .1       0  5937.3     .05       0
Bank Sta=4972.6,5029
XS Rating Curve= 0 ,0
Exp/Cntr=0.3,0.1

Type RM Length L Ch R = 1 ,11877   ,1414,1414,1414
BEGIN DESCRIPTION:
UNT0076 IN CHRS 16.1
END DESCRIPTION:
XS GIS Cut Line= 4
      3500861.25     10573259.55      3500293.54     10573837.68
      3498918.54     10574983.51      3498466.27     10575690.51
#Sta/Elev= 30
  3404.5  472.68  3693.1  469.06  4063.1  463.62  4142.7  462.23    4360  458.35
  4497.6  454.02  4645.1  446.84  4708.9  446.31  4729.7  444.29  4828.6  440.84
  4971.6  438.64  4978.3  437.52  4999.2   428.8  5006.7   428.2    5010   428.7
  5021.3  436.24  5027.8     438    5063  435.83  5127.8  439.08  5182.3  437.35
  5219.2   433.6  5247.8  437.36  5305.1  439.05  5475.6  435.08  5582.3  437.78
  5695.6  437.06  6132.1  441.54  6434.9  449.82  6637.9  458.85  6843.9  463.22
#Mann= 8 ,-1 , 0
  3404.5     .05       0  3693.1     .16       0  4063.1     .12       0
  4142.7     .05       0  4497.6     .16       0  4971.6     .07       0
  5027.8     .16       0  5182.3     .05       0
Bank Sta=4971.6,5305.1
XS Rating Curve= 0 ,0
Exp/Cntr=0.3,0.1

Type RM Length L Ch R = 1 ,10463   ,1115,1115,1115
BEGIN DESCRIPTION:
UNT0076 IN CHRS 14.0
END DESCRIPTION:
XS GIS Cut Line= 4
      3500638.12     10572428.47      3499249.25     10573477.06
      3498415.92     10574706.23      3498249.25     10575602.08
#Sta/Elev= 30
    2849  478.99    3256  473.55  3747.3  463.53  3783.8   463.4  3833.9  466.82
  3861.8  465.57  3890.9  461.86  3926.3  460.85  4219.7  459.67  4504.9  450.77
  4655.2  443.96  4668.8  442.02  4770.6  438.39  4886.8  437.09  4965.3  437.22
  4980.2  435.89  4986.3  434.13  4993.5  427.52    5001  425.68  5022.2  434.62
    5145  437.03  5417.6  435.36  5453.5  433.59    5513  435.23  5612.3  434.79
  6110.3  439.39  6287.4  442.39  6588.4   454.9  6730.8  459.05  6985.5  461.67
#Mann= 5 ,-1 , 0
    2849     .05       0  4886.8     .16       0  4980.2     .07       0
  5022.2     .16       0    5145     .05       0
Bank Sta=4980.2,5022.2
XS Rating Curve= 0 ,0
Exp/Cntr=0.3,0.1

Type RM Length L Ch R = 1 ,9348    ,1226,1226,1226
BEGIN DESCRIPTION:
UNT0076 IN CHRS 12.0
END DESCRIPTION:
XS GIS Cut Line= 4
      3500270.04     10572393.74      3498992.31     10572859.01
       3498193.7     10573567.34      3497131.18     10574602.08
#Sta/Elev= 30
  3028.4  475.21  3866.9  462.64  3975.4  457.43  4159.2  452.36  4228.8  448.58
  4295.8  442.25  4408.3  439.17  4475.2  443.61  4716.1  435.88  4816.7  435.24
  4893.4  434.56  4900.1  431.34  4921.8  426.57  4928.5  428.35    4936  427.48
  4942.7  429.98  4956.9  425.86  4971.2  425.81  4977.8  429.05  4991.8  423.37
  4999.6   424.2  5013.8  431.85  5020.5  433.44  5048.9  435.92    5068  435.31
  5261.4  431.53  5657.8  431.61  6110.5  437.54  6591.3   451.3  6938.8  452.32
#Mann= 7 ,-1 , 0
  3028.4     .05       0  4159.2     .16       0  4408.3     .05       0
  4816.7     .16       0  4893.4     .07       0  5020.5     .16       0
    5068     .05       0
#XS Ineff= 1 ,-1
 5087.55 6699.83 436.595
Permanent Ineff=
       F
Bank Sta=4900.1,5020.5
XS Rating Curve= 0 ,0
Exp/Cntr=0.3,0.1

Type RM Length L Ch R = 1 ,8122    ,1947,1947,1947
BEGIN DESCRIPTION:
UNT0076 IN CHRS 9.0
END DESCRIPTION:
XS GIS Cut Line= 4
      3499346.44     10571859.02      3498346.48     10572359.01
      3497672.86     10572824.28        3496652.     10573352.08
#Sta/Elev= 30
  3590.7  466.94  3774.4  465.43  4012.5   458.9  4364.7  454.57  4526.8   448.8
  4691.2  439.26  4708.3  437.21  4849.5  432.68  4971.9  431.63  4980.7  428.17
  4986.8  427.45  4993.5  423.15  5001.4  421.79  5007.7  422.42  5016.5  430.59
  5073.3  432.96  5446.4  431.02  5467.5  430.62    5512  426.84  5533.2  429.35
  5555.3  429.66  5660.4  429.19  5798.9  431.22  5992.6     432  6202.8  436.63
  6230.6  439.19    6297  441.09  6357.8  445.11  6468.5  448.23  6676.6  449.86
#Mann= 3 , 0 , 0
  3590.7     .05       0  4971.9     .03       0  5016.5     .05       0
#XS Ineff= 1 ,-1
 5099.77 6530.42432.2685
Permanent Ineff=
       F
Bank Sta=4971.9,5016.5
XS Rating Curve= 0 ,0
Exp/Cntr=0.3,0.1

Type RM Length L Ch R = 1 ,6175    ,91,91,91
BEGIN DESCRIPTION:
UNT0076 IN CHRS 4.9
END DESCRIPTION:
XS GIS Cut Line= 5
      3498817.87     10570908.02      3497731.03     10571019.14
      3496925.48       10571849.      3496755.34     10572088.58
      3496574.77     10572821.26
#Sta/Elev= 30
  3020.7  462.78  3157.2  459.57  3208.1  459.46  3267.8  456.92  3396.9  453.69
    3509  448.42  3720.1   443.2  3880.9  440.41  4071.9  440.49  4467.7  429.06
    4885  425.39  4955.7  425.93  4969.9  424.71    4984   419.9  4991.2  415.73
    4997   415.4  4999.8   414.9  5005.3  416.91  5047.8  424.59  5061.9  426.17
  5203.4  427.61  5238.6   425.9  5309.8  427.59  5367.8  426.94  5504.3  428.52
  5600.4  432.25  5885.7  438.06    5989  442.69  6153.8  447.39  6318.2  448.14
#Mann= 3 ,-1 , 0
  3020.7     .05       0    4997     .04       0  5047.8     .05       0
Bank Sta=4955.7,5061.9
XS Rating Curve= 0 ,0
Exp/Cntr=0.3,0.1