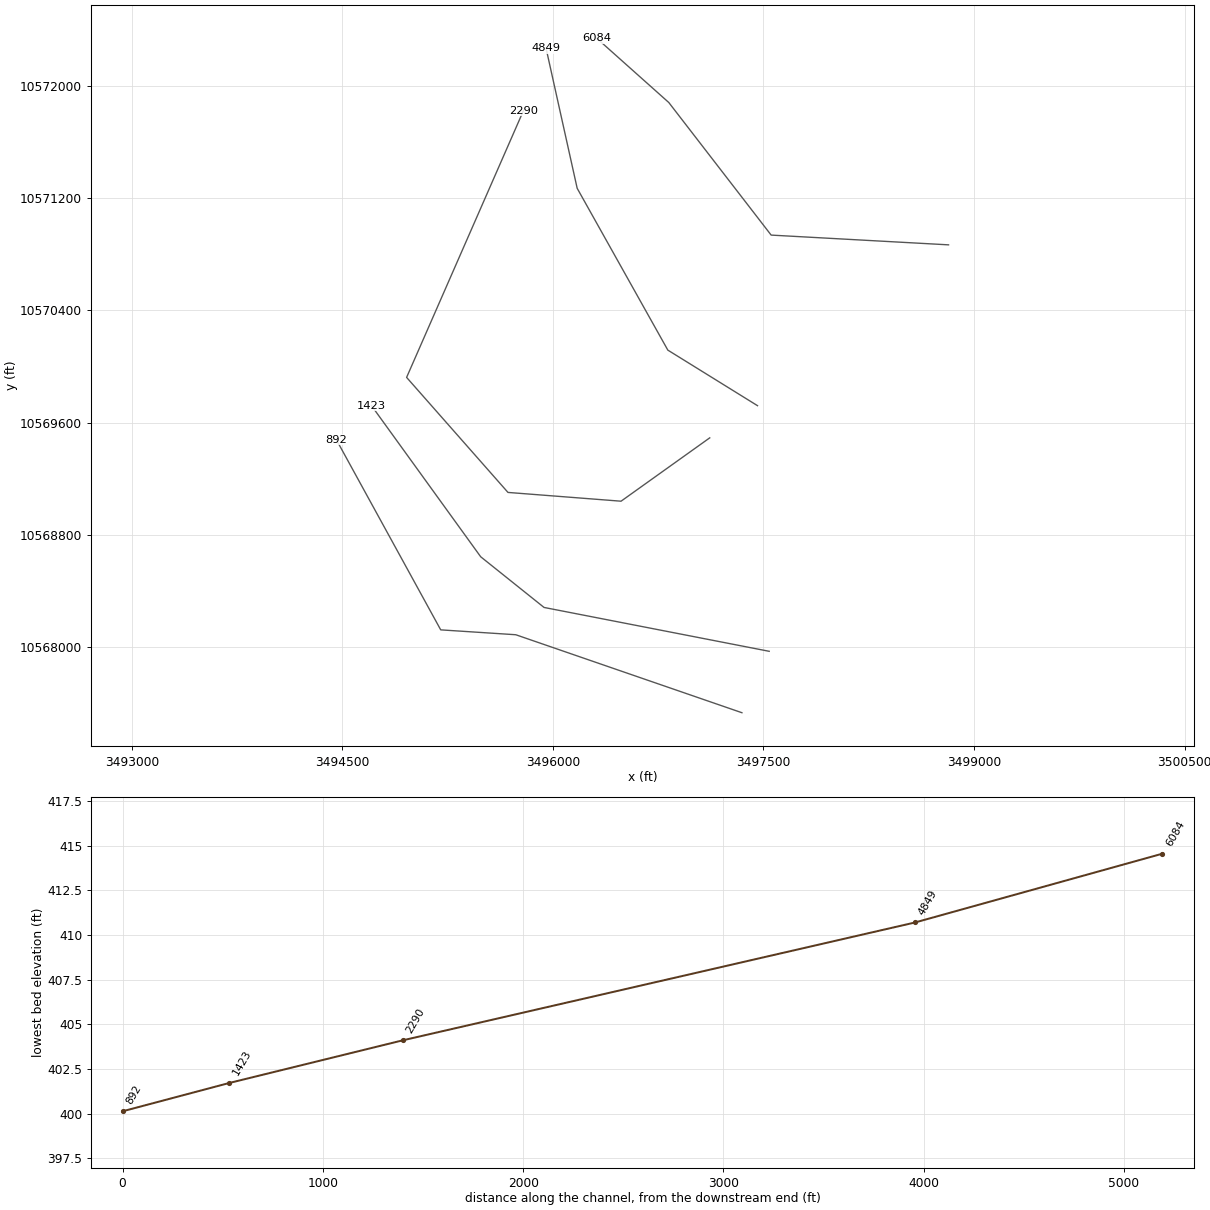
HEC-RAS study UNT0076 IN CHRS.prj: UNT0076 IN CHRS Base Level Engineering

--- UNT0076 IN CHRS.g01 (geometry) --- (continued)

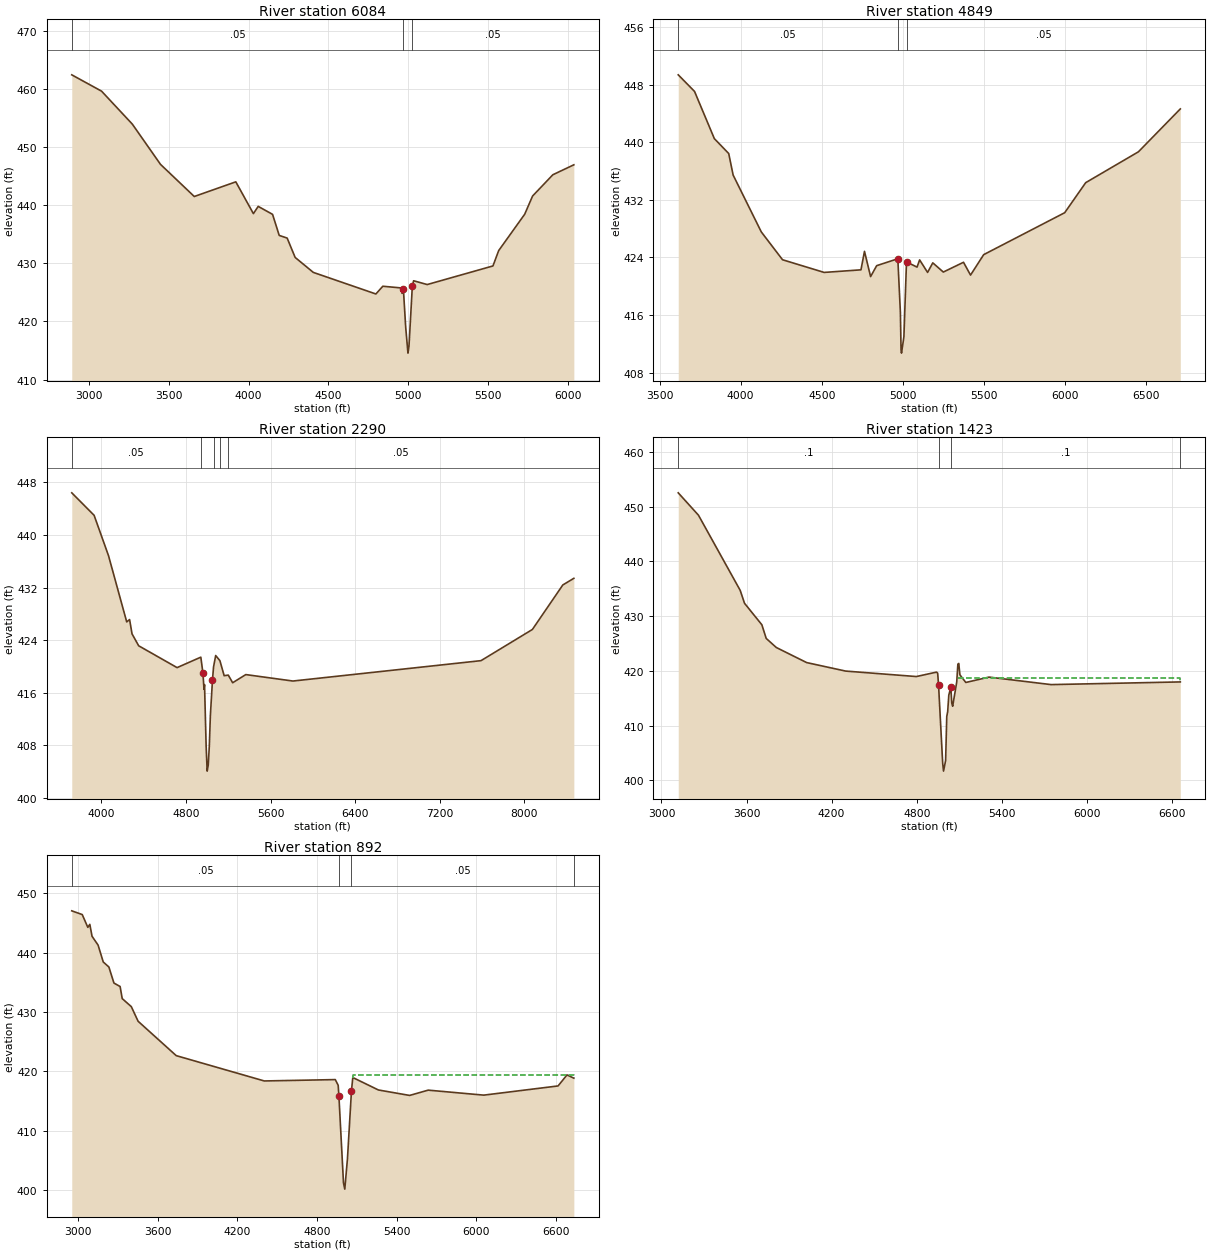
Type RM Length L Ch R = 1 ,6084    ,1235,1235,1235
BEGIN DESCRIPTION:
UNT0076 IN CHRS 4.0
END DESCRIPTION:
XS GIS Cut Line= 4
      3498818.65     10570865.95      3497554.81      10570935.4
      3496825.64     10571879.84      3496312.58     10572337.44
#Sta/Elev= 30
  2892.4   462.4  3079.2  459.59    3272  453.92  3448.3  447.01  3660.1  441.48
  3920.5     444  4030.7  438.53  4060.7  439.78  4150.8  438.41  4192.4  434.79
  4242.2  434.33  4292.4     431  4406.1  428.43  4798.3  424.72  4841.8  426.05
  4955.9  425.76  4962.2  424.83  4970.4  425.66  4984.9  419.06  4999.2  414.55
  5005.7  415.74  5026.5  426.01  5034.7  426.99  5119.9  426.34  5531.9  429.54
  5567.8  432.18  5730.8  438.43  5780.2  441.56  5907.3  445.22  6038.8  446.93
#Mann= 3 , 0 , 0
  2892.4     .05       0  4970.4     .04       0  5026.5     .05       0
Bank Sta=4970.4,5026.5
XS Rating Curve= 0 ,0
Exp/Cntr=0.3,0.1

Type RM Length L Ch R = 1 ,4849    ,2559,2559,2559
BEGIN DESCRIPTION:
UNT0076 IN CHRS 3.0
END DESCRIPTION:
XS GIS Cut Line= 4
      3497457.62     10569720.09       3496818.7     10570115.95
      3496172.86     10571268.73      3495950.87     10572267.68
#Sta/Elev= 30
  3615.3  449.39  3715.9  447.08    3838  440.52  3926.6  438.45  3953.8  435.46
  4127.6  427.55  4258.6  423.68  4515.1  421.92  4742.2  422.28  4763.9  424.85
  4801.6  421.34  4839.2  422.86  4969.5  423.82  4985.3  416.38  4989.4   411.2
  4992.2   410.7    5007  412.98    5023  423.38  5088.1  422.66    5104  423.66
  5153.1  421.92  5185.1  423.25  5250.1  421.97  5374.6  423.33  5417.9  421.55
    5499  424.39  5998.6  430.22  6128.2   434.4  6453.4  438.69  6711.6  444.65
#Mann= 3 , 0 , 0
  3615.3     .05       0  4969.5    .035       0    5023     .05       0
#XS Ineff= 1 ,-1
 3736.63 4767.33424.2668
Permanent Ineff=
       F
Bank Sta=4969.5,5023
XS Rating Curve= 0 ,0
Exp/Cntr=0.3,0.1

Type RM Length L Ch R = 1 ,2290    ,867,867,867
BEGIN DESCRIPTION:
UNT0076 IN CHRS 2.0
END DESCRIPTION:
XS GIS Cut Line= 5
      3497117.28     10569490.93      3496485.36     10569039.56
      3495679.81     10569102.06      3494957.59     10569921.51
       3495789.5     10571820.89
#Sta/Elev= 30
  3719.3  446.42  3930.8     443  4067.2  436.85  4239.2  426.79  4266.4  427.15
  4289.6  424.97  4352.4  423.16  4715.7  419.84  4940.4  421.43  4960.5  418.99
  4970.4  416.55  4975.4  417.25  4990.6  407.91  5000.4   404.1  5010.7  405.04
  5020.7  407.91  5030.7  412.55  5050.8     418  5060.8  419.95  5080.9  421.68
    5121   420.9  5161.1  418.61  5200.2   418.7  5241.4  417.54  5365.8  418.78
  5811.7   417.8  7591.5   420.9  8077.5  425.64  8365.4  432.41  8469.7  433.42
#Mann= 5 ,-1 , 0
  3719.3     .05       0  4940.4    .035       0  5060.8     .05       0
    5121     .16       0  5200.2     .05       0
#XS Ineff= 1 ,-1
 5080.73 8641.84420.8348
Permanent Ineff=
       F
Bank Sta=4960.5,5050.8
XS Rating Curve= 0 ,0
Exp/Cntr=0.3,0.1

Type RM Length L Ch R = 1 ,1423    ,531,531,531
BEGIN DESCRIPTION:
UNT0076 IN CHRS 1.1
END DESCRIPTION:
XS GIS Cut Line= 4
      3497540.94     10567970.11      3495936.75     10568282.62
      3495485.36     10568643.73      3494707.58     10569720.12
#Sta/Elev= 30
  3118.5   452.5  3261.1  448.42  3555.4   434.7    3586  432.34  3708.2  428.42
  3738.8  425.93  3810.1  424.27    4024  421.52  4298.6  419.97  4797.5  418.97
  4939.9  419.78  4947.9  419.59  4954.3  417.38  4983.2  403.18  4989.3  401.71
    5004  403.65    5012  411.67  5018.4  412.54  5026.4  415.57  5040.5  417.02
  5047.2  414.16  5053.6  413.55  5082.4  417.99  5090.4  421.24  5096.8  421.36
  5104.6  419.29  5146.4  417.89  5309.7  418.87  5747.8   417.5  6658.9  417.99
#Mann= 4 ,-1 , 0
  3118.5      .1       0  4954.3     .03       0  5040.5      .1       0
  6658.9     .05       0
#XS Ineff= 1 ,-1
 5094.37  6702.1  418.77
Permanent Ineff=
       F
Bank Sta=4954.3,5040.5
XS Rating Curve= 0 ,0
Exp/Cntr=0.3,0.1

Type RM Length L Ch R = 1 ,892     ,0,0,0
BEGIN DESCRIPTION:
UNT0076 IN CHRS 1.0
END DESCRIPTION:
XS GIS Cut Line= 4
      3497346.52      10567532.6      3495735.36     10568088.17
      3495200.64      10568122.9       3494457.7     10569476.85
#Sta/Elev= 30
  2950.8  447.06  3029.7  446.43  3071.8  444.27  3086.8  444.78  3103.6  442.77
  3149.2  441.28  3188.2  438.43  3230.5  437.59  3268.7  434.88  3315.1   434.3
  3331.1  432.26  3399.7   430.9  3450.7  428.44  3738.2  422.64  4402.1  418.37
    4937   418.6    4959  417.64  4964.4  415.84    4999  401.16  5008.8  400.13
  5029.1  405.33  5059.2  416.75  5069.2  418.95  5262.1  416.85  5497.4  415.93
  5637.4  416.82  6056.4  415.98  6616.4  417.53  6683.7  419.39  6735.3  418.84
#Mann= 4 ,-1 , 0
  2950.8     .05       0  4964.4     .05       0  5059.2     .05       0
  6735.3     .05       0
#XS Ineff= 1 ,-1
 5072.37 6771.88   419.4
Permanent Ineff=
       F
Bank Sta=4964.4,5059.2
XS Rating Curve= 0 ,0
Exp/Cntr=0.3,0.1

Chan Stop Cuts=-1
Use User Specified Reach Order=0
Composite Channel Slope=5