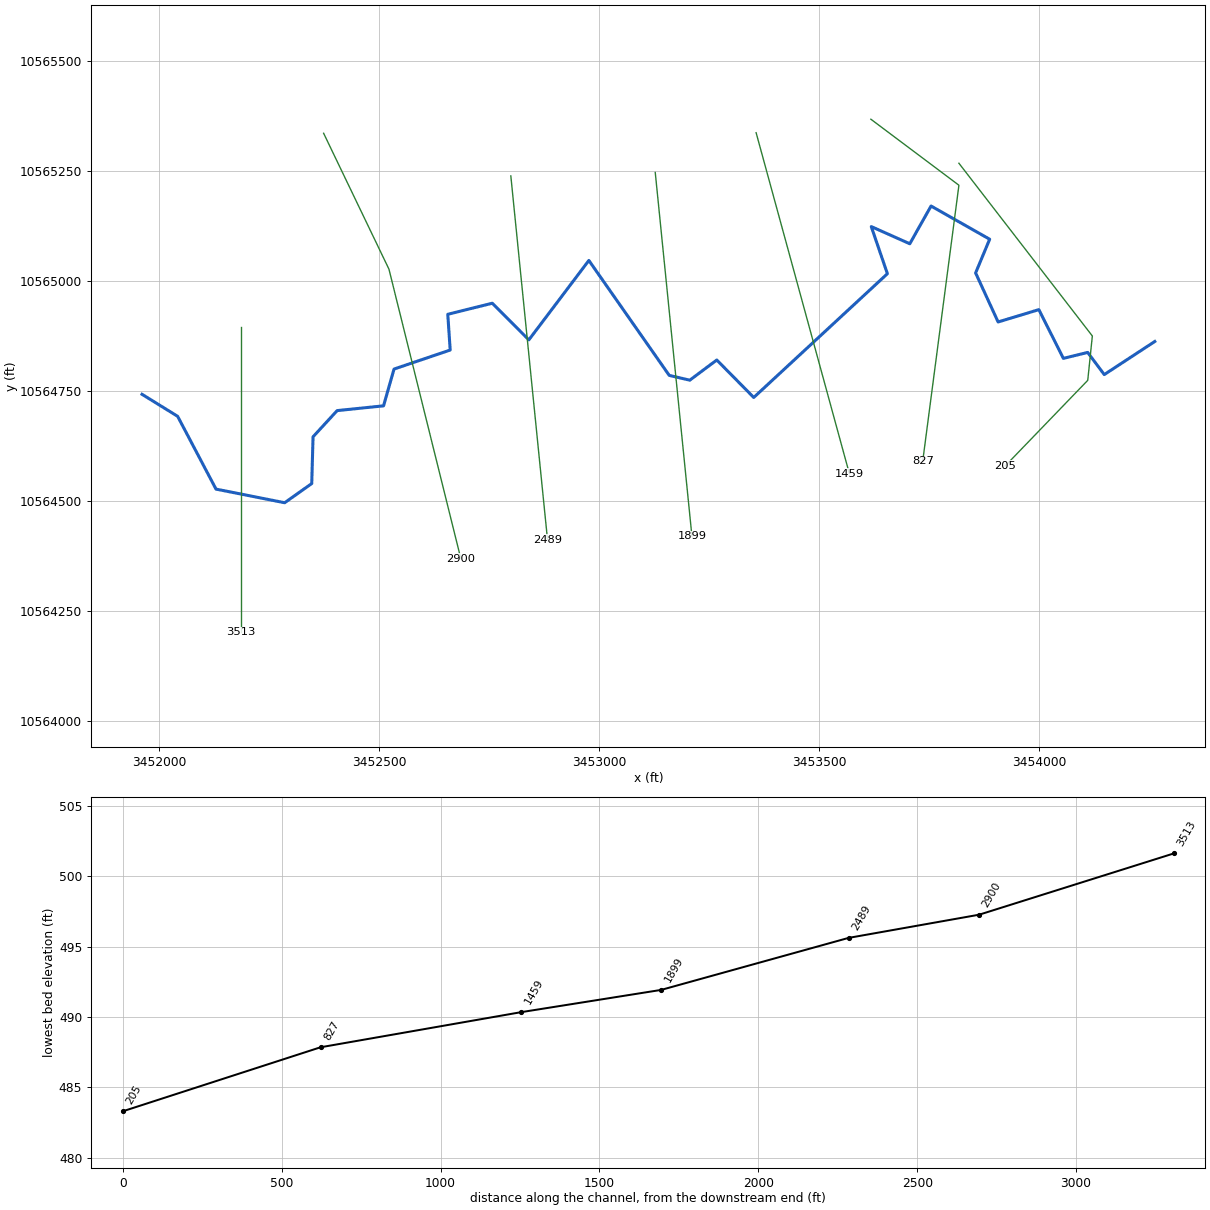
--- UNT00763 IN CHRS.prj (project) ---

Proj Title=UNT00763 IN CHRS Base Level Engineering
Current Plan=p01
Default Exp/Contr=0.3,0.1
English Units
Geom File=g01
Flow File=f01
Plan File=p01
BEGIN DESCRIPTION:
UNT00763 IN CHRS
END DESCRIPTION:

--- UNT00763 IN CHRS.p01 (plan) ---

Plan Title=Multiple Run
Short Identifier=Multiple
Geom File=g01
Flow File=f01
Subcritical Flow
K Sum by GR= 0
Std Step Tol= 0.01
Critical Tol= 0.01
Num of Std Step Trials= 20
Max Error Tol= 0.3
Flow Tol Ratio= 0.001
Split Flow NTrial= 30
Split Flow Tol= 0.02
Split Flow Ratio= 0.02
Log Output Level= 0
Friction Slope Method= 1
Unsteady Friction Slope Method= 2
Unsteady Bridges Friction Slope Method= 1
Parabolic Critical Depth
Global Vel Dist=  1 , 1 , 1
Global Log Level= 0
CheckData=True
Encroach Param= -1, 0, 0, 0
BEGIN DESCRIPTION:
Multiple Run
END DESCRIPTION:

--- UNT00763 IN CHRS.f01 (steady flow) ---

Flow Title=Multiple
Number of Profiles=7
Profile Names=10-year,25-year,50-year,1pct_min,100-year,1pct_plu,500-year
River Rch & RM= UNT00763 IN CHRS,Reach-1,3513
     457     581     674     570     771    1043    1005
River Rch & RM= UNT00763 IN CHRS,Reach-1,2900
     482     613     711     601     812    1099    1057
Boundary for River Rch & Prof#=UNT00763 IN CHRS,Reach-1,1
Up Type=0
Dn Type=3
Dn Slope=0.005
Boundary for River Rch & Prof#=UNT00763 IN CHRS,Reach-1,2
Up Type=0
Dn Type=3
Dn Slope=0.005
Boundary for River Rch & Prof#=UNT00763 IN CHRS,Reach-1,3
Up Type=0
Dn Type=3
Dn Slope=0.005
Boundary for River Rch & Prof#=UNT00763 IN CHRS,Reach-1,4
Up Type=0
Dn Type=3
Dn Slope=0.005
Boundary for River Rch & Prof#=UNT00763 IN CHRS,Reach-1,5
Up Type=0
Dn Type=3
Dn Slope=0.005
Boundary for River Rch & Prof#=UNT00763 IN CHRS,Reach-1,6
Up Type=0
Dn Type=3
Dn Slope=0.005
Boundary for River Rch & Prof#=UNT00763 IN CHRS,Reach-1,7
Up Type=0
Dn Type=3
Dn Slope=0.005

--- UNT00763 IN CHRS.g01 (geometry) ---

Geom Title=Existing Conditions

River Reach=UNT00763 IN CHRS,Reach-1
Reach XY= 30
      3451961.25     10564741.64      3452042.11     10564691.64
      3452129.24     10564526.28      3452285.25     10564495.32
      3452346.76     10564538.88      3452349.75     10564645.15
      3452404.50     10564704.65      3452509.90     10564715.45
      3452533.72     10564798.99      3452661.33     10564842.23
      3452655.84     10564923.45      3452756.97     10564948.58
      3452840.05     10564865.34      3452976.37     10565045.80
      3453158.93     10564784.70      3453205.64     10564773.73
      3453266.99     10564819.61      3453350.98     10564734.48
      3453654.63     10565015.62      3453617.98     10565122.74
      3453705.52     10565083.65      3453753.82     10565169.42
      3453887.01     10565094.00      3453855.06     10565017.40
      3453906.17     10564906.01      3453998.74     10564934.03
      3454054.45     10564823.29      3454109.66     10564836.80
      3454147.33     10564786.47      3454262.11     10564861.64

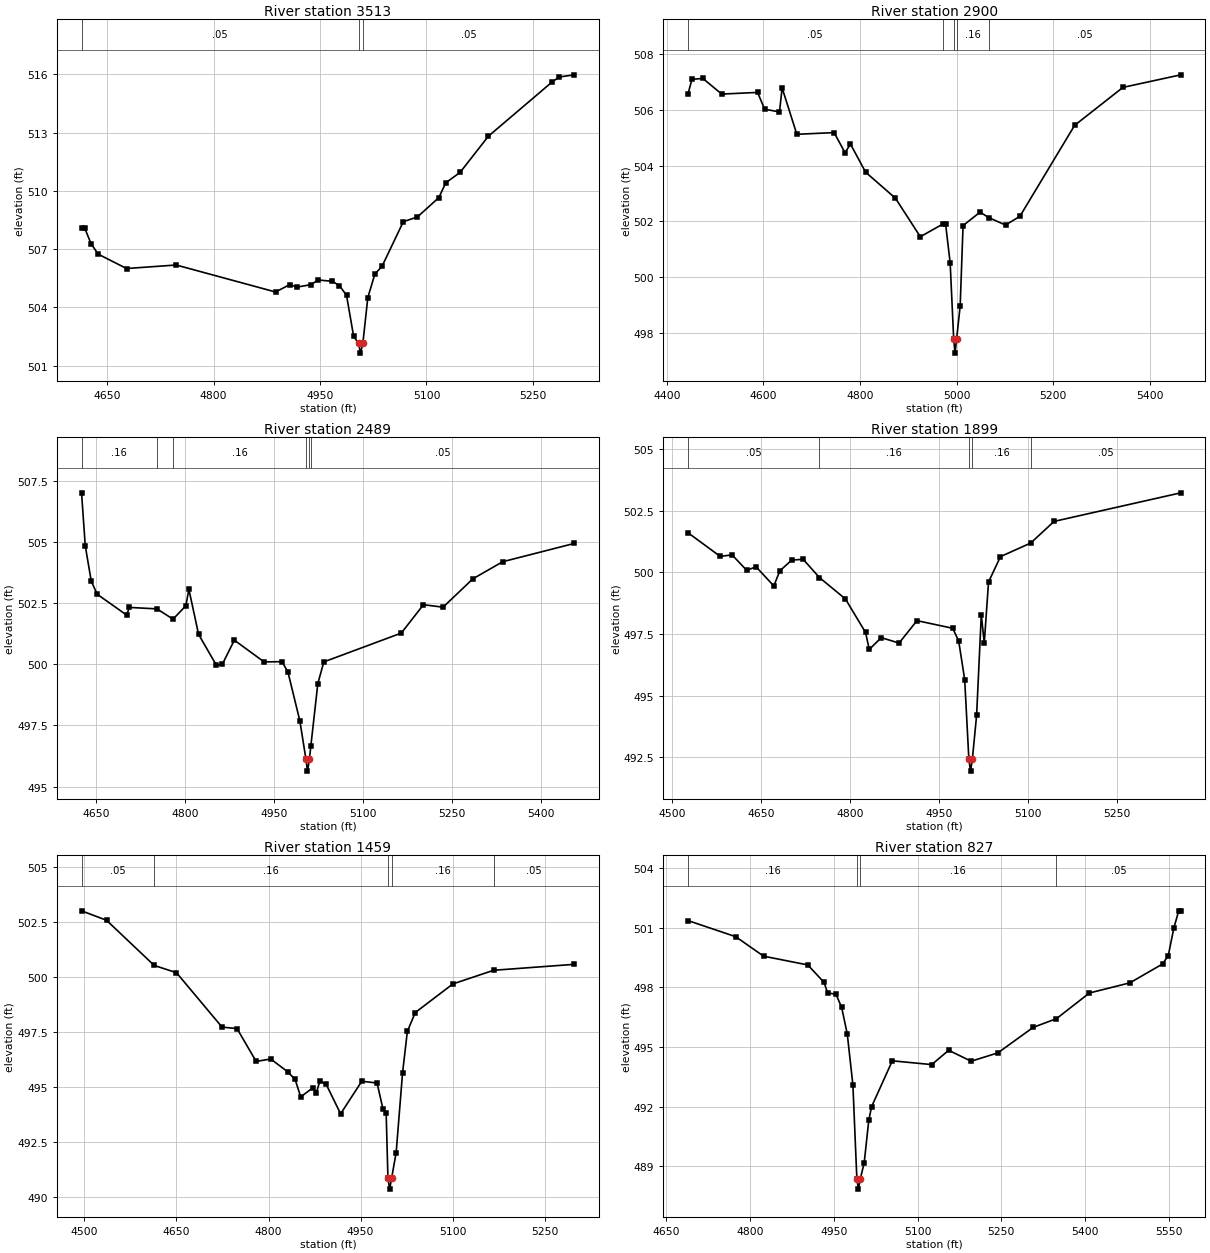
Type RM Length L Ch R = 1,3513,613,613,613
BEGIN DESCRIPTION:
UNT00763 IN CHRS 1.6
END DESCRIPTION:
XS GIS Cut Line= 2
      3452185.08     10564895.00      3452185.08     10564200.50
#Sta/Elev= 30
  4613.9  508.10  4618.1  508.10  4627.3  507.28  4637.3  506.74  4677.3  506.00
  4747.3  506.18  4887.3  504.79  4907.3  505.17  4917.3  505.04  4937.3  505.17
  4947.3  505.41  4967.3  505.34  4977.3  505.12  4987.3  504.62  4997.3  502.51
  5004.3  502.14  5007.0  501.64  5010.3  502.14  5017.3  504.50  5027.3  505.72
  5037.3  506.11  5067.3  508.41  5087.3  508.66  5117.3  509.65  5127.3  510.42
  5147.3  510.95  5187.3  512.82  5277.3  515.62  5287.3  515.87  5308.4  515.98
#Mann=3,-1,0
  4613.9    0.05       0  5004.3   0.035       0  5010.3    0.05       0
Bank Sta=5004.3,5010.3
Exp/Cntr=0.3,0.1

Type RM Length L Ch R = 1,2900,411,411,411
BEGIN DESCRIPTION:
UNT00763 IN CHRS 1.5
END DESCRIPTION:
XS GIS Cut Line= 3
      3452373.79     10565334.66      3452522.20     10565025.97
      3452685.46     10564368.45
#Sta/Elev= 30
  4443.9  506.56  4452.2  507.09  4474.8  507.12  4513.8  506.56  4588.0  506.62
  4602.6  506.02  4633.3  505.92  4638.8  506.78  4669.2  505.12  4746.4  505.18
  4769.0  504.46  4780.2  504.77  4811.7  503.76  4873.3  502.83  4924.8  501.45
  4971.0  501.90  4977.1  501.91  4986.6  500.51  4993.9  497.78  4996.7  497.28
  4999.9  497.78  5007.3  498.97  5013.3  501.85  5048.5  502.33  5067.0  502.13
  5101.2  501.87  5130.9  502.18  5244.2  505.44  5344.2  506.80  5463.9  507.25
#Mann=5,-1,0
  4443.9    0.05       0  4971.0    0.16       0  4993.9    0.07       0
  4999.9    0.16       0  5067.0    0.05       0
Bank Sta=4993.9,4999.9
Exp/Cntr=0.3,0.1

Type RM Length L Ch R = 1,2489,590,590,590
BEGIN DESCRIPTION:
UNT00763 IN CHRS 1.4
END DESCRIPTION:
XS GIS Cut Line= 2
      3452799.08     10565237.83      3452882.42     10564411.43
#Sta/Elev= 30
  4625.3  507.02  4631.5  504.86  4641.6  503.41  4651.6  502.87  4701.1  502.02
  4706.1  502.33  4752.4  502.27  4779.5  501.85  4801.1  502.40  4806.2  503.07
  4822.5  501.23  4852.6  499.96  4862.7  500.01  4882.8  500.99  4933.0  500.10
  4963.2  500.11  4973.2  499.68  4993.3  497.68  5003.4  496.13  5006.1  495.63
  5009.4  496.13  5011.8  496.67  5023.5  499.21  5033.6  500.10  5164.2  501.28
  5201.5  502.44  5234.6  502.34  5284.8  503.50  5335.1  504.20  5455.9  504.95
#Mann=6,-1,0
  4625.3    0.16       0  4752.4    0.05       0  4779.5    0.16       0
  5003.4    0.07       0  5009.4    0.16       0  5011.8    0.05       0
Bank Sta=5003.4,5009.4
Exp/Cntr=0.3,0.1

Type RM Length L Ch R = 1,1899,440,440,440
BEGIN DESCRIPTION:
UNT00763 IN CHRS 1.3
END DESCRIPTION:
XS GIS Cut Line= 2
      3453127.21     10565245.66      3453210.54     10564419.25
#Sta/Elev= 30
  4527.4  501.61  4581.7  500.65  4601.8  500.71  4626.5  500.08  4642.0  500.23
  4672.1  499.45  4682.2  500.06  4702.3  500.50  4721.6  500.53  4749.0  499.79
  4792.8  498.92  4826.7  497.56  4833.0  496.87  4853.1  497.35  4883.2  497.13
  4913.4  498.04  4973.7  497.73  4983.7  497.21  4993.8  495.65  5000.8  492.43
  5003.6  491.93  5006.8  492.43  5013.9  494.20  5021.8  498.28  5026.8  497.13
  5034.0  499.61  5054.1  500.64  5105.0  501.19  5144.5  502.07  5358.0  503.23
#Mann=5,-1,0
  4527.4    0.05       0  4749.0    0.16       0  5000.8    0.07       0
  5006.8    0.16       0  5105.0    0.05       0
Bank Sta=5000.8,5006.8
Exp/Cntr=0.3,0.1

Type RM Length L Ch R = 1,1459,632,632,632
BEGIN DESCRIPTION:
UNT00763 IN CHRS 1.2
END DESCRIPTION:
XS GIS Cut Line= 2
      3453356.36     10565335.97      3453568.18     10564561.62
#Sta/Elev= 30
  4495.4  502.99  4536.1  502.56  4613.7  500.51  4650.0  500.18  4724.2  497.71
  4748.7  497.64  4779.8  496.15  4803.6  496.26  4831.6  495.67  4843.3  495.33
  4852.4  494.54  4872.6  494.96  4877.8  494.71  4883.5  495.25  4893.9  495.11
  4917.4  493.77  4951.9  495.25  4976.8  495.17  4986.4  493.99  4991.6  493.79
  4994.5  490.85  4997.3  490.35  5000.5  490.85  5007.9  492.01  5018.3  495.63
  5026.1  497.51  5039.0  498.37  5100.3  499.67  5166.7  500.29  5298.2  500.56
#Mann=5,-1,0
  4495.4    0.05       0  4613.7    0.16       0  4994.5    0.07       0
  5000.5    0.16       0  5166.7    0.05       0
Bank Sta=4994.5,5000.5
Exp/Cntr=0.3,0.1

Type RM Length L Ch R = 1,827,622,622,622
BEGIN DESCRIPTION:
UNT00763 IN CHRS 1.1
END DESCRIPTION:
XS GIS Cut Line= 3
      3453617.08     10565366.66      3453817.11     10565216.64
      3453734.85     10564589.45
#Sta/Elev= 30
  4688.8  501.35  4774.3  500.54  4824.3  499.56  4903.4  499.12  4932.6  498.24
  4938.8  497.72  4954.0  497.64  4964.0  496.99  4974.1  495.65  4984.2  493.09
  4991.3  488.35  4994.1  487.85  4997.3  488.35  5004.4  489.17  5012.6  491.30
  5017.6  491.99  5054.8  494.30  5125.4  494.11  5155.7  494.83  5196.0  494.28
  5243.9  494.70  5307.0  495.98  5348.8  496.42  5407.8  497.71  5480.3  498.22
  5538.9  499.17  5549.0  499.59  5559.1  500.99  5567.8  501.84  5571.4  501.84
#Mann=4,-1,0
  4688.8    0.16       0  4991.3    0.07       0  4997.3    0.16       0
  5348.8    0.05       0
Bank Sta=4991.3,4997.3
Exp/Cntr=0.3,0.1

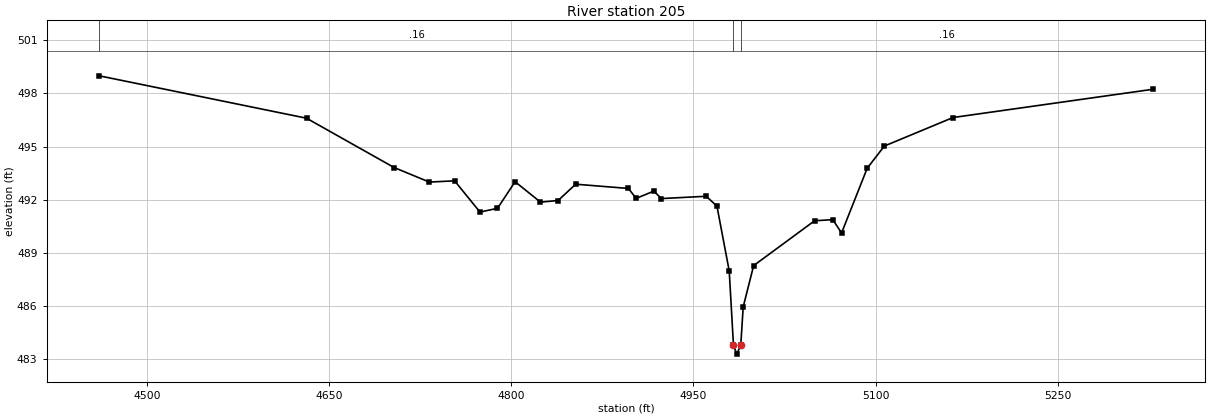
Type RM Length L Ch R = 1,205,0,0,0
BEGIN DESCRIPTION:
UNT00763 IN CHRS 1.0
END DESCRIPTION:
XS GIS Cut Line= 4
      3453817.11     10565266.64      3454120.26     10564874.14
      3454109.84     10564773.44      3453922.34     10564578.99
#Sta/Elev= 30
  4460.9  498.99  4631.5  496.60  4703.6  493.82  4732.6  493.00  4753.4  493.07
  4774.3  491.31  4788.7  491.52  4803.2  493.02  4824.1  491.87  4838.6  491.96
  4853.1  492.88  4896.5  492.64  4902.9  492.08  4917.4  492.49  4923.7  492.07
  4960.6  492.20  4969.4  491.64  4979.5  487.99  4983.0  483.80  4985.7  483.30
  4989.0  483.80  4991.0  485.96  4999.6  488.29  5049.8  490.82  5064.8  490.88
  5072.0  490.13  5093.1  493.78  5107.2  495.03  5163.8  496.64  5328.2  498.23
#Mann=3,-1,0
  4460.9    0.16       0  4983.0    0.07       0  4989.0    0.16       0
Bank Sta=4983,4989
Exp/Cntr=0.3,0.1

Chan Stop Cuts=-1