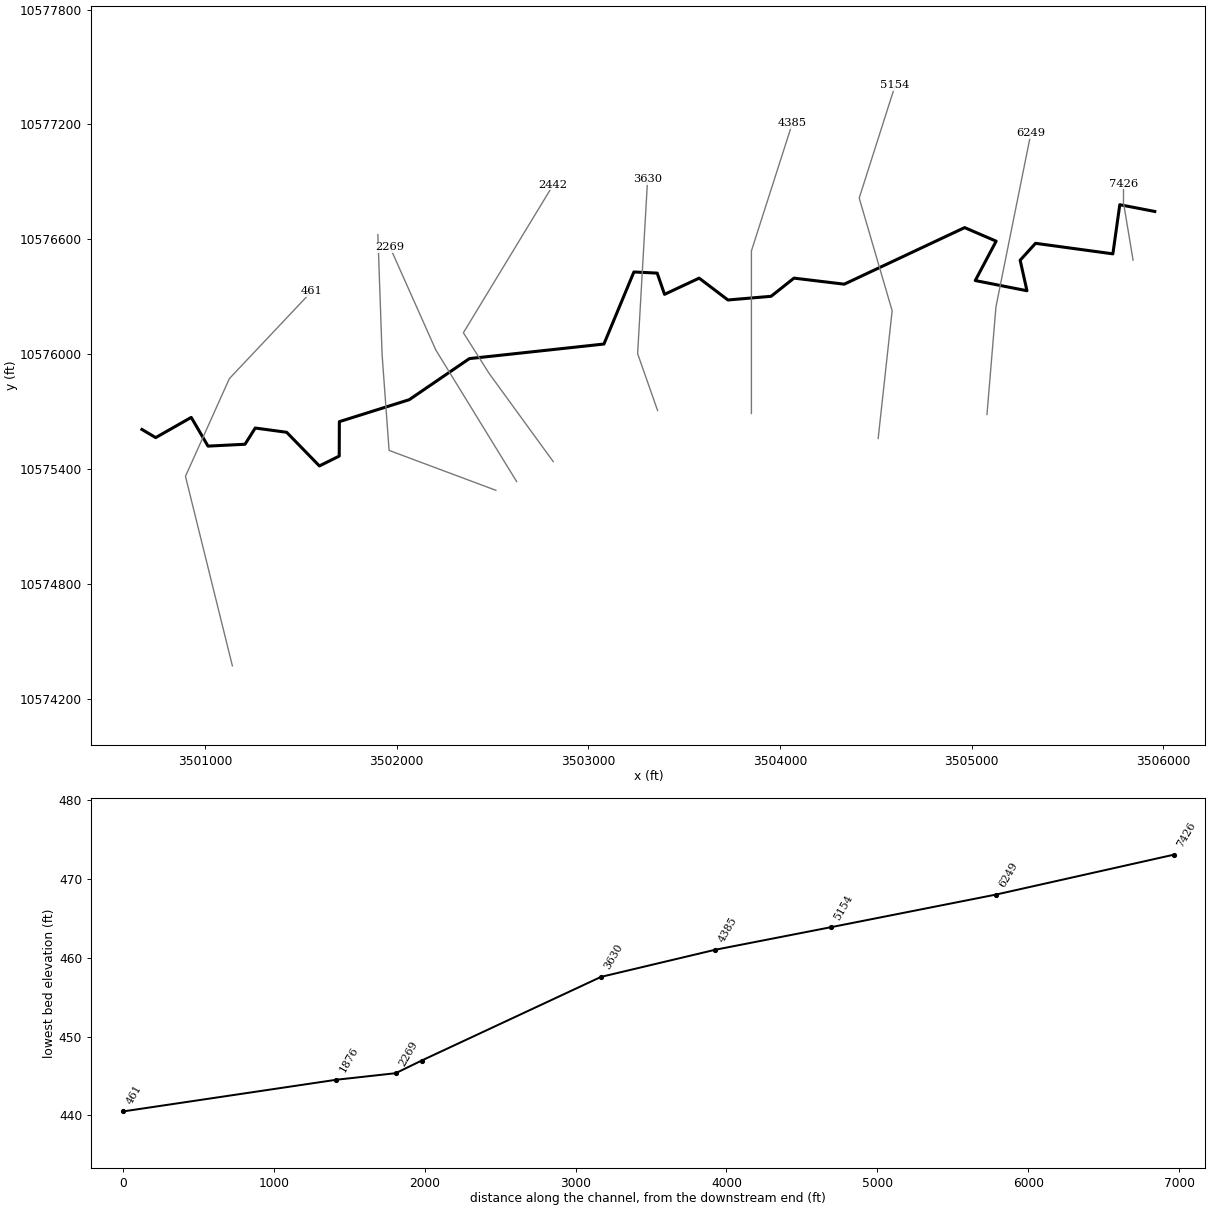
--- UNT0077 IN CHRS.prj (project) ---

Proj Title=UNT0077 IN CHRS Base Level Engineering
Current Plan=p01
Default Exp/Contr=0.3,0.1
English Units
Geom File=g01
Flow File=f01
Plan File=p01
Y Axis Title=Elevation
X Axis Title(PF)=Main Channel Distance
X Axis Title(XS)=Station
BEGIN DESCRIPTION:
UNT0077 IN CHRS
END DESCRIPTION:
DSS Export Rating Curves= 0
DSS Export Rating Curve Sorted= 0
DSS Export Volume Flow Curves= 0
DXF OffsetX= 0
DXF OffsetY= 0
DXF ScaleX= 1
DXF ScaleY= 10

--- UNT0077 IN CHRS.p01 (plan) ---

Plan Title=Multiple Run
Short Identifier=Multiple
Geom File=g01
Flow File=f01
Subcritical Flow
K Sum by GR= 0
Std Step Tol= 0.01
Critical Tol= 0.01
Num of Std Step Trials= 20
Max Error Tol= 0.3
Flow Tol Ratio= 0.001
Split Flow NTrial= 30
Split Flow Tol= 0.02
Split Flow Ratio= 0.02
Log Output Level= 0
Friction Slope Method= 1
Unsteady Friction Slope Method= 2
Unsteady Bridges Friction Slope Method= 1
Parabolic Critical Depth
Global Vel Dist=  1 , 1 , 1
Global Log Level= 0
CheckData=True
Encroach Param= -1, 0, 0, 0
BEGIN DESCRIPTION:
Multiple Run
END DESCRIPTION:

--- UNT0077 IN CHRS.f01 (steady flow) ---

Flow Title=Multiple
Number of Profiles=7
Profile Names=10-year,25-year,50-year,1pct_min,100-year,1pct_plu,500-year
River Rch & RM= UNT0077 IN CHRS,Reach-1,7426
     394     491     561     468     632     855     800
Boundary for River Rch & Prof#=UNT0077 IN CHRS,Reach-1,1
Up Type=0
Dn Type=3
Dn Slope=0.005
Boundary for River Rch & Prof#=UNT0077 IN CHRS,Reach-1,2
Up Type=0
Dn Type=3
Dn Slope=0.005
Boundary for River Rch & Prof#=UNT0077 IN CHRS,Reach-1,3
Up Type=0
Dn Type=3
Dn Slope=0.005
Boundary for River Rch & Prof#=UNT0077 IN CHRS,Reach-1,4
Up Type=0
Dn Type=3
Dn Slope=0.005
Boundary for River Rch & Prof#=UNT0077 IN CHRS,Reach-1,5
Up Type=0
Dn Type=3
Dn Slope=0.005
Boundary for River Rch & Prof#=UNT0077 IN CHRS,Reach-1,6
Up Type=0
Dn Type=3
Dn Slope=0.005
Boundary for River Rch & Prof#=UNT0077 IN CHRS,Reach-1,7
Up Type=0
Dn Type=3
Dn Slope=0.005

--- UNT0077 IN CHRS.g01 (geometry) ---

Geom Title=Existing Conditions
Program Version=4.10

River Reach=UNT0077 IN CHRS ,Reach-1
Reach XY= 30
      3505955.32     10576745.82      3505772.76     10576781.03
      3505736.65     10576524.41      3505332.98     10576579.45
      3505252.87     10576491.11      3505288.44     10576331.81
      3505018.61     10576385.04       3505127.6     10576590.68
      3504963.23     10576661.45      3504334.92     10576366.09
      3504072.78     10576397.65      3503953.34     10576302.73
       3503728.1     10576283.56      3503577.83     10576397.57
      3503397.23     10576312.95      3503358.93     10576423.92
      3503237.35     10576429.76        3503081.      10576053.5
      3502378.94      10575977.4      3502065.05     10575762.82
      3501700.47     10575648.23      3501699.77     10575468.37
       3501596.3     10575416.98      3501425.47     10575592.68
      3501261.58      10575614.9       3501208.1     10575530.18
      3501015.05     10575520.45      3500927.55     10575670.45
      3500742.13      10575564.9      3500670.29     10575607.41

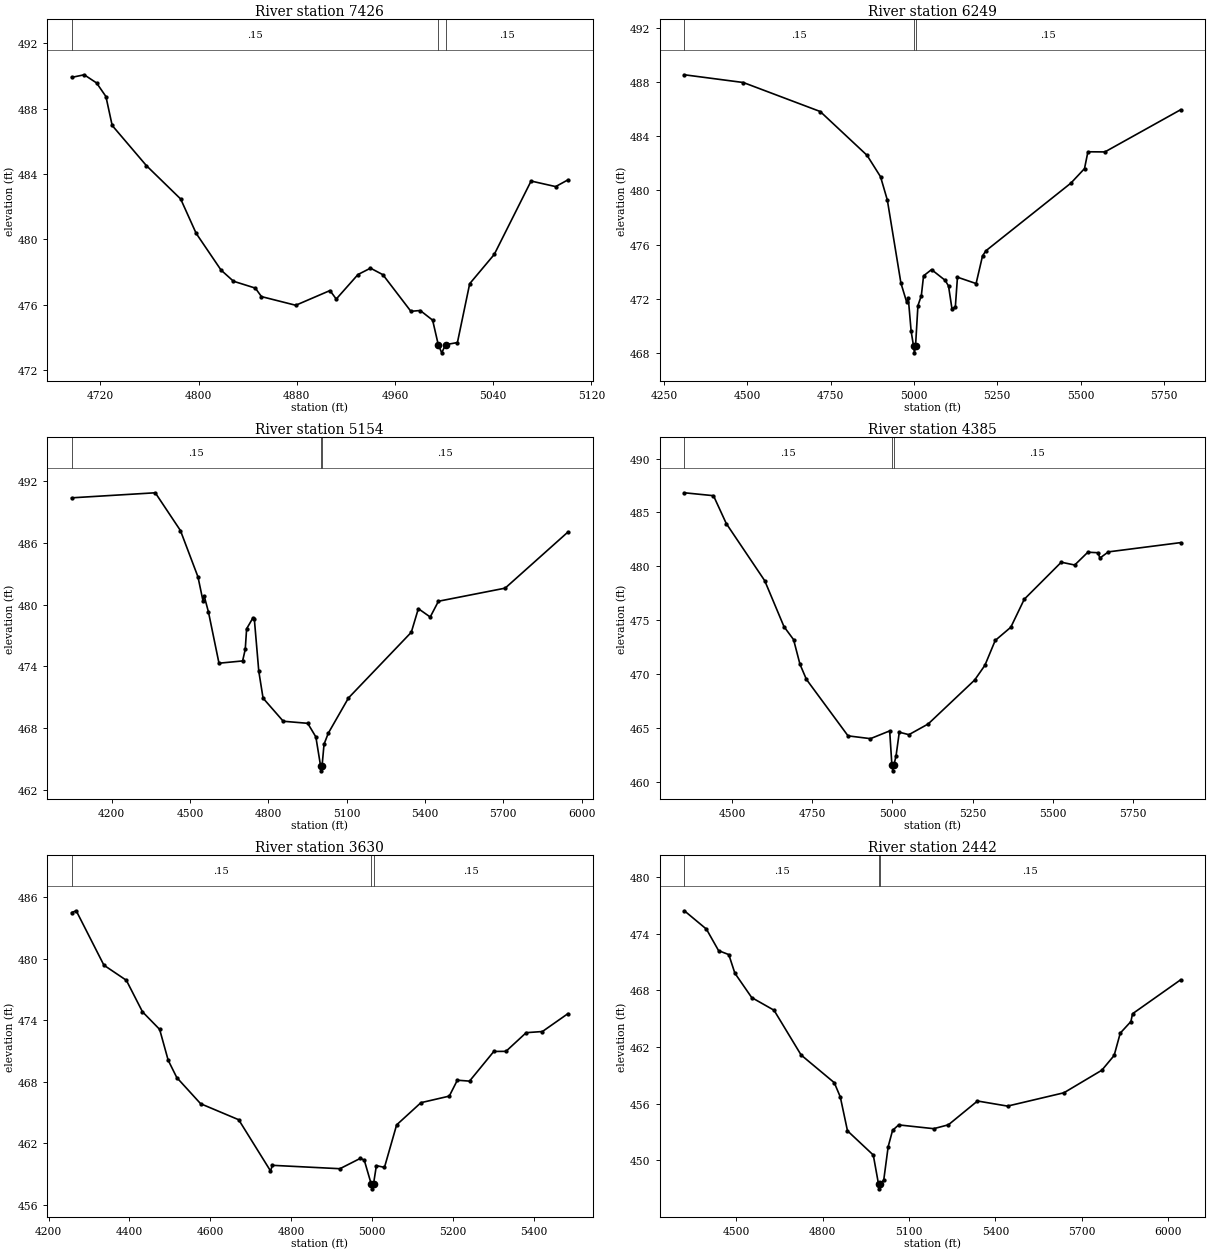
Type RM Length L Ch R = 1 ,7426    ,1177,1177,1177
BEGIN DESCRIPTION:
UNT0077 IN CHRS 12.0
END DESCRIPTION:
XS GIS Cut Line= 3
      3505842.11      10576491.6      3505792.11     10576791.64
      3505792.11     10576891.66
#Sta/Elev= 30
  4696.6  489.91  4706.8  490.07  4716.9  489.57  4724.5  488.74  4729.6  486.97
  4757.5  484.51  4785.4  482.47    4798  480.37  4818.3  478.12  4828.4  477.44
  4846.2  477.02  4851.2   476.5  4879.1  475.97    4907  476.87  4912.1  476.35
  4929.8  477.85    4940  478.24  4950.1  477.84  4972.9   475.6  4980.5  475.65
  4990.6  475.06  4995.2  473.56    4998  473.06  5001.2  473.56  5010.8  473.69
  5020.8  477.29  5040.8  479.08  5070.8  483.57  5090.8  483.23  5100.8  483.64
#Mann= 3 ,-1 , 0
  4696.6     .15       0  4995.2     .05       0  5001.2     .15       0
Bank Sta=4995.2,5001.2
XS Rating Curve= 0 ,0
Exp/Cntr=0.3,0.1

Type RM Length L Ch R = 1 ,6249    ,1095,1095,1095
BEGIN DESCRIPTION:
UNT0077 IN CHRS 10.0
END DESCRIPTION:
XS GIS Cut Line= 3
      3505079.72     10575685.48      3505126.59     10576248.03
      3505308.89     10577154.28
#Sta/Elev= 30
  4311.2  488.52    4488  487.95  4718.8  485.81  4859.3  482.58  4899.8     481
  4920.2  479.28    4961  473.15    4978  471.77  4983.1  472.03  4991.6  469.61
  4998.8  468.51  5001.5  468.01  5004.8  468.51    5012  471.49  5022.2  472.23
  5028.9  473.69  5052.8  474.15  5093.6  473.36  5103.8  472.94    5114  471.28
  5124.2  471.38  5130.6  473.59  5186.5  473.12  5205.8  475.16    5216  475.54
    5471  480.53  5511.8   481.6    5522  482.84    5573  482.83  5800.1  485.94
#Mann= 3 ,-1 , 0
  4311.2     .15       0  4998.8     .05       0  5004.8     .15       0
Bank Sta=4998.8,5004.8
XS Rating Curve= 0 ,0
Exp/Cntr=0.3,0.1

Type RM Length L Ch R = 1 ,5154    ,769,769,769
BEGIN DESCRIPTION:
UNT0077 IN CHRS 8.0
END DESCRIPTION:
XS GIS Cut Line= 4
      3504512.01     10575560.51      3504584.93      10576227.2
      3504413.05     10576815.74      3504600.56      10577404.3
#Sta/Elev= 30
  4046.4  490.35  4366.8  490.84  4463.1  487.18  4530.4  482.68  4549.3  480.39
  4554.4  480.81  4570.6  479.27  4610.9  474.31  4701.4  474.53  4711.5  475.65
  4716.8  477.65  4741.1  478.71  4746.4  478.57  4763.4  473.53  4779.8  470.92
  4857.2  468.68  4950.9  468.48  4982.1  467.16    5000  464.37  5002.7  463.87
    5006  464.37  5013.4  466.45  5029.7  467.52  5107.1  470.94  5347.8  477.31
  5374.8   479.6  5420.3  478.79  5451.8  480.32  5707.4  481.59  5947.9  487.03
#Mann= 3 ,-1 , 0
  4046.4     .15       0    5000     .05       0    5006     .15       0
Bank Sta=5000,5006
XS Rating Curve= 0 ,0
Exp/Cntr=0.3,0.1

Type RM Length L Ch R = 1 ,4385    ,755,755,755
BEGIN DESCRIPTION:
UNT0077 IN CHRS 6.0
END DESCRIPTION:
XS GIS Cut Line= 3
      3503850.55     10575690.76      3503850.55      10576539.7
       3504064.1     10577206.39
#Sta/Elev= 30
  4350.4  486.83  4441.3  486.56  4481.3  483.97  4601.3  478.66  4661.3   474.4
  4691.3  473.19  4711.3   470.9  4731.3   469.5  4861.3  464.25  4931.3  463.99
  4991.3  464.71  4998.3   461.5    5001     461  5004.3   461.5  5011.3  462.41
  5021.3  464.59  5051.3  464.36  5111.3  465.35  5256.4  469.43  5288.5   470.8
  5320.7  473.11  5369.4  474.34  5411.4  476.94  5526.9  480.38  5568.9  480.12
  5609.9  481.31  5642.1  481.26  5647.3  480.76  5673.9  481.34  5899.4   482.2
#Mann= 3 ,-1 , 0
  4350.4     .15       0  4998.3     .05       0  5004.3     .15       0
Bank Sta=4998.3,5004.3
XS Rating Curve= 0 ,0
Exp/Cntr=0.3,0.1

Type RM Length L Ch R = 1 ,3630    ,1188,1188,1188
BEGIN DESCRIPTION:
UNT0077 IN CHRS 3.0
END DESCRIPTION:
XS GIS Cut Line= 3
      3503360.99     10575706.32       3503256.8     10576003.24
      3503308.88     10576914.68
#Sta/Elev= 30
    4257  484.48  4268.3  484.65  4336.8  479.35  4392.3  477.88  4432.2  474.81
  4474.6   473.1  4495.8  470.09    4517  468.41    4576  465.86  4670.2   464.3
  4748.8  459.32  4753.8  459.86  4920.6  459.53  4970.7  460.53  4980.7  460.38
  4997.8  458.07  5000.5  457.57  5003.8  458.07  5010.8  459.83  5030.8  459.66
  5060.9   463.8    5121  465.96  5191.1   466.6  5211.1  468.15  5241.2  468.06
  5301.3  470.95  5331.3  470.96  5381.4  472.78  5421.5  472.89  5484.6  474.63
#Mann= 3 ,-1 , 0
    4257     .15       0  4997.8     .05       0  5003.8     .15       0
Bank Sta=4997.8,5003.8
XS Rating Curve= 0 ,0
Exp/Cntr=0.3,0.1

Type RM Length L Ch R = 1 ,2442    ,173,173,173
BEGIN DESCRIPTION:
UNT0077 IN CHRS 2.3
END DESCRIPTION:
XS GIS Cut Line= 4
      3502816.35     10575439.64      3502482.17     10575899.68
      3502347.62     10576112.36      3502816.36     10576884.91
#Sta/Elev= 30
  4319.2  476.41  4395.8  474.47  4438.1  472.19  4473.6  471.77  4494.7   469.8
  4553.2  467.22  4630.7  465.88  4724.8  461.14    4840  458.21  4860.9   456.7
  4885.9  453.11  4975.5  450.55  4993.7  447.47  4996.4  446.97  4999.7  447.47
  5011.9  447.91  5027.2  451.43  5042.5  453.16  5063.7  453.74  5185.4  453.34
  5236.5  453.75  5337.5  456.27  5441.9  455.73  5637.7  457.14  5769.5  459.53
  5812.2  461.09  5833.5  463.46  5870.4  464.68  5876.2  465.51  6043.1   469.1
#Mann= 3 ,-1 , 0
  4319.2     .15       0  4993.7     .05       0  4999.7     .15       0
Bank Sta=4993.7,4999.7
XS Rating Curve= 0 ,0
Exp/Cntr=0.3,0.1

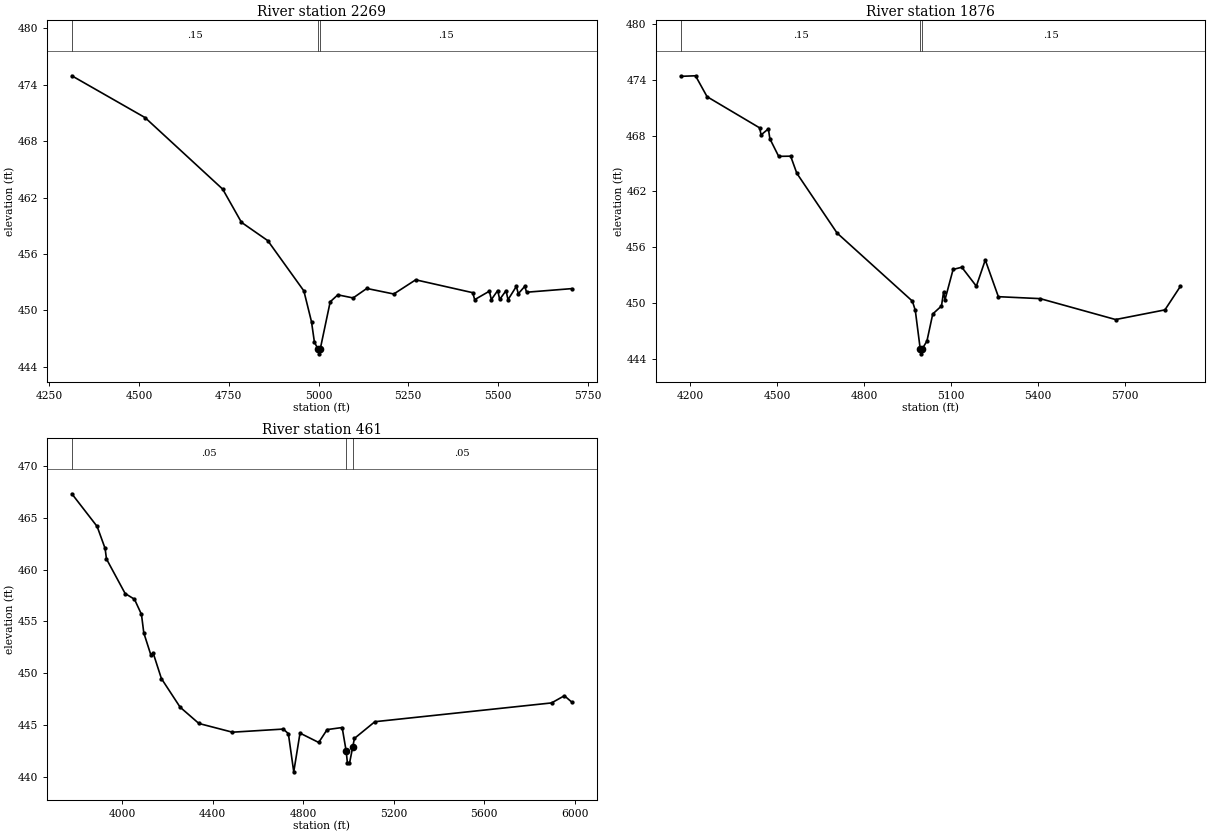
Type RM Length L Ch R = 1 ,2269    ,393,393,393
BEGIN DESCRIPTION:
UNT0077 IN CHRS 2.9
END DESCRIPTION:
XS GIS Cut Line= 3
      3502625.41     10575335.43      3502204.39     10576021.21
      3501965.06     10576558.29
#Sta/Elev= 30
  4312.4  474.96  4516.4  470.51  4732.9  462.89  4785.1  459.36  4858.5  457.41
  4959.1  452.06  4980.4  448.77  4988.5   446.6  4998.7  445.86  5001.4  445.36
  5004.7  445.86  5032.5   450.9  5053.8  451.64  5096.4  451.31  5134.5  452.32
  5209.7  451.73  5270.8  453.24  5429.7  451.87  5435.2  451.13  5476.2  452.03
  5481.6  451.13  5499.4   452.1  5504.9  451.15  5522.6  452.09  5528.1  451.12
  5551.3  452.54  5556.8  451.76  5574.6  452.54    5580  451.92  5705.1   452.3
#Mann= 3 ,-1 , 0
  4312.4     .15       0  4998.7     .05       0  5004.7     .15       0
Bank Sta=4998.7,5004.7
XS Rating Curve= 0 ,0
Exp/Cntr=0.3,0.1

Type RM Length L Ch R = 1 ,1876    ,1415,1415,1415
BEGIN DESCRIPTION:
UNT0077 IN CHRS 2.1
END DESCRIPTION:
XS GIS Cut Line= 4
       3502517.2     10575289.71      3501959.93     10575498.03
      3501923.47     10575998.03      3501901.38     10576625.08
#Sta/Elev= 30
  4166.7  474.39  4217.6  474.45  4257.5   472.2  4438.6  468.85    4444  468.09
  4468.9  468.74  4474.2  467.67  4504.5  465.78  4545.8   465.8  4567.1  463.96
  4705.9  457.53  4965.8   450.2  4975.8   449.2  4992.9  445.03  4995.6  444.53
  4998.9  445.03  5015.9   445.9    5036  448.82  5066.1  449.68  5073.3  451.17
  5078.3  450.36  5106.2  453.61  5136.2  453.85  5186.4  451.81  5217.2  454.63
  5262.3  450.68  5406.7  450.47  5666.8  448.22  5836.9  449.26  5890.4   451.8
#Mann= 3 ,-1 , 0
  4166.7     .15       0  4992.9     .05       0  4998.9     .15       0
Bank Sta=4992.9,4998.9
XS Rating Curve= 0 ,0
Exp/Cntr=0.3,0.1

Type RM Length L Ch R = 1 ,461     ,0,0,0
BEGIN DESCRIPTION:
UNT0077 IN CHRS 1.0
END DESCRIPTION:
XS GIS Cut Line= 4
      3501142.21     10574373.08      3500897.43     10575362.62
      3501126.59     10575873.03      3501557.99     10576330.42
#Sta/Elev= 30
  3778.3   467.3  3890.1  464.15  3925.3  462.03  3931.3  461.02  4013.8  457.69
    4055  457.14  4085.9  455.68  4096.2   453.9  4127.1  451.79  4137.6  451.96
  4173.9   449.5  4256.7  446.74  4339.6  445.17  4487.6  444.33  4712.4  444.63
  4734.9  444.19  4758.7  440.51  4786.4  444.24    4869  443.34  4906.2  444.58
  4972.6  444.78  4990.3  442.51  4995.8  441.36  5004.9  441.32    5019  442.88
  5026.8  443.73  5117.1  445.34  5897.7  447.15  5954.3  447.84  5985.9  447.25
#Mann= 3 , 0 , 0
  3778.3     .05       0  4990.3     .03       0    5019     .05       0
Bank Sta=4990.3,5019
XS Rating Curve= 0 ,0
Exp/Cntr=0.3,0.1

Chan Stop Cuts=-1
Use User Specified Reach Order=0
Composite Channel Slope=5