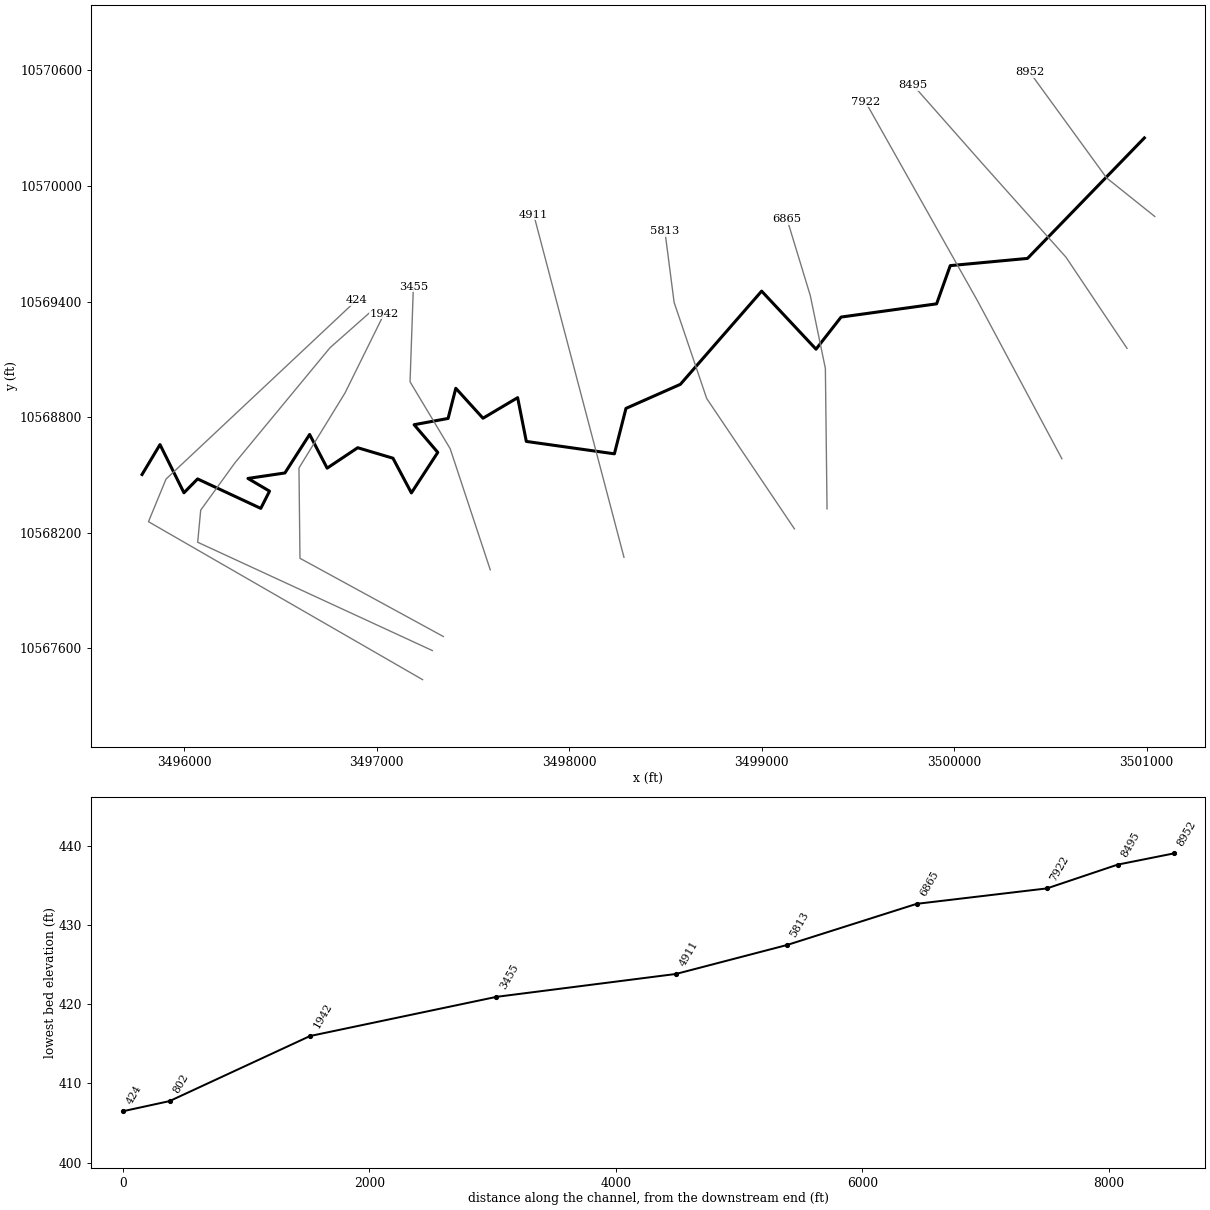
--- UNT0078 IN CHRS.prj (project) ---

Proj Title=UNT0078 IN CHRS Base Level Engineering
Current Plan=p01
Default Exp/Contr=0.3,0.1
English Units
Geom File=g01
Flow File=f01
Plan File=p01
Y Axis Title=Elevation
X Axis Title(PF)=Main Channel Distance
X Axis Title(XS)=Station
BEGIN DESCRIPTION:
UNT0078 IN CHRS
END DESCRIPTION:
DSS Export Rating Curves= 0
DSS Export Rating Curve Sorted= 0
DSS Export Volume Flow Curves= 0
DXF OffsetX= 0
DXF OffsetY= 0
DXF ScaleX= 1
DXF ScaleY= 10

--- UNT0078 IN CHRS.p01 (plan) ---

Plan Title=Multiple Run
Short Identifier=Multiple
Geom File=g01
Flow File=f01
Subcritical Flow
K Sum by GR= 0
Std Step Tol= 0.01
Critical Tol= 0.01
Num of Std Step Trials= 20
Max Error Tol= 0.3
Flow Tol Ratio= 0.001
Split Flow NTrial= 30
Split Flow Tol= 0.02
Split Flow Ratio= 0.02
Log Output Level= 0
Friction Slope Method= 1
Unsteady Friction Slope Method= 2
Unsteady Bridges Friction Slope Method= 1
Parabolic Critical Depth
Global Vel Dist=  1 , 1 , 1
Global Log Level= 0
CheckData=True
Encroach Param= -1, 0, 0, 0
BEGIN DESCRIPTION:
Multiple Run
END DESCRIPTION:

--- UNT0078 IN CHRS.f01 (steady flow) ---

Flow Title=Multiple
Number of Profiles=7
Profile Names=10-year,25-year,50-year,1pct_min,100-year,1pct_plu,500-year
River Rch & RM= UNT0078 IN CHRS,Reach-1,8952
     439     552     635     532     720     973     921
River Rch & RM= UNT0078 IN CHRS,Reach-1,6865
     498     629     726     610     825    1116    1062
Boundary for River Rch & Prof#=UNT0078 IN CHRS,Reach-1,1
Up Type=0
Dn Type=3
Dn Slope=0.005
Boundary for River Rch & Prof#=UNT0078 IN CHRS,Reach-1,2
Up Type=0
Dn Type=3
Dn Slope=0.005
Boundary for River Rch & Prof#=UNT0078 IN CHRS,Reach-1,3
Up Type=0
Dn Type=3
Dn Slope=0.005
Boundary for River Rch & Prof#=UNT0078 IN CHRS,Reach-1,4
Up Type=0
Dn Type=3
Dn Slope=0.005
Boundary for River Rch & Prof#=UNT0078 IN CHRS,Reach-1,5
Up Type=0
Dn Type=3
Dn Slope=0.005
Boundary for River Rch & Prof#=UNT0078 IN CHRS,Reach-1,6
Up Type=0
Dn Type=3
Dn Slope=0.005
Boundary for River Rch & Prof#=UNT0078 IN CHRS,Reach-1,7
Up Type=0
Dn Type=3
Dn Slope=0.005

--- UNT0078 IN CHRS.g01 (geometry) ---

Geom Title=Existing Conditions
Program Version=4.10

River Reach=UNT0078 IN CHRS ,Reach-1
Reach XY= 30
      3500987.94     10570249.63      3500381.07     10569623.95
      3499979.78     10569586.44      3499908.97     10569388.02
      3499412.81     10569319.34       3499282.6     10569152.52
      3499000.12     10569454.04      3498577.93     10568969.89
       3498295.5     10568845.01      3498235.34     10568609.09
      3497777.97     10568673.48       3497732.9     10568900.83
      3497552.89     10568793.96      3497411.68     10568949.43
      3497371.58     10568792.88      3497195.13     10568760.27
      3497318.07     10568616.51      3497180.99     10568406.04
      3497085.28      10568586.4       3496902.2     10568640.74
      3496743.47     10568534.74      3496652.41     10568709.64
      3496524.08     10568509.68      3496332.16     10568481.24
      3496444.25     10568415.18      3496398.75     10568325.77
       3496070.5      10568478.7      3495999.73     10568406.78
      3495875.32     10568657.04      3495782.11     10568501.64

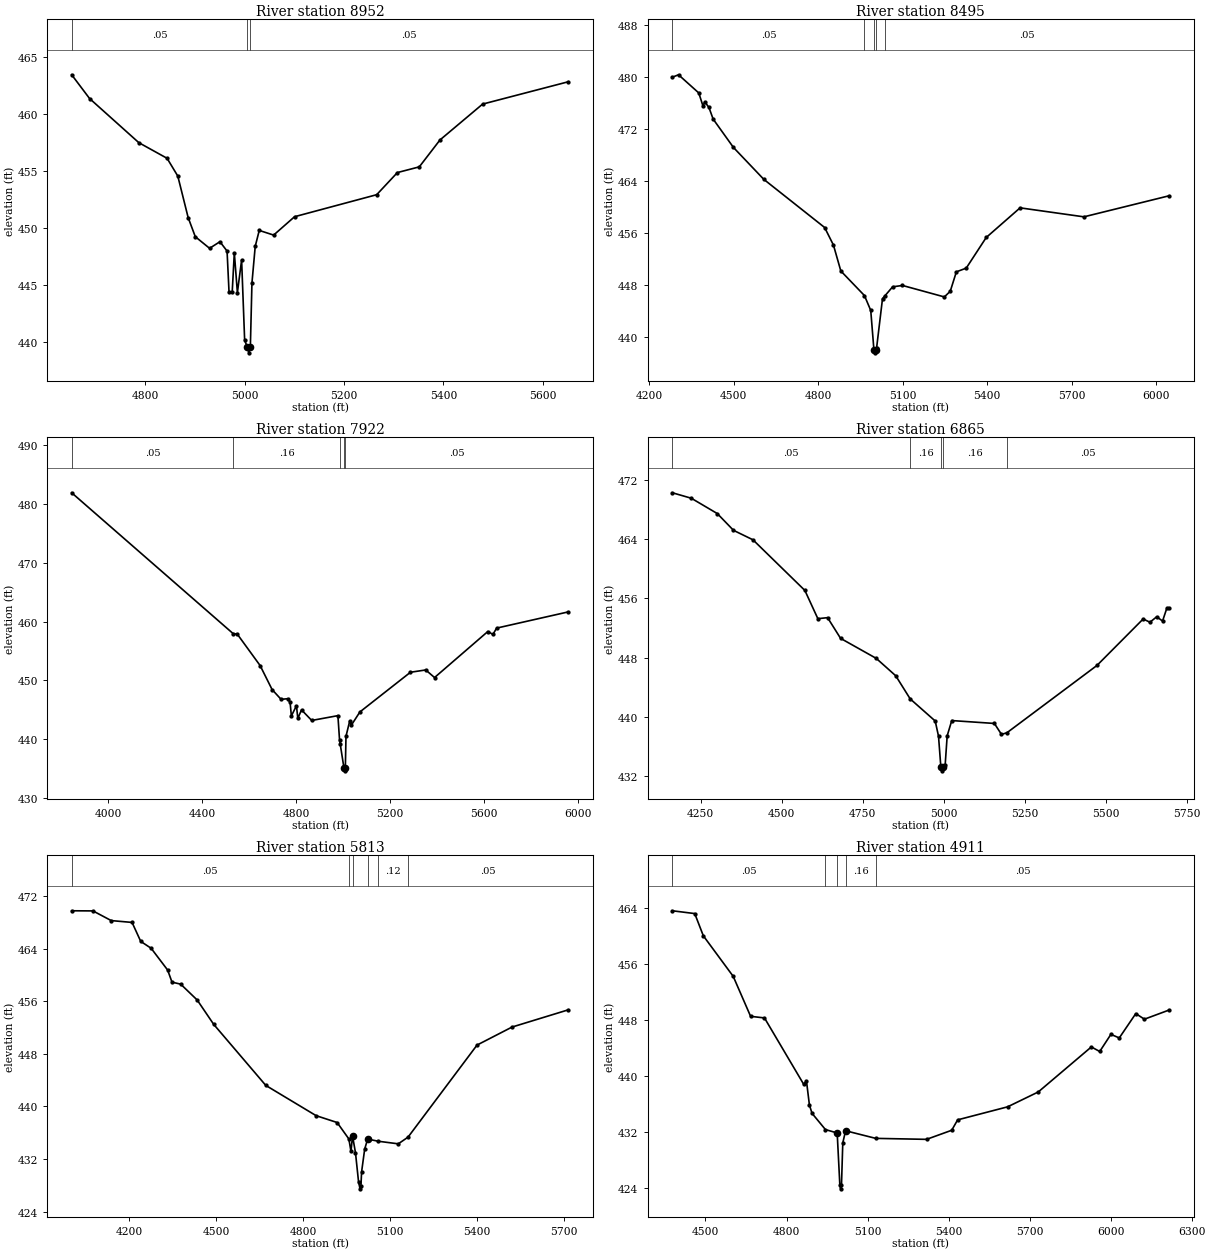
Type RM Length L Ch R = 1 ,8952    ,457,457,457
BEGIN DESCRIPTION:
UNT0078 IN CHRS 12.0
END DESCRIPTION:
XS GIS Cut Line= 3
      3501042.09     10569841.66      3500792.11     10570041.64
      3500392.11     10570591.64
#Sta/Elev= 30
  4651.5  463.42  4687.5  461.34  4786.7  457.47  4843.6   456.1  4865.2  454.54
    4886  450.91  4900.4  449.23  4929.2  448.21    4950  448.79  4964.4  447.97
  4968.4  444.34  4974.7  444.34    4979  447.82  4985.2  444.33  4993.7  447.19
  4999.8  440.15  5005.3  439.55  5008.1  439.05  5011.3  439.55  5014.5  445.17
  5021.1  448.38  5029.2  449.78  5058.2  449.37  5100.3  450.98  5265.7  452.91
  5307.4  454.85  5351.5  455.35  5393.2  457.71    5479  460.85  5651.7  462.81
#Mann= 3 ,-1 , 0
  4651.5     .05       0  5005.3    .035       0  5011.3     .05       0
Bank Sta=5005.3,5011.3
XS Rating Curve= 0 ,0
Exp/Cntr=0.3,0.1

Type RM Length L Ch R = 1 ,8495    ,573,573,573
BEGIN DESCRIPTION:
UNT0078 IN CHRS 11.0
END DESCRIPTION:
XS GIS Cut Line= 4
        3500898.     10569156.78      3500581.17     10569629.86
      3500147.14     10570115.97      3499786.97     10570523.87
#Sta/Elev= 30
  4281.6  479.93  4303.3   480.3  4375.4  477.51  4390.4  475.49  4396.4  476.16
  4411.4  475.29  4426.4   473.5  4498.5  469.15  4606.5  464.25  4822.7  456.86
    4854  454.16  4880.2  450.19  4964.1  446.42  4986.5  444.14  4997.7  438.13
  5000.4  437.63  5003.7  438.13  5007.4  438.41  5028.3  445.94  5036.5  446.36
  5064.2  447.76  5099.3  447.97  5248.1  446.21  5269.1  447.08  5290.8  450.06
  5325.9  450.63  5396.9  455.33  5517.3  459.88  5744.1   458.5  6046.8  461.73
#Mann= 5 ,-1 , 0
  4281.6     .05       0  4964.1     .16       0  4997.7     .07       0
  5003.7     .16       0  5036.5     .05       0
Bank Sta=4997.7,5003.7
XS Rating Curve= 0 ,0
Exp/Cntr=0.3,0.1

Type RM Length L Ch R = 1 ,7922    ,1057,1057,1057
BEGIN DESCRIPTION:
UNT0078 IN CHRS 9.0
END DESCRIPTION:
XS GIS Cut Line= 3
      3500559.47     10568583.85       3500121.1     10569404.16
      3499539.63     10570436.92
#Sta/Elev= 30
  3844.4  481.93  4531.8  457.98  4550.1  457.86  4646.9  452.54    4698  448.45
  4736.2  446.79  4763.9   446.9  4774.5   446.3    4780  443.97  4801.7   445.7
  4807.4  443.55  4823.3     445  4866.7   443.2  4978.2  444.02  4985.2  439.87
  4988.2  439.15  5003.9  435.13  5006.6  434.63  5009.9  435.13  5012.6   440.5
  5028.5  443.12  5035.6  442.41  5071.9  444.65  5287.2   451.4  5352.2  451.79
  5389.8   450.5  5616.7  458.33  5638.4  457.84  5654.3  458.91  5959.7  461.67
#Mann= 5 ,-1 , 0
  3844.4     .05       0  4531.8     .16       0  4988.2     .05       0
  5003.9    .035       0  5009.9     .05       0
Bank Sta=5003.9,5009.9
XS Rating Curve= 0 ,0
Exp/Cntr=0.3,0.1

Type RM Length L Ch R = 1 ,6865    ,1052,1052,1052
BEGIN DESCRIPTION:
UNT0078 IN CHRS 7.0
END DESCRIPTION:
XS GIS Cut Line= 4
      3499339.85     10568323.39      3499331.17      10569052.6
      3499253.04     10569430.21      3499131.94     10569828.12
#Sta/Elev= 30
  4163.4  470.29  4221.7  469.55  4301.7  467.48  4351.7  465.21  4411.7  463.93
  4571.7  457.08  4611.7  453.26  4641.7   453.4  4681.7   450.6  4791.7  447.89
  4851.7  445.54  4896.3  442.41  4973.4  439.42  4983.6  437.36  4990.8  433.18
  4993.5  432.68  4996.8  433.18    5004  433.44  5010.3  437.42  5024.4  439.48
  5155.8  439.09  5177.6  437.61  5194.4  437.83  5471.8  446.93  5614.3  453.22
  5635.2  452.78  5656.1  453.52  5674.1  452.94  5687.4   454.7  5694.2  454.71
#Mann= 5 ,-1 , 0
  4163.4     .05       0  4896.3     .16       0  4990.8     .07       0
  4996.8     .16       0  5194.4     .05       0
Bank Sta=4990.8,4996.8
XS Rating Curve= 0 ,0
Exp/Cntr=0.3,0.1

Type RM Length L Ch R = 1 ,5813    ,902,902,902
BEGIN DESCRIPTION:
UNT0078 IN CHRS 5.0
END DESCRIPTION:
XS GIS Cut Line= 4
      3499170.55     10568219.31      3498714.85     10568896.35
      3498545.58     10569395.48      3498497.83     10569764.43
#Sta/Elev= 30
  4001.5  469.74    4075  469.72    4138  468.25    4210  467.97  4239.9  465.09
  4275.9  464.04  4332.9  460.73  4347.9  458.89  4377.9  458.59  4434.9  456.18
  4491.9  452.48  4671.8   443.2  4845.7   438.6  4918.2  437.56  4958.7  435.06
    4966  433.16  4971.3  435.53  4981.6  432.95  4992.1  428.56  4997.2  427.48
  5000.4  427.98  5002.7  430.07  5013.3  433.52  5023.5  435.04  5060.9  434.71
  5129.4  434.32  5163.1  435.34  5401.3  449.33  5522.3  452.07  5716.7  454.69
#Mann= 6 ,-1 , 0
  4001.5     .05       0  4958.7     .16       0  4971.3     .07       0
  5023.5     .16       0  5060.9     .12       0  5163.1     .05       0
Bank Sta=4971.3,5023.5
XS Rating Curve= 0 ,0
Exp/Cntr=0.3,0.1

Type RM Length L Ch R = 1 ,4911    ,1456,1456,1456
BEGIN DESCRIPTION:
UNT0078 IN CHRS 4.0
END DESCRIPTION:
XS GIS Cut Line= 2
      3498285.16      10568071.7      3497816.75     10569849.94
#Sta/Elev= 30
  4377.5   463.6  4460.2   463.2    4492  460.02  4602.6  454.22    4667   448.5
  4718.4  448.27  4863.5  438.78  4873.8  439.27  4884.8  435.81  4894.5  434.62
  4944.1   432.3  4987.6  431.81  4997.5  424.32  5000.3  423.82  5003.5  424.32
  5008.3  430.38  5018.6  432.13  5130.4  431.04  5318.5   430.9  5411.6   432.2
  5433.6  433.69  5618.4  435.55  5732.1  437.68  5928.6  444.12  5959.6  443.47
    6001  445.92    6032  445.41  6093.1  448.89  6125.1  448.09  6216.4   449.4
#Mann= 5 ,-1 , 0
  4377.5     .05       0  4944.1     .16       0  4987.6     .07       0
  5018.6     .16       0  5130.4     .05       0
Bank Sta=4987.6,5018.6
XS Rating Curve= 0 ,0
Exp/Cntr=0.3,0.1

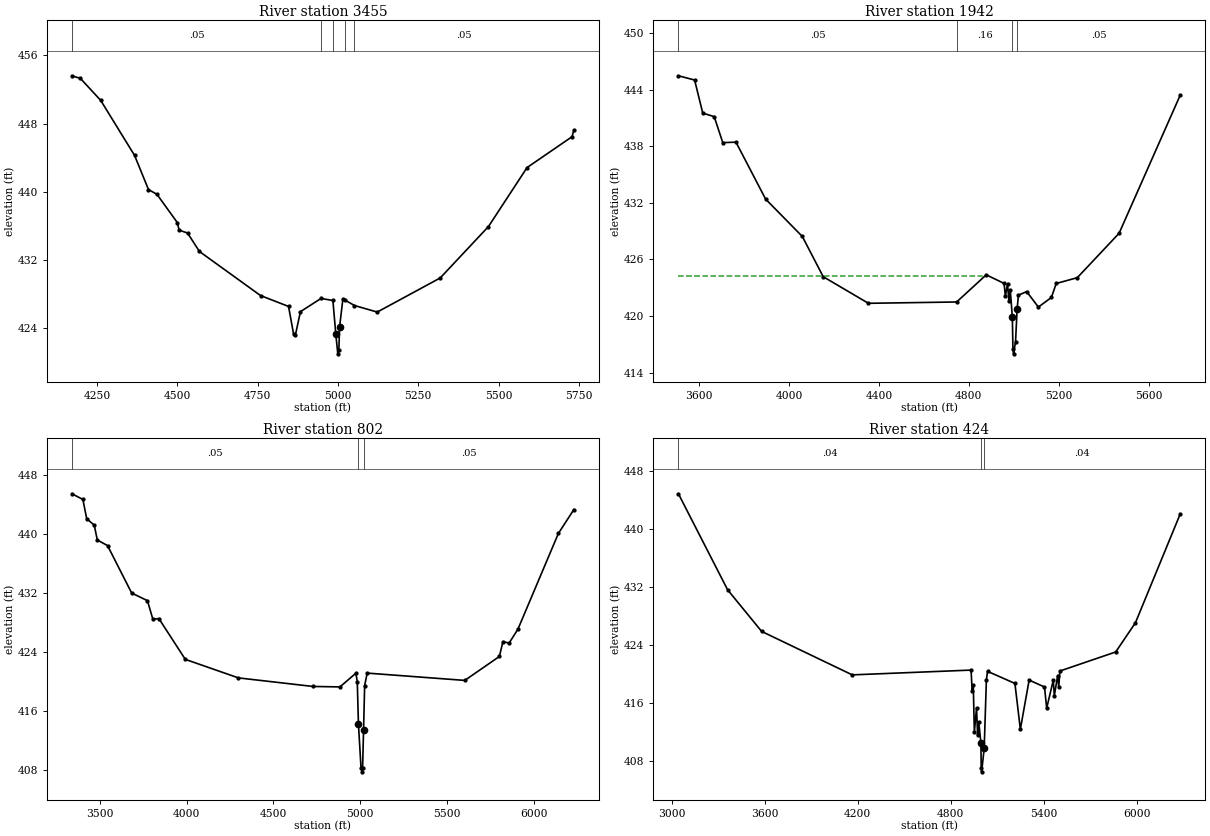
Type RM Length L Ch R = 1 ,3455    ,1513,1513,1513
BEGIN DESCRIPTION:
UNT0078 IN CHRS 3.0
END DESCRIPTION:
XS GIS Cut Line= 4
       3497590.7     10568006.64      3497382.38     10568635.94
      3497174.05     10568983.16      3497191.38     10569477.25
#Sta/Elev= 30
  4172.3  453.61  4198.6   453.3  4261.8  450.72  4367.2  444.25  4410.5  440.24
    4437  439.67  4500.4  436.35  4505.7  435.47  4532.1  435.13  4569.1  432.96
  4759.3  427.78  4846.5   426.5  4862.1  423.26  4867.9  423.16  4883.5  425.89
  4947.6  427.44  4984.5   427.2  4993.4  423.31  4999.8  420.93  5003.1  421.43
 5005.34   424.1  5015.6  427.38  5021.5  427.26  5051.7  426.61  5122.5  425.84
  5318.6  429.85  5468.7  435.89  5588.8  442.82  5728.9  446.45  5734.5  447.22
#Mann= 5 ,-1 , 0
  4172.3     .05       0  4947.6     .16       0  4984.5     .07       0
  5021.5     .16       0  5051.7     .05       0
Bank Sta=4993.4,5005.34
XS Rating Curve= 0 ,0
Exp/Cntr=0.3,0.1

Type RM Length L Ch R = 1 ,1942    ,1140,1140,1140
BEGIN DESCRIPTION:
UNT0078 IN CHRS 2.0
END DESCRIPTION:
XS GIS Cut Line= 5
      3497347.06     10567660.34      3496602.31     10568066.57
       3496597.1     10568535.32      3496836.69     10568925.95
      3497039.62     10569337.02
#Sta/Elev= 30
  3507.3  445.47  3579.4  445.02  3615.5  441.52  3666.7  441.13  3704.7  438.38
  3763.5  438.43  3895.4  432.39  4058.7  428.43  4151.7  424.16  4352.9  421.34
  4745.6  421.48  4877.3  424.36  4956.7  423.45  4962.5  422.08  4972.1  423.43
    4978  421.56  4984.3  422.75  4993.4   419.9  4996.2  416.48    4999  415.98
  5007.8  417.28  5014.7  420.71  5020.5   422.2  5057.3  422.58  5109.4  420.94
  5167.4  421.96  5188.7  423.44  5282.7  424.06  5468.7  428.77  5741.1  443.44
#Mann= 4 ,-1 , 0
  3507.3     .05       0  4745.6     .16       0  4993.4     .07       0
  5014.7     .05       0
#XS Ineff= 2 , 0
       0 4857.95   424.2               0
Permanent Ineff=
       T       F
Bank Sta=4993.4,5014.7
XS Rating Curve= 0 ,0
Exp/Cntr=0.3,0.1

Type RM Length L Ch R = 1 ,802     ,378,378,378
BEGIN DESCRIPTION:
UNT0078 IN CHRS 1.0
END DESCRIPTION:
XS GIS Cut Line= 6
      3497289.77     10567587.42      3496071.06     10568149.91
      3496086.69     10568316.57      3496263.77     10568561.36
      3496758.56     10569160.32      3496981.63     10569357.45
#Sta/Elev= 30
  3339.9  445.44  3402.9  444.67  3424.7  442.07  3468.4  441.18    3486  439.17
  3544.8  438.42  3683.8  431.99  3774.2  430.96  3806.1  428.43  3840.4  428.53
  3992.6     423  4298.4  420.49  4727.5  419.33  4882.8  419.27  4974.8  421.12
  4982.7  419.96  4989.5  414.21  5004.2  408.32  5010.1  407.76  5013.4  408.26
  5018.9  413.44  5025.1  419.44  5039.8  421.14  5601.5  420.15  5800.8  423.39
  5821.6  425.41  5856.8   425.2  5907.7  427.09  6140.7  440.07  6229.7   443.3
#Mann= 3 ,-1 , 0
  3339.9     .05       0  4989.5     .03       0  5018.9     .05       0
Bank Sta=4989.5,5018.9
XS Rating Curve= 0 ,0
Exp/Cntr=0.3,0.1

Type RM Length L Ch R = 1 ,424     ,0,0,0
BEGIN DESCRIPTION:
UNT0078 IN CHRS 1.9
END DESCRIPTION:
XS GIS Cut Line= 4
      3497239.15     10567436.37      3495815.52     10568256.69
      3495906.67     10568478.05      3496896.14     10569406.77
#Sta/Elev= 30
  3042.7  444.82  3360.2  431.58    3580  425.84  4164.7  419.85  4931.7  420.51
  4938.6   417.6  4945.9  418.46  4952.8  411.93  4966.9  415.31  4973.8  411.52
  4981.1  413.38  4995.2  410.46    4997  406.98  4999.8  406.48  5016.3  409.72
  5030.4   419.1  5037.7  420.34  5214.6  418.67  5249.7  412.35  5306.4  419.13
  5405.5  418.18  5419.7  415.26  5462.2  419.11    5469  416.98  5490.5  419.76
  5497.4  418.11  5504.7  420.38  5865.2  423.01  5992.6  427.04  6282.2  442.07
#Mann= 3 , 0 , 0
  3042.7     .04       0  4995.2    .035       0  5016.3     .04       0
Bank Sta=4995.2,5016.3
XS Rating Curve= 0 ,0
Exp/Cntr=0.3,0.1

Chan Stop Cuts=-1
Use User Specified Reach Order=0
Composite Channel Slope=5