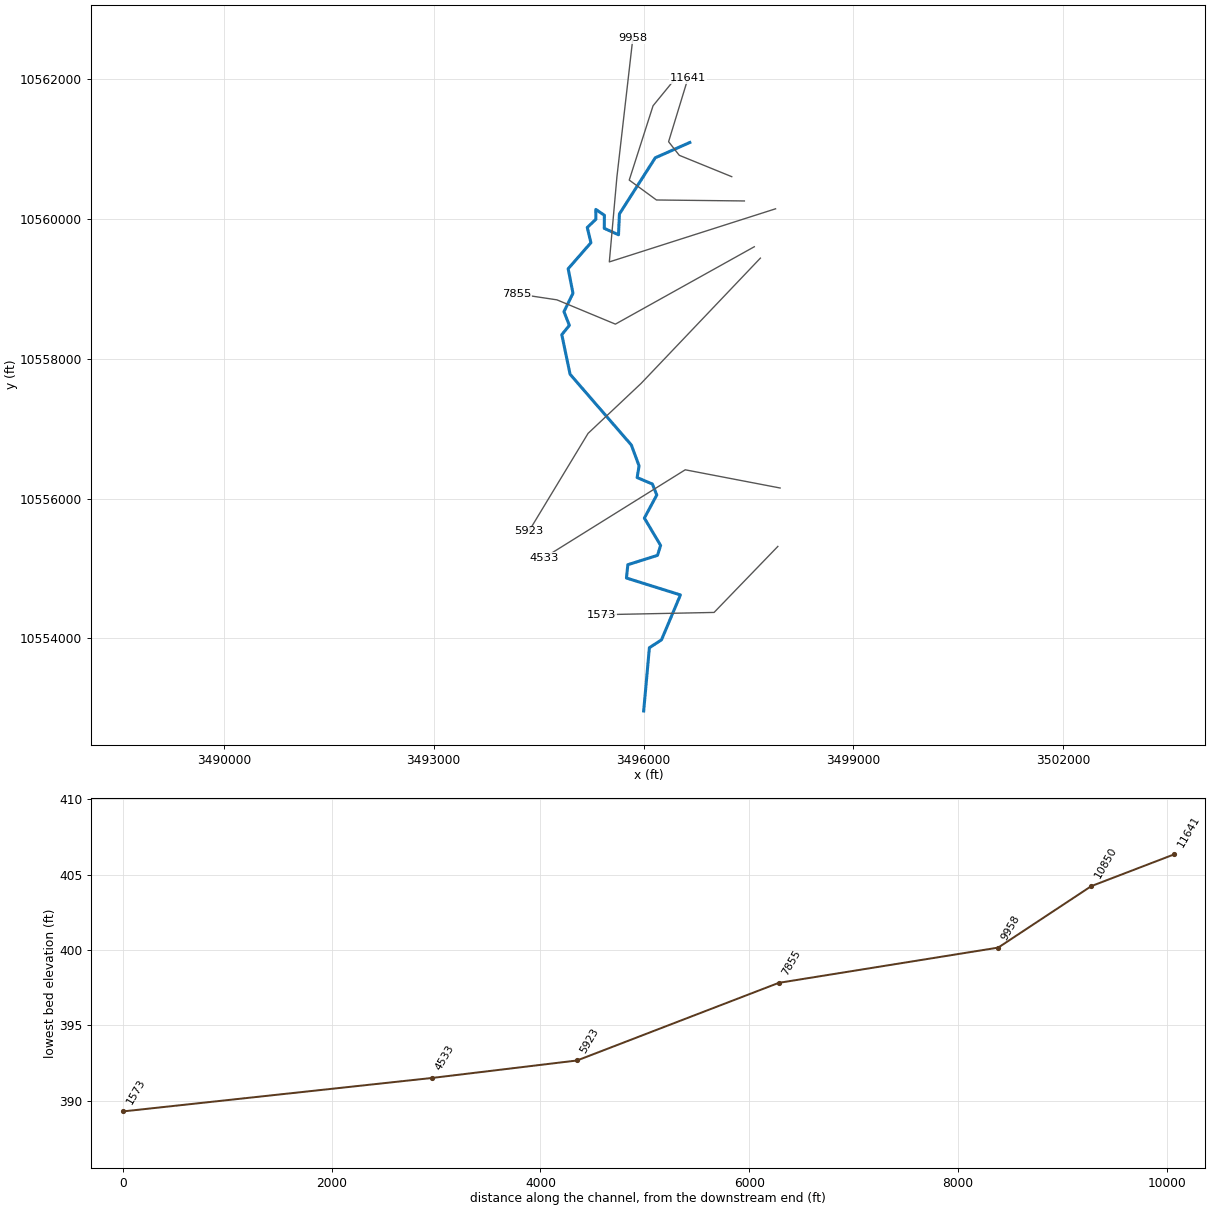
--- UNT0080 IN CHRS.prj (project) ---

Proj Title=UNT0080 IN CHRS Base Level Engineering
Current Plan=p01
Default Exp/Contr=0.3,0.1
English Units
Geom File=g01
Flow File=f01
Plan File=p01
Y Axis Title=Elevation
X Axis Title(PF)=Main Channel Distance
X Axis Title(XS)=Station
BEGIN DESCRIPTION:
UNT0080 IN CHRS
END DESCRIPTION:
DSS Export Rating Curves= 0
DSS Export Rating Curve Sorted= 0
DSS Export Volume Flow Curves= 0
DXF OffsetX= 0
DXF OffsetY= 0
DXF ScaleX= 1
DXF ScaleY= 10

--- UNT0080 IN CHRS.p01 (plan) ---

Plan Title=Multiple Run
Short Identifier=Multiple
Geom File=g01
Flow File=f01
Subcritical Flow
K Sum by GR= 0
Std Step Tol= 0.01
Critical Tol= 0.01
Num of Std Step Trials= 20
Max Error Tol= 0.3
Flow Tol Ratio= 0.001
Split Flow NTrial= 30
Split Flow Tol= 0.02
Split Flow Ratio= 0.02
Log Output Level= 0
Friction Slope Method= 1
Unsteady Friction Slope Method= 2
Unsteady Bridges Friction Slope Method= 1
Parabolic Critical Depth
Global Vel Dist=  1 , 1 , 1
Global Log Level= 0
CheckData=True
Encroach Param= -1, 0, 0, 0
BEGIN DESCRIPTION:
Multiple Run
END DESCRIPTION:

--- UNT0080 IN CHRS.f01 (steady flow) ---

Flow Title=Multiple
Program Version=4.10
Number of Profiles= 7
Profile Names=10-year,25-year,50-year,1pct_min,100-year,1pct_plu,500-year
River Rch & RM=UNT0080 IN CHRS,Reach-1         ,11641
     404     506     580     485     656     887     836
River Rch & RM=UNT0080 IN CHRS,Reach-1         ,7855
     627     801     931     787    1065    1440    1388
River Rch & RM=UNT0080 IN CHRS,Reach-1         ,1573
     701     898    1045     884    1196    1617    1562
Boundary for River Rch & Prof#=UNT0080 IN CHRS,Reach-1         , 1
Up Type= 0
Dn Type= 3
Dn Slope=0.005
Boundary for River Rch & Prof#=UNT0080 IN CHRS,Reach-1         , 2
Up Type= 0
Dn Type= 3
Dn Slope=0.005
Boundary for River Rch & Prof#=UNT0080 IN CHRS,Reach-1         , 3
Up Type= 0
Dn Type= 3
Dn Slope=0.005
Boundary for River Rch & Prof#=UNT0080 IN CHRS,Reach-1         , 4
Up Type= 0
Dn Type= 3
Dn Slope=0.005
Boundary for River Rch & Prof#=UNT0080 IN CHRS,Reach-1         , 5
Up Type= 0
Dn Type= 3
Dn Slope=0.005
Boundary for River Rch & Prof#=UNT0080 IN CHRS,Reach-1         , 6
Up Type= 0
Dn Type= 3
Dn Slope=0.005
Boundary for River Rch & Prof#=UNT0080 IN CHRS,Reach-1         , 7
Up Type= 0
Dn Type= 3
Dn Slope=0.005
DSS Import GetInterval= 0
DSS Import GetPeak= 0
DSS Import FillOption= 0

--- UNT0080 IN CHRS.g01 (geometry) ---

Geom Title=Existing Conditions
Program Version=4.10

River Reach=UNT0080 IN CHRS ,Reach-1
Reach XY= 30
       3496662.1     10561091.85      3496167.97     10560873.23
       3495655.6     10560070.13      3495642.38     10559771.95
      3495438.98     10559864.09      3495440.71     10560050.99
      3495317.62     10560134.73      3495318.52     10559993.23
      3495195.89     10559876.57      3495247.97     10559658.69
       3494922.8     10559286.14      3494991.47     10558935.91
      3494862.89      10558672.2       3494939.9      10558476.8
       3494831.8     10558342.78      3494950.14     10557777.33
      3495825.97     10556765.02      3495936.39     10556466.41
      3495908.61     10556299.74      3496126.66     10556207.38
      3496189.55     10556050.16      3496011.94     10555720.44
      3496244.16      10555329.2      3496200.01     10555187.37
      3495775.81     10555053.65      3495755.94      10554863.2
      3496527.42     10554620.96      3496256.88     10553978.82
      3496083.86     10553865.85      3496002.11     10552961.64

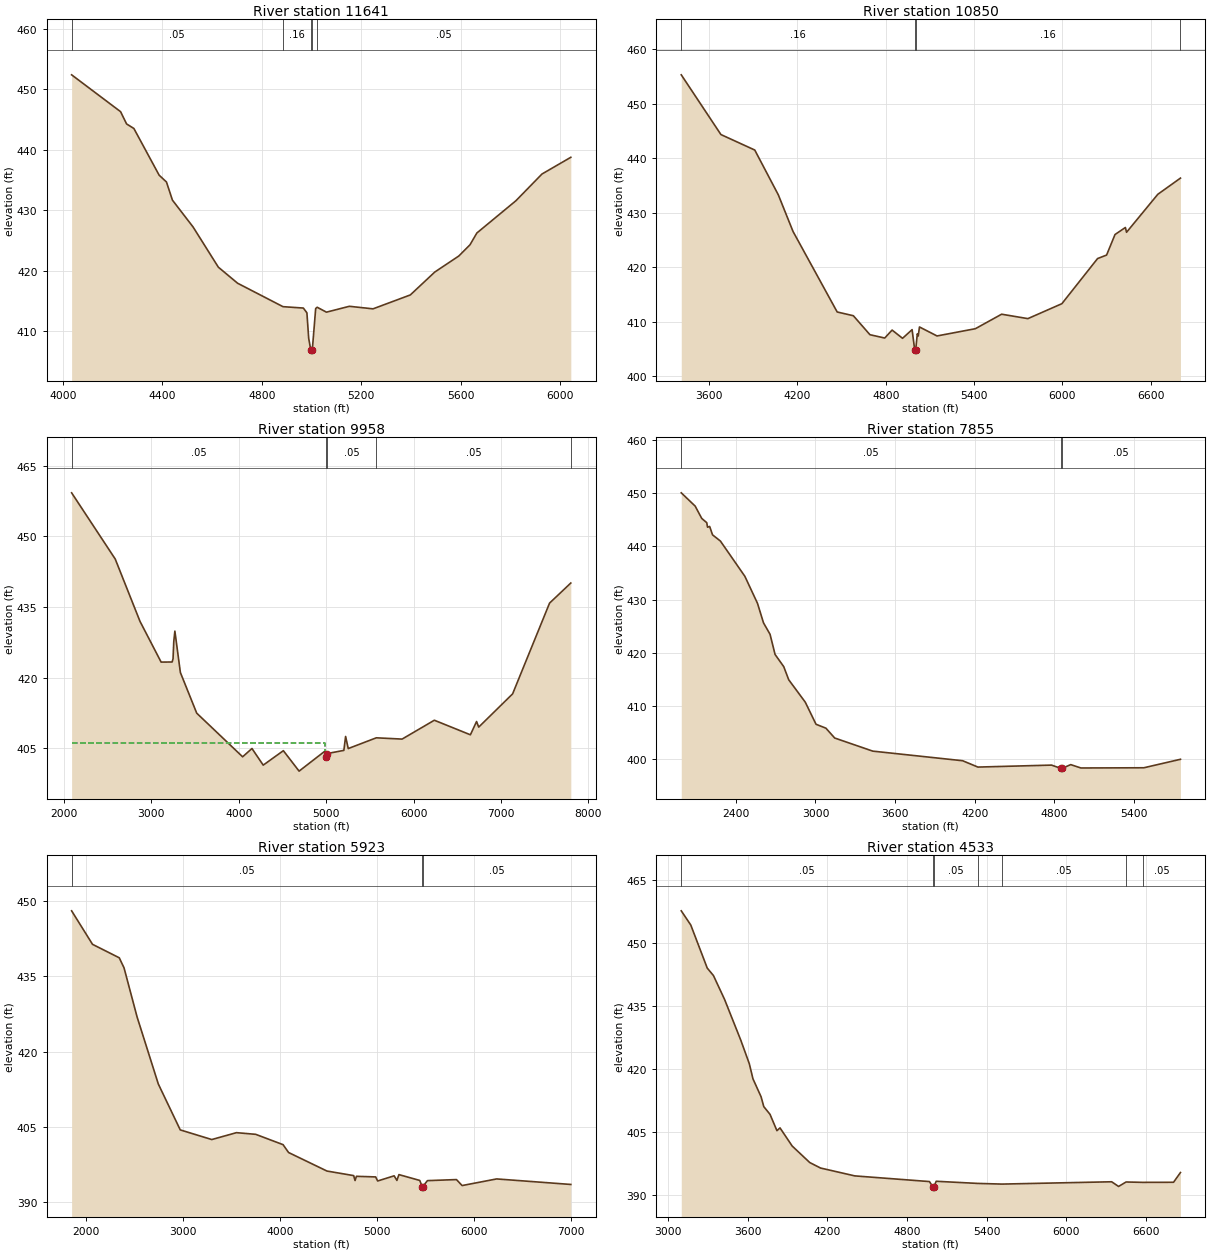
Type RM Length L Ch R = 1 ,11641   ,791,791,791
BEGIN DESCRIPTION:
UNT0080 IN CHRS 10.0
END DESCRIPTION:
XS GIS Cut Line= 4
      3497261.12     10560602.95      3496511.13     10560908.51
      3496358.35     10561102.95      3496636.12     10562012.65
#Sta/Elev= 30
  4034.8  452.39  4231.8  446.29  4255.9  444.26  4285.3  443.51  4386.9  435.78
  4416.4  434.65  4440.4  431.65  4523.4  427.21    4625  420.56  4702.5   417.9
  4885.1  414.02    4967  413.79  4981.4     413  4988.5   408.8    4997  406.83
  4999.8  406.33    5003  406.83  5016.7  413.72  5022.8  413.92    5060  413.11
  5152.1  414.08  5247.4  413.66  5397.4  415.96  5495.9  419.75  5592.4   422.4
  5637.5  424.26  5665.1  426.21  5822.5  431.56    5927  435.97  6043.1  438.74
#Mann= 5 ,-1 , 0
  4034.8     .05       0  4885.1     .16       0    4997     .07       0
    5003     .16       0  5022.8     .05       0
Bank Sta=4997,5003
XS Rating Curve= 0 ,0
Exp/Cntr=0.3,0.1

Type RM Length L Ch R = 1 ,10850   ,892,892,892
BEGIN DESCRIPTION:
UNT0080 IN CHRS 9.9
END DESCRIPTION:
XS GIS Cut Line= 5
      3497441.67     10560255.73      3496184.74     10560269.62
      3495795.85     10560554.34      3496136.13     10561616.84
       3496476.4     10562033.51
#Sta/Elev= 30
  3410.1  455.29  3679.7  444.33  3909.7  441.49  4069.7  433.27  4169.7  426.55
  4469.7  411.78  4579.7  411.09  4692.4  407.61  4792.8     407    4843  408.46
    4914  406.95  4978.9  408.54    4997  404.73  4999.8  404.23    5003  404.73
  5014.4  407.77  5020.6  407.37    5029  409.03  5148.3  407.38  5408.8  408.71
  5587.3  411.37  5765.8  410.56  5996.8   413.3  6239.4  421.58  6300.6  422.22
    6358  425.99  6428.4  427.28  6436.3   426.4  6648.8  433.37  6802.7  436.34
#Mann= 4 ,-1 , 0
  3410.1     .16       0    4997     .07       0    5003     .16       0
  6802.7     .05       0
Bank Sta=4997,5003
XS Rating Curve= 0 ,0
Exp/Cntr=0.3,0.1

Type RM Length L Ch R = 1 ,9958    ,2103,2103,2103
BEGIN DESCRIPTION:
UNT0080 IN CHRS 9.0
END DESCRIPTION:
XS GIS Cut Line= 4
      3497887.43     10560143.44      3495511.13     10559383.89
      3495619.63     10560599.17       3495847.3     10562583.09
#Sta/Elev= 30
  2087.4  459.21  2586.4  445.16  2870.1  431.92  3111.3  423.29  3237.3  423.31
  3247.8  423.98  3256.2  427.64  3268.8  429.86  3331.8  421.08  3518.8  412.45
    4044  403.19    4151  404.95  4279.7  401.42  4510.1  404.49  4690.1  400.15
  4991.6  404.48 4999.02  403.14  5011.6  403.88  5202.4  404.55  5222.4  407.51
  5252.5  404.94  5573.8  407.22    5869  406.95  6237.6  410.95  6650.3  407.86
  6720.7  410.68  6745.4  409.49  7133.4  416.55  7556.2  435.81  7799.2  440.07
#Mann= 5 ,-1 , 0
  2087.4     .05       0 4999.02    .035       0  5011.6     .05       0
  5573.8     .05       0  7799.2     .16       0
#XS Ineff= 2 , 0
       0 4991.48  406.05               0
Permanent Ineff=
       T       F
Bank Sta=4999.02,5011.6
XS Rating Curve= 0 ,0
Exp/Cntr=0.3,0.1

Type RM Length L Ch R = 1 ,7855    ,1932,1932,1932
BEGIN DESCRIPTION:
UNT0080 IN CHRS 7.0
END DESCRIPTION:
XS GIS Cut Line= 4
      3497583.57     10559600.88      3495597.93     10558494.13
      3494762.43     10558841.36      3494187.37     10558928.16
#Sta/Elev= 30
  1989.5  450.02  2094.2  447.53  2143.9  445.21  2181.6  444.42  2187.3  443.57
  2203.3  443.71    2225  442.14  2284.4  440.97  2468.5  434.36  2563.6  429.29
    2609  425.62  2658.2  423.48  2695.9   419.7  2761.1  417.42  2798.8  414.95
  2923.4  410.75  3004.5   406.6  3078.8  405.87  3145.1  404.02    3432  401.56
  4108.6  399.76  4223.6  398.57    4778  398.94  4850.8  398.31  4853.6  397.81
  4856.8  398.31  4922.5  399.03  4999.5   398.4  5473.6  398.44  5749.1  400.03
#Mann= 3 ,-1 , 0
  1989.5     .05       0  4850.8     .03       0  4856.8     .05       0
Bank Sta=4850.8,4856.8
XS Rating Curve= 0 ,0
Exp/Cntr=0.3,0.1

Type RM Length L Ch R = 1 ,5923    ,1390,1390,1390
BEGIN DESCRIPTION:
UNT0080 IN CHRS 5.0
END DESCRIPTION:
XS GIS Cut Line= 4
       3497670.4     10559438.13      3495966.86     10557647.78
      3495207.31     10556931.63      3494360.94     10555531.86
#Sta/Elev= 30
  1847.8  448.06  2063.5  441.39  2339.4  438.71  2388.8   436.7  2523.1  426.95
  2742.3  413.59  2968.8  404.45    3294  402.53  3548.8   403.9    3747  403.57
  4029.7  401.51  4086.3  399.95  4482.4  396.26  4758.3  395.35  4772.5  394.37
  4786.7  395.21  4984.9  395.09  5005.9  394.28  5175.9  395.31  5204.2  394.39
  5225.2  395.55  5439.9  394.39  5465.2  393.16    5468  392.66  5471.2  393.16
  5519.4  394.35  5818.8  394.56  5877.2  393.37  6233.4  394.69  6998.8  393.59
#Mann= 3 ,-1 , 0
  1847.8     .05       0  5465.2     .03       0  5471.2     .05       0
Bank Sta=5465.2,5471.2
XS Rating Curve= 0 ,0
Exp/Cntr=0.3,0.1

Type RM Length L Ch R = 1 ,4533    ,2960,2960,2960
BEGIN DESCRIPTION:
UNT0080 IN CHRS 2.0
END DESCRIPTION:
XS GIS Cut Line= 3
      3497952.49     10556150.39       3496596.2      10556410.8
      3494577.99     10555152.13
#Sta/Elev= 30
  3099.2  457.77  3170.9  454.39  3294.8  444.14  3341.7  442.35  3425.4  436.67
  3547.6  426.96  3611.7  421.36  3639.3  417.76  3700.4  413.49  3720.8  411.14
  3767.7  409.31  3819.6  405.42  3842.9  406.08  3934.6  401.76  4066.9  397.83
  4148.4  396.52  4406.6  394.65  4968.3   393.3    4995     392  4997.8   391.5
    5001     392  5019.3  393.37  5331.6  392.86  5515.8   392.7  6340.7  393.25
  6392.6  392.14  6449.4   393.2    6574  393.11  6806.7  393.13  6858.8  395.45
#Mann= 7 ,-1 , 0
  3099.2     .05       0    4995     .03       0    5001     .05       0
  5331.6     .16       0  5515.8     .05       0  6449.4     .16       0
    6574     .05       0
Bank Sta=4995,5001
XS Rating Curve= 0 ,0
Exp/Cntr=0.3,0.1

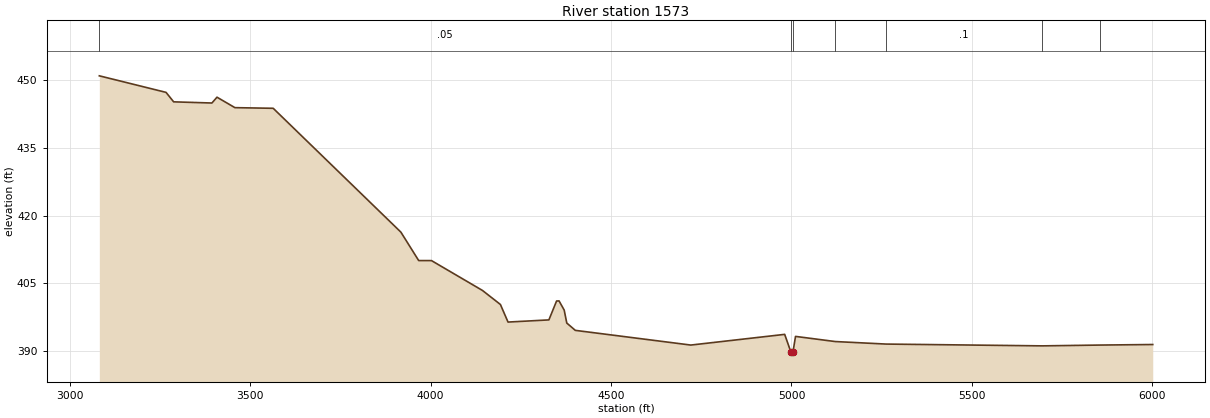
Type RM Length L Ch R = 1 ,1573    ,0,0,0
BEGIN DESCRIPTION:
UNT0080 IN CHRS 1.0
END DESCRIPTION:
XS GIS Cut Line= 3
        3497920.     10555314.89      3497008.52     10554370.87
      3495402.59     10554338.32
#Sta/Elev= 30
  3082.5     451  3267.3  447.33  3288.4  445.23  3394.4  444.97  3408.5  446.26
  3458.2  443.94  3564.2   443.8  3917.9  416.34  3967.3  410.03  4002.8  410.02
    4144   403.4  4193.7  400.29  4214.8  396.39    4328  396.87  4349.3  401.06
  4356.2  401.08  4370.4  399.05  4377.6  396.17  4401.2  394.55  4721.2  391.29
  4981.3  393.66  4998.3  389.78    5001  389.28  5004.3  389.78  5011.3  393.21
  5121.4  392.07  5262.1  391.51  5695.3  391.11  5854.7  391.29    6001  391.41
#Mann= 7 ,-1 , 0
  3082.5     .05       0  4998.3    .035       0  5004.3     .05       0
  5121.4     .07       0  5262.1      .1       0  5695.3     .07       0
  5854.7     .05       0
Bank Sta=4998.3,5004.3
XS Rating Curve= 0 ,0
Exp/Cntr=0.3,0.1

Chan Stop Cuts=-1
Use User Specified Reach Order=0
Composite Channel Slope=5