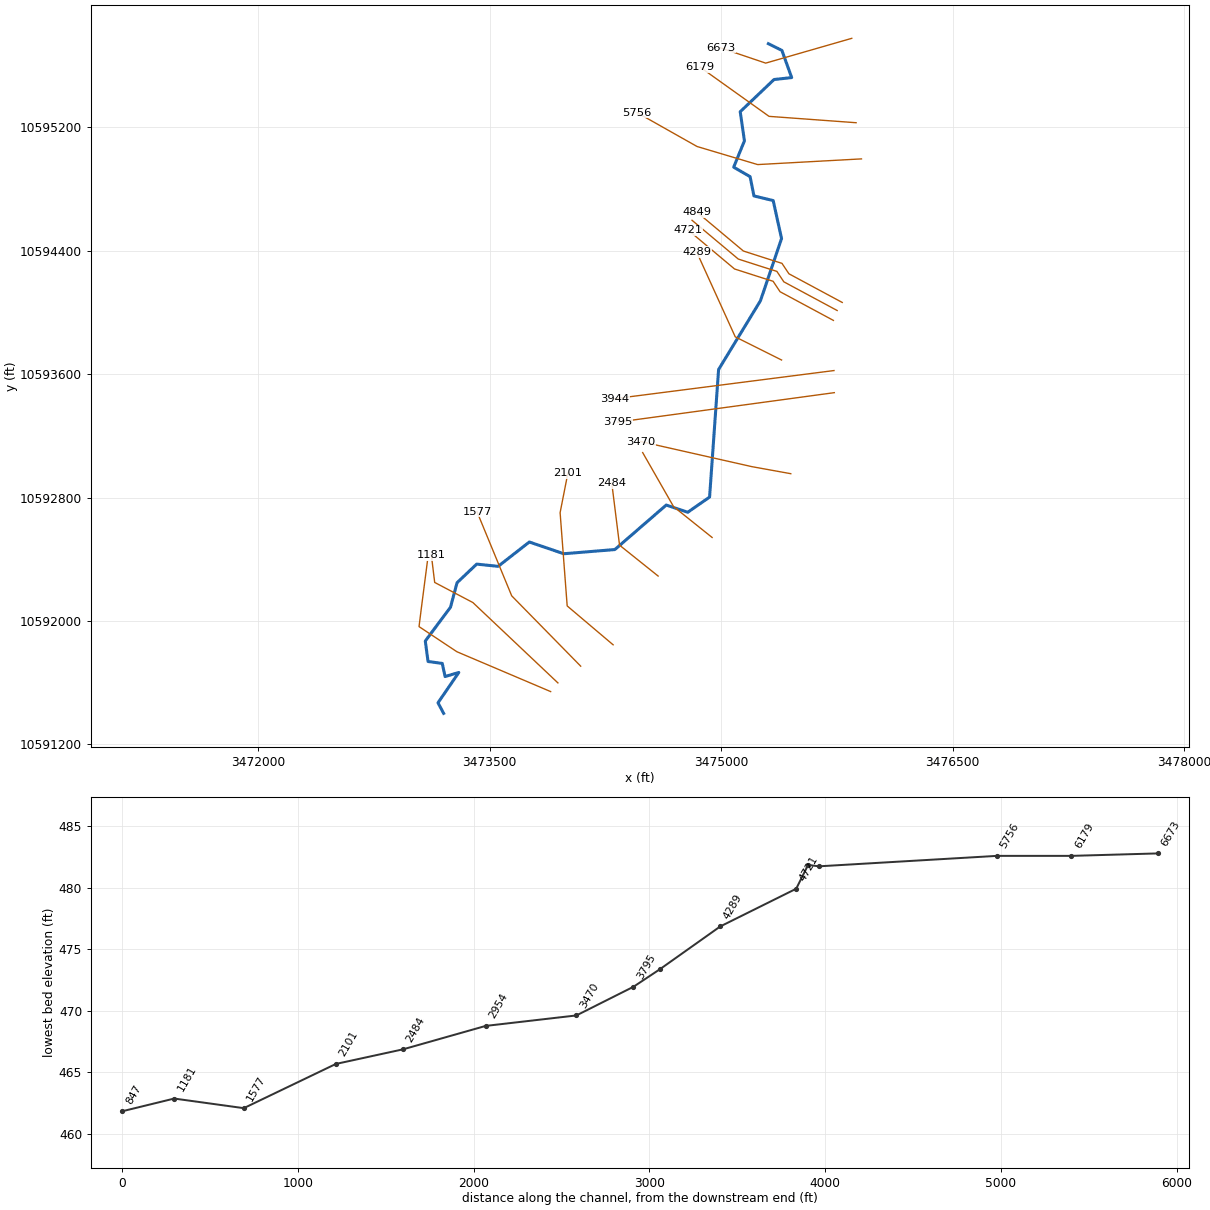
--- UNT00804 IN CHRS.prj (project) ---

Proj Title=UNT00804 IN CHRS Base Level Engineering
Current Plan=p01
Default Exp/Contr=0.3,0.1
English Units
Geom File=g01
Flow File=f01
Plan File=p01
Y Axis Title=Elevation
X Axis Title(PF)=Main Channel Distance
X Axis Title(XS)=Station
BEGIN DESCRIPTION:
UNT00804 IN CHRS
END DESCRIPTION:
DSS Export Rating Curves= 0
DSS Export Rating Curve Sorted= 0
DSS Export Volume Flow Curves= 0
DXF OffsetX= 0
DXF OffsetY= 0
DXF ScaleX= 1
DXF ScaleY= 10

--- UNT00804 IN CHRS.p01 (plan) ---

Plan Title=Multiple Run
Short Identifier=Multiple
Geom File=g01
Flow File=f01
Subcritical Flow
K Sum by GR= 0
Std Step Tol= 0.01
Critical Tol= 0.01
Num of Std Step Trials= 20
Max Error Tol= 0.3
Flow Tol Ratio= 0.001
Split Flow NTrial= 30
Split Flow Tol= 0.02
Split Flow Ratio= 0.02
Log Output Level= 0
Friction Slope Method= 1
Unsteady Friction Slope Method= 2
Unsteady Bridges Friction Slope Method= 1
Parabolic Critical Depth
Global Vel Dist=  1 , 1 , 1
Global Log Level= 0
CheckData=True
Encroach Param= -1, 0, 0, 0
BEGIN DESCRIPTION:
Multiple Run
END DESCRIPTION:

--- UNT00804 IN CHRS.f01 (steady flow) ---

Flow Title=Multiple
Program Version=4.10
Number of Profiles= 7
Profile Names=10-year,25-year,50-year,1pct_min,100-year,1pct_plu,500-year
River Rch & RM=UNT00804 IN CHRS,Reach-1         ,6673
     291     355     399     328     443     599     544
River Rch & RM=UNT00804 IN CHRS,Reach-1         ,3795
     333     410     465     384     519     702     645
Boundary for River Rch & Prof#=UNT00804 IN CHRS,Reach-1         , 1
Up Type= 0
Dn Type= 3
Dn Slope=0.004
Boundary for River Rch & Prof#=UNT00804 IN CHRS,Reach-1         , 2
Up Type= 0
Dn Type= 3
Dn Slope=0.004
Boundary for River Rch & Prof#=UNT00804 IN CHRS,Reach-1         , 3
Up Type= 0
Dn Type= 3
Dn Slope=0.004
Boundary for River Rch & Prof#=UNT00804 IN CHRS,Reach-1         , 4
Up Type= 0
Dn Type= 3
Dn Slope=0.004
Boundary for River Rch & Prof#=UNT00804 IN CHRS,Reach-1         , 5
Up Type= 0
Dn Type= 3
Dn Slope=0.004
Boundary for River Rch & Prof#=UNT00804 IN CHRS,Reach-1         , 6
Up Type= 0
Dn Type= 3
Dn Slope=0.004
Boundary for River Rch & Prof#=UNT00804 IN CHRS,Reach-1         , 7
Up Type= 0
Dn Type= 3
Dn Slope=0.004
DSS Import GetInterval= 0
DSS Import GetPeak= 0
DSS Import FillOption= 0

--- UNT00804 IN CHRS.g01 (geometry) ---

Geom Title=Existing Conditions
Program Version=4.10

River Reach=UNT00804 IN CHRS,Reach-1
Reach XY= 30
      3475306.73     10595741.64      3475394.35     10595698.16
      3475457.64     10595521.96      3475343.38      10595509.5
      3475124.21     10595300.74       3475151.6     10595112.15
      3475081.83     10594941.33       3475188.2     10594879.95
       3475213.2     10594754.95      3475337.86     10594725.05
      3475392.11     10594478.74      3475255.36     10594075.76
        3474984.     10593629.93      3474925.67     10592803.37
        3474784.     10592704.93      3474644.94     10592751.81
      3474311.61     10592463.27      3473980.88     10592436.18
      3473757.44     10592512.22      3473555.36     10592354.41
       3473416.3     10592368.99      3473289.05     10592248.34
      3473246.41     10592089.17      3473083.26     10591870.69
      3473101.08     10591737.85      3473193.26     10591725.37
      3473211.47     10591640.33      3473300.36     10591666.73
      3473165.73     10591470.32      3473202.11     10591401.64

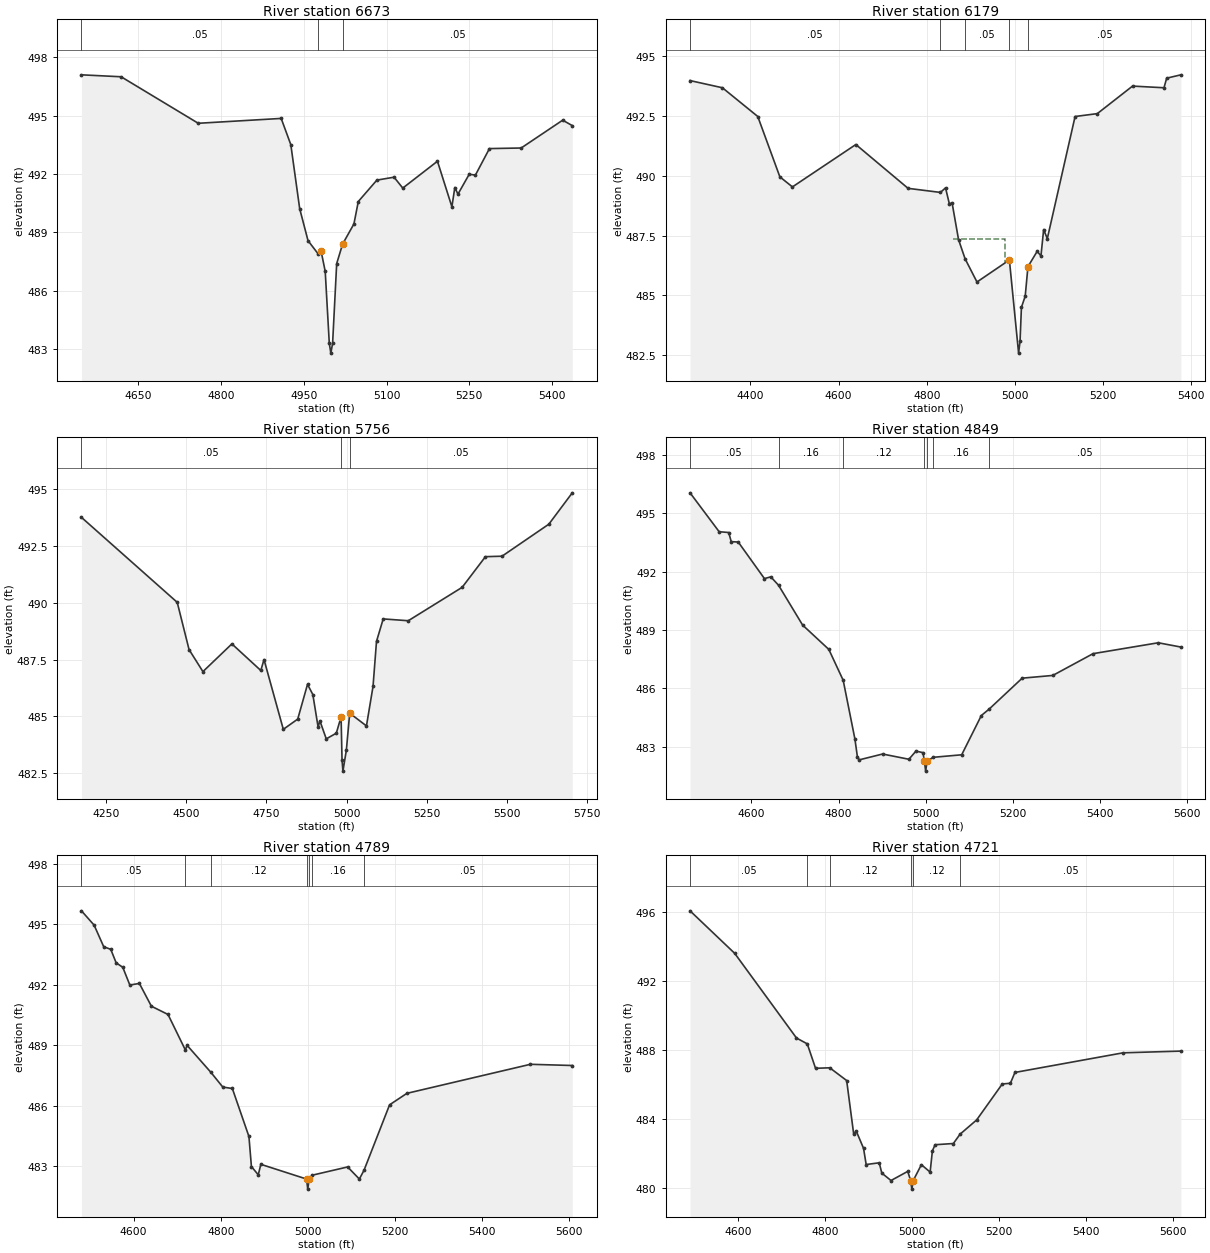
Type RM Length L Ch R = 1 ,6673    ,494,494,494
BEGIN DESCRIPTION:
UNT00804 IN CHRS 10.0
END DESCRIPTION:
XS GIS Cut Line= 3
      3475847.07     10595776.35      3475289.33     10595615.76
      3474995.67     10595715.09
#Sta/Elev= 30
  4546.6  497.09  4618.6  496.99  4758.5   494.6  4908.9  494.85  4926.4   493.5
  4942.5  490.21  4957.6  488.57  4976.2  487.88  4981.4  488.02  4988.8  486.99
  4996.2  483.29    4999  482.79  5002.2  483.29  5009.6  487.39  5020.3  488.39
  5040.9  489.43  5048.8  490.58  5082.5  491.68  5113.7  491.83  5129.5  491.27
  5192.4  492.65  5218.6  490.31  5223.9   491.3  5229.6  490.96    5250  491.98
  5261.3  491.94  5286.7   493.3  5344.3  493.33  5419.6  494.76    5437  494.48
#Mann= 3 ,-1 , 0
  4546.6     .05       0  4976.2    .035       0  5020.3     .05       0
Bank Sta=4981.4,5020.3
XS Rating Curve= 0 ,0
Exp/Cntr=0.3,0.1

Type RM Length L Ch R = 1 ,6179    ,423,423,423
BEGIN DESCRIPTION:
UNT00804 IN CHRS 10.1
END DESCRIPTION:
XS GIS Cut Line= 3
      3475875.31     10595229.47      3475311.03     10595270.71
      3474865.52     10595588.62
#Sta/Elev= 30
  4263.2  493.97  4336.6  493.67  4416.8  492.47  4466.9  489.95  4495.4  489.53
  4639.2   491.3  4757.7  489.47  4831.1   489.3  4842.6  489.49  4851.3  488.82
  4857.4  488.87  4872.1  487.33  4886.9  486.53  4913.9  485.56  4987.4  486.48
  5008.3  482.59  5011.6  483.09  5014.7   484.5  5023.3  484.97  5029.5   486.2
  5050.4  486.84    5059  486.65  5065.1  487.75  5073.4  487.37  5136.4  492.47
  5186.8  492.59  5266.7  493.74    5338  493.67  5344.1  494.07  5376.3  494.21
#Mann= 5 ,-1 , 0
  4263.2     .05       0  4831.1     .16       0  4886.9     .05       0
  4987.4    .035       0  5029.5     .05       0
#XS Ineff= 1 ,-1
 4859.71 4978.17  487.34
Permanent Ineff=
       T
Bank Sta=4987.4,5029.5
XS Rating Curve= 0 ,0
Exp/Cntr=0.3,0.1

Type RM Length L Ch R = 1 ,5756    ,1015,1015,1015
BEGIN DESCRIPTION:
UNT00804 IN CHRS 10.2
END DESCRIPTION:
XS GIS Cut Line= 4
      3475909.96      10594995.1      3475237.25     10594958.21
      3474844.45     10595075.39      3474456.56     10595294.26
#Sta/Elev= 30
  4174.3  493.76  4472.6  490.02  4509.5  487.94  4552.7  486.97  4642.9  488.19
    4733  487.02    4743   487.5  4803.1  484.43    4848  484.88  4878.5  486.41
  4895.1  485.96  4911.6  484.52  4916.9  484.81  4936.9  484.01  4968.2  484.26
  4983.1  484.98    4986  483.09  4988.8  482.59  4999.5  483.51  5009.9  485.14
  5062.1  484.58  5082.6  486.32  5093.4   488.3  5114.3  489.29  5192.4  489.21
  5360.2  490.68  5432.8  492.03  5484.4  492.05  5630.3  493.46  5703.3  494.84
#Mann= 3 ,-1 , 0
  4174.3     .05       0  4983.1    .035       0  5009.9     .05       0
#XS Ineff= 1 ,-1
 4716.53 4881.22  486.21
Permanent Ineff=
       T
Bank Sta=4983.1,5009.9
XS Rating Curve= 0 ,0
Exp/Cntr=0.3,0.1

Type RM Length L Ch R = 1 ,4849    ,60,60,60
BEGIN DESCRIPTION:
UNT00804 IN CHRS 9.9
END DESCRIPTION:
XS GIS Cut Line= 6
      3475785.32     10594064.69      3475439.84     10594250.45
       3475394.7     10594318.16      3475295.74     10594349.41
       3475144.7     10594398.02      3474845.71     10594648.62
#Sta/Elev= 30
  4459.2  496.05    4526  494.05  4547.9  494.01  4553.7  493.54  4569.8  493.52
  4629.9  491.64  4644.5  491.73  4662.2   491.3  4717.5  489.25  4777.6     488
  4810.6  486.41  4837.5  483.39  4843.3  482.46  4847.4  482.32    4901  482.62
  4961.4  482.35  4977.5  482.77  4993.7  482.69    4997  482.24  4999.8  481.74
    5003  482.24  5016.8  482.45  5082.5  482.58  5127.6   484.6  5145.5  484.93
  5221.3  486.52  5291.5  486.66  5383.9  487.78  5533.5  488.34  5585.4  488.12
#Mann= 7 ,-1 , 0
  4459.2     .05       0  4662.2     .16       0  4810.6     .12       0
    4997     .07       0    5003     .12       0  5016.8     .16       0
  5145.5     .05       0
Bank Sta=4997,5003
XS Rating Curve= 0 ,0
Exp/Cntr=0.3,0.1

Type RM Length L Ch R = 1 ,4789    ,68,68,68
BEGIN DESCRIPTION:
UNT00804 IN CHRS 9.0
END DESCRIPTION:
XS GIS Cut Line= 6
      3475752.33      10594012.6      3475406.86     10594198.36
      3475361.72     10594266.07      3475262.76     10594297.32
      3475111.72     10594345.93      3474811.96     10594597.18
#Sta/Elev= 30
  4480.1  495.66  4509.2  494.95  4531.2  493.88  4547.4  493.75  4559.8  493.08
    4575  492.86  4591.2  491.98  4613.1  492.06  4640.7  490.93  4678.9  490.52
  4718.7  488.76  4722.7  488.99  4777.4  487.65  4804.7  486.92  4826.6  486.85
  4864.7  484.47  4870.4  482.98  4886.1  482.57  4892.1  483.09    4997  482.36
  4999.8  481.86    5003  482.36  5009.9  482.55  5091.4  482.96  5118.3  482.36
  5129.1   482.8  5187.7  486.04  5227.5  486.61  5511.2  488.05  5607.3  487.99
#Mann= 7 ,-1 , 0
  4480.1     .05       0  4718.7     .16       0  4777.4     .12       0
    4997     .07       0    5003     .12       0  5009.9     .16       0
  5129.1     .05       0
Bank Sta=4997,5003
XS Rating Curve= 0 ,0
Exp/Cntr=0.3,0.1

Type RM Length L Ch R = 1 ,4721    ,432,432,432
BEGIN DESCRIPTION:
UNT00804 IN CHRS 9.5
END DESCRIPTION:
XS GIS Cut Line= 6
      3475728.03     10593948.37      3475382.55     10594134.13
      3475337.41     10594201.84      3475238.45     10594233.09
      3475087.41      10594281.7      3474787.12     10594533.39
#Sta/Elev= 30
  4490.1  496.09  4592.7  493.62  4734.7   488.7  4759.5  488.36  4778.5  486.94
  4811.1  486.97    4850  486.23  4866.2  483.11  4871.9   483.3  4888.8  482.29
  4894.8  481.35  4924.8  481.45  4930.8  480.85  4951.9  480.42  4990.3  480.95
    4997  480.42  4999.8  479.92    5003  480.42  5021.7  481.34  5041.8  480.91
    5047  482.14  5053.2   482.5  5095.2  482.57  5110.5  483.11  5148.7  483.94
  5207.6  486.03  5226.2  486.07  5236.7   486.7  5485.2  487.84    5618  487.94
#Mann= 6 ,-1 , 0
  4490.1     .05       0  4759.5     .16       0  4811.1     .12       0
    4997     .07       0    5003     .12       0  5110.5     .05       0
Bank Sta=4997,5003
XS Rating Curve= 0 ,0
Exp/Cntr=0.3,0.1

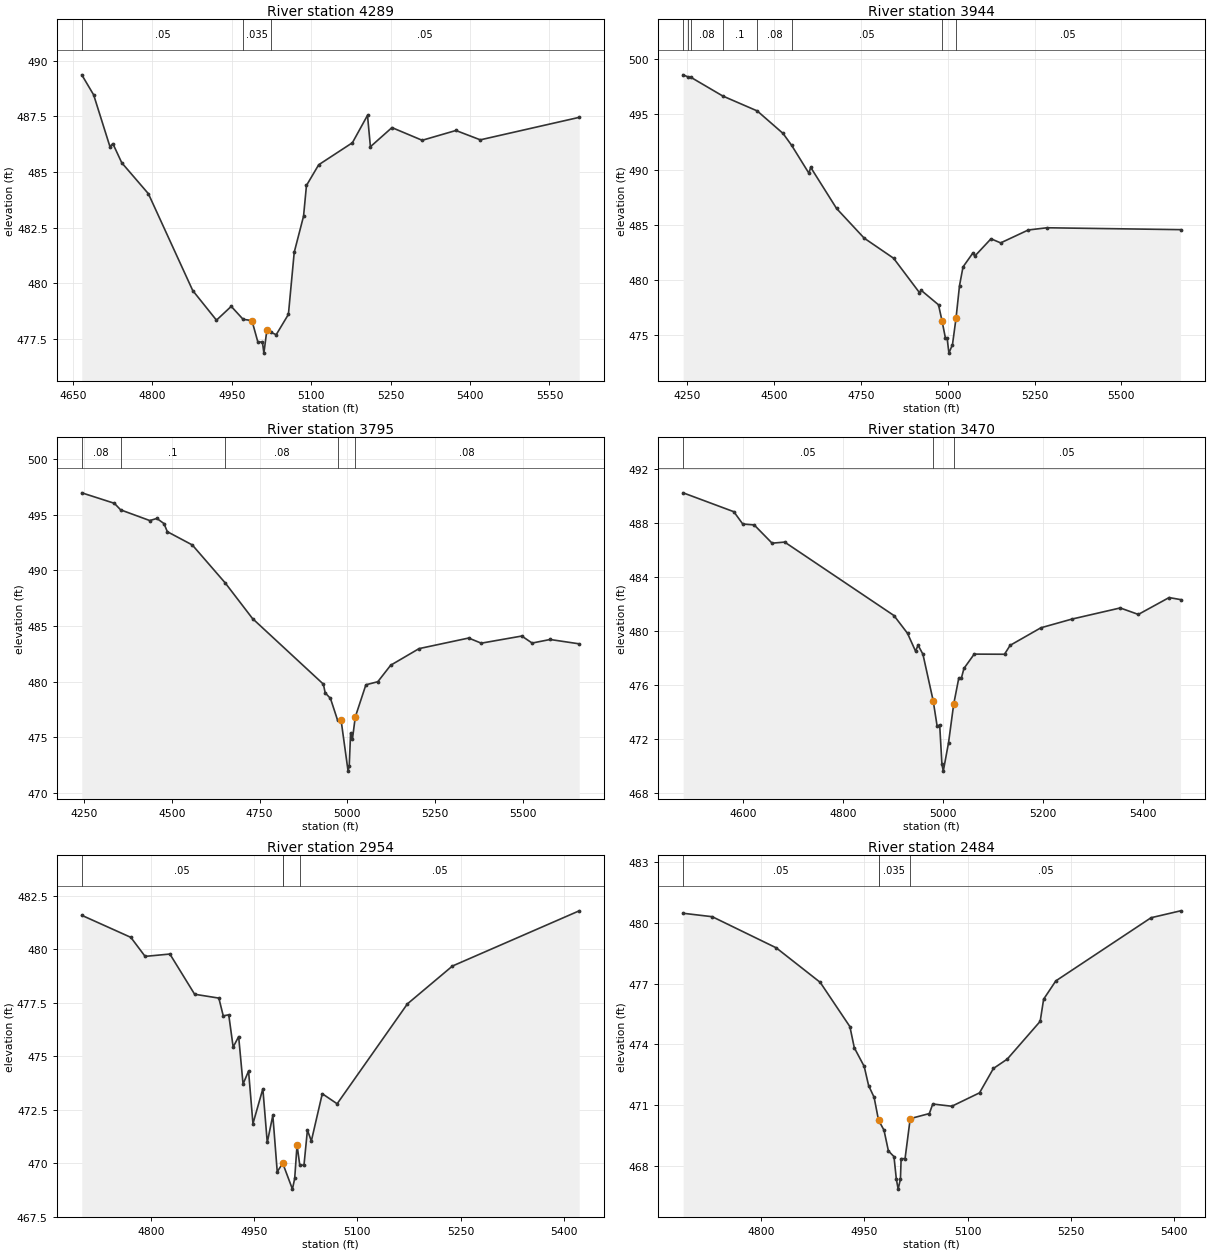
Type RM Length L Ch R = 1 ,4289    ,345,345,345
BEGIN DESCRIPTION:
UNT00804 IN CHRS 8.0
END DESCRIPTION:
XS GIS Cut Line= 3
      3475392.12     10593691.64      3475092.11     10593841.64
       3474842.1     10594391.66
#Sta/Elev= 30
  4666.6  489.36    4689  488.46  4719.7  486.14  4725.3  486.27  4742.1  485.41
  4792.4  484.02  4876.2  479.67    4921  478.34  4948.9  478.96  4971.3  478.38
    4988  478.32  4999.2  477.36  5007.8  477.36  5010.6  476.86  5016.3  477.91
    5024  477.79  5033.9  477.69  5056.9   478.6  5067.9  481.39  5085.5  483.01
    5091  484.39  5114.1  485.32  5177.8  486.31  5206.3  487.54  5211.8  486.13
  5252.5  486.99  5309.6  486.42  5373.3  486.86  5419.4  486.44  5606.2  487.45
#Mann= 3 ,-1 , 0
  4666.6     .05       0  4971.3    .035       0    5024     .05       0
Bank Sta=4988,5016.3
XS Rating Curve= 0 ,0
Exp/Cntr=0.3,0.1

Type RM Length L Ch R = 1 ,3944    ,149,149,149
BEGIN DESCRIPTION:
UNT00804 IN CHRS 7.0
END DESCRIPTION:
XS GIS Cut Line= 2
      3475731.84     10593623.34      3474310.48     10593441.05
#Sta/Elev= 30
  4237.6  498.59  4252.5  498.39  4259.7  498.37  4351.8  496.67    4451  495.32
  4525.4  493.28  4550.2   492.2    4600  489.67    4605  490.21  4679.6  486.48
  4759.2  483.79  4843.9  481.97  4918.5  478.85  4923.5  479.06  4973.3  477.75
  4983.4   476.3  4993.1  474.76  4998.1  474.74  5003.3  473.37  5013.6  474.15
  5023.7  476.51  5033.8  479.48  5043.9  481.18  5072.7  482.46  5077.8  482.16
  5124.5  483.73  5152.4  483.36    5232  484.53  5285.8  484.73  5670.6  484.56
#Mann= 8 ,-1 , 0
  4237.6     .05       0  4252.5      .1       0  4259.7     .08       0
  4351.8      .1       0    4451     .08       0  4550.2     .05       0
  4983.4     .04       0  5023.7     .05       0
Bank Sta=4983.4,5023.7
XS Rating Curve= 0 ,0
Exp/Cntr=0.3,0.1

Type RM Length L Ch R = 1 ,3795    ,325,325,325
BEGIN DESCRIPTION:
UNT00804 IN CHRS 7.1
END DESCRIPTION:
XS GIS Cut Line= 2
      3475734.06     10593480.11      3474329.99     10593289.14
#Sta/Elev= 30
  4243.6  496.95  4336.4  496.01  4354.3  495.42  4437.3  494.46  4457.5  494.65
  4477.7  494.19  4487.3  493.46  4558.4  492.27  4652.2  488.86    4730  485.66
  4931.8  479.77    4937  478.99    4952  478.49  4972.2  476.54  4982.3  476.53
  5002.2  471.96  5005.5  472.46  5009.4  475.39  5014.5  474.81  5022.7  476.82
  5052.9  479.71  5086.9  479.99  5123.6  481.47  5204.3  482.96  5345.6  483.91
  5381.6  483.45    5497  484.09  5526.5  483.46  5577.7  483.78  5660.6  483.39
#Mann= 5 ,-1 , 0
  4243.6     .08       0  4354.3      .1       0  4652.2     .08       0
  4972.2    .035       0  5022.7     .08       0
Bank Sta=4982.3,5022.7
XS Rating Curve= 0 ,0
Exp/Cntr=0.3,0.1

Type RM Length L Ch R = 1 ,3470    ,516,516,516
BEGIN DESCRIPTION:
UNT00804 IN CHRS 6.0
END DESCRIPTION:
XS GIS Cut Line= 3
      3475451.89     10592954.94      3475200.19     10593000.51
      3474479.74     10593163.26
#Sta/Elev= 30
  4479.9  490.25  4581.3  488.85  4599.1  487.94    4622  487.87  4657.7  486.52
  4682.9   486.6  4901.3  481.16  4928.5  479.84  4944.5  478.52  4949.6  478.96
  4959.3  478.29  4979.8  474.84  4987.7  472.96  4992.8  473.05  4997.3  470.13
    5000  469.63  5010.5  471.74  5020.8  474.59  5030.9  476.51    5036   476.5
  5041.3  477.24  5061.8   478.3  5122.4  478.29  5133.6  478.95  5195.1  480.25
  5256.6  480.89  5353.7  481.72  5389.9  481.24  5451.4  482.49  5474.3  482.34
#Mann= 3 , 0 , 0
  4479.9     .05       0  4979.8    .035       0  5020.8     .05       0
Bank Sta=4979.8,5020.8
XS Rating Curve= 0 ,0
Exp/Cntr=0.3,0.1

Type RM Length L Ch R = 1 ,2954    ,470,470,470
BEGIN DESCRIPTION:
UNT00804 IN CHRS 5.0
END DESCRIPTION:
XS GIS Cut Line= 3
      3474942.12     10592541.63      3474692.11     10592741.64
       3474492.1     10593091.66
#Sta/Elev= 30
  4699.3  481.58  4770.6  480.55  4791.4  479.66  4827.4  479.77  4863.4  477.89
  4898.6  477.71    4905  476.88    4913  476.93  4919.4  475.42  4927.4  475.91
  4933.8  473.69  4941.8   474.3  4948.2  471.84  4962.6  473.47    4969  470.96
  4977.1  472.23  4983.5  469.59  4991.5  469.99  5005.6  468.78  5008.9  469.28
  5012.3  470.84  5016.3   469.9  5022.4   469.9  5027.4  471.54  5033.1  471.03
    5049  473.24  5070.6  472.77  5172.8  477.44  5238.3  479.21  5422.6  481.79
#Mann= 4 ,-1 , 0
  4699.3     .05       0  4991.5     .16       0  4991.5    .035       0
  5016.3     .05       0
Bank Sta=4991.5,5012.3
XS Rating Curve= 0 ,0
Exp/Cntr=0.3,0.1

Type RM Length L Ch R = 1 ,2484    ,383,383,383
BEGIN DESCRIPTION:
UNT00804 IN CHRS 4.0
END DESCRIPTION:
XS GIS Cut Line= 3
      3474592.11     10592291.64      3474342.11     10592491.64
       3474292.1     10592891.67
#Sta/Elev= 30
  4686.3  480.46  4728.7  480.29  4821.6  478.76  4885.6  477.06  4928.8  474.88
  4935.2  473.84  4949.6  472.92    4956  471.98    4964   471.4  4970.4  470.28
  4978.4  469.78  4984.8  468.76  4992.9  468.48  4996.3  467.38    4999  466.88
  5002.3  467.38  5003.3  468.38    5009  468.38  5016.5  470.35  5044.3   470.6
  5049.3  471.07    5077  470.96  5117.3  471.62  5137.5  472.82  5157.6  473.28
  5205.5  475.14  5210.5  476.23  5228.2  477.13  5366.7  480.24  5409.6  480.58
#Mann= 4 ,-1 , 0
  4686.3     .05       0  4970.4     .16       0  4970.4    .035       0
  5016.5     .05       0
Bank Sta=4970.4,5016.5
XS Rating Curve= 0 ,0
Exp/Cntr=0.3,0.1

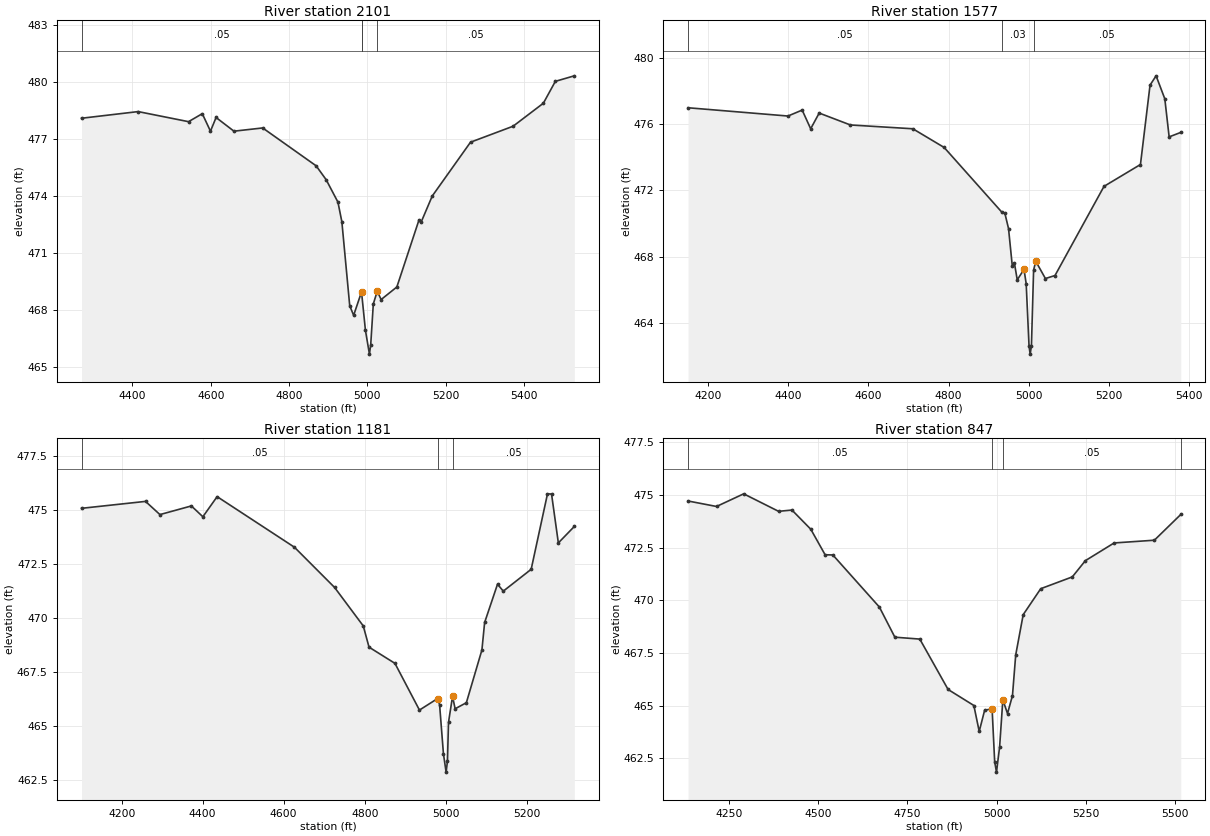
Type RM Length L Ch R = 1 ,2101    ,524,524,524
BEGIN DESCRIPTION:
UNT00804 IN CHRS 3.0
END DESCRIPTION:
XS GIS Cut Line= 4
       3474300.6     10591845.99      3474002.83     10592097.95
      3473957.02     10592702.63      3474007.41     10592959.15
#Sta/Elev= 30
  4270.3  478.09  4414.8  478.44  4543.4  477.91  4578.5  478.33  4599.4  477.41
  4613.7  478.13  4659.3  477.41  4732.7  477.58  4869.1  475.59  4894.7  474.86
  4924.8  473.68  4934.8  472.65  4954.9  468.23  4964.9  467.73    4985  468.96
    4995  466.94  5005.2  465.69  5008.5  466.19  5015.1  468.33  5025.1  468.99
  5035.1  468.56  5075.2  469.22  5131.8  472.75  5136.8  472.61  5165.5     474
  5263.2  476.83  5371.9  477.67  5449.2  478.88  5479.8  480.03  5528.2  480.32
#Mann= 4 ,-1 , 0
  4270.3     .05       0    4985     .16       0    4985    .035       0
  5025.1     .05       0
Bank Sta=4985,5025.1
XS Rating Curve= 0 ,0
Exp/Cntr=0.3,0.1

Type RM Length L Ch R = 1 ,1577    ,396,396,396
BEGIN DESCRIPTION:
UNT00804 IN CHRS 2.0
END DESCRIPTION:
XS GIS Cut Line= 3
      3474090.35     10591707.61      3473643.29     10592163.35
      3473418.33     10592708.45
#Sta/Elev= 30
  4150.7  476.99  4399.8  476.49  4435.2  476.85  4456.4  475.72  4477.6  476.67
  4555.4  475.95    4711  475.72  4789.1  474.59  4932.8  470.68  4940.2  470.63
  4949.5  469.69  4958.8  467.45  4964.2   467.6  4971.2  466.59  4988.1  467.22
  4993.5  466.36  5000.6   462.6  5003.4   462.1  5006.6   462.6    5012  467.18
  5017.4  467.71  5041.4  466.67  5065.3  466.85  5187.5  472.24  5278.3  473.56
  5302.2  478.36  5317.3  478.92    5339  477.53  5349.8  475.23  5378.8   475.5
#Mann= 3 ,-1 , 0
  4150.7     .05       0  4932.8     .03       0    5012     .05       0
Bank Sta=4988.1,5017.4
XS Rating Curve= 0 ,0
Exp/Cntr=0.3,0.1

Type RM Length L Ch R = 1 ,1181    ,295,295,295
BEGIN DESCRIPTION:
UNT00804 IN CHRS 1.0
END DESCRIPTION:
XS GIS Cut Line= 4
      3473942.78      10591599.1      3473391.55     10592119.95
      3473144.16     10592250.16      3473122.54      10592427.4
#Sta/Elev= 30
    4101  475.08  4258.9   475.4  4294.5  474.79  4372.1  475.19  4400.5  474.69
  4435.7  475.62  4626.6  473.28  4725.7  471.42  4796.5  469.64  4810.7  468.66
  4874.7  467.91  4935.2  465.75 4979.78  466.28  4984.9     466  4994.4  463.73
    5001  462.88  5004.3  463.38  5006.9  465.18 5016.85  466.38  5023.3  465.81
    5051  466.09  5089.4  468.53  5096.1   469.8  5127.9  471.57  5142.2  471.25
    5211  472.26  5251.3  475.75  5261.3  475.74  5278.1  473.48  5317.5  474.24
#Mann= 3 ,-1 , 0
    4101     .05       0 4979.78     .03       0 5016.85     .05       0
Bank Sta=4979.78,5016.85
XS Rating Curve= 0 ,0
Exp/Cntr=0.3,0.1

Type RM Length L Ch R = 1 ,847     ,0,0,0
BEGIN DESCRIPTION:
UNT00804 IN CHRS 1.0
END DESCRIPTION:
XS GIS Cut Line= 5
      3473895.65     10591542.88      3473288.01     10591801.13
      3473042.78     10591963.89      3473057.97     10592085.42
      3473097.01     10592386.86
#Sta/Elev= 30
  4135.3  474.71  4215.2  474.45  4291.3  475.05  4389.1  474.22  4426.6  474.28
  4479.4  473.37  4519.5  472.16  4541.2  472.15  4671.6  469.68    4715  468.25
  4784.9  468.16  4864.2  465.77  4936.4  465.01  4951.4  463.78  4966.5  464.78
  4987.5  464.86  4994.7  462.35  4999.8  461.85  5008.6  463.05  5017.6  465.28
  5030.7  464.63  5044.6  465.48  5053.7  467.41  5074.7  469.32  5123.8  470.55
  5212.3  471.11  5248.9  471.88  5329.5  472.72  5442.3  472.85  5516.3  474.07
#Mann= 4 ,-1 , 0
  4135.3     .05       0  4987.5     .07       0  5017.6     .05       0
  5516.3     .05       0
Bank Sta=4987.5,5017.6
XS Rating Curve= 0 ,0
Exp/Cntr=0.3,0.1

Chan Stop Cuts=-1
Use User Specified Reach Order=0
Composite Channel Slope=5