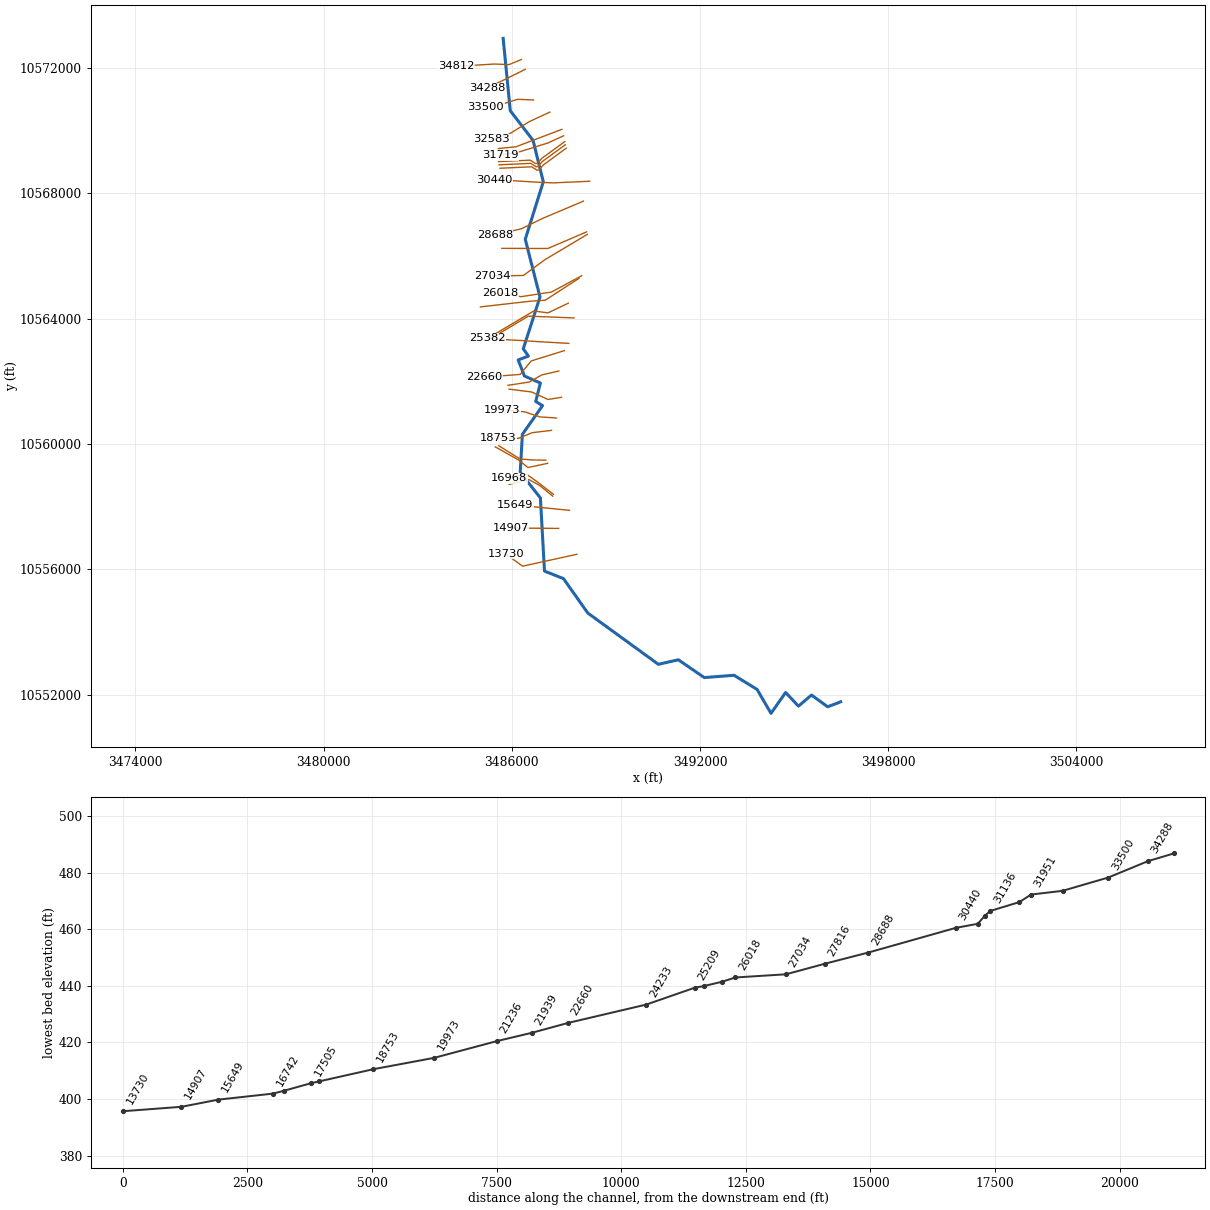
--- UNT0081 IN CHRS.prj (project) ---

Proj Title=UNT0081 IN CHRS Base Level Engineering
Current Plan=p01
Default Exp/Contr=0.3,0.1
English Units
Geom File=g01
Flow File=f01
Plan File=p01
Y Axis Title=Elevation
X Axis Title(PF)=Main Channel Distance
X Axis Title(XS)=Station
BEGIN DESCRIPTION:
UNT0081 IN CHRS
END DESCRIPTION:
DSS Export Rating Curves= 0
DSS Export Rating Curve Sorted= 0
DSS Export Volume Flow Curves= 0
DXF OffsetX= 0
DXF OffsetY= 0
DXF ScaleX= 1
DXF ScaleY= 10

--- UNT0081 IN CHRS.p01 (plan) ---

Plan Title=Multiple Run
Short Identifier=Multiple
Geom File=g01
Flow File=f01
Subcritical Flow
K Sum by GR= 0
Std Step Tol= 0.01
Critical Tol= 0.01
Num of Std Step Trials= 20
Max Error Tol= 0.3
Flow Tol Ratio= 0.001
Split Flow NTrial= 30
Split Flow Tol= 0.02
Split Flow Ratio= 0.02
Log Output Level= 0
Friction Slope Method= 1
Unsteady Friction Slope Method= 2
Unsteady Bridges Friction Slope Method= 1
Parabolic Critical Depth
Global Vel Dist=  1 , 1 , 1
Global Log Level= 0
CheckData=True
Encroach Param= -1, 0, 0, 0
BEGIN DESCRIPTION:
Multiple Run
END DESCRIPTION:

--- UNT0081 IN CHRS.f01 (steady flow) ---

Flow Title=Multiple
Program Version=4.10
Number of Profiles= 7
Profile Names=10-year,25-year,50-year,1pct_min,100-year,1pct_plu,500-year
River Rch & RM=UNT0081 IN CHRS,Reach-1         ,34812
     612     779     904     762    1030    1393    1336
River Rch & RM=UNT0081 IN CHRS,Reach-1         ,30440
     706     906    1056     894    1209    1635    1582
River Rch & RM=UNT0081 IN CHRS,Reach-1         ,28688
     740     951    1108     939    1270    1717    1662
River Rch & RM=UNT0081 IN CHRS,Reach-1         ,25382
     932    1211    1424    1216    1644    2223    2186
River Rch & RM=UNT0081 IN CHRS,Reach-1         ,16968
    1069    1395    1644    1406    1902    2572    2540
River Rch & RM=UNT0081 IN CHRS,Reach-1         ,9816
    1117    1453    1709    1457    1970    2665    2615
Boundary for River Rch & Prof#=UNT0081 IN CHRS,Reach-1         , 1
Up Type= 0
Dn Type= 3
Dn Slope=0.005
Boundary for River Rch & Prof#=UNT0081 IN CHRS,Reach-1         , 2
Up Type= 0
Dn Type= 3
Dn Slope=0.005
Boundary for River Rch & Prof#=UNT0081 IN CHRS,Reach-1         , 3
Up Type= 0
Dn Type= 3
Dn Slope=0.005
Boundary for River Rch & Prof#=UNT0081 IN CHRS,Reach-1         , 4
Up Type= 0
Dn Type= 3
Dn Slope=0.005
Boundary for River Rch & Prof#=UNT0081 IN CHRS,Reach-1         , 5
Up Type= 0
Dn Type= 3
Dn Slope=0.005
Boundary for River Rch & Prof#=UNT0081 IN CHRS,Reach-1         , 6
Up Type= 0
Dn Type= 3
Dn Slope=0.005
Boundary for River Rch & Prof#=UNT0081 IN CHRS,Reach-1         , 7
Up Type= 0
Dn Type= 3
Dn Slope=0.005
DSS Import GetInterval= 0
DSS Import GetPeak= 0
DSS Import FillOption= 0

--- UNT0081 IN CHRS.g01 (geometry) ---

Geom Title=Existing Conditions
Program Version=4.10

River Reach=UNT0081 IN CHRS ,Reach-1
Reach XY= 30
      3485722.26      10572934.8      3485948.51     10570627.86
      3486674.73     10569682.66      3487001.96     10568362.41
      3486427.04     10566528.24      3486896.41     10564688.15
      3486363.38     10563035.52      3486528.67     10562802.58
      3486202.11     10562681.64      3486400.32     10562167.23
      3486908.08     10561946.86      3486761.94     10561356.64
      3486977.39     10561223.37      3486335.46     10560310.32
      3486265.93     10559096.75       3486909.9     10558280.53
      3487039.44     10555949.86      3487645.03     10555709.02
      3488419.52     10554612.94      3490669.62     10552977.01
      3491308.29     10553121.29      3492133.27     10552554.41
      3493084.96     10552627.43       3493818.7      10552175.5
      3494261.81     10551412.82       3494727.5     10552079.75
      3495137.62     10551643.24      3495552.95     10551997.79
      3496067.43     10551623.05      3496482.11     10551781.64

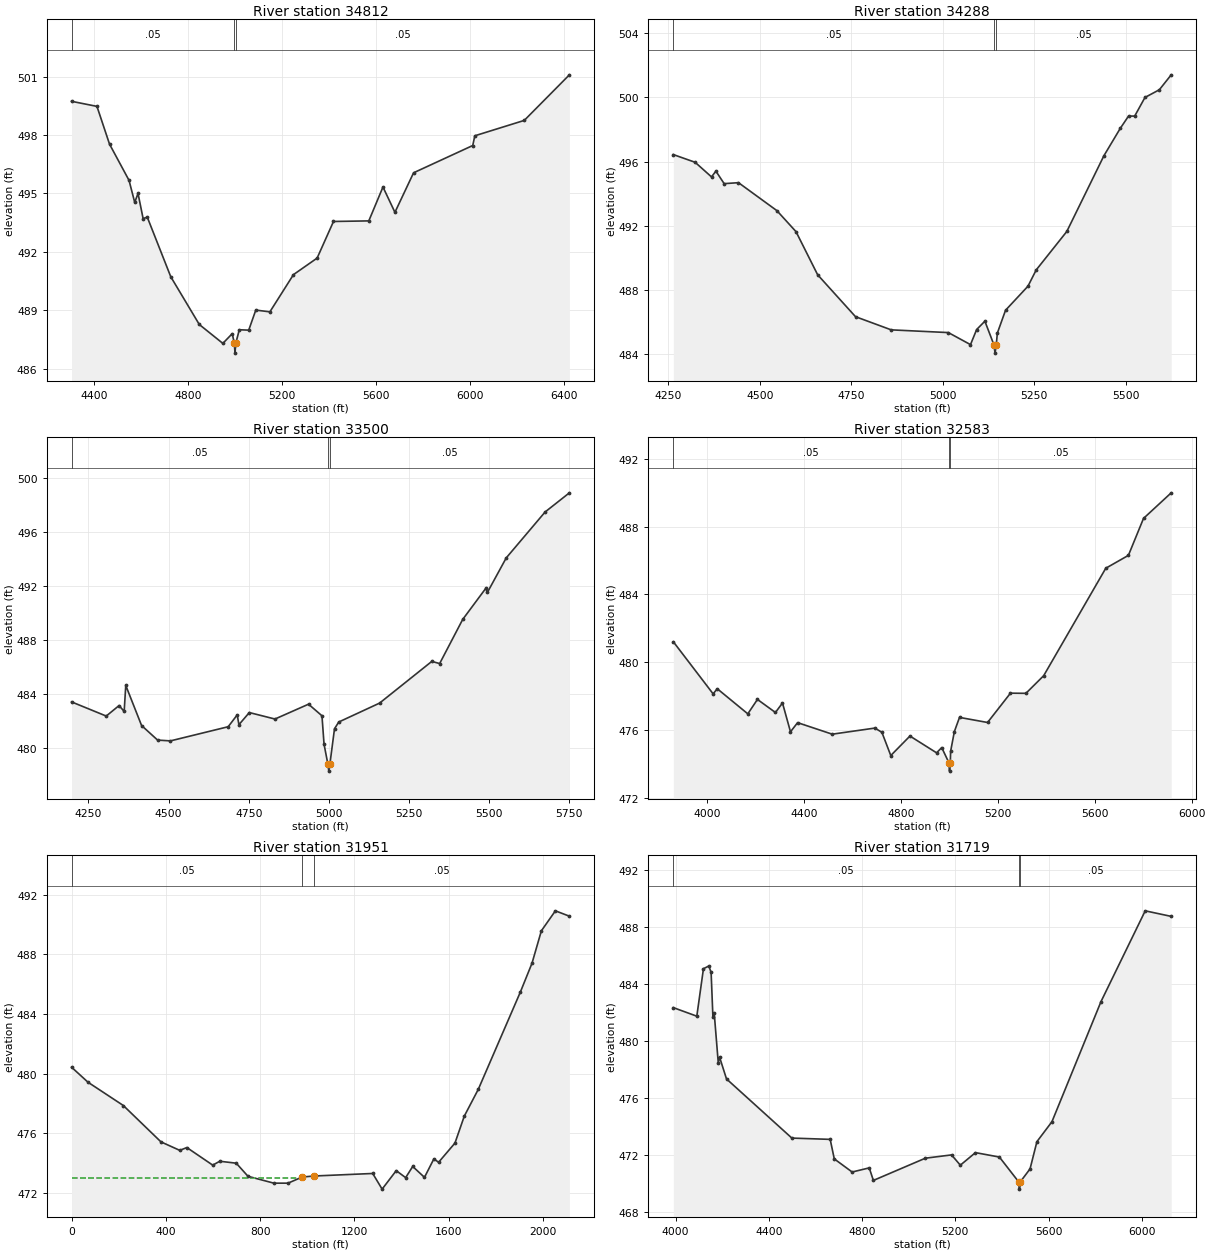
Type RM Length L Ch R = 1 ,34812   ,519,519,519
BEGIN DESCRIPTION:
UNT0081 IN CHRS 59.0
END DESCRIPTION:
XS GIS Cut Line= 4
      3486303.95      10572258.6      3485908.99     10572098.01
      3485440.24     10572115.37       3484220.6     10572041.59
#Sta/Elev= 30
  4304.7  499.73  4412.7  499.47  4466.2  497.53  4549.2  495.67  4573.3  494.54
  4587.4     495    4609  493.71  4626.8  493.78  4726.7  490.72    4848  488.27
  4948.1   487.3  4988.1   487.8    4997   487.3  4999.8   486.8    5003   487.3
  5018.1     488  5058.2  487.98  5088.2  489.01  5148.2  488.92  5248.4  490.83
  5349.1  491.68  5418.7  493.56  5568.9  493.59  5629.1  495.33    5680  494.03
  5759.3  496.06  6010.9  497.46  6019.8  497.96  6230.1  498.75    6422  501.09
#Mann= 3 ,-1 , 0
  4304.7     .05       0    4997     .03       0    5003     .05       0
Bank Sta=4997,5003
XS Rating Curve= 0 ,0
Exp/Cntr=0.3,0.1

Type RM Length L Ch R = 1 ,34288   ,798,798,798
BEGIN DESCRIPTION:
UNT0081 IN CHRS 58.0
END DESCRIPTION:
XS GIS Cut Line= 2
      3486425.48      10571946.1      3485206.46      10571343.1
#Sta/Elev= 30
    4264  496.44  4323.5  495.96  4368.2  495.05  4380.2  495.41  4402.7  494.63
  4441.9  494.69  4546.7  492.95    4599  491.64  4658.2  488.95  4761.6  486.34
  4859.1  485.52  5015.2  485.35  5075.7   484.6  5092.5  485.54    5115  486.06
    5140  484.57  5142.7  484.07    5146  484.57  5149.1  485.32  5171.4  486.74
  5232.7  488.24  5255.1  489.25  5338.8  491.65  5440.2  496.37    5485  498.08
  5507.5  498.84  5524.3  498.84  5552.3     500  5591.6  500.48    5624  501.41
#Mann= 3 ,-1 , 0
    4264     .05       0    5140     .03       0    5146     .05       0
Bank Sta=5140,5146
XS Rating Curve= 0 ,0
Exp/Cntr=0.3,0.1

Type RM Length L Ch R = 1 ,33500   ,917,917,917
BEGIN DESCRIPTION:
UNT0081 IN CHRS 56.0
END DESCRIPTION:
XS GIS Cut Line= 4
      3486690.25     10570969.54      3486186.76     10570991.24
      3485670.27     10570830.65      3485166.98     10570761.23
#Sta/Elev= 30
  4197.3   483.4  4305.5  482.35  4345.6  483.13  4361.4  482.69  4366.4  484.62
  4415.7  481.65  4465.7  480.57  4505.7  480.51  4685.9  481.56  4714.1  482.44
  4719.3  481.71  4751.8  482.61  4831.8  482.13  4936.5  483.23  4978.4  482.37
  4984.9  480.26    4997  478.77  4999.8  478.27    5003  478.77  5017.5  481.41
  5030.8  481.91  5158.1  483.31    5321   486.4  5345.5  486.24  5417.4  489.51
  5489.3  491.81  5494.4  491.51  5553.2  494.07  5674.4  497.47  5750.2  498.89
#Mann= 3 ,-1 , 0
  4197.3     .05       0    4997     .03       0    5003     .05       0
Bank Sta=4997,5003
XS Rating Curve= 0 ,0
Exp/Cntr=0.3,0.1

Type RM Length L Ch R = 1 ,32583   ,632,632,632
BEGIN DESCRIPTION:
UNT0081 IN CHRS 54.0
END DESCRIPTION:
XS GIS Cut Line= 4
      3487211.06     10570583.25      3486555.69     10570279.43
      3485865.58     10569854.09      3485362.08     10569710.85
#Sta/Elev= 30
    3859   481.2  4023.2  478.13  4040.4  478.43  4166.5  476.95  4206.3   477.8
  4280.6  477.03  4309.8  477.59  4342.8  475.89  4372.2  476.43  4515.2  475.75
  4691.3  476.11  4720.4  475.86  4757.1  474.49  4836.3  475.64  4946.3  474.65
  4967.6  474.96    4997  474.07  4999.8  473.57    5003  474.07  5004.3  474.74
  5019.7   475.9    5041  476.74  5156.9  476.44  5251.5  478.17  5315.3  478.16
  5388.7   479.2  5645.2  485.54  5738.7   486.3  5801.1  488.48  5915.5  489.99
#Mann= 3 ,-1 , 0
    3859     .05       0    4997    .035       0    5003     .05       0
Bank Sta=4997,5003
XS Rating Curve= 0 ,0
Exp/Cntr=0.3,0.1

Type RM Length L Ch R = 1 ,31951   ,232,232,232
XS GIS Cut Line= 3
       3487593.4    10570032.373     3486128.122    10569476.817
     3485569.094    10569421.262
#Sta/Elev= 30
       0  480.43   69.86  479.42  219.56  477.86  379.23  475.42  459.07  474.85
  489.01  475.04  598.79  473.86  628.73  474.12  698.58  473.99  748.48  473.11
  858.26  472.65  918.14  472.65  978.02  473.06 1027.92  473.13 1277.41   473.3
 1317.33  472.25 1377.21  473.49 1417.13  473.02 1447.07  473.77 1496.97  473.04
 1536.89  474.28 1556.85  474.05 1626.33  475.34 1665.96  477.15 1725.39  478.95
  1903.7  485.47 1953.23  487.41 1992.85  489.58 2052.28  490.92 2111.72  490.56
#Mann= 3 , 0 , 0
       0     .05       0  978.02    .035       0 1027.92     .05       0
#XS Ineff= 2 , 0
       0  961.59     473 1038.28       0  473.04
Permanent Ineff=
       T       T
Bank Sta=978.02,1027.92
XS Rating Curve= 0 ,0
Exp/Cntr=0.3,0.1

Type RM Length L Ch R = 1 ,31719   ,583,583,583
BEGIN DESCRIPTION:
UNT0081 IN CHRS 52.0
END DESCRIPTION:
XS GIS Cut Line= 4
      3487649.48     10569828.06      3487145.97     10569598.01
      3486256.21     10569320.23      3485615.51     10569207.68
#Sta/Elev= 30
  3990.3  482.33  4090.9  481.73  4119.4  485.06  4142.5  485.25  4152.3   484.8
    4160  481.68  4165.5  481.96    4183  478.45  4188.5  478.86  4218.3  477.33
  4498.8  473.18  4663.2  473.09  4680.8  471.72  4757.4   470.8  4830.8  471.09
  4848.5  470.21  5071.7  471.77  5183.9     472  5221.6  471.28  5286.6  472.16
  5389.3  471.85  5472.5   470.1  5475.3   469.6  5478.5   470.1  5520.8  471.02
  5550.3  472.93  5614.8  474.33  5825.4  482.76    6015  489.12  6126.5  488.73
#Mann= 3 ,-1 , 0
  3990.3     .05       0  5472.5    .035       0  5478.5     .05       0
Bank Sta=5472.5,5478.5
XS Rating Curve= 0 ,0
Exp/Cntr=0.3,0.1

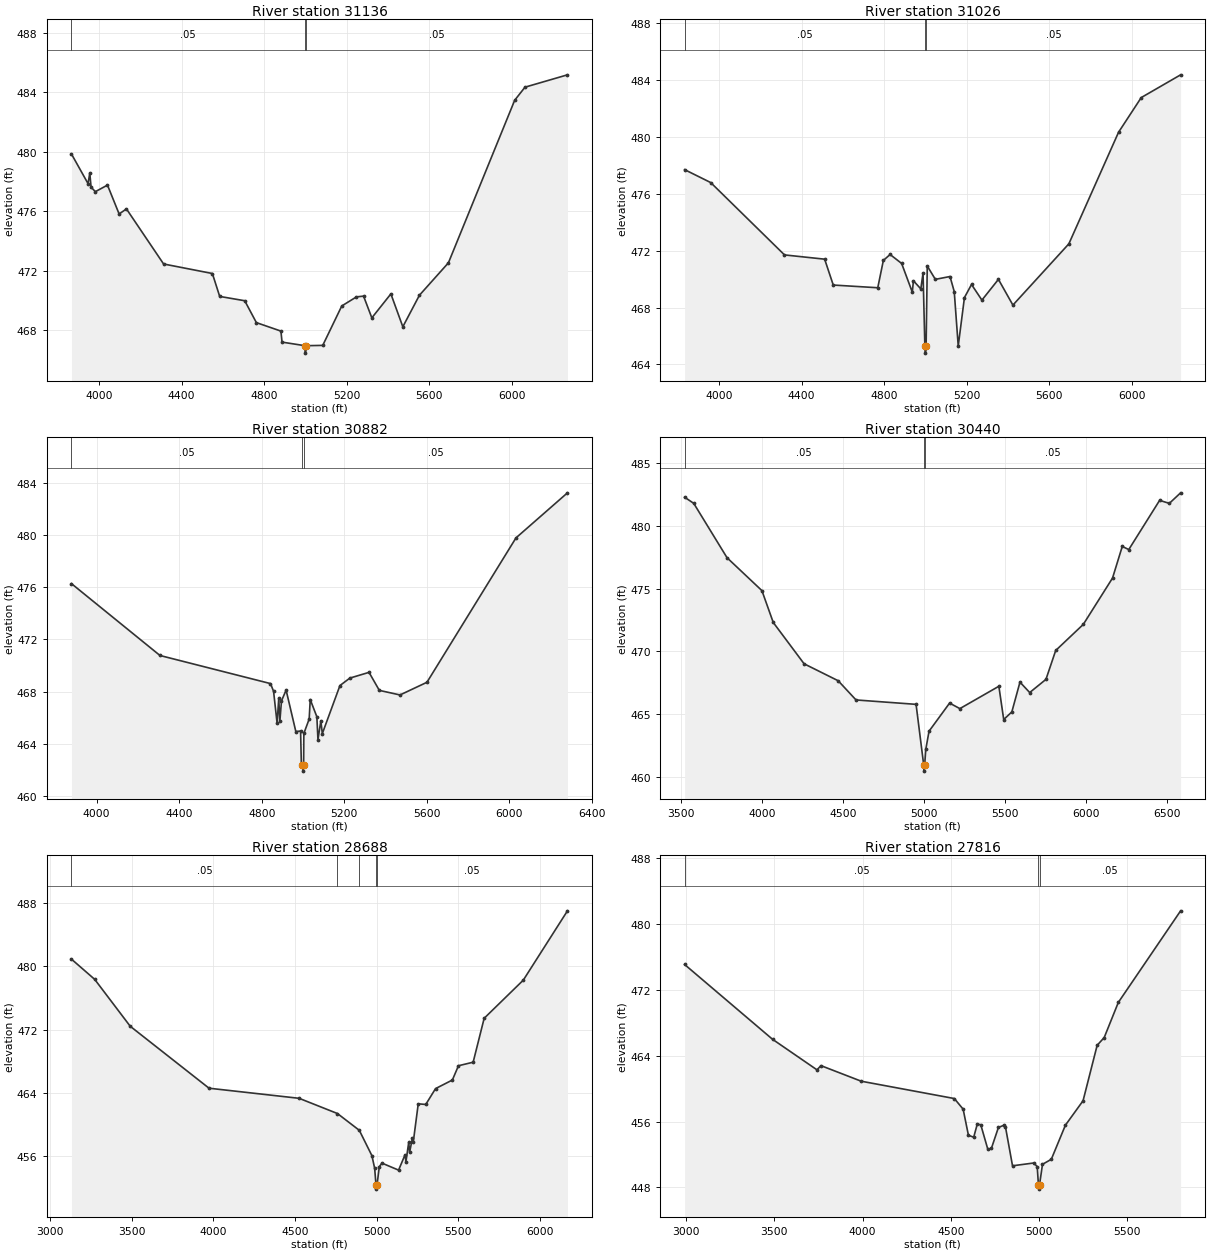
Type RM Length L Ch R = 1 ,31136   ,110,110,110
BEGIN DESCRIPTION:
UNT0081 IN CHRS 50.1
END DESCRIPTION:
XS GIS Cut Line= 6
      3487685.02     10569641.78      3486950.65     10569105.32
      3486823.05     10568954.28      3486757.94     10568941.26
      3486583.46     10569050.63      3485576.34     10569003.76
#Sta/Elev= 30
  3866.1  479.85  3946.4  477.86  3954.9  478.57  3961.1  477.62  3981.9  477.32
  4040.6  477.76    4097  475.82  4132.5  476.16  4312.5  472.46  4548.8  471.82
  4584.3  470.28  4705.6  469.99    4762  468.52    4881  467.95  4886.3  467.21
    4997  466.97  4999.8  466.47    5003  466.97  5083.6  466.99  5175.8  469.64
  5247.1  470.25  5281.4   470.3  5321.4  468.84  5413.7  470.45  5471.6  468.24
    5552  470.36  5692.6  472.54  6013.5  483.46  6063.5  484.34  6269.3  485.17
#Mann= 3 ,-1 , 0
  3866.1     .05       0    4997    .035       0    5003     .05       0
Bank Sta=4997,5003
XS Rating Curve= 0 ,0
Exp/Cntr=0.3,0.1

Type RM Length L Ch R = 1 ,31026   ,144,144,144
BEGIN DESCRIPTION:
UNT0081 IN CHRS 50.2
END DESCRIPTION:
XS GIS Cut Line= 6
      3487700.67     10569540.23      3486966.28     10569003.76
      3486838.67     10568852.72      3486773.57      10568839.7
      3486599.09     10568949.07      3485591.29      10568902.2
#Sta/Elev= 30
  3832.6   477.7  3959.1  476.79  4316.7   471.7  4511.3   471.4    4553  469.58
  4768.7  469.39  4795.8  471.31  4828.5  471.73  4884.4   471.1  4936.1  469.08
  4941.6  469.88  4977.4  469.31  4988.2  470.43    4997  465.29  4999.8  464.79
    5003  465.29  5008.6  470.92  5047.8  469.98  5118.9  470.18  5139.4  469.12
  5158.7  465.29  5188.8   468.7  5223.1  469.62  5273.5  468.52  5353.5  469.98
  5423.7  468.17  5694.9  472.48  5935.7  480.33  6045.7  482.77  6236.5  484.37
#Mann= 3 ,-1 , 0
  3832.6     .05       0    4997     .03       0    5003     .05       0
Bank Sta=4997,5003
XS Rating Curve= 0 ,0
Exp/Cntr=0.3,0.1

Type RM Length L Ch R = 1 ,30882   ,442,442,442
BEGIN DESCRIPTION:
UNT0081 IN CHRS 50.5
END DESCRIPTION:
XS GIS Cut Line= 6
      3487731.89     10569430.84      3486997.53     10568894.38
      3486869.92     10568743.34      3486804.82     10568730.32
      3486630.34      10568839.7      3485622.51     10568792.82
#Sta/Elev= 30
  3877.8  476.26  4306.8  470.76  4842.4  468.61  4857.3  468.02  4874.4  465.58
  4882.4  467.48  4887.7  465.71  4895.7  467.29  4918.1  468.11  4965.2  464.94
  4988.2  464.98  4992.1  462.41    4997  462.41  4999.8  461.91    5003  462.41
    5004  464.79  5029.9   465.9    5035  467.39  5067.1  466.07  5072.4  464.32
  5086.5  465.77  5093.5  464.78    5179  468.46    5227  469.03  5319.9  469.47
  5369.9  468.09  5470.1  467.74  5600.7  468.71  6032.1  479.76  6281.7  483.21
#Mann= 3 ,-1 , 0
  3877.8     .05       0    4997     .03       0    5003     .05       0
Bank Sta=4997,5003
XS Rating Curve= 0 ,0
Exp/Cntr=0.3,0.1

Type RM Length L Ch R = 1 ,30440   ,1752,1752,1752
BEGIN DESCRIPTION:
UNT0081 IN CHRS 50.0
END DESCRIPTION:
XS GIS Cut Line= 4
      3488478.47     10568378.39      3487319.58     10568326.31
      3486811.76     10568348.01      3485422.85     10568430.48
#Sta/Elev= 30
  3522.1  482.29  3578.5   481.8  3783.8  477.47  3998.9  474.85    4069  472.31
  4259.2  469.02  4469.4  467.67  4579.5  466.14  4949.9  465.79  4996.9  460.97
  4999.7  460.47  5002.9  460.97  5009.9  462.21  5029.9  463.65  5156.7  465.89
  5220.1  465.45  5460.6  467.23  5490.6  464.58  5540.7  465.19  5590.8  467.56
  5650.9  466.73  5751.1  467.78  5811.2  470.08  5981.5  472.16  6161.8  475.85
  6221.9  478.37    6262  478.12  6452.3  482.04  6512.2   481.8  6581.8  482.64
#Mann= 3 ,-1 , 0
  3522.1     .05       0  4996.9     .03       0  5002.9     .05       0
Bank Sta=4996.9,5002.9
XS Rating Curve= 0 ,0
Exp/Cntr=0.3,0.1

Type RM Length L Ch R = 1 ,28688   ,872,872,872
BEGIN DESCRIPTION:
UNT0081 IN CHRS 47.0
END DESCRIPTION:
XS GIS Cut Line= 4
      3488283.15     10567744.73       3486998.4     10567202.18
      3486303.95     10566863.64       3485455.2     10566664.44
#Sta/Elev= 30
  3129.9  480.93  3272.1  478.37  3489.8  472.42  3972.8  464.56  4524.5  463.28
  4759.5  461.35  4893.5  459.22  4970.8     456  4987.6   454.4  4995.9  452.26
  4998.7  451.76  5001.9  452.26  5015.9   454.6  5032.1  455.06  5134.2  454.17
  5173.7  456.12  5179.2  455.24  5196.2  457.69  5201.8  456.44  5218.7  458.22
  5224.3  457.76  5254.6  462.58  5300.6   462.5  5360.6  464.51  5463.7   465.6
    5501  467.41    5591  467.86  5658.5  473.43  5898.3  478.27  6168.9  487.06
#Mann= 5 ,-1 , 0
  3129.9     .05       0  4759.5     .16       0  4893.5     .05       0
  4995.9    .035       0  5001.9     .05       0
Bank Sta=4995.9,5001.9
XS Rating Curve= 0 ,0
Exp/Cntr=0.3,0.1

Type RM Length L Ch R = 1 ,27816   ,782,782,782
BEGIN DESCRIPTION:
UNT0081 IN CHRS 46.0
END DESCRIPTION:
XS GIS Cut Line= 3
      3488382.95     10566763.81      3487145.97      10566234.3
      3485678.93     10566238.64
#Sta/Elev= 30
    2991  475.05  3489.4  465.98  3741.6  462.27  3764.2  462.78  3992.7  460.89
  4520.4  458.79  4570.4   457.5  4600.4  454.33  4630.4   454.1  4650.4  455.68
  4670.4  455.61  4710.4  452.63  4730.4  452.73  4770.4  455.28  4800.4  455.54
  4810.4  455.35  4850.4  450.63  4970.4  450.97  4990.4  450.54  4997.4   448.3
  5000.2   447.8  5003.4   448.3  5020.4  450.81  5070.4  451.42  5150.4  455.56
  5250.4  458.52  5330.4  465.25  5370.4  466.19  5450.4  470.45  5803.6  481.56
#Mann= 3 ,-1 , 0
    2991     .05       0  4997.4     .03       0  5003.4     .05       0
Bank Sta=4997.4,5003.4
XS Rating Curve= 0 ,0
Exp/Cntr=0.3,0.1

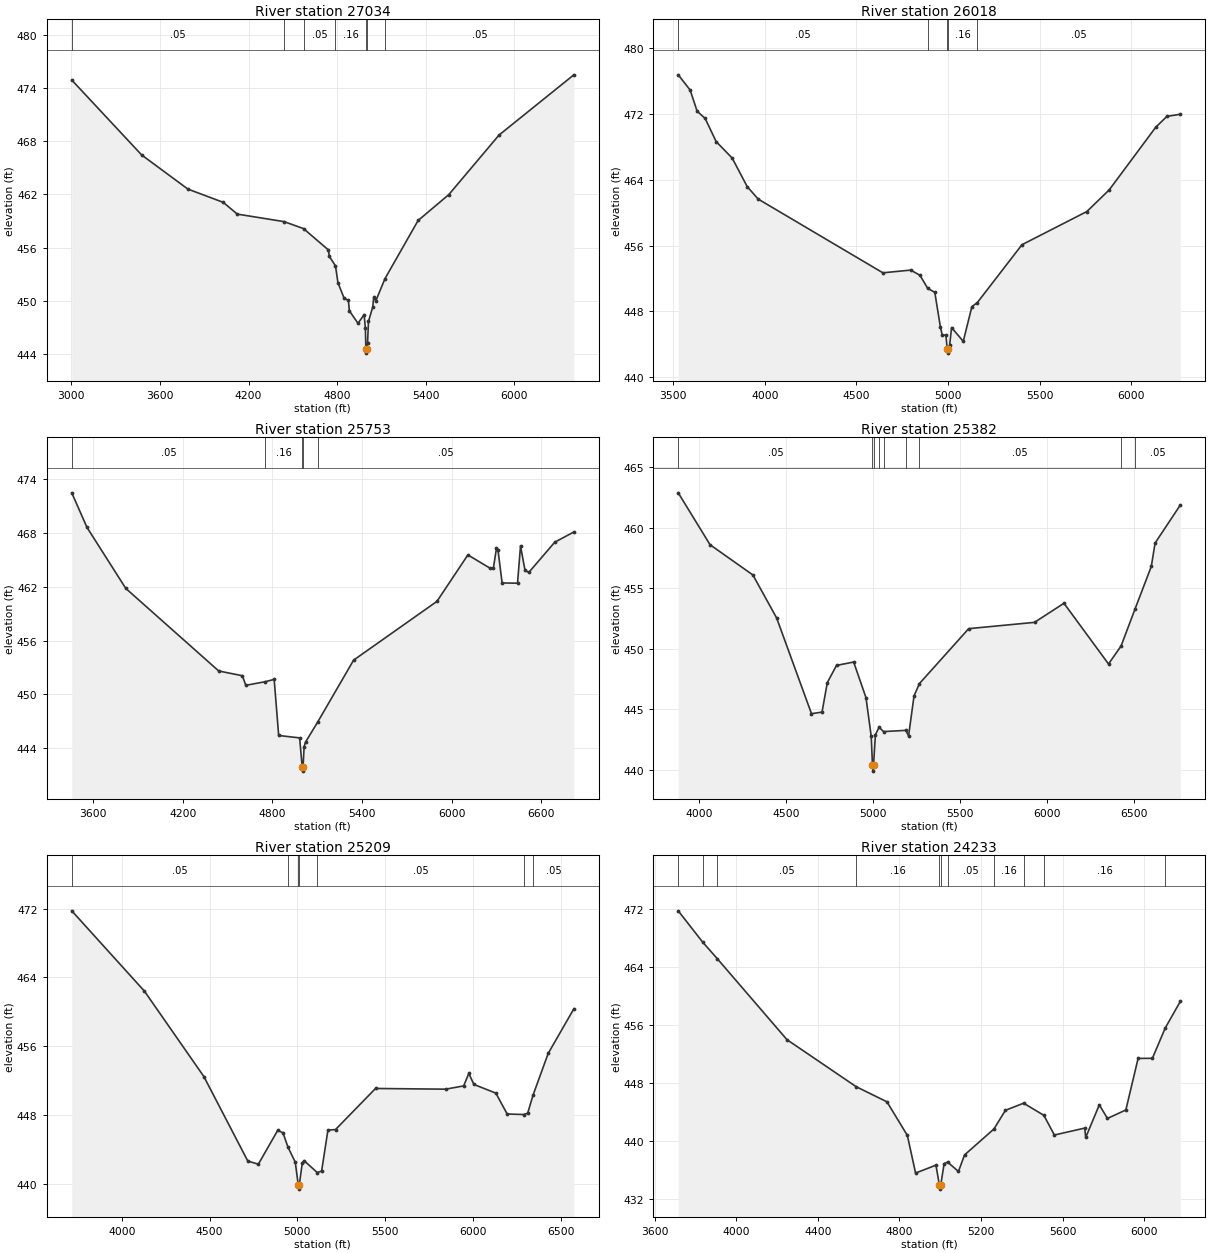
Type RM Length L Ch R = 1 ,27034   ,1016,1016,1016
BEGIN DESCRIPTION:
UNT0081 IN CHRS 44.0
END DESCRIPTION:
XS GIS Cut Line= 4
      3488400.33     10566681.36       3487041.8     10565869.71
      3486369.06     10565374.92      3485385.44     10565357.59
#Sta/Elev= 30
  3002.6  474.94    3476  466.47  3789.3  462.61  4028.6  461.11  4123.9  459.78
  4441.1  458.93  4572.7  458.14  4741.1  455.73  4747.3     455  4789.1  453.93
  4805.9  452.02  4847.6  450.27  4876.8  450.02  4883.1  448.85  4941.6  447.43
  4983.3  448.41  4991.8  446.88    4995  444.56  4997.7  444.06    5001  444.56
  5006.4  445.16  5012.6  447.64  5041.9  449.29  5048.1  450.37  5062.8  449.99
  5124.7  452.49    5349  459.06  5557.2  461.99  5897.3  468.72    6404  475.53
#Mann= 7 ,-1 , 0
  3002.6     .05       0  4441.1     .16       0  4572.7     .05       0
  4789.1     .16       0    4995     .07       0    5001     .16       0
  5124.7     .05       0
Bank Sta=4995,5001
XS Rating Curve= 0 ,0
Exp/Cntr=0.3,0.1

Type RM Length L Ch R = 1 ,26018   ,265,265,265
BEGIN DESCRIPTION:
UNT0081 IN CHRS 43.0
END DESCRIPTION:
XS GIS Cut Line= 4
      3488226.73     10565366.26      3487263.15     10564845.41
      3486290.93     10564697.84      3485639.94     10564810.68
#Sta/Elev= 30
  3528.1  476.76  3593.1  474.91  3631.2  472.34    3675  471.46  3734.9  468.65
  3822.5  466.64  3904.3  463.18  3964.3  461.66  4644.7   452.7  4796.4  453.03
    4847   452.4  4889.4  450.81  4927.9  450.33  4958.3  446.14  4968.4  445.15
  4988.6  445.14  4995.7  443.44  4998.5  442.94  5001.7  443.44  5008.9  443.89
  5019.5  446.05  5083.2  444.37  5130.2  448.58  5160.3  449.09  5403.3  456.11
  5757.8  460.15  5879.6  462.78  6133.4  470.39  6194.3  471.71  6267.5  471.97
#Mann= 5 ,-1 , 0
  3528.1     .05       0  4889.4     .16       0  4995.7     .07       0
  5001.7     .16       0  5160.3     .05       0
Bank Sta=4995.7,5001.7
XS Rating Curve= 0 ,0
Exp/Cntr=0.3,0.1

Type RM Length L Ch R = 1 ,25753   ,371,371,371
BEGIN DESCRIPTION:
UNT0081 IN CHRS 42.0
END DESCRIPTION:
XS GIS Cut Line= 4
      3488139.85     10565283.75       3487063.5     10564584.99
      3486590.41     10564554.61      3484997.55     10564372.32
#Sta/Elev= 30
  3457.3   472.5  3559.1  468.64  3818.8  461.83    4441  452.61  4599.2  452.08
  4622.2  451.01  4751.1  451.41  4812.1  451.67  4842.2  445.41  4982.5  445.14
  4999.5  441.93  5002.3  441.43  5005.5  441.93  5012.5  444.17  5022.2  444.68
  5102.9   446.9  5343.8  453.82  5901.4  460.38  6108.7  465.57  6259.7  464.06
  6279.9  464.16    6300  466.31    6310  466.14  6337.7  462.44  6440.9  462.41
    6461  466.56  6491.2  463.84  6516.2  463.61  6689.7  466.98  6817.9  468.13
#Mann= 5 ,-1 , 0
  3457.3     .05       0  4751.1     .16       0  4999.5     .07       0
  5005.5     .16       0  5102.9     .05       0
Bank Sta=4999.5,5005.5
XS Rating Curve= 0 ,0
Exp/Cntr=0.3,0.1

Type RM Length L Ch R = 1 ,25382   ,173,173,173
BEGIN DESCRIPTION:
UNT0081 IN CHRS 41.0
END DESCRIPTION:
XS GIS Cut Line= 4
      3487796.99     10564489.49      3487150.31     10564181.34
      3486698.92     10564242.11      3485227.52     10563369.69
#Sta/Elev= 30
  3882.2  462.89  4064.8   458.6  4310.7   456.1  4446.9  452.55  4647.2  444.63
  4707.7  444.76    4738   447.2  4790.8  448.62  4889.3   448.9    4960  445.96
  4990.2  442.75  4997.3  440.38  5000.1  439.88  5003.3  440.38  5014.3  442.89
  5035.3  443.51  5060.8  443.15  5188.7  443.25  5204.6  442.79  5235.8  446.09
  5266.9  447.12  5549.7  451.66  5927.7  452.18  6096.6  453.76  6352.4  448.74
  6424.3  450.22  6503.8  453.25  6598.2  456.81  6619.8  458.74  6764.6  461.88
#Mann= 9 ,-1 , 0
  3882.2     .05       0  4997.3     .04       0  5003.3     .05       0
  5035.3     .16       0  5060.8     .05       0  5188.7     .16       0
  5266.9     .05       0  6424.3     .16       0  6503.8     .05       0
Bank Sta=4997.3,5003.3
XS Rating Curve= 0 ,0
Exp/Cntr=0.3,0.1

Type RM Length L Ch R = 1 ,25209   ,976,976,976
BEGIN DESCRIPTION:
UNT0081 IN CHRS 40.0
END DESCRIPTION:
XS GIS Cut Line= 3
      3487983.61     10564020.76      3486525.31     10564077.18
      3485323.03     10563361.02
#Sta/Elev= 30
  3715.7  471.73  4129.6  462.38  4467.8  452.45  4717.9  442.62    4778  442.25
  4888.1  446.18  4918.1  445.91  4946.8  444.24  4988.2  442.49  5005.2  439.85
  5007.9  439.35  5011.2  439.85  5028.2  442.39  5038.2  442.67  5113.4  441.28
  5138.3  441.45  5174.2  446.21  5217.4  446.28  5445.2  451.06  5844.3  450.98
    5947  451.36  5976.7  452.81  6005.2  451.53  6130.5  450.52  6194.8  448.09
  6288.6  448.03  6311.6  448.18  6342.1  450.28  6428.4  455.14  6574.5  460.33
#Mann= 7 ,-1 , 0
  3715.7     .05       0  4946.8     .16       0  5005.2     .07       0
  5011.2     .16       0  5113.4     .05       0  6288.6     .16       0
  6342.1     .05       0
Bank Sta=5005.2,5011.2
XS Rating Curve= 0 ,0
Exp/Cntr=0.3,0.1

Type RM Length L Ch R = 1 ,24233   ,1573,1573,1573
BEGIN DESCRIPTION:
UNT0081 IN CHRS 38.0
END DESCRIPTION:
XS GIS Cut Line= 4
       3487814.4     10563209.12      3486824.79     10563265.55
      3486299.61     10563300.27      3485355.28     10563352.25
#Sta/Elev= 30
  3714.6  471.68    3834  467.39  3905.6  465.11  4247.8  453.95  4588.3  447.46
  4738.6  445.39  4838.8  440.76    4879  435.58  4979.1  436.67  4996.1  433.87
  4998.9  433.37  5002.1  433.87  5019.2  436.89  5036.5  437.09  5089.3   435.8
  5119.4  438.08  5263.6  441.65  5319.8  444.22  5409.1   445.2  5508.4  443.53
  5560.1  440.82  5708.7  441.77  5713.7  440.48  5780.5  444.97  5820.5   443.1
  5910.7  444.27  5970.8  451.36  6040.9  451.38    6104  455.55  6177.9  459.21
#Mann= 11 ,-1 , 0
  3714.6     .05       0    3834     .16       0  3905.6     .05       0
  4588.3     .16       0  4996.1     .07       0  5002.1     .16       0
  5036.5     .05       0  5263.6     .16       0  5409.1     .05       0
  5508.4     .16       0    6104     .05       0
Bank Sta=4996.1,5002.1
XS Rating Curve= 0 ,0
Exp/Cntr=0.3,0.1

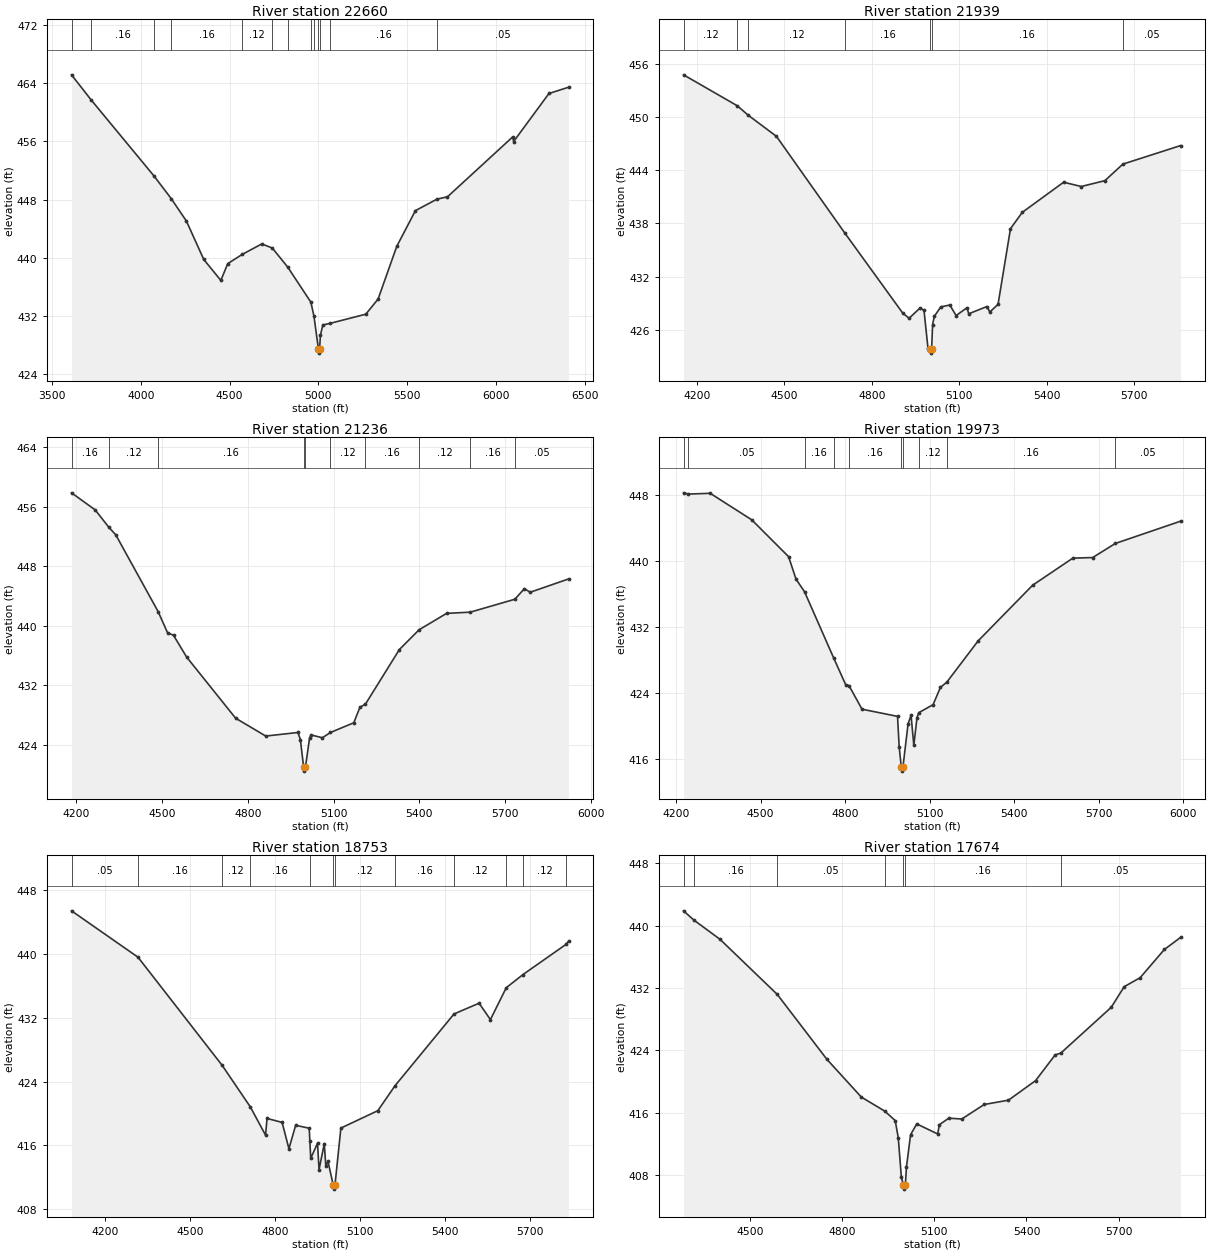
Type RM Length L Ch R = 1 ,22660   ,721,721,721
BEGIN DESCRIPTION:
UNT0081 IN CHRS 36.0
END DESCRIPTION:
XS GIS Cut Line= 4
      3487675.48     10562979.09      3486616.45     10562649.23
      3486264.89     10562219.54      3485132.11     10562132.74
#Sta/Elev= 30
  3609.1  465.17  3719.9  461.71  4073.4  451.26  4170.6  448.14  4256.5  445.04
  4354.1  439.76  4450.5  436.87  4489.4  439.18  4571.6  440.46    4681  441.89
  4740.4  441.33  4826.8  438.72  4957.8  433.88  4975.1  431.96  5000.7  427.36
  5003.5  426.86  5006.7  427.36  5011.6  429.32  5025.3  430.74    5065  430.95
  5267.2  432.22  5336.5   434.3    5442  441.57  5547.1  446.48  5668.7  448.06
  5727.6  448.38  6095.2  456.63  6100.2  455.99  6299.3   462.6  6409.6  463.46
#Mann= 13 ,-1 , 0
  3609.1     .05       0  3719.9     .16       0  4073.4     .12       0
  4170.6     .16       0  4571.6     .12       0  4740.4     .16       0
  4826.8     .12       0  4957.8     .16       0  4975.1     .12       0
  5000.7     .07       0  5006.7     .12       0    5065     .16       0
  5668.7     .05       0
Bank Sta=5000.7,5006.7
XS Rating Curve= 0 ,0
Exp/Cntr=0.3,0.1

Type RM Length L Ch R = 1 ,21939   ,703,703,703
BEGIN DESCRIPTION:
UNT0081 IN CHRS 34.0
END DESCRIPTION:
XS GIS Cut Line= 4
      3487497.55     10562328.05      3486950.65     10562202.18
      3486555.69     10561976.48      3485875.69     10561872.53
#Sta/Elev= 30
  4154.6  454.74  4339.1  451.25  4375.9   450.2  4473.1  447.81  4708.1  436.89
  4906.3  427.89  4927.9  427.32  4965.3  428.47    4979  428.21  4992.6  423.95
  4999.1  423.89  5001.8  423.39  5005.1  423.89  5008.5   426.6  5014.2  427.53
  5036.6   428.6  5067.5  428.81  5089.1  427.62  5126.5  428.51  5132.3  427.82
  5194.6  428.64  5204.7  428.02  5232.9  428.89  5275.5  437.41    5316  439.25
  5457.6  442.64  5518.3  442.16  5599.2  442.82  5660.7  444.68  5858.6  446.77
#Mann= 7 ,-1 , 0
  4154.6     .12       0  4339.1     .16       0  4375.9     .12       0
  4708.1     .16       0  4999.1     .07       0  5005.1     .16       0
  5660.7     .05       0
Bank Sta=4999.1,5005.1
XS Rating Curve= 0 ,0
Exp/Cntr=0.3,0.1

Type RM Length L Ch R = 1 ,21236   ,1263,1263,1263
BEGIN DESCRIPTION:
UNT0081 IN CHRS 32.0
END DESCRIPTION:
XS GIS Cut Line= 4
      3487584.38     10561490.38      3487150.31     10561420.93
      3486629.47     10561659.64      3485908.94     10561750.79
#Sta/Elev= 30
  4183.4   457.9    4266  455.61  4314.5  453.24  4338.2  452.25  4486.4  441.92
  4519.2  439.08  4540.2  438.73  4586.3  435.79  4757.6  427.57    4863  425.17
  4975.6  425.65    4984   424.7  4995.6  420.95  4998.4  420.45  5001.6  420.95
  5016.1  424.87  5021.6  425.32    5061  424.94  5089.4  425.65    5171  426.96
  5192.3  429.04  5211.8  429.47  5330.4  436.81  5399.3  439.47  5495.7  441.68
  5578.3  441.84  5734.4  443.58  5767.8  445.01    5788  444.52  5922.2  446.31
#Mann= 10 ,-1 , 0
  4183.4     .16       0  4314.5     .12       0  4486.4     .16       0
  4995.6     .07       0  5001.6     .16       0  5089.4     .12       0
  5211.8     .16       0  5399.3     .12       0  5578.3     .16       0
  5734.4     .05       0
Bank Sta=4995.6,5001.6
XS Rating Curve= 0 ,0
Exp/Cntr=0.3,0.1

Type RM Length L Ch R = 1 ,19973   ,1220,1220,1220
BEGIN DESCRIPTION:
UNT0081 IN CHRS 30.0
END DESCRIPTION:
XS GIS Cut Line= 4
      3487423.79     10560830.65      3486889.89     10560865.37
      3486412.46     10561025.96      3485691.97     10561099.75
#Sta/Elev= 30
    4227  448.26  4243.9  448.11  4321.6   448.2  4468.8  444.99  4599.5  440.52
    4626  437.79  4656.2  436.26  4759.8  428.21  4802.3  424.98  4813.9  424.88
    4860  422.02    4986  421.15  4991.8  417.49  4999.3  415.01  5002.1  414.51
  5005.3  415.01  5023.4  420.25    5034  421.28  5043.8  417.62  5055.1  421.01
  5061.4   421.6  5112.1  422.57  5138.3  424.67  5160.9   425.3  5271.8   430.3
  5465.4  437.06  5607.9  440.34  5678.2  440.41  5758.6  442.12    5990  444.82
#Mann= 10 ,-1 , 0
    4227     .16       0  4243.9     .05       0  4656.2     .16       0
  4759.8     .12       0  4813.9     .16       0  4999.3     .07       0
  5005.3     .16       0  5061.4     .12       0  5160.9     .16       0
  5758.6     .05       0
Bank Sta=4999.3,5005.3
XS Rating Curve= 0 ,0
Exp/Cntr=0.3,0.1

Type RM Length L Ch R = 1 ,18753   ,1079,1079,1079
BEGIN DESCRIPTION:
UNT0081 IN CHRS 28.0
END DESCRIPTION:
XS GIS Cut Line= 4
      3487263.19     10560435.69      3486646.83      10560361.9
      3486204.13     10560179.61      3485545.77     10560183.94
#Sta/Elev= 30
    4080  445.42  4315.2   439.6  4612.6  426.04  4712.4  420.82  4766.2  417.28
  4771.6  419.37  4824.9  418.87  4848.9  415.57  4872.8  418.51  4920.7  418.14
  4922.9   416.6  4926.1  414.36  4950.1  416.26  4955.5  412.94    4974  416.21
  4979.4  413.38    4987     414  5005.8     411  5008.5   410.5  5011.8     411
  5032.7  418.16  5163.3  420.34  5224.3  423.48  5432.9  432.48  5521.6  433.83
  5561.6  431.77  5617.6  435.77    5677  437.43  5828.6   441.2  5837.9  441.61
#Mann= 12 ,-1 , 0
    4080     .05       0  4315.2     .16       0  4612.6     .12       0
  4712.4     .16       0  4922.9     .12       0  5005.8     .07       0
  5011.8     .12       0  5224.3     .16       0  5432.9     .12       0
  5617.6     .16       0    5677     .12       0  5828.6     .16       0
Bank Sta=5005.8,5011.8
XS Rating Curve= 0 ,0
Exp/Cntr=0.3,0.1

Type RM Length L Ch R = 1 ,17674   ,169,169,169
BEGIN DESCRIPTION:
UNT0081 IN CHRS 27.0
END DESCRIPTION:
XS GIS Cut Line= 4
       3487080.9     10559485.16      3486646.83     10559493.84
      3486256.21     10559524.23      3485583.45     10559945.25
#Sta/Elev= 30
  4282.6  441.89  4315.7  440.72  4401.4  438.24  4587.9  431.18  4749.7  422.86
  4861.9  418.02  4937.8  416.23  4972.3  415.01  4982.3   412.8  4992.3  407.77
  4999.3  406.72  5002.1  406.22  5005.3  406.72  5009.1   409.1  5022.4  413.19
  5042.5  414.58  5110.8  413.29  5116.2  414.48  5146.9  415.31  5189.3  415.21
  5262.4  417.07  5341.4  417.62  5429.8  420.13  5493.5  423.42  5512.1  423.66
  5676.2  429.52  5718.6  432.17  5770.5  433.32  5849.5  436.94  5902.2  438.48
#Mann= 7 ,-1 , 0
  4282.6     .05       0  4315.7     .16       0  4587.9     .05       0
  4937.8     .16       0  4999.3     .07       0  5005.3     .16       0
  5512.1     .05       0
Bank Sta=4999.3,5005.3
XS Rating Curve= 0 ,0
Exp/Cntr=0.3,0.1

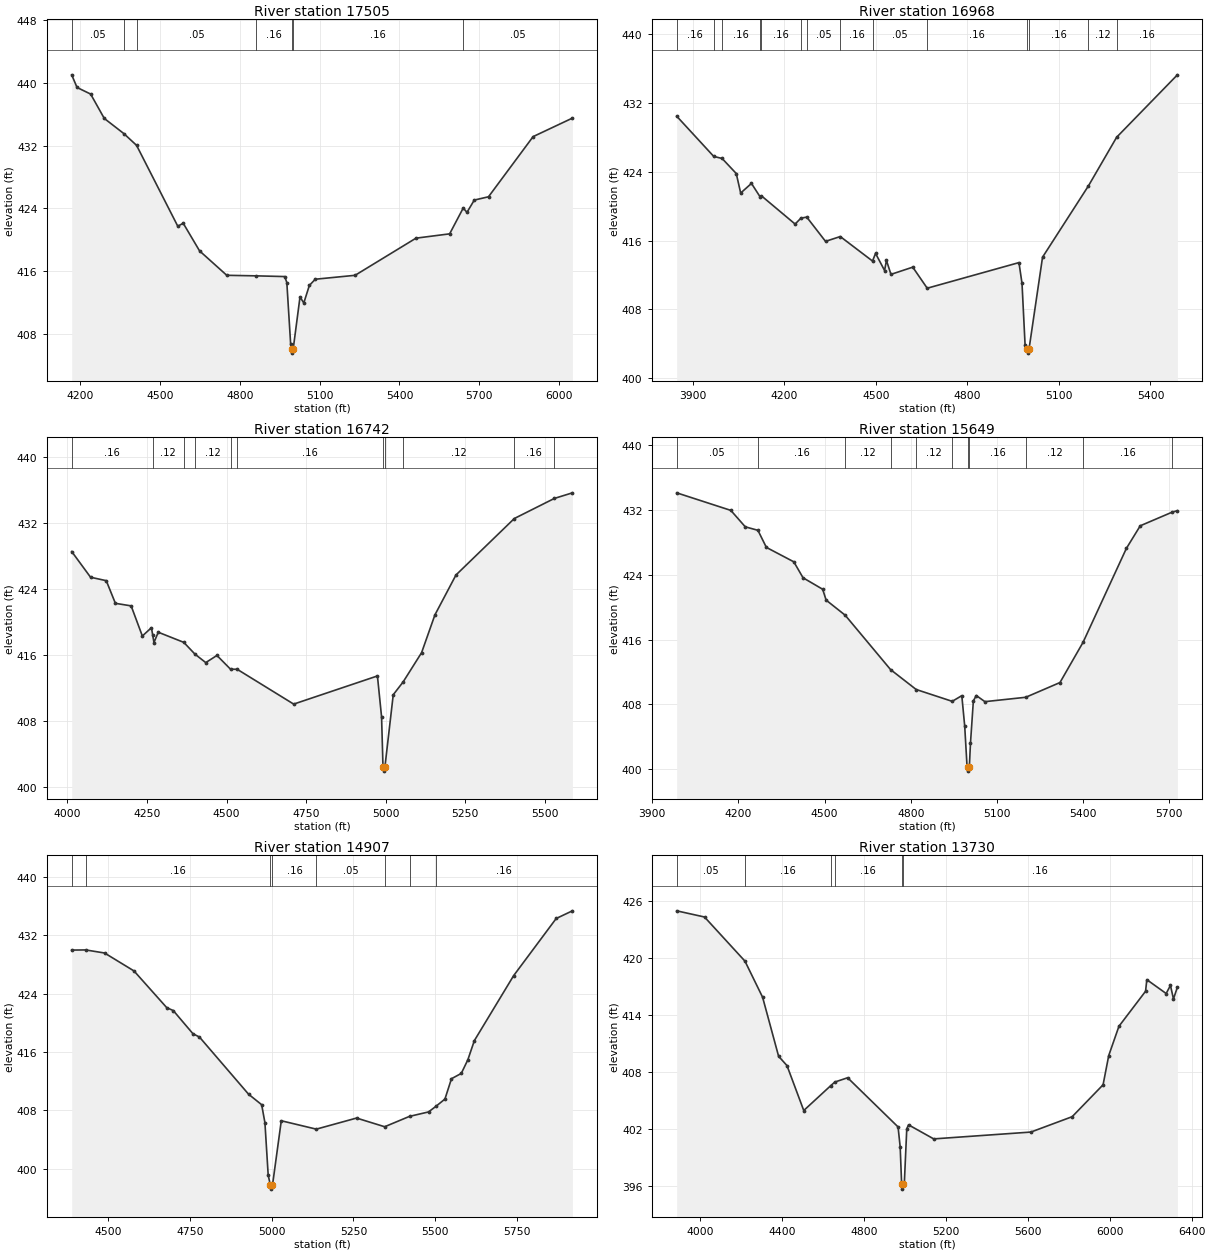
Type RM Length L Ch R = 1 ,17505   ,537,537,537
BEGIN DESCRIPTION:
UNT0081 IN CHRS 26.0
END DESCRIPTION:
XS GIS Cut Line= 4
      3487141.65     10559385.34      3486512.29     10559250.79
      3486238.85     10559476.48      3485470.62     10559910.51
#Sta/Elev= 30
  4169.1     441  4189.1  439.39  4240.2  438.55  4291.4  435.45  4364.8  433.52
  4412.7  432.02  4567.5  421.72  4587.9   422.1  4649.3  418.58  4751.5  415.47
  4862.3   415.4  4969.1  415.31    4977  414.55  4991.3  406.76  4994.8  406.06
  4997.6  405.56  5000.8  406.06  5026.5  412.71  5040.8  411.95  5061.6  414.18
  5083.8  414.97  5233.4  415.47  5462.1   420.2  5588.5  420.75  5639.4  424.03
  5653.6  423.49    5681  425.05  5734.4  425.47  5901.9  433.13  6049.6  435.49
#Mann= 7 ,-1 , 0
  4169.1     .05       0  4364.8     .16       0  4412.7     .05       0
  4862.3     .16       0  4994.8     .07       0  5000.8     .16       0
  5639.4     .05       0
Bank Sta=4994.8,5000.8
XS Rating Curve= 0 ,0
Exp/Cntr=0.3,0.1

Type RM Length L Ch R = 1 ,16968   ,226,226,226
BEGIN DESCRIPTION:
UNT0081 IN CHRS 25.0
END DESCRIPTION:
XS GIS Cut Line= 5
      3487322.59       10558398.      3486814.76     10558791.24
      3486476.21     10559030.83      3486187.15     10559002.18
      3485908.49     10558911.03
#Sta/Elev= 30
  3847.6  430.47    3969  425.79  3996.5  425.55  4042.8   423.8  4057.3  421.53
  4092.6  422.65  4121.4  421.06  4125.5   421.2  4235.7  417.92  4254.6  418.61
  4273.8  418.73  4335.3  415.91  4383.6  416.47  4489.3  413.62  4499.2  414.51
  4528.8  412.52  4534.9   413.7  4549.7  412.07  4621.1  412.91  4668.5  410.46
  4969.1  413.44  4979.1  411.03  4989.2  403.84  4996.2  403.41    4999  402.91
  5002.2  403.41  5046.4  414.07  5196.7  422.36  5289.2  428.02  5488.3  435.28
#Mann= 14 ,-1 , 0
  3847.6     .16       0    3969     .05       0  3996.5     .16       0
  4121.4     .05       0  4125.5     .16       0  4254.6     .12       0
  4273.8     .05       0  4383.6     .16       0  4489.3     .05       0
  4668.5     .16       0  4996.2     .07       0  5002.2     .16       0
  5196.7     .12       0  5289.2     .16       0
Bank Sta=4996.2,5002.2
XS Rating Curve= 0 ,0
Exp/Cntr=0.3,0.1

Type RM Length L Ch R = 1 ,16742   ,1093,1093,1093
BEGIN DESCRIPTION:
UNT0081 IN CHRS 24.0
END DESCRIPTION:
XS GIS Cut Line= 4
      3487301.72     10558338.13      3486895.49     10558674.05
      3486543.92     10558866.76      3485916.29     10558715.71
#Sta/Elev= 30
  4013.3  428.55  4072.5  425.43  4121.9  425.01  4150.6  422.26  4200.1  421.95
  4235.3  418.29  4263.9   419.3  4267.9  418.39  4271.8   417.5  4285.3  418.75
  4365.5  417.52  4400.6  416.09  4434.6  415.06  4469.7  415.93  4512.4  414.26
  4533.3  414.25  4710.9  410.02  4974.1  413.44  4987.1  408.47  4991.6  402.38
  4994.4  401.88  4997.6  402.38  5023.8  411.16    5055  412.72  5112.9  416.27
  5154.8  420.86  5220.9   425.7  5404.3  432.56  5530.1     435  5586.9  435.68
#Mann= 11 ,-1 , 0
  4013.3     .16       0  4267.9     .12       0  4365.5     .16       0
  4400.6     .12       0  4512.4     .05       0  4533.3     .16       0
  4991.6     .07       0  4997.6     .16       0    5055     .12       0
  5404.3     .16       0  5530.1     .12       0
Bank Sta=4991.6,4997.6
XS Rating Curve= 0 ,0
Exp/Cntr=0.3,0.1

Type RM Length L Ch R = 1 ,15649   ,742,742,742
BEGIN DESCRIPTION:
UNT0081 IN CHRS 22.0
END DESCRIPTION:
XS GIS Cut Line= 2
      3487839.69     10557885.77      3486105.34     10558059.21
#Sta/Elev= 30
  3985.1  434.13  4173.6  431.96  4223.9  429.93  4267.9   429.5  4297.3  427.39
  4392.8  425.61  4424.9  423.64  4493.3  422.22  4505.3  420.88  4571.5  419.02
  4729.6   412.3  4818.8  409.84  4944.2  408.38  4977.6  409.08  4987.7  405.32
  4995.8  400.36  4997.8  400.26  5000.5  399.76  5003.8  400.26  5007.8  403.23
  5017.8  408.43  5027.9   409.1    5058  408.34  5200.1  408.88  5319.3   410.7
  5399.7  415.67  5550.5  427.27  5598.8  430.06  5710.9  431.76  5728.1  431.92
#Mann= 11 ,-1 , 0
  3985.1     .05       0  4267.9     .16       0  4571.5     .12       0
  4729.6     .16       0  4818.8     .12       0  4944.2     .16       0
  4997.8     .07       0  5003.8     .16       0  5200.1     .12       0
  5399.7     .16       0  5710.9     .05       0
Bank Sta=4997.8,5003.8
XS Rating Curve= 0 ,0
Exp/Cntr=0.3,0.1

Type RM Length L Ch R = 1 ,14907   ,1177,1177,1177
BEGIN DESCRIPTION:
UNT0081 IN CHRS 20.0
END DESCRIPTION:
XS GIS Cut Line= 2
      3487492.46     10557310.68       3485962.5     10557321.54
#Sta/Elev= 30
    4389  429.98  4431.9     430  4489.4  429.58  4579.4  427.12  4679.4  422.09
  4699.4  421.69  4759.4  418.52  4779.4  418.06  4929.4  410.23  4969.4  408.79
  4979.4  406.33  4989.4  399.12  4996.4  397.72  4999.1  397.22  5002.4  397.72
  5029.4  406.59  5136.4  405.44  5259.4  406.96  5345.3  405.77  5421.2  407.19
  5479.4   407.8  5501.4  408.55  5529.4  409.56  5549.4  412.35  5579.4  413.08
  5599.4  414.94  5619.4  417.58  5739.4  426.48  5869.4  434.31    5919  435.36
#Mann= 8 ,-1 , 0
    4389     .05       0  4431.9     .16       0  4996.4     .07       0
  5002.4     .16       0  5136.4     .05       0  5345.3     .16       0
  5421.2     .12       0  5501.4     .16       0
Bank Sta=4996.4,5002.4
XS Rating Curve= 0 ,0
Exp/Cntr=0.3,0.1

Type RM Length L Ch R = 1 ,13730   ,1467,1467,1467
BEGIN DESCRIPTION:
UNT0081 IN CHRS 16.0
END DESCRIPTION:
XS GIS Cut Line= 3
      3488078.37     10556486.02      3486342.29     10556106.26
      3485799.88     10556496.79
#Sta/Elev= 30
    3885  424.96  4020.9  424.31  4218.5  419.66  4304.6  415.86  4382.8  409.64
  4423.7  408.66  4505.6  403.93  4637.5  406.55  4657.6  406.93  4719.9  407.38
  4966.2   402.2  4976.5   400.1  4983.7  396.15  4986.5  395.65  4989.7  396.15
  4996.9  396.33  5008.7     402  5017.4  402.42  5140.3  400.94  5614.9  401.66
  5816.6  403.28  5967.5  406.64  5995.1  409.72  6044.9   412.8    6175  416.49
  6181.1  417.71  6275.6  416.25  6296.5  417.11  6311.2  415.68  6330.5  416.92
#Mann= 6 ,-1 , 0
    3885     .05       0  4218.5     .16       0  4637.5     .12       0
  4657.6     .16       0  4983.7     .07       0  4989.7     .16       0
Bank Sta=4983.7,4989.7
XS Rating Curve= 0 ,0
Exp/Cntr=0.3,0.1