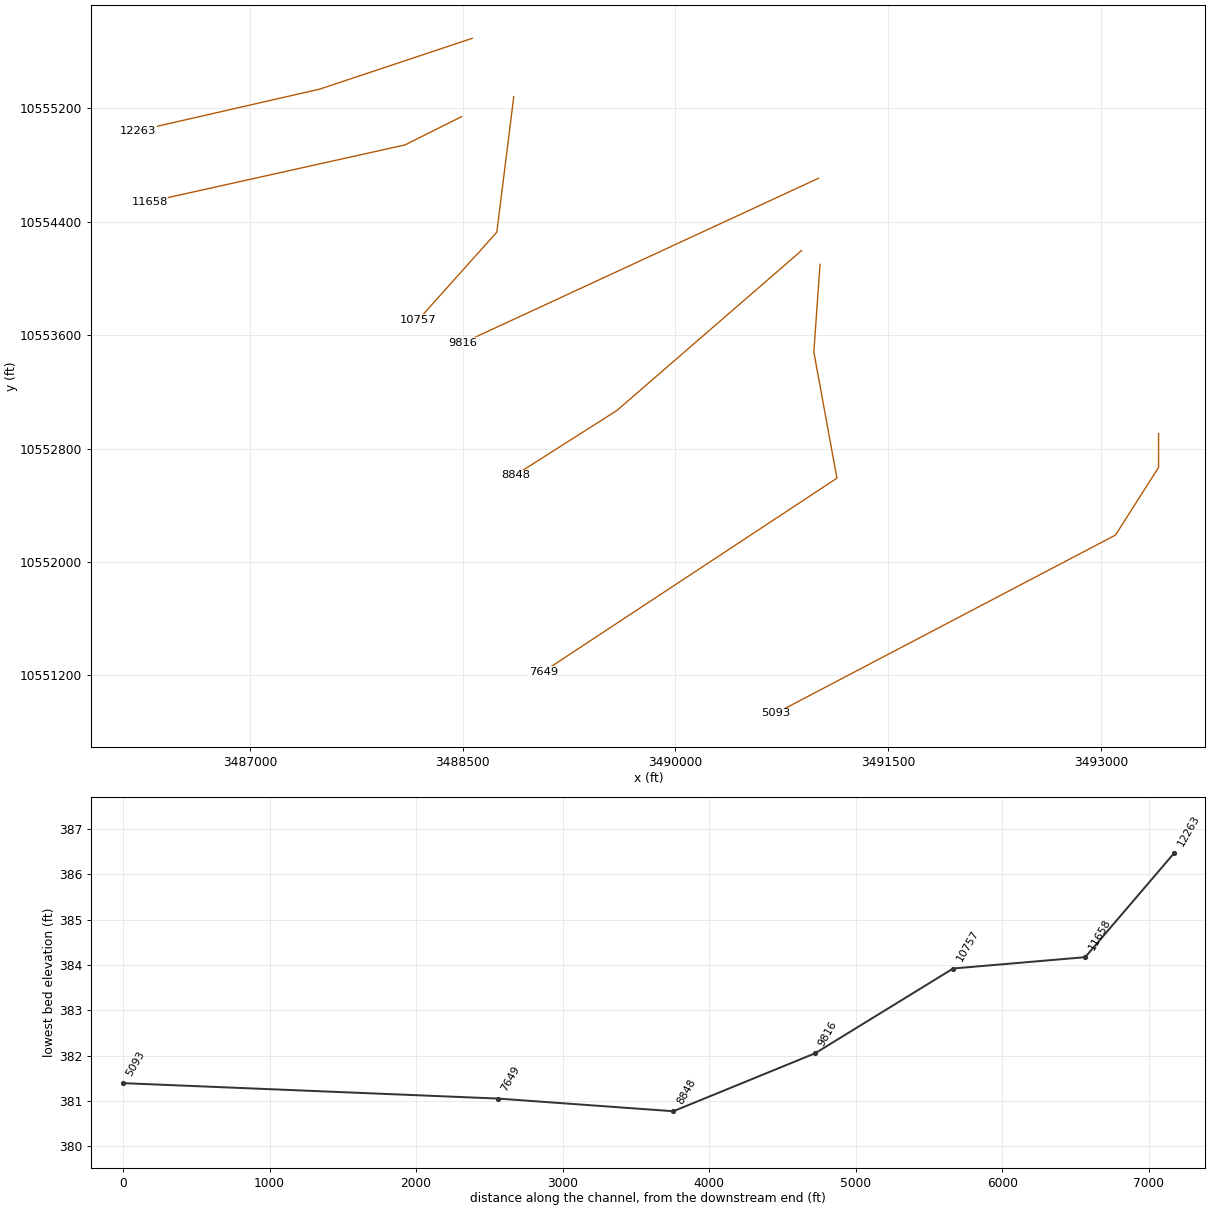
HEC-RAS study UNT0081 IN CHRS.prj: UNT0081 IN CHRS Base Level Engineering

--- UNT0081 IN CHRS.g01 (geometry) --- (continued)

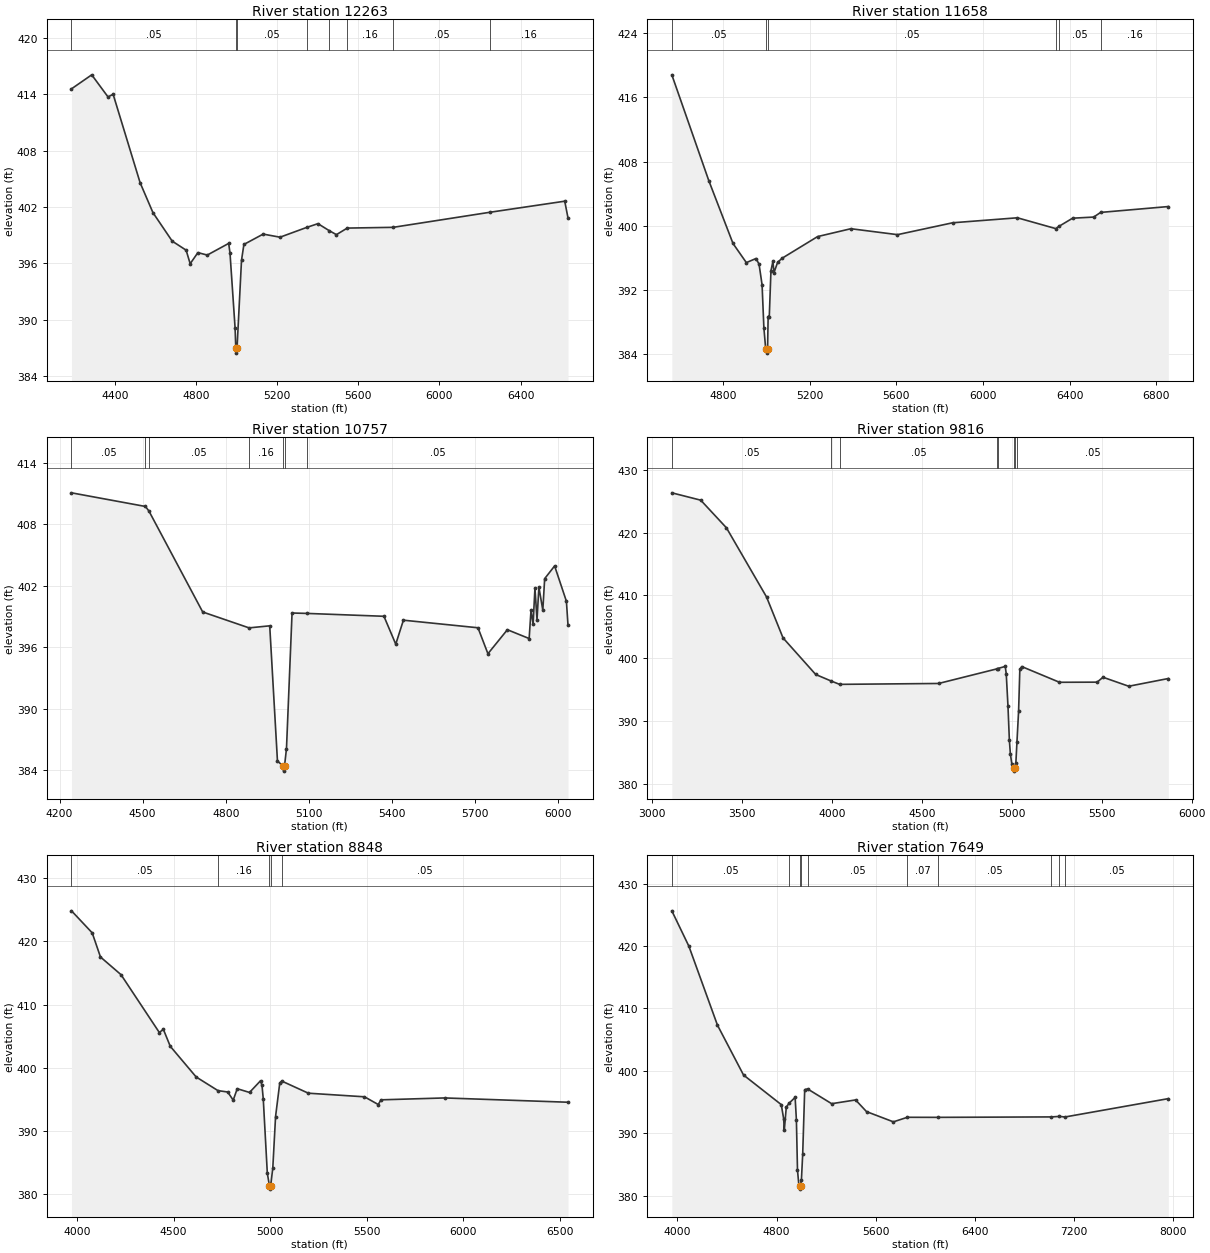
Type RM Length L Ch R = 1 ,12263   ,605,605,605
BEGIN DESCRIPTION:
UNT0081 IN CHRS 14.0
END DESCRIPTION:
XS GIS Cut Line= 3
      3488566.67     10555693.93      3487492.46     10555335.86
      3486212.07     10555042.89
#Sta/Elev= 30
  4187.2  414.57  4286.9  416.06  4367.1  413.71  4392.3  413.99  4525.3  404.58
  4588.5   401.4  4683.4  398.37  4751.9  397.41  4771.8  395.97  4809.9  397.15
  4856.1  396.89  4961.5  398.13    4968  397.11  4993.1  389.13  4996.6  386.96
  4999.3  386.46  5002.6  386.96  5024.7  396.33  5036.5  398.02  5131.4  399.12
  5214.5  398.79  5345.8  399.83  5401.2  400.23  5455.8   399.5  5492.2  399.06
  5545.6  399.76  5771.9  399.84  6247.7  401.44  6616.9  402.62    6633  400.84
#Mann= 8 ,-1 , 0
  4187.2     .05       0  4996.6    .035       0  5002.6     .05       0
  5345.8     .16       0  5455.8     .05       0  5545.6     .16       0
  5771.9     .05       0  6247.7     .16       0
Bank Sta=4996.6,5002.6
XS Rating Curve= 0 ,0
Exp/Cntr=0.3,0.1

Type RM Length L Ch R = 1 ,11658   ,901,901,901
BEGIN DESCRIPTION:
UNT0081 IN CHRS 13.0
END DESCRIPTION:
XS GIS Cut Line= 3
      3488492.07     10555141.62      3488092.11     10554941.64
      3486292.08     10554541.64
#Sta/Elev= 30
  4564.6  418.82  4735.1  405.65  4846.9  397.82  4908.4  395.44  4953.1  395.95
    4967  395.25    4981  392.69  4989.4   387.3  4997.8  384.67  5000.4  384.67
  5003.1  384.17  5006.4  384.67    5009  388.73  5014.3  388.73    5022  394.43
    5031  395.59  5036.1   394.2  5052.7  395.47  5073.2  395.98  5237.1  398.68
  5390.8  399.66  5605.9  398.92  5860.7   400.4  6159.1  401.02  6336.7  399.67
    6350  399.94  6413.9  400.97  6511.2  401.11  6543.2  401.69  6855.7  402.42
#Mann= 6 ,-1 , 0
  4564.6     .05       0  5000.4    .035       0  5006.4     .05       0
  6336.7     .16       0    6350     .05       0  6543.2     .16       0
Bank Sta=5000.4,5006.4
XS Rating Curve= 0 ,0
Exp/Cntr=0.3,0.1

Type RM Length L Ch R = 1 ,10757   ,941,941,941
BEGIN DESCRIPTION:
UNT0081 IN CHRS 11.0
END DESCRIPTION:
XS GIS Cut Line= 3
      3488859.65     10555281.62      3488740.29     10554326.74
      3488186.99     10553708.35
#Sta/Elev= 30
  4243.2  411.06  4510.1  409.73  4522.6  409.29  4716.8  399.44  4884.1  397.89
  4958.7  398.09  4986.6  384.92  5006.1  384.42  5008.8  383.92  5012.1  384.42
  5019.2  386.12  5039.3  399.34  5094.1   399.3    5371  399.02  5413.6   396.3
  5441.2  398.64  5710.4   397.9  5746.3  395.37  5816.5  397.71  5895.1  396.85
  5901.8   399.6  5909.3  398.27    5916  401.76  5923.5   398.7  5930.2  401.87
  5944.4  399.62  5951.1  402.69    5987  403.93  6029.6  400.48  6035.3  398.15
#Mann= 7 ,-1 , 0
  4243.2     .05       0  4510.1     .16       0  4522.6     .05       0
  4884.1     .16       0  5006.1     .07       0  5012.1     .16       0
  5094.1     .05       0
Bank Sta=5006.1,5012.1
XS Rating Curve= 0 ,0
Exp/Cntr=0.3,0.1

Type RM Length L Ch R = 1 ,9816    ,968,968,968
BEGIN DESCRIPTION:
UNT0081 IN CHRS 10.0
END DESCRIPTION:
XS GIS Cut Line= 2
       3491008.1     10554706.52      3488502.81     10553546.07
#Sta/Elev= 30
  3109.3  426.31  3270.1  425.14  3413.1  420.74  3635.9  409.75  3727.6  403.24
  3909.4  397.42  3993.6   396.4  4042.2  395.85  4592.7  395.99  4919.4  398.33
  4921.6  398.37  4963.3   398.7  4968.9  397.53  4978.4  392.47  4986.3  386.97
  4991.8  384.81  5000.4  383.11  5011.7  382.55  5014.4  382.05  5017.7  382.55
  5022.5   383.4  5028.6  386.76  5037.6   391.6  5044.5  398.22    5055  398.68
  5264.9  396.18  5474.3   396.2    5507  396.98    5650  395.55  5870.3  396.78
#Mann= 8 ,-1 , 0
  3109.3     .05       0  3993.6     .16       0  4042.2     .05       0
  4919.4     .16       0  4921.6     .12       0  5011.7     .07       0
  5017.7     .12       0  5028.6     .05       0
Bank Sta=5011.7,5017.7
XS Rating Curve= 0 ,0
Exp/Cntr=0.3,0.1

Type RM Length L Ch R = 1 ,8848    ,1199,1199,1199
BEGIN DESCRIPTION:
UNT0081 IN CHRS 7.0
END DESCRIPTION:
XS GIS Cut Line= 3
      3490888.71     10554196.51      3489586.65     10553068.06
      3488870.47     10552612.31
#Sta/Elev= 30
  3971.1  424.84  4078.4  421.35  4121.2  417.53  4227.6  414.73  4426.1  405.57
  4446.9  406.08  4482.7  403.39  4616.9  398.53  4729.8  396.37  4780.3  396.15
  4808.8  394.86  4829.7  396.67  4893.3  396.08  4950.3  397.93  4957.9   397.2
  4964.5  395.06  4985.5  383.28  4996.7  381.27  4999.4  380.77  5002.7  381.27
  5013.9  384.14  5028.2  392.27    5050  397.59  5060.4  397.88  5198.1  395.96
  5488.8  395.39    5560  394.17  5574.3  394.91  5904.3  395.21    6543  394.53
#Mann= 5 ,-1 , 0
  3971.1     .05       0  4729.8     .16       0  4996.7     .07       0
  5002.7     .16       0  5060.4     .05       0
Bank Sta=4996.7,5002.7
XS Rating Curve= 0 ,0
Exp/Cntr=0.3,0.1

Type RM Length L Ch R = 1 ,7649    ,2556,2556,2556
BEGIN DESCRIPTION:
UNT0081 IN CHRS 3.0
END DESCRIPTION:
XS GIS Cut Line= 4
      3491018.94      10554098.9      3490975.54     10553480.39
       3491138.3     10552590.63      3489066.46     10551223.87
#Sta/Elev= 30
    3955  425.64  4092.6  419.97  4323.2  407.32  4533.7  399.33  4838.1  394.59
  4857.5  392.31  4862.5   390.5  4878.7  394.19  4901.9  394.83  4949.9  395.75
  4960.1  392.18    4969  384.11  4980.4  381.62  4987.6  381.55  4990.3  381.05
  4993.6  381.55  5000.7  382.54  5010.9  386.61  5027.2  396.98    5050  397.11
  5244.7  394.74  5437.9  395.34    5526  393.47  5742.8  391.83  5855.7  392.56
  6100.1  392.55  7016.5  392.62  7082.9   392.7    7128  392.61  7961.6  395.55
#Mann= 10 ,-1 , 0
    3955     .05       0  4901.9     .16       0  4987.6     .07       0
  4993.6     .16       0    5050     .05       0  5855.7     .07       0
  6100.1     .05       0  7016.5     .07       0  7082.9     .16       0
    7128     .05       0
Bank Sta=4987.6,4993.6
XS Rating Curve= 0 ,0
Exp/Cntr=0.3,0.1

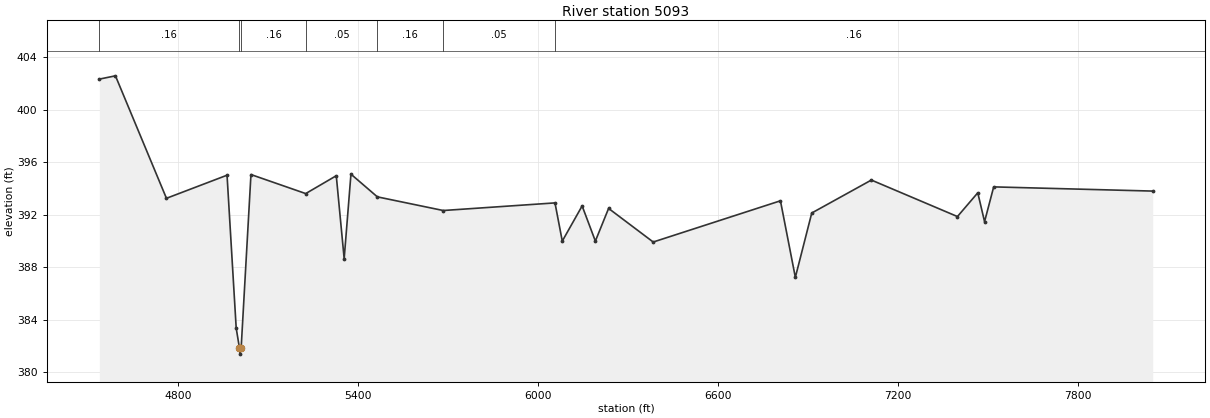
Type RM Length L Ch R = 1 ,5093    ,0,0,0
BEGIN DESCRIPTION:
UNT0081 IN CHRS 1.0
END DESCRIPTION:
XS GIS Cut Line= 4
      3493406.09     10552905.33      3493406.09     10552666.59
      3493102.27     10552189.16       3490705.7     10550931.23
#Sta/Elev= 30
  4537.3  402.34    4591  402.59    4761  393.26    4963  395.02  4993.5  383.37
  5004.1  381.89  5006.9  381.39  5010.1  381.89  5042.7  395.07  5225.2  393.62
  5327.1  394.98  5353.4  388.66    5376   395.1    5464  393.37  5683.6  392.33
  6056.1  392.91  6080.4     390  6146.6  392.68  6190.7     390  6234.8  392.49
  6383.5  389.93  6807.6  393.07  6857.3  387.24    6912  392.14  7110.7  394.65
  7397.6  391.87  7465.4  393.68    7488  391.48  7518.4  394.13  8048.6  393.81
#Mann= 7 ,-1 , 0
  4537.3     .16       0  5004.1     .07       0  5010.1     .16       0
  5225.2     .05       0    5464     .16       0  5683.6     .05       0
  6056.1     .16       0
Bank Sta=5004.1,5010.1
XS Rating Curve= 0 ,0
Exp/Cntr=0.3,0.1
Stream Node=UNT0081 IN CHRS ,Reach-1         , 0 , 0 ,Upstream end
Stream Node=UNT0081 IN CHRS ,Reach-1         , 0 , 1 ,Downstream end

Chan Stop Cuts=-1
Use User Specified Reach Order=0
Composite Channel Slope=5