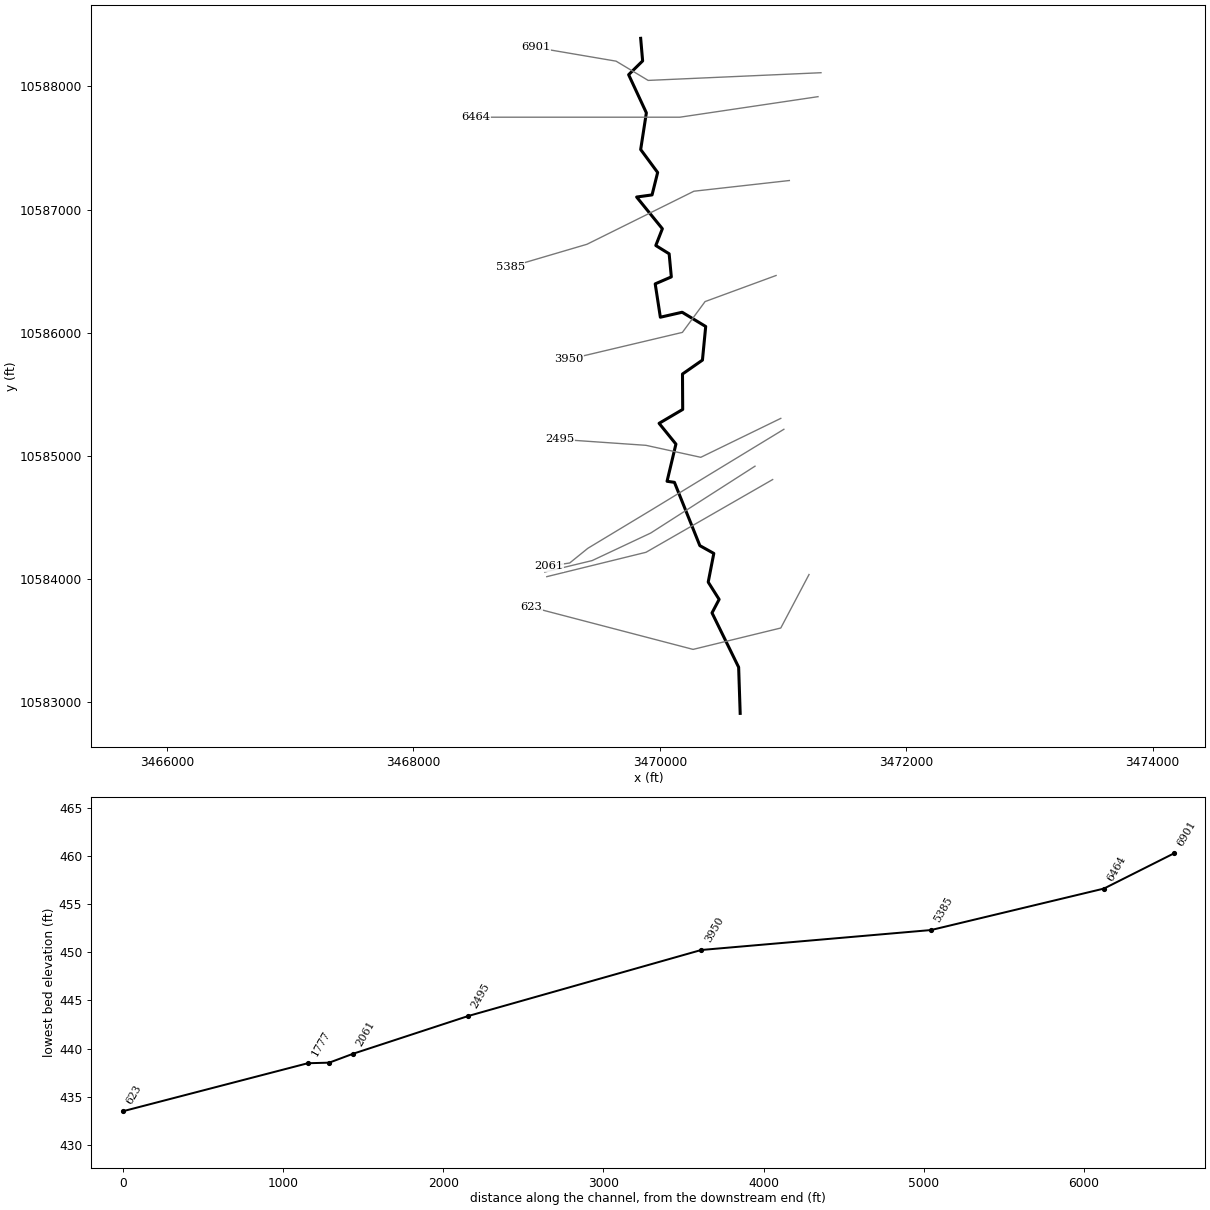
--- UNT00822 IN CHRS.prj (project) ---

Proj Title=UNT00822 IN CHRS Base Level Engineering
Current Plan=p01
Default Exp/Contr=0.3,0.1
English Units
Geom File=g01
Flow File=f01
Plan File=p01
Y Axis Title=Elevation
X Axis Title(PF)=Main Channel Distance
X Axis Title(XS)=Station
BEGIN DESCRIPTION:
UNT00822 IN CHRS
END DESCRIPTION:
DSS Export Rating Curves= 0
DSS Export Rating Curve Sorted= 0
DSS Export Volume Flow Curves= 0
DXF OffsetX= 0
DXF OffsetY= 0
DXF ScaleX= 1
DXF ScaleY= 10

--- UNT00822 IN CHRS.p01 (plan) ---

Plan Title=Multiple Run
Short Identifier=Multiple
Geom File=g01
Flow File=f01
Subcritical Flow
K Sum by GR= 0
Std Step Tol= 0.01
Critical Tol= 0.01
Num of Std Step Trials= 20
Max Error Tol= 0.3
Flow Tol Ratio= 0.001
Split Flow NTrial= 30
Split Flow Tol= 0.02
Split Flow Ratio= 0.02
Log Output Level= 0
Friction Slope Method= 1
Unsteady Friction Slope Method= 2
Unsteady Bridges Friction Slope Method= 1
Parabolic Critical Depth
Global Vel Dist=  1 , 1 , 1
Global Log Level= 0
CheckData=True
Encroach Param= -1, 0, 0, 0
BEGIN DESCRIPTION:
Multiple Run
END DESCRIPTION:

--- UNT00822 IN CHRS.f01 (steady flow) ---

Flow Title=Multiple
Number of Profiles=7
Profile Names=10-year,25-year,50-year,1pct_min,100-year,1pct_plu,500-year
River Rch & RM= UNT00822 IN CHRS,Reach-1,6901
     357     442     504     418     566     765     711
River Rch & RM= UNT00822 IN CHRS,Reach-1,3950
     450     563     647     540     730     988     929
Boundary for River Rch & Prof#=UNT00822 IN CHRS,Reach-1,1
Up Type=0
Dn Type=3
Dn Slope=0.005
Boundary for River Rch & Prof#=UNT00822 IN CHRS,Reach-1,2
Up Type=0
Dn Type=3
Dn Slope=0.005
Boundary for River Rch & Prof#=UNT00822 IN CHRS,Reach-1,3
Up Type=0
Dn Type=3
Dn Slope=0.005
Boundary for River Rch & Prof#=UNT00822 IN CHRS,Reach-1,4
Up Type=0
Dn Type=3
Dn Slope=0.005
Boundary for River Rch & Prof#=UNT00822 IN CHRS,Reach-1,5
Up Type=0
Dn Type=3
Dn Slope=0.005
Boundary for River Rch & Prof#=UNT00822 IN CHRS,Reach-1,6
Up Type=0
Dn Type=3
Dn Slope=0.005
Boundary for River Rch & Prof#=UNT00822 IN CHRS,Reach-1,7
Up Type=0
Dn Type=3
Dn Slope=0.005

--- UNT00822 IN CHRS.g01 (geometry) ---

Geom Title=Existing Conditions
Program Version=4.10

River Reach=UNT00822 IN CHRS,Reach-1
Reach XY= 30
      3469844.39     10588390.51       3469860.3     10588207.22
      3469746.72     10588095.29      3469890.63     10587785.93
      3469844.49     10587488.06      3469982.18     10587301.74
      3469936.88     10587119.75      3469811.61     10587102.51
      3470020.47     10586845.22      3469967.19     10586708.99
       3470075.5     10586641.73       3470093.2     10586454.25
      3469962.41     10586397.61      3470004.15     10586127.02
      3470181.26     10586167.34      3470372.21     10586051.78
      3470345.74     10585779.01      3470183.86     10585665.92
      3470185.48     10585378.51       3469993.9     10585265.66
       3470130.5     10585097.24      3470058.61     10584795.42
      3470118.51     10584786.74      3470324.74     10584273.08
      3470438.02     10584209.86       3470392.6     10583977.01
      3470481.18     10583836.78       3470423.5     10583727.19
      3470639.57      10583286.1      3470652.11     10582911.64

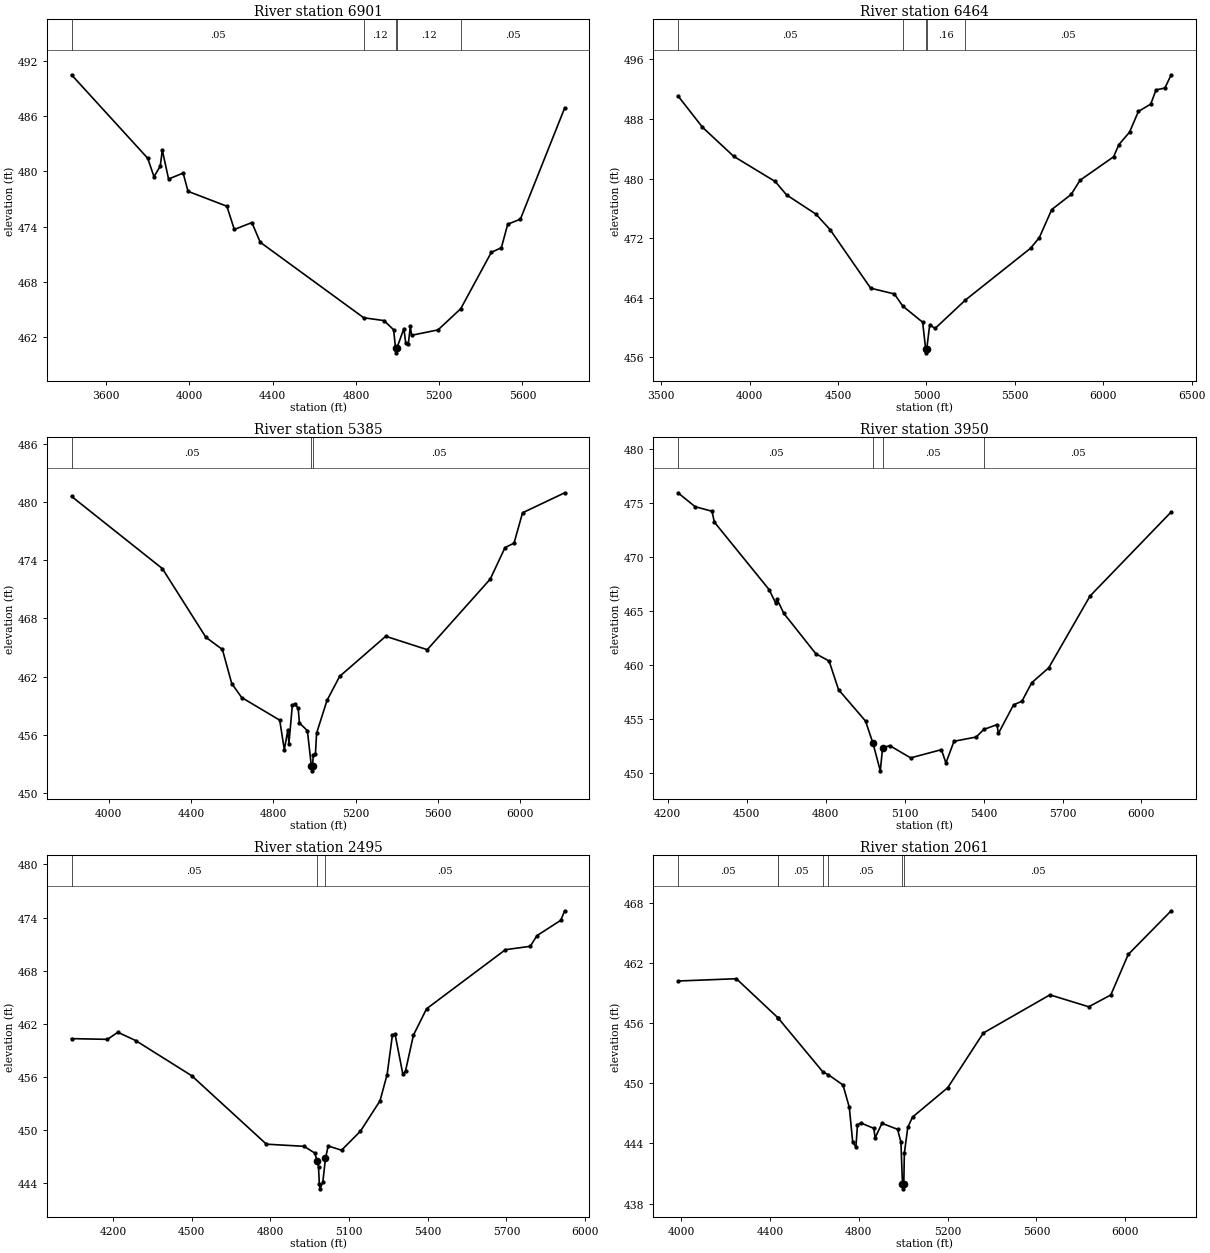
Type RM Length L Ch R = 1 ,6901    ,437,437,437
BEGIN DESCRIPTION:
UNT00822 IN CHRS 3.0
END DESCRIPTION:
XS GIS Cut Line= 4
      3471307.99     10588111.49      3469905.26       10588049.
      3469644.85     10588205.25      3468992.05     10588316.36
#Sta/Elev= 30
  3433.1  490.52  3799.4  481.43  3829.4  479.42  3859.4  480.57  3869.4  482.31
  3899.5  479.17  3969.5  479.82    3993  477.83  4179.7  476.21  4215.4  473.68
  4299.8  474.43  4339.9  472.29  4837.2  464.07  4934.9  463.76  4980.8  462.76
  4990.2  460.75    4993  460.25  4996.2  460.75  5030.2  462.89  5039.2  461.29
  5051.5  461.23  5061.3  463.15  5067.1  462.16  5194.4  462.75  5303.3  465.05
  5450.1  471.18  5498.7   471.7  5529.2  474.25    5590   474.8  5803.1  486.92
#Mann= 5 ,-1 , 0
  3433.1     .05       0  4837.2     .12       0  4990.2     .07       0
  4996.2     .12       0  5303.3     .05       0
Bank Sta=4990.2,4996.2
XS Rating Curve= 0 ,0
Exp/Cntr=0.3,0.1

Type RM Length L Ch R = 1 ,6464    ,1079,1079,1079
BEGIN DESCRIPTION:
UNT00822 IN CHRS 2.6
END DESCRIPTION:
XS GIS Cut Line= 4
      3471283.76     10587917.06      3470162.21     10587750.39
      3469544.15     10587750.39      3468506.57     10587750.39
#Sta/Elev= 30
  3594.6  491.11  3733.1   486.9  3909.7  482.99  4144.5  479.61  4208.8  477.81
  4374.7  475.23  4455.6  473.13  4684.5  465.28  4818.6  464.51  4866.1  462.88
  4978.6  460.71  4995.6   457.1  4998.3   456.6  5001.6   457.1  5018.6  460.39
  5048.6  459.87  5220.8   463.7  5588.6  470.64  5638.6  472.08  5708.6  475.84
  5818.6  477.87  5868.6  479.77  6058.6  482.93  6088.6  484.57  6148.6  486.23
  6198.6  489.01  6268.6  490.01  6298.6  491.91  6348.6  492.16  6384.1  493.94
#Mann= 5 ,-1 , 0
  3594.6     .05       0  4866.1     .16       0  4995.6     .07       0
  5001.6     .16       0  5220.8     .05       0
Bank Sta=4995.6,5001.6
XS Rating Curve= 0 ,0
Exp/Cntr=0.3,0.1

Type RM Length L Ch R = 1 ,5385    ,1435,1435,1435
BEGIN DESCRIPTION:
UNT00822 IN CHRS 2.5
END DESCRIPTION:
XS GIS Cut Line= 4
      3471051.13      10587236.5      3470276.79     10587149.69
      3469408.74     10586719.14      3468785.45     10586535.61
#Sta/Elev= 30
  3818.9  480.57  4260.7  473.13    4472  466.06  4552.5   464.8  4597.9  461.29
  4646.2  459.85  4831.1  457.52  4853.5  454.48  4870.3  456.47  4875.9  455.11
  4892.7   459.1  4904.7  459.16  4920.7  458.76    4927  457.23  4965.6  456.44
    4985   452.8  4987.7   452.3    4991   452.8    4994  453.91  5004.8  454.02
  5010.4  456.18    5061  459.55  5122.5  462.03  5346.6  466.16  5548.4  464.78
  5854.7  472.05  5926.6   475.3  5970.3  475.75  6011.8  478.88  6216.8  480.94
#Mann= 3 ,-1 , 0
  3818.9     .05       0    4985    .035       0    4991     .05       0
Bank Sta=4985,4991
XS Rating Curve= 0 ,0
Exp/Cntr=0.3,0.1

Type RM Length L Ch R = 1 ,3950    ,1455,1455,1455
BEGIN DESCRIPTION:
UNT00822 IN CHRS 2.4
END DESCRIPTION:
XS GIS Cut Line= 4
      3470943.46     10586465.66      3470367.07     10586253.86
      3470183.04     10586003.86       3469259.4      10585785.1
#Sta/Elev= 30
  4239.1  475.98  4304.5  474.69  4368.4  474.27  4377.5  473.26  4585.5  467.01
  4610.6  465.76    4616   466.1  4641.1  464.82    4763  461.07  4813.3   460.4
  4849.1  457.75  4951.7  454.84  4980.1  452.77  5007.8  450.23  5016.5  452.35
  5043.5  452.57    5123  451.43    5240  452.19  5257.1  450.96  5287.9  452.97
  5371.9  453.36  5400.9  454.06  5451.2  454.51  5456.4  453.69    5514  456.34
    5546  456.68  5583.1  458.39  5647.6  459.77  5804.6  466.42  6112.8   474.2
#Mann= 4 ,-1 , 0
  4239.1     .05       0  4980.1    .035       0  5016.5     .05       0
  5400.9     .05       0
Bank Sta=4980.1,5016.5
XS Rating Curve= 0 ,0
Exp/Cntr=0.3,0.1

Type RM Length L Ch R = 1 ,2495    ,718,718,718
BEGIN DESCRIPTION:
UNT00822 IN CHRS 2.3
END DESCRIPTION:
XS GIS Cut Line= 4
      3470981.67     10585305.95      3470332.35     10584989.97
       3469887.9     10585087.19      3469186.76     10585135.78
#Sta/Elev= 30
  4042.2  460.33  4179.2  460.25  4218.8  461.05  4286.4  460.12  4500.5  456.14
    4785  448.42  4928.4  448.18  4969.3  447.42  4978.6  446.55  4983.7  445.84
  4986.8  443.88  4989.5  443.38    5000  444.13  5010.2  446.82  5020.5  448.22
  5071.4  447.74  5143.3  449.88    5218  453.31  5245.1  456.28  5265.2   460.7
  5275.2  460.87  5305.3  456.29  5315.3  456.69  5345.4  460.72  5395.5   463.7
  5696.2  470.37  5790.7  470.75  5816.5  471.96  5906.7  473.68  5922.1  474.76
#Mann= 3 , 0 , 0
  4042.2     .05       0  4978.6    .035       0  5010.2     .05       0
Bank Sta=4978.6,5010.2
XS Rating Curve= 0 ,0
Exp/Cntr=0.3,0.1

Type RM Length L Ch R = 1 ,2061    ,150,150,150
BEGIN DESCRIPTION:
UNT00822 IN CHRS 2.9
END DESCRIPTION:
XS GIS Cut Line= 6
       3471006.7     10585217.37      3470396.88     10584846.27
      3469941.15     10584568.49      3469415.97     10584251.65
       3469268.4     10584132.29      3469100.41     10584106.44
#Sta/Elev= 30
  3986.1  460.21    4249  460.44  4436.8  456.53  4437.5  456.51  4638.7  451.14
  4663.6  450.85    4729  449.84  4757.6  447.61    4773  444.11  4787.5  443.65
  4794.4  445.87  4809.8  446.04  4867.9  445.51  4873.8  444.56  4904.6  446.01
  4974.9  445.41    4990  444.14    4997  439.97  4999.8  439.47    5003  439.97
  5005.4     443  5020.9  445.61  5042.2  446.63    5201  449.57    5361  455.02
    5661  458.83  5835.7  457.64  5935.1  458.82  6013.4  462.86  6206.8  467.22
#Mann= 7 ,-1 , 0
  3986.1     .05       0  4436.8     .08       0  4437.5     .05       0
  4638.7     .08       0  4663.6     .05       0    4997    .035       0
    5003     .05       0
Bank Sta=4997,5003
XS Rating Curve= 0 ,0
Exp/Cntr=0.3,0.1

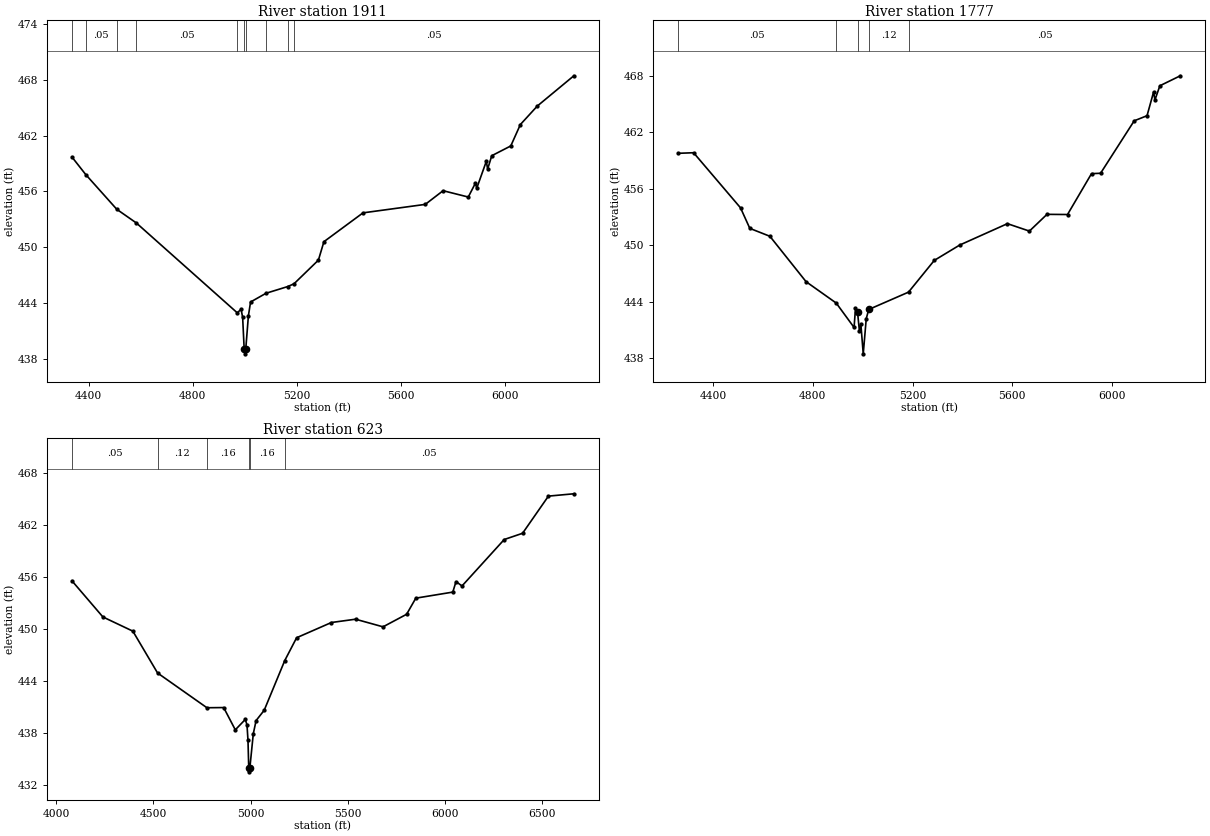
Type RM Length L Ch R = 1 ,1911    ,134,134,134
BEGIN DESCRIPTION:
UNT00822 IN CHRS 2.8
END DESCRIPTION:
XS GIS Cut Line= 4
      3470772.33     10584917.89      3469925.96     10584375.35
       3469450.7     10584151.82       3469065.8     10584058.84
#Sta/Elev= 30
  4335.9  459.69    4389   457.8  4508.1  454.07  4582.8  452.61  4970.4  442.95
  4985.1  443.33  4991.1  442.46    4997  439.04  4999.8  438.54    5003  439.04
  5013.2  442.63  5021.5  444.11  5080.9  445.05  5164.2  445.77  5188.3  446.07
  5281.9  448.61    5303  450.59  5453.1  453.69  5692.1   454.6  5760.5  456.07
  5857.2  455.39  5884.5  456.88  5889.6  456.33  5926.3  459.22  5931.5   458.4
  5947.3  459.83  6020.3  460.88  6057.1  463.18  6122.2  465.17  6262.4  468.42
#Mann= 10 ,-1 , 0
  4335.9     .08       0    4389     .05       0  4508.1     .08       0
  4582.8     .05       0  4970.4     .16       0    4997     .07       0
    5003     .16       0  5080.9     .05       0  5164.2     .16       0
  5188.3     .05       0
Bank Sta=4997,5003
XS Rating Curve= 0 ,0
Exp/Cntr=0.3,0.1

Type RM Length L Ch R = 1 ,1777    ,1154,1154,1154
BEGIN DESCRIPTION:
UNT00822 IN CHRS 2.2
END DESCRIPTION:
XS GIS Cut Line= 3
      3470915.67     10584809.41       3469887.9     10584219.14
      3469082.37     10584021.22
#Sta/Elev= 30
  4260.3  459.77  4321.2  459.83  4509.6  453.98  4546.9   451.8  4627.5  450.96
  4772.7  446.14  4893.8  443.87  4965.4  441.28  4971.1   443.3  4979.4   442.9
  4986.9  440.88  4992.7  441.62  5002.2  438.48  5014.3  442.22  5024.3  443.19
  5183.9  445.03  5287.4   448.4  5389.5  450.03  5580.9   452.3  5669.2  451.51
  5739.8  453.29  5822.2  453.27  5918.5  457.61  5954.9  457.65  6089.9  463.22
  6141.4  463.76  6167.8  466.29    6173  465.42  6192.9  466.94    6275     468
#Mann= 5 ,-1 , 0
  4260.3     .05       0  4893.8     .12       0  4979.4     .07       0
  5024.3     .12       0  5183.9     .05       0
Bank Sta=4979.4,5024.3
XS Rating Curve= 0 ,0
Exp/Cntr=0.3,0.1

Type RM Length L Ch R = 1 ,623     ,0,0,0
BEGIN DESCRIPTION:
UNT00822 IN CHRS 2.1
END DESCRIPTION:
XS GIS Cut Line= 4
      3471210.82     10584038.57      3470981.65     10583604.55
      3470269.85     10583430.94      3468955.52     10583774.26
#Sta/Elev= 30
  4080.7  455.55  4239.9  451.38    4394  449.74  4521.2  444.91    4775   440.9
  4861.2  440.92    4921  438.35  4972.5  439.55  4981.2  438.92  4986.3  437.13
  4990.1     434  4992.8   433.5  4996.1     434  5013.6   437.9    5028  439.42
  5069.7  440.61  5175.5  446.35  5236.4  448.98  5415.5  450.74  5539.6  451.12
    5681  450.24  5802.3  451.69  5849.6  453.55  6039.9  454.25  6056.3  455.46
  6087.3  454.96  6304.4  460.32  6398.8  461.04  6531.8  465.33  6662.6   465.6
#Mann= 6 ,-1 , 0
  4080.7     .05       0  4521.2     .12       0    4775     .16       0
  4990.1     .07       0  4996.1     .16       0  5175.5     .05       0
Bank Sta=4990.1,4996.1
XS Rating Curve= 0 ,0
Exp/Cntr=0.3,0.1

Chan Stop Cuts=-1
Use User Specified Reach Order=0
Composite Channel Slope=5