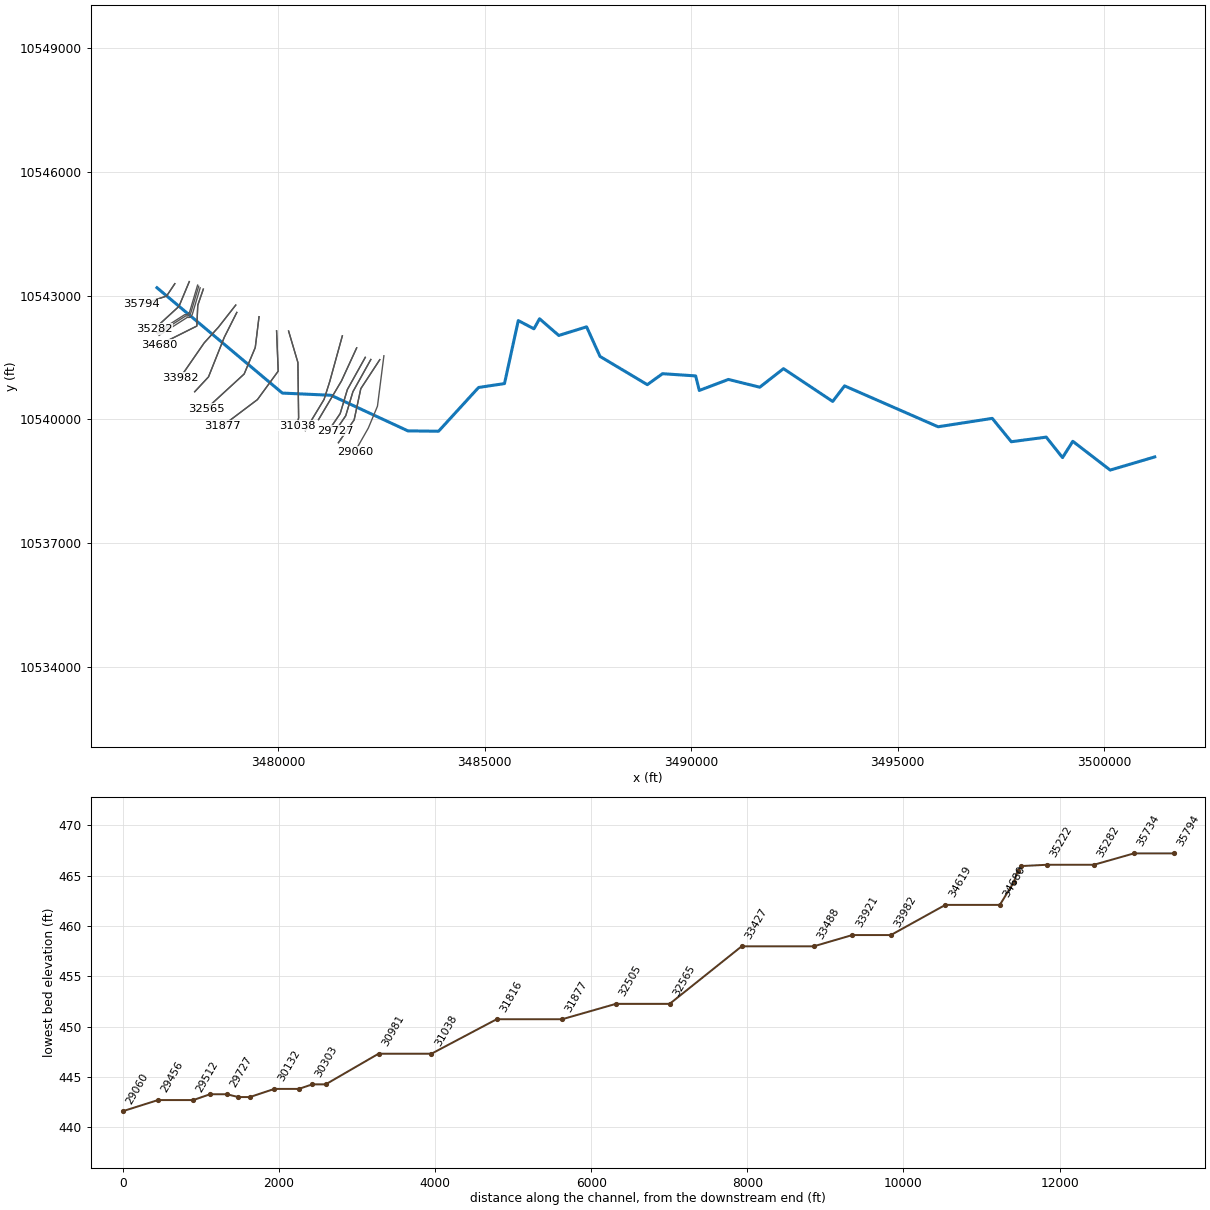
--- UNT0083 IN CHRS.prj (project) ---

Proj Title=UNT0083 IN CHRS Base Level Engineering
Current Plan=p01
Default Exp/Contr=0.3,0.1
English Units
Geom File=g01
Flow File=f01
Plan File=p01
Y Axis Title=Elevation
X Axis Title(PF)=Main Channel Distance
X Axis Title(XS)=Station
BEGIN DESCRIPTION:
UNT0083 IN CHRS
END DESCRIPTION:
DSS Export Rating Curves= 0
DSS Export Rating Curve Sorted= 0
DSS Export Volume Flow Curves= 0
DXF OffsetX= 0
DXF OffsetY= 0
DXF ScaleX= 1
DXF ScaleY= 10

--- UNT0083 IN CHRS.p01 (plan) ---

Plan Title=Multiple Run
Short Identifier=Multiple
Geom File=g01
Flow File=f01
Subcritical Flow
K Sum by GR= 0
Std Step Tol= 0.01
Critical Tol= 0.01
Num of Std Step Trials= 20
Max Error Tol= 0.3
Flow Tol Ratio= 0.001
Split Flow NTrial= 30
Split Flow Tol= 0.02
Split Flow Ratio= 0.02
Log Output Level= 0
Friction Slope Method= 1
Unsteady Friction Slope Method= 2
Unsteady Bridges Friction Slope Method= 1
Parabolic Critical Depth
Global Vel Dist=  1 , 1 , 1
Global Log Level= 0
CheckData=True
Encroach Param= -1, 0, 0, 0
BEGIN DESCRIPTION:
Multiple Run
END DESCRIPTION:

--- UNT0083 IN CHRS.f01 (steady flow) ---

Flow Title=Multiple
Number of Profiles=7
Profile Names=10-year,25-year,50-year,1pct_min,100-year,1pct_plu,500-year
River Rch & RM= UNT0083 IN CHRS,Reach-1,35794
     220     265     295     241     325     440     393
River Rch & RM= UNT0083 IN CHRS,Reach-1,32565
     339     417     473     390     528     714     656
River Rch & RM= UNT0083 IN CHRS,Reach-1,29875
     471     589     675     563     761    1029     965
River Rch & RM= UNT0083 IN CHRS,Reach-1,23019
     769     983    1143     966    1306    1766    1700
River Rch & RM= UNT0083 IN CHRS,Reach-1,13890
     939    1211    1417    1202    1626    2198    2136
River Rch & RM= UNT0083 IN CHRS,Reach-1,8429
    1092    1416    1663    1416    1915    2589    2533
Boundary for River Rch & Prof#=UNT0083 IN CHRS,Reach-1,1
Up Type=0
Dn Type=3
Dn Slope=0.005
Boundary for River Rch & Prof#=UNT0083 IN CHRS,Reach-1,2
Up Type=0
Dn Type=3
Dn Slope=0.005
Boundary for River Rch & Prof#=UNT0083 IN CHRS,Reach-1,3
Up Type=0
Dn Type=3
Dn Slope=0.005
Boundary for River Rch & Prof#=UNT0083 IN CHRS,Reach-1,4
Up Type=0
Dn Type=3
Dn Slope=0.005
Boundary for River Rch & Prof#=UNT0083 IN CHRS,Reach-1,5
Up Type=0
Dn Type=3
Dn Slope=0.005
Boundary for River Rch & Prof#=UNT0083 IN CHRS,Reach-1,6
Up Type=0
Dn Type=3
Dn Slope=0.005
Boundary for River Rch & Prof#=UNT0083 IN CHRS,Reach-1,7
Up Type=0
Dn Type=3
Dn Slope=0.005

--- UNT0083 IN CHRS.g01 (geometry) ---

Geom Title=Existing Conditions
Program Version=4.10

River Reach=UNT0083 IN CHRS ,Reach-1
Reach XY= 30
      3477059.07     10543193.44      3480096.44     10540639.51
      3481276.13     10540586.13      3483138.01     10539723.07
      3483880.91      10539714.4       3484850.7      10540775.5
      3485478.21     10540869.49       3485812.3     10542396.96
      3486192.28      10542197.8      3486327.14     10542441.33
      3486793.23     10542036.49      3487467.61     10542245.52
      3487792.26      10541528.5      3488937.73     10540843.66
      3489306.73     10541109.33      3490109.25     10541055.57
      3490197.52     10540703.08      3490902.27     10540970.38
      3491662.11     10540781.64      3492236.95     10541231.53
      3493428.57     10540437.24      3493717.24     10540814.22
      3495982.24     10539822.81      3497294.55     10540026.21
       3497755.7      10539459.8      3498602.11     10539571.64
       3498997.1     10539075.35      3499246.02     10539469.99
      3500151.54     10538772.59      3501231.61     10539091.76

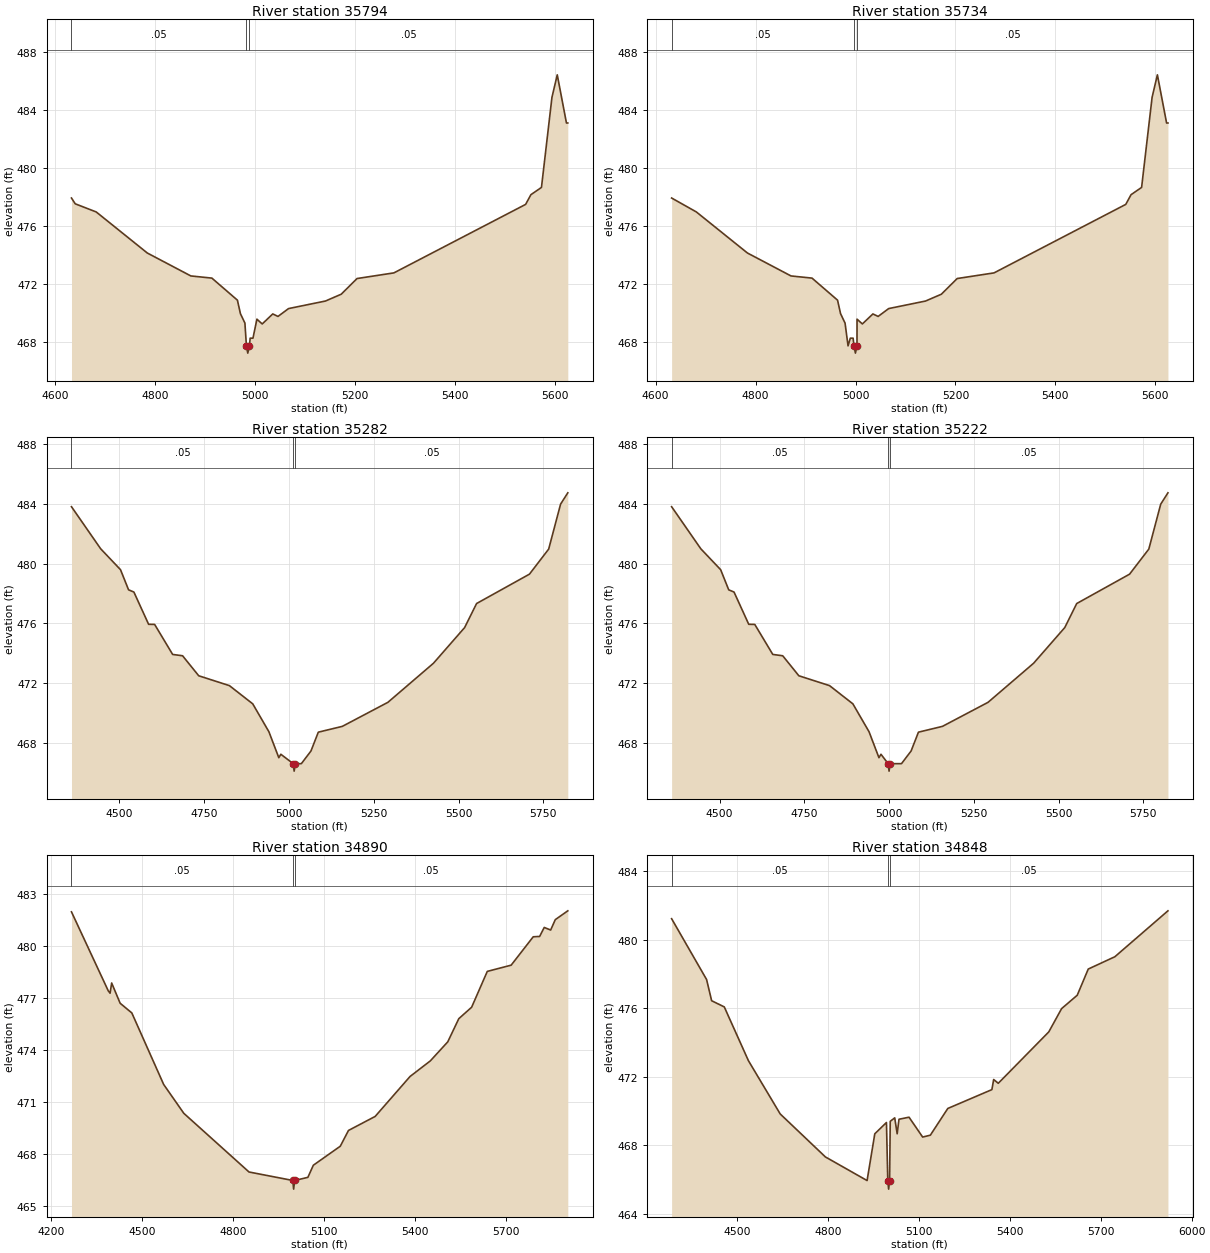
Type RM Length L Ch R = 1 ,35794   ,512,512,512
BEGIN DESCRIPTION:
UNT0083 IN CHRS 65.0
END DESCRIPTION:
XS GIS Cut Line= 3
      3477492.08      10543291.6      3477292.11     10542991.64
      3476692.07     10542791.63
#Sta/Elev= 30
  4632.1  477.91  4639.6  477.51  4681.6  476.95  4783.8  474.12  4870.9  472.54
    4913  472.39  4964.1  470.87  4970.1  469.94  4979.1  469.29  4982.1  467.72
  4984.8  467.22  4988.1  467.72  4989.6  468.25  4995.2  468.25  5003.1  469.56
  5013.7  469.23  5034.8  469.92  5045.3  469.75  5066.4  470.29  5140.2  470.81
  5171.8  471.28  5203.4  472.36  5277.2  472.75  5540.7  477.47  5551.3  478.14
  5572.4  478.64  5593.4  484.85    5604   486.4  5622.4  483.08  5625.1  483.08
#Mann= 3 ,-1 , 0
  4632.1     .05       0  4982.1     .03       0  4988.1     .05       0
Bank Sta=4982.1,4988.1
XS Rating Curve= 0 ,0
Exp/Cntr=0.3,0.1

Type RM Length L Ch R = 1 ,35734   ,512,512,512
BEGIN DESCRIPTION:
UNT0083 IN CHRS 65.0
END DESCRIPTION:
XS GIS Cut Line= 3
      3477492.08      10543291.6      3477292.11     10542991.64
      3476692.07     10542791.63
#Sta/Elev= 30
  4632.1  477.91  4681.6  476.95  4783.8  474.12  4870.9  472.54    4913  472.39
  4964.1  470.87  4970.1  469.94  4979.1  469.29  4985.1  467.72  4989.6  468.25
  4995.2  468.25    4997  467.72  4999.8  467.22    5003  467.72  5003.1  469.56
  5013.7  469.23  5034.8  469.92  5045.3  469.75  5066.4  470.29  5140.2  470.81
  5171.8  471.28  5203.4  472.36  5277.2  472.75  5540.7  477.47  5551.3  478.14
  5572.4  478.64  5593.4  484.85    5604   486.4  5622.4  483.08  5625.1  483.08
#Mann= 3 ,-1 , 0
  4632.1     .05       0    4997     .03       0    5003     .05       0
Bank Sta=4997,5003
XS Rating Curve= 0 ,0
Exp/Cntr=0.3,0.1

Type RM Length L Ch R = 1 ,35282   ,602,602,602
BEGIN DESCRIPTION:
UNT0083 IN CHRS 64.0
END DESCRIPTION:
XS GIS Cut Line= 3
       3477842.1     10543341.62      3477592.11     10542741.64
      3476992.12     10542191.65
#Sta/Elev= 30
  4358.4  483.81  4444.5  480.99    4503  479.59  4526.8  478.24  4542.5  478.09
  4585.9  475.93  4603.7  475.92  4656.8  473.91  4686.1  473.82  4733.7  472.48
  4824.2  471.82    4893   470.6  4940.7  468.73  4969.9  466.99  4975.9  467.22
  5012.5  466.59  5015.2  466.09  5018.5  466.59  5036.4  466.59  5064.8  467.44
  5086.4   468.7  5157.3  469.09  5291.7   470.7  5426.1  473.32    5518  475.71
  5553.2  477.32  5709.2  479.29  5765.9  480.97    5801  483.98  5822.3  484.74
#Mann= 3 ,-1 , 0
  4358.4     .05       0  5012.5     .03       0  5018.5     .05       0
Bank Sta=5012.5,5018.5
XS Rating Curve= 0 ,0
Exp/Cntr=0.3,0.1

Type RM Length L Ch R = 1 ,35222   ,332,332,332
BEGIN DESCRIPTION:
UNT0083 IN CHRS 64.0
END DESCRIPTION:
XS GIS Cut Line= 3
       3477842.1     10543341.62      3477592.11     10542741.64
      3476992.12     10542191.65
#Sta/Elev= 30
  4358.4  483.81  4444.5  480.99    4503  479.59  4526.8  478.24  4542.5  478.09
  4585.9  475.93  4603.7  475.92  4656.8  473.91  4686.1  473.82  4733.7  472.48
  4824.2  471.82    4893   470.6  4940.7  468.73  4969.9  466.99  4975.9  467.22
    4997  466.59  4999.8  466.09    5003  466.59  5036.4  466.59  5064.8  467.44
  5086.4   468.7  5157.3  469.09  5291.7   470.7  5426.1  473.32    5518  475.71
  5553.2  477.32  5709.2  479.29  5765.9  480.97    5801  483.98  5822.3  484.74
#Mann= 3 ,-1 , 0
  4358.4     .05       0    4997     .03       0    5003     .05       0
Bank Sta=4997,5003
XS Rating Curve= 0 ,0
Exp/Cntr=0.3,0.1

Type RM Length L Ch R = 1 ,34890   ,42,42,42
BEGIN DESCRIPTION:
UNT0083 IN CHRS 64.1
END DESCRIPTION:
XS GIS Cut Line= 6
      3478043.54      10543257.8      3477852.56     10542613.67
      3477828.25     10542570.26      3477783.11     10542539.01
      3477731.03     10542540.75      3477050.08     10542105.84
#Sta/Elev= 30
  4267.2  481.98  4388.4  477.42  4394.5  477.28  4399.7  477.87  4427.7   476.7
  4466.2  476.14  4571.1  472.01  4637.6  470.34  4852.6  466.95    4997  466.46
  4999.8  465.96    5003  466.46  5046.7  466.64  5064.7  467.34  5153.6  468.44
  5180.6  469.35  5268.6  470.16  5383.7  472.47  5450.5  473.37    5508  474.47
  5544.4  475.81  5586.7  476.47  5638.3  478.54    5717   478.9  5789.8  480.54
  5810.9  480.56  5826.1  481.08  5847.3  480.93  5862.5  481.53  5903.8  482.04
#Mann= 3 ,-1 , 0
  4267.2     .05       0    4997    .035       0    5003     .05       0
Bank Sta=4997,5003
XS Rating Curve= 0 ,0
Exp/Cntr=0.3,0.1

Type RM Length L Ch R = 1 ,34848   ,53,53,53
BEGIN DESCRIPTION:
UNT0083 IN CHRS 64.2
END DESCRIPTION:
XS GIS Cut Line= 6
      3478069.59      10543228.3       3477878.6     10542584.15
      3477854.29     10542540.75      3477809.16      10542509.5
      3477757.07     10542511.24      3477074.78     10542075.47
#Sta/Elev= 30
  4283.5  481.23  4398.9  477.68  4415.6  476.44  4457.3  476.08    4537  472.94
  4641.9  469.83  4791.1  467.32  4928.7  465.94  4954.1  468.67  4992.6  469.33
    4997  465.94  4999.8  465.44    5003  465.94  5005.1   469.4  5019.9   469.6
    5028  468.67    5034  469.52  5067.1  469.64  5112.1  468.48  5137.5  468.59
  5195.1  470.15  5340.6  471.25  5346.5  471.84  5361.7  471.62  5528.4  474.62
  5570.7  475.98  5622.3  476.76  5658.7  478.29  5746.6  479.01  5921.7  481.69
#Mann= 3 ,-1 , 0
  4283.5     .05       0    4997    .035       0    5003     .05       0
Bank Sta=4997,5003
XS Rating Curve= 0 ,0
Exp/Cntr=0.3,0.1

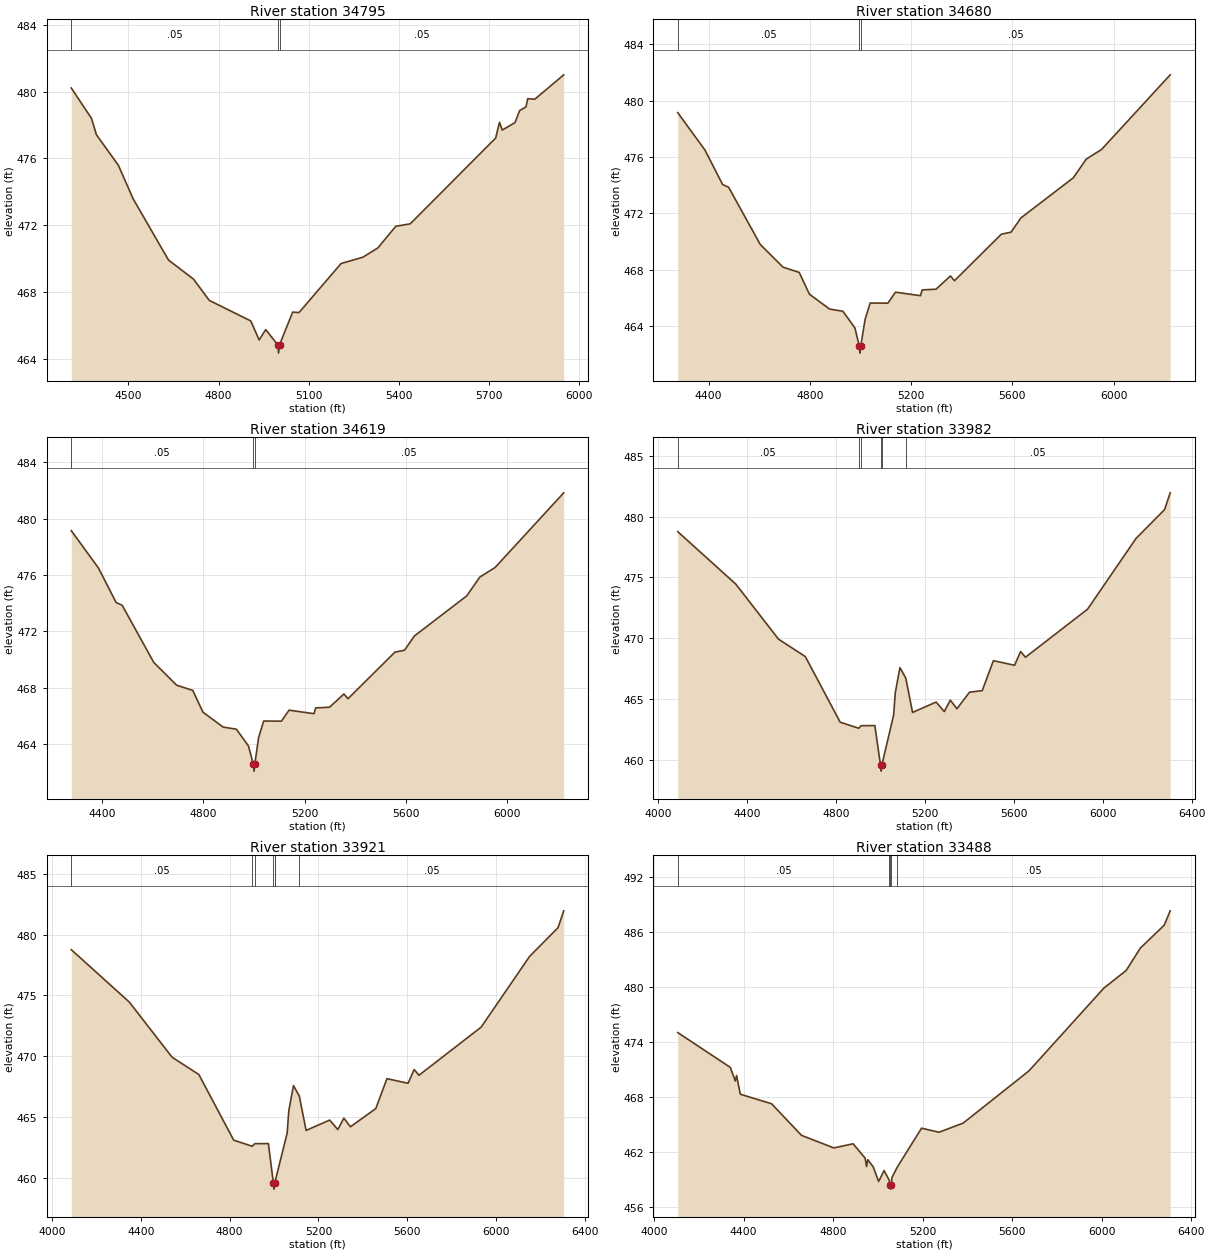
Type RM Length L Ch R = 1 ,34795   ,176,176,176
BEGIN DESCRIPTION:
UNT0083 IN CHRS 64.3
END DESCRIPTION:
XS GIS Cut Line= 6
      3478106.02     10543191.75      3477915.06     10542547.69
      3477890.75     10542504.29      3477845.61     10542473.04
      3477793.53     10542474.78      3477111.24     10542039.01
#Sta/Elev= 30
  4310.3  480.22  4377.5   478.4  4393.9  477.42  4466.9  475.59  4515.7  473.59
  4633.7  469.91  4717.2  468.76  4769.3  467.49  4907.3  466.26  4935.3  465.12
  4957.1  465.74    4997  464.83  4999.8  464.33    5003  464.83  5046.8  466.79
  5067.8  466.76  5207.7   469.7  5280.5  470.08  5330.4  470.64  5389.6  471.93
  5437.8  472.08  5721.9  477.22  5734.8  478.16  5744.1   477.7  5786.4  478.15
  5801.6  478.86  5822.8  479.09  5828.7  479.58  5852.4  479.55  5948.4  481.01
#Mann= 3 ,-1 , 0
  4310.3     .05       0    4997    .035       0    5003     .05       0
Bank Sta=4997,5003
XS Rating Curve= 0 ,0
Exp/Cntr=0.3,0.1

Type RM Length L Ch R = 1 ,34680   ,698,698,698
BEGIN DESCRIPTION:
UNT0083 IN CHRS 63.0
END DESCRIPTION:
XS GIS Cut Line= 4
      3478181.84     10543159.08      3478047.29     10542768.46
      3478025.59     10542264.98      3477105.48     10541804.93
#Sta/Elev= 30
  4277.8  479.14  4385.3  476.49  4454.9  474.05  4478.9  473.85  4603.8   469.8
    4694  468.19  4757.8  467.82  4797.9  466.28  4877.9  465.22  4930.2  465.07
    4978  463.88    4995   462.6  4997.8   462.1    5001   462.6  5018.1  464.49
  5038.1  465.65  5108.1  465.64  5138.2  466.42  5236.9  466.17  5243.5  466.58
  5298.4  466.63  5355.3  467.57  5371.1  467.23  5556.6  470.53  5594.7  470.67
  5633.8  471.68  5840.6  474.52    5892  475.85  5952.4  476.53  6223.6  481.82
#Mann= 3 ,-1 , 0
  4277.8     .05       0    4995    .035       0    5001     .05       0
Bank Sta=4995,5001
XS Rating Curve= 0 ,0
Exp/Cntr=0.3,0.1

Type RM Length L Ch R = 1 ,34619   ,698,698,698
BEGIN DESCRIPTION:
UNT0083 IN CHRS 63.0
END DESCRIPTION:
XS GIS Cut Line= 4
      3478181.84     10543159.08      3478047.29     10542768.46
      3478025.59     10542264.98      3477105.48     10541804.93
#Sta/Elev= 30
  4277.8  479.14  4385.3  476.49  4454.9  474.05  4478.9  473.85  4603.8   469.8
    4694  468.19  4757.8  467.82  4797.9  466.28  4877.9  465.22  4930.2  465.07
    4978  463.88    4997   462.6  4999.8   462.1    5003   462.6  5018.1  464.49
  5038.1  465.65  5108.1  465.64  5138.2  466.42  5236.9  466.17  5243.5  466.58
  5298.4  466.63  5355.3  467.57  5371.1  467.23  5556.6  470.53  5594.7  470.67
  5633.8  471.68  5840.6  474.52    5892  475.85  5952.4  476.53  6223.6  481.82
#Mann= 3 ,-1 , 0
  4277.8     .05       0    4997    .035       0    5003     .05       0
Bank Sta=4997,5003
XS Rating Curve= 0 ,0
Exp/Cntr=0.3,0.1

Type RM Length L Ch R = 1 ,33982   ,494,494,494
BEGIN DESCRIPTION:
UNT0083 IN CHRS 61.0
END DESCRIPTION:
XS GIS Cut Line= 4
      3478967.44     10542772.82      3478546.42      10542234.6
      3478203.54       10541857.      3477622.53     10541015.83
#Sta/Elev= 30
  4087.7  478.76  4348.7  474.46  4541.3  469.93  4661.6  468.51  4818.5  463.12
  4901.9  462.62  4912.9  462.83  4974.6  462.84    5000   459.6  5002.7   459.1
    5006   459.6    5059   463.7  5066.5  465.54  5087.4   467.6  5113.7  466.74
  5144.2  463.92  5250.3  464.77    5287  463.99    5314  464.93  5343.7  464.22
  5400.5  465.58  5457.7  465.71    5508  468.17  5603.3  467.79  5630.3  468.92
  5652.2  468.45  5931.8   472.4  6149.5   478.2  6277.9  480.57  6303.4  481.95
#Mann= 6 ,-1 , 0
  4087.7     .05       0  4901.9      .1       0  4912.9     .05       0
    5000    .035       0    5006     .05       0  5113.7     .05       0
Bank Sta=5000,5006
XS Rating Curve= 0 ,0
Exp/Cntr=0.3,0.1

Type RM Length L Ch R = 1 ,33921   ,494,494,494
BEGIN DESCRIPTION:
UNT0083 IN CHRS 61.0
END DESCRIPTION:
XS GIS Cut Line= 4
      3478967.44     10542772.82      3478546.42      10542234.6
      3478203.54       10541857.      3477622.53     10541015.83
#Sta/Elev= 30
  4087.7  478.76  4348.7  474.46  4541.3  469.93  4661.6  468.51  4818.5  463.12
  4901.9  462.62  4912.9  462.83  4974.6  462.84    4997   459.6  4999.8   459.1
    5003   459.6  5004.3  459.69    5059   463.7  5066.5  465.54  5087.4   467.6
  5113.7  466.74  5144.2  463.92  5250.3  464.77    5287  463.99    5314  464.93
  5343.7  464.22  5457.7  465.71    5508  468.17  5603.3  467.79  5630.3  468.92
  5652.2  468.45  5931.8   472.4  6149.5   478.2  6277.9  480.57  6303.4  481.95
#Mann= 7 ,-1 , 0
  4087.7     .05       0  4901.9      .1       0  4912.9     .05       0
    4997    .035       0    5003     .05       0  5004.3      .1       0
  5113.7     .05       0
Bank Sta=4997,5003
XS Rating Curve= 0 ,0
Exp/Cntr=0.3,0.1

Type RM Length L Ch R = 1 ,33488   ,923,923,923
BEGIN DESCRIPTION:
UNT0083 IN CHRS 60.0
END DESCRIPTION:
XS GIS Cut Line= 4
      3478993.45     10542594.81      3478689.65     10541991.55
      3478307.71     10541032.35      3477973.49     10540672.09
#Sta/Elev= 30
  4105.6  475.07  4340.4  471.27  4362.7  469.78  4368.3  470.39    4385  468.34
  4524.5   467.3  4658.3  463.85  4802.5  462.48  4888.6  462.93  4942.4  461.37
  4948.9  460.45  4954.3  461.19  4978.6  460.41  5002.9  458.82  5027.2  460.01
  5050.5  458.93  5053.8  458.48  5056.6  457.98  5059.8  458.48  5062.2  459.25
  5085.5  460.36  5194.4  464.63  5272.6  464.19  5380.5  465.19  5674.3  470.89
  6008.9  479.93  6108.1  481.84  6171.6  484.29  6278.1  486.79  6304.9  488.36
#Mann= 5 ,-1 , 0
  4105.6     .05       0  5050.5      .1       0  5053.8    .035       0
  5059.8      .1       0  5085.5     .05       0
Bank Sta=5053.8,5059.8
XS Rating Curve= 0 ,0
Exp/Cntr=0.3,0.1

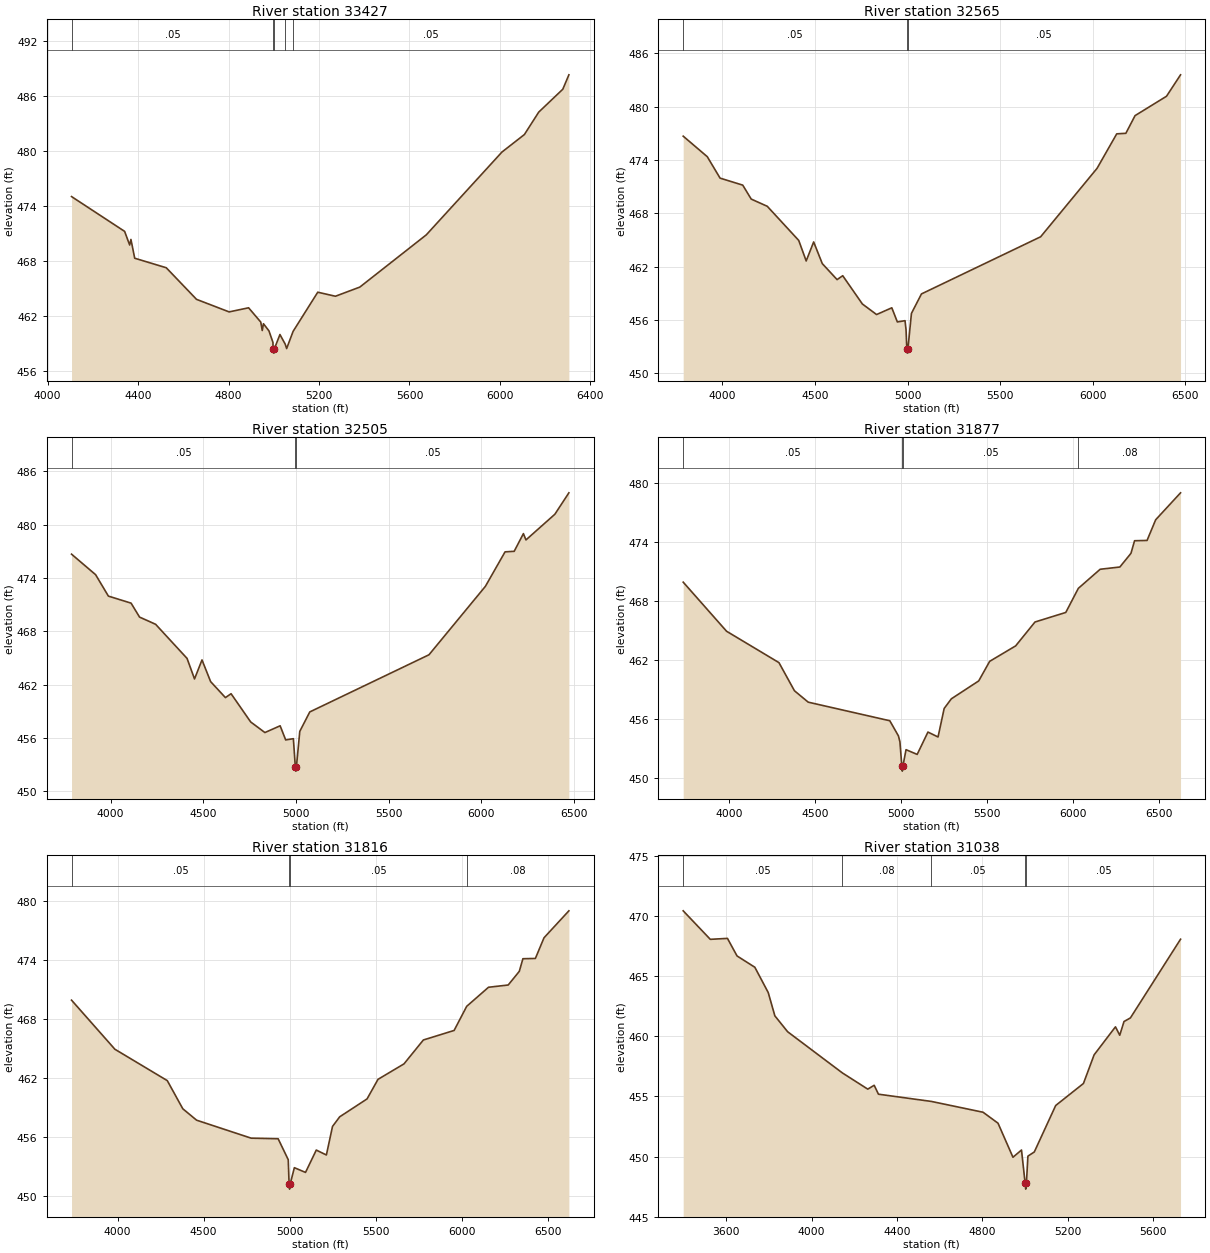
Type RM Length L Ch R = 1 ,33427   ,922,922,922
BEGIN DESCRIPTION:
UNT0083 IN CHRS 60.0
END DESCRIPTION:
XS GIS Cut Line= 4
      3478993.45     10542594.81      3478689.65     10541991.55
      3478307.71     10541032.35      3477973.49     10540672.09
#Sta/Elev= 30
  4105.6  475.07  4340.4  471.27  4362.7  469.78  4368.3  470.39    4385  468.34
  4524.5   467.3  4658.3  463.85  4802.5  462.48  4888.6  462.93  4942.4  461.37
  4948.9  460.45  4954.3  461.19  4978.6  460.41  4996.2  459.16    4997  458.48
  4999.8  457.98    5003  458.48  5027.2  460.01  5050.5  458.96  5056.8  458.48
  5085.5  460.36  5194.4  464.63  5272.6  464.19  5380.5  465.19  5674.3  470.89
  6008.9  479.93  6108.1  481.84  6171.6  484.29  6278.1  486.79  6304.9  488.36
#Mann= 5 ,-1 , 0
  4105.6     .05       0    4997    .035       0    5003     .05       0
  5050.5      .1       0  5085.5     .05       0
Bank Sta=4997,5003
XS Rating Curve= 0 ,0
Exp/Cntr=0.3,0.1

Type RM Length L Ch R = 1 ,32565   ,688,688,688
BEGIN DESCRIPTION:
UNT0083 IN CHRS 58.0
END DESCRIPTION:
XS GIS Cut Line= 4
      3479531.66     10542490.65      3479440.52     10541744.15
      3479171.42     10541101.79      3478261.37     10540265.41
#Sta/Elev= 30
  3789.1  476.67  3919.1  474.36  3988.1  471.95  4110.5  471.16  4156.3  469.59
  4242.9  468.78  4412.7  464.94    4453  462.63  4493.3  464.77  4539.9  462.33
  4619.8  460.53  4650.2  460.97  4756.2  457.79  4832.9   456.6  4915.1  457.36
    4945  455.77  4986.5  455.91  4991.9  454.91  4996.2  452.76    4999  452.26
  5002.2  452.76  5021.1  456.73  5075.1  458.92  5718.5  465.35    6023  473.05
  6129.1  476.93  6178.4  476.99  6228.1  478.98  6397.9  481.16  6473.6  483.57
#Mann= 3 ,-1 , 0
  3789.1     .05       0  4996.2     .03       0  5002.2     .05       0
Bank Sta=4996.2,5002.2
XS Rating Curve= 0 ,0
Exp/Cntr=0.3,0.1

Type RM Length L Ch R = 1 ,32505   ,689,689,689
BEGIN DESCRIPTION:
UNT0083 IN CHRS 58.0
END DESCRIPTION:
XS GIS Cut Line= 4
      3479531.66     10542490.65      3479440.52     10541744.15
      3479171.42     10541101.79      3478261.37     10540265.41
#Sta/Elev= 30
  3789.1  476.67  3919.1  474.36  3988.1  471.95  4110.5  471.16  4156.3  469.59
  4242.9  468.78  4412.7  464.94    4453  462.63  4493.3  464.77  4539.9  462.33
  4619.8  460.53  4650.2  460.97  4756.2  457.79  4832.9   456.6  4915.1  457.36
    4945  455.77  4986.5  455.91    4997  452.76  4999.8  452.26    5003  452.76
  5021.1  456.73  5075.1  458.92  5718.5  465.35    6023  473.05  6129.1  476.93
  6178.4  476.99  6228.1  478.98  6241.9  478.27  6397.9  481.16  6473.6  483.57
#Mann= 3 ,-1 , 0
  3789.1     .05       0    4997     .03       0    5003     .05       0
Bank Sta=4997,5003
XS Rating Curve= 0 ,0
Exp/Cntr=0.3,0.1

Type RM Length L Ch R = 1 ,31877   ,839,839,839
BEGIN DESCRIPTION:
UNT0083 IN CHRS 56.0
END DESCRIPTION:
XS GIS Cut Line= 4
      3479957.01     10542147.83      3479996.07     10541171.23
       3479492.6     10540481.13      3478646.66     10539843.42
#Sta/Elev= 30
  3732.3  469.94  3984.3  464.95  4288.9  461.76    4379   458.9  4459.1  457.74
  4933.3  455.85  4983.5  454.31    4992  453.72  5003.3  451.23    5006  450.73
  5009.3  451.23  5027.6  452.91  5092.4  452.43    5155   454.7  5213.7   454.2
  5249.3   457.1    5291  458.08  5450.1   459.9  5513.8  461.89  5664.7  463.46
  5777.4  465.89  5956.2  466.86  6029.2  469.31  6156.1  471.25  6270.6  471.48
  6335.1  472.87    6356  474.15  6428.6  474.18  6478.7  476.28  6623.3  479.02
#Mann= 4 ,-1 , 0
  3732.3     .05       0  5003.3    .035       0  5009.3     .05       0
  6029.2     .08       0
Bank Sta=5003.3,5009.3
XS Rating Curve= 0 ,0
Exp/Cntr=0.3,0.1

Type RM Length L Ch R = 1 ,31816   ,835,835,835
BEGIN DESCRIPTION:
UNT0083 IN CHRS 56.0
END DESCRIPTION:
XS GIS Cut Line= 4
      3479957.01     10542147.83      3479996.07     10541171.23
       3479492.6     10540481.13      3478646.66     10539843.42
#Sta/Elev= 30
  3732.3  469.94  3984.3  464.95  4288.9  461.76    4379   458.9  4459.1  457.74
  4776.5  455.91  4933.3  455.85    4992  453.72    4997  451.23  4999.8  450.73
    5003  451.23  5027.6  452.91  5092.4  452.43    5155   454.7  5213.7   454.2
  5249.3   457.1    5291  458.08  5450.1   459.9  5513.8  461.89  5664.7  463.46
  5777.4  465.89  5956.2  466.86  6029.2  469.31  6156.1  471.25  6270.6  471.48
  6335.1  472.87    6356  474.15  6428.6  474.18  6478.7  476.28  6623.3  479.02
#Mann= 4 ,-1 , 0
  3732.3     .05       0    4997    .035       0    5003     .05       0
  6029.2     .08       0
Bank Sta=4997,5003
XS Rating Curve= 0 ,0
Exp/Cntr=0.3,0.1

Type RM Length L Ch R = 1 ,31038   ,678,678,678
BEGIN DESCRIPTION:
UNT0083 IN CHRS 55.0
END DESCRIPTION:
XS GIS Cut Line= 4
       3480247.8     10542143.48       3480473.5     10541379.57
      3480490.87     10540038.42      3480447.47     10539851.81
#Sta/Elev= 30
  3398.4  470.43  3525.4  468.06  3605.7  468.14  3650.6  466.68    3734  465.74
  3796.6  463.64  3827.8   461.7  3887.6  460.38  4143.8  456.96  4262.9  455.61
  4292.9  455.93  4312.9  455.19  4560.4  454.59  4802.9  453.69  4872.9  452.78
  4942.9  449.95  4982.9  450.55  4999.9   447.8  5002.7   447.3  5005.9   447.8
  5012.9  450.04  5042.9  450.39    5143  454.25    5273  456.08    5323  458.46
    5423  460.79    5443  460.09    5463  461.23    5493  461.53  5727.8  468.07
#Mann= 5 ,-1 , 0
  3398.4     .05       0  4143.8     .08       0  4560.4     .05       0
  4999.9     .04       0  5005.9     .05       0
Bank Sta=4999.9,5005.9
XS Rating Curve= 0 ,0
Exp/Cntr=0.3,0.1

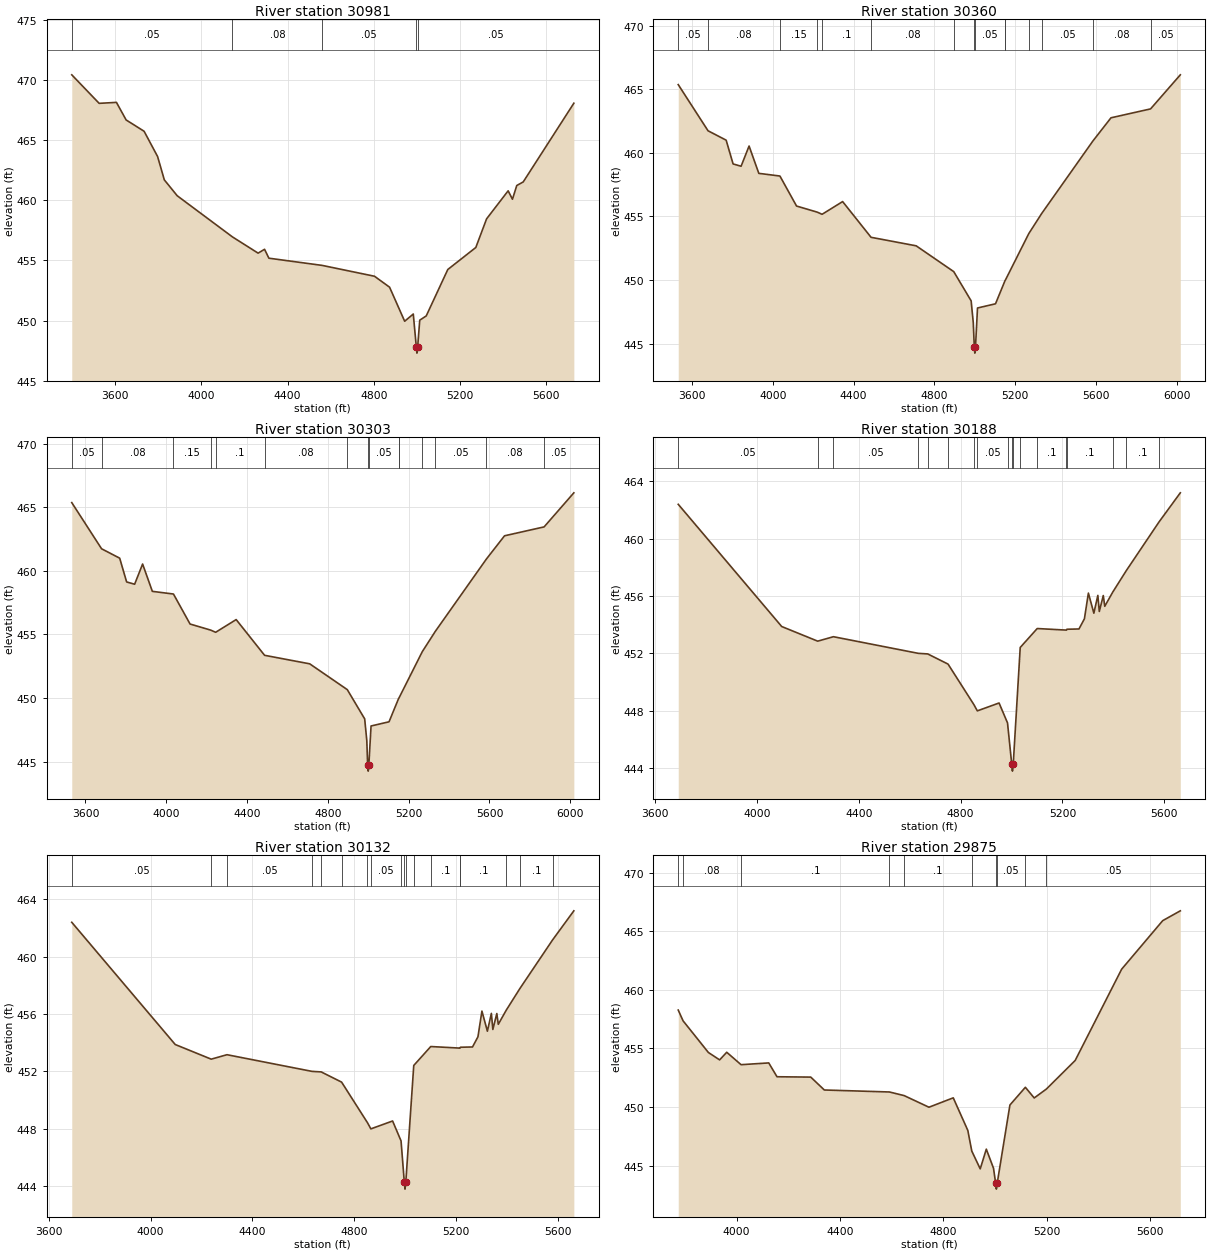
Type RM Length L Ch R = 1 ,30981   ,678,678,678
BEGIN DESCRIPTION:
UNT0083 IN CHRS 55.0
END DESCRIPTION:
XS GIS Cut Line= 4
       3480247.8     10542143.48       3480473.5     10541379.57
      3480490.87     10540038.42      3480447.47     10539851.81
#Sta/Elev= 30
  3398.4  470.43  3525.4  468.06  3605.7  468.14  3650.6  466.68    3734  465.74
  3796.6  463.64  3827.8   461.7  3887.6  460.38  4143.8  456.96  4262.9  455.61
  4292.9  455.93  4312.9  455.19  4560.4  454.59  4802.9  453.69  4872.9  452.78
  4942.9  449.95  4982.9  450.55    4997   447.8  4999.8   447.3    5003   447.8
  5012.9  450.04  5042.9  450.39    5143  454.25    5273  456.08    5323  458.46
    5423  460.79    5443  460.09    5463  461.23    5493  461.53  5727.8  468.07
#Mann= 5 ,-1 , 0
  3398.4     .05       0  4143.8     .08       0  4560.4     .05       0
    4997     .04       0    5003     .05       0
Bank Sta=4997,5003
XS Rating Curve= 0 ,0
Exp/Cntr=0.3,0.1

Type RM Length L Ch R = 1 ,30360   ,172,172,172
BEGIN DESCRIPTION:
UNT0083 IN CHRS 53.1
END DESCRIPTION:
XS GIS Cut Line= 4
      3481549.89     10542026.24      3481246.07     10540923.84
      3481107.19     10540485.47      3480651.46     10539730.26
#Sta/Elev= 30
  3532.3  465.37  3679.8  461.74  3769.5     461  3803.9  459.13  3843.5  458.95
    3883  460.54  3931.2  458.39  4035.7  458.18  4117.9  455.82  4220.3  455.34
  4244.5  455.17  4346.1  456.17  4486.8  453.36  4710.2  452.69  4896.2  450.66
  4982.3  448.36  4992.8  446.65  4997.8  444.75  5000.5  444.25  5003.8  444.75
  5013.8   447.8  5102.9  448.13  5150.2  449.96  5152.3  450.01  5267.6  453.65
  5331.8  455.24  5585.2  460.94  5674.6  462.76  5870.5  463.46  6017.7  466.14
#Mann= 15 ,-1 , 0
  3532.3     .05       0  3679.8     .08       0  4035.7     .15       0
  4220.3     .08       0  4244.5      .1       0  4486.8     .08       0
  4896.2     .05       0  4997.8     .04       0  5003.8     .05       0
  5150.2     .08       0  5152.3     .05       0  5267.6     .08       0
  5331.8     .05       0  5585.2     .08       0  5870.5     .05       0
Bank Sta=4997.8,5003.8
XS Rating Curve= 0 ,0
Exp/Cntr=0.3,0.1

Type RM Length L Ch R = 1 ,30303   ,171,171,171
BEGIN DESCRIPTION:
UNT0083 IN CHRS 53.1
END DESCRIPTION:
XS GIS Cut Line= 4
      3481549.89     10542026.24      3481246.07     10540923.84
      3481107.19     10540485.47      3480651.46     10539730.26
#Sta/Elev= 30
  3532.3  465.37  3679.8  461.74  3769.5     461  3803.9  459.13  3843.5  458.95
    3883  460.54  3931.2  458.39  4035.7  458.18  4117.9  455.82  4220.3  455.34
  4244.5  455.17  4346.1  456.17  4486.8  453.36  4710.2  452.69  4896.2  450.66
  4982.3  448.36  4992.8  446.65    4997  444.75  4999.8  444.25    5003  444.75
  5013.8   447.8  5102.9  448.13  5150.2  449.96  5152.3  450.01  5267.6  453.65
  5331.8  455.24  5585.2  460.94  5674.6  462.76  5870.5  463.46  6017.7  466.14
#Mann= 15 ,-1 , 0
  3532.3     .05       0  3679.8     .08       0  4035.7     .15       0
  4220.3     .08       0  4244.5      .1       0  4486.8     .08       0
  4896.2     .05       0    4997     .04       0    5003     .05       0
  5150.2     .08       0  5152.3     .05       0  5267.6     .08       0
  5331.8     .05       0  5585.2     .08       0  5870.5     .05       0
Bank Sta=4997,5003
XS Rating Curve= 0 ,0
Exp/Cntr=0.3,0.1

Type RM Length L Ch R = 1 ,30188   ,313,313,313
BEGIN DESCRIPTION:
UNT0083 IN CHRS 53.0
END DESCRIPTION:
XS GIS Cut Line= 3
      3481897.11     10541735.45      3481528.19     10540932.52
      3480973.13     10539995.86
#Sta/Elev= 30
  3690.7   462.4  4097.2  453.88  4238.6  452.86  4300.5  453.17  4633.9  452.01
  4670.7  451.97  4750.7  451.26  4852.4  448.43  4865.7     448  4951.1  448.55
  4984.3  447.16  5000.8   444.3  5003.6   443.8  5006.8   444.3  5034.2  452.42
    5101  453.74  5215.9  453.63  5217.8  453.69    5265  453.71  5286.4  454.42
    5302  456.21  5323.5  454.81  5339.1  456.05  5344.9  454.93  5360.5  456.04
  5366.3  455.29  5397.7  456.28  5451.4  457.79  5579.5  461.17  5663.1   463.2
#Mann= 18 ,-1 , 0
  3690.7     .05       0  4238.6     .08       0  4300.5     .05       0
  4633.9      .1       0  4670.7     .08       0  4750.7      .1       0
  4852.4     .08       0  4865.7     .05       0  4984.3     .08       0
  5000.8     .07       0  5006.8     .08       0  5034.2     .05       0
    5101      .1       0  5215.9     .08       0  5217.8      .1       0
  5397.7     .08       0  5451.4      .1       0  5579.5     .08       0
Bank Sta=5000.8,5006.8
XS Rating Curve= 0 ,0
Exp/Cntr=0.3,0.1

Type RM Length L Ch R = 1 ,30132   ,314,314,314
BEGIN DESCRIPTION:
UNT0083 IN CHRS 53.0
END DESCRIPTION:
XS GIS Cut Line= 3
      3481897.11     10541735.45      3481528.19     10540932.52
      3480973.13     10539995.86
#Sta/Elev= 30
  3690.7   462.4  4097.2  453.88  4238.6  452.86  4300.5  453.17  4633.9  452.01
  4670.7  451.97  4750.7  451.26  4852.4  448.43  4865.7     448  4951.1  448.55
  4984.3  447.16    4997   444.3  4999.8   443.8    5003   444.3  5034.2  452.42
    5101  453.74  5215.9  453.63  5217.8  453.69    5265  453.71  5286.4  454.42
    5302  456.21  5323.5  454.81  5339.1  456.05  5344.9  454.93  5360.5  456.04
  5366.3  455.29  5397.7  456.28  5451.4  457.79  5579.5  461.17  5663.1   463.2
#Mann= 18 ,-1 , 0
  3690.7     .05       0  4238.6     .08       0  4300.5     .05       0
  4633.9      .1       0  4670.7     .08       0  4750.7      .1       0
  4852.4     .08       0  4865.7     .05       0  4984.3     .08       0
    4997     .07       0    5003     .08       0  5034.2     .05       0
    5101      .1       0  5215.9     .08       0  5217.8      .1       0
  5397.7     .08       0  5451.4      .1       0  5579.5     .08       0
Bank Sta=4997,5003
XS Rating Curve= 0 ,0
Exp/Cntr=0.3,0.1

Type RM Length L Ch R = 1 ,29875   ,148,148,148
BEGIN DESCRIPTION:
UNT0083 IN CHRS 52.0
END DESCRIPTION:
XS GIS Cut Line= 4
      3482105.46     10541505.45      3481671.42     10540724.19
      3481497.81     10540142.59      3481250.41     10539777.99
#Sta/Elev= 30
  3774.7  458.27  3793.5  457.35  3891.3  454.65  3934.8  454.02  3962.2  454.67
  4017.6  453.61  4124.7  453.76  4156.6  452.58  4287.1  452.55  4339.6  451.45
  4591.4  451.28  4648.4  450.97  4744.1  449.98  4838.1  450.78  4894.4     448
  4909.7  446.24  4942.4  444.72  4965.9   446.4  4993.8  444.77    5002  443.49
  5004.8  442.99    5008  443.49  5057.2  450.17  5116.9  451.68  5151.1  450.77
  5198.1  451.53  5309.5  453.97  5489.2  461.76  5647.9   465.9    5716  466.74
#Mann= 10 ,-1 , 0
  3774.7      .1       0  3793.5     .08       0  4017.6      .1       0
  4591.4     .08       0  4648.4      .1       0  4909.7     .05       0
    5002     .04       0    5008     .05       0  5116.9     .16       0
  5198.1     .05       0
Bank Sta=5002,5008
XS Rating Curve= 0 ,0
Exp/Cntr=0.3,0.1

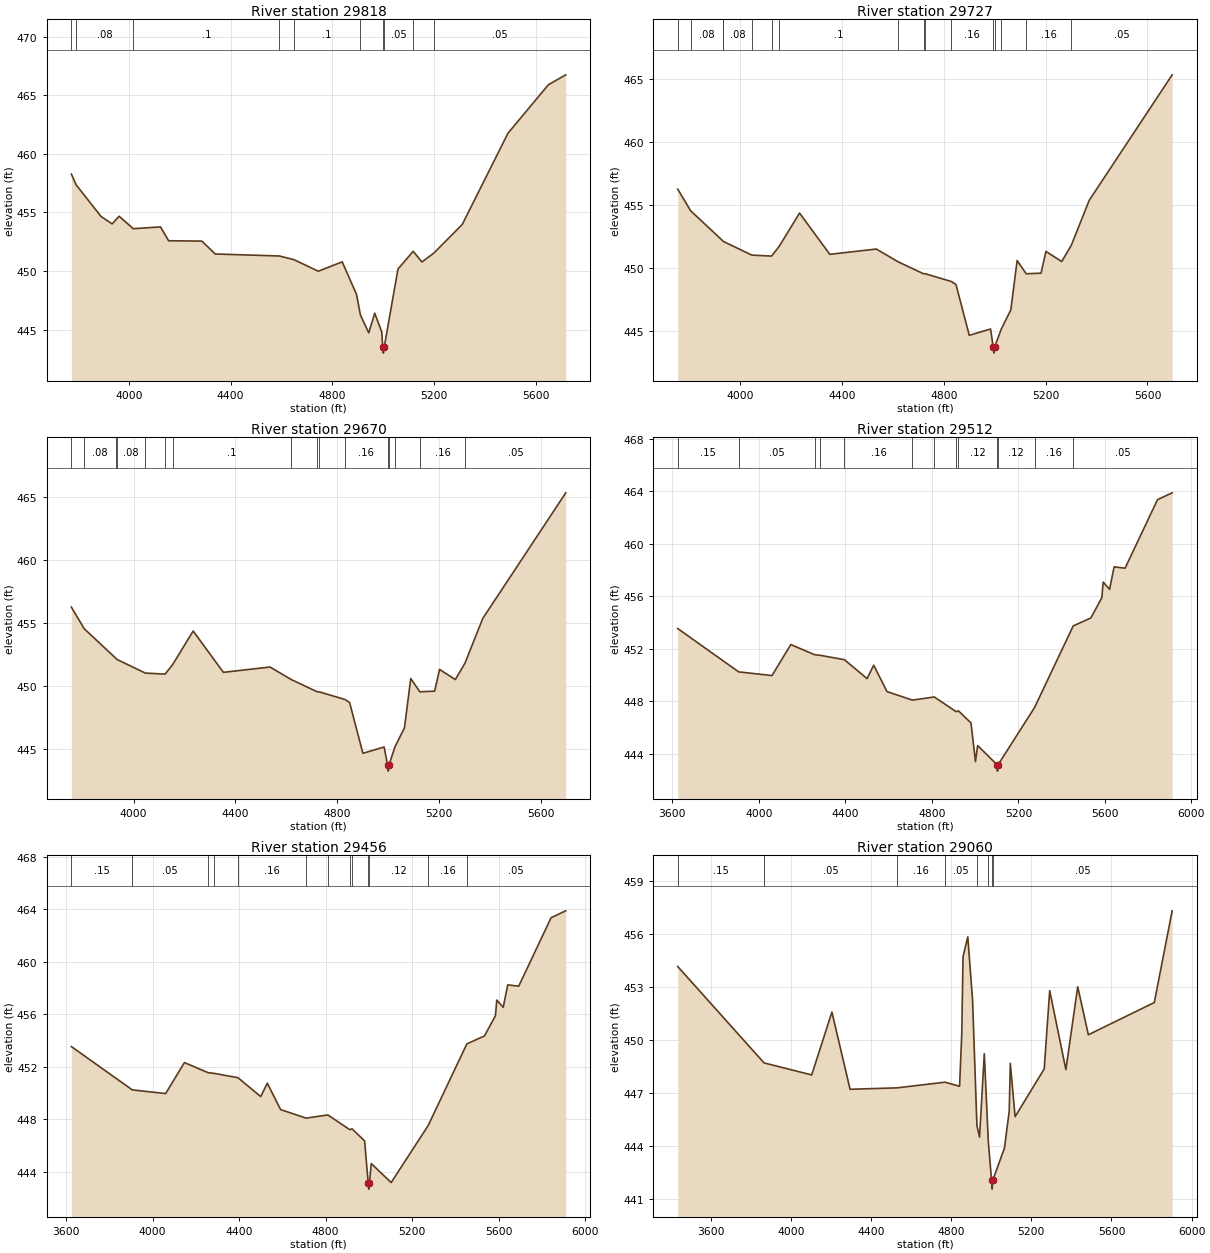
Type RM Length L Ch R = 1 ,29818   ,148,148,148
BEGIN DESCRIPTION:
UNT0083 IN CHRS 52.0
END DESCRIPTION:
XS GIS Cut Line= 4
      3482105.46     10541505.45      3481671.42     10540724.19
      3481497.81     10540142.59      3481250.41     10539777.99
#Sta/Elev= 30
  3774.7  458.27  3793.5  457.35  3891.3  454.65  3934.8  454.02  3962.2  454.67
  4017.6  453.61  4124.7  453.76  4156.6  452.58  4287.1  452.55  4339.6  451.45
  4591.4  451.28  4648.4  450.97  4744.1  449.98  4838.1  450.78  4894.4     448
  4909.7  446.24  4942.4  444.72  4965.9   446.4  4993.8  444.77    4997  443.49
  4999.8  442.99    5003  443.49  5057.2  450.17  5116.9  451.68  5151.1  450.77
  5198.1  451.53  5309.5  453.97  5489.2  461.76  5647.9   465.9    5716  466.74
#Mann= 10 ,-1 , 0
  3774.7      .1       0  3793.5     .08       0  4017.6      .1       0
  4591.4     .08       0  4648.4      .1       0  4909.7     .05       0
    4997     .04       0    5003     .05       0  5116.9     .16       0
  5198.1     .05       0
Bank Sta=4997,5003
XS Rating Curve= 0 ,0
Exp/Cntr=0.3,0.1

Type RM Length L Ch R = 1 ,29727   ,215,215,215
BEGIN DESCRIPTION:
UNT0083 IN CHRS 52.1
END DESCRIPTION:
XS GIS Cut Line= 4
      3482240.02     10541453.39      3481805.97      10540672.1
      3481632.36      10540090.5      3481384.97     10539725.94
#Sta/Elev= 30
  3755.7  456.25  3806.2  454.54  3931.4  452.18  3933.9  452.12  4046.2  451.03
  4123.9  450.95  4153.9  451.72  4233.9  454.36  4352.6  451.09  4535.6  451.51
    4620  450.51  4720.9  449.55  4726.5  449.56  4830.1  448.94  4848.2   448.7
  4900.4  444.68  4983.9  445.18  4994.3  443.77  4997.1  443.27  5000.3  443.77
  5025.9  445.17  5063.6   446.7  5088.3   450.6    5124  449.55  5182.2   449.6
  5201.4  451.32  5263.4  450.52  5301.1  451.81  5371.2  455.36    5697   465.3
#Mann= 16 ,-1 , 0
  3755.7      .1       0  3806.2     .08       0  3931.4     .05       0
  3933.9     .08       0  4046.2     .05       0  4123.9     .08       0
  4153.9      .1       0    4620     .05       0  4720.9     .08       0
  4726.5     .05       0  4830.1     .16       0  4994.3     .07       0
  5000.3     .16       0  5025.9     .12       0    5124     .16       0
  5301.1     .05       0
Bank Sta=4994.3,5000.3
XS Rating Curve= 0 ,0
Exp/Cntr=0.3,0.1

Type RM Length L Ch R = 1 ,29670   ,214,214,214
BEGIN DESCRIPTION:
UNT0083 IN CHRS 52.1
END DESCRIPTION:
XS GIS Cut Line= 4
      3482240.02     10541453.39      3481805.97      10540672.1
      3481632.36      10540090.5      3481384.97     10539725.94
#Sta/Elev= 30
  3755.7  456.25  3806.2  454.54  3931.4  452.18  3933.9  452.12  4046.2  451.03
  4123.9  450.95  4153.9  451.72  4233.9  454.36  4352.6  451.09  4535.6  451.51
    4620  450.51  4720.9  449.55  4726.5  449.56  4830.1  448.94  4848.2   448.7
  4900.4  444.68  4983.9  445.18    4997  443.77  4999.8  443.27    5003  443.77
  5025.9  445.17  5063.6   446.7  5088.3   450.6    5124  449.55  5182.2   449.6
  5201.4  451.32  5263.4  450.52  5301.1  451.81  5371.2  455.36    5697   465.3
#Mann= 16 ,-1 , 0
  3755.7      .1       0  3806.2     .08       0  3931.4     .05       0
  3933.9     .08       0  4046.2     .05       0  4123.9     .08       0
  4153.9      .1       0    4620     .05       0  4720.9     .08       0
  4726.5     .05       0  4830.1     .16       0    4997     .07       0
    5003     .16       0  5025.9     .12       0    5124     .16       0
  5301.1     .05       0
Bank Sta=4997,5003
XS Rating Curve= 0 ,0
Exp/Cntr=0.3,0.1

Type RM Length L Ch R = 1 ,29512   ,452,452,452
BEGIN DESCRIPTION:
UNT0083 IN CHRS 51.0
END DESCRIPTION:
XS GIS Cut Line= 4
      3482456.99     10541448.98      3481996.94     10540745.89
      3481836.35     10539990.68      3481454.92     10539435.87
#Sta/Elev= 30
    3625  453.55  3906.6  450.25  4060.6  449.97  4147.6  452.33  4257.3  451.56
  4284.1  451.51  4395.1  451.18  4500.2  449.74  4530.9  450.76  4592.2  448.75
  4709.8   448.1  4810.9  448.34  4912.1  447.22  4922.6  447.28  4980.7  446.36
  5001.2  443.42  5011.4  444.64  5100.4  443.19  5103.2  442.69  5106.4  443.19
  5274.4  447.53  5453.2  453.75  5534.8  454.36  5585.5   455.9  5591.6  457.09
  5621.4  456.54  5642.3  458.25  5693.1  458.15  5842.9  463.37  5910.6  463.89
#Mann= 13 ,-1 , 0
    3625     .15       0  3906.6     .05       0  4257.3     .16       0
  4284.1     .05       0  4395.1     .16       0  4709.8     .05       0
  4810.9     .16       0  4912.1     .05       0  4922.6     .12       0
  5100.4     .07       0  5106.4     .12       0  5274.4     .16       0
  5453.2     .05       0
Bank Sta=5100.4,5106.4
XS Rating Curve= 0 ,0
Exp/Cntr=0.3,0.1

Type RM Length L Ch R = 1 ,29456   ,452,452,452
BEGIN DESCRIPTION:
UNT0083 IN CHRS 51.0
END DESCRIPTION:
XS GIS Cut Line= 4
      3482456.99     10541448.98      3481996.94     10540745.89
      3481836.35     10539990.68      3481454.92     10539435.87
#Sta/Elev= 30
    3625  453.55  3906.6  450.25  4060.6  449.97  4147.6  452.33  4257.3  451.56
  4284.1  451.51  4395.1  451.18  4500.2  449.74  4530.9  450.76  4592.2  448.75
  4709.8   448.1  4810.9  448.34  4912.1  447.22  4922.6  447.28  4980.7  446.36
    4997  443.19  4999.8  442.69    5003  443.19  5011.4  444.64  5103.4  443.19
  5274.4  447.53  5453.2  453.75  5534.8  454.36  5585.5   455.9  5591.6  457.09
  5621.4  456.54  5642.3  458.25  5693.1  458.15  5842.9  463.37  5910.6  463.89
#Mann= 13 ,-1 , 0
    3625     .15       0  3906.6     .05       0  4257.3     .16       0
  4284.1     .05       0  4395.1     .16       0  4709.8     .05       0
  4810.9     .16       0  4912.1     .05       0  4922.6     .12       0
    4997     .07       0    5003     .12       0  5274.4     .16       0
  5453.2     .05       0
Bank Sta=4997,5003
XS Rating Curve= 0 ,0
Exp/Cntr=0.3,0.1

Type RM Length L Ch R = 1 ,29060   ,938,938,938
BEGIN DESCRIPTION:
UNT0083 IN CHRS 50.0
END DESCRIPTION:
XS GIS Cut Line= 4
      3482556.84     10541544.52      3482400.59     10540320.54
      3482179.23     10539791.03       3481853.7     10539218.09
#Sta/Elev= 30
  3435.9  454.15  3866.5  448.71  4104.2  448.03    4205  451.58  4295.7  447.22
  4529.7   447.3  4769.1  447.62    4842  447.39  4852.9  450.35  4859.3  454.71
  4883.1  455.83  4906.9  452.24  4928.6  445.17  4941.6  444.52  4965.4  449.23
  4985.4  444.26  5001.6  442.08  5004.4  441.58  5007.6  442.08    5066   443.9
  5089.8  445.99  5095.2  448.69    5119  445.67  5264.3  448.37  5291.7  452.79
  5372.4  448.33  5431.5  453.01  5484.6   450.3  5813.6  452.12  5902.7   457.3
#Mann= 8 ,-1 , 0
  3435.9     .15       0  3866.5     .05       0  4529.7     .16       0
  4769.1     .05       0  4928.6     .12       0  4985.4     .05       0
  5001.6     .04       0  5007.6     .05       0
Bank Sta=5001.6,5007.6
XS Rating Curve= 0 ,0
Exp/Cntr=0.3,0.1