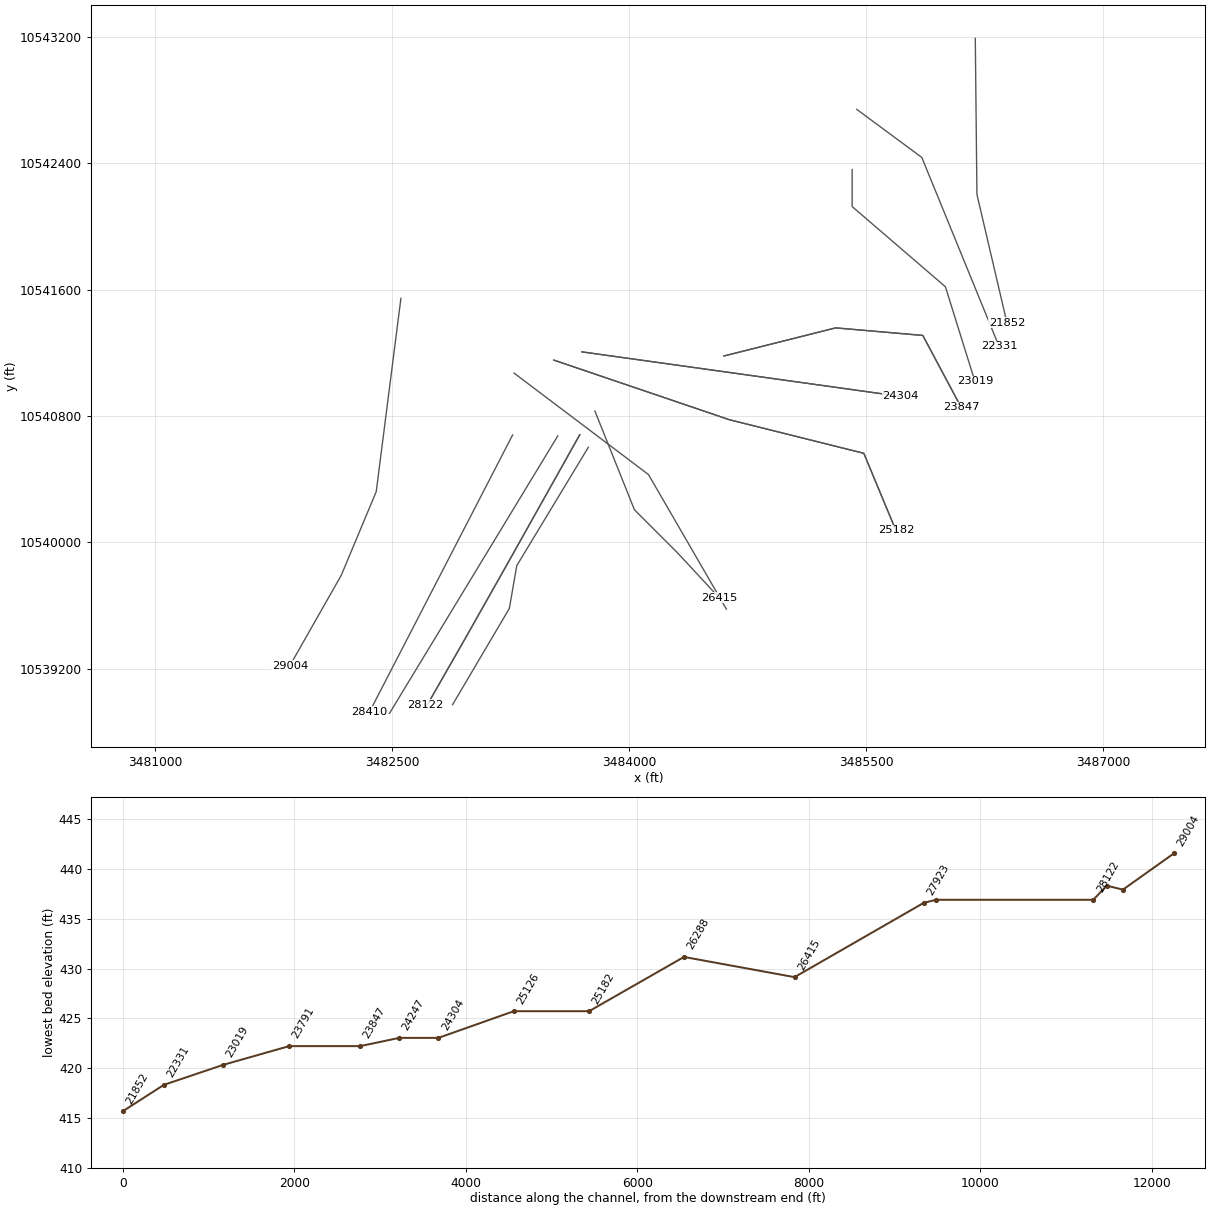
HEC-RAS study UNT0083 IN CHRS.prj: UNT0083 IN CHRS Base Level Engineering

--- UNT0083 IN CHRS.g01 (geometry) --- (continued)

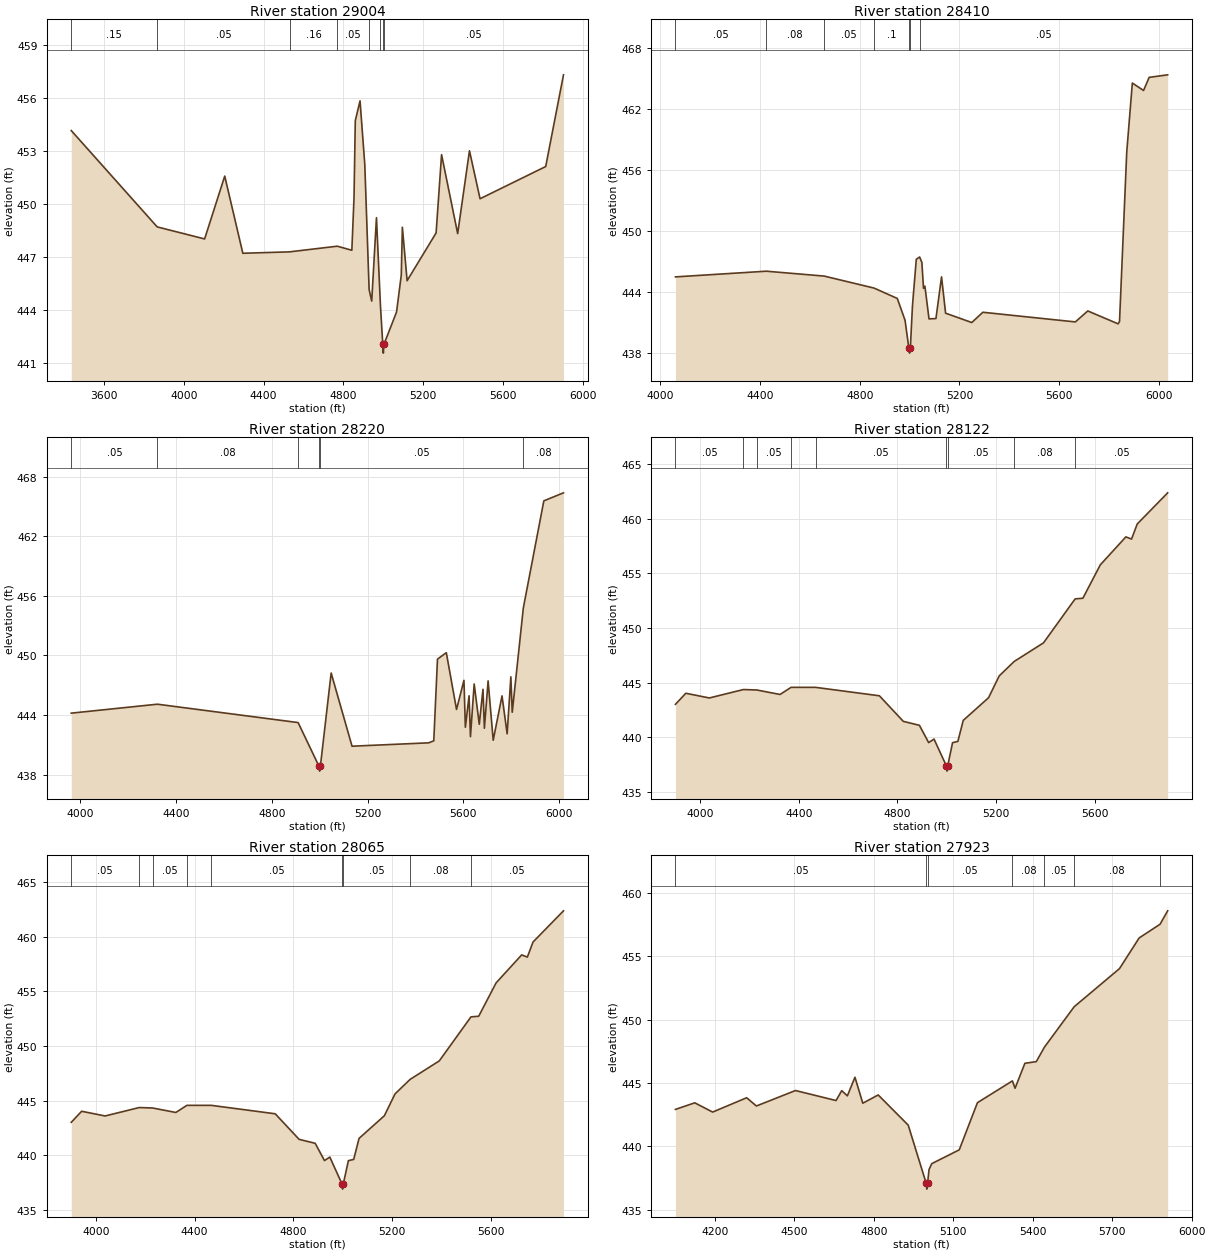
Type RM Length L Ch R = 1 ,29004   ,594,594,594
BEGIN DESCRIPTION:
UNT0083 IN CHRS 50.0
END DESCRIPTION:
XS GIS Cut Line= 4
      3482556.84     10541544.52      3482400.59     10540320.54
      3482179.23     10539791.03       3481853.7     10539218.09
#Sta/Elev= 30
  3435.9  454.15  3866.5  448.71  4104.2  448.03    4205  451.58  4295.7  447.22
  4529.7   447.3  4769.1  447.62    4842  447.39  4852.9  450.35  4859.3  454.71
  4883.1  455.83  4906.9  452.24  4928.6  445.17  4941.6  444.52  4965.4  449.23
  4985.4  444.26    4997  442.08  4999.8  441.58    5003  442.08    5066   443.9
  5089.8  445.99  5095.2  448.69    5119  445.67  5264.3  448.37  5291.7  452.79
  5372.4  448.33  5431.5  453.01  5484.6   450.3  5813.6  452.12  5902.7   457.3
#Mann= 8 ,-1 , 0
  3435.9     .15       0  3866.5     .05       0  4529.7     .16       0
  4769.1     .05       0  4928.6     .12       0  4985.4     .05       0
    4997     .04       0    5003     .05       0
Bank Sta=4997,5003
XS Rating Curve= 0 ,0
Exp/Cntr=0.3,0.1

Type RM Length L Ch R = 1 ,28410   ,190,190,190
BEGIN DESCRIPTION:
UNT0083 IN CHRS 49.3
END DESCRIPTION:
XS GIS Cut Line= 2
       3483263.9     10540679.88      3482358.19     10538925.71
#Sta/Elev= 30
  4060.9  445.44  4425.2     446  4657.3  445.52  4857.4  444.34  4950.6  443.32
  4981.8  441.17    4997  438.44  4999.8  437.94    5003  438.44  5011.5  442.59
  5026.8  447.17  5040.3   447.4  5049.3  446.86  5055.8  444.32  5061.4  444.53
  5077.9  441.31  5105.7  441.34  5128.1  445.44  5144.4  441.87  5249.5  440.95
  5293.8  441.96  5664.8  441.01  5714.7  442.09  5836.4  440.82    5842  441.05
  5870.9   457.7  5893.4  464.51  5938.4  463.78  5960.9  465.07  6035.1  465.32
#Mann= 7 ,-1 , 0
  4060.9     .05       0  4425.2     .08       0  4657.3     .05       0
  4857.4      .1       0    4997     .07       0    5003      .1       0
  5040.3     .05       0
Bank Sta=4997,5003
XS Rating Curve= 0 ,0
Exp/Cntr=0.3,0.1

Type RM Length L Ch R = 1 ,28220   ,155,155,155
BEGIN DESCRIPTION:
UNT0083 IN CHRS 49.2
END DESCRIPTION:
XS GIS Cut Line= 2
      3483549.96     10540674.29      3482484.44     10538916.52
#Sta/Elev= 30
  3962.7  444.18  4322.3  445.08    4910  443.23    4997  438.84  4999.8  438.34
    5003  438.84    5048  448.22  5135.2  440.85  5455.2  441.19  5476.5  441.39
    5492  449.62  5528.9  450.27  5571.5  444.55  5602.5  447.48  5608.4  442.76
  5623.9  445.93  5629.7  441.81  5645.2  447.12  5666.5  443.06    5682  446.58
  5687.9  442.66  5703.4  447.43  5724.7  441.45  5761.5  445.92  5782.9   442.1
  5798.4  447.84  5804.2  444.27  5850.4  454.76  5936.1  465.56  6018.2  466.37
#Mann= 6 ,-1 , 0
  3962.7     .05       0  4322.3     .08       0    4910     .05       0
    4997    .035       0    5003     .05       0  5850.4     .08       0
Bank Sta=4997,5003
XS Rating Curve= 0 ,0
Exp/Cntr=0.3,0.1

Type RM Length L Ch R = 1 ,28122   ,1834,1834,1834
BEGIN DESCRIPTION:
UNT0083 IN CHRS 49.0
END DESCRIPTION:
XS GIS Cut Line= 5
      3483688.83     10540681.23      3483224.43     10539852.26
      3482959.67     10539383.51      3482716.62     10538958.17
      3482707.93      10538971.2
#Sta/Elev= 30
  3900.7  443.03  3942.7  444.04  4037.8  443.61    4176  444.38  4230.2  444.34
  4324.3  443.93  4369.1  444.58  4468.3  444.58  4726.9  443.81  4823.9  441.47
    4889  441.11  4926.5  439.53  4948.2  439.85  4997.9  437.42  5000.7  436.92
  5003.9  437.42  5023.3  439.52  5044.9  439.64  5066.6  441.56  5169.1  443.63
  5212.4  445.63  5273.1  446.95  5391.8  448.65  5519.9  452.67  5551.3  452.73
  5621.8  455.78  5725.4  458.34  5748.4  458.14  5771.5  459.52  5894.8  462.37
#Mann= 9 ,-1 , 0
  3900.7     .05       0    4176     .08       0  4230.2     .05       0
  4369.1     .08       0  4468.3     .05       0  4997.9     .04       0
  5003.9     .05       0  5273.1     .08       0  5519.9     .05       0
Bank Sta=4997.9,5003.9
XS Rating Curve= 0 ,0
Exp/Cntr=0.3,0.1

Type RM Length L Ch R = 1 ,28065   ,142,142,142
BEGIN DESCRIPTION:
UNT0083 IN CHRS 49.1
END DESCRIPTION:
XS GIS Cut Line= 5
      3483688.83     10540681.23      3483224.43     10539852.26
      3482959.67     10539383.51      3482716.62     10538958.17
      3482707.93      10538971.2
#Sta/Elev= 30
  3900.7  443.03  3942.7  444.04  4037.8  443.61    4176  444.38  4230.2  444.34
  4324.3  443.93  4369.1  444.58  4468.3  444.58  4726.9  443.81  4823.9  441.47
    4889  441.11  4926.5  439.53  4948.2  439.85    4997  437.42  4999.8  436.92
    5003  437.42  5023.3  439.52  5044.9  439.64  5066.6  441.56  5169.1  443.63
  5212.4  445.63  5273.1  446.95  5391.8  448.65  5519.9  452.67  5551.3  452.73
  5621.8  455.78  5725.4  458.34  5748.4  458.14  5771.5  459.52  5894.8  462.37
#Mann= 9 ,-1 , 0
  3900.7     .05       0    4176     .08       0  4230.2     .05       0
  4369.1     .08       0  4468.3     .05       0    4997     .04       0
    5003     .05       0  5273.1     .08       0  5519.9     .05       0
Bank Sta=4997,5003
XS Rating Curve= 0 ,0
Exp/Cntr=0.3,0.1

Type RM Length L Ch R = 1 ,27923   ,1508,1508,1508
BEGIN DESCRIPTION:
UNT0083 IN CHRS 49.4
END DESCRIPTION:
XS GIS Cut Line= 4
       3483743.1     10540601.82      3483289.97      10539851.8
      3483243.09     10539580.96      3482883.71     10538971.58
#Sta/Elev= 30
  4050.8  442.91  4123.7  443.43  4191.2   442.7  4319.7  443.83  4356.5  443.18
    4504   444.4  4657.3  443.61  4678.6  444.39    4700  443.98  4728.6  445.45
  4758.2   443.4  4816.4  444.05  4929.7  441.67    4997  437.12  4999.8  436.62
    5003  437.12  5008.4  438.17  5018.6  438.63  5122.4  439.72  5191.1  443.44
  5323.1  445.16  5333.2  444.58  5370.3  446.55  5413.3  446.68    5444  447.82
  5556.3  451.01  5727.5  454.02  5801.7  456.44  5880.6  457.52  5909.4  458.58
#Mann= 7 ,-1 , 0
  4050.8     .05       0    4997    .035       0    5003     .05       0
  5323.1     .08       0    5444     .05       0  5556.3     .08       0
  5880.6     .05       0
Bank Sta=4997,5003
XS Rating Curve= 0 ,0
Exp/Cntr=0.3,0.1

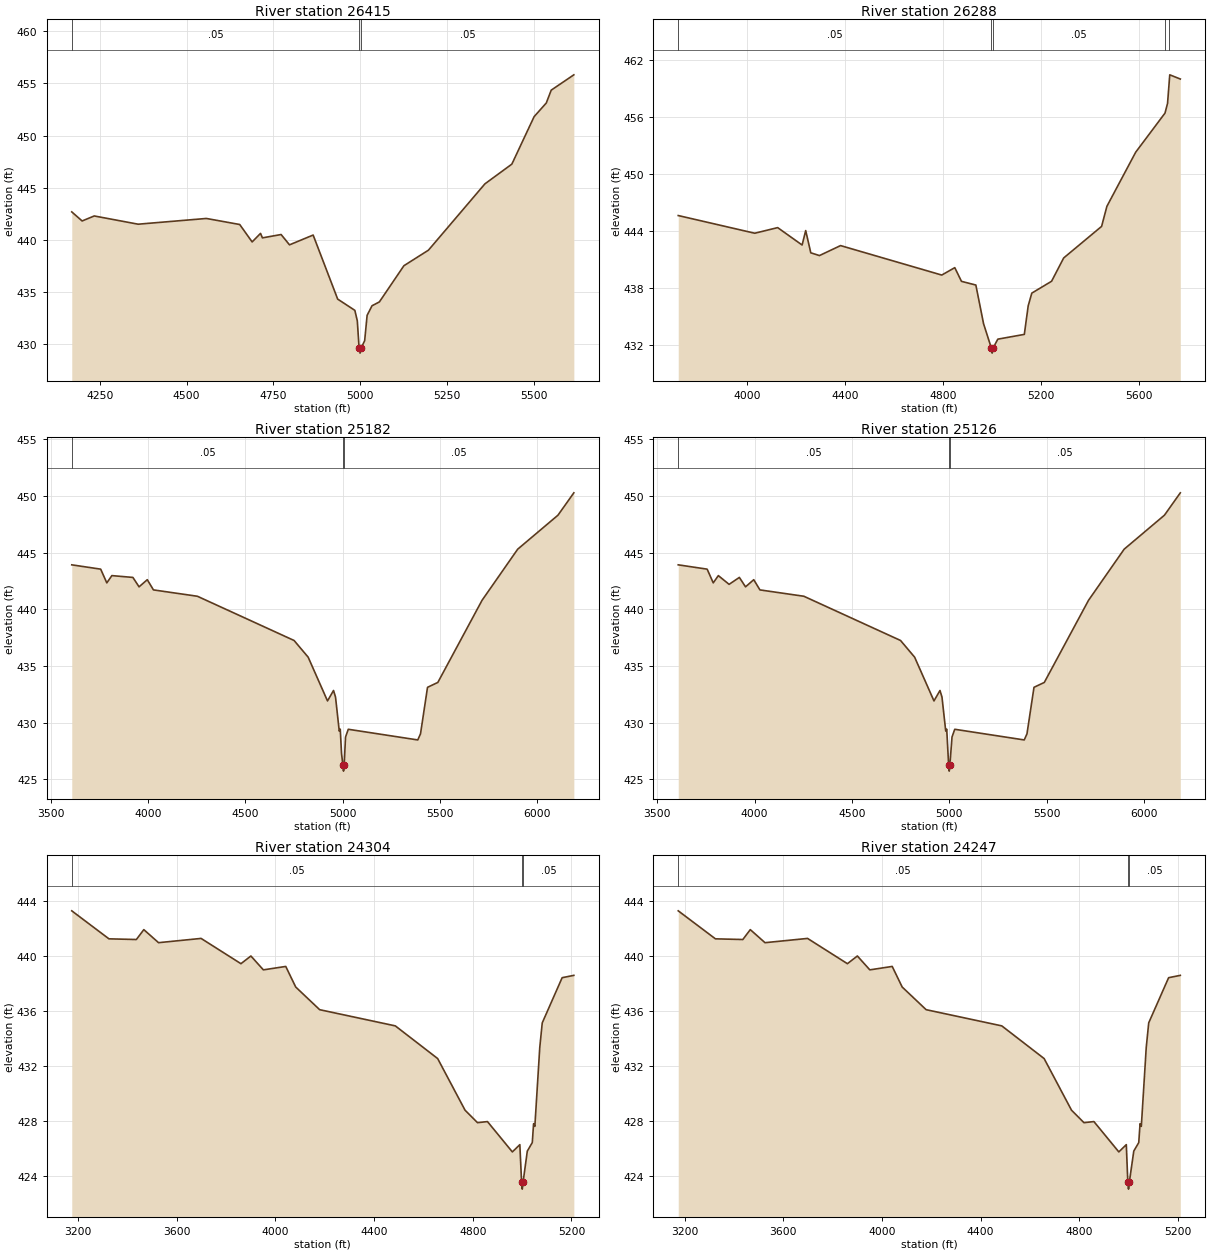
Type RM Length L Ch R = 1 ,26415   ,1289,1289,1289
BEGIN DESCRIPTION:
UNT0083 IN CHRS 49.0
END DESCRIPTION:
XS GIS Cut Line= 4
      3483784.74       10540831.      3484034.76     10540205.96
      3484305.59     10539935.13      3484571.24     10539648.64
#Sta/Elev= 30
    4169  442.69  4198.8  441.82  4233.8   442.3  4360.3  441.51  4556.9  442.06
    4653  441.48  4688.8  439.81    4713  440.63  4718.4   440.2  4772.3  440.52
  4796.5  439.53  4864.6  440.47  4935.3  434.33  4984.8  433.25  4991.9  432.24
    4997  429.65  4999.8  429.15    5003  429.65  5013.1  430.34  5020.1  432.77
  5034.3  433.69  5055.5  434.06  5126.2  437.53  5196.9  439.02  5359.7  445.38
  5437.3  447.27  5501.4  451.82  5536.5  453.13  5550.7  454.36  5615.9  455.83
#Mann= 3 ,-1 , 0
    4169     .05       0    4997     .04       0    5003     .05       0
Bank Sta=4997,5003
XS Rating Curve= 0 ,0
Exp/Cntr=0.3,0.1

Type RM Length L Ch R = 1 ,26288   ,1106,1106,1106
BEGIN DESCRIPTION:
UNT0083 IN CHRS 47.0
END DESCRIPTION:
XS GIS Cut Line= 3
      3483272.96     10541071.43      3484123.68     10540429.05
      3484617.02     10539576.51
#Sta/Elev= 30
  3717.4  445.65    4030  443.79  4123.6  444.38  4223.5  442.55  4238.1  444.07
  4258.9  441.73  4294.3  441.44  4380.5  442.49    4794  439.39  4847.1  440.17
  4874.4  438.73  4933.2  438.34  4964.7  434.27  4996.9  431.68  4999.7  431.18
  5002.9  431.68    5023  432.65  5131.2  433.15    5147  436.15  5161.7  437.49
  5242.6  438.74    5292  441.19  5446.9  444.51  5468.5  446.62  5586.1  452.31
    5706  456.43  5716.3  457.45    5722  459.35  5725.3  460.45  5768.4  460.01
#Mann= 5 ,-1 , 0
  3717.4     .05       0  4996.9    .035       0  5002.9     .05       0
    5706     .08       0    5722     .05       0
Bank Sta=4996.9,5002.9
XS Rating Curve= 0 ,0
Exp/Cntr=0.3,0.1

Type RM Length L Ch R = 1 ,25182   ,878,878,878
BEGIN DESCRIPTION:
UNT0083 IN CHRS 46.0
END DESCRIPTION:
XS GIS Cut Line= 4
      3483524.73     10541153.87      3484635.83     10540776.27
      3485486.53      10540563.6       3485689.8     10540074.87
#Sta/Elev= 30
  3607.5  443.92  3756.1  443.54  3787.5  442.33  3813.6  442.97  3921.6  442.81
  3953.3  441.98  3995.5  442.61  4027.2  441.71  4252.9  441.15  4749.7  437.25
  4822.1  435.78  4921.5  431.92  4952.4  432.84  4962.7  432.26  4981.9  429.26
    4987  429.43  4993.6  427.27  5000.9  426.23  5003.7  425.73  5006.9  426.23
  5014.2  428.74  5028.3  429.42  5385.3  428.48  5399.4  429.02  5435.4  433.12
  5488.4  433.55  5715.5  440.79  5898.7   445.3  6105.8   448.3  6187.2  450.27
#Mann= 3 ,-1 , 0
  3607.5     .05       0  5000.9    .035       0  5006.9     .05       0
Bank Sta=5000.9,5006.9
XS Rating Curve= 0 ,0
Exp/Cntr=0.3,0.1

Type RM Length L Ch R = 1 ,25126   ,879,879,879
BEGIN DESCRIPTION:
UNT0083 IN CHRS 46.0
END DESCRIPTION:
XS GIS Cut Line= 4
      3483524.73     10541153.87      3484635.83     10540776.27
      3485486.53      10540563.6       3485689.8     10540074.87
#Sta/Elev= 30
  3607.5  443.92  3756.1  443.54  3787.5  442.33  3813.6  442.97  3868.8   442.2
  3921.6  442.81  3953.3  441.98  3995.5  442.61  4027.2  441.71  4252.9  441.15
  4749.7  437.25  4822.1  435.78  4921.5  431.92  4952.4  432.84  4962.7  432.26
  4981.9  429.26    4987  429.43    4997  426.23  4999.8  425.73    5003  426.23
  5014.2  428.74  5028.3  429.42  5385.3  428.48  5399.4  429.02  5435.4  433.12
  5488.4  433.55  5715.5  440.79  5898.7   445.3  6105.8   448.3  6187.2  450.27
#Mann= 3 ,-1 , 0
  3607.5     .05       0    4997    .035       0    5003     .05       0
Bank Sta=4997,5003
XS Rating Curve= 0 ,0
Exp/Cntr=0.3,0.1

Type RM Length L Ch R = 1 ,24304   ,457,457,457
BEGIN DESCRIPTION:
UNT0083 IN CHRS 45.0
END DESCRIPTION:
XS GIS Cut Line= 2
      3483702.72     10541205.95      3485719.02      10540924.1
#Sta/Elev= 30
  3173.9  443.32  3324.7  441.28  3435.8  441.23  3466.1  441.95  3525.8     441
  3698.3  441.31  3859.9  439.47  3900.3  440.03  3950.8  439.02  4041.6  439.27
    4082  437.77  4179.1  436.12  4485.9  434.94  4657.6  432.56  4768.6   428.8
  4819.1  427.89  4859.5  427.97  4960.5  425.76  4990.8  426.29  4997.9  423.55
  5000.6  423.05  5003.9  423.55  5021.1  425.82  5041.3  426.44  5046.6  427.82
  5051.7  427.62  5071.6  433.36  5081.7  435.16  5162.4  438.45  5209.8  438.62
#Mann= 3 ,-1 , 0
  3173.9     .05       0  4997.9    .035       0  5003.9     .05       0
Bank Sta=4997.9,5003.9
XS Rating Curve= 0 ,0
Exp/Cntr=0.3,0.1

Type RM Length L Ch R = 1 ,24247   ,456,456,456
BEGIN DESCRIPTION:
UNT0083 IN CHRS 45.0
END DESCRIPTION:
XS GIS Cut Line= 2
      3483702.72     10541205.95      3485719.02      10540924.1
#Sta/Elev= 30
  3173.9  443.32  3324.7  441.28  3435.8  441.23  3466.1  441.95  3525.8     441
  3698.3  441.31  3859.9  439.47  3900.3  440.03  3950.8  439.02  4041.6  439.27
    4082  437.77  4179.1  436.12  4485.9  434.94  4657.6  432.56  4768.6   428.8
  4819.1  427.89  4859.5  427.97  4960.5  425.76  4990.8  426.29    4997  423.55
  4999.8  423.05    5003  423.55  5021.1  425.82  5041.3  426.44  5046.6  427.82
  5051.7  427.62  5071.6  433.36  5081.7  435.16  5162.4  438.45  5209.8  438.62
#Mann= 3 ,-1 , 0
  3173.9     .05       0    4997    .035       0    5003     .05       0
Bank Sta=4997,5003
XS Rating Curve= 0 ,0
Exp/Cntr=0.3,0.1

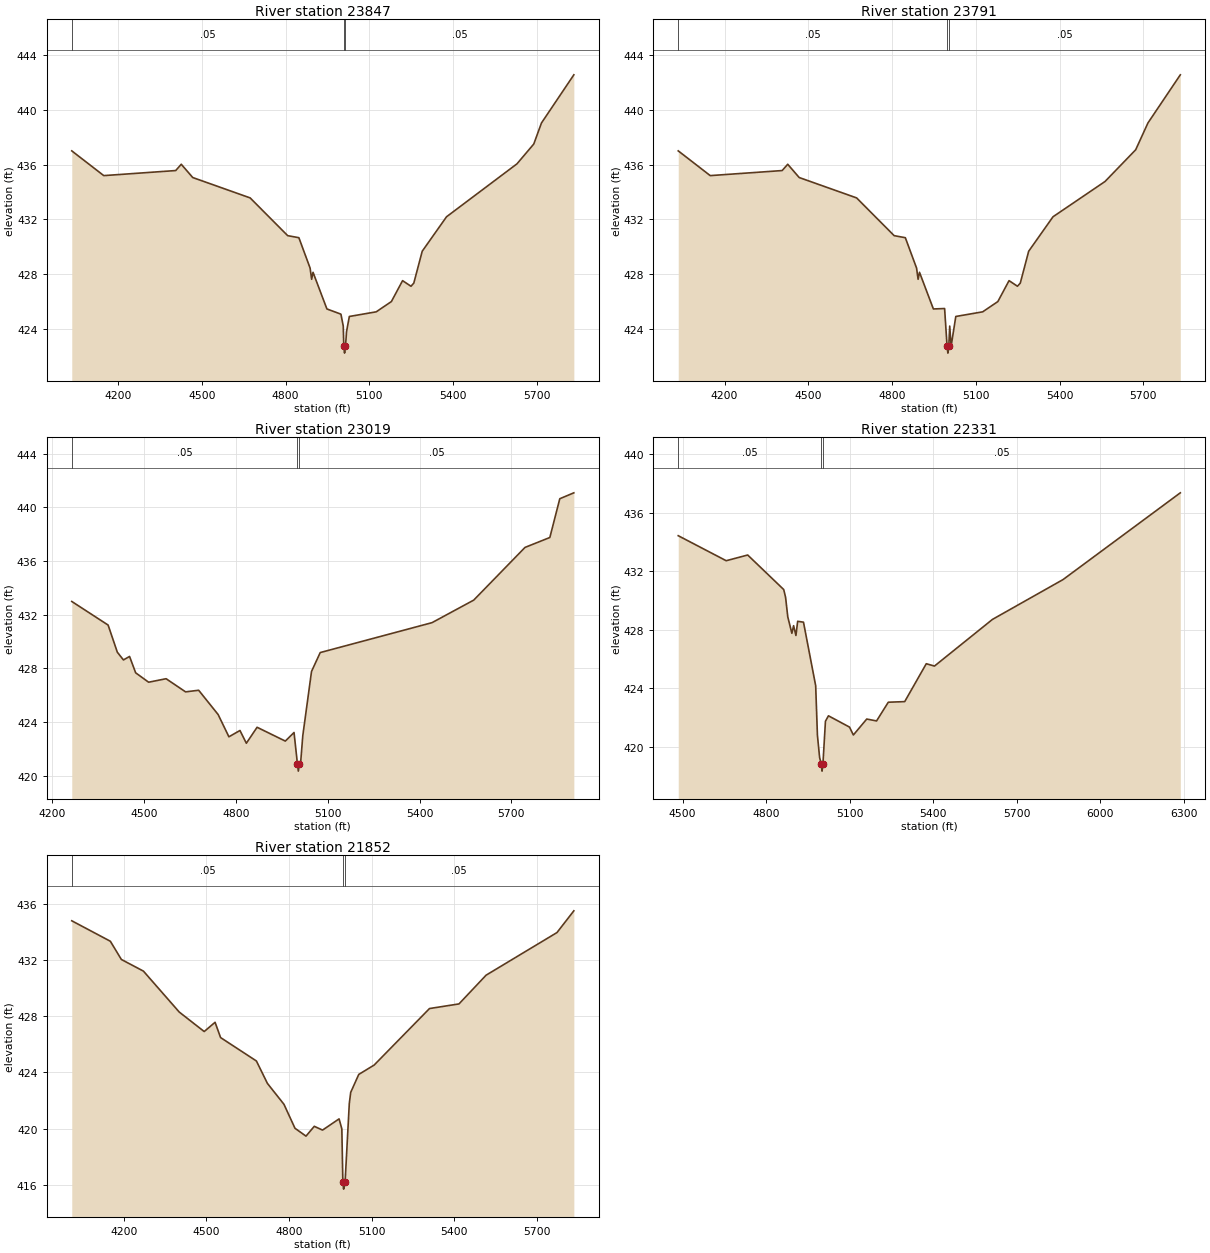
Type RM Length L Ch R = 1 ,23847   ,828,828,828
BEGIN DESCRIPTION:
UNT0083 IN CHRS 44.0
END DESCRIPTION:
XS GIS Cut Line= 4
      3484601.13     10541179.92      3485308.57     10541357.87
      3485859.79     10541310.12      3486102.25      10540855.5
#Sta/Elev= 30
  4034.2  437.01  4148.8   435.2  4406.4  435.57  4426.3  436.03  4467.4  435.06
    4673  433.57  4807.4  430.81  4847.5  430.66  4887.7  428.44  4893.2  427.62
  4898.2  428.13  4947.9  425.45  4998.1  425.07  5006.4   424.2  5008.4  422.72
  5011.1  422.22  5014.4  422.72  5018.2  423.79  5028.2   424.9  5124.5  425.24
  5178.8  425.99  5218.9  427.52    5249  427.11  5259.1  427.34  5289.2  429.67
  5376.3  432.19  5628.5  436.06  5688.7  437.51  5716.3  439.05  5832.2  442.57
#Mann= 3 ,-1 , 0
  4034.2     .05       0  5008.4    .035       0  5014.4     .05       0
Bank Sta=5008.4,5014.4
XS Rating Curve= 0 ,0
Exp/Cntr=0.3,0.1

Type RM Length L Ch R = 1 ,23791   ,772,772,772
BEGIN DESCRIPTION:
UNT0083 IN CHRS 44.0
END DESCRIPTION:
XS GIS Cut Line= 4
      3484601.13     10541179.92      3485308.57     10541357.87
      3485859.79     10541310.12      3486102.25      10540855.5
#Sta/Elev= 30
  4034.2  437.01  4148.8   435.2  4406.4  435.57  4426.3  436.03  4467.4  435.06
    4673  433.57  4807.4  430.81  4847.5  430.66  4887.7  428.44  4893.2  427.62
  4898.2  428.13  4947.9  425.45  4988.1  425.48    4997  422.72  4999.8  422.22
    5003  422.72  5006.4   424.2  5011.4  422.72  5028.2   424.9  5124.5  425.24
  5178.8  425.99  5218.9  427.52    5249  427.11  5259.1  427.34  5289.2  429.67
  5376.3  432.19  5562.6  434.77  5672.4  437.09  5716.3  439.05  5832.2  442.57
#Mann= 3 ,-1 , 0
  4034.2     .05       0    4997    .035       0    5003     .05       0
Bank Sta=4997,5003
XS Rating Curve= 0 ,0
Exp/Cntr=0.3,0.1

Type RM Length L Ch R = 1 ,23019   ,688,688,688
BEGIN DESCRIPTION:
UNT0083 IN CHRS 43.0
END DESCRIPTION:
XS GIS Cut Line= 4
      3485412.74     10542360.49      3485412.74      10542126.1
      3486003.02     10541618.28      3486189.65     10541019.33
#Sta/Elev= 30
  4263.7  432.98  4382.5  431.22  4412.5   429.2  4432.5  428.62  4452.5  428.88
  4472.5  427.66  4514.8  426.96  4571.9  427.22  4635.5  426.24  4678.3  426.36
  4741.9  424.55  4777.1  422.89  4813.3  423.36  4834.1  422.41  4869.2   423.6
  4961.4  422.57  4989.9  423.21  5001.2  420.83  5003.9  420.33  5007.2  420.83
  5011.7  421.03  5018.5  422.97    5047  427.76  5075.5  429.17  5440.8   431.4
    5577  433.08  5744.6  437.01  5825.7  437.75  5858.2  440.64  5904.1  441.08
#Mann= 3 ,-1 , 0
  4263.7     .05       0  5001.2     .03       0  5007.2     .05       0
Bank Sta=5001.2,5007.2
XS Rating Curve= 0 ,0
Exp/Cntr=0.3,0.1

Type RM Length L Ch R = 1 ,22331   ,479,479,479
BEGIN DESCRIPTION:
UNT0083 IN CHRS 42.0
END DESCRIPTION:
XS GIS Cut Line= 3
      3485442.07     10542741.67      3485853.65     10542437.22
      3486342.12      10541241.6
#Sta/Elev= 30
  4484.2  434.42  4656.5  432.71  4733.7   433.1  4863.1  430.74  4869.8  430.21
  4877.7  428.87  4892.4  427.75  4898.6  428.27    4907   427.6  4913.2  428.57
  4934.1  428.51  4977.9  424.17  4984.2  420.78  4992.1  419.25    4998  418.83
  5000.8  418.33    5004  418.83    5013  421.74  5023.8  422.11  5099.4  421.34
  5113.3   420.8  5161.4  421.89  5196.6  421.76  5238.8  423.04  5297.7  423.08
  5375.2  425.67  5404.6  425.51    5613   428.7  5866.4  431.42  6287.7  437.35
#Mann= 3 ,-1 , 0
  4484.2     .05       0    4998     .03       0    5004     .05       0
Bank Sta=4998,5004
XS Rating Curve= 0 ,0
Exp/Cntr=0.3,0.1

Type RM Length L Ch R = 1 ,21852   ,945,945,945
BEGIN DESCRIPTION:
UNT0083 IN CHRS 41.0
END DESCRIPTION:
XS GIS Cut Line= 3
      3486192.11      10543191.6      3486202.48     10542203.25
      3486392.11     10541391.61
#Sta/Elev= 30
  4011.8  434.82  4151.8  433.36  4191.8  432.06  4271.8  431.23  4401.8  428.31
  4492.4  426.92  4531.8  427.58  4551.8  426.49  4681.8  424.82  4721.8  423.22
  4781.8  421.73  4821.8  420.02  4861.8  419.46  4891.8  420.16  4921.8  419.89
  4981.8  420.69  4991.8  419.98  4995.5  416.18  4998.3  415.68  5001.5  416.18
  5003.6  416.18  5018.9  421.79    5024  422.58  5053.2  423.86  5109.1  424.53
  5309.9  428.56  5416.9  428.89  5515.3  430.94  5772.5  433.98  5833.7  435.53
#Mann= 3 ,-1 , 0
  4011.8     .05       0  4995.5     .03       0  5001.5     .05       0
Bank Sta=4995.5,5001.5
XS Rating Curve= 0 ,0
Exp/Cntr=0.3,0.1