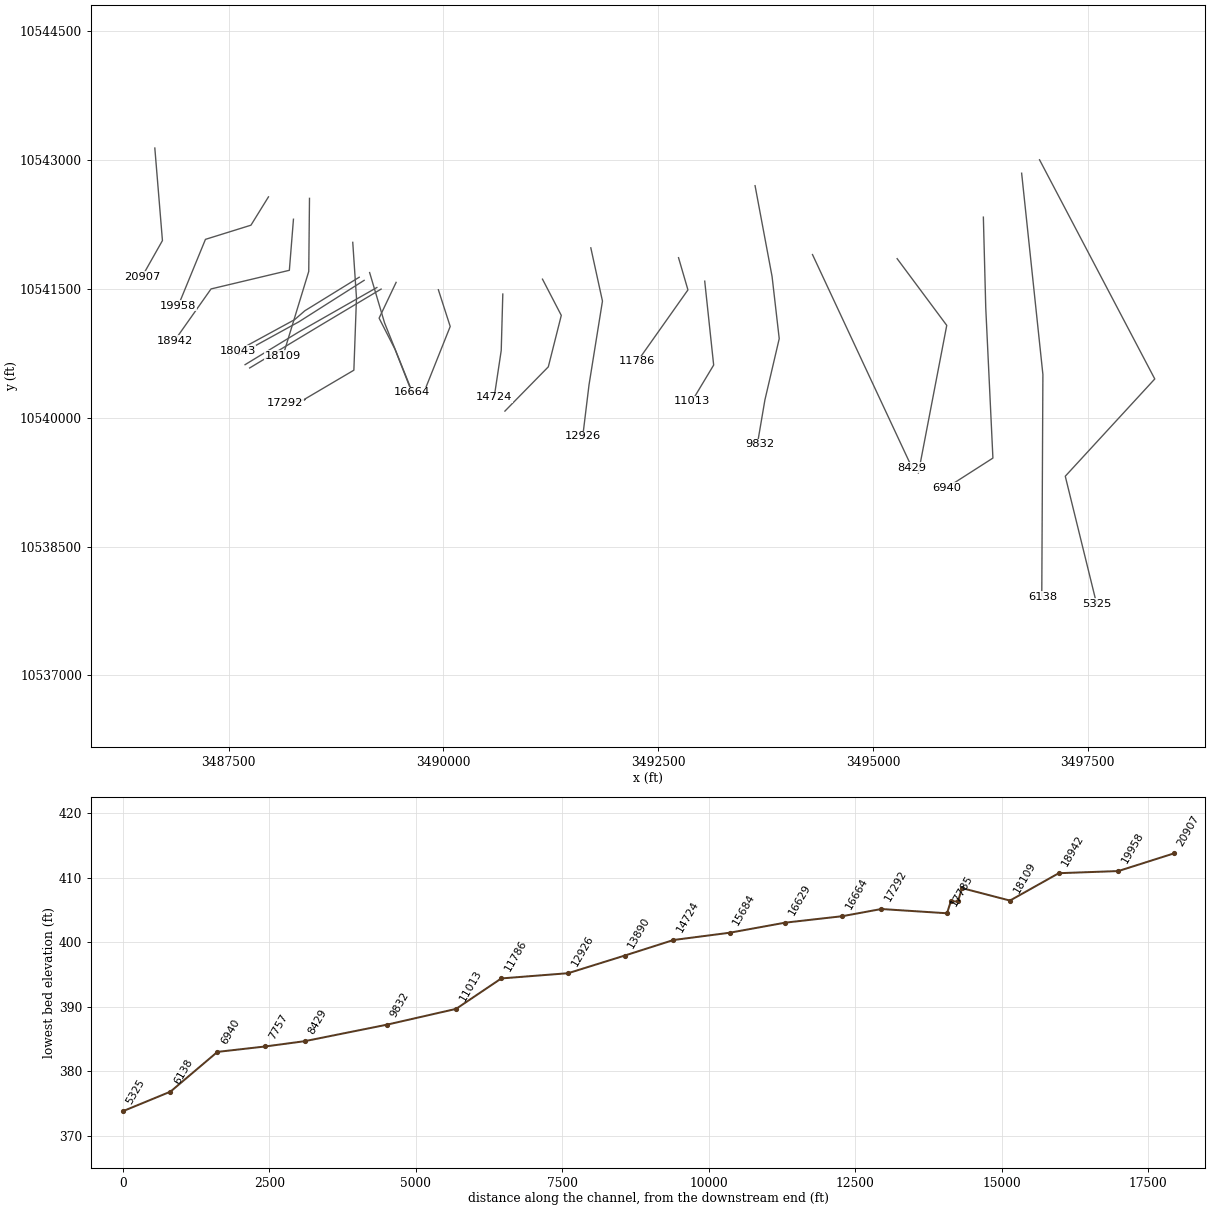
HEC-RAS study UNT0083 IN CHRS.prj: UNT0083 IN CHRS Base Level Engineering

--- UNT0083 IN CHRS.g01 (geometry) --- (continued)

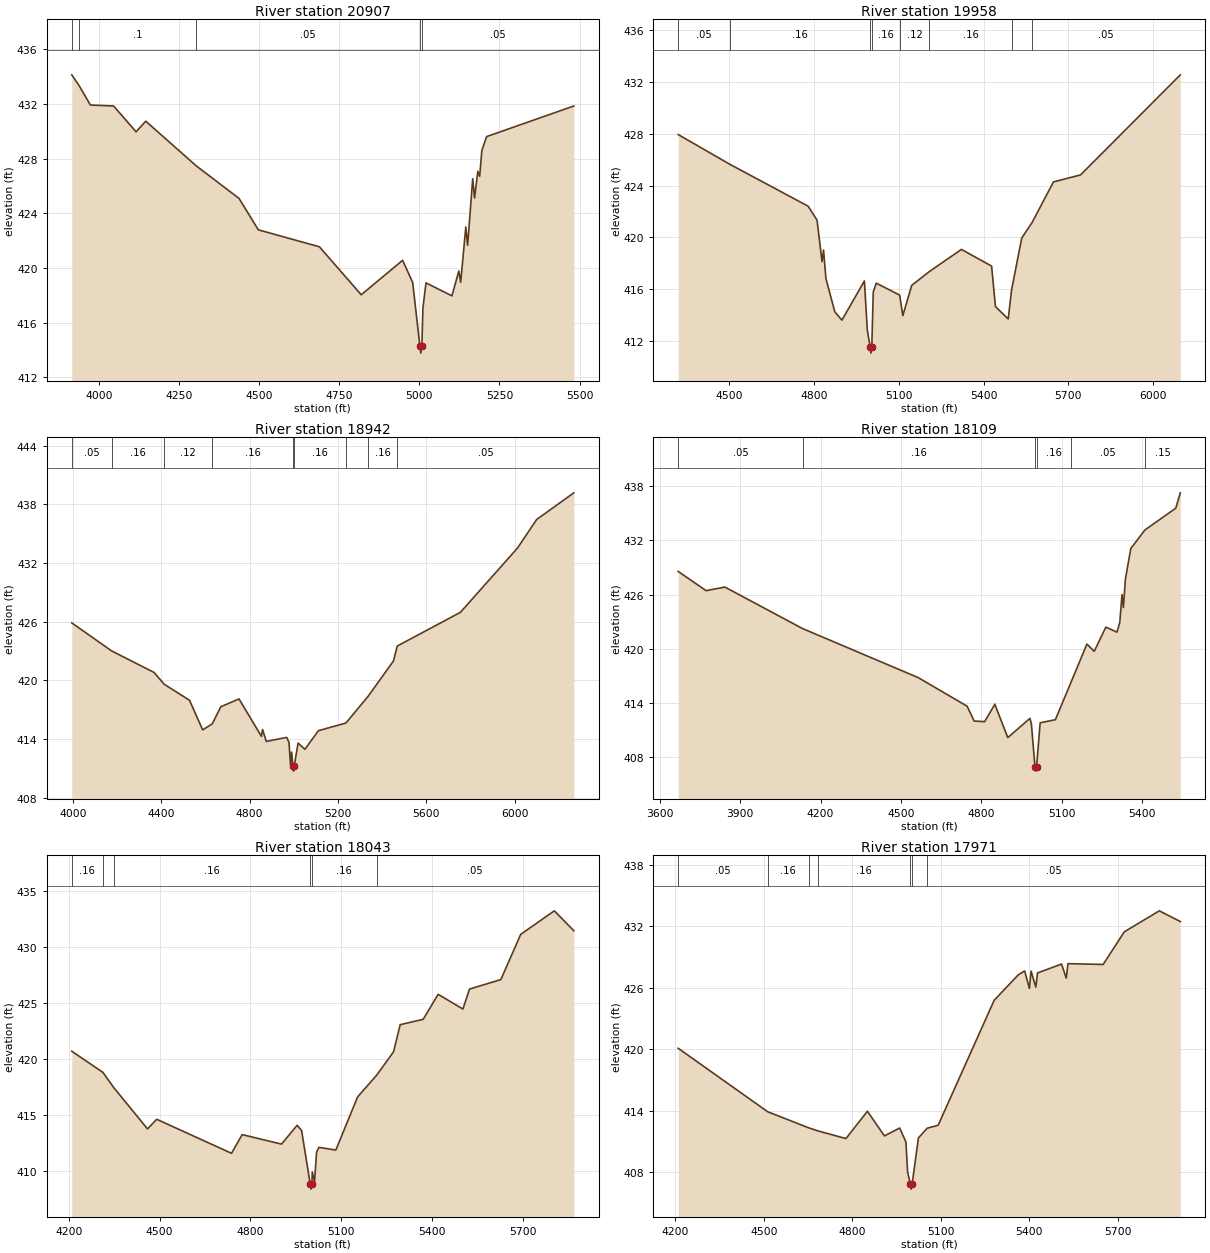
Type RM Length L Ch R = 1 ,20907   ,949,949,949
BEGIN DESCRIPTION:
UNT0083 IN CHRS 39.0
END DESCRIPTION:
XS GIS Cut Line= 3
       3486642.1     10543141.66      3486730.82     10542064.22
      3486492.12     10541641.67
#Sta/Elev= 30
  3915.8  434.14  3938.2  433.37  3973.9  431.93  4046.3  431.86  4116.5  429.97
  4146.6  430.75  4304.1  427.48  4437.6   425.1  4497.8   422.8  4688.4  421.56
  4818.9  418.05    4948  420.57  4979.4  418.95    5002  414.28  5004.8  413.78
    5008  414.28  5011.3  417.07  5020.9  418.92  5101.8  417.97  5123.4  419.79
  5129.2  418.96  5145.1  423.01  5150.8  421.67  5166.7  426.54  5172.5  425.13
  5182.6  427.08  5188.4  426.72  5195.1  428.59    5210  429.62  5482.2  431.86
#Mann= 5 ,-1 , 0
  3915.8     .05       0  3938.2      .1       0  4304.1     .05       0
    5002     .03       0    5008     .05       0
Bank Sta=5002,5008
XS Rating Curve= 0 ,0
Exp/Cntr=0.3,0.1

Type RM Length L Ch R = 1 ,19958   ,1016,1016,1016
BEGIN DESCRIPTION:
UNT0083 IN CHRS 38.0
END DESCRIPTION:
XS GIS Cut Line= 4
      3487964.84     10542573.17      3487760.83     10542243.28
      3487231.32     10542078.35      3486914.66     10541306.24
#Sta/Elev= 30
  4319.4  427.94  4501.4  425.65  4779.3   422.4  4810.7  421.32  4828.4  418.11
  4833.7  419.01  4842.1  416.81  4873.5  414.24  4898.7  413.59  4978.3  416.62
  4988.7  412.81  4998.5  411.54  5001.3  411.04  5004.5  411.54  5009.7  415.77
  5020.2  416.45    5103  415.53  5114.4  413.94  5145.8  416.28  5207.7  417.34
  5321.7  419.06  5428.5  417.77  5442.1  414.64  5487.3  413.68  5499.3  415.94
  5535.2  419.94  5572.4  421.16  5647.4  424.28  5743.3  424.82  6096.4  432.56
#Mann= 8 ,-1 , 0
  4319.4     .05       0  4501.4     .16       0  4998.5     .07       0
  5004.5     .16       0    5103     .12       0  5207.7     .16       0
  5499.3     .12       0  5572.4     .05       0
Bank Sta=4998.5,5004.5
XS Rating Curve= 0 ,0
Exp/Cntr=0.3,0.1

Type RM Length L Ch R = 1 ,18942   ,833,833,833
BEGIN DESCRIPTION:
UNT0083 IN CHRS 36.0
END DESCRIPTION:
XS GIS Cut Line= 4
      3488255.62     10542312.74      3488207.88     10541718.11
      3487296.42      10541501.1      3486871.05     10540897.76
#Sta/Elev= 30
  3995.3  425.88  4175.8  423.01  4367.6  420.81  4413.2  419.61  4528.1  417.96
  4587.6  414.93  4631.4  415.56  4669.7   417.3    4752   418.1  4853.4  414.27
  4858.6  414.97  4875.3  413.75  4967.8  414.16  4978.1  413.66    4985  411.39
  4990.1  412.66  4995.7  411.21  4998.4  410.71  5001.7  411.21  5019.2  413.58
  5050.1  412.94  5111.4  414.85  5235.6  415.63  5336.3  418.37    5451  421.99
    5468  423.51  5753.8  426.96  6012.5  433.55  6098.7  436.46    6267  439.19
#Mann= 9 ,-1 , 0
  3995.3     .05       0  4175.8     .16       0  4413.2     .12       0
  4631.4     .16       0  4995.7     .07       0  5001.7     .16       0
  5235.6     .12       0  5336.3     .16       0    5468     .05       0
Bank Sta=4995.7,5001.7
XS Rating Curve= 0 ,0
Exp/Cntr=0.3,0.1

Type RM Length L Ch R = 1 ,18109   ,817,817,817
BEGIN DESCRIPTION:
UNT0083 IN CHRS 34.0
END DESCRIPTION:
XS GIS Cut Line= 3
      3488442.25      10542555.8      3488433.57     10541705.09
      3488134.46     10540725.39
#Sta/Elev= 30
  3668.5  428.56  3772.7  426.43  3842.7  426.83  4133.3  422.23  4564.7  416.81
  4747.3  413.65  4773.8     412  4812.9  411.94  4850.9  413.86  4899.3  410.17
  4982.1   412.3  4987.4   411.7  5000.8  406.96  5003.6  406.46  5006.8  406.96
  5020.2  411.81    5077  412.15  5135.9  416.33  5194.7  420.52  5222.2  419.72
  5265.5   422.4    5307  421.84  5317.5  422.89  5325.9     426  5331.1  424.57
  5338.4  427.69  5358.7  431.09  5411.1  433.14  5526.6  435.56  5543.6  437.26
#Mann= 6 ,-1 , 0
  3668.5     .05       0  4133.3     .16       0  5000.8     .07       0
  5006.8     .16       0  5135.9     .05       0  5411.1     .15       0
Bank Sta=5000.8,5006.8
XS Rating Curve= 0 ,0
Exp/Cntr=0.3,0.1

Type RM Length L Ch R = 1 ,18043   ,72,72,72
BEGIN DESCRIPTION:
UNT0083 IN CHRS 34.0
END DESCRIPTION:
XS GIS Cut Line= 4
      3489020.68     10541637.39      3488387.85     10541246.76
      3488268.06     10541142.59      3487605.53     10540781.45
#Sta/Elev= 30
  4210.3  420.71  4313.1  418.82  4348.8  417.46  4460.3  413.77  4490.7  414.63
  4737.5  411.59  4772.7  413.26  4902.5  412.41    4954  414.09  4968.8  413.63
    4997  408.89  4999.8  408.39    5003  408.89  5003.9  409.93  5011.6  409.07
  5018.2  411.67  5025.8  412.12  5081.8  411.88  5153.7  416.63  5216.4  418.56
  5272.3  420.66  5294.2  423.08  5370.1  423.56  5419.5  425.79  5501.2  424.48
    5523  426.26  5626.5  427.11    5692  431.15  5802.9  433.25  5867.3  431.47
#Mann= 6 ,-1 , 0
  4210.3     .16       0  4313.1     .05       0  4348.8     .16       0
    4997     .07       0    5003     .16       0  5216.4     .05       0
Bank Sta=4997,5003
XS Rating Curve= 0 ,0
Exp/Cntr=0.3,0.1

Type RM Length L Ch R = 1 ,17971   ,120,120,120
BEGIN DESCRIPTION:
UNT0083 IN CHRS 34.1
END DESCRIPTION:
XS GIS Cut Line= 3
      3489077.96     10541600.93      3488320.14     10541119.15
      3487615.78     10540731.88
#Sta/Elev= 30
  4210.1  420.08  4513.3  413.88  4652.1  412.31  4683.7  412.01  4778.6  411.26
  4851.4  413.93    4909  411.52  4960.7  412.29  4981.8  410.93  4987.7  407.97
    4997  406.82  4999.8  406.32    5003  406.82  5024.2  411.32    5054  412.27
  5091.1  412.56    5281  424.77  5362.5  427.25  5384.3  427.64  5400.4  425.93
  5406.1  427.62  5422.2  426.06  5427.9  427.44  5509.3  428.31  5525.4  426.93
  5531.1  428.35  5650.4  428.27  5722.1  431.46  5840.8  433.51  5911.9  432.46
#Mann= 7 ,-1 , 0
  4210.1     .05       0  4513.3     .16       0  4652.1     .05       0
  4683.7     .16       0    4997     .07       0    5003     .16       0
    5054     .05       0
Bank Sta=4997,5003
XS Rating Curve= 0 ,0
Exp/Cntr=0.3,0.1

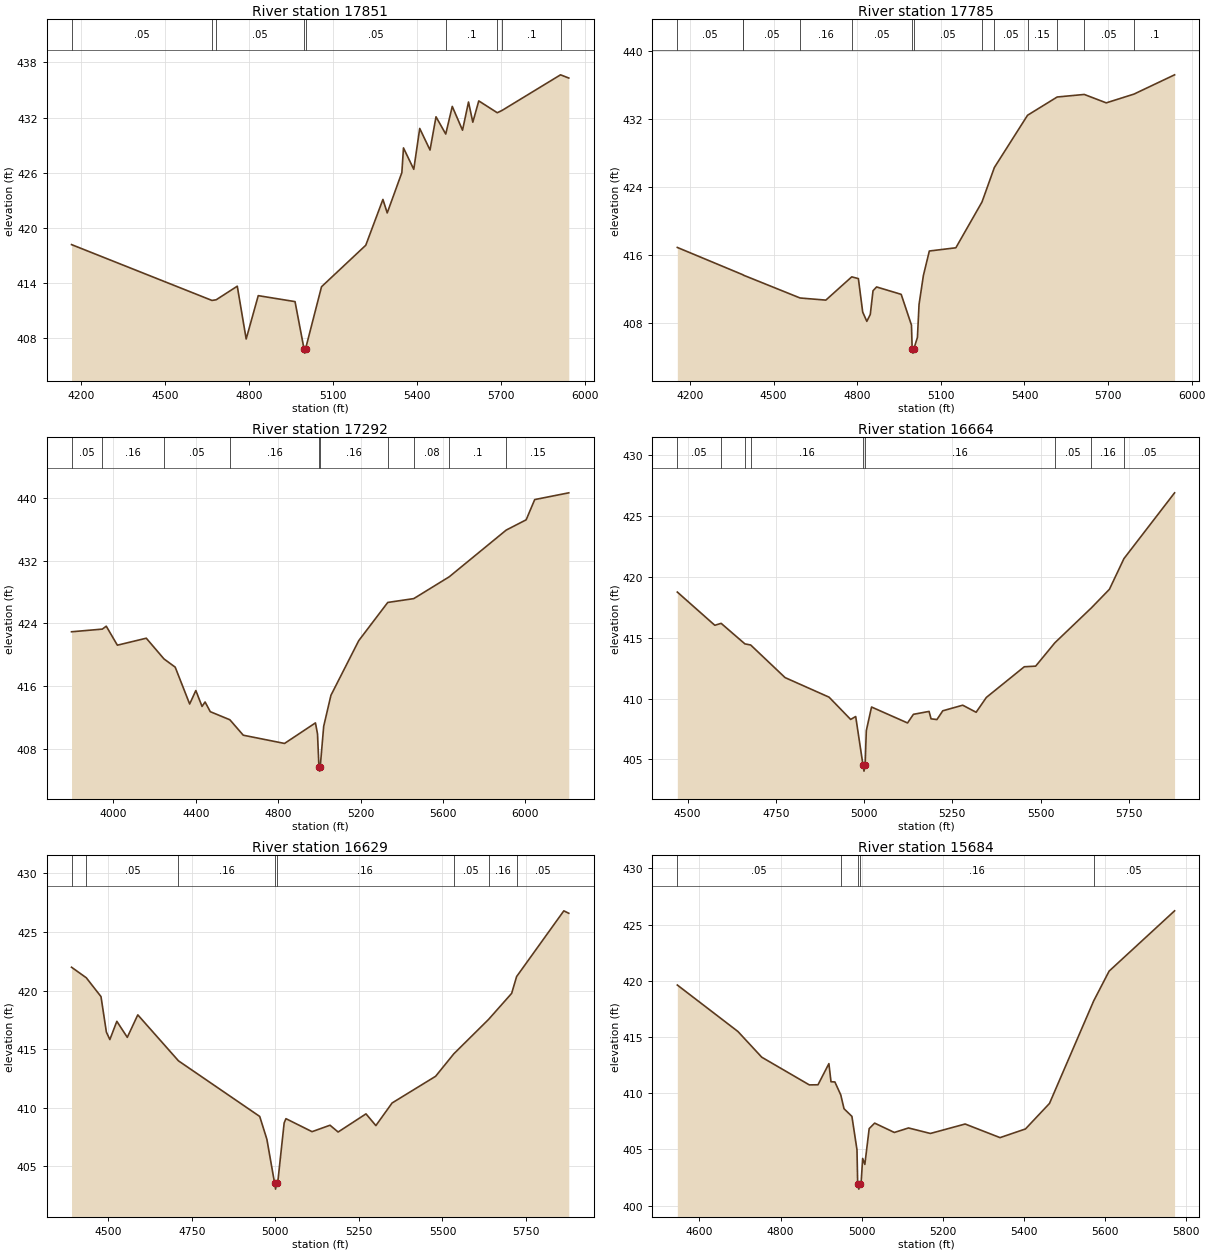
Type RM Length L Ch R = 1 ,17851   ,66,66,66
BEGIN DESCRIPTION:
UNT0083 IN CHRS 34.2
END DESCRIPTION:
XS GIS Cut Line= 3
      3489226.36     10541517.57      3488312.33     10540996.76
      3487692.51     10540619.13
#Sta/Elev= 30
    4166  418.16    4668  412.08  4683.2  412.15  4758.6  413.63  4790.4  407.88
  4833.6   412.6  4965.1  411.95    4997  406.84  4999.8  406.34    5003  406.84
  5059.8  413.57    5218  418.09  5279.3  423.08  5294.7  421.61    5347     426
  5352.8  428.69  5389.6  426.36  5410.9  430.81  5447.7  428.46  5469.1  432.08
  5503.9   430.2  5527.2  433.21  5563.9  430.62  5585.3  433.69  5600.7  431.49
    5622  433.81  5688.2  432.52  5705.6  432.78  5914.3  436.65  5943.8   436.3
#Mann= 9 ,-1 , 0
    4166     .05       0    4668     .16       0  4683.2     .05       0
    4997     .04       0    5003     .05       0  5503.9      .1       0
  5688.2     .05       0  5705.6      .1       0  5914.3     .05       0
Bank Sta=4997,5003
XS Rating Curve= 0 ,0
Exp/Cntr=0.3,0.1

Type RM Length L Ch R = 1 ,17785   ,1121,1121,1121
BEGIN DESCRIPTION:
UNT0083 IN CHRS 34.3
END DESCRIPTION:
XS GIS Cut Line= 3
      3489275.89     10541499.37      3488583.16      10541085.3
      3487745.84     10540580.82
#Sta/Elev= 30
  4154.2  416.93  4389.9  413.71  4391.1  413.67  4594.8  410.98  4687.2  410.73
  4780.2  413.47    4804  413.26  4819.5  409.32  4834.3  408.23  4846.7  409.04
  4856.5  411.83  4869.3  412.28  4957.6  411.41  4994.5  407.79    4997  404.99
  4999.8  404.49    5003  404.99  5015.9  406.34  5021.7  410.22  5037.3  413.63
  5058.6  416.51  5153.8  416.89  5247.6  422.28    5292  426.34  5411.1  432.49
  5517.4  434.64  5614.6  434.94  5693.6  433.95  5792.9  434.98  5938.8  437.25
#Mann= 13 ,-1 , 0
  4154.2     .05       0  4389.9     .16       0  4391.1     .05       0
  4594.8     .16       0  4780.2     .05       0    4997     .04       0
    5003     .05       0  5247.6     .08       0    5292     .05       0
  5411.1     .15       0  5517.4      .1       0  5614.6     .05       0
  5792.9      .1       0
Bank Sta=4997,5003
XS Rating Curve= 0 ,0
Exp/Cntr=0.3,0.1

Type RM Length L Ch R = 1 ,17292   ,663,663,663
BEGIN DESCRIPTION:
UNT0083 IN CHRS 32.0
END DESCRIPTION:
XS GIS Cut Line= 6
      3488945.73     10542043.61      3488989.13     10541396.93
      3488958.75     10540554.91      3488377.15     10540212.03
      3488390.17     10540212.03      3488159.27      10540172.1
#Sta/Elev= 30
  3797.1  422.92  3946.5  423.26  3965.7  423.63  4019.6  421.21  4159.9   422.1
  4245.7  419.46  4300.2  418.41  4370.4  413.71  4400.4  415.43  4430.5   413.4
  4445.2  413.97  4470.5  412.73  4565.5   411.7  4630.6  409.73  4830.8  408.68
  4980.9   411.3  4990.9  409.89  4997.9  405.65  5000.6  405.15  5003.9  405.65
  5020.9  410.87    5056  414.82    5191  421.79  5331.7  426.66    5458  427.15
    5630  429.93  5906.7  435.89  6003.5   437.2    6045  439.78  6210.3  440.64
#Mann= 10 ,-1 , 0
  3797.1     .05       0  3946.5     .16       0  4245.7     .05       0
  4565.5     .16       0  4997.9     .07       0  5003.9     .16       0
  5331.7     .05       0    5458     .08       0    5630      .1       0
  5906.7     .15       0
Bank Sta=4997.9,5003.9
XS Rating Curve= 0 ,0
Exp/Cntr=0.3,0.1

Type RM Length L Ch R = 1 ,16664   ,980,980,980
BEGIN DESCRIPTION:
UNT0083 IN CHRS 31.0
END DESCRIPTION:
XS GIS Cut Line= 4
      3489450.36     10541577.51      3489252.44     10541160.82
      3489437.33     10540798.84      3489634.64     10540295.18
#Sta/Elev= 30
    4471  418.76  4577.2  416.03  4595.1  416.19  4662.5   414.5  4678.8  414.41
  4776.2  411.73  4900.9  410.12    4962  408.29  4976.3  408.53    4997  404.54
  4999.8  404.04    5003  404.54  5006.4  407.37  5021.2  409.31  5123.2     408
  5139.8  408.71  5184.2  408.95  5189.8  408.34  5206.4  408.28    5223     409
  5279.5  409.46  5317.5  408.88  5346.5   410.1  5453.9  412.62  5486.1  412.67
  5540.5  414.59  5644.3  417.47  5695.1  418.99  5736.2  421.51  5879.7  426.92
#Mann= 9 ,-1 , 0
    4471     .05       0  4595.1     .16       0  4662.5     .05       0
  4678.8     .16       0    4997     .07       0    5003     .16       0
  5540.5     .05       0  5644.3     .16       0  5736.2     .05       0
Bank Sta=4997,5003
XS Rating Curve= 0 ,0
Exp/Cntr=0.3,0.1

Type RM Length L Ch R = 1 ,16629   ,945,945,945
BEGIN DESCRIPTION:
UNT0083 IN CHRS 31.0
END DESCRIPTION:
XS GIS Cut Line= 3
      3489142.12      10541691.6      3489316.11     10541105.45
      3489642.11     10540291.64
#Sta/Elev= 30
    4390  421.99  4434.2  421.09  4478.2  419.48  4494.3  416.45  4504.7  415.81
  4525.6  417.37  4556.9     416  4588.3  417.92  4710.1  413.99  4953.2  409.24
  4974.6  407.29  4997.8  403.53  5000.6  403.03  5003.8  403.53  5007.5   403.7
  5026.3  408.68  5031.7  409.05  5109.8  407.94  5163.6  408.49  5187.8  407.91
  5271.2  409.46  5300.8  408.46  5349.3  410.39  5479.5  412.67    5534  414.59
    5638  417.53  5707.2  419.76  5721.9  421.19  5863.3  426.81  5878.1   426.6
#Mann= 8 ,-1 , 0
    4390     .16       0  4434.2     .05       0  4710.1     .16       0
  4997.8     .07       0  5003.8     .16       0    5534     .05       0
    5638     .16       0  5721.9     .05       0
Bank Sta=4997.8,5003.8
XS Rating Curve= 0 ,0
Exp/Cntr=0.3,0.1

Type RM Length L Ch R = 1 ,15684   ,960,960,960
BEGIN DESCRIPTION:
UNT0083 IN CHRS 29.0
END DESCRIPTION:
XS GIS Cut Line= 3
       3489942.1     10541491.65      3490079.99     10541063.78
      3489792.09      10540341.6
#Sta/Elev= 30
  4545.3  419.62  4694.8  415.49  4753.7   413.2    4871  410.74  4892.4  410.75
  4919.3  412.63  4924.5  411.02  4934.1     411  4948.6  409.85  4956.6  408.62
  4976.1  407.94  4988.6  404.97  4990.3  401.97  4993.1  401.47  4996.3  401.97
  4998.7  401.97  5002.6   404.2    5008  403.67  5018.7  406.85  5032.2  407.34
  5080.8  406.51  5115.8  406.91  5169.7  406.42  5255.5  407.26  5341.6  406.05
  5404.3  406.82  5463.6  409.09  5572.7  418.21  5610.8  420.86  5772.3  426.22
#Mann= 5 ,-1 , 0
  4545.3     .05       0  4948.6     .16       0  4990.3     .07       0
  4996.3     .16       0  5572.7     .05       0
Bank Sta=4990.3,4996.3
XS Rating Curve= 0 ,0
Exp/Cntr=0.3,0.1

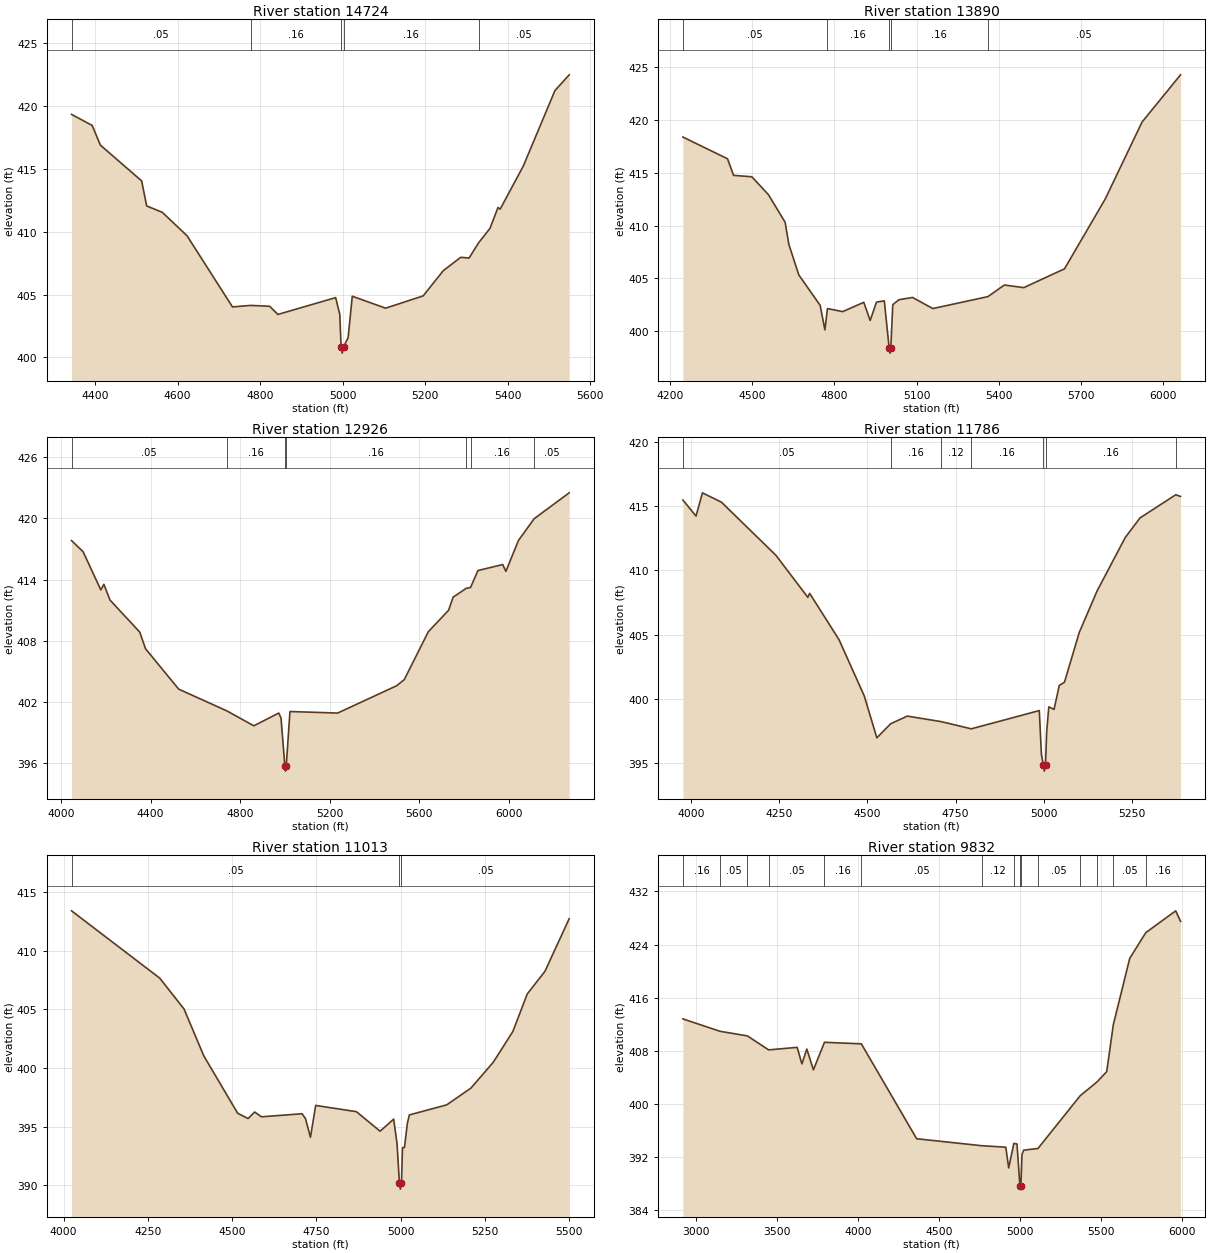
Type RM Length L Ch R = 1 ,14724   ,834,834,834
BEGIN DESCRIPTION:
UNT0083 IN CHRS 27.0
END DESCRIPTION:
XS GIS Cut Line= 3
      3490692.11     10541441.63      3490673.74     10540784.27
      3490592.11     10540241.69
#Sta/Elev= 30
  4343.1  419.35  4393.1  418.47  4413.1   416.9  4513.1  414.05  4525.2  412.06
  4563.2  411.55  4623.2  409.68  4733.2  404.02  4777.5  404.14  4823.3  404.07
  4843.3  403.42  4983.3  404.76  4993.3  403.43  4996.5  400.84  4999.3  400.34
  5002.5  400.84  5013.5  401.57  5023.6  404.87  5104.5  403.92  5195.5   404.9
    5244   406.9  5286.5  407.97  5306.7  407.91  5329.7  409.12  5357.3  410.27
  5376.9  411.94    5382   411.8  5438.2  415.24  5514.9  421.25  5549.4   422.5
#Mann= 5 ,-1 , 0
  4343.1     .05       0  4777.5     .16       0  4996.5     .07       0
  5002.5     .16       0  5329.7     .05       0
Bank Sta=4996.5,5002.5
XS Rating Curve= 0 ,0
Exp/Cntr=0.3,0.1

Type RM Length L Ch R = 1 ,13890   ,964,964,964
BEGIN DESCRIPTION:
UNT0083 IN CHRS 25.0
END DESCRIPTION:
XS GIS Cut Line= 4
      3491154.07      10541614.8      3491372.81     10541192.94
      3491221.77     10540593.98      3490716.83     10540078.63
#Sta/Elev= 30
    4248  418.38  4410.8  416.32  4432.9  414.75  4499.4  414.62    4560  412.92
  4620.8  410.31  4634.5   408.2  4670.7  405.32  4748.4  402.45  4765.8  400.12
  4775.1  402.14  4830.6  401.85  4907.6  402.73  4930.8  401.01  4953.8  402.75
  4982.4  402.87    5000  398.42  5002.7  397.92    5006  398.42  5013.3  402.51
  5035.9  402.98  5085.5  403.19  5159.2  402.14  5360.1  403.27  5420.1  404.37
  5490.8  404.12  5639.3   405.9  5787.8  412.51  5922.1   419.8  6062.4  424.27
#Mann= 5 ,-1 , 0
    4248     .05       0  4775.1     .16       0    5000     .07       0
    5006     .16       0  5360.1     .05       0
Bank Sta=5000,5006
XS Rating Curve= 0 ,0
Exp/Cntr=0.3,0.1

Type RM Length L Ch R = 1 ,12926   ,1140,1140,1140
BEGIN DESCRIPTION:
UNT0083 IN CHRS 24.0
END DESCRIPTION:
XS GIS Cut Line= 4
      3491716.56     10541979.42      3491851.98      10541359.6
      3491695.73     10540385.64      3491622.81     10539786.71
#Sta/Elev= 30
  4046.3  417.82    4098  416.73  4177.1  412.98  4190.9  413.53    4218  411.99
  4351.1  408.84  4376.8  407.21  4525.1  403.24  4740.9   401.1    4861  399.64
  4972.4  400.89  4982.5  400.41  4999.8  395.69  5002.5  395.19  5005.8  395.69
  5022.5  401.04  5235.7  400.89    5499  403.57  5533.3  404.17  5640.8  408.87
  5731.6  410.99  5751.8  412.27  5810.6  413.14  5829.5  413.21  5862.6  414.88
  5973.4  415.47  5987.6   414.8  6043.9  417.84    6114  419.97  6270.5  422.51
#Mann= 7 ,-1 , 0
  4046.3     .05       0  4740.9     .16       0  4999.8     .07       0
  5005.8     .16       0  5810.6     .12       0  5829.5     .16       0
    6114     .05       0
Bank Sta=4999.8,5005.8
XS Rating Curve= 0 ,0
Exp/Cntr=0.3,0.1

Type RM Length L Ch R = 1 ,11786   ,773,773,773
BEGIN DESCRIPTION:
UNT0083 IN CHRS 21.0
END DESCRIPTION:
XS GIS Cut Line= 3
      3492737.38     10541864.85      3492846.77     10541489.81
      3492258.27     10540656.54
#Sta/Elev= 30
  3977.1  415.47  4014.4  414.22  4032.5  416.03  4086.5   415.3  4240.9  411.17
  4331.3   407.9  4336.5  408.21  4419.9   404.6  4491.3  400.23    4527  396.97
  4565.9  398.06  4613.2  398.66  4709.6  398.23  4794.7  397.67  4987.5  399.09
  4993.6  395.65  4999.1  394.88  5001.9  394.38  5005.1  394.88  5008.4  397.43
  5014.5  399.38  5029.3  399.18  5044.1  401.04  5058.9   401.3  5100.7  405.16
  5151.2  408.39  5231.3  412.56  5273.1  414.08  5374.4  415.88  5387.9  415.75
#Mann= 7 ,-1 , 0
  3977.1     .05       0  4565.9     .16       0  4709.6     .12       0
  4794.7     .16       0  4999.1     .07       0  5005.1     .16       0
  5374.4     .05       0
Bank Sta=4999.1,5005.1
XS Rating Curve= 0 ,0
Exp/Cntr=0.3,0.1

Type RM Length L Ch R = 1 ,11013   ,1181,1181,1181
BEGIN DESCRIPTION:
UNT0083 IN CHRS 20.0
END DESCRIPTION:
XS GIS Cut Line= 3
       3493042.1     10541591.68      3493146.18     10540614.56
      3492892.11     10540191.66
#Sta/Elev= 30
  4023.5  413.43    4285  407.68  4357.2  405.04  4415.7  401.04  4516.3  396.13
  4547.1  395.68  4566.6  396.24  4586.7  395.83  4707.4  396.09  4717.4  395.67
  4732.1  394.08  4747.6   396.8  4868.3  396.27  4938.7   394.6  4978.9  395.63
    4989  393.52    4996  390.15  4998.8  389.65    5002  390.15  5005.1   393.2
  5010.8   393.2  5019.6  395.28  5025.4  395.99  5136.2  396.85  5207.9  398.28
  5274.1  400.48  5332.4  403.12  5375.2  406.33  5427.6  408.26  5499.5  412.76
#Mann= 3 ,-1 , 0
  4023.5     .05       0    4996    .035       0    5002     .05       0
Bank Sta=4996,5002
XS Rating Curve= 0 ,0
Exp/Cntr=0.3,0.1

Type RM Length L Ch R = 1 ,9832    ,1403,1403,1403
BEGIN DESCRIPTION:
UNT0083 IN CHRS 18.0
END DESCRIPTION:
XS GIS Cut Line= 6
      3493628.01     10542703.39      3493825.94     10541646.06
      3493909.27      10540922.1       3493742.6     10540208.56
      3493659.27     10539718.98      3493685.29     10539692.96
#Sta/Elev= 30
  2919.7  412.81  3148.6  410.95  3317.9  410.25  3448.8  408.15  3624.9  408.53
    3654  406.04  3684.5  408.27  3725.1  405.15  3793.3  409.29  4020.8  409.06
  4362.2  394.78    4764  393.73    4912  393.51    4930   390.4  4961.9  394.08
  4981.3  393.99  4999.2   387.7    5002   387.2  5005.2   387.7  5012.1  392.42
  5022.4  393.06  5110.8  393.32  5370.8  401.24  5475.5  403.34  5534.9  404.88
  5575.7  411.95  5676.9  421.92  5776.1  425.79  5960.7  429.07  5990.3  427.49
#Mann= 15 ,-1 , 0
  2919.7     .16       0  3148.6     .05       0  3317.9     .16       0
  3448.8     .05       0  3793.3     .16       0  4020.8     .05       0
    4764     .12       0  4961.9     .16       0  4999.2     .07       0
  5005.2     .16       0  5110.8     .05       0  5370.8     .16       0
  5475.5     .07       0  5575.7     .05       0  5776.1     .16       0
Bank Sta=4999.2,5005.2
XS Rating Curve= 0 ,0
Exp/Cntr=0.3,0.1

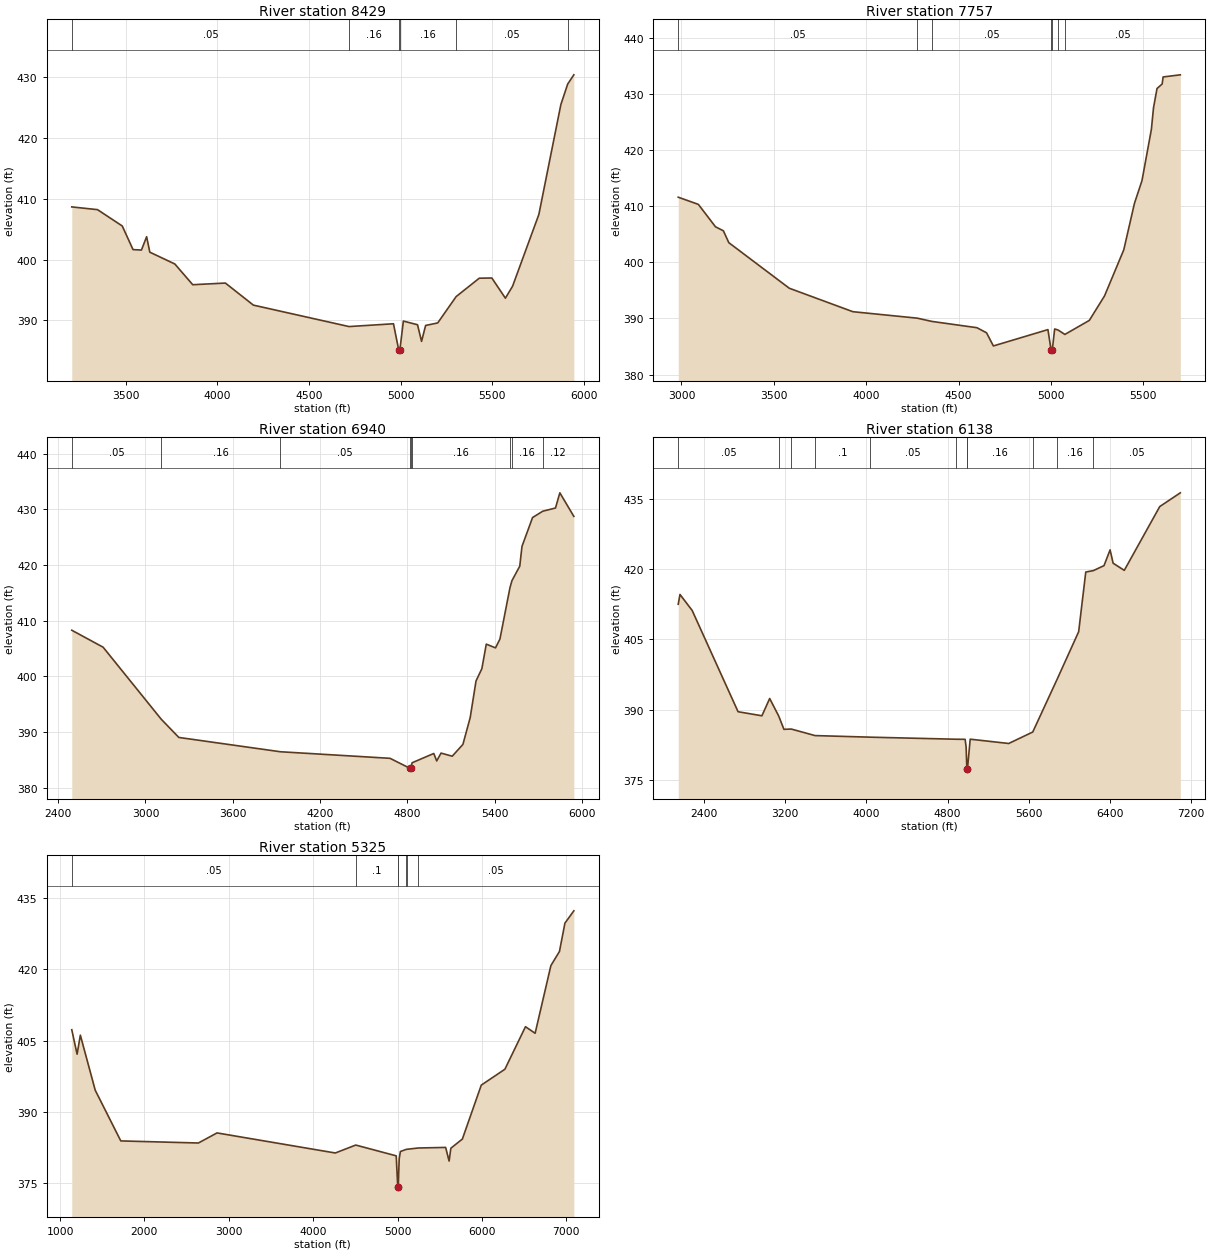
Type RM Length L Ch R = 1 ,8429    ,672,672,672
BEGIN DESCRIPTION:
UNT0083 IN CHRS 15.0
END DESCRIPTION:
XS GIS Cut Line= 2
       3494296.4     10541901.31      3495455.26     10539418.66
#Sta/Elev= 30
  3206.1  408.64  3346.6  408.19  3481.6  405.51  3540.5  401.63  3586.3  401.56
  3614.6  403.75    3632  401.21  3768.6  399.27  3866.1  395.87  4044.5  396.14
  4197.1  392.52  4719.2     389  4961.6  389.46  4990.5  385.14  4993.3  384.64
  4996.5  385.14  5015.6   389.9  5092.9   389.3  5114.9  386.57    5137  389.18
  5203.2   389.6  5303.6  393.92  5429.8  396.94  5498.4  396.97  5572.4  393.66
  5611.5  395.62    5755   407.4  5875.1  425.44  5912.4  428.81  5945.9  430.32
#Mann= 6 ,-1 , 0
  3206.1     .05       0  4719.2     .16       0  4990.5     .07       0
  4996.5     .16       0  5303.6     .05       0  5912.4      .1       0
Bank Sta=4990.5,4996.5
XS Rating Curve= 0 ,0
Exp/Cntr=0.3,0.1

Type RM Length L Ch R = 1 ,7757    ,817,817,817
BEGIN DESCRIPTION:
UNT0083 IN CHRS 13.0
END DESCRIPTION:
XS GIS Cut Line= 3
      3495281.68      10541853.5      3495858.92     10541076.62
      3495529.06     10539357.84
#Sta/Elev= 30
  2982.7   411.6  3091.7  410.32  3184.3  406.33  3227.2  405.61  3256.5   403.5
  3583.9  395.38  3928.2   391.2  4276.6  390.05  4355.6  389.47  4599.5  388.35
  4651.5  387.45  4688.8   385.1  4984.1  388.01  5001.4  384.32  5004.2  383.82
  5007.4  384.32  5020.5  388.12  5038.9  387.94  5075.8  387.15  5208.1  389.65
  5290.6  394.02  5394.6  402.22  5452.5  410.51  5493.2  414.55  5544.1  423.68
  5555.6  427.53  5574.6  430.96  5602.5  431.77  5607.6  433.02  5700.7   433.4
#Mann= 7 ,-1 , 0
  2982.7     .05       0  4276.6     .16       0  4355.6     .05       0
  5001.4    .035       0  5007.4     .05       0  5038.9     .16       0
  5075.8     .05       0
Bank Sta=5001.4,5007.4
XS Rating Curve= 0 ,0
Exp/Cntr=0.3,0.1

Type RM Length L Ch R = 1 ,6940    ,802,802,802
BEGIN DESCRIPTION:
UNT0083 IN CHRS 11.0
END DESCRIPTION:
XS GIS Cut Line= 4
      3496285.14     10542337.01      3496312.91     10541281.48
      3496396.25     10539531.48      3495855.83     10539185.06
#Sta/Elev= 30
  2493.7  408.29  2709.1  405.24  3107.9  392.32  3229.3  389.03  3927.2  386.46
  4680.7  385.28  4817.9  383.48  4820.6  382.98  4823.9  383.48  4832.1  384.48
  4981.1  386.15  5001.1  384.81  5031.1  386.22  5107.8  385.66  5181.3  387.78
  5231.3  392.59  5271.4  399.18  5311.5  401.38  5341.9  405.79  5405.3  405.12
  5435.7  406.71  5504.4   415.9    5518  417.18  5571.9   419.8  5587.1  423.34
  5659.8  428.53    5730  429.67  5817.3  430.24  5847.4  432.97  5943.5  428.74
#Mann= 9 ,-1 , 0
  2493.7     .05       0  3107.9     .16       0  3927.2     .05       0
  4817.9     .07       0  4823.9     .05       0  4832.1     .16       0
  5504.4     .12       0    5518     .16       0    5730     .12       0
Bank Sta=4817.9,4823.9
XS Rating Curve= 0 ,0
Exp/Cntr=0.3,0.1

Type RM Length L Ch R = 1 ,6138    ,813,813,813
BEGIN DESCRIPTION:
UNT0083 IN CHRS 3.0
END DESCRIPTION:
XS GIS Cut Line= 4
      3496730.57     10542848.72      3496977.97     10540504.94
      3496964.95     10537926.82      3496977.57      10537914.2
#Sta/Elev= 30
  2143.6  412.54  2160.8  414.64  2281.4   411.2  2733.9  389.53  2969.1  388.66
  3045.7  392.36  3134.3  388.63  3186.4  385.76  3258.8  385.82  3493.1  384.42
  4039.9  384.08  4882.2  383.64  4973.7  383.62  4983.7  381.93  4990.7  377.31
  4993.5  376.81  4996.7  377.31  5023.7  383.65  5403.7  382.73  5640.7  385.18
  5883.8   396.6  6093.7  406.66  6163.7  419.44    6238  419.74  6343.7  420.81
  6403.7  424.19  6433.7  421.33  6543.7   419.8  6893.7  433.46  7096.4   436.4
#Mann= 11 ,-1 , 0
  2143.6     .05       0  3134.3     .16       0  3258.8     .05       0
  3493.1      .1       0  4039.9     .05       0  4882.2     .16       0
  4990.7     .07       0  4996.7     .16       0  5640.7     .05       0
  5883.8     .16       0    6238     .05       0
Bank Sta=4990.7,4996.7
XS Rating Curve= 0 ,0
Exp/Cntr=0.3,0.1

Type RM Length L Ch R = 1 ,5325    ,0,0,0
BEGIN DESCRIPTION:
UNT0083 IN CHRS 1.0
END DESCRIPTION:
XS GIS Cut Line= 4
      3496938.92     10543004.93      3498280.06     10540452.86
      3497238.39     10539320.05      3497602.85     10537836.19
#Sta/Elev= 30
  1139.3  407.29  1202.5  402.15    1241  406.15  1417.3  394.57  1720.3  383.91
    2640  383.47  2860.4  385.59  4262.4  381.37  4504.6  383.04  4984.3  380.77
  5002.3  374.27  5005.1  373.77  5008.3  374.27  5019.5  380.14  5033.7  381.68
  5105.8  382.15  5106.9  382.14  5245.2  382.42  5569.9  382.54  5611.1  379.68
  5631.7  382.37  5768.1   384.3  5992.1  395.64  6271.9  398.98  6516.1  407.93
  6630.5  406.55  6817.3  420.79  6918.8  423.75  6983.5  429.71  7089.2   432.3
#Mann= 7 ,-1 , 0
  1139.3     .05       0  4504.6      .1       0  5002.3     .07       0
  5008.3      .1       0  5105.8     .16       0  5106.9      .1       0
  5245.2     .05       0
Bank Sta=5002.3,5008.3
XS Rating Curve= 0 ,0
Exp/Cntr=0.3,0.1

Chan Stop Cuts=-1
Use User Specified Reach Order=0
Composite Channel Slope=5