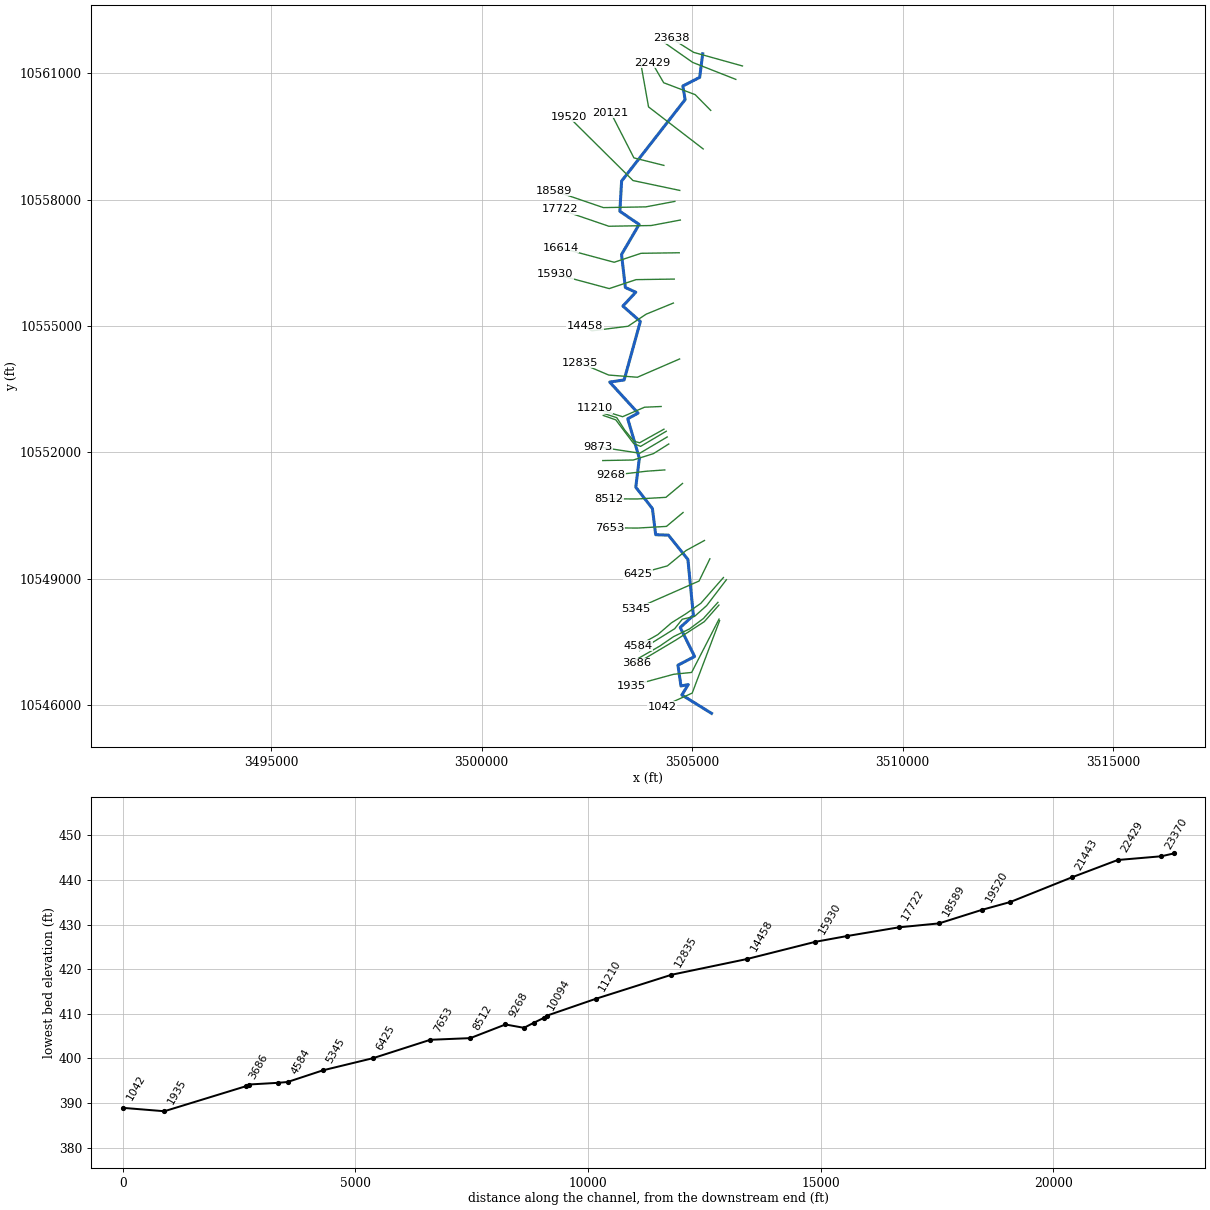
--- UNT0085 IN CHRS.prj (project) ---

Proj Title=UNT0085 IN CHRS Base Level Engineering
Current Plan=p01
Default Exp/Contr=0.3,0.1
English Units
Geom File=g01
Flow File=f01
Plan File=p01
BEGIN DESCRIPTION:
UNT0085 IN CHRS
END DESCRIPTION:

--- UNT0085 IN CHRS.p01 (plan) ---

Plan Title=Multiple Run
Short Identifier=Multiple
Geom File=g01
Flow File=f01
Subcritical Flow
K Sum by GR= 0
Std Step Tol= 0.01
Critical Tol= 0.01
Num of Std Step Trials= 20
Max Error Tol= 0.3
Flow Tol Ratio= 0.001
Split Flow NTrial= 30
Split Flow Tol= 0.02
Split Flow Ratio= 0.02
Log Output Level= 0
Friction Slope Method= 1
Unsteady Friction Slope Method= 2
Unsteady Bridges Friction Slope Method= 1
Parabolic Critical Depth
Global Vel Dist=  1 , 1 , 1
Global Log Level= 0
CheckData=True
Encroach Param= -1, 0, 0, 0
BEGIN DESCRIPTION:
Multiple Run
END DESCRIPTION:

--- UNT0085 IN CHRS.f01 (steady flow) ---

Flow Title=Multiple
Number of Profiles=7
Profile Names=10-year,25-year,50-year,1pct_min,100-year,1pct_plu,500-year
River Rch & RM= UNT0085 IN CHRS,Reach-1,23638
     450     565     649     542     733     992     934
River Rch & RM= UNT0085 IN CHRS,Reach-1,22429
     460     576     661     552     747    1010     950
River Rch & RM= UNT0085 IN CHRS,Reach-1,21443
     625     795     921     775    1049    1418    1357
River Rch & RM= UNT0085 IN CHRS,Reach-1,14458
     725     925    1075     907    1227    1659    1594
River Rch & RM= UNT0085 IN CHRS,Reach-1,9873
     857    1101    1285    1088    1472    1990    1927
River Rch & RM= UNT0085 IN CHRS,Reach-1,3754
     889    1144    1336    1132    1531    2070    2007
Boundary for River Rch & Prof#=UNT0085 IN CHRS,Reach-1,1
Up Type=0
Dn Type=3
Dn Slope=0.005
Boundary for River Rch & Prof#=UNT0085 IN CHRS,Reach-1,2
Up Type=0
Dn Type=3
Dn Slope=0.005
Boundary for River Rch & Prof#=UNT0085 IN CHRS,Reach-1,3
Up Type=0
Dn Type=3
Dn Slope=0.005
Boundary for River Rch & Prof#=UNT0085 IN CHRS,Reach-1,4
Up Type=0
Dn Type=3
Dn Slope=0.005
Boundary for River Rch & Prof#=UNT0085 IN CHRS,Reach-1,5
Up Type=0
Dn Type=3
Dn Slope=0.005
Boundary for River Rch & Prof#=UNT0085 IN CHRS,Reach-1,6
Up Type=0
Dn Type=3
Dn Slope=0.005
Boundary for River Rch & Prof#=UNT0085 IN CHRS,Reach-1,7
Up Type=0
Dn Type=3
Dn Slope=0.005

--- UNT0085 IN CHRS.g01 (geometry) ---

Geom Title=Existing Conditions

River Reach=UNT0085 IN CHRS,Reach-1
Reach XY= 30
      3505252.11     10561461.64      3505179.94     10560902.63
      3504780.05     10560697.80      3504834.46     10560375.42
      3503326.25     10558440.65      3503284.77     10557722.65
      3503742.59     10557411.68      3503324.74     10556697.02
      3503415.33     10555913.02      3503662.52     10555801.94
      3503357.01     10555472.88      3503771.39     10555106.82
      3503386.68     10553719.02      3503043.89     10553667.51
      3503717.52     10552930.55      3503471.61     10552796.75
      3503747.76     10551860.93      3503662.93     10551171.83
      3504057.62     10550664.50      3504135.05     10550043.48
      3504437.70     10550033.89      3504900.40     10549456.08
      3505030.13     10548128.23      3504718.50     10547840.91
      3505059.95     10547151.27      3504663.82     10546945.89
      3504735.71     10546452.31      3504909.52     10546486.09
      3504757.03     10546238.51      3505462.11     10545801.64

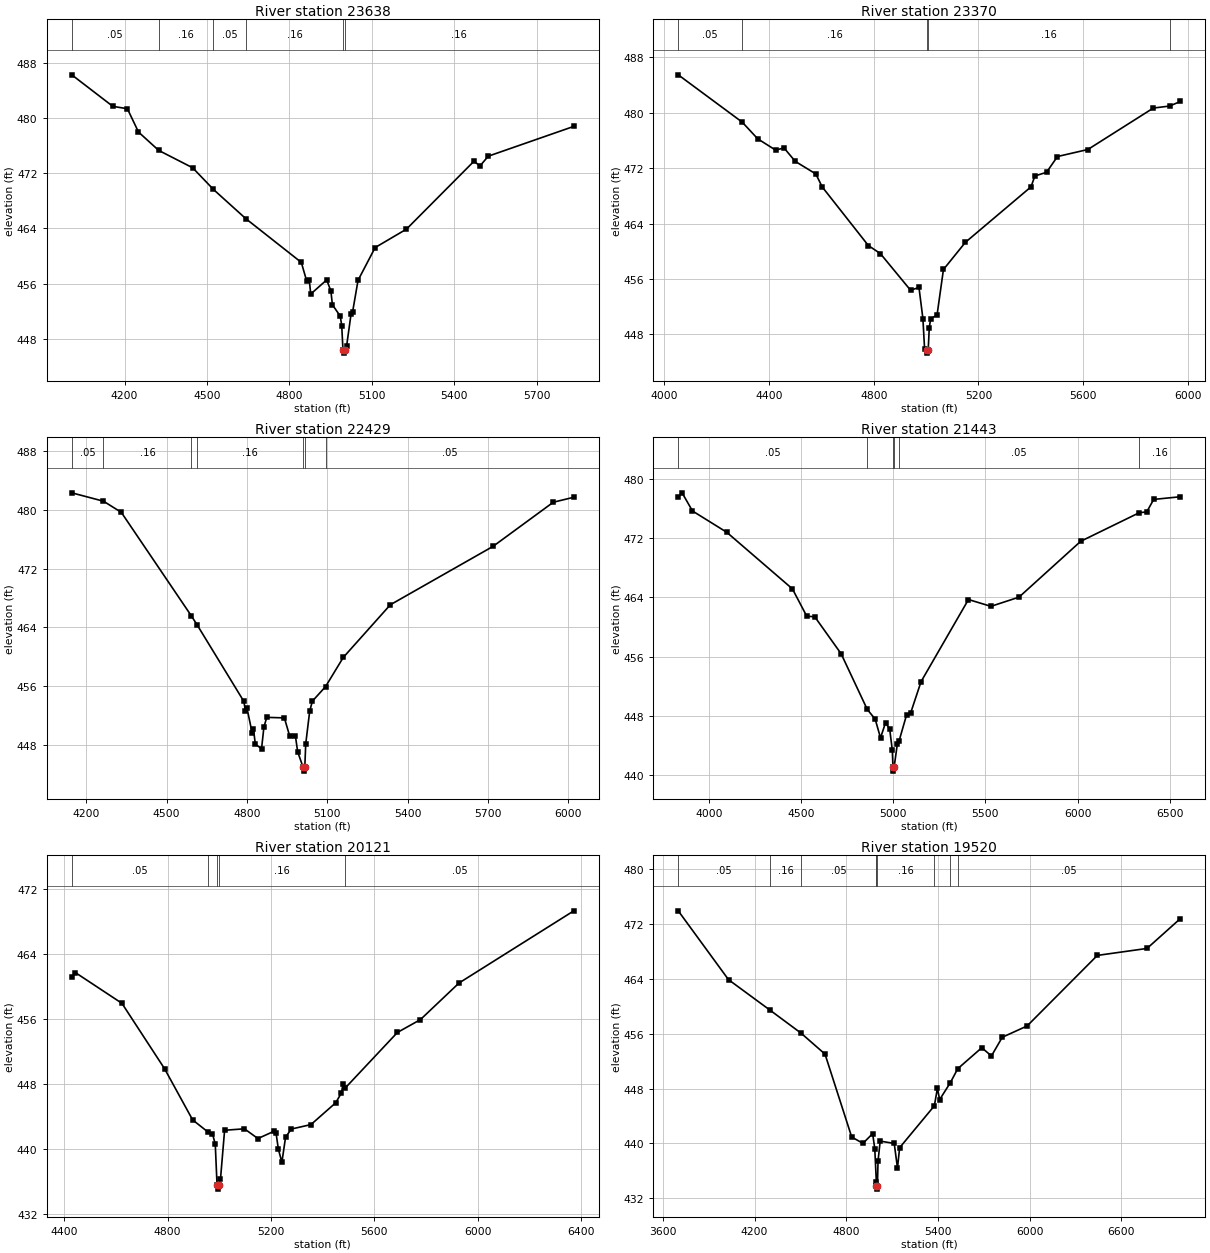
Type RM Length L Ch R = 1,23638,268,268,268
BEGIN DESCRIPTION:
UNT0085 IN CHRS 41.1
END DESCRIPTION:
XS GIS Cut Line= 3
      3506196.10     10561173.45      3505037.28     10561496.35
      3504508.66     10561829.67
#Sta/Elev= 30
  4007.7  486.26  4157.2  481.69  4210.1  481.35  4250.6  477.97  4324.1  475.31
  4447.8  472.79  4523.5  469.65  4641.5  465.41  4843.4  459.08  4863.1  456.36
  4872.4  456.58  4877.6  454.49  4935.8  456.54  4951.1  454.93  4956.5  452.95
  4985.3  451.28  4990.5  449.92  4995.0  446.43  4997.8  445.93  5001.0  446.43
  5008.4  446.98  5024.7  451.66  5029.9  451.85  5049.9  456.48  5112.2  461.23
  5226.3  463.90  5472.3  473.75  5493.5  473.04  5524.1  474.47  5835.6  478.79
#Mann=6,-1,0
  4007.7    0.05       0  4324.1    0.16       0  4523.5    0.05       0
  4641.5    0.16       0  4995.0    0.07       0  5001.0    0.16       0
Bank Sta=4995,5001
Exp/Cntr=0.3,0.1

Type RM Length L Ch R = 1,23370,941,941,941
BEGIN DESCRIPTION:
UNT0085 IN CHRS 41.0
END DESCRIPTION:
XS GIS Cut Line= 3
      3506038.24     10560854.98      3505013.91     10561257.77
      3504343.76     10561726.53
#Sta/Elev= 30
  4053.0  485.49  4297.6  478.65  4356.6  476.25  4424.9  474.62  4457.2  474.93
  4500.2  472.99  4578.7  471.17  4603.1  469.30  4779.5  460.83  4825.3  459.67
  4940.7  454.38  4972.9  454.77  4987.9  450.29  4994.4  445.85  5002.2  445.79
  5004.9  445.29  5008.2  445.79  5012.3  448.99  5017.6  450.25  5042.0  450.80
  5066.4  457.37  5150.4  461.30  5401.0  469.31  5415.8  470.88  5460.3  471.41
  5502.2  473.69  5618.1  474.70  5868.4  480.69  5930.7  480.98  5971.5  481.64
#Mann=5,-1,0
  4053.0    0.05       0  4297.6    0.16       0  5002.2    0.07       0
  5008.2    0.16       0  5930.7    0.05       0
Bank Sta=5002.2,5008.2
Exp/Cntr=0.3,0.1

Type RM Length L Ch R = 1,22429,986,986,986
BEGIN DESCRIPTION:
UNT0085 IN CHRS 39.0
END DESCRIPTION:
XS GIS Cut Line= 4
      3505441.42     10560119.51      3505072.47     10560492.80
      3504325.95     10560774.92      3504048.15     10561252.37
#Sta/Elev= 30
  4145.7  482.29  4264.2  481.15  4330.6  479.64  4592.9  465.53  4615.0  464.27
  4788.5  453.93  4794.2  452.64  4799.6  453.10  4819.1  449.70  4824.4  450.15
  4831.3  448.11  4854.6  447.50  4863.4  450.46  4874.1  451.76  4939.8  451.69
  4959.3  449.26  4981.0  449.23  4989.5  447.07  5010.0  444.95  5012.8  444.45
  5016.0  444.95  5019.6  448.17  5034.4  452.61  5044.5  453.97  5093.6  455.94
  5159.8  459.91  5335.6  467.07  5719.2  475.01  5944.2  481.01  6021.0  481.69
#Mann=7,-1,0
  4145.7    0.05       0  4264.2    0.16       0  4592.9    0.05       0
  4615.0    0.16       0  5010.0    0.07       0  5016.0    0.16       0
  5093.6    0.05       0
Bank Sta=5010,5016
Exp/Cntr=0.3,0.1

Type RM Length L Ch R = 1,21443,1322,1322,1322
BEGIN DESCRIPTION:
UNT0085 IN CHRS 37.0
END DESCRIPTION:
XS GIS Cut Line= 3
      3505263.47     10559203.71      3503965.70     10560202.00
      3503774.74     10561274.01
#Sta/Elev= 30
  3832.0  477.55  3852.9  478.12  3909.4  475.67  4095.8  472.79  4451.9  465.16
  4529.8  461.47  4573.3  461.39  4716.5  456.40  4858.3  448.89  4901.3  447.58
  4930.4  445.05  4957.5  447.09  4980.2  446.24  4994.4  443.38  4998.0  441.06
  5000.8  440.56  5004.0  441.06  5021.8  444.24  5031.3  444.65  5071.7  448.14
  5094.4  448.44  5150.5  452.64  5407.9  463.72  5529.9  462.80  5682.3  464.04
  6017.4  471.58  6335.7  475.44  6375.8  475.54  6413.6  477.23  6558.2  477.59
#Mann=6,-1,0
  3832.0    0.05       0  4858.3    0.16       0  4998.0    0.07       0
  5004.0    0.16       0  5031.3    0.05       0  6335.7    0.16       0
Bank Sta=4998,5004
Exp/Cntr=0.3,0.1

Type RM Length L Ch R = 1,20121,601,601,601
BEGIN DESCRIPTION:
UNT0085 IN CHRS 34.0
END DESCRIPTION:
XS GIS Cut Line= 3
      3504330.30     10558813.11      3503618.48     10558991.06
      3503067.47     10560067.06
#Sta/Elev= 30
  4429.6  461.15  4443.7  461.71  4623.6  457.93  4788.5  449.88  4897.2  443.57
  4957.2  442.06  4974.0  441.86  4984.8  440.58  4991.7  435.54  4994.4  435.04
  4997.7  435.54  5005.0  436.27  5020.9  442.29  5097.7  442.47  5149.8  441.27
  5212.4  442.17  5220.2  441.90  5229.0  439.95  5242.6  438.35  5256.8  441.44
  5279.0  442.44  5355.0  442.99  5451.0  445.68  5473.2  446.91  5478.8  447.98
  5487.8  447.50  5689.6  454.34  5778.5  455.92  5928.0  460.43  6372.2  469.32
#Mann=5,-1,0
  4429.6    0.05       0  4957.2    0.16       0  4991.7    0.07       0
  4997.7    0.16       0  5487.8    0.05       0
Bank Sta=4991.7,4997.7
Exp/Cntr=0.3,0.1

Type RM Length L Ch R = 1,19520,931,931,931
BEGIN DESCRIPTION:
UNT0085 IN CHRS 33.0
END DESCRIPTION:
XS GIS Cut Line= 3
      3504707.92     10558218.49      3503596.78     10558452.87
      3502069.51     10559967.12
#Sta/Elev= 30
  3700.3  473.94  4029.4  463.89  4302.2  459.42  4503.7  456.09  4661.1  453.02
  4835.7  440.92  4909.1  439.99  4972.7  441.41  4986.8  439.21  4996.9  434.40
  4998.0  433.81  5000.7  433.31  5004.0  433.81  5008.1  437.43  5022.2  440.32
  5114.1  439.98  5135.3  436.39  5149.5  439.36  5376.6  445.47  5396.9  448.04
  5411.1  446.37  5481.5  448.86  5529.9  450.89  5686.9  453.95  5750.5  452.76
  5821.2  455.48  5983.8  457.13  6443.5  467.43  6768.8  468.45  6986.6  472.80
#Mann=9,-1,0
  3700.3    0.05       0  4302.2    0.16       0  4503.7    0.05       0
  4996.9    0.16       0  4998.0    0.07       0  5004.0    0.16       0
  5376.6    0.12       0  5481.5    0.16       0  5529.9    0.05       0
Bank Sta=4998,5004
Exp/Cntr=0.3,0.1

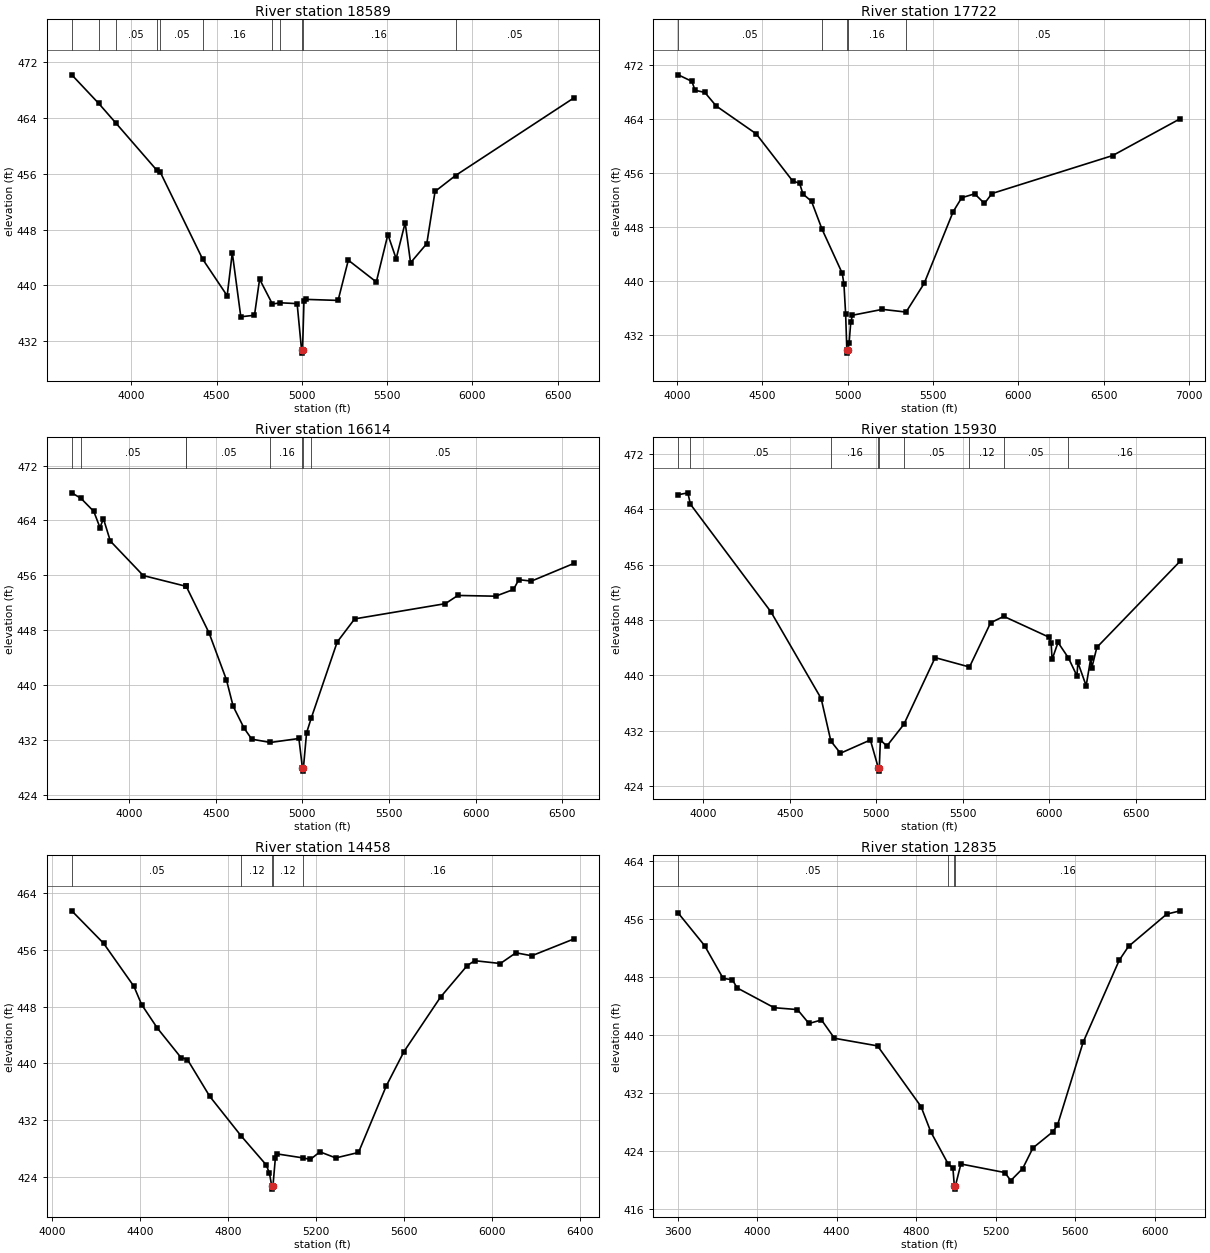
Type RM Length L Ch R = 1,18589,867,867,867
BEGIN DESCRIPTION:
UNT0085 IN CHRS 29.0
END DESCRIPTION:
XS GIS Cut Line= 4
      3504590.73     10557958.08      3503900.60     10557827.87
      3502893.65     10557810.51      3501726.63     10558209.64
#Sta/Elev= 30
  3651.5  470.22  3809.5  466.11  3909.4  463.31  4148.4  456.56  4168.6  456.32
  4418.6  443.75  4562.3  438.49  4592.3  444.67  4642.3  435.47  4722.4  435.69
  4752.4  440.87  4827.4  437.30  4873.9  437.48  4972.4  437.36  4998.2  430.75
  5000.9  430.25  5004.2  430.75  5012.4  437.67  5022.4  437.97  5212.4  437.82
  5272.4  443.60  5436.5  440.47  5504.3  447.28  5552.8  443.81  5605.6  448.98
  5637.3  443.23  5732.4  445.98  5780.8  453.47  5901.0  455.76  6594.3  466.90
#Mann=11,-1,0
  3651.5    0.05       0  3809.5    0.12       0  3909.4    0.05       0
  4148.4    0.16       0  4168.6    0.05       0  4418.6    0.16       0
  4827.4    0.05       0  4873.9    0.16       0  4998.2    0.07       0
  5004.2    0.16       0  5901.0    0.05       0
Bank Sta=4998.2,5004.2
Exp/Cntr=0.3,0.1

Type RM Length L Ch R = 1,17722,1108,1108,1108
BEGIN DESCRIPTION:
UNT0085 IN CHRS 29.1
END DESCRIPTION:
XS GIS Cut Line= 4
      3504720.88     10557515.36      3504030.81     10557385.16
      3503023.86     10557367.80      3501857.44     10557766.72
#Sta/Elev= 30
  4007.1  470.50  4087.3  469.53  4105.3  468.22  4162.8  467.90  4229.7  465.89
  4463.8  461.78  4677.5  454.81  4718.1  454.47  4738.1  452.88  4788.1  451.80
  4849.9  447.67  4968.1  441.17  4978.1  439.56  4988.1  435.11  4995.1  429.86
  4997.8  429.36  5001.1  429.86  5008.1  430.81  5018.1  433.93  5028.1  434.96
  5203.3  435.83  5342.1  435.43  5448.2  439.67  5618.2  450.27  5668.2  452.33
  5744.2  452.91  5801.6  451.48  5845.1  452.95  6553.2  458.57  6949.2  464.02
#Mann=5,-1,0
  4007.1    0.05       0  4849.9    0.16       0  4995.1    0.07       0
  5001.1    0.16       0  5342.1    0.05       0
Bank Sta=4995.1,5001.1
Exp/Cntr=0.3,0.1

Type RM Length L Ch R = 1,16614,684,684,684
BEGIN DESCRIPTION:
UNT0085 IN CHRS 27.1
END DESCRIPTION:
XS GIS Cut Line= 4
      3504694.86     10556738.46      3503787.75     10556725.44
      3503149.73     10556512.76      3501875.37     10556855.19
#Sta/Elev= 30
  3668.6  468.02  3721.9  467.21  3795.7  465.31  3831.4  462.95  3851.4  464.24
  3891.4  460.98  4081.4  455.95  4325.9  454.40  4330.0  454.36  4461.4  447.58
  4561.5  440.76  4600.6  436.88  4663.8  433.68  4708.2  432.08  4815.6  431.60
  4980.1  432.18  5000.4  427.92  5003.1  427.42  5006.4  427.92  5024.5  433.01
  5052.1  435.20  5201.4  446.26  5302.3  449.63  5825.7  451.85  5898.2  453.05
  6116.0  452.94  6219.2  453.92  6250.3  455.35  6322.8  455.14  6567.9  457.72
#Mann=8,-1,0
  3668.6    0.16       0  3721.9    0.05       0  4325.9    0.16       0
  4330.0    0.05       0  4815.6    0.16       0  5000.4    0.07       0
  5006.4    0.16       0  5052.1    0.05       0
Bank Sta=5000.4,5006.4
Exp/Cntr=0.3,0.1

Type RM Length L Ch R = 1,15930,1472,1472,1472
BEGIN DESCRIPTION:
UNT0085 IN CHRS 27.0
END DESCRIPTION:
XS GIS Cut Line= 4
      3504577.70     10556113.46      3503670.56     10556100.44
      3503032.54     10555887.76      3501756.76     10556230.58
#Sta/Elev= 30
  3855.8  466.12  3911.4  466.40  3925.9  464.76  4391.4  449.17  4681.5  436.63
  4737.6  430.47  4793.0  428.71  4965.9  430.63  5011.4  426.62  5014.1  426.12
  5017.4  426.62  5023.8  430.65  5060.7  429.74  5159.4  432.89  5340.1  442.55
  5538.5  441.19  5660.5  447.59  5736.6  448.52  5995.2  445.54  6010.0  444.70
  6015.9  442.28  6050.0  444.75  6110.3  442.50  6159.5  439.90  6164.7  441.85
  6212.6  438.48  6239.5  442.50  6244.7  441.01  6274.3  444.03  6756.6  456.53
#Mann=9,-1,0
  3855.8    0.16       0  3925.9    0.05       0  4737.6    0.16       0
  5011.4    0.07       0  5017.4    0.16       0  5159.4    0.05       0
  5538.5    0.12       0  5736.6    0.05       0  6110.3    0.16       0
Bank Sta=5011.4,5017.4
Exp/Cntr=0.3,0.1

Type RM Length L Ch R = 1,14458,1623,1623,1623
BEGIN DESCRIPTION:
UNT0085 IN CHRS 23.0
END DESCRIPTION:
XS GIS Cut Line= 5
      3504555.94     10555544.86      3503909.28     10555280.12
      3503479.59     10554993.67      3502620.22     10554885.16
      3502450.97     10554993.65
#Sta/Elev= 30
  4090.7  461.51  4235.3  456.93  4373.4  450.85  4408.2  448.29  4480.2  444.95
  4587.0  440.82  4616.4  440.54  4717.8  435.35  4860.7  429.76  4974.2  425.69
  4989.2  424.53  4999.4  422.76  5002.1  422.26  5005.4  422.76  5016.2  426.64
  5025.3  427.22  5140.4  426.67  5175.5  426.45  5218.7  427.52  5290.8  426.66
  5394.1  427.43  5520.8  436.84  5601.1  441.67  5767.0  449.34  5887.9  453.77
  5922.0  454.48  6039.1  454.08  6109.7  455.59  6181.7  455.17  6373.1  457.54
#Mann=5,-1,0
  4090.7    0.05       0  4860.7    0.12       0  4999.4    0.07       0
  5005.4    0.12       0  5140.4    0.16       0
Bank Sta=4999.4,5005.4
Exp/Cntr=0.3,0.1

Type RM Length L Ch R = 1,12835,1625,1625,1625
BEGIN DESCRIPTION:
UNT0085 IN CHRS 19.0
END DESCRIPTION:
XS GIS Cut Line= 4
      3504703.56     10554216.76      3503700.95     10553782.73
      3503019.52     10553834.81      3502329.42     10554129.95
#Sta/Elev= 30
  3603.1  456.83  3735.4  452.35  3829.0  447.82  3876.0  447.62  3898.9  446.51
  4085.6  443.77  4203.0  443.51  4260.9  441.59  4323.9  442.08  4389.3  439.55
  4606.0  438.50  4824.8  430.13  4874.1  426.63  4960.9  422.23  4985.3  421.62
  4992.3  419.23  4995.1  418.73  4998.3  419.23  5025.4  422.20  5246.1  421.02
  5276.5  419.91  5336.3  421.57  5388.1  424.42  5487.9  426.64  5511.5  427.56
  5640.4  438.99  5822.2  450.32  5869.0  452.23  6061.4  456.69  6129.6  457.14
#Mann=4,-1,0
  3603.1    0.05       0  4960.9    0.16       0  4992.3    0.07       0
  4998.3    0.16       0
Bank Sta=4992.3,4998.3
Exp/Cntr=0.3,0.1

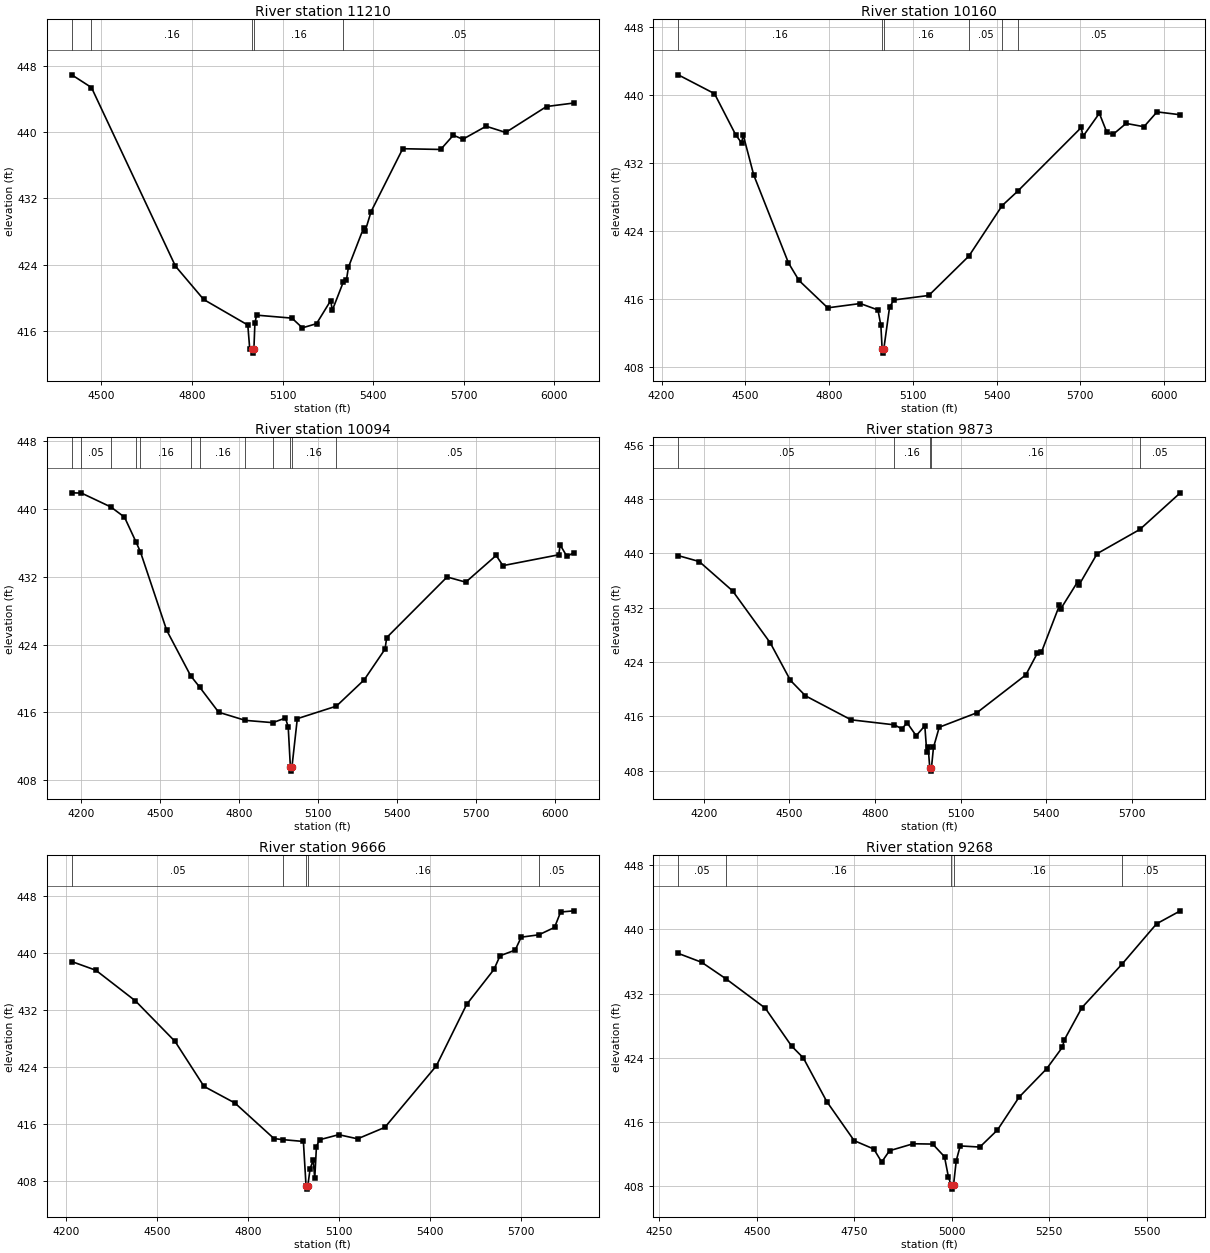
Type RM Length L Ch R = 1,11210,1050,1050,1050
BEGIN DESCRIPTION:
UNT0085 IN CHRS 16.1
END DESCRIPTION:
XS GIS Cut Line= 4
      3504265.17     10553088.28      3503870.22     10553070.92
      3503349.38     10552845.23      3502680.97     10553053.57
#Sta/Elev= 30
  4401.8  446.91  4467.0  445.38  4745.2  423.84  4838.7  419.82  4984.9  416.74
  4991.2  413.90  4999.1  413.85  5001.9  413.35  5005.1  413.85  5008.4  416.93
  5013.8  417.93  5131.2  417.57  5165.6  416.40  5212.5  416.90  5259.4  419.68
  5264.9  418.52  5301.1  421.91  5311.8  422.21  5318.2  423.71  5368.3  428.42
  5373.6  428.05  5393.3  430.42  5498.1  438.00  5623.8  437.91  5665.7  439.63
  5697.1  439.14  5774.2  440.71  5839.2  439.96  5974.5  443.09  6064.9  443.51
#Mann=5,-1,0
  4401.8    0.05       0  4467.0    0.16       0  4999.1    0.07       0
  5005.1    0.16       0  5301.1    0.05       0
Bank Sta=4999.1,5005.1
Exp/Cntr=0.3,0.1

Type RM Length L Ch R = 1,10160,66,66,66
BEGIN DESCRIPTION:
UNT0085 IN CHRS 16.0
END DESCRIPTION:
XS GIS Cut Line= 6
      3504331.52     10552549.46      3503753.43     10552226.56
      3503615.41     10552265.62      3503396.66     10552533.85
      3503211.76     10552822.92      3502922.74     10552916.65
#Sta/Elev= 30
  4259.6  442.40  4389.5  440.18  4464.9  435.36  4486.6  434.36  4492.3  435.32
  4530.0  430.59  4654.6  420.21  4692.2  418.15  4795.1  414.92  4911.8  415.43
  4975.1  414.67  4985.5  412.85  4990.1  410.08  4992.8  409.58  4996.1  410.08
  5016.7  415.00  5032.2  415.85  5157.1  416.38  5301.0  421.03  5420.1  426.98
  5475.8  428.68  5703.5  436.19  5709.4  435.13  5768.2  437.86  5794.9  435.64
  5817.2  435.37  5864.1  436.67  5928.1  436.28  5974.9  438.03  6058.3  437.69
#Mann=6,-1,0
  4259.6    0.16       0  4990.1    0.07       0  4996.1    0.16       0
  5301.0    0.05       0  5420.1    0.16       0  5475.8    0.05       0
Bank Sta=4990.1,4996.1
Exp/Cntr=0.3,0.1

Type RM Length L Ch R = 1,10094,221,221,221
BEGIN DESCRIPTION:
UNT0085 IN CHRS 16.2
END DESCRIPTION:
XS GIS Cut Line= 5
      3504386.22     10552499.99      3503776.86     10552140.62
      3503610.20     10552210.94      3503188.32     10552770.83
      3502891.43     10552875.01
#Sta/Elev= 30
  4166.1  441.92  4202.9  441.89  4314.4  440.25  4366.0  439.05  4409.9  436.11
  4426.6  434.94  4526.0  425.70  4617.0  420.33  4650.9  419.00  4723.1  416.03
  4824.0  415.07  4928.7  414.80  4976.4  415.35  4986.9  414.29  4995.1  409.58
  4997.8  409.08  5001.1  409.58  5021.4  415.27  5169.6  416.75  5275.0  419.85
  5354.1  423.48  5360.4  424.84  5589.4  431.99  5660.2  431.38  5775.5  434.53
  5801.2  433.33  6012.9  434.61  6018.2  435.77  6043.9  434.42  6070.1  434.86
#Mann=12,-1,0
  4166.1    0.16       0  4202.9    0.05       0  4314.4    0.16       0
  4409.9    0.05       0  4426.6    0.16       0  4617.0    0.05       0
  4650.9    0.16       0  4824.0    0.05       0  4928.7    0.16       0
  4995.1    0.07       0  5001.1    0.16       0  5169.6    0.05       0
Bank Sta=4995.1,5001.1
Exp/Cntr=0.3,0.1

Type RM Length L Ch R = 1,9873,207,207,207
BEGIN DESCRIPTION:
UNT0085 IN CHRS 9.3
END DESCRIPTION:
XS GIS Cut Line= 3
      3504409.67     10552364.58      3503758.63     10551979.17
      3502766.73     10552130.17
#Sta/Elev= 30
  4110.4  439.67  4184.0  438.80  4301.0  434.48  4433.0  426.83  4503.7  421.31
  4556.4  419.04  4716.3  415.51  4868.3  414.77  4893.8  414.18  4912.8  415.06
  4944.4  413.17  4974.7  414.63  4981.4  410.83  4986.5  411.50  4992.0  408.46
  4994.7  407.96  4998.0  408.46  5005.1  411.45  5025.3  414.42  5156.8  416.54
  5328.8  422.12  5369.2  425.32  5383.1  425.42  5446.6  432.35  5451.7  431.87
  5510.2  435.80  5515.3  435.36  5578.8  439.96  5728.4  443.52  5870.3  448.91
#Mann=5,-1,0
  4110.4    0.05       0  4868.3    0.16       0  4992.0    0.07       0
  4998.0    0.16       0  5728.4    0.05       0
Bank Sta=4992,4998
Exp/Cntr=0.3,0.1

Type RM Length L Ch R = 1,9666,398,398,398
BEGIN DESCRIPTION:
UNT0085 IN CHRS 9.1
END DESCRIPTION:
XS GIS Cut Line= 4
      3504446.10     10552197.89      3504081.55     10551968.75
      3503604.99     10551817.71      3502878.41     10551804.69
#Sta/Elev= 30
  4218.2  438.83  4297.7  437.61  4428.4  433.30  4559.2  427.60  4654.6  421.29
  4756.7  418.95  4885.8  413.95  4916.2  413.80  4982.7  413.55  4991.4  407.35
  4994.1  406.85  4997.4  407.35  5004.9  409.71  5015.0  410.94  5020.2  408.37
  5025.8  412.84  5036.3  413.79  5099.3  414.50  5161.6  413.92  5251.6  415.53
  5421.6  424.18  5521.6  432.81  5611.7  437.72  5631.7  439.64  5681.7  440.44
  5701.7  442.26  5760.0  442.59  5811.7  443.63  5831.7  445.79  5875.4  445.96
#Mann=5,-1,0
  4218.2    0.05       0  4916.2    0.16       0  4991.4    0.07       0
  4997.4    0.16       0  5760.0    0.05       0
Bank Sta=4991.4,4997.4
Exp/Cntr=0.3,0.1

Type RM Length L Ch R = 1,9268,756,756,756
BEGIN DESCRIPTION:
UNT0085 IN CHRS 13.0
END DESCRIPTION:
XS GIS Cut Line= 3
      3504352.02     10551582.21      3503922.30     10551551.83
      3503071.63     10551452.00
#Sta/Elev= 30
  4298.8  437.01  4358.9  435.90  4421.1  433.84  4521.9  430.18  4589.4  425.45
  4619.5  423.97  4679.7  418.52  4749.9  413.65  4800.3  412.60  4820.4  410.98
  4840.5  412.39  4901.0  413.26  4951.3  413.22  4981.5  411.64  4991.6  409.10
  4998.6  408.10  5001.4  407.60  5004.6  408.10  5011.7  411.17  5021.8  412.99
  5072.1  412.85  5117.3  414.98  5172.8  419.08  5243.3  422.61  5283.6  425.29
  5288.7  426.22  5333.9  430.25  5437.2  435.70  5525.2  440.70  5586.1  442.32
#Mann=5,-1,0
  4298.8    0.05       0  4421.1    0.16       0  4998.6    0.07       0
  5004.6    0.16       0  5437.2    0.05       0
Bank Sta=4998.6,5004.6
Exp/Cntr=0.3,0.1

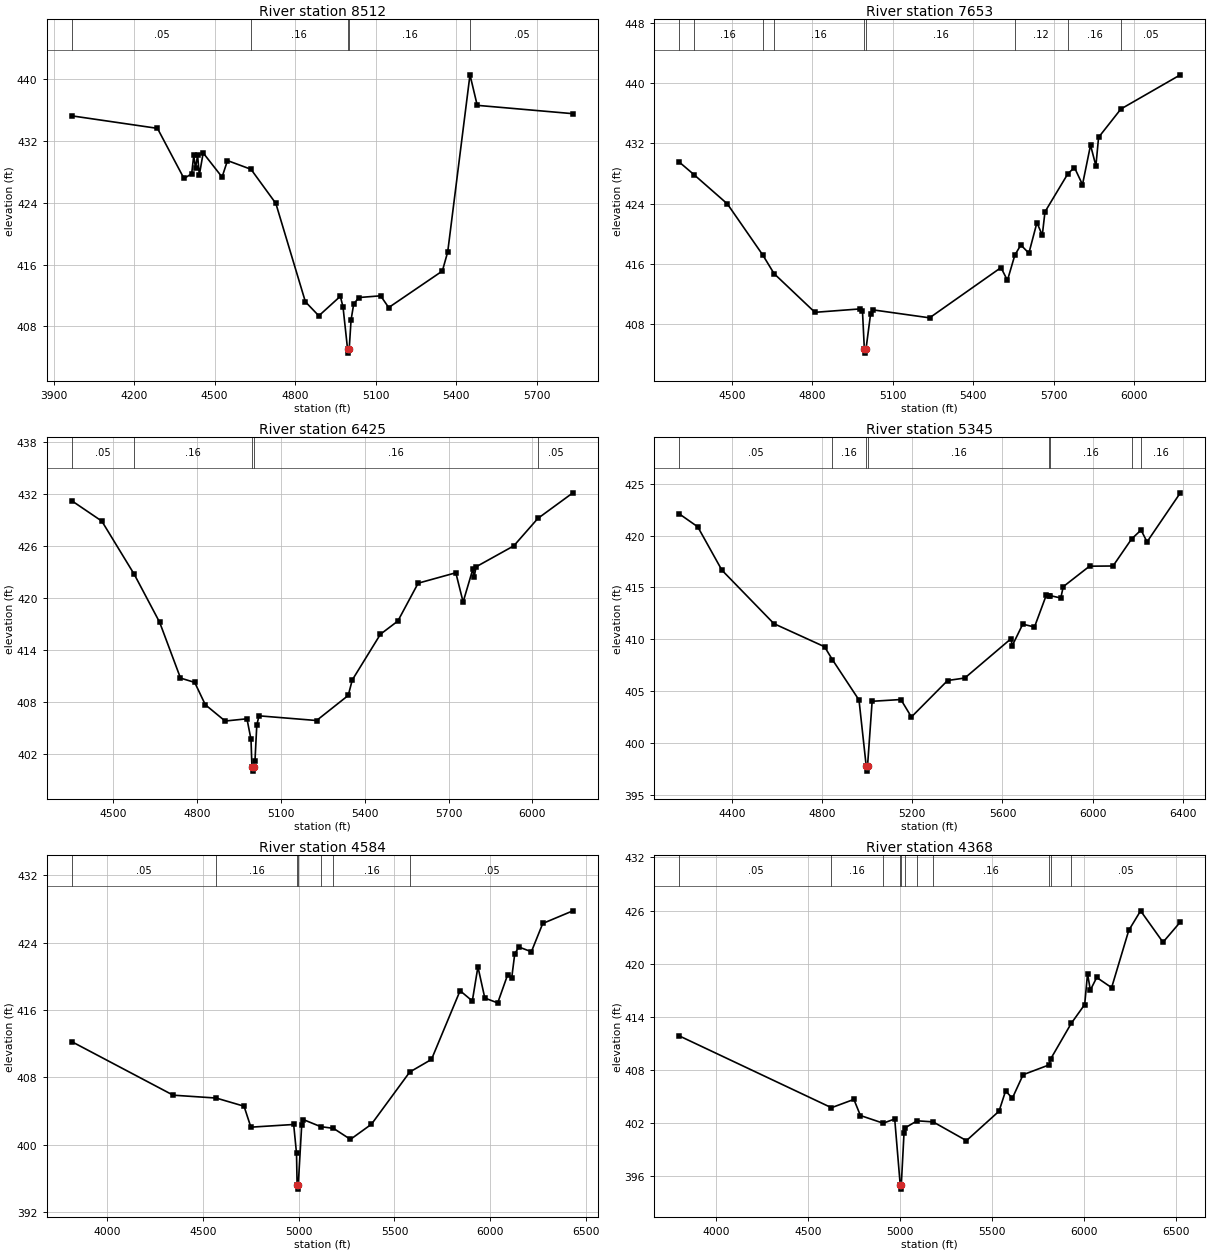
Type RM Length L Ch R = 1,8512,859,859,859
BEGIN DESCRIPTION:
UNT0085 IN CHRS 9.0
END DESCRIPTION:
XS GIS Cut Line= 4
      3504772.96     10551261.00      3504378.03     10550931.17
      3503692.27     10550892.10      3503025.50     10550896.43
#Sta/Elev= 30
  3967.1  435.26  4286.7  433.64  4385.6  427.15  4414.2  427.76  4422.0  430.13
  4428.5  428.49  4436.3  430.15  4442.8  427.60  4457.1  430.46  4527.6  427.33
  4547.7  429.47  4635.4  428.34  4728.0  423.92  4838.1  411.19  4888.2  409.37
  4968.4  411.90  4978.4  410.52  4995.4  405.04  4998.2  404.54  5001.4  405.04
  5008.4  408.83  5018.4  410.94  5038.5  411.74  5118.6  411.96  5148.7  410.44
  5348.7  415.17  5368.7  417.65  5451.7  440.57  5478.7  436.62  5835.3  435.54
#Mann=5,-1,0
  3967.1    0.05       0  4635.4    0.16       0  4995.4    0.07       0
  5001.4    0.16       0  5451.7    0.05       0
Bank Sta=4995.4,5001.4
Exp/Cntr=0.3,0.1

Type RM Length L Ch R = 1,7653,1228,1228,1228
BEGIN DESCRIPTION:
UNT0085 IN CHRS 9.2
END DESCRIPTION:
XS GIS Cut Line= 4
      3504785.98     10550570.90      3504391.05     10550241.06
      3503705.29     10550202.00      3503037.03     10550206.34
#Sta/Elev= 30
  4302.7  429.51  4357.4  427.85  4482.3  423.96  4614.7  417.17  4656.7  414.71
  4809.0  409.58  4976.5  410.03  4986.5  409.72  4993.5  404.67  4996.2  404.17
  4999.5  404.67  5016.5  409.31  5026.5  409.90  5236.9  408.85  5503.2  415.51
  5527.3  413.82  5554.9  417.17  5577.3  418.51  5607.3  417.42  5637.3  421.47
  5657.3  419.80  5667.3  422.90  5752.8  427.96  5777.3  428.78  5807.3  426.51
  5837.3  431.75  5857.3  429.00  5867.3  432.78  5950.6  436.54  6172.4  441.07
#Mann=9,-1,0
  4302.7    0.05       0  4357.4    0.16       0  4614.7    0.12       0
  4656.7    0.16       0  4993.5    0.07       0  4999.5    0.16       0
  5554.9    0.12       0  5752.8    0.16       0  5950.6    0.05       0
Bank Sta=4993.5,4999.5
Exp/Cntr=0.3,0.1

Type RM Length L Ch R = 1,6425,1080,1080,1080
BEGIN DESCRIPTION:
UNT0085 IN CHRS 6.2
END DESCRIPTION:
XS GIS Cut Line= 4
      3505293.81     10549906.85      3504855.46     10549668.15
      3504412.75     10549303.56      3503718.28     10549112.58
#Sta/Elev= 30
  4352.0  431.21  4459.6  428.86  4575.7  422.73  4666.6  417.20  4741.1  410.78
  4791.9  410.28  4829.9  407.71  4900.8  405.83  4978.9  406.09  4993.3  403.72
  4996.8  400.56  4999.5  400.06  5002.8  400.56  5007.6  401.26  5014.1  405.38
  5022.0  406.43  5227.9  405.89  5341.2  408.78  5355.6  410.56  5456.4  415.83
  5518.7  417.35  5591.3  421.71  5726.1  422.91  5752.2  419.54  5786.6  423.29
  5791.8  422.46  5798.7  423.60  5933.5  426.01  6019.6  429.17  6144.9  432.12
#Mann=5,-1,0
  4352.0    0.05       0  4575.7    0.16       0  4996.8    0.07       0
  5002.8    0.16       0  6019.6    0.05       0
Bank Sta=4996.8,5002.8
Exp/Cntr=0.3,0.1

Type RM Length L Ch R = 1,5345,761,761,761
BEGIN DESCRIPTION:
UNT0085 IN CHRS 6.3
END DESCRIPTION:
XS GIS Cut Line= 3
      3505422.39     10549472.18      3505165.46     10548944.44
      3503666.31     10548285.09
#Sta/Elev= 30
  4165.0  422.09  4247.3  420.84  4354.5  416.67  4585.5  411.52  4810.2  409.30
  4844.7  408.07  4963.2  404.17  4995.1  397.83  4997.9  397.33  5001.1  397.83
  5021.5  404.05  5149.1  404.22  5195.8  402.54  5356.5  406.05  5432.9  406.29
  5637.9  410.07  5643.3  409.39  5690.0  411.47  5742.2  411.20  5794.3  414.25
  5808.6  414.21  5809.5  414.23  5858.9  413.99  5869.9  415.08  5986.5  417.05
  6090.8  417.07  6173.3  419.67  6215.2  420.53  6241.8  419.39  6389.7  424.11
#Mann=8,-1,0
  4165.0    0.05       0  4844.7    0.16       0  4995.1    0.07       0
  5001.1    0.16       0  5808.6    0.12       0  5809.5    0.16       0
  6173.3    0.05       0  6215.2    0.16       0
Bank Sta=4995.1,5001.1
Exp/Cntr=0.3,0.1

Type RM Length L Ch R = 1,4584,216,216,216
BEGIN DESCRIPTION:
UNT0085 IN CHRS 6.0
END DESCRIPTION:
XS GIS Cut Line= 6
      3505743.79     10549026.77      3505207.30     10548414.76
      3504850.53     10548164.76      3504509.39     10547951.21
      3504183.87     10547669.96      3503720.29     10547409.53
#Sta/Elev= 30
  3816.8  412.23  4345.8  405.87  4570.1  405.53  4715.5  404.56  4751.2  402.07
  4974.4  402.39  4989.2  398.97  4992.3  395.21  4995.0  394.71  4998.3  395.21
  5016.2  402.28  5024.9  402.97  5115.6  402.13  5182.0  401.93  5270.5  400.62
  5380.1  402.42  5579.8  408.62  5693.2  410.12  5842.4  418.28  5906.2  417.06
  5935.4  421.12  5971.3  417.41  6038.6  416.83  6089.9  420.14  6111.6  419.79
  6127.5  422.67  6149.2  423.47  6214.2  422.91  6273.5  426.27  6430.7  427.77
#Mann=7,-1,0
  3816.8    0.05       0  4570.1    0.16       0  4992.3    0.07       0
  4998.3    0.16       0  5115.6    0.12       0  5182.0    0.16       0
  5579.8    0.05       0
Bank Sta=4992.3,4998.3
Exp/Cntr=0.3,0.1

Type RM Length L Ch R = 1,4368,614,614,614
BEGIN DESCRIPTION:
UNT0085 IN CHRS 6.1
END DESCRIPTION:
XS GIS Cut Line= 6
      3505814.07     10548974.64      3505345.32     10548360.07
      3505058.87     10548104.86      3504767.20     10548037.15
      3504584.91     10547810.59      3503751.54     10547292.34
#Sta/Elev= 30
  3797.0  411.84  4626.2  403.72  4748.3  404.66  4783.7  402.84  4908.0  401.97
  4970.6  402.45  5000.5  395.02  5003.3  394.52  5006.5  395.02  5021.4  400.91
  5028.4  401.46  5092.5  402.24  5179.6  402.12  5361.2  400.00  5538.8  403.33
  5574.3  405.61  5611.3  404.80  5669.8  407.45  5811.5  408.56  5819.3  409.21
  5931.6  413.24  6005.1  415.38  6020.7  418.86  6035.9  417.01  6070.7  418.44
  6151.8  417.29  6245.1  423.76  6309.6  425.97  6431.6  422.42  6526.1  424.71
#Mann=11,-1,0
  3797.0    0.05       0  4626.2    0.16       0  4908.0    0.12       0
  5000.5    0.07       0  5006.5    0.12       0  5028.4    0.16       0
  5092.5    0.12       0  5179.6    0.16       0  5811.5    0.05       0
  5819.3    0.16       0  5931.6    0.05       0
Bank Sta=5000.5,5006.5
Exp/Cntr=0.3,0.1

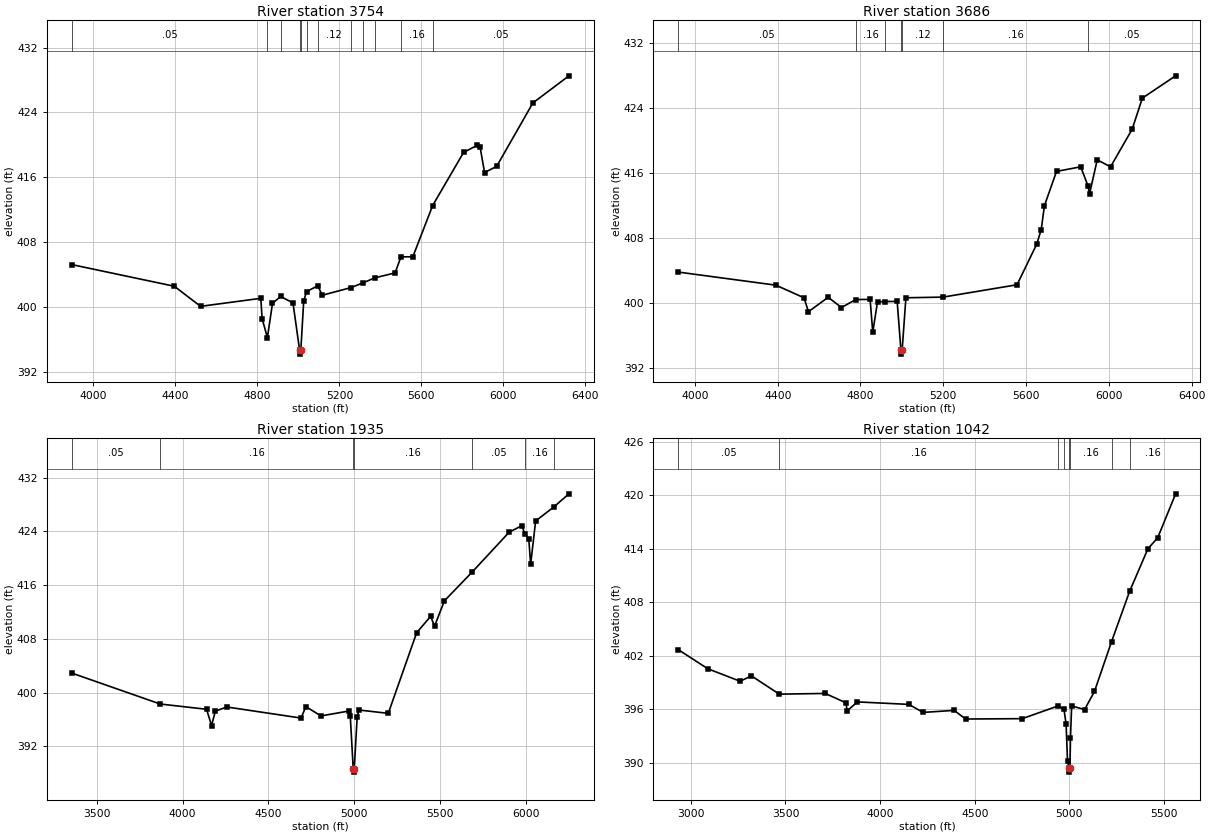
Type RM Length L Ch R = 1,3754,68,68,68
BEGIN DESCRIPTION:
UNT0085 IN CHRS 2.1
END DESCRIPTION:
XS GIS Cut Line= 6
      3505613.53     10548438.16      3505267.20     10548052.78
      3504936.47     10547805.38      3504558.87     10547623.09
      3504228.14     10547396.53      3503642.16     10547060.57
#Sta/Elev= 30
  3893.1  405.21  4394.5  402.53  4522.7  400.05  4816.6  401.04  4822.8  398.54
  4848.7  396.19  4873.5  400.42  4913.4  401.27  4973.5  400.47  5005.8  394.65
  5008.6  394.15  5011.8  394.65  5025.9  400.73  5039.8  401.87  5094.5  402.59
  5116.3  401.42  5256.3  402.36  5316.1  402.96  5373.0  403.57  5471.7  404.18
  5500.3  406.16  5558.3  406.17  5655.0  412.50  5806.0  419.06  5870.8  419.91
  5886.6  419.67  5908.2  416.57  5967.1  417.33  6144.1  425.17  6319.9  428.51
#Mann=12,-1,0
  3893.1    0.05       0  4848.7    0.16       0  4913.4    0.12       0
  5005.8    0.07       0  5011.8    0.12       0  5039.8    0.05       0
  5094.5    0.12       0  5256.3    0.05       0  5316.1    0.16       0
  5373.0    0.05       0  5500.3    0.16       0  5655.0    0.05       0
Bank Sta=5005.8,5011.8
Exp/Cntr=0.3,0.1

Type RM Length L Ch R = 1,3686,1751,1751,1751
BEGIN DESCRIPTION:
UNT0085 IN CHRS 2.2
END DESCRIPTION:
XS GIS Cut Line= 4
      3505636.99     10548373.09      3505290.64     10547979.86
      3504618.76     10547544.96      3503691.66     10546992.87
#Sta/Elev= 30
  3919.2  403.85  4391.1  402.24  4526.8  400.69  4548.7  398.98  4644.0  400.75
  4708.1  399.49  4776.8  400.47  4846.5  400.49  4859.2  396.46  4882.2  400.18
  4920.7  400.23  4977.2  400.24  4995.3  394.26  4998.1  393.76  5001.3  394.26
  5019.4  400.69  5198.4  400.77  5556.4  402.29  5651.8  407.30  5673.2  409.07
  5688.8  412.02  5747.2  416.23  5864.0  416.79  5898.7  414.48  5906.8  413.47
  5943.8  417.65  6008.1  416.79  6112.6  421.41  6161.9  425.24  6322.6  427.98
#Mann=7,-1,0
  3919.2    0.05       0  4776.8    0.16       0  4920.7    0.12       0
  4995.3    0.07       0  5001.3    0.12       0  5198.4    0.16       0
  5898.7    0.05       0
Bank Sta=4995.3,5001.3
Exp/Cntr=0.3,0.1

Type RM Length L Ch R = 1,1935,893,893,893
BEGIN DESCRIPTION:
UNT0085 IN CHRS 2.0
END DESCRIPTION:
XS GIS Cut Line= 4
      3505639.95     10548040.79      3504988.93     10546773.47
      3504563.58     10546730.07      3503556.85     10546456.69
#Sta/Elev= 30
  3354.0  402.92  3870.5  398.30  4140.0  397.52  4169.0  395.10  4191.2  397.24
  4257.8  397.86  4690.2  396.21  4718.0  397.92  4805.7  396.53  4966.6  397.25
  4976.6  396.48  4993.7  388.66  4996.5  388.16  4999.7  388.66  5016.8  396.40
  5026.9  397.41  5197.7  396.91  5363.3  408.94  5444.7  411.36  5466.9  409.87
  5524.3  413.66  5686.4  417.96  5901.6  423.89  5974.6  424.85  5992.9  423.66
  6015.8  422.88  6026.5  419.10  6055.6  425.56  6162.6  427.67  6249.5  429.60
#Mann=7,-1,0
  3354.0    0.05       0  3870.5    0.16       0  4993.7    0.07       0
  4999.7    0.16       0  5686.4    0.05       0  5992.9    0.16       0
  6162.6    0.05       0
Bank Sta=4993.7,4999.7
Exp/Cntr=0.3,0.1

Type RM Length L Ch R = 1,1042,0,0,0
BEGIN DESCRIPTION:
UNT0085 IN CHRS 1.0
END DESCRIPTION:
XS GIS Cut Line= 3
      3505653.01     10548001.81      3505001.95     10546283.02
      3504281.44     10545957.49
#Sta/Elev= 30
  2933.2  402.67  3089.7  400.52  3260.0  399.12  3320.3  399.72  3467.3  397.67
  3710.4  397.75  3820.3  396.69  3825.6  395.79  3880.6  396.80  4152.4  396.52
  4227.3  395.62  4391.3  395.85  4451.8  394.88  4751.2  394.92  4941.1  396.35
  4971.9  395.96  4983.0  394.32  4990.5  390.17  4997.6  389.42  5000.3  388.92
  5003.6  389.42  5006.1  392.72  5012.4  396.35  5080.9  395.94  5133.1  397.98
  5223.0  403.55  5318.8  409.21  5415.5  413.99  5467.2  415.22  5561.8  420.15
#Mann=8,-1,0
  2933.2    0.05       0  3467.3    0.16       0  4941.1    0.12       0
  4971.9    0.16       0  4997.6    0.07       0  5003.6    0.16       0
  5223.0    0.12       0  5318.8    0.16       0
Bank Sta=4997.6,5003.6
Exp/Cntr=0.3,0.1

Chan Stop Cuts=-1