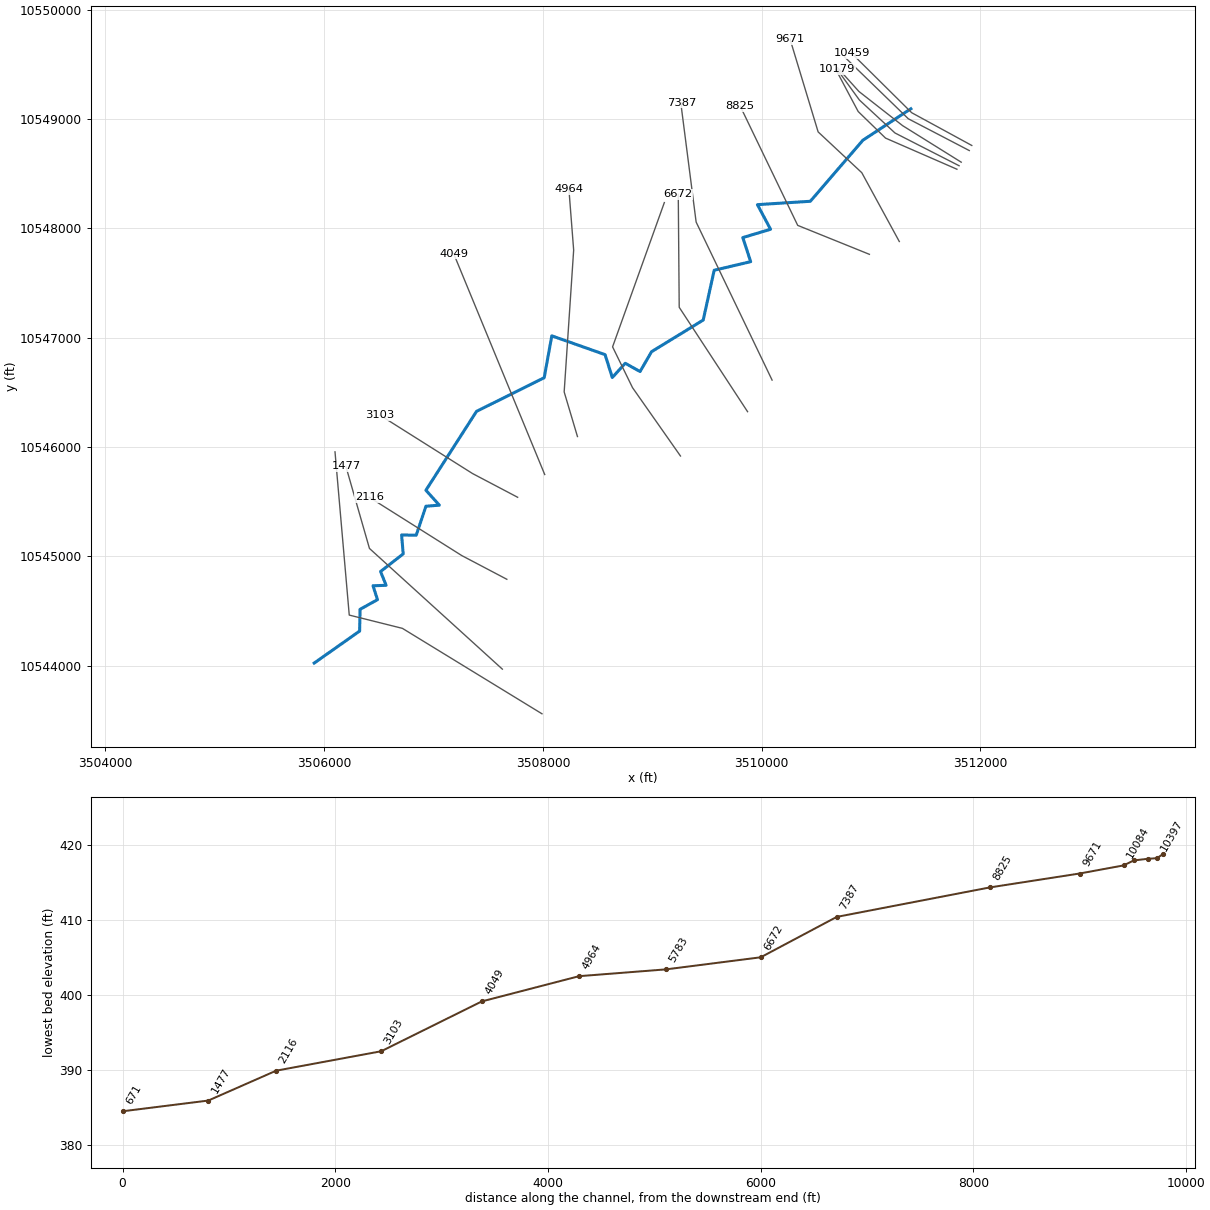
--- UNT0086 IN CHRS.prj (project) ---

Proj Title=UNT0086 IN CHRS Base Level Engineering
Current Plan=p01
Default Exp/Contr=0.3,0.1
English Units
Geom File=g01
Flow File=f01
Plan File=p01
BEGIN DESCRIPTION:
UNT0086 IN CHRS
END DESCRIPTION:

--- UNT0086 IN CHRS.p01 (plan) ---

Plan Title=Multiple Run
Short Identifier=Multiple
Geom File=g01
Flow File=f01
Subcritical Flow
K Sum by GR= 0
Std Step Tol= 0.01
Critical Tol= 0.01
Num of Std Step Trials= 20
Max Error Tol= 0.3
Flow Tol Ratio= 0.001
Split Flow NTrial= 30
Split Flow Tol= 0.02
Split Flow Ratio= 0.02
Log Output Level= 0
Friction Slope Method= 1
Unsteady Friction Slope Method= 2
Unsteady Bridges Friction Slope Method= 1
Parabolic Critical Depth
Global Vel Dist=  1 , 1 , 1
Global Log Level= 0
CheckData=True
Encroach Param= -1, 0, 0, 0
BEGIN DESCRIPTION:
Multiple Run
END DESCRIPTION:

--- UNT0086 IN CHRS.f01 (steady flow) ---

Flow Title=Multiple
Number of Profiles=7
Profile Names=10-year,25-year,50-year,1pct_min,100-year,1pct_plu,500-year
River Rch & RM= UNT0086 IN CHRS,Reach-1,10459
     435     545     625     523     707     956     901
River Rch & RM= UNT0086 IN CHRS,Reach-1,10309
     713     913    1064     901    1218    1647    1593
Boundary for River Rch & Prof#=UNT0086 IN CHRS,Reach-1,1
Up Type=0
Dn Type=3
Dn Slope=0.005
Boundary for River Rch & Prof#=UNT0086 IN CHRS,Reach-1,2
Up Type=0
Dn Type=3
Dn Slope=0.005
Boundary for River Rch & Prof#=UNT0086 IN CHRS,Reach-1,3
Up Type=0
Dn Type=3
Dn Slope=0.005
Boundary for River Rch & Prof#=UNT0086 IN CHRS,Reach-1,4
Up Type=0
Dn Type=3
Dn Slope=0.005
Boundary for River Rch & Prof#=UNT0086 IN CHRS,Reach-1,5
Up Type=0
Dn Type=3
Dn Slope=0.005
Boundary for River Rch & Prof#=UNT0086 IN CHRS,Reach-1,6
Up Type=0
Dn Type=3
Dn Slope=0.005
Boundary for River Rch & Prof#=UNT0086 IN CHRS,Reach-1,7
Up Type=0
Dn Type=3
Dn Slope=0.005

--- UNT0086 IN CHRS.g01 (geometry) ---

Geom Title=Existing Conditions

River Reach=UNT0086 IN CHRS,Reach-1
Reach XY= 30
      3511363.71     10549092.86      3510925.16     10548805.03
      3510444.71     10548246.77      3509960.89     10548215.77
      3510080.96     10547990.56      3509827.21     10547914.63
      3509899.25     10547694.34      3509565.55     10547615.70
      3509465.24     10547160.38      3508992.76     10546870.79
      3508887.80     10546689.18      3508752.53     10546764.85
      3508633.80     10546634.66      3508568.14     10546843.78
      3508080.77     10547015.97      3508011.20     10546632.62
      3507392.43     10546325.14      3506929.68     10545603.49
      3507052.50     10545467.13      3506929.93     10545457.41
      3506841.13     10545192.23      3506707.48     10545194.44
      3506722.11     10545021.64      3506515.05     10544860.16
      3506566.09     10544734.11      3506445.73     10544729.91
      3506487.09     10544602.91      3506327.64     10544514.39
      3506323.67     10544315.61      3505908.37     10544022.88

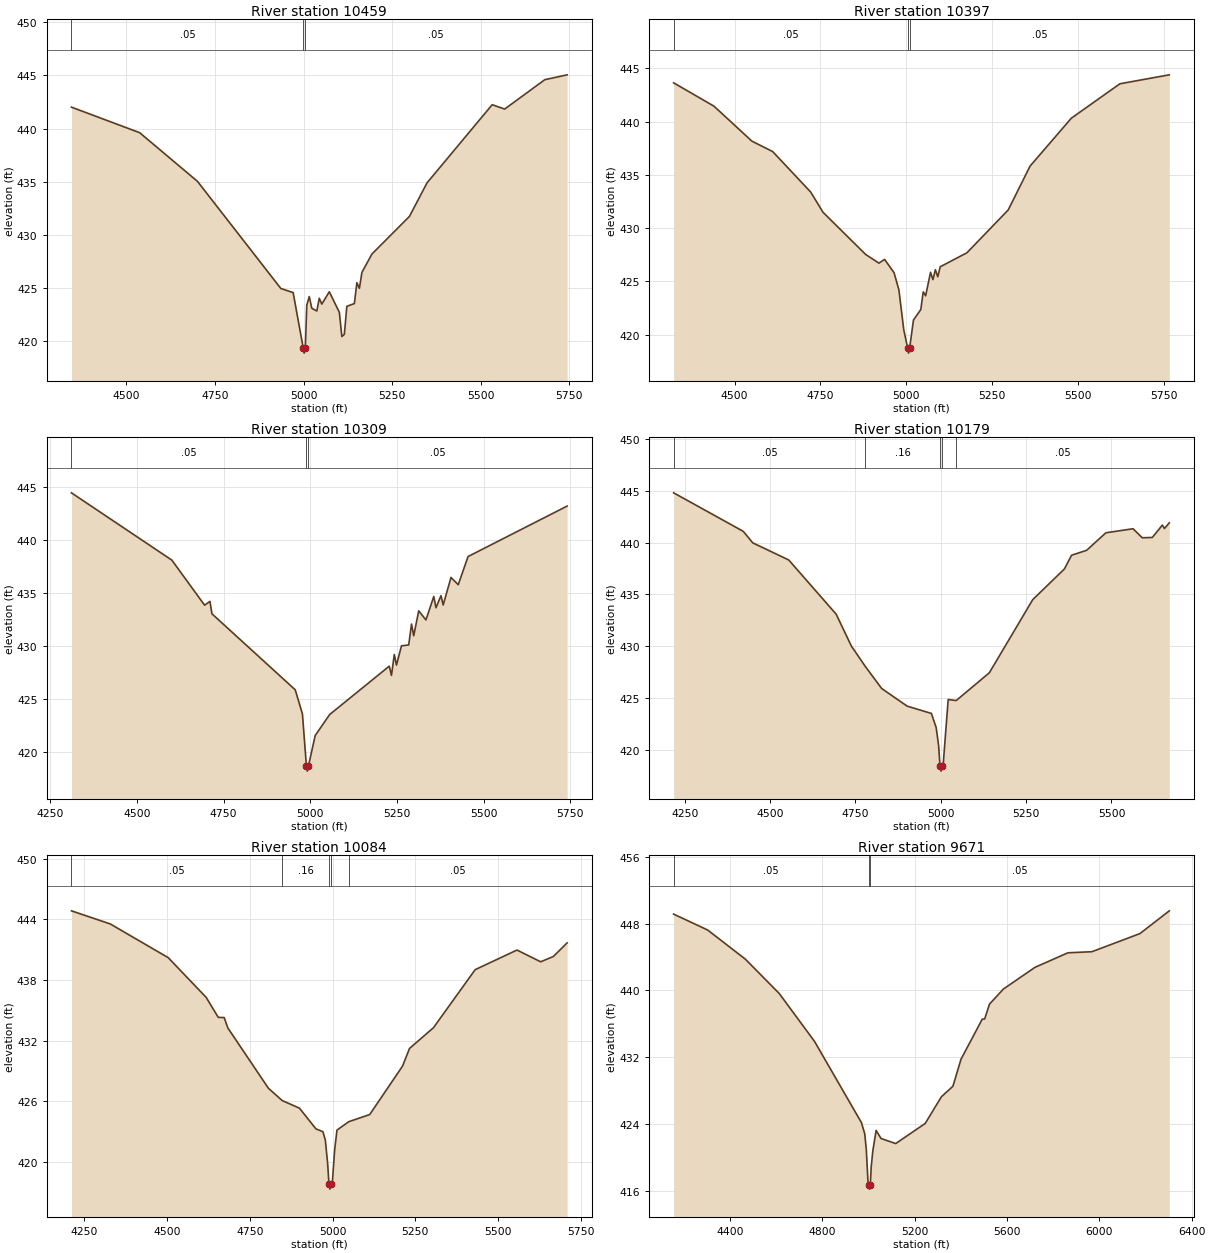
Type RM Length L Ch R = 1,10459,62,62,62
BEGIN DESCRIPTION:
UNT0086 IN CHRS 18.4
END DESCRIPTION:
XS GIS Cut Line= 3
      3511921.00     10548757.15      3511371.50     10549056.64
      3510822.03     10549600.90
#Sta/Elev= 30
  4344.7  442.01  4537.2  439.61  4700.5  435.03  4935.7  424.96  4970.5  424.57
  4998.9  419.38  5001.6  418.88  5004.9  419.38  5009.0  423.40  5016.0  424.20
  5023.1  423.10  5037.3  422.84  5044.3  424.04  5051.4  423.49  5072.6  424.65
  5100.9  422.72  5108.0  420.44  5115.0  420.65  5122.1  423.28  5143.3  423.54
  5150.4  425.51  5157.5  424.97  5164.6  426.47  5192.9  428.20  5298.9  431.74
  5348.4  434.89  5532.3  442.24  5567.6  441.83  5680.7  444.59  5743.9  445.05
#Mann=3,-1,0
  4344.7    0.05       0  4998.9   0.035       0  5004.9    0.05       0
Bank Sta=4998.9,5004.9
Exp/Cntr=0.3,0.1

Type RM Length L Ch R = 1,10397,88,88,88
BEGIN DESCRIPTION:
UNT0086 IN CHRS 18.3
END DESCRIPTION:
XS GIS Cut Line= 3
      3511898.10     10548710.62      3511340.40     10549001.40
      3510755.76     10549568.72
#Sta/Elev= 30
  4322.5  443.63  4440.0  441.44  4550.5  438.16  4611.1  437.18  4721.6  433.39
  4757.8  431.48  4881.9  427.53  4920.4  426.72  4936.9  427.07  4964.5  425.82
  4978.6  424.21  4992.8  420.46  5003.9  418.78  5006.7  418.28  5009.9  418.78
  5021.1  421.39  5042.4  422.37  5049.4  424.02  5056.5  423.66  5070.7  425.86
  5077.7  425.17  5084.8  426.10  5091.8  425.44  5099.0  426.38  5176.7  427.69
  5297.0  431.71  5360.6  435.82  5480.7  440.31  5622.2  443.54  5766.1  444.38
#Mann=3,-1,0
  4322.5    0.05       0  5003.9    0.04       0  5009.9    0.05       0
Bank Sta=5003.9,5009.9
Exp/Cntr=0.3,0.1

Type RM Length L Ch R = 1,10309,130,130,130
BEGIN DESCRIPTION:
UNT0086 IN CHRS 18.1
END DESCRIPTION:
XS GIS Cut Line= 4
      3511824.38     10548604.24      3511288.31     10548938.47
      3510889.01     10549250.97      3510694.32     10549467.29
#Sta/Elev= 30
  4310.9  444.45  4600.6  438.10  4695.0  433.85  4710.4  434.21  4716.2  433.04
  4956.4  425.87  4977.2  423.59  4988.6  418.70  4991.4  418.20  4994.6  418.70
  5014.0  421.56  5055.8  423.54  5227.6  428.10  5234.0  427.23  5242.1  429.20
  5248.4  428.20  5262.9  430.02  5283.7  430.10  5291.8  432.07  5298.2  430.97
  5312.6  433.32  5333.4  432.46  5356.0  434.67  5362.4  433.61  5376.8  434.75
  5383.2  433.87  5405.7  436.47  5426.6  435.78  5454.9  438.44  5740.7  443.20
#Mann=3,-1,0
  4310.9    0.05       0  4988.6    0.04       0  4994.6    0.05       0
Bank Sta=4988.6,4994.6
Exp/Cntr=0.3,0.1

Type RM Length L Ch R = 1,10179,95,95,95
BEGIN DESCRIPTION:
UNT0086 IN CHRS 18.2
END DESCRIPTION:
XS GIS Cut Line= 4
      3511804.77     10548571.74      3511218.87     10548871.19
      3510893.35     10549172.84      3510687.43     10549456.36
#Sta/Elev= 30
  4217.3  444.79  4421.3  441.08  4449.2  439.97  4554.6  438.32  4693.5  433.10
  4738.0  430.03  4779.0  428.06  4826.8  425.94  4901.5  424.24  4972.4  423.54
  4986.5  422.18  4993.6  420.45  4997.7  418.48  5000.5  417.98  5003.7  418.48
  5007.5  418.82  5021.7  424.88  5045.3  424.78  5142.4  427.46  5269.4  434.50
  5362.3  437.46  5383.2  438.78  5427.2  439.25  5483.7  440.94  5563.3  441.33
  5590.3  440.46  5619.7  440.49  5649.1  441.68  5655.3  441.35  5669.5  441.90
#Mann=5,-1,0
  4217.3    0.05       0  4779.0    0.16       0  4997.7    0.07       0
  5003.7    0.16       0  5045.3    0.05       0
Bank Sta=4997.7,5003.7
Exp/Cntr=0.3,0.1

Type RM Length L Ch R = 1,10084,413,413,413
BEGIN DESCRIPTION:
UNT0086 IN CHRS 18.0
END DESCRIPTION:
XS GIS Cut Line= 4
      3511785.04     10548539.87      3511132.22     10548824.61
      3510882.22     10549067.67      3510677.35     10549453.11
#Sta/Elev= 30
  4211.1  444.85  4328.5  443.55  4503.3  440.22  4618.0  436.29  4654.7  434.31
  4672.5  434.29  4683.6  433.26  4806.1  427.30  4847.8  426.08  4899.8  425.33
  4949.7  423.28  4970.8  423.00  4978.0  422.18  4984.9  419.91  4989.1  417.82
  4991.8  417.32  4995.1  417.82  4999.1  417.93  5006.2  421.19  5013.2  423.16
  5048.8  423.99  5112.2  424.70  5211.3  429.49  5232.4  431.24  5304.5  433.28
  5430.7  439.03  5556.9  440.97  5628.5  439.81  5666.8  440.33  5708.5  441.68
#Mann=5,-1,0
  4211.1    0.05       0  4847.8    0.16       0  4989.1    0.07       0
  4995.1    0.16       0  5048.8    0.05       0
Bank Sta=4989.1,4995.1
Exp/Cntr=0.3,0.1

Type RM Length L Ch R = 1,9671,846,846,846
BEGIN DESCRIPTION:
UNT0086 IN CHRS 17.0
END DESCRIPTION:
XS GIS Cut Line= 4
      3511258.11     10547878.62      3510915.21     10548507.99
      3510515.91     10548881.25      3510259.96     10549727.17
#Sta/Elev= 30
  4156.1  449.13  4303.2  447.23  4466.5  443.75  4613.7  439.63  4766.6  433.90
  4969.7  424.19  4983.9  422.86  4990.7  420.99  4998.0  417.14  5001.9  416.74
  5004.6  416.24  5007.9  416.74  5012.2  418.99  5019.0  420.82  5033.2  423.26
  5054.7  422.29  5118.2  421.69  5245.7  424.09  5316.1  427.29  5365.9  428.54
  5401.0  431.78  5493.0  436.56  5503.4  436.59  5524.3  438.36  5584.8  440.17
  5721.8  442.77  5864.0  444.50  5968.0  444.63  6176.1  446.80  6303.2  449.52
#Mann=3,-1,0
  4156.1    0.05       0  5001.9   0.035       0  5007.9    0.05       0
Bank Sta=5001.9,5007.9
Exp/Cntr=0.3,0.1

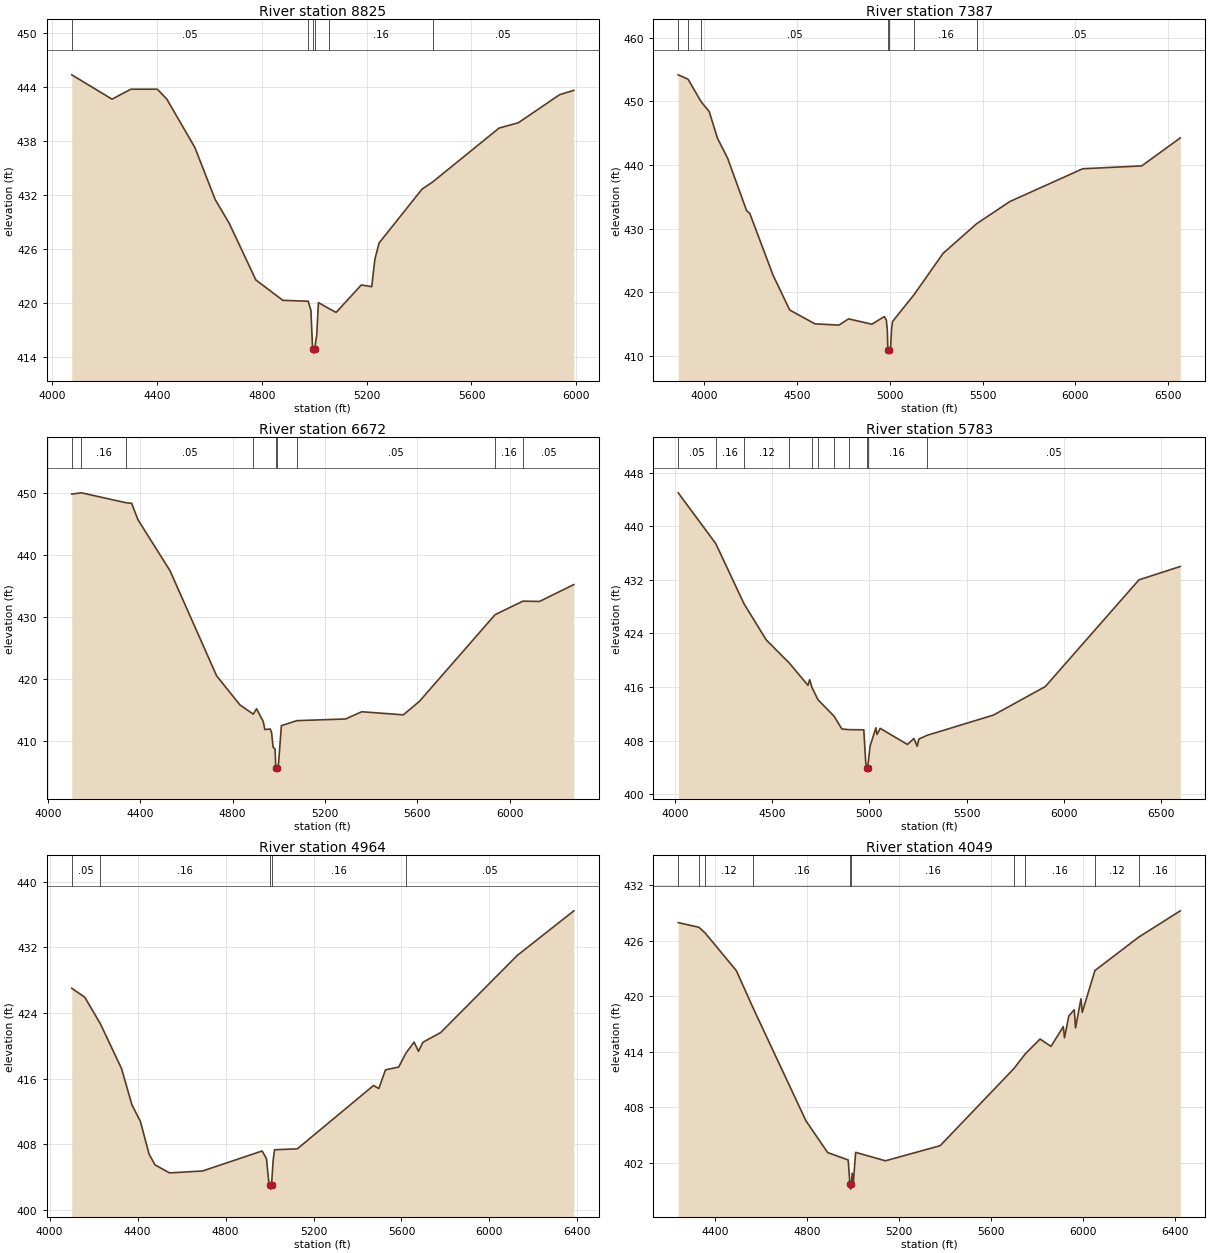
Type RM Length L Ch R = 1,8825,1438,1438,1438
BEGIN DESCRIPTION:
UNT0086 IN CHRS 15.0
END DESCRIPTION:
XS GIS Cut Line= 3
      3510984.64     10547761.47      3510329.27     10548026.22
      3509804.11     10549115.61
#Sta/Elev= 30
  4074.6  445.37  4228.3  442.66  4300.2  443.77  4400.9  443.77  4437.1  442.68
  4544.4  437.28  4622.2  431.47  4675.8  428.82  4777.2  422.53  4880.2  420.26
  4976.7  420.16  4987.3  419.16  4993.2  415.25  4995.8  414.88  4998.5  414.38
  5001.8  414.88  5009.5  416.41  5015.9  420.01  5055.6  419.35  5083.7  418.92
  5179.7  421.97  5219.4  421.78  5231.5  424.84  5247.6  426.65  5411.4  432.64
  5452.4  433.45  5705.4  439.44  5778.8  440.03  5937.1  443.17  5990.8  443.64
#Mann=6,-1,0
  4074.6    0.05       0  4976.7    0.12       0  4995.8    0.07       0
  5001.8    0.12       0  5055.6    0.16       0  5452.4    0.05       0
Bank Sta=4995.8,5001.8
Exp/Cntr=0.3,0.1

Type RM Length L Ch R = 1,7387,715,715,715
BEGIN DESCRIPTION:
UNT0086 IN CHRS 12.1
END DESCRIPTION:
XS GIS Cut Line= 4
      3510094.91     10546611.27      3509400.45     10548056.60
      3509265.91     10549102.61      3509270.08     10549148.48
#Sta/Elev= 30
  3860.9  454.15  3913.8  453.46  3984.4  449.92  4027.7  448.39  4072.1  444.21
  4127.5  441.01  4229.1  432.83  4246.2  432.40  4371.7  422.68  4461.1  417.23
  4596.9  415.05  4726.7  414.85  4778.0  415.83  4904.2  414.99  4970.8  416.19
  4981.8  415.66  4987.3  413.92  4989.9  410.95  4992.7  410.45  4995.9  410.95
  5004.0  410.98  5010.0  414.27  5015.5  415.42  5132.8  419.70  5287.2  426.11
  5468.1  430.77  5646.7  434.25  6039.2  439.40  6357.3  439.85  6565.1  444.25
#Mann=7,-1,0
  3860.9    0.05       0  3913.8    0.16       0  3984.4    0.05       0
  4989.9    0.03       0  4995.9    0.05       0  5132.8    0.16       0
  5468.1    0.05       0
Bank Sta=4989.9,4995.9
Exp/Cntr=0.3,0.1

Type RM Length L Ch R = 1,6672,889,889,889
BEGIN DESCRIPTION:
UNT0086 IN CHRS 12.0
END DESCRIPTION:
XS GIS Cut Line= 3
      3509870.79     10546322.19      3509245.77     10547277.09
      3509237.09     10548310.09
#Sta/Elev= 30
  4103.5  449.85  4145.4  450.05  4338.2  448.45  4362.8  448.35  4389.9  445.72
  4528.7  437.48  4730.7  420.47  4831.9  415.76  4889.5  414.27  4903.6  415.14
  4932.7  413.08  4939.5  411.79  4962.9  411.87  4968.9  411.28  4975.3  408.93
  4984.0  408.62  4987.0  405.56  4989.7  405.06  4993.0  405.56  4999.1  406.34
  5011.2  412.41  5078.3  413.22  5289.3  413.49  5359.3  414.66  5539.3  414.16
  5609.3  416.35  5936.7  430.35  6057.2  432.54  6129.3  432.49  6277.8  435.22
#Mann=9,-1,0
  4103.5    0.05       0  4145.4    0.16       0  4338.2    0.05       0
  4889.5    0.16       0  4987.0    0.07       0  4993.0    0.16       0
  5078.3    0.05       0  5936.7    0.16       0  6057.2    0.05       0
Bank Sta=4987,4993
Exp/Cntr=0.3,0.1

Type RM Length L Ch R = 1,5783,819,819,819
BEGIN DESCRIPTION:
UNT0086 IN CHRS 10.0
END DESCRIPTION:
XS GIS Cut Line= 4
      3509257.20     10545916.87      3508818.86     10546541.84
      3508636.57     10546915.11      3509109.67     10548234.58
#Sta/Elev= 30
  4017.3  444.99  4210.2  437.41  4355.0  428.45  4469.6  423.04  4588.2  419.58
  4684.0  416.26  4692.7  417.11  4704.8  415.93  4735.5  414.11  4818.0  411.66
  4858.5  409.74  4895.7  409.64  4971.1  409.62  4980.8  404.81  4985.0  403.95
  4987.8  403.45  4991.0  403.95  5003.0  407.15  5033.1  409.92  5038.7  408.92
  5055.6  409.83  5195.5  407.43  5228.4  408.32  5245.5  407.16  5253.9  408.23
  5294.9  408.78  5637.7  411.82  5903.8  416.07  6385.2  432.00  6597.8  434.00
#Mann=11,-1,0
  4017.3    0.05       0  4210.2    0.16       0  4355.0    0.12       0
  4588.2    0.16       0  4704.8    0.12       0  4735.5    0.16       0
  4818.0    0.12       0  4895.7    0.16       0  4985.0    0.07       0
  4991.0    0.16       0  5294.9    0.05       0
Bank Sta=4985,4991
Exp/Cntr=0.3,0.1

Type RM Length L Ch R = 1,4964,915,915,915
BEGIN DESCRIPTION:
UNT0086 IN CHRS 9.0
END DESCRIPTION:
XS GIS Cut Line= 4
      3508315.39     10546094.79      3508193.86     10546502.78
      3508280.66     10547800.52      3508237.26     10548356.08
#Sta/Elev= 30
  4100.5  427.02  4159.6  425.93  4230.1  422.72  4326.8  417.24  4374.2  412.81
  4412.6  410.80  4452.0  406.82  4478.9  405.50  4545.1  404.52  4695.4  404.75
  4966.1  407.19  4986.1  406.26  4996.1  403.52  5003.1  403.04  5005.9  402.54
  5009.1  403.04  5016.2  405.99  5022.8  407.34  5126.4  407.45  5473.0  415.17
  5497.2  414.80  5527.3  417.08  5587.4  417.42  5620.8  419.14  5657.6  420.46
  5677.6  419.34  5697.7  420.44  5778.2  421.62  6126.6  431.02  6384.1  436.46
#Mann=5,-1,0
  4100.5    0.05       0  4230.1    0.16       0  5003.1    0.07       0
  5009.1    0.16       0  5620.8    0.05       0
Bank Sta=5003.1,5009.1
Exp/Cntr=0.3,0.1

Type RM Length L Ch R = 1,4049,946,946,946
BEGIN DESCRIPTION:
UNT0086 IN CHRS 7.0
END DESCRIPTION:
XS GIS Cut Line= 2
      3508015.92     10545747.53      3507183.28     10547768.42
#Sta/Elev= 30
  4238.8  427.96  4329.0  427.45  4355.9  426.84  4492.0  422.76  4564.7  418.74
  4794.8  406.55  4889.4  403.12  4978.7  402.32  4986.5  399.67  4989.3  399.17
  4992.5  399.67  4995.9  400.90  5001.3  399.94  5011.1  403.14  5140.9  402.23
  5378.9  403.86  5700.4  412.20  5749.6  413.78  5813.8  415.38  5861.7  414.59
  5915.0  416.72  5920.4  415.52  5938.9  417.86  5962.9  418.55  5968.3  416.59
  5992.2  419.73  5997.6  418.26  6052.7  422.78  6244.0  426.40  6424.5  429.23
#Mann=10,-1,0
  4238.8    0.16       0  4329.0    0.05       0  4355.9    0.12       0
  4564.7    0.16       0  4986.5    0.07       0  4992.5    0.16       0
  5700.4    0.05       0  5749.6    0.16       0  6052.7    0.12       0
  6244.0    0.16       0
Bank Sta=4986.5,4992.5
Exp/Cntr=0.3,0.1

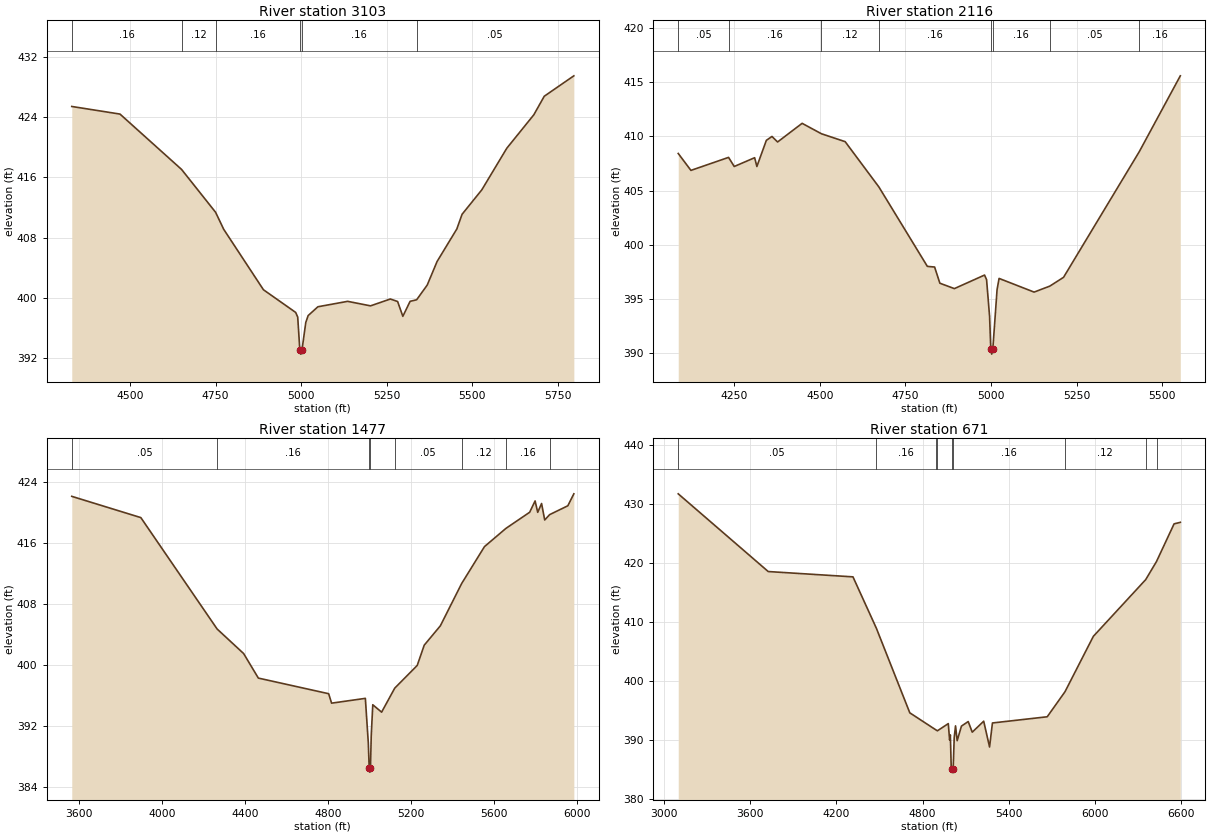
Type RM Length L Ch R = 1,3103,987,987,987
BEGIN DESCRIPTION:
UNT0086 IN CHRS 4.1
END DESCRIPTION:
XS GIS Cut Line= 3
      3507768.48     10545539.25      3507356.18     10545756.25
      3506509.81     10546290.12
#Sta/Elev= 30
  4329.9  425.41  4470.8  424.40  4650.8  417.04  4750.0  411.36  4773.7  409.10
  4889.8  401.07  4983.9  398.06  4989.9  397.44  4996.2  393.02  4999.0  392.52
  5002.2  393.02  5013.5  396.73  5020.4  397.64  5048.9  398.81  5135.8  399.53
  5202.6  398.93  5260.5  399.84  5281.7  399.51  5297.0  397.54  5318.2  399.53
  5337.3  399.74  5368.2  401.69  5397.0  404.82  5454.7  409.14  5470.0  411.09
  5527.7  414.34  5600.6  419.86  5679.5  424.30  5710.1  426.77  5796.5  429.48
#Mann=6,-1,0
  4329.9    0.16       0  4650.8    0.12       0  4750.0    0.16       0
  4996.2    0.07       0  5002.2    0.16       0  5337.3    0.05       0
Bank Sta=4996.2,5002.2
Exp/Cntr=0.3,0.1

Type RM Length L Ch R = 1,2116,639,639,639
BEGIN DESCRIPTION:
UNT0086 IN CHRS 4.0
END DESCRIPTION:
XS GIS Cut Line= 3
      3507669.58     10544789.22      3507257.22     10545006.25
      3506410.91     10545540.08
#Sta/Elev= 30
  4086.2  408.43  4123.3  406.87  4233.2  408.07  4249.8  407.23  4309.4  408.04
  4315.9  407.23  4343.6  409.64  4360.0  410.00  4376.4  409.49  4448.1  411.21
  4504.4  410.25  4573.8  409.52  4672.4  405.34  4813.9  398.02  4835.1  397.96
  4850.4  396.47  4892.8  395.97  4981.0  397.22  4986.9  396.79  4995.7  393.40
  4999.2  390.43  5001.9  389.93  5005.2  390.43  5017.5  395.87  5023.4  396.91
  5125.7  395.65  5171.6  396.20  5211.7  397.01  5433.0  408.60  5552.8  415.59
#Mann=8,-1,0
  4086.2    0.05       0  4233.2    0.16       0  4504.4    0.12       0
  4672.4    0.16       0  4999.2    0.07       0  5005.2    0.16       0
  5171.6    0.05       0  5433.0    0.16       0
Bank Sta=4999.2,5005.2
Exp/Cntr=0.3,0.1

Type RM Length L Ch R = 1,1477,806,806,806
BEGIN DESCRIPTION:
UNT0086 IN CHRS 2.0
END DESCRIPTION:
XS GIS Cut Line= 3
      3507628.72     10543967.22      3506413.47     10545071.36
      3506198.20     10545821.34
#Sta/Elev= 30
  3564.8  422.13  3898.0  419.34  4266.1  404.72  4393.9  401.50  4464.9  398.28
  4804.1  396.23  4818.3  394.99  4981.2  395.62  4995.4  389.78  4999.8  386.44
  5002.5  385.94  5005.8  386.44  5009.5  390.70  5017.0  394.78  5059.6  393.81
  5122.9  396.96  5231.4  399.94  5265.2  402.60  5343.0  405.14  5445.6  410.68
  5555.8  415.53  5659.1  417.92  5773.8  420.04  5800.1  421.53  5812.7  420.03
  5831.3  421.19  5846.4  419.03  5870.3  419.73  5958.0  420.89  5987.0  422.46
#Mann=8,-1,0
  3564.8    0.05       0  4266.1    0.16       0  4999.8    0.07       0
  5005.8    0.16       0  5122.9    0.05       0  5445.6    0.12       0
  5659.1    0.16       0  5870.3    0.12       0
Bank Sta=4999.8,5005.8
Exp/Cntr=0.3,0.1

Type RM Length L Ch R = 1,671,0,0,0
BEGIN DESCRIPTION:
UNT0086 IN CHRS 1.0
END DESCRIPTION:
XS GIS Cut Line= 4
      3507990.88     10543559.00      3506714.86     10544340.24
      3506228.75     10544461.77      3506098.54     10545954.85
#Sta/Elev= 30
  3098.9  431.67  3725.6  418.50  4315.6  417.60  4478.4  408.90  4711.3  394.56
  4895.5  391.63  4903.3  391.51  4979.3  392.73  4988.5  389.96  4993.7  390.82
  4999.9  385.15  5007.2  385.01  5010.0  384.51  5013.2  385.01  5020.5  390.33
  5029.7  392.35  5041.2  389.84  5071.0  392.31  5118.1  393.08  5146.2  391.28
  5225.9  393.14  5266.7  388.77  5286.7  392.84  5668.2  393.89  5791.9  398.13
  5989.4  407.52  6353.9  417.13  6429.1  420.20  6551.5  426.58  6594.9  426.84
#Mann=9,-1,0
  3098.9    0.05       0  4478.4    0.16       0  4895.5    0.05       0
  4903.3    0.16       0  5007.2    0.07       0  5013.2    0.16       0
  5791.9    0.12       0  6353.9    0.16       0  6429.1    0.12       0
Bank Sta=5007.2,5013.2
Exp/Cntr=0.3,0.1

Chan Stop Cuts=-1