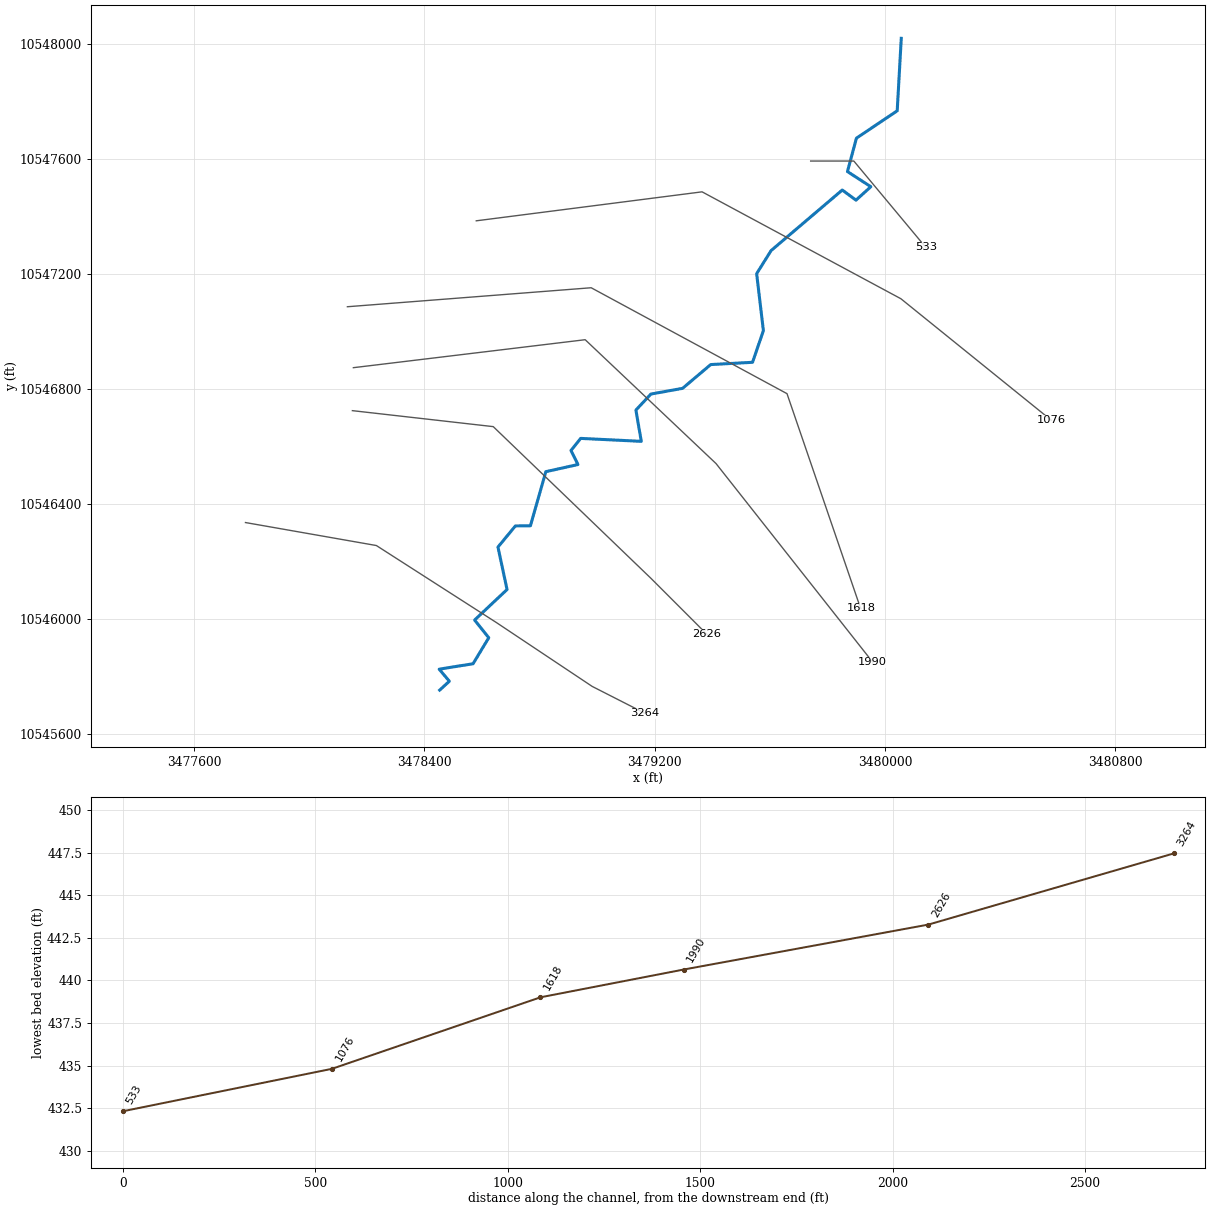
--- UNT00921 IN CHRS.prj (project) ---

Proj Title=UNT00921 IN CHRS Base Level Engineering
Current Plan=p01
Default Exp/Contr=0.3,0.1
English Units
Geom File=g01
Flow File=f01
Plan File=p01
BEGIN DESCRIPTION:
UNT00921 IN CHRS
END DESCRIPTION:

--- UNT00921 IN CHRS.p01 (plan) ---

Plan Title=Multiple Run
Short Identifier=Multiple
Geom File=g01
Flow File=f01
Subcritical Flow
K Sum by GR= 0
Std Step Tol= 0.01
Critical Tol= 0.01
Num of Std Step Trials= 20
Max Error Tol= 0.3
Flow Tol Ratio= 0.001
Split Flow NTrial= 30
Split Flow Tol= 0.02
Split Flow Ratio= 0.02
Log Output Level= 0
Friction Slope Method= 1
Unsteady Friction Slope Method= 2
Unsteady Bridges Friction Slope Method= 1
Parabolic Critical Depth
Global Vel Dist=  1 , 1 , 1
Global Log Level= 0
CheckData=True
Encroach Param= -1, 0, 0, 0
BEGIN DESCRIPTION:
Multiple Run
END DESCRIPTION:

--- UNT00921 IN CHRS.f01 (steady flow) ---

Flow Title=Multiple
Number of Profiles=7
Profile Names=10-year,25-year,50-year,1pct_min,100-year,1pct_plu,500-year
River Rch & RM= UNT00921 IN CHRS,Reach-1,3264
     213     257     287     235     317     429     386
Boundary for River Rch & Prof#=UNT00921 IN CHRS,Reach-1,1
Up Type=0
Dn Type=3
Dn Slope=0.005
Boundary for River Rch & Prof#=UNT00921 IN CHRS,Reach-1,2
Up Type=0
Dn Type=3
Dn Slope=0.005
Boundary for River Rch & Prof#=UNT00921 IN CHRS,Reach-1,3
Up Type=0
Dn Type=3
Dn Slope=0.005
Boundary for River Rch & Prof#=UNT00921 IN CHRS,Reach-1,4
Up Type=0
Dn Type=3
Dn Slope=0.005
Boundary for River Rch & Prof#=UNT00921 IN CHRS,Reach-1,5
Up Type=0
Dn Type=3
Dn Slope=0.005
Boundary for River Rch & Prof#=UNT00921 IN CHRS,Reach-1,6
Up Type=0
Dn Type=3
Dn Slope=0.005
Boundary for River Rch & Prof#=UNT00921 IN CHRS,Reach-1,7
Up Type=0
Dn Type=3
Dn Slope=0.005

--- UNT00921 IN CHRS.g01 (geometry) ---

Geom Title=Existing Conditions

River Reach=UNT00921 IN CHRS,Reach-1
Reach XY= 30
      3478452.89     10545753.02      3478486.48     10545783.87
      3478451.05     10545825.72      3478568.90     10545844.63
      3478623.35     10545934.89      3478574.16     10545996.48
      3478686.94     10546102.54      3478655.35     10546250.21
      3478715.97     10546323.50      3478768.13     10546324.09
      3478821.72     10546512.09      3478933.32     10546536.90
      3478909.13     10546585.77      3478942.84     10546627.78
      3479153.40     10546617.54      3479134.80     10546726.15
      3479186.89     10546781.83      3479297.00     10546801.70
      3479394.75     10546884.33      3479540.08     10546892.19
      3479577.81     10547002.20      3479554.33     10547200.19
      3479604.68     10547280.55      3479851.94     10547490.93
      3479899.60     10547455.77      3479951.16     10547502.39
      3479869.94     10547555.04      3479901.16     10547671.14
      3480042.83     10547766.19      3480056.91     10548018.07

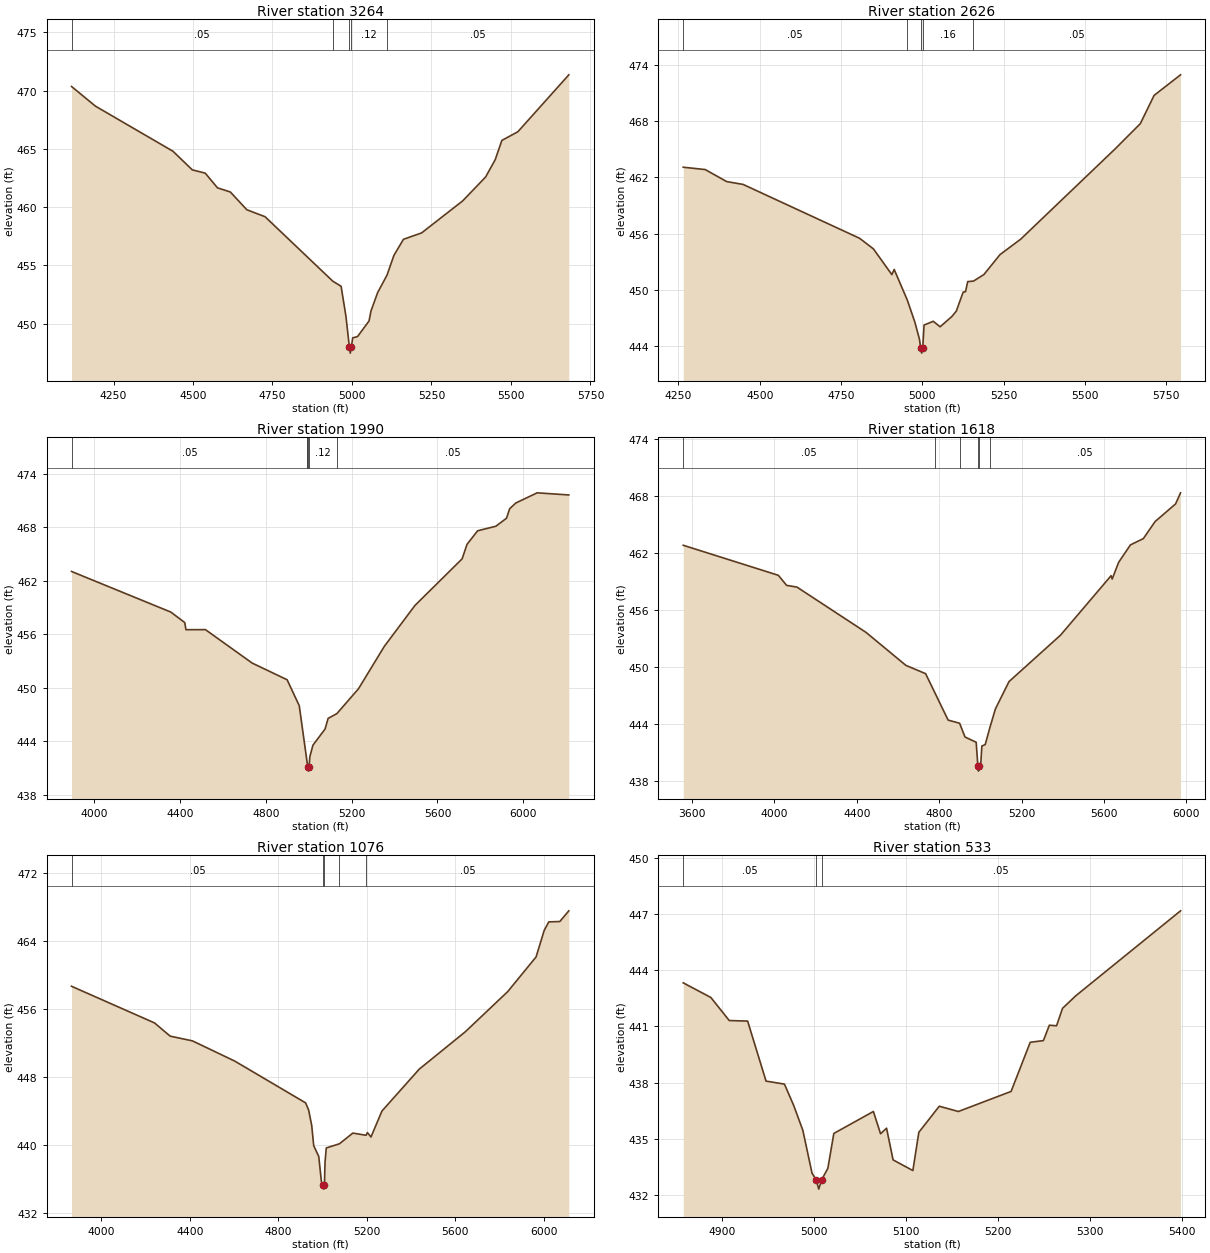
Type RM Length L Ch R = 1,3264,638,638,638
BEGIN DESCRIPTION:
UNT00921 IN CHRS 6.0
END DESCRIPTION:
XS GIS Cut Line= 5
      3477777.89     10546335.31      3478232.76     10546255.44
      3478649.43     10545988.08      3478982.76     10545765.86
      3479166.75     10545672.13
#Sta/Elev= 30
  4118.0  470.35  4193.3  468.66  4437.0  464.79  4497.9  463.19  4538.5  462.91
  4577.0  461.65  4617.6  461.29  4669.2  459.77  4726.7  459.17  4939.9  453.63
  4965.8  453.20  4981.0  450.63  4991.9  447.96  4994.7  447.46  4997.9  447.96
  5002.2  448.77  5017.4  448.88  5053.7  450.22  5059.7  451.07  5080.8  452.66
  5110.1  454.15  5131.9  455.85  5161.9  457.23  5219.0  457.78  5348.2  460.53
  5420.3  462.58  5450.4  464.06  5471.4  465.72  5521.6  466.46  5682.0  471.35
#Mann=5,-1,0
  4118.0    0.05       0  4939.9    0.12       0  4991.9    0.07       0
  4997.9    0.12       0  5110.1    0.05       0
Bank Sta=4991.9,4997.9
Exp/Cntr=0.3,0.1

Type RM Length L Ch R = 1,2626,636,636,636
BEGIN DESCRIPTION:
UNT00921 IN CHRS 5.0
END DESCRIPTION:
XS GIS Cut Line= 4
      3478149.44     10546724.19      3478639.01     10546668.64
      3479187.62     10546140.86      3479381.95     10545946.53
#Sta/Elev= 30
  4264.8  463.08  4332.3  462.83  4398.3  461.55  4448.6  461.25  4807.0  455.51
  4849.5  454.38  4906.1  451.64  4913.3  452.19  4953.7  448.92  4976.8  446.58
  4991.0  444.76  4994.9  443.78  4997.7  443.28  5000.9  443.78  5005.1  446.27
  5033.4  446.67  5054.5  446.09  5090.0  447.16  5104.2  447.75  5125.3  449.78
  5132.5  449.82  5139.4  450.90  5157.0  450.95  5189.1  451.65  5238.5  453.77
  5302.3  455.42  5592.1  465.02  5669.9  467.72  5712.3  470.73  5793.6  472.92
#Mann=5,-1,0
  4264.8    0.05       0  4953.7    0.16       0  4994.9    0.07       0
  5000.9    0.16       0  5157.0    0.05       0
Bank Sta=4994.9,5000.9
Exp/Cntr=0.3,0.1

Type RM Length L Ch R = 1,1990,372,372,372
BEGIN DESCRIPTION:
UNT00921 IN CHRS 4.0
END DESCRIPTION:
XS GIS Cut Line= 4
      3478152.87     10546873.50      3478958.46     10546970.72
      3479413.32     10546540.17      3479957.79     10545850.04
#Sta/Elev= 30
  3895.1  463.06  4357.7  458.50  4422.6  457.32  4428.2  456.52  4518.8  456.53
  4736.9  452.77  4899.5  450.90  4956.1  447.98  4992.8  441.60  4994.4  441.34
  4995.6  441.14  4998.4  440.64  5001.6  441.14  5005.5  442.27  5019.7  443.55
  5076.3  445.37  5090.5  446.56  5131.4  447.10  5232.0  449.89  5352.6  454.66
  5495.3  459.25  5714.9  464.48  5737.4  466.10  5787.1  467.63  5872.0  468.14
  5921.7  469.04  5936.2  470.10  5965.1  470.75  6064.4  471.89  6211.9  471.65
#Mann=6,-1,0
  3895.1    0.05       0  4992.8    0.16       0  4994.4    0.12       0
  4995.6    0.07       0  5001.6    0.12       0  5131.4    0.05       0
Bank Sta=4995.6,5001.6
Exp/Cntr=0.3,0.1

Type RM Length L Ch R = 1,1618,542,542,542
BEGIN DESCRIPTION:
UNT00921 IN CHRS 3.0
END DESCRIPTION:
XS GIS Cut Line= 5
      3478132.06     10547085.30      3478979.29     10547151.28
      3479659.85     10546783.22      3479913.32     10546043.64
      3479916.80     10546036.68
#Sta/Elev= 30
  3558.3  462.78  4019.7  459.62  4059.9  458.56  4110.0  458.38  4445.4  453.61
  4638.7  450.14  4734.2  449.27  4780.2  447.22  4843.6  444.38  4899.3  444.05
  4925.5  442.60  4979.7  442.05  4988.1  439.51  4990.9  439.01  4994.1  439.51
  5001.6  439.67  5007.3  441.65  5023.5  441.80  5045.3  443.52  5072.9  445.55
  5138.9  448.43  5389.4  453.33  5634.4  459.58  5639.7  459.23  5670.9  460.98
  5728.2  462.82  5790.8  463.48  5848.0  465.28  5947.2  467.13  5971.4  468.30
#Mann=6,-1,0
  3558.3    0.05       0  4780.2     0.1       0  4899.3    0.12       0
  4988.1    0.07       0  4994.1    0.12       0  5045.3    0.05       0
Bank Sta=4988.1,4994.1
Exp/Cntr=0.3,0.1

Type RM Length L Ch R = 1,1076,543,543,543
BEGIN DESCRIPTION:
UNT00921 IN CHRS 2.0
END DESCRIPTION:
XS GIS Cut Line= 4
      3478579.99     10547383.92      3479364.71     10547484.61
      3480055.68     10547113.08      3480578.57     10546690.62
#Sta/Elev= 30
  3865.5  458.66  4240.7  454.35  4311.2  452.80  4412.1  452.24  4603.6  449.86
  4923.7  444.95  4937.5  444.09  4951.3  442.28  4960.2  439.92  4983.0  438.65
  4995.1  435.68  5002.7  435.31  5005.4  434.81  5008.7  435.31  5011.3  437.95
  5017.0  439.65  5076.4  440.14  5137.1  441.40  5196.8  441.14  5202.9  441.46
  5219.1  440.94  5268.6  443.99  5437.4  448.92  5645.5  453.31  5837.4  458.04
  5965.4  462.11  6002.1  465.23  6022.9  466.23  6072.5  466.27  6113.4  467.53
#Mann=5,-1,0
  3865.5    0.05       0  5002.7   0.035       0  5008.7    0.05       0
  5076.4     0.1       0  5196.8    0.05       0
Bank Sta=5002.7,5008.7
Exp/Cntr=0.3,0.1

Type RM Length L Ch R = 1,533,0,0,0
BEGIN DESCRIPTION:
UNT00921 IN CHRS 1.0
END DESCRIPTION:
XS GIS Cut Line= 3
      3479742.06     10547591.64      3479892.11     10547591.64
      3480142.14     10547291.61
#Sta/Elev= 30
  4858.1  443.32  4888.1  442.54  4908.1  441.31  4928.1  441.28  4948.1  438.08
  4968.1  437.92  4978.1  436.79  4988.1  435.46  4998.1  433.17  5002.6  432.82
  5005.4  432.32  5008.6  432.82  5015.3  433.43  5021.8  435.29  5064.8  436.46
  5072.6  435.27  5079.1  435.57  5086.2  433.88  5107.7  433.31  5114.2  435.35
  5136.4  436.74  5157.2  436.46  5214.5  437.53  5235.3  440.15  5249.6  440.24
  5256.1  441.06  5263.9  441.03  5270.4  441.96  5284.8  442.63  5398.7  447.16
#Mann=3,-1,0
  4858.1    0.05       0  5002.6   0.035       0  5008.6    0.05       0
Bank Sta=5002.6,5008.6
Exp/Cntr=0.3,0.1

Chan Stop Cuts=-1