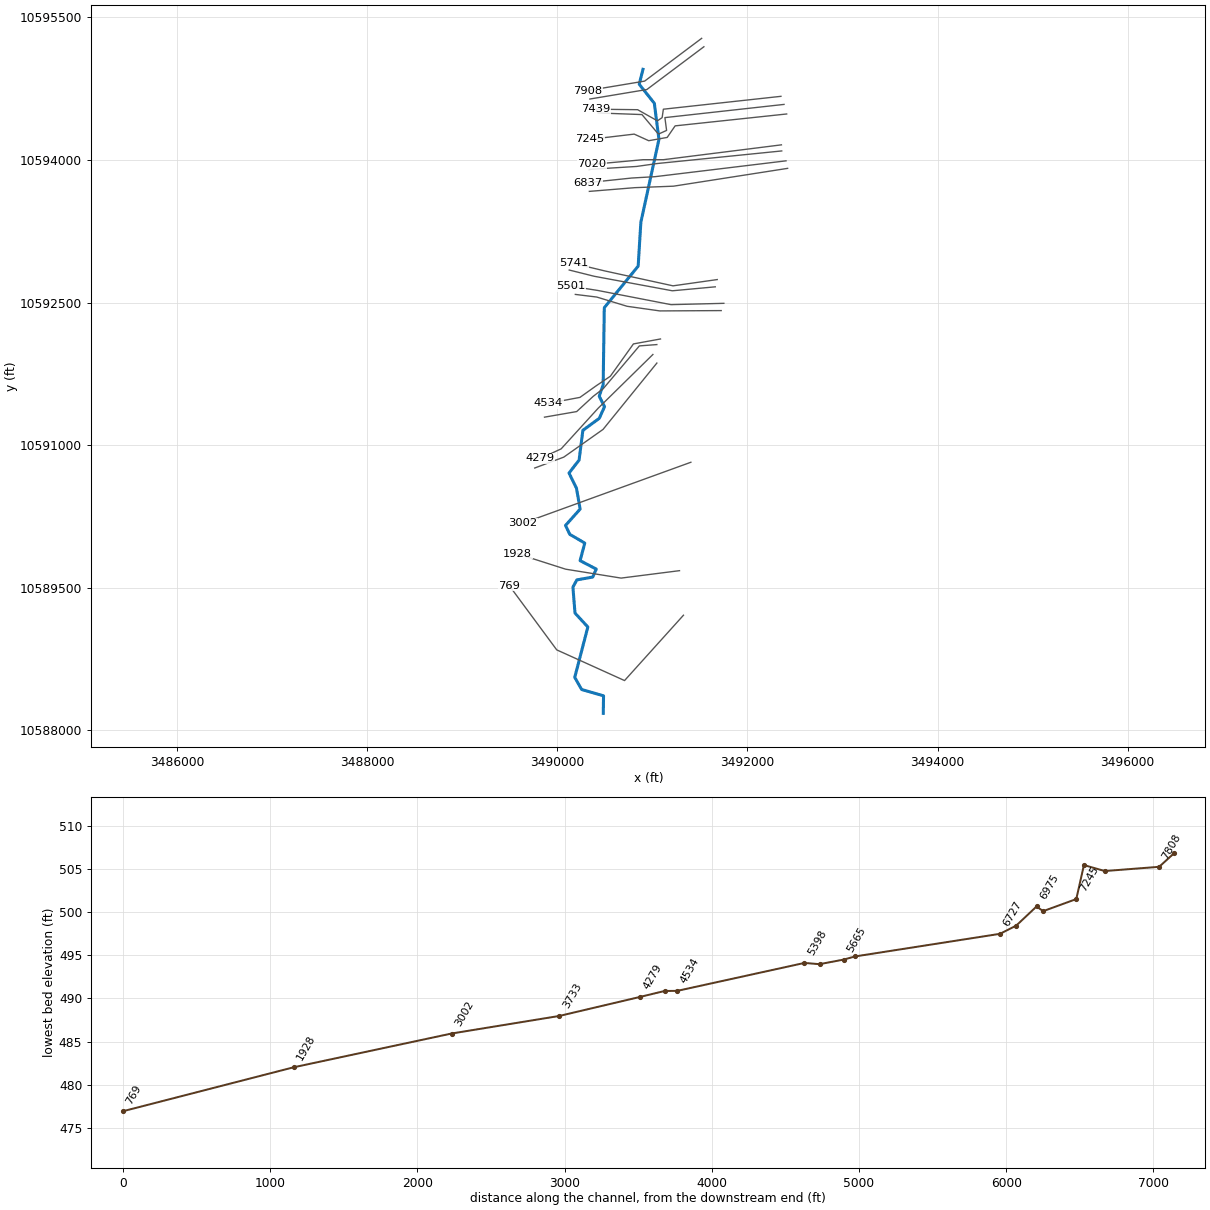
--- UNT00946 IN CHRS.prj (project) ---

Proj Title=UNT00946 IN CHRS Base Level Engineering
Current Plan=p01
Default Exp/Contr=0.3,0.1
English Units
Geom File=g01
Flow File=f01
Plan File=p01
Y Axis Title=Elevation
X Axis Title(PF)=Main Channel Distance
X Axis Title(XS)=Station
BEGIN DESCRIPTION:
UNT00946 IN CHRS
END DESCRIPTION:
DSS Export Rating Curves= 0
DSS Export Rating Curve Sorted= 0
DSS Export Volume Flow Curves= 0
DXF OffsetX= 0
DXF OffsetY= 0
DXF ScaleX= 1
DXF ScaleY= 10

--- UNT00946 IN CHRS.p01 (plan) ---

Plan Title=Multiple Run
Program Version=4.10
Short Identifier=Multiple
Geom File=g01
Flow File=f01
Subcritical Flow
K Sum by GR= 0
Std Step Tol= 0.01
Critical Tol= 0.01
Num of Std Step Trials= 20
Max Error Tol= 0.3
Flow Tol Ratio= 0.001
Split Flow NTrial= 30
Split Flow Tol= 0.02
Split Flow Ratio= 0.02
Log Output Level= 0
Friction Slope Method= 1
Unsteady Friction Slope Method= 2
Unsteady Bridges Friction Slope Method= 1
Parabolic Critical Depth
Global Vel Dist= 1 , 1 , 1
Global Log Level= 0
CheckData=True
Encroach Param=-1 ,0,0, 0
BEGIN DESCRIPTION:
Multiple Run
END DESCRIPTION:
Computation Interval=1HOUR
Output Interval=1HOUR
Run HTab= 0
Run UNet= 0
Run PostProcess= 0
Run WQNet= 0
UNET Theta= 1
UNET Theta Warmup= 1
UNET ZTol= 0.02
UNET ZSATol= 0.05
UNET MxIter= 20
UNET MaxInSteps= 0
UNET DtIC= 0
UNET DtMin= 0
UNET MaxCRTS= 20
UNET WFStab= 2
UNET SFStab= 1
UNET WFX= 1
UNET SFX= 1
UNET DSS MLevel= 4
UNET DZMax Abort= 100
UNET Convert EG Bridges= 0
UNET Use Existing IB Tables=-1
UNET Froude Reduction=False
UNET Froude Limit= 1
UNET Froude Power= 10
UNET Time Slicing=0,0, 5
UNET Junction Losses=0
Instantaneous Interval=1HOUR
Write IC File= 0
Write IC File at Sim End=0
Echo Input=False
Echo Parameters=False
Echo Output=False
Write Detailed= 0
WQ AD Non Conservative
WQ ULTIMATE=-1
WQ Max Comp Step=1HOUR
WQ Output Interval=15MIN
WQ Output Selected Increments= 0
WQ Output face flow=0
WQ Output face velocity=0
WQ Output face area=0
WQ Output face dispersion=0
WQ Output cell volume=0
WQ Output cell surface area=0
WQ Output cell continuity=0
WQ Output cumulative cell continuity=0
WQ Output face conc=0
WQ Output face dconc_dx=0
WQ Output face courant=0
WQ Output face peclet=0
WQ Output face adv mass=0
WQ Output face disp mass=0
WQ Output cell mass=0
WQ Output cell source sink temp=0
WQ Output cell source sink nsm=0
WQ Output MaxMinRange=-1
WQ Daily Max Min Mean=-1
WQ Daily Range=0
WQ Daily Time=0
WQ Create Restart=0
WQ Fixed Restart=0
WQ System Summary=0
WQ Use Fixed Temperature=0
Sorting and Armoring Iterations= 10
XS Update Threshold= 0.02
Hydraulics Update Threshold= 0.02
Energy Slope Method= 1
Volume Change Method= 0
XS Weighting Method= 0
Number of US Weighted Cross Sections= 1
Number of DS Weighted Cross Sections= 1
Upstream XS Weight=0.25
Main XS Weight=0.5
Downstream XS Weight=0.25
Number of DS XS's Weighted with US Boundary= 1
Upstream Boundary Weight= 1
Weight of XSs Associated with US Boundary= 0
Number of US XS's Weighted with DS Boundary= 1
Downstream Boundary Weight= 0.5
Weight of XSs Associated with DS Boundary= 0.5
Sediment Output Level= 4
Mass or Volume Output= 0
Output Increment Type= 1
Profile and TS Output Increment= 10
XS Output Flag= 0
XS Output Increment= 10
Disregard all LS=0
Disregard all Conn=0
Disregard all Breaches=0
Disregard all Pumps=0

--- UNT00946 IN CHRS.f01 (steady flow) ---

Flow Title=Multiple
Program Version=4.10
Number of Profiles= 7
Profile Names=10-year,25-year,50-year,1pct_min,100-year,1pct_plu,500-year
River Rch & RM=UNT00946 IN CHRS,Reach-1         ,7908
     341     420     476     393     531     719     660
Boundary for River Rch & Prof#=UNT00946 IN CHRS,Reach-1         , 1
Up Type= 0
Dn Type= 3
Dn Slope=0.005
Boundary for River Rch & Prof#=UNT00946 IN CHRS,Reach-1         , 2
Up Type= 0
Dn Type= 3
Dn Slope=0.005
Boundary for River Rch & Prof#=UNT00946 IN CHRS,Reach-1         , 3
Up Type= 0
Dn Type= 3
Dn Slope=0.005
Boundary for River Rch & Prof#=UNT00946 IN CHRS,Reach-1         , 4
Up Type= 0
Dn Type= 3
Dn Slope=0.005
Boundary for River Rch & Prof#=UNT00946 IN CHRS,Reach-1         , 5
Up Type= 0
Dn Type= 3
Dn Slope=0.005
Boundary for River Rch & Prof#=UNT00946 IN CHRS,Reach-1         , 6
Up Type= 0
Dn Type= 3
Dn Slope=0.005
Boundary for River Rch & Prof#=UNT00946 IN CHRS,Reach-1         , 7
Up Type= 0
Dn Type= 3
Dn Slope=0.005
DSS Import GetInterval= 0
DSS Import GetPeak= 0
DSS Import FillOption= 0

--- UNT00946 IN CHRS.g01 (geometry) ---

Geom Title=Existing Conditions
Program Version=4.10

River Reach=UNT00946 IN CHRS,Reach-1
Reach XY= 30
      3490901.36     10594954.26      3490861.73       10594797.
      3491020.73     10594596.71      3491069.34     10594217.93
      3490879.06     10593345.71      3490850.59      10592883.9
       3490494.3     10592445.94      3490482.27     10591635.83
      3490441.17     10591515.09      3490496.72     10591404.68
      3490441.17     10591281.76      3490268.95     10591156.06
       3490229.1     10590842.88      3490123.19     10590706.93
      3490201.72     10590546.09      3490240.14     10590327.33
      3490085.86     10590155.09      3490131.79     10590061.23
      3490288.75     10589970.04      3490239.87      10589784.9
      3490410.03     10589696.11      3490371.92     10589612.23
      3490205.21     10589582.36      3490164.11     10589506.35
      3490186.02     10589233.29      3490321.18     10589087.01
      3490183.35     10588556.61       3490255.8     10588429.51
      3490486.33     10588362.81       3490483.6     10588178.12

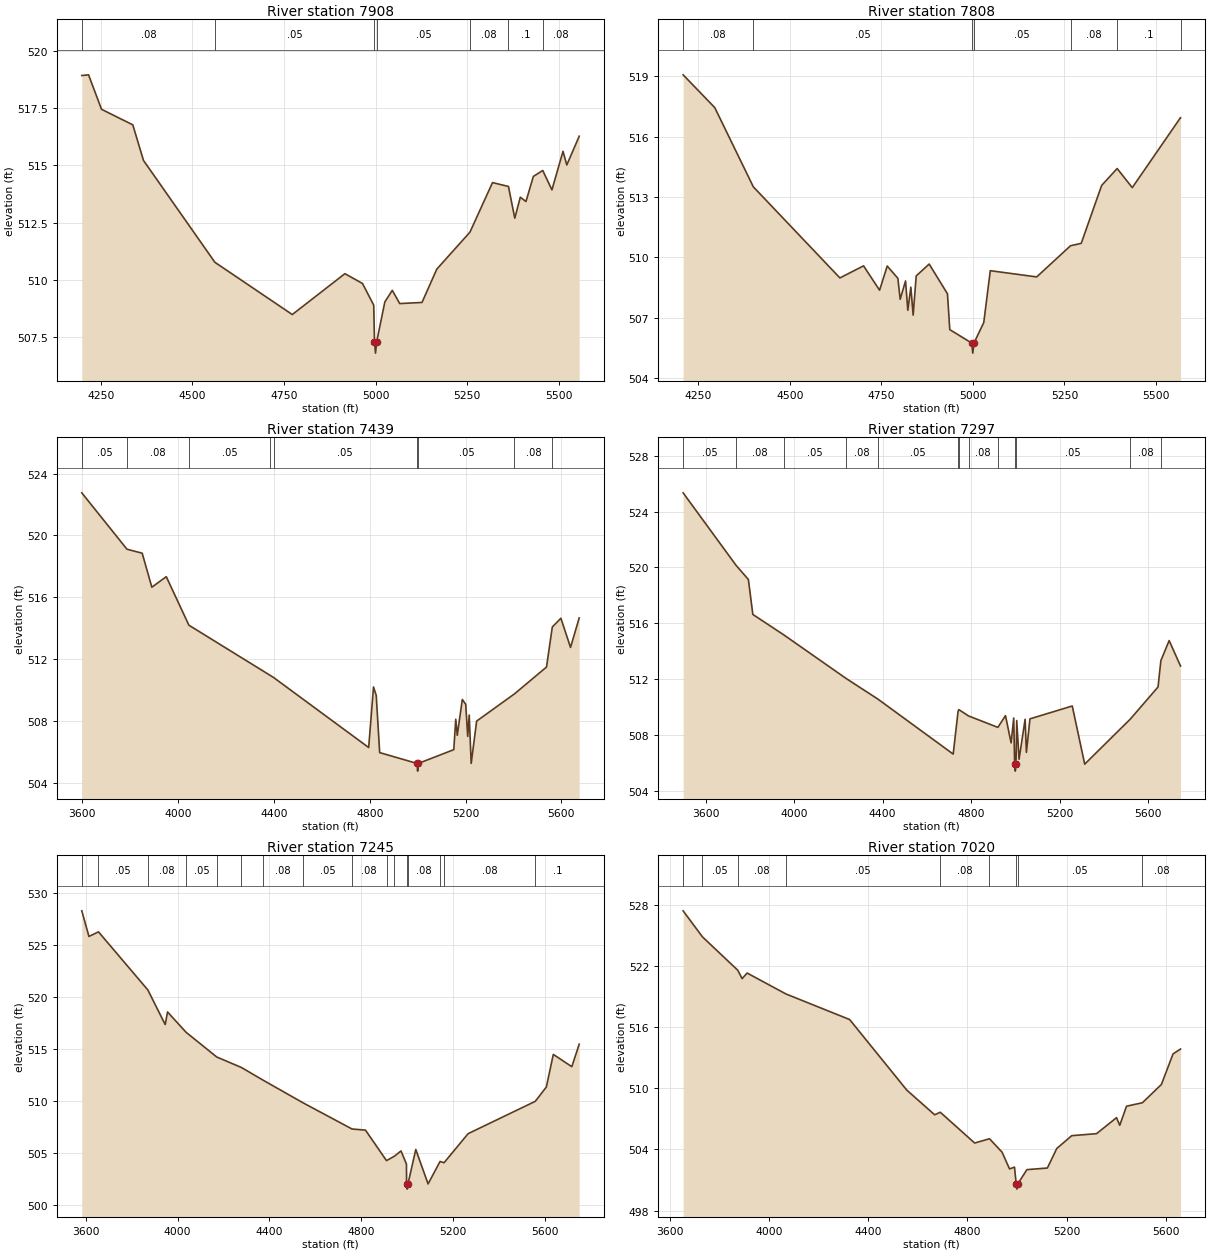
Type RM Length L Ch R = 1 ,7908    ,100,100,100
BEGIN DESCRIPTION:
UNT00946 IN CHRS 15.0b
END DESCRIPTION:
XS GIS Cut Line= 3
      3491518.67     10595280.18      3490918.67     10594830.18
      3490318.64     10594730.18
#Sta/Elev= 30
  4197.7  518.94  4216.2  518.97  4251.6  517.46    4337  516.78  4366.2  515.22
  4561.1  510.76  4772.5  508.47  4916.2  510.26  4964.3  509.83  4994.9  508.88
    4997  507.28  4999.8  506.78    5003  507.28  5025.2  509.02  5045.6  509.53
  5065.9  508.95  5126.7     509  5167.2  510.46  5257.7  512.08  5319.3  514.25
  5362.8  514.08  5380.1  512.69  5395.2  513.61  5410.6  513.42  5430.8  514.52
  5456.5  514.78  5481.5  513.93  5511.8  515.62  5522.1  515.02    5556  516.28
#Mann= 7 ,-1 , 0
  4197.7     .08       0  4561.1     .05       0    4997     .04       0
    5003     .05       0  5257.7     .08       0  5362.8      .1       0
  5456.5     .08       0
Bank Sta=4997,5003
XS Rating Curve= 0 ,0
Exp/Cntr=0.3,0.1

Type RM Length L Ch R = 1 ,7808    ,369,369,369
BEGIN DESCRIPTION:
UNT00946 IN CHRS 15.0
END DESCRIPTION:
XS GIS Cut Line= 3
      3491542.07     10595191.62      3490942.11     10594741.64
      3490342.14     10594641.65
#Sta/Elev= 30
  4208.9  519.07  4295.3  517.44  4400.6   513.5    4637  508.97  4701.6  509.57
  4745.3  508.36  4766.2  509.56  4795.3  508.95  4801.6  507.91  4816.2  508.82
  4822.4  507.36  4830.7  508.51    4837  507.12  4845.3  509.07  4880.7  509.66
  4930.7  508.18    4937   506.4    4997  505.73  4999.8  505.23    5003  505.73
  5029.8  506.75  5047.6  509.33  5174.3  509.02  5266.7  510.57  5295.9  510.69
  5351.7  513.57    5394  514.41  5435.3  513.46    5567  516.94  5567.1  516.94
#Mann= 7 ,-1 , 0
  4208.9     .08       0  4400.6     .05       0    4997     .04       0
    5003     .05       0  5266.7     .08       0    5394      .1       0
    5567     .08       0
Bank Sta=4997,5003
XS Rating Curve= 0 ,0
Exp/Cntr=0.3,0.1

Type RM Length L Ch R = 1 ,7439    ,142,142,142
BEGIN DESCRIPTION:
UNT00946 IN CHRS 14.9
END DESCRIPTION:
XS GIS Cut Line= 6
      3492352.82     10594670.02      3491115.81      10594534.6
      3491102.79     10594446.06      3491053.31     10594412.21
      3490844.98      10594529.4      3490405.95     10594534.68
#Sta/Elev= 30
  3597.6  522.76  3786.2  519.11  3849.8  518.85  3890.1  516.65  3950.4  517.33
  4044.8  514.19  4385.2  510.93  4398.6   510.8  4795.4  506.27  4815.6  510.19
    4827  509.64  4841.3  505.94    4997  505.24  4999.8  504.74    5003  505.24
  5150.8  506.13    5159   508.1  5165.3  507.06  5186.4  509.38  5200.7  509.06
  5208.9  506.99  5215.2  508.37  5223.4  505.24  5246.2  507.98    5404  509.74
  5537.9  511.48  5562.1  514.07    5598  514.64  5638.2  512.75  5674.4  514.66
#Mann= 9 ,-1 , 0
  3597.6     .05       0  3786.2     .08       0  4044.8     .05       0
  4385.2     .08       0  4398.6     .05       0    4997     .04       0
    5003     .05       0    5404     .08       0  5562.1      .1       0
Bank Sta=4997,5003
XS Rating Curve= 0 ,0
Exp/Cntr=0.3,0.1

Type RM Length L Ch R = 1 ,7297    ,52,52,52
BEGIN DESCRIPTION:
UNT00946 IN CHRS 14.2
END DESCRIPTION:
XS GIS Cut Line= 6
      3492385.31     10594585.03      3491131.87     10594446.15
      3491149.67     10594311.43      3491063.73     10594272.36
      3490890.55     10594478.09      3490430.87     10594495.02
#Sta/Elev= 30
  3498.6  525.34  3737.5  520.16  3793.5  519.14  3813.7  516.64  3953.4  515.18
  4235.2  512.06  4379.2  510.58  4719.2  506.65  4741.2  509.71  4744.8  509.83
  4788.4  509.38    4921  508.56  4955.5   509.4    4981  507.45  4992.7  509.23
    4997  505.93  4999.8  505.43    5003  505.93  5006.3  509.05  5016.9  506.28
  5044.3  509.14    5050  506.77  5066.2  509.17  5257.3  510.09  5313.6  505.93
  5520.1  509.16    5645  511.45  5657.7  513.33  5695.2  514.77  5746.7  512.95
#Mann= 13 ,-1 , 0
  3498.6     .05       0  3737.5     .08       0  3953.4     .05       0
  4235.2     .08       0  4379.2     .05       0  4741.2     .08       0
  4744.8     .05       0  4788.4     .08       0    4921     .05       0
    4997     .04       0    5003     .05       0  5520.1     .08       0
  5657.7      .1       0
Bank Sta=4997,5003
XS Rating Curve= 0 ,0
Exp/Cntr=0.3,0.1

Type RM Length L Ch R = 1 ,7245    ,225,225,225
BEGIN DESCRIPTION:
UNT00946 IN CHRS 14.0
END DESCRIPTION:
XS GIS Cut Line= 6
      3492413.17     10594484.35      3491239.51     10594359.34
      3491156.18     10594237.82      3490961.73     10594203.09
      3490808.96     10594272.54      3490340.23     10594216.99
#Sta/Elev= 30
  3583.3  528.25  3614.5  525.79    3656  526.23  3870.7  520.65  3946.4  517.32
  3956.5  518.53    4037  516.58  4170.7   514.2  4278.3  513.19  4370.3     512
  4545.2  509.81  4759.5  507.28  4818.1  507.17  4909.6  504.24  4943.8  504.66
  4972.7  505.17  4996.4  503.91    4997     502  4999.8   501.5    5003     502
    5037  505.31  5090.6     502  5142.7  504.16  5160.2  504.04  5264.7  506.83
  5557.2  509.94  5605.4  511.32  5635.6  514.45  5716.2  513.27  5748.3  515.43
#Mann= 16 ,-1 , 0
  3583.3      .1       0    3656     .05       0  3870.7     .08       0
    4037     .05       0  4170.7     .08       0  4278.3     .05       0
  4370.3     .08       0  4545.2     .05       0  4759.5     .08       0
  4909.6     .05       0  4943.8     .08       0    4997     .07       0
    5003     .08       0  5142.7     .05       0  5160.2     .08       0
  5557.2      .1       0
Bank Sta=4997,5003
XS Rating Curve= 0 ,0
Exp/Cntr=0.3,0.1

Type RM Length L Ch R = 1 ,7020    ,45,45,45
BEGIN DESCRIPTION:
UNT00946 IN CHRS 14.1
END DESCRIPTION:
XS GIS Cut Line= 4
      3492357.96      10594159.6      3491115.81     10594003.35
      3490902.27     10594003.35       3490365.2     10593954.06
#Sta/Elev= 30
  3654.5  527.39  3732.3  524.84    3875  521.56  3892.2  520.74  3912.4  521.29
  4068.7  519.24  4325.6  516.73    4556  509.81  4668.3  507.39  4690.9  507.64
  4829.5  504.62  4889.3  505.04  4940.1  503.72  4970.1  502.08  4990.1  502.26
    4997   500.6  4999.8   500.1    5003   500.6  5040.1  502.01  5122.6  502.17
  5160.3  504.08  5220.6  505.34    5321  505.54  5401.3  507.11  5414.3  506.36
  5441.5  508.23  5505.5  508.57  5582.1  510.36  5629.1  513.36  5659.3  513.84
#Mann= 9 ,-1 , 0
  3654.5     .08       0  3732.3     .05       0    3875     .08       0
  4068.7     .05       0  4690.9     .08       0  4889.3     .05       0
    4997     .04       0    5003     .05       0  5505.5     .08       0
Bank Sta=4997,5003
XS Rating Curve= 0 ,0
Exp/Cntr=0.3,0.1

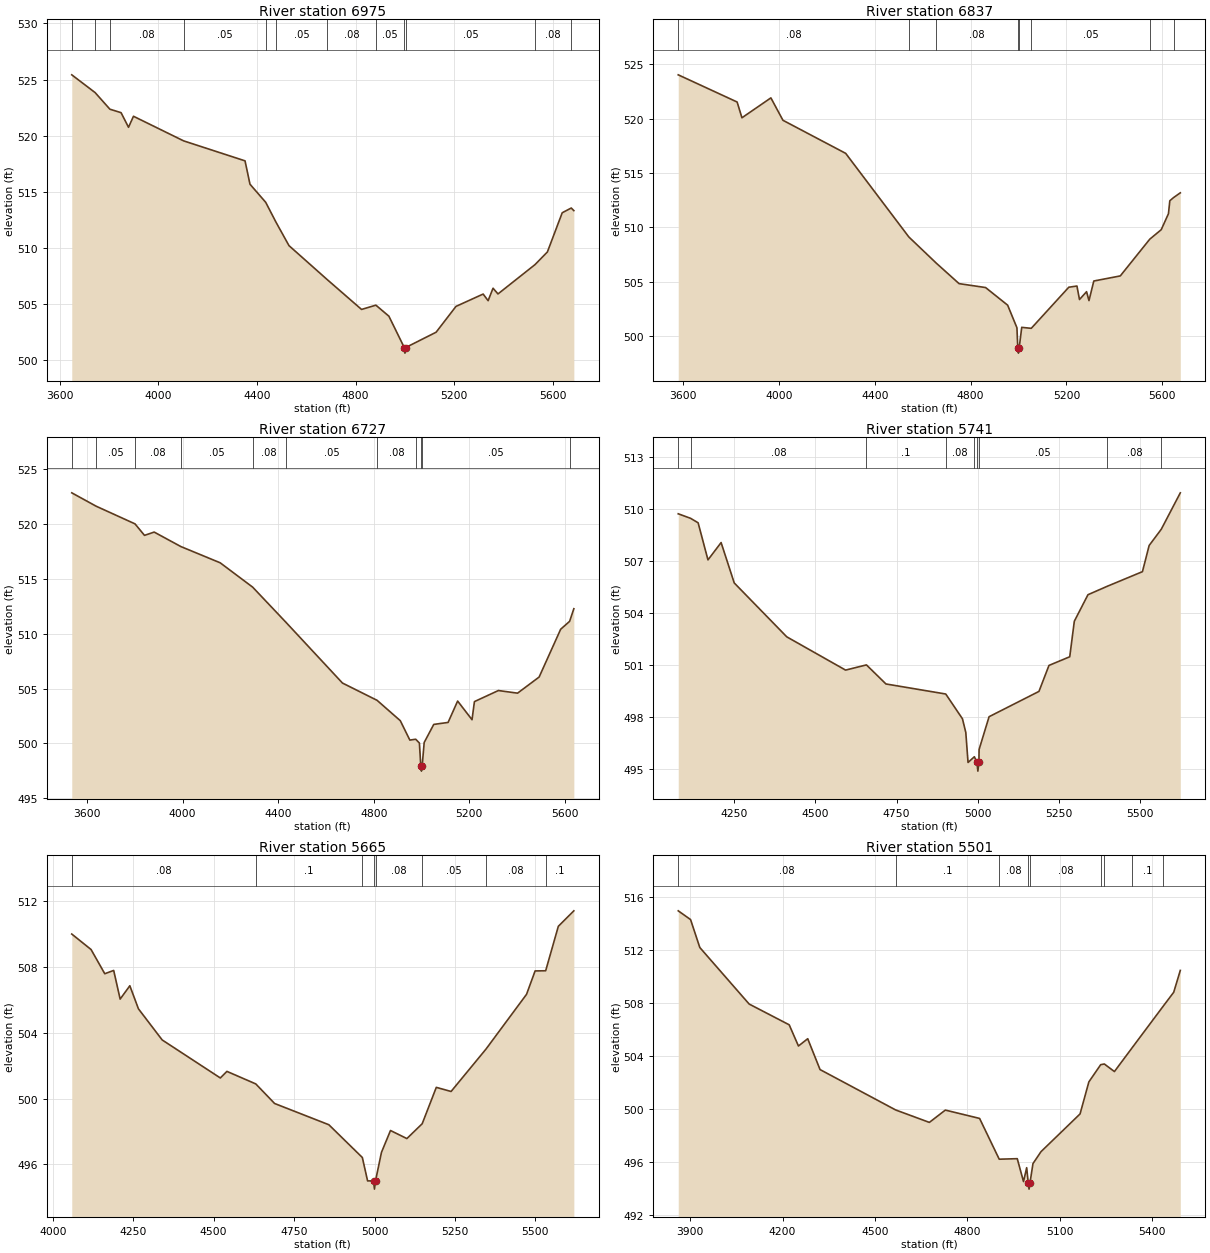
Type RM Length L Ch R = 1 ,6975    ,138,138,138
BEGIN DESCRIPTION:
UNT00946 IN CHRS 14.7
END DESCRIPTION:
XS GIS Cut Line= 4
      3492361.04     10594095.45      3491055.48     10593963.51
      3490833.26     10593932.26      3490335.15     10593901.13
#Sta/Elev= 30
  3648.9  525.42  3743.5  523.84  3803.5  522.36  3848.8  522.05    3879  520.75
  3899.1  521.73  4102.4  519.54  4351.4  517.76  4371.5  515.68  4435.2  514.07
  4476.7  512.31  4529.7  510.21    4684   507.2  4823.8  504.53    4882  504.91
  4934.7  503.93    4997  501.14  4999.8  500.64    5003  501.14  5126.1   502.5
  5206.7   504.8  5316.9   505.9    5337  505.31    5357  506.42    5377  505.91
  5527.1  508.52  5577.4  509.65  5637.5  513.14  5674.1  513.56  5684.6  513.33
#Mann= 12 ,-1 , 0
  3648.9     .08       0  3743.5     .05       0  3803.5     .08       0
  4102.4     .05       0  4435.2     .08       0  4476.7     .05       0
    4684     .08       0    4882     .05       0    4997     .04       0
    5003     .05       0  5527.1     .08       0  5674.1      .1       0
Bank Sta=4997,5003
XS Rating Curve= 0 ,0
Exp/Cntr=0.3,0.1

Type RM Length L Ch R = 1 ,6837    ,110,110,110
BEGIN DESCRIPTION:
UNT00946 IN CHRS 13.0
END DESCRIPTION:
XS GIS Cut Line= 4
      3492406.18     10593991.29      3491027.71     10593824.62
      3490784.65     10593810.73      3490322.87     10593762.12
#Sta/Elev= 30
  3579.4  524.02  3825.3  521.52  3845.4  520.07  3966.3   521.9  4016.6  519.84
  4278.5   516.8  4542.3  509.11    4657   506.7    4752  504.82  4862.7  504.46
  4954.8  502.84  4993.6  500.76    4997  498.93  4999.8  498.43    5003  498.93
  5013.6   500.8  5053.4  500.71  5210.1  504.49  5244.1   504.6  5254.8  503.36
  5284.3  504.08  5294.4  503.26  5314.5  505.06  5425.1  505.53  5548.3  508.91
    5596  509.78  5626.2  511.25  5631.9  512.44  5647.4  512.73  5675.7  513.17
#Mann= 8 ,-1 , 0
  3579.4     .08       0  4542.3     .05       0    4657     .08       0
    4997     .07       0    5003     .08       0  5053.4     .05       0
  5548.3     .08       0  5647.4      .1       0
Bank Sta=4997,5003
XS Rating Curve= 0 ,0
Exp/Cntr=0.3,0.1

Type RM Length L Ch R = 1 ,6727    ,986,986,986
BEGIN DESCRIPTION:
UNT00946 IN CHRS 13.2
END DESCRIPTION:
XS GIS Cut Line= 4
       3492423.1     10593912.21      3491222.59     10593724.71
      3490816.34     10593709.08      3490337.15     10593670.02
#Sta/Elev= 30
  3535.6  522.86  3637.7  521.64  3800.3  520.03  3840.2  518.98  3880.7  519.28
  3992.4  517.96    4157  516.48    4293  514.26  4431.7  511.07  4669.2  505.51
  4813.9  503.94  4911.3  502.08  4951.3  500.31  4975.7  500.39  4991.3  500.04
    4997  497.98  4999.8  497.48    5003  497.98  5011.3  500.09  5051.4  501.74
  5111.4  501.92  5151.4  503.87  5211.6  502.17  5221.7  503.82    5322  504.83
  5402.3  504.59  5492.6  506.06  5582.9  510.42  5620.3  511.14    5638  512.29
#Mann= 11 ,-1 , 0
  3535.6     .08       0  3637.7     .05       0  3800.3     .08       0
  3992.4     .05       0    4293     .08       0  4431.7     .05       0
  4813.9     .08       0  4975.7     .05       0    4997    .035       0
    5003     .05       0  5620.3      .1       0
Bank Sta=4997,5003
XS Rating Curve= 0 ,0
Exp/Cntr=0.3,0.1

Type RM Length L Ch R = 1 ,5741    ,76,76,76
BEGIN DESCRIPTION:
UNT00946 IN CHRS 11.0
END DESCRIPTION:
XS GIS Cut Line= 4
      3491682.65     10592742.21      3491217.41     10592676.24
      3490502.13     10592832.49      3490168.81     10592912.35
#Sta/Elev= 30
  4077.9  509.71  4115.8  509.45  4139.1  509.19  4169.4  507.05  4209.8  508.05
  4250.2  505.72  4411.8  502.61  4592.8  500.69    4657  500.99    4717  499.89
    4901  499.31  4952.4  497.88  4962.7  497.09  4969.6  495.36  4989.1  495.69
    4997  495.36  4999.8  494.86    5003  495.36  5003.6  496.11  5034.3     498
  5187.8  499.46  5218.6  500.96  5282.5  501.46  5296.6  503.51  5338.6  505.04
  5398.3  505.53  5506.2  506.37  5526.8  507.88  5564.2  508.82  5622.7  510.92
#Mann= 9 ,-1 , 0
  4077.9     .05       0  4115.8     .08       0    4657      .1       0
    4901     .08       0  4989.1     .05       0    4997    .035       0
    5003     .05       0  5398.3     .08       0  5564.2      .1       0
Bank Sta=4997,5003
XS Rating Curve= 0 ,0
Exp/Cntr=0.3,0.1

Type RM Length L Ch R = 1 ,5665    ,164,164,164
BEGIN DESCRIPTION:
UNT00946 IN CHRS 11.2
END DESCRIPTION:
XS GIS Cut Line= 4
      3491661.88     10592665.83      3491210.46     10592624.16
      3490387.54     10592776.94      3490125.33     10592842.49
#Sta/Elev= 30
  4058.9  509.99  4118.9  509.05  4161.5  507.58  4189.2  507.78  4209.3  506.04
  4239.4  506.85  4266.1  505.45  4339.9  503.56  4520.7  501.25  4541.1  501.65
  4630.8  500.89  4689.4   499.7    4858  498.41  4962.1  496.42  4978.4     495
    4997     495  4999.8   494.5    5003     495  5021.5  496.73  5049.6  498.06
  5100.5  497.57  5148.1  498.47    5192  500.68  5237.9  500.43  5346.3     503
  5472.5  506.33  5499.1  507.75  5531.9  507.76  5571.3  510.46  5619.5   511.4
#Mann= 8 ,-1 , 0
  4058.9     .08       0  4630.8      .1       0  4962.1     .08       0
    4997     .07       0    5003     .08       0  5148.1     .05       0
  5346.3     .08       0  5531.9      .1       0
Bank Sta=4997,5003
XS Rating Curve= 0 ,0
Exp/Cntr=0.3,0.1

Type RM Length L Ch R = 1 ,5501    ,103,103,103
BEGIN DESCRIPTION:
UNT00946 IN CHRS 9.0
END DESCRIPTION:
XS GIS Cut Line= 4
      3491752.13     10592492.21      3491196.57     10592478.33
      3490425.74     10592627.63      3490140.99     10592672.77
#Sta/Elev= 30
  3861.4  514.99  3901.4  514.33  3931.4  512.22  4091.5  507.95  4221.5  506.38
  4251.5  504.78  4281.6  505.33  4321.6     503  4566.9  499.95  4676.3  499.01
  4728.1  499.94  4839.3  499.31    4903  496.23  4961.5  496.27  4981.8  494.54
  4992.1  495.59    4997  494.47  4999.8  493.97    5003  494.47  5012.5   495.9
  5038.6   496.8  5165.3  499.65  5193.9  502.07  5232.3  503.37  5244.1  503.42
  5276.8  502.85  5333.1  504.61  5433.9  507.75  5469.2  508.84  5490.6  510.49
#Mann= 9 ,-1 , 0
  3861.4     .08       0  4566.9      .1       0    4903     .08       0
    4997     .07       0    5003     .08       0  5232.3     .15       0
  5244.1     .08       0  5333.1      .1       0  5433.9     .15       0
Bank Sta=4997,5003
XS Rating Curve= 0 ,0
Exp/Cntr=0.3,0.1

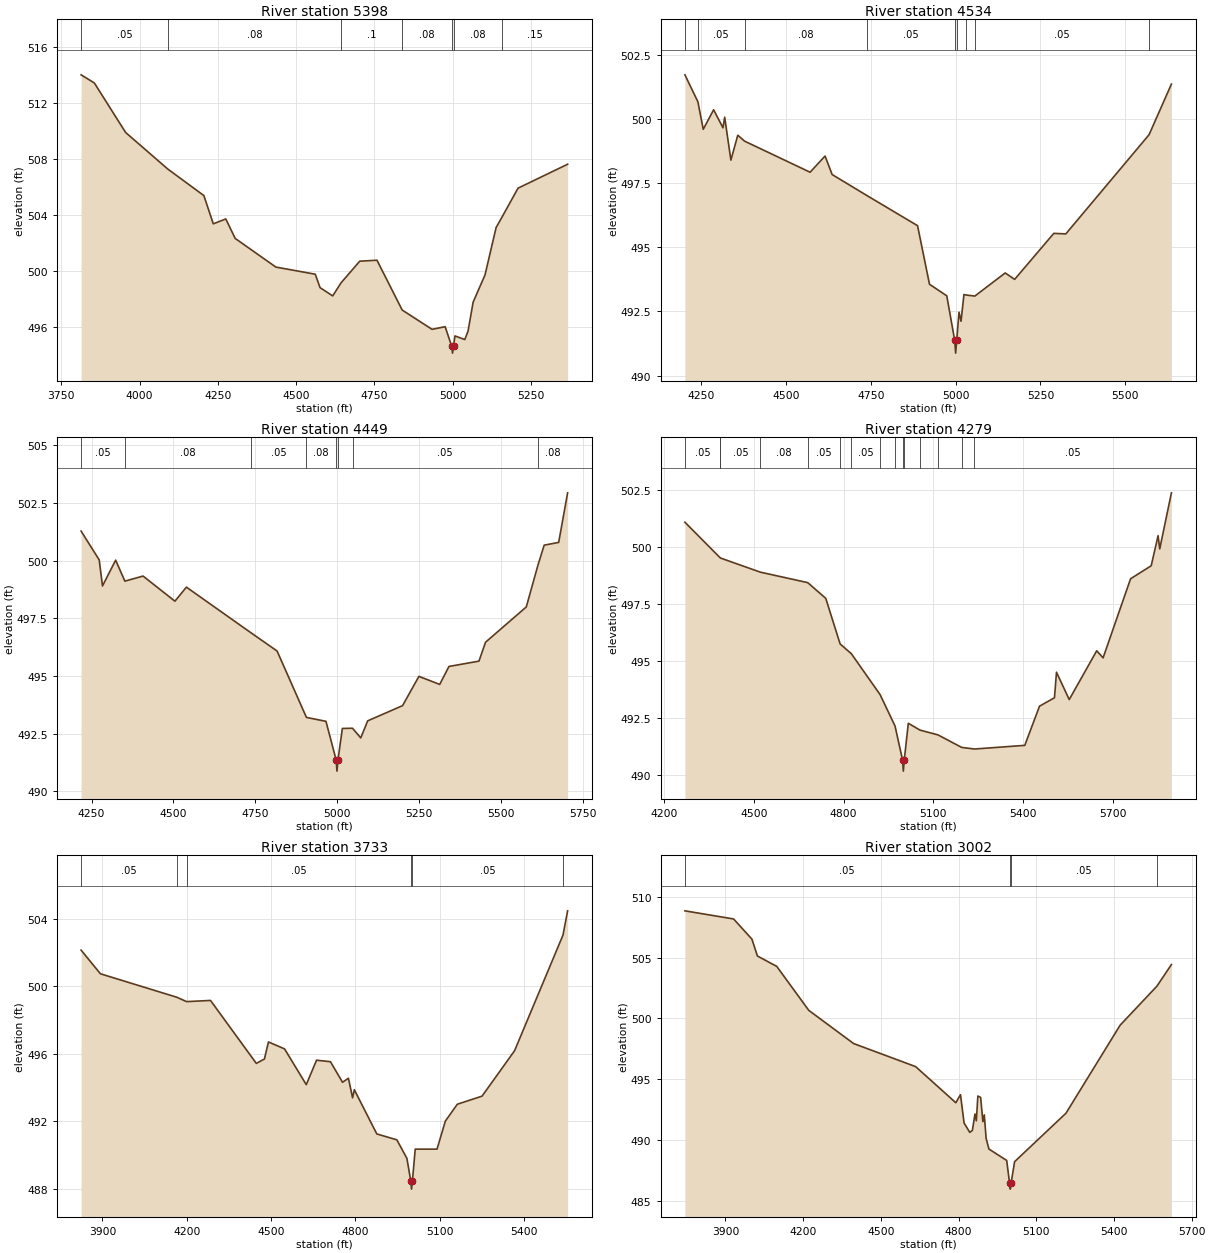
Type RM Length L Ch R = 1 ,5398    ,864,864,864
BEGIN DESCRIPTION:
UNT00946 IN CHRS 9.1
END DESCRIPTION:
XS GIS Cut Line= 5
       3491724.3     10592415.83      3491078.52     10592412.35
      3490734.77     10592460.96      3490415.32     10592558.19
       3490189.6     10592585.97
#Sta/Elev= 30
  3813.2     514  3855.4  513.42  3955.4  509.88  4089.9  507.27  4205.4  505.37
  4235.4  503.35  4275.4   503.7  4305.4  502.31  4435.4  500.26  4561.2  499.75
  4576.6  498.79    4617   498.2  4643.5  499.13  4703.3  500.68  4758.4  500.75
    4839  497.19  4934.4  495.81  4976.2     496    4997  494.61  4999.8  494.11
    5003  494.61  5007.6  495.34  5038.9  495.08  5049.4  495.68  5065.6  497.75
  5103.6   499.7  5139.1  503.09  5156.6  503.78  5209.1   505.9  5367.5  507.61
#Mann= 7 ,-1 , 0
  3813.2     .05       0  4089.9     .08       0  4643.5      .1       0
    4839     .08       0    4997     .07       0    5003     .08       0
  5156.6     .15       0
Bank Sta=4997,5003
XS Rating Curve= 0 ,0
Exp/Cntr=0.3,0.1

Type RM Length L Ch R = 1 ,4534    ,85,85,85
BEGIN DESCRIPTION:
UNT00946 IN CHRS 9.8
END DESCRIPTION:
XS GIS Cut Line= 6
      3491085.46     10592117.21      3490800.74     10592065.13
      3490557.68     10591724.85      3490408.38     10591624.16
      3490238.24     10591502.63      3489906.02     10591440.34
#Sta/Elev= 30
  4201.4  501.71  4239.7  500.66  4255.4  499.59  4286.1  500.35  4313.6  499.65
  4318.7  500.06    4337  498.39  4357.3  499.36  4377.3  499.13  4570.5  497.92
  4614.7  498.55  4635.6  497.83  4739.7     497  4887.5  495.84  4922.7  493.56
  4973.7  493.11    4997  491.38  4999.8  490.88    5003  491.38  5009.7  492.47
  5015.7  492.12  5024.3  493.16  5031.8  493.14  5056.4   493.1    5146     494
  5173.8  493.75  5289.3  495.54  5324.8  495.52  5570.3  499.38  5636.2  501.35
#Mann= 9 ,-1 , 0
  4201.4     .08       0  4239.7     .05       0  4377.3     .08       0
  4739.7     .05       0    4997    .035       0    5003     .05       0
  5031.8     .08       0  5056.4     .05       0  5570.3      .1       0
Bank Sta=4997,5003
XS Rating Curve= 0 ,0
Exp/Cntr=0.3,0.1

Type RM Length L Ch R = 1 ,4449    ,170,170,170
BEGIN DESCRIPTION:
UNT00946 IN CHRS 9.9
END DESCRIPTION:
XS GIS Cut Line= 6
      3491047.27     10592058.19      3490863.24      10592044.3
      3490484.77     10591596.38      3490377.13     10591513.05
      3490203.52     10591353.33      3489865.16     10591294.63
#Sta/Elev= 30
  4218.1  501.28  4273.4  500.03  4283.4   498.9  4323.6  500.02  4351.8  499.11
  4407.4  499.33  4504.7  498.24  4539.8  498.85  4737.1  496.87  4816.8  496.08
  4906.5   493.2  4966.2  493.03    4997  491.37  4999.8  490.87    5003  491.37
  5016.3  492.72  5047.3  492.73  5072.5  492.31  5093.6  493.05  5200.2  493.71
  5250.2  494.98  5313.7  494.63    5342  495.41  5433.6  495.64  5453.7  496.46
  5578.2  497.99  5614.2  499.82  5632.9  500.67  5677.2  500.79  5704.5  502.94
#Mann= 8 ,-1 , 0
  4218.1     .05       0  4351.8     .08       0  4737.1     .05       0
  4906.5     .08       0    4997     .07       0    5003     .08       0
  5047.3     .05       0  5614.2     .08       0
Bank Sta=4997,5003
XS Rating Curve= 0 ,0
Exp/Cntr=0.3,0.1

Type RM Length L Ch R = 1 ,4279    ,546,546,546
BEGIN DESCRIPTION:
UNT00946 IN CHRS 7.0
END DESCRIPTION:
XS GIS Cut Line= 4
      3491005.58       10591954.      3490429.21     10591388.05
      3490040.32     10590960.96      3489821.57     10590860.27
#Sta/Elev= 30
  4269.7  501.09  4388.3  499.52  4388.4  499.52  4521.7   498.9  4680.2  498.44
  4740.5  497.75  4788.5  495.75  4826.1  495.32    4922  493.53    4972  492.15
    4997  490.67  4999.8  490.17    5003  490.67  5016.4  492.27  5055.4  491.97
  5115.6  491.76  5194.9  491.21  5237.1  491.14  5405.7   491.3    5455  493.02
    5505  493.39  5511.7  494.51  5554.3  493.31  5646.2  495.45  5667.5  495.14
  5759.4  498.61  5828.3  499.18  5851.3   500.5  5856.8  499.92  5895.9  502.38
#Mann= 15 ,-1 , 0
  4269.7     .05       0  4388.3     .08       0  4388.4     .05       0
  4521.7     .08       0  4680.2     .05       0  4788.5     .08       0
  4826.1     .05       0    4922     .08       0    4972     .05       0
    4997     .04       0    5003     .05       0  5055.4     .08       0
  5115.6     .05       0  5194.9     .08       0  5237.1     .05       0
Bank Sta=4997,5003
XS Rating Curve= 0 ,0
Exp/Cntr=0.3,0.1

Type RM Length L Ch R = 1 ,3733    ,731,731,731
BEGIN DESCRIPTION:
UNT00946 IN CHRS 7.1
END DESCRIPTION:
XS GIS Cut Line= 4
      3491047.29     10591863.77      3490481.29     10591165.83
       3490068.1     10590874.16      3489762.54     10590759.57
#Sta/Elev= 30
  3824.4  502.14  3893.1  500.74  4164.8  499.35  4199.8  499.09  4284.7  499.16
  4447.7  495.43  4476.5  495.69  4490.8   496.7  4548.1  496.29  4625.4  494.17
  4661.9  495.62  4711.4  495.53  4754.4  494.31  4775.3  494.55  4790.1  493.39
  4796.3  493.87  4876.3  491.25  4947.7   490.9  4983.4   489.8    4997  488.48
  4999.8  487.98    5003  488.48    5013  490.35  5090.5  490.35  5120.1  492.01
  5162.7  493.01  5250.7  493.49  5366.4  496.18  5538.6  503.03  5555.1  504.47
#Mann= 6 ,-1 , 0
  3824.4     .05       0  4164.8     .08       0  4199.8     .05       0
    4997     .03       0    5003     .05       0  5538.6     .08       0
Bank Sta=4997,5003
XS Rating Curve= 0 ,0
Exp/Cntr=0.3,0.1

Type RM Length L Ch R = 1 ,3002    ,1074,1074,1074
BEGIN DESCRIPTION:
UNT00946 IN CHRS 5.0
END DESCRIPTION:
XS GIS Cut Line= 2
      3491405.32      10590820.2      3489639.65     10590179.56
#Sta/Elev= 30
  3743.6  508.85  3931.6  508.18  4002.3  506.52  4023.6  505.13  4098.1  504.28
  4221.8  500.66  4394.8  497.93  4634.4  496.03  4789.5  493.06  4807.5  493.72
  4821.4  491.39  4843.4  490.62  4853.4  490.78  4863.4  492.13  4868.7  491.57
  4874.6  493.61  4885.3   493.5    4894   491.5  4899.4  492.06  4906.5  490.13
  4917.2  489.25  4985.9  488.31    4997  486.45  4999.8  485.95    5003  486.45
  5016.5  488.21  5214.9   492.2  5423.9  499.44  5565.9  502.65  5621.9  504.43
#Mann= 4 ,-1 , 0
  3743.6     .05       0    4997     .03       0    5003     .05       0
  5565.9     .08       0
Bank Sta=4997,5003
XS Rating Curve= 0 ,0
Exp/Cntr=0.3,0.1

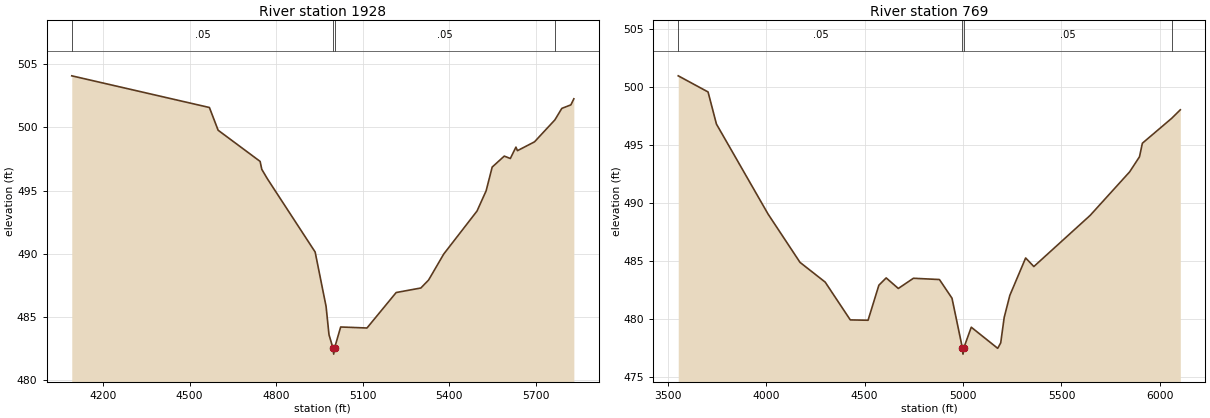
Type RM Length L Ch R = 1 ,1928    ,1159,1159,1159
BEGIN DESCRIPTION:
UNT00946 IN CHRS 2.0
END DESCRIPTION:
XS GIS Cut Line= 4
       3491285.5     10589679.57      3490670.92     10589601.44
      3490087.59     10589695.19       3489582.4     10589856.65
#Sta/Elev= 30
  4091.7  504.09  4568.9  501.58  4599.1  499.78  4744.7  497.31  4750.5  496.68
  4770.8   495.9  4935.5  490.13  4973.4  485.82  4983.5  483.58    4997  482.54
  4999.8  482.04    5003  482.54    5024  484.19  5115.2  484.11  5216.4  486.92
    5302  487.28  5328.8  487.91  5381.3  489.97  5496.8  493.38  5528.3  494.98
  5549.3  496.86  5591.2  497.73  5612.2  497.54  5631.6  498.44  5636.9  498.16
    5696  498.86  5766.7   500.6  5790.7  501.51  5822.2  501.79  5832.4  502.27
#Mann= 4 ,-1 , 0
  4091.7     .05       0    4997    .035       0    5003     .05       0
  5766.7     .08       0
Bank Sta=4997,5003
XS Rating Curve= 0 ,0
Exp/Cntr=0.3,0.1

Type RM Length L Ch R = 1 ,769     ,0,0,0
BEGIN DESCRIPTION:
UNT00946 IN CHRS 1.0
END DESCRIPTION:
XS GIS Cut Line= 4
      3491327.14     10589210.78      3490707.38     10588523.32
      3489993.84     10588846.24      3489493.83     10589523.33
#Sta/Elev= 30
  3553.1  500.95  3704.6  499.56  3747.2  496.79  4009.6  489.03  4171.7  484.87
  4299.5  483.17  4427.1  479.91  4517.4  479.88  4572.3   482.9  4609.4  483.53
  4671.1  482.62  4747.9   483.5    4880  483.39  4943.8  481.78    4997  477.46
  4999.8  476.96    5003  477.46  5041.7  479.28    5176  477.46  5191.3  477.93
  5208.9  480.12  5237.5  482.02  5317.9  485.25  5359.6  484.51  5645.7  488.92
  5846.1  492.67  5896.2  493.97  5910.9  495.14    6060  497.29  6103.6  498.02
#Mann= 4 ,-1 , 0
  3553.1     .05       0    4997     .03       0    5003     .05       0
    6060     .08       0
Bank Sta=4997,5003
XS Rating Curve= 0 ,0
Exp/Cntr=0.3,0.1

Chan Stop Cuts=-1
Use User Specified Reach Order=0
Composite Channel Slope=5