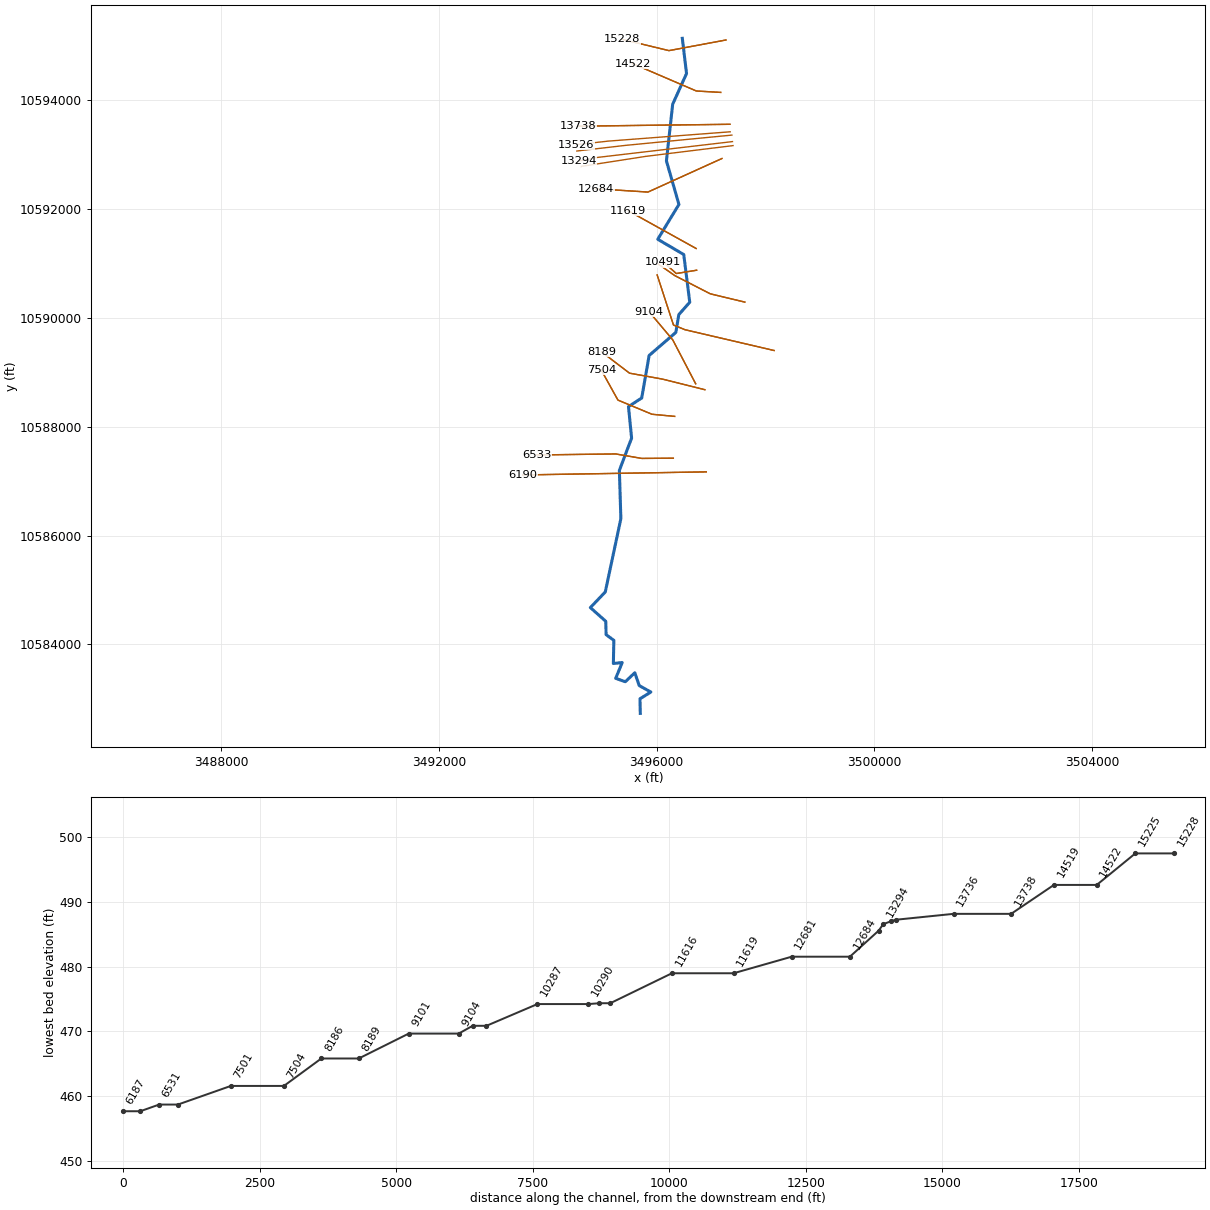
--- UNT00953 IN CHRS.prj (project) ---

Proj Title=UNT00953 IN CHRS Base Level Engineering
Current Plan=p01
Default Exp/Contr=0.3,0.1
English Units
Geom File=g01
Flow File=f01
Plan File=p01
Y Axis Title=Elevation
X Axis Title(PF)=Main Channel Distance
X Axis Title(XS)=Station
BEGIN DESCRIPTION:
UNT00953 IN CHRS
END DESCRIPTION:
DSS Export Rating Curves= 0
DSS Export Rating Curve Sorted= 0
DSS Export Volume Flow Curves= 0
DXF OffsetX= 0
DXF OffsetY= 0
DXF ScaleX= 1
DXF ScaleY= 10

--- UNT00953 IN CHRS.p01 (plan) ---

Plan Title=Multiple Run
Short Identifier=Multiple
Geom File=g01
Flow File=f01
Subcritical Flow
K Sum by GR= 0
Std Step Tol= 0.01
Critical Tol= 0.01
Num of Std Step Trials= 20
Max Error Tol= 0.3
Flow Tol Ratio= 0.001
Split Flow NTrial= 30
Split Flow Tol= 0.02
Split Flow Ratio= 0.02
Log Output Level= 0
Friction Slope Method= 1
Unsteady Friction Slope Method= 2
Unsteady Bridges Friction Slope Method= 1
Parabolic Critical Depth
Global Vel Dist=  1 , 1 , 1
Global Log Level= 0
CheckData=True
Encroach Param= -1, 0, 0, 0
BEGIN DESCRIPTION:
Multiple Run
END DESCRIPTION:

--- UNT00953 IN CHRS.f01 (steady flow) ---

Flow Title=Multiple
Program Version=4.10
Number of Profiles= 7
Profile Names=10-year,25-year,50-year,1pct_min,100-year,1pct_plu,500-year
River Rch & RM=UNT00953 IN CHRS,Reach-1         ,15228
     304     373     422     348     470     636     583
River Rch & RM=UNT00953 IN CHRS,Reach-1         ,10287
     451     565     649     542     732     990     932
River Rch & RM=UNT00953 IN CHRS,Reach-1         ,6531
     619     788     914     770    1041    1408    1348
Boundary for River Rch & Prof#=UNT00953 IN CHRS,Reach-1         , 1
Up Type= 0
Dn Type= 3
Dn Slope=0.005
Boundary for River Rch & Prof#=UNT00953 IN CHRS,Reach-1         , 2
Up Type= 0
Dn Type= 3
Dn Slope=0.005
Boundary for River Rch & Prof#=UNT00953 IN CHRS,Reach-1         , 3
Up Type= 0
Dn Type= 3
Dn Slope=0.005
Boundary for River Rch & Prof#=UNT00953 IN CHRS,Reach-1         , 4
Up Type= 0
Dn Type= 3
Dn Slope=0.005
Boundary for River Rch & Prof#=UNT00953 IN CHRS,Reach-1         , 5
Up Type= 0
Dn Type= 3
Dn Slope=0.005
Boundary for River Rch & Prof#=UNT00953 IN CHRS,Reach-1         , 6
Up Type= 0
Dn Type= 3
Dn Slope=0.005
Boundary for River Rch & Prof#=UNT00953 IN CHRS,Reach-1         , 7
Up Type= 0
Dn Type= 3
Dn Slope=0.005
DSS Import GetInterval= 0
DSS Import GetPeak= 0
DSS Import FillOption= 0

--- UNT00953 IN CHRS.g01 (geometry) ---

Geom Title=Existing Conditions
Program Version=4.10

River Reach=UNT00953 IN CHRS,Reach-1
Reach XY= 30
      3496473.84     10595139.55      3496551.23     10594492.17
       3496296.8     10593928.65      3496181.91     10592886.68
      3496411.63     10592086.23      3496022.82     10591446.25
      3496500.06     10591165.79      3496610.34     10590288.83
      3496409.82     10590061.74      3496354.96     10589734.07
      3495864.59     10589310.61      3495727.88     10588528.48
      3495484.87     10588370.58      3495542.33     10587791.24
      3495317.59     10587197.85      3495345.04     10586310.81
      3495058.51     10584963.11      3494784.45     10584675.87
      3495067.34     10584424.49      3495074.11     10584178.03
      3495216.05     10584074.52       3495207.3     10583648.68
      3495370.22     10583666.06      3495249.75     10583375.63
      3495426.99      10583313.4      3495600.98     10583478.02
      3495682.91     10583241.58      3495896.01     10583123.96
      3495695.69     10582999.33      3495702.11     10582731.64

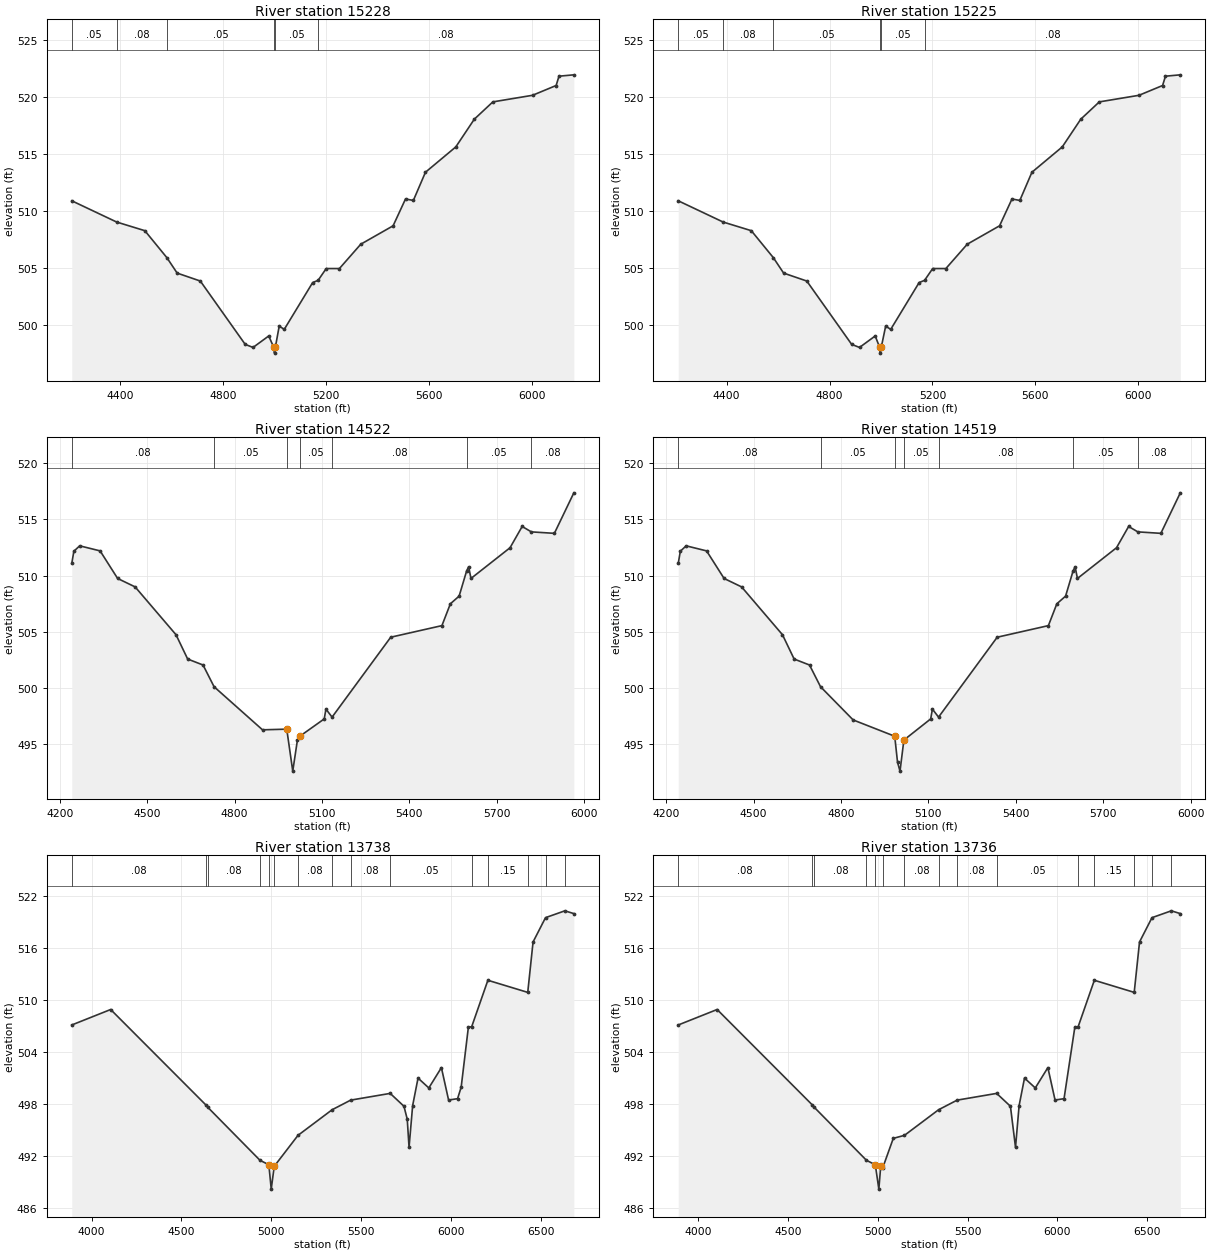
Type RM Length L Ch R = 1 ,15228   ,706,706,706
BEGIN DESCRIPTION:
UNT00953 IN CHRS 27.0
END DESCRIPTION:
XS GIS Cut Line= 3
      3497274.74     10595109.04      3496228.72     10594913.73
      3495366.06     10595121.81
#Sta/Elev= 30
  4211.8   510.9  4386.4  509.03  4495.8  508.27  4581.7  505.89  4621.4  504.54
  4711.5  503.84  4885.9  498.27  4916.4     498  4977.4  499.01    4997     498
  4999.8   497.5    5003     498  5018.1  499.88  5037.7  499.59  5148.2  503.71
  5169.2   503.9  5200.8  504.94  5252.1  504.94  5335.1  507.08  5460.8   508.7
    5509  511.06  5539.5  510.93  5586.5  513.41  5704.5  515.64  5776.5  518.08
  5848.5   519.6  6002.8  520.18  6094.4  521.04  6105.6  521.86  6163.3  521.98
#Mann= 6 ,-1 , 0
  4211.8     .05       0  4386.4     .08       0  4581.7     .05       0
    4997     .04       0    5003     .05       0  5169.2     .08       0
Bank Sta=4997,5003
XS Rating Curve= 0 ,0
Exp/Cntr=0.3,0.1

Type RM Length L Ch R = 1 ,15225   ,706,706,706
BEGIN DESCRIPTION:
UNT00953 IN CHRS 27.0
END DESCRIPTION:
XS GIS Cut Line= 3
      3497274.74     10595109.04      3496228.72     10594913.73
      3495366.06     10595121.81
#Sta/Elev= 30
  4211.8   510.9  4386.4  509.03  4495.8  508.27  4581.7  505.89  4621.4  504.54
  4711.5  503.84  4885.9  498.27  4916.4     498  4977.4  499.01  4994.8     498
  4997.5   497.5  5000.8     498  5018.1  499.88  5037.7  499.59  5148.2  503.71
  5169.2   503.9  5200.8  504.94  5252.1  504.94  5335.1  507.08  5460.8   508.7
    5509  511.06  5539.5  510.93  5586.5  513.41  5704.5  515.64  5776.5  518.08
  5848.5   519.6  6002.8  520.18  6094.4  521.04  6105.6  521.86  6163.3  521.98
#Mann= 6 ,-1 , 0
  4211.8     .05       0  4386.4     .08       0  4581.7     .05       0
  4994.8     .04       0  5000.8     .05       0  5169.2     .08       0
Bank Sta=4994.8,5000.8
XS Rating Curve= 0 ,0
Exp/Cntr=0.3,0.1

Type RM Length L Ch R = 1 ,14522   ,784,784,784
BEGIN DESCRIPTION:
UNT00953 IN CHRS 25.0
END DESCRIPTION:
XS GIS Cut Line= 3
      3497179.28      10594145.5      3496732.19     10594171.54
      3495560.31     10594675.02
#Sta/Elev= 30
  4241.3  511.08  4248.5  512.17  4268.5  512.65  4338.6   512.2  4398.7  509.75
  4458.8     509  4599.1  504.75  4639.1  502.59  4691.9  502.06  4729.7  500.13
    4896   496.3  4979.2  496.36  4999.8  492.63  5015.8  495.39  5026.3  495.77
  5107.8  497.27  5113.7  498.14  5134.8  497.43  5336.1  504.53  5511.8  505.56
  5540.8   507.5  5570.8  508.18  5596.7  510.43  5603.5  510.79  5611.5  509.75
  5745.6  512.48  5787.2  514.37  5818.8  513.89  5897.8  513.76  5964.6  517.36
#Mann= 7 ,-1 , 0
  4241.3     .08       0  4729.7     .05       0  4979.2     .04       0
  5026.3     .05       0  5134.8     .08       0  5596.7     .05       0
  5818.8     .08       0
Bank Sta=4979.2,5026.3
XS Rating Curve= 0 ,0
Exp/Cntr=0.3,0.1

Type RM Length L Ch R = 1 ,14519   ,783,783,783
BEGIN DESCRIPTION:
UNT00953 IN CHRS 25.0
END DESCRIPTION:
XS GIS Cut Line= 3
      3497179.28      10594145.5      3496732.19     10594171.54
      3495560.31     10594675.02
#Sta/Elev= 30
  4241.3  511.08  4248.5  512.17  4268.5  512.65  4338.6   512.2  4398.7  509.75
  4458.8     509  4599.1  504.75  4639.1  502.59  4691.9  502.06  4729.7  500.13
  4841.6  497.18 4984.35  495.73    4994  493.42  5002.5  492.63  5015.8  495.39
  5107.8  497.27  5113.7  498.14  5134.8  497.43  5336.1  504.53  5511.8  505.56
  5540.8   507.5  5570.8  508.18  5596.7  510.43  5603.5  510.79  5611.5  509.75
  5745.6  512.48  5787.2  514.37  5818.8  513.89  5897.8  513.76  5964.6  517.36
#Mann= 7 ,-1 , 0
  4241.3     .08       0  4729.7     .05       0 4984.35     .04       0
  5015.8     .05       0  5134.8     .08       0  5596.7     .05       0
  5818.8     .08       0
Bank Sta=4984.35,5015.8
XS Rating Curve= 0 ,0
Exp/Cntr=0.3,0.1

Type RM Length L Ch R = 1 ,13738   ,1054,1054,1054
BEGIN DESCRIPTION:
UNT00953 IN CHRS 23.0
END DESCRIPTION:
XS GIS Cut Line= 2
      3497348.51     10593559.56      3494555.23     10593524.86
#Sta/Elev= 30
    3890  507.14  4106.4  508.93  4634.4  497.93  4646.4  497.63  4937.4  491.49
  4986.5  490.98  4999.8  488.16  5016.5   490.8  5148.8  494.38  5338.6  497.34
  5441.7  498.45  5661.7  499.23  5738.3  497.74  5756.6  496.24  5766.6  492.99
  5786.6  497.82  5816.6     501  5876.6  499.86  5946.6  502.21  5986.6  498.46
  6036.6  498.62  6056.6  499.95  6096.6  506.88  6115.1  506.94  6205.2  512.31
    6427  510.91  6456.6  516.74  6525.9  519.55  6633.4  520.34  6683.5  520.02
#Mann= 15 ,-1 , 0
    3890     .08       0  4634.4     .05       0  4646.4     .08       0
  4937.4     .05       0  4986.5     .04       0  5016.5     .05       0
  5148.8     .08       0  5338.6     .05       0  5441.7     .08       0
  5661.7     .05       0  6115.1      .1       0  6205.2     .15       0
    6427      .1       0  6525.9     .08       0  6633.4      .1       0
Bank Sta=4986.5,5016.5
XS Rating Curve= 0 ,0
Exp/Cntr=0.3,0.1

Type RM Length L Ch R = 1 ,13736   ,1055,1055,1055
BEGIN DESCRIPTION:
UNT00953 IN CHRS 23.0
END DESCRIPTION:
XS GIS Cut Line= 2
      3497348.51     10593559.56      3494555.23     10593524.86
#Sta/Elev= 30
    3890  507.14  4106.4  508.93  4634.4  497.93  4646.4  497.63  4937.4  491.49
  4986.5  490.98  5006.2  488.16  5016.5   490.8  5026.5  490.55  5086.5  494.03
  5148.8  494.38  5338.6  497.34  5441.7  498.45  5661.7  499.23  5738.3  497.74
  5766.6  492.99  5786.6  497.82  5816.6     501  5876.6  499.86  5946.6  502.21
  5986.6  498.46  6036.6  498.62  6096.6  506.88  6115.1  506.94  6205.2  512.31
    6427  510.91  6456.6  516.74  6525.9  519.55  6633.4  520.34  6683.5  520.02
#Mann= 15 ,-1 , 0
    3890     .08       0  4634.4     .05       0  4646.4     .08       0
  4937.4     .05       0  4986.5     .04       0  5026.5     .05       0
  5148.8     .08       0  5338.6     .05       0  5441.7     .08       0
  5661.7     .05       0  6115.1      .1       0  6205.2     .15       0
    6427      .1       0  6525.9     .08       0  6633.4      .1       0
Bank Sta=4986.5,5016.5
XS Rating Curve= 0 ,0
Exp/Cntr=0.3,0.1

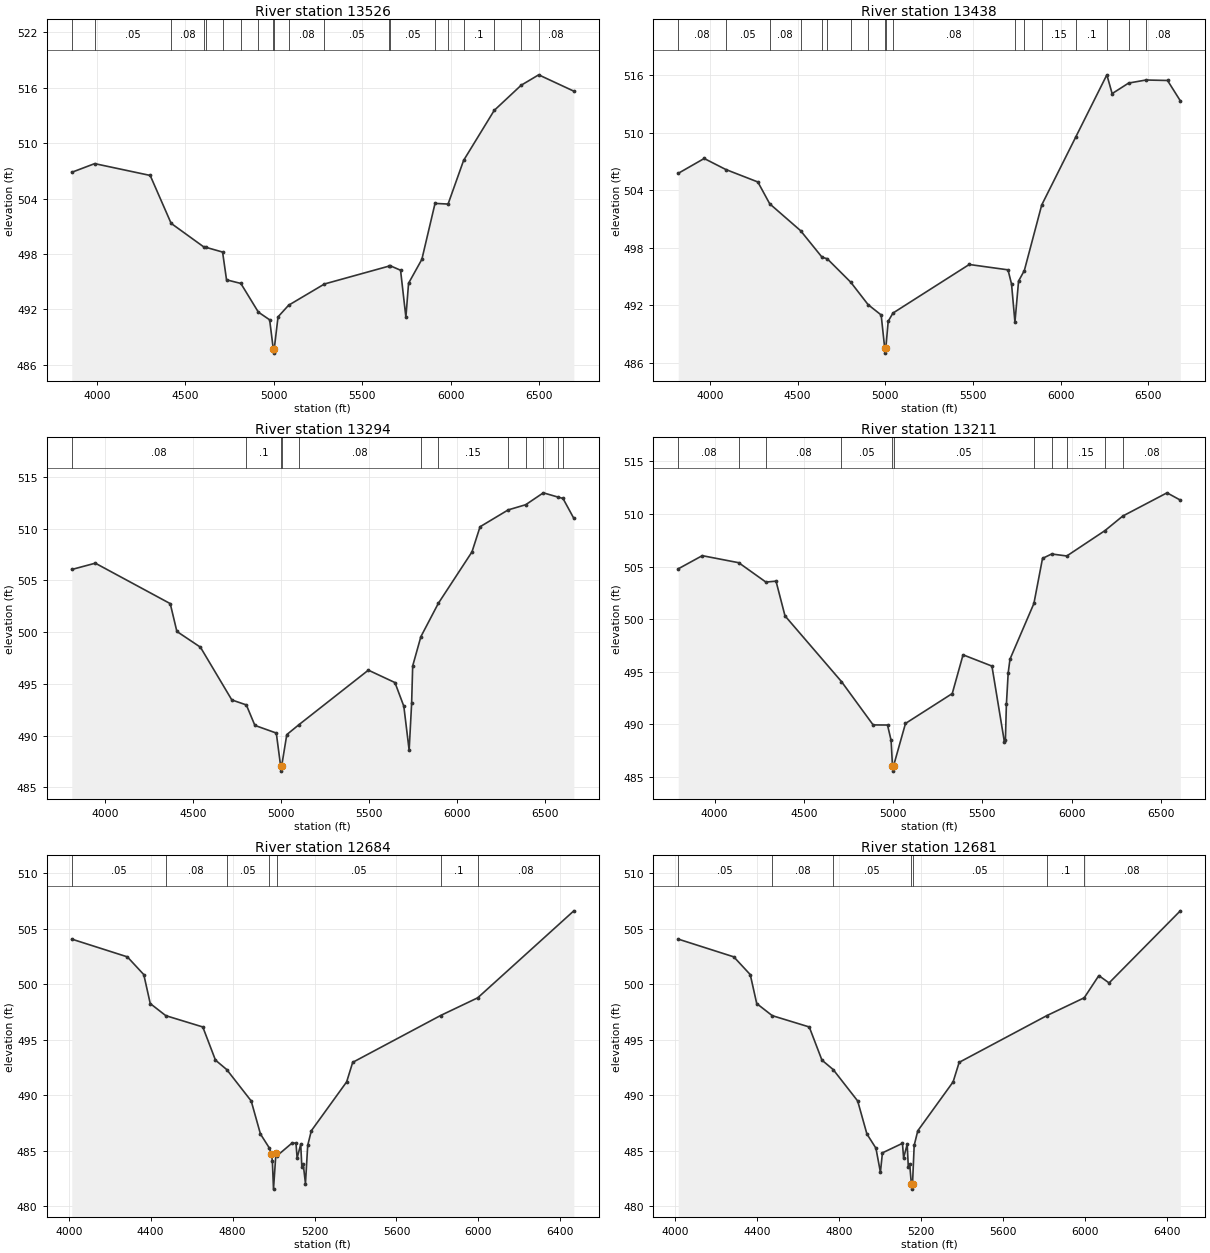
Type RM Length L Ch R = 1 ,13526   ,88,88,88
BEGIN DESCRIPTION:
UNT00953 IN CHRS 23.7
END DESCRIPTION:
XS GIS Cut Line= 3
      3497353.68     10593421.69      3495111.94     10593250.25
      3494528.15     10593185.14
#Sta/Elev= 30
  3859.2  506.84  3988.6  507.78  4302.1   506.5  4420.4  501.31  4608.8   498.7
  4619.2   498.7    4711   498.2  4733.3  495.19  4814.1   494.8  4913.1  491.69
  4976.8  490.86    4997  487.75  4999.8  487.25    5003  487.75  5024.2  491.18
    5084  492.44  5286.3  494.74  5653.2  496.69  5658.5  496.71  5716.2  496.23
  5746.3  491.14  5761.4  494.82  5836.5  497.41  5910.9  503.47  5984.6   503.4
  6072.3  508.13  6244.9  513.54  6397.2  516.27  6496.3   517.4  6694.9  515.63
#Mann= 20 ,-1 , 0
  3859.2     .08       0  3988.6     .05       0  4420.4     .08       0
  4608.8      .1       0  4619.2     .08       0    4711      .1       0
  4814.1     .08       0  4913.1     .05       0    4997     .04       0
    5003     .05       0    5084     .08       0  5286.3     .05       0
  5653.2     .08       0  5658.5     .05       0  5910.9      .1       0
  5984.6     .15       0  6072.3      .1       0  6244.9     .15       0
  6397.2      .1       0  6496.3     .08       0
Bank Sta=4997,5003
XS Rating Curve= 0 ,0
Exp/Cntr=0.3,0.1

Type RM Length L Ch R = 1 ,13438   ,144,144,144
BEGIN DESCRIPTION:
UNT00953 IN CHRS 23.6
END DESCRIPTION:
XS GIS Cut Line= 3
      3497384.04     10593360.93      3495430.95     10593172.13
      3494535.87      10593068.1
#Sta/Elev= 30
  3819.4  505.78  3967.4  507.33  4090.8  506.18  4273.4  504.88  4341.2   502.6
    4517   499.8  4639.9  497.02  4668.9  496.87  4803.2  494.42  4902.2  492.08
  4976.7     491    4997  487.52  4999.8  487.02    5003  487.52  5016.9  490.35
    5044   491.2    5479  496.27  5700.1  495.71  5720.2  494.23  5739.6  490.25
  5760.3  494.54  5793.2  495.64  5892.3  502.48  6086.4  509.57  6263.8  516.06
  6293.9   514.1  6387.9   515.2  6487.1  515.52  6609.8  515.47  6682.7  513.35
#Mann= 18 ,-1 , 0
  3819.4     .08       0  4090.8     .05       0  4341.2     .08       0
    4517      .1       0  4639.9     .08       0  4668.9      .1       0
  4803.2     .08       0  4902.2     .05       0    4997     .04       0
    5003     .05       0    5044     .08       0  5739.6     .05       0
  5793.2      .1       0  5892.3     .15       0  6086.4      .1       0
  6263.8     .15       0  6387.9      .1       0  6487.1     .08       0
Bank Sta=4997,5003
XS Rating Curve= 0 ,0
Exp/Cntr=0.3,0.1

Type RM Length L Ch R = 1 ,13294   ,83,83,83
BEGIN DESCRIPTION:
UNT00953 IN CHRS 23.8
END DESCRIPTION:
XS GIS Cut Line= 3
       3497394.9     10593241.57      3494862.37     10592944.26
      3494567.28     10592883.51
#Sta/Elev= 30
    3811  506.06  3944.7  506.67  4370.2  502.76  4407.9  500.07  4541.6  498.55
    4720  493.45  4802.3  492.97  4850.9  490.99  4972.5  490.25    4997  487.07
  4999.8  486.57    5003  487.07  5032.1   490.1  5099.7  491.04  5495.3  496.33
  5646.3  495.13  5696.7  492.84  5726.9  488.59    5741  493.12    5747  496.74
  5793.6  499.57  5892.7  502.79  6083.7  507.76  6129.6  510.19  6289.3  511.82
  6388.7  512.32  6488.9  513.47  6571.8  513.06  6600.4  512.93  6662.2     511
#Mann= 12 ,-1 , 0
    3811     .08       0  4802.3      .1       0    4997     .07       0
    5003      .1       0  5099.7     .08       0  5793.6      .1       0
  5892.7     .15       0  6289.3      .1       0  6388.7     .15       0
  6488.9      .1       0  6571.8     .08       0  6600.4     .15       0
Bank Sta=4997,5003
XS Rating Curve= 0 ,0
Exp/Cntr=0.3,0.1

Type RM Length L Ch R = 1 ,13211   ,527,527,527
BEGIN DESCRIPTION:
UNT00953 IN CHRS 23.9
END DESCRIPTION:
XS GIS Cut Line= 3
      3497405.77     10593167.79      3495804.21      10592970.3
      3494619.27     10592785.84
#Sta/Elev= 30
  3796.7  504.79  3931.4  506.04  4135.7  505.37  4287.9  503.53  4344.5  503.62
  4394.9  500.32  4711.1  494.08  4888.6  489.96  4969.2  489.95  4989.3  488.49
    4997  486.07  4999.8  485.57    5003  486.07  5069.9   490.1  5331.9  492.94
  5392.4  496.62  5554.2  495.55  5624.6  488.29  5629.7  488.52  5635.2   491.9
  5645.3  494.91  5655.4  496.21  5789.4   501.5  5837.6  505.78  5888.9   506.2
  5973.7  506.01  6187.4  508.42  6286.9   509.8  6535.1  512.01  6609.6  511.32
#Mann= 11 ,-1 , 0
  3796.7     .08       0  4135.7     .05       0  4287.9     .08       0
  4711.1     .05       0    4997     .04       0    5003     .05       0
  5789.4     .08       0  5888.9      .1       0  5973.7     .15       0
  6187.4      .1       0  6286.9     .08       0
Bank Sta=4997,5003
XS Rating Curve= 0 ,0
Exp/Cntr=0.3,0.1

Type RM Length L Ch R = 1 ,12684   ,1065,1065,1065
BEGIN DESCRIPTION:
UNT00953 IN CHRS 21.0
END DESCRIPTION:
XS GIS Cut Line= 3
      3497200.96     10592930.23      3495842.44      10592313.9
      3494885.15     10592374.54
#Sta/Elev= 30
    4015  504.08  4286.3  502.48  4366.6  500.88  4398.1  498.27  4473.9  497.18
  4654.6  496.16  4716.5  493.17  4771.4  492.32  4890.9  489.49  4936.1  486.51
  4980.1  485.23  4988.7  484.72  4994.2  484.11  4999.8  481.54  5011.8  484.81
  5017.3  484.55    5092  485.72  5109.6  485.67  5115.1  484.35  5132.7  485.58
  5138.2  483.51  5144.8  483.82  5155.8  482.04  5166.8  485.48  5184.4   486.8
  5356.9  491.21  5386.4  492.97  5815.2  497.19  5996.9  498.79    6466  506.63
#Mann= 7 ,-1 , 0
    4015     .05       0  4473.9     .08       0  4771.4     .05       0
  4980.1     .03       0  5017.3     .05       0  5815.2      .1       0
  5996.9     .08       0
Bank Sta=4988.7,5011.8
XS Rating Curve= 0 ,0
Exp/Cntr=0.3,0.1

Type RM Length L Ch R = 1 ,12681   ,1065,1065,1065
BEGIN DESCRIPTION:
UNT00953 IN CHRS 21.0
END DESCRIPTION:
XS GIS Cut Line= 3
      3497200.96     10592930.23      3495842.44      10592313.9
      3494885.15     10592374.54
#Sta/Elev= 30
    4015  504.08  4286.3  502.48  4366.6  500.88  4398.1  498.27  4473.9  497.18
  4654.6  496.16  4716.5  493.17  4771.4  492.32  4890.9  489.49  4936.1  486.51
  4980.1  485.23    5002  483.06  5011.8  484.81  5109.6  485.67  5115.1  484.35
  5132.7  485.58  5138.2  483.51  5144.8  483.82  5152.8  482.04  5155.5  481.54
  5158.8  482.04  5166.8  485.48  5184.4   486.8  5356.9  491.21  5386.4  492.97
  5815.2  497.19  5996.9  498.79  6068.2  500.79  6118.3  500.13    6466  506.63
#Mann= 7 ,-1 , 0
    4015     .05       0  4473.9     .08       0  4771.4     .05       0
  5152.8     .03       0  5158.8     .05       0  5815.2      .1       0
  5996.9     .08       0
Bank Sta=5152.8,5158.8
XS Rating Curve= 0 ,0
Exp/Cntr=0.3,0.1

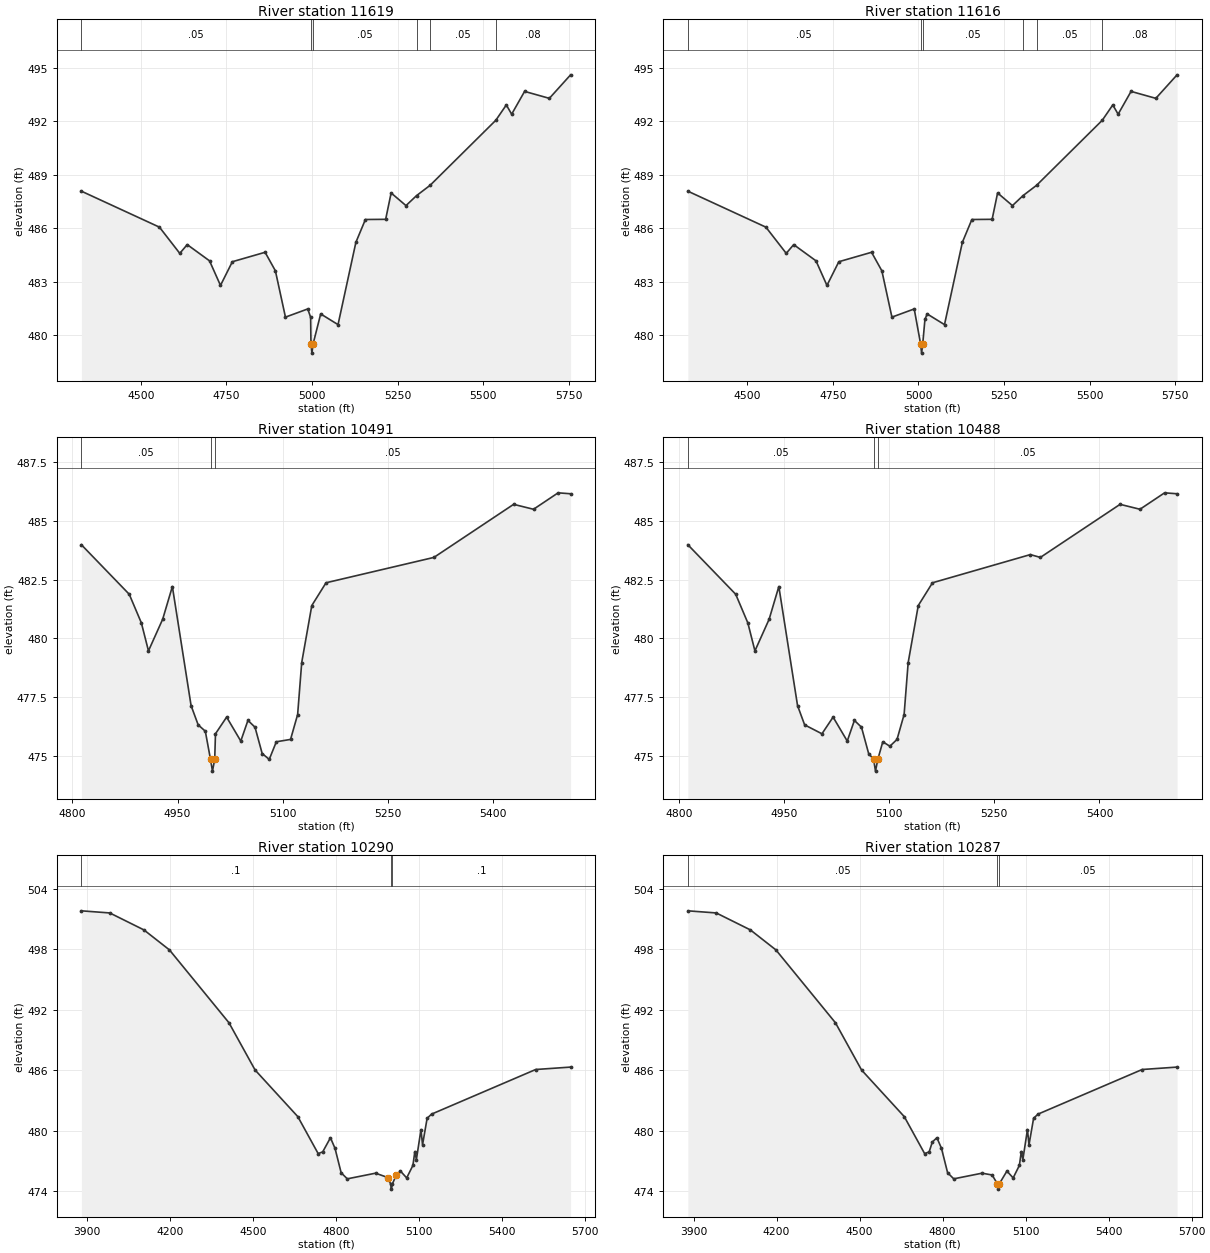
Type RM Length L Ch R = 1 ,11619   ,1128,1128,1128
BEGIN DESCRIPTION:
UNT00953 IN CHRS 18.0
END DESCRIPTION:
XS GIS Cut Line= 2
      3496727.86     10591276.57      3495477.82     10591971.04
#Sta/Elev= 30
  4325.9  488.07  4554.1  486.05  4613.5  484.58  4635.3  485.07  4700.5  484.16
  4732.5  482.78  4767.2  484.11  4862.9  484.64    4893   483.6  4922.4     481
  4987.6  481.46    4996  480.99    4997  479.48  4999.8  478.98    5003  479.48
  5025.4  481.18  5076.1  480.58  5128.3   485.2  5156.1  486.48  5215.3  486.49
  5231.3  487.97  5274.7  487.26  5305.6  487.82  5345.3   488.4  5537.3  492.05
    5568  492.91  5583.6  492.39  5621.4  493.67  5693.8  493.28  5755.9   494.6
#Mann= 6 ,-1 , 0
  4325.9     .05       0    4997     .03       0    5003     .05       0
  5305.6      .1       0  5345.3     .05       0  5537.3     .08       0
Bank Sta=4997,5003
XS Rating Curve= 0 ,0
Exp/Cntr=0.3,0.1

Type RM Length L Ch R = 1 ,11616   ,1128,1128,1128
BEGIN DESCRIPTION:
UNT00953 IN CHRS 18.0
END DESCRIPTION:
XS GIS Cut Line= 2
      3496727.86     10591276.57      3495477.82     10591971.04
#Sta/Elev= 30
  4325.9  488.07  4554.1  486.05  4613.5  484.58  4635.3  485.07  4700.5  484.16
  4732.5  482.78  4767.2  484.11  4862.9  484.64    4893   483.6  4922.4     481
  4987.6  481.46  5006.4  479.48  5009.1  478.98  5012.4  479.48  5018.9  480.87
  5025.4  481.18  5076.1  480.58  5128.3   485.2  5156.1  486.48  5215.3  486.49
  5231.3  487.97  5274.7  487.26  5305.6  487.82  5345.3   488.4  5537.3  492.05
    5568  492.91  5583.6  492.39  5621.4  493.67  5693.8  493.28  5755.9   494.6
#Mann= 6 ,-1 , 0
  4325.9     .05       0  5006.4     .03       0  5012.4     .05       0
  5305.6      .1       0  5345.3     .05       0  5537.3     .08       0
Bank Sta=5006.4,5012.4
XS Rating Curve= 0 ,0
Exp/Cntr=0.3,0.1

Type RM Length L Ch R = 1 ,10491   ,201,201,201
BEGIN DESCRIPTION:
UNT00953 IN CHRS 17.0
END DESCRIPTION:
XS GIS Cut Line= 3
      3496736.58     10590877.28      3496363.27     10590816.51
      3496124.58     10591029.15
#Sta/Elev= 30
  4812.8  483.99  4881.1  481.88  4898.4  480.66  4908.5  479.47  4928.8  480.82
  4942.6  482.21  4969.3  477.14  4979.4  476.32  4989.6  476.05    4997  474.85
  4999.8  474.35    5003  474.85  5004.1  475.94    5020  476.65  5040.2  475.63
  5050.4  476.51  5060.5  476.22  5070.7   475.1  5080.8  474.85  5090.9   475.6
  5111.2   475.7  5121.3  476.76  5127.1  478.97  5141.5   481.4  5161.8  482.37
  5315.7  483.45  5429.4  485.71  5457.8   485.5  5492.9   486.2  5510.7  486.16
#Mann= 3 ,-1 , 0
  4812.8     .05       0    4997    .035       0    5003     .05       0
Bank Sta=4997,5003
XS Rating Curve= 0 ,0
Exp/Cntr=0.3,0.1

Type RM Length L Ch R = 1 ,10488   ,201,201,201
BEGIN DESCRIPTION:
UNT00953 IN CHRS 17.0
END DESCRIPTION:
XS GIS Cut Line= 3
      3496736.58     10590877.28      3496363.27     10590816.51
      3496124.58     10591029.15
#Sta/Elev= 30
  4812.8  483.99  4881.1  481.88  4898.4  480.66  4908.5  479.47  4928.8  480.82
  4942.6  482.21  4969.3  477.14  4979.4  476.32  5004.1  475.94    5020  476.65
  5040.2  475.63  5050.4  476.51  5060.5  476.22  5070.7   475.1  5077.8  474.85
  5080.5  474.35  5083.8  474.85  5090.9   475.6    5101  475.41  5111.2   475.7
  5121.3  476.76  5127.1  478.97  5141.5   481.4  5161.8  482.37  5301.4  483.57
  5315.7  483.45  5429.4  485.71  5457.8   485.5  5492.9   486.2  5510.7  486.16
#Mann= 3 ,-1 , 0
  4812.8     .05       0  5077.8    .035       0  5083.8     .05       0
Bank Sta=5077.8,5083.8
XS Rating Curve= 0 ,0
Exp/Cntr=0.3,0.1

Type RM Length L Ch R = 1 ,10290   ,932,932,932
BEGIN DESCRIPTION:
UNT00953 IN CHRS 15.0
END DESCRIPTION:
XS GIS Cut Line= 4
      3497621.92     10590291.34      3496988.27     10590443.24
      3496337.23     10590777.44      3496021.96      10590997.7
#Sta/Elev= 30
  3879.4  501.79    3982  501.58  4105.4   499.9  4197.6  497.92  4412.8   490.7
  4507.2  486.02  4661.6   481.4  4735.1  477.74  4751.5  477.91  4779.5  479.31
    4796  478.26  4818.2  475.84  4840.4  475.24  4942.6   475.8  4987.6  475.36
    4997  474.72  4999.8  474.22    5003  474.72  5017.9  475.64  5032.5  476.01
    5055  475.33  5077.5  476.57  5084.5  477.94  5090.1  477.15  5106.7  480.12
  5112.3  478.61  5128.9  481.24  5144.9  481.65  5521.2  486.07  5647.4  486.31
#Mann= 3 ,-1 , 0
  3879.4      .1       0    4997    .035       0    5003      .1       0
Bank Sta=4987.6,5017.9
XS Rating Curve= 0 ,0
Exp/Cntr=0.3,0.1

Type RM Length L Ch R = 1 ,10287   ,932,932,932
BEGIN DESCRIPTION:
UNT00953 IN CHRS 15.0
END DESCRIPTION:
XS GIS Cut Line= 4
      3497621.92     10590291.34      3496988.27     10590443.24
      3496337.23     10590777.44      3496021.96      10590997.7
#Sta/Elev= 30
  3879.4  501.79    3982  501.58  4105.4   499.9  4197.6  497.92  4412.8   490.7
  4507.2  486.02  4661.6   481.4  4735.1  477.74  4751.5  477.91  4762.9  478.89
  4779.5  479.31    4796  478.26  4818.2  475.84  4840.4  475.24  4942.6   475.8
  4979.2  475.62  4998.4  474.72  5001.1  474.22  5004.4  474.72  5032.5  476.01
    5055  475.33  5077.5  476.57  5084.5  477.94  5090.1  477.15  5106.7  480.12
  5112.3  478.61  5128.9  481.24  5144.9  481.65  5521.2  486.07  5647.4  486.31
#Mann= 3 ,-1 , 0
  3879.4     .05       0  4998.4    .035       0  5004.4     .05       0
Bank Sta=4998.4,5004.4
XS Rating Curve= 0 ,0
Exp/Cntr=0.3,0.1

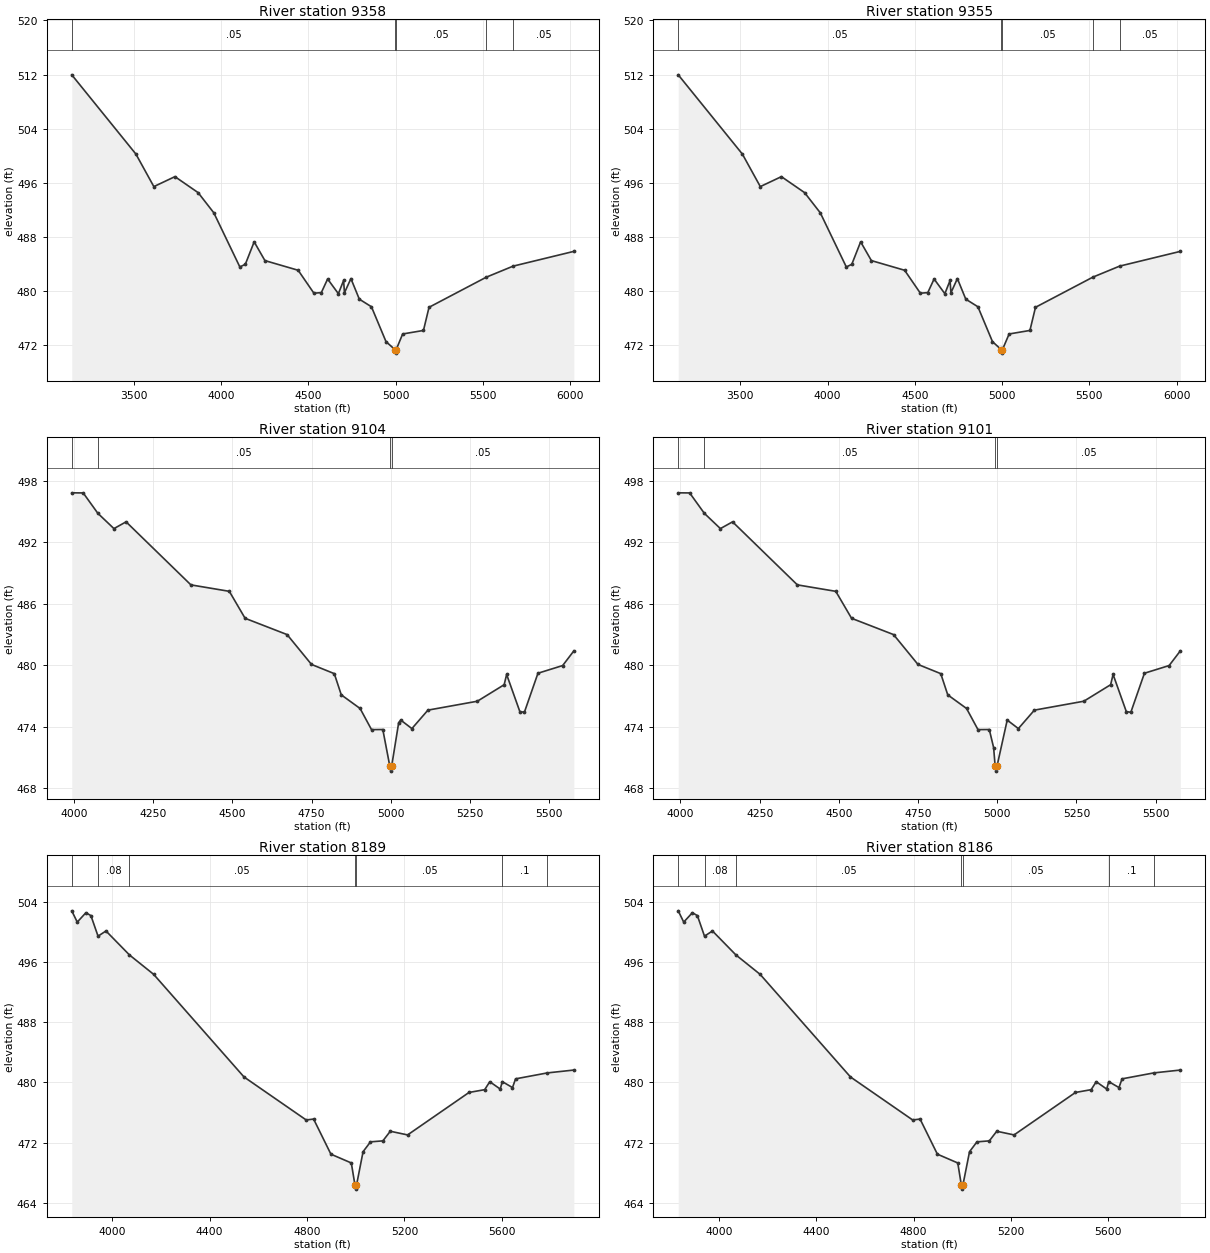
Type RM Length L Ch R = 1 ,9358    ,254,254,254
BEGIN DESCRIPTION:
UNT00953 IN CHRS 14.0
END DESCRIPTION:
XS GIS Cut Line= 4
      3498160.16     10589401.57      3496523.86     10589783.52
      3496311.19     10589870.32      3496011.72     10590790.43
#Sta/Elev= 30
  3143.9  511.97  3511.6  500.26  3614.3  495.46  3735.2  496.93    3868  494.57
  3958.2  491.58  4107.2  483.59  4138.6  483.98  4189.3   487.3  4250.9  484.53
  4441.4   483.1  4531.7  479.71  4574.2   479.8  4610.3  481.81    4672  479.64
  4701.8  481.59  4706.9  479.78  4743.8  481.87    4792  478.83  4861.4  477.71
  4944.9  472.56    4997  471.36  4999.8  470.86    5003  471.36  5040.4  473.69
  5159.6  474.21  5191.5  477.63  5519.9  482.08  5673.5  483.71  6021.5  485.89
#Mann= 5 ,-1 , 0
  3143.9     .05       0    4997     .04       0    5003     .05       0
  5519.9     .08       0  5673.5     .05       0
Bank Sta=4997,5003
XS Rating Curve= 0 ,0
Exp/Cntr=0.3,0.1

Type RM Length L Ch R = 1 ,9355    ,254,254,254
BEGIN DESCRIPTION:
UNT00953 IN CHRS 14.0
END DESCRIPTION:
XS GIS Cut Line= 4
      3498160.16     10589401.57      3496523.86     10589783.52
      3496311.19     10589870.32      3496011.72     10590790.43
#Sta/Elev= 30
  3143.9  511.97  3511.6  500.26  3614.3  495.46  3735.2  496.93    3868  494.57
  3958.2  491.58  4107.2  483.59  4138.6  483.98  4189.3   487.3  4250.9  484.53
  4441.4   483.1  4531.7  479.71  4574.2   479.8  4610.3  481.81    4672  479.64
  4701.8  481.59  4706.9  479.78  4743.8  481.87    4792  478.83  4861.4  477.71
  4944.9  472.56  4995.9  471.36  4998.6  470.86  5001.9  471.36  5040.4  473.69
  5159.6  474.21  5191.5  477.63  5519.9  482.08  5673.5  483.71  6021.5  485.89
#Mann= 5 ,-1 , 0
  3143.9     .05       0  4995.9     .04       0  5001.9     .05       0
  5519.9     .08       0  5673.5     .05       0
Bank Sta=4995.9,5001.9
XS Rating Curve= 0 ,0
Exp/Cntr=0.3,0.1

Type RM Length L Ch R = 1 ,9104    ,915,915,915
BEGIN DESCRIPTION:
UNT00953 IN CHRS 13.0
END DESCRIPTION:
XS GIS Cut Line= 3
      3496719.17     10588789.59      3496298.17     10589596.89
      3495864.15     10590113.36
#Sta/Elev= 30
    3993  496.81  4029.1   496.8  4075.4  494.81  4126.1  493.32  4164.5  493.98
  4369.1  487.83  4490.4   487.2  4540.2  484.57  4672.8  482.98  4749.8  480.07
  4821.8  479.17  4843.9   477.1  4903.3  475.77  4939.3  473.71    4975  473.72
    4997  470.16  4999.8  469.66    5003  470.16  5025.1  474.39  5031.6  474.64
  5066.8  473.81  5117.4  475.61  5273.5  476.48  5358.1  478.09  5365.9  479.09
  5407.6  475.47  5421.9   475.4  5464.8  479.21  5542.8  479.96  5578.1  481.39
#Mann= 4 ,-1 , 0
    3993     .08       0  4075.4     .05       0    4997    .035       0
    5003     .05       0
Bank Sta=4997,5003
XS Rating Curve= 0 ,0
Exp/Cntr=0.3,0.1

Type RM Length L Ch R = 1 ,9101    ,915,915,915
BEGIN DESCRIPTION:
UNT00953 IN CHRS 13.0
END DESCRIPTION:
XS GIS Cut Line= 3
      3496719.17     10588789.59      3496298.17     10589596.89
      3495864.15     10590113.36
#Sta/Elev= 30
    3993  496.81  4029.1   496.8  4075.4  494.81  4126.1  493.32  4164.5  493.98
  4369.1  487.83  4490.4   487.2  4540.2  484.57  4672.8  482.98  4749.8  480.07
  4821.8  479.17  4843.9   477.1  4903.3  475.77  4939.3  473.71    4975  473.72
  4988.7  471.96  4993.5  470.16  4996.2  469.66  4999.5  470.16  5031.6  474.64
  5066.8  473.81  5117.4  475.61  5273.5  476.48  5358.1  478.09  5365.9  479.09
  5407.6  475.47  5421.9   475.4  5464.8  479.21  5542.8  479.96  5578.1  481.39
#Mann= 4 ,-1 , 0
    3993     .08       0  4075.4     .05       0  4993.5    .035       0
  4999.5     .05       0
Bank Sta=4993.5,4999.5
XS Rating Curve= 0 ,0
Exp/Cntr=0.3,0.1

Type RM Length L Ch R = 1 ,8189    ,685,685,685
BEGIN DESCRIPTION:
UNT00953 IN CHRS 12.0
END DESCRIPTION:
XS GIS Cut Line= 4
      3496888.47     10588681.08      3496107.19      10588876.4
      3495503.89     10588984.91      3494991.76     10589375.52
#Sta/Elev= 30
  3833.5  502.83    3856  501.33  3891.6  502.58  3912.2  502.19  3941.4  499.46
  3974.1  500.15  4070.5  496.96  4169.9  494.38    4541  480.73  4796.4  475.01
  4826.9  475.13    4898  470.46  4981.8  469.29    4997  466.31  4999.8  465.81
    5003  466.31  5030.1  470.79  5060.6   472.1  5111.4  472.23  5141.9  473.51
    5213  473.02  5465.3  478.67  5529.7  479.04  5550.5   480.1  5593.6  479.12
  5601.9  480.11  5643.9  479.32  5656.6  480.48    5787  481.27  5895.9  481.65
#Mann= 7 ,-1 , 0
  3833.5     .05       0  3941.4     .08       0  4070.5     .05       0
    4997     .04       0    5003     .05       0  5601.9      .1       0
    5787     .05       0
Bank Sta=4997,5003
XS Rating Curve= 0 ,0
Exp/Cntr=0.3,0.1

Type RM Length L Ch R = 1 ,8186    ,685,685,685
BEGIN DESCRIPTION:
UNT00953 IN CHRS 12.0
END DESCRIPTION:
XS GIS Cut Line= 4
      3496888.47     10588681.08      3496107.19      10588876.4
      3495503.89     10588984.91      3494991.76     10589375.52
#Sta/Elev= 30
  3833.5  502.83    3856  501.33  3891.6  502.58  3912.2  502.19  3941.4  499.46
  3974.1  500.15  4070.5  496.96  4169.9  494.38    4541  480.73  4796.4  475.01
  4826.9  475.13    4898  470.46  4981.8  469.29  4996.6  466.31  4999.4  465.81
  5002.6  466.31  5030.1  470.79  5060.6   472.1  5111.4  472.23  5141.9  473.51
    5213  473.02  5465.3  478.67  5529.7  479.04  5550.5   480.1  5593.6  479.12
  5601.9  480.11  5643.9  479.32  5656.6  480.48    5787  481.27  5895.9  481.65
#Mann= 7 ,-1 , 0
  3833.5     .05       0  3941.4     .08       0  4070.5     .05       0
  4996.6     .04       0  5002.6     .05       0  5601.9      .1       0
    5787     .05       0
Bank Sta=4996.6,5002.6
XS Rating Curve= 0 ,0
Exp/Cntr=0.3,0.1

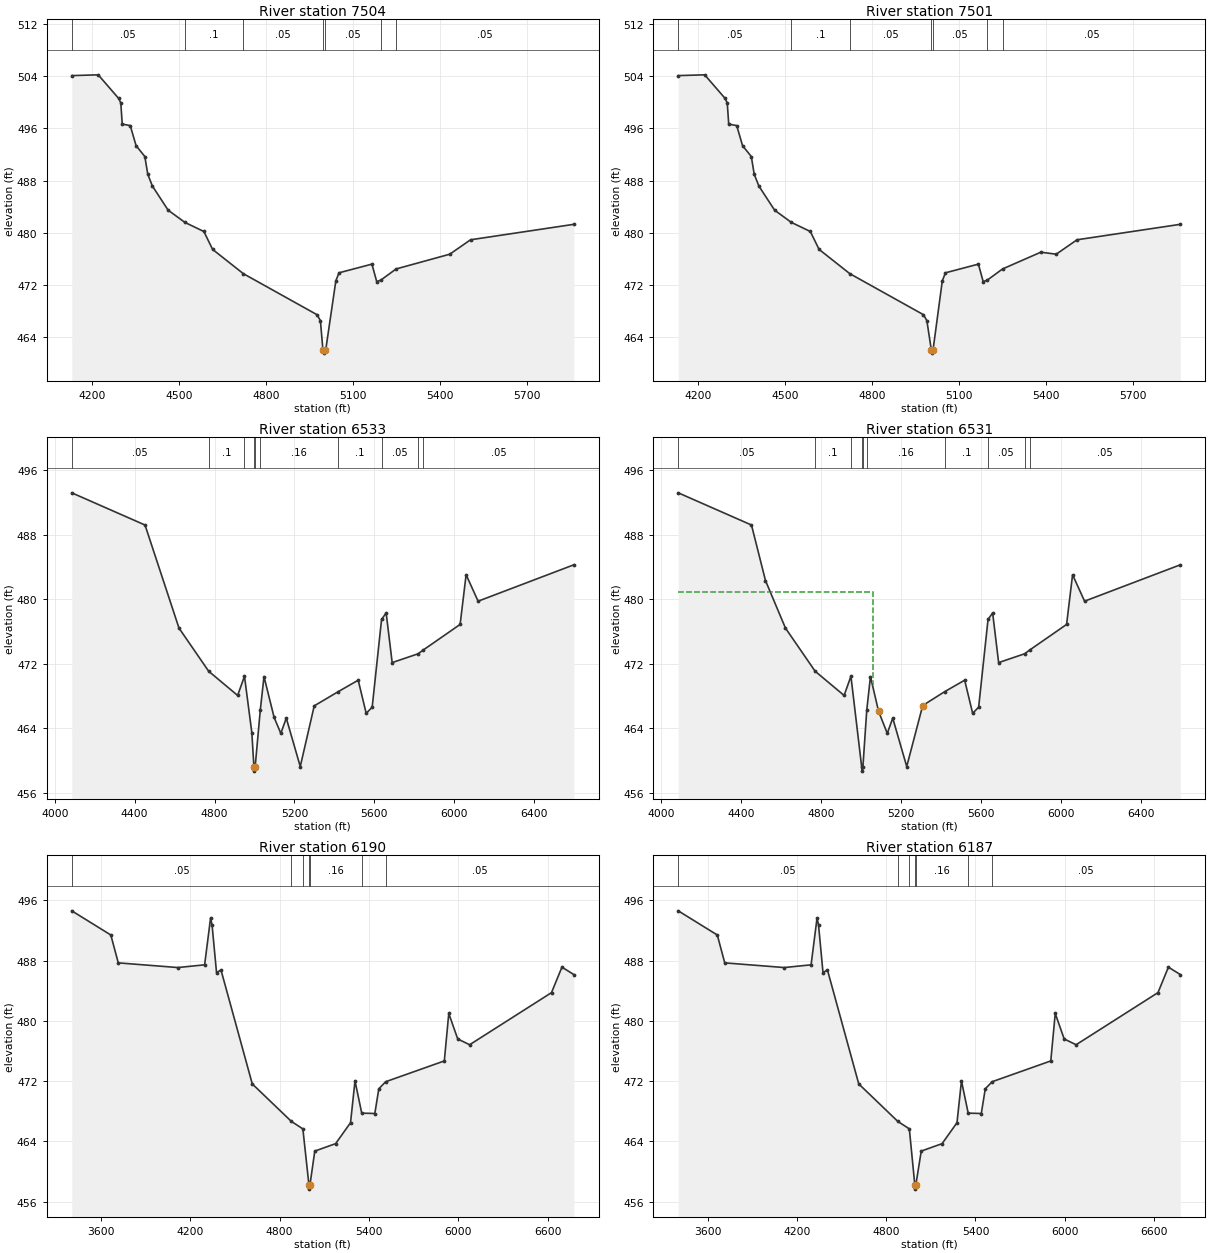
Type RM Length L Ch R = 1 ,7504    ,971,971,971
BEGIN DESCRIPTION:
UNT00953 IN CHRS 9.0
END DESCRIPTION:
XS GIS Cut Line= 4
      3496332.87     10588190.64      3495916.22      10588229.7
      3495291.22     10588490.12      3494983.04     10589045.71
#Sta/Elev= 30
  4131.1   504.1  4222.3  504.22  4292.6  500.61  4300.1  499.92  4305.1  496.67
  4332.7  496.44  4352.8  493.37    4383   491.7    4393     489  4408.9  487.19
  4463.3  483.48  4520.9  481.61  4586.5  480.21  4616.6  477.47  4722.5  473.75
  4976.5  467.46  4988.2  466.56    4997  462.07  4999.8  461.57    5003  462.07
  5006.6  462.07  5041.5  472.65  5052.4  473.88  5165.9  475.21  5182.4  472.53
  5196.6  472.76  5249.2  474.47  5434.2  476.73  5505.9  478.94    5862  481.31
#Mann= 7 ,-1 , 0
  4131.1     .05       0  4520.9      .1       0  4722.5     .05       0
    4997    .035       0    5003     .05       0  5196.6      .1       0
  5249.2     .05       0
Bank Sta=4997,5003
XS Rating Curve= 0 ,0
Exp/Cntr=0.3,0.1

Type RM Length L Ch R = 1 ,7501    ,970,970,970
BEGIN DESCRIPTION:
UNT00953 IN CHRS 9.0
END DESCRIPTION:
XS GIS Cut Line= 4
      3496332.87     10588190.64      3495916.22      10588229.7
      3495291.22     10588490.12      3494983.04     10589045.71
#Sta/Elev= 30
  4131.1   504.1  4222.3  504.22  4292.6  500.61  4300.1  499.92  4305.1  496.67
  4332.7  496.44  4352.8  493.37    4383   491.7    4393     489  4408.9  487.19
  4463.3  483.48  4520.9  481.61  4586.5  480.21  4616.6  477.47  4722.5  473.75
  4976.5  467.46  4988.2  466.56  5003.6  462.07  5006.4  461.57  5009.6  462.07
  5041.5  472.65  5052.4  473.88  5165.9  475.21  5182.4  472.53  5196.6  472.76
  5249.2  474.47  5381.1  477.04  5434.2  476.73  5505.9  478.94    5862  481.31
#Mann= 7 ,-1 , 0
  4131.1     .05       0  4520.9      .1       0  4722.5     .05       0
  5003.6    .035       0  5009.6     .05       0  5196.6      .1       0
  5249.2     .05       0
Bank Sta=5003.6,5009.6
XS Rating Curve= 0 ,0
Exp/Cntr=0.3,0.1

Type RM Length L Ch R = 1 ,6533    ,343,343,343
BEGIN DESCRIPTION:
UNT00953 IN CHRS 8.0
END DESCRIPTION:
XS GIS Cut Line= 4
      3496308.67      10587422.3      3495731.48     10587417.72
      3495250.47     10587500.18      3493802.92     10587481.85
#Sta/Elev= 30
  4085.3  493.18  4451.9  489.19  4621.9  476.42  4770.5  471.07  4915.5  468.07
  4949.7  470.45  4986.5  463.46    4997  459.19  4999.8  458.69    5003  459.19
  5028.8  466.24  5047.4  470.41  5098.1  465.34  5131.6  463.37  5158.9  465.26
  5228.9  459.26  5298.9  466.78  5418.3  468.53  5518.9  469.96  5558.9  465.85
  5588.9  466.62  5635.9   477.5  5658.9  478.29  5688.9  472.14  5818.5  473.23
  5843.9  473.69    6029  476.87    6059  483.03    6119  479.75  6598.2  484.26
#Mann= 10 ,-1 , 0
  4085.3     .05       0  4770.5      .1       0  4949.7     .12       0
    4997     .07       0    5003     .12       0  5028.8     .16       0
  5418.3      .1       0  5635.9     .05       0  5818.5      .1       0
  5843.9     .05       0
Bank Sta=4997,5003
XS Rating Curve= 0 ,0
Exp/Cntr=0.3,0.1

Type RM Length L Ch R = 1 ,6531    ,344,344,344
BEGIN DESCRIPTION:
UNT00953 IN CHRS 8.0
END DESCRIPTION:
XS GIS Cut Line= 4
      3496308.67      10587422.3      3495731.48     10587417.72
      3495250.47     10587500.18      3493802.92     10587481.85
#Sta/Elev= 30
  4085.3  493.18  4451.9  489.19  4521.9  482.31  4621.9  476.42  4770.5  471.07
  4915.5  468.07  4949.7  470.45  5003.5  459.19  5006.3  458.69  5009.5  459.19
  5028.8  466.24  5047.4  470.41    5088   466.1  5131.6  463.37  5158.9  465.26
  5228.9  459.26  5308.9  466.82  5418.3  468.53  5518.9  469.96  5558.9  465.85
  5588.9  466.62  5635.9   477.5  5658.9  478.29  5688.9  472.14  5818.5  473.23
  5843.9  473.69    6029  476.87    6059  483.03    6119  479.75  6598.2  484.26
#Mann= 10 ,-1 , 0
  4085.3     .05       0  4770.5      .1       0  4949.7     .12       0
  5003.5     .07       0  5009.5     .12       0  5028.8     .16       0
  5418.3      .1       0  5635.9     .05       0  5818.5      .1       0
  5843.9     .05       0
#XS Ineff= 1 ,-1
 4074.64 5059.39  480.84
Permanent Ineff=
       F
Bank Sta=5088,5308.9
XS Rating Curve= 0 ,0
Exp/Cntr=0.3,0.1

Type RM Length L Ch R = 1 ,6190    ,318,318,318
BEGIN DESCRIPTION:
UNT00953 IN CHRS 7.0
END DESCRIPTION:
XS GIS Cut Line= 2
       3496914.5     10587170.67      3493542.07     10587114.25
#Sta/Elev= 30
  3403.4  494.61  3665.8   491.4  3715.8   487.7  4115.9  487.08  4295.9  487.44
  4335.9  493.65  4345.9  492.74  4375.9  486.41  4405.9  486.75    4616  471.63
  4878.7  466.65  4955.9  465.66    4997  458.16  4999.8  457.66    5003  458.16
    5036  462.71    5176   463.7  5276.1  466.48  5306.1  472.03  5351.3  467.75
  5439.3   467.7  5466.1  470.98  5512.1  471.92  5906.1  474.68  5936.1  480.98
  5996.2   477.6  6076.2  476.83  6626.2  483.75  6696.3  487.13  6776.3  486.15
#Mann= 7 ,-1 , 0
  3403.4     .05       0  4878.7      .1       0  4955.9     .16       0
    4997     .07       0    5003     .16       0  5351.3      .1       0
  5512.1     .05       0
Bank Sta=4997,5003
XS Rating Curve= 0 ,0
Exp/Cntr=0.3,0.1

Type RM Length L Ch R = 1 ,6187    ,318,318,318
BEGIN DESCRIPTION:
UNT00953 IN CHRS 7.0
END DESCRIPTION:
XS GIS Cut Line= 2
       3496914.5     10587170.67      3493542.07     10587114.25
#Sta/Elev= 30
  3403.4  494.61  3665.8   491.4  3715.8   487.7  4115.9  487.08  4295.9  487.44
  4335.9  493.65  4345.9  492.74  4375.9  486.41  4405.9  486.75    4616  471.63
  4878.7  466.65  4955.9  465.66    4993  458.16  4995.8  457.66    4999  458.16
    5036  462.71    5176   463.7  5276.1  466.48  5306.1  472.03  5351.3  467.75
  5439.3   467.7  5466.1  470.98  5512.1  471.92  5906.1  474.68  5936.1  480.98
  5996.2   477.6  6076.2  476.83  6626.2  483.75  6696.3  487.13  6776.3  486.15
#Mann= 7 ,-1 , 0
  3403.4     .05       0  4878.7      .1       0  4955.9     .16       0
    4993     .07       0    4999     .16       0  5351.3      .1       0
  5512.1     .05       0
Bank Sta=4993,4999
XS Rating Curve= 0 ,0
Exp/Cntr=0.3,0.1