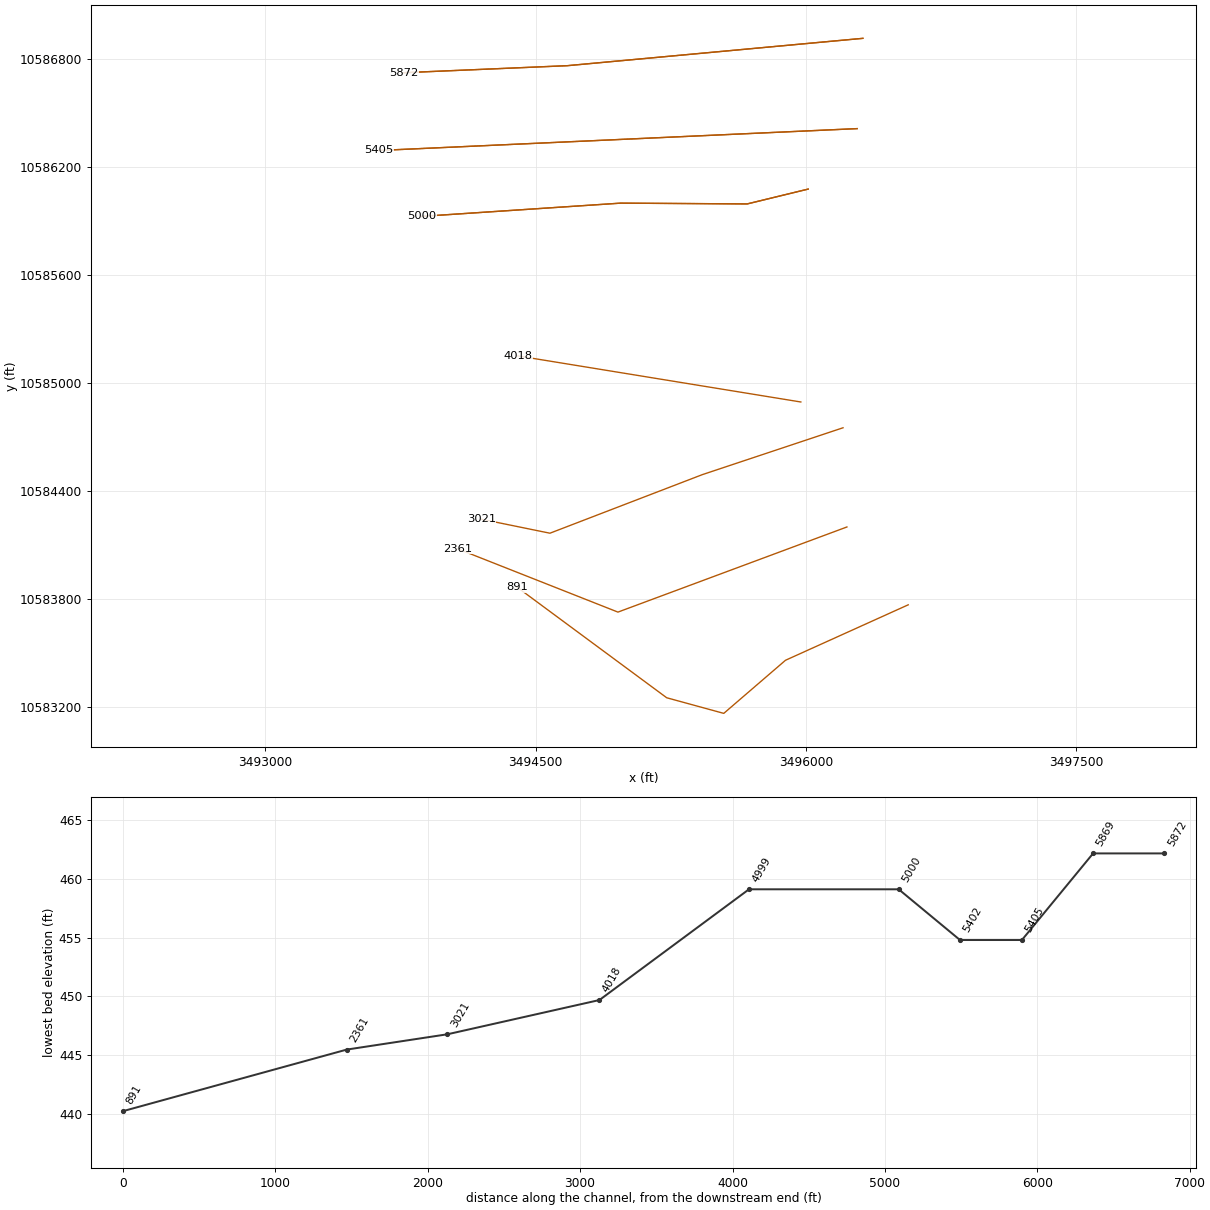
HEC-RAS study UNT00953 IN CHRS.prj: UNT00953 IN CHRS Base Level Engineering

--- UNT00953 IN CHRS.g01 (geometry) --- (continued)

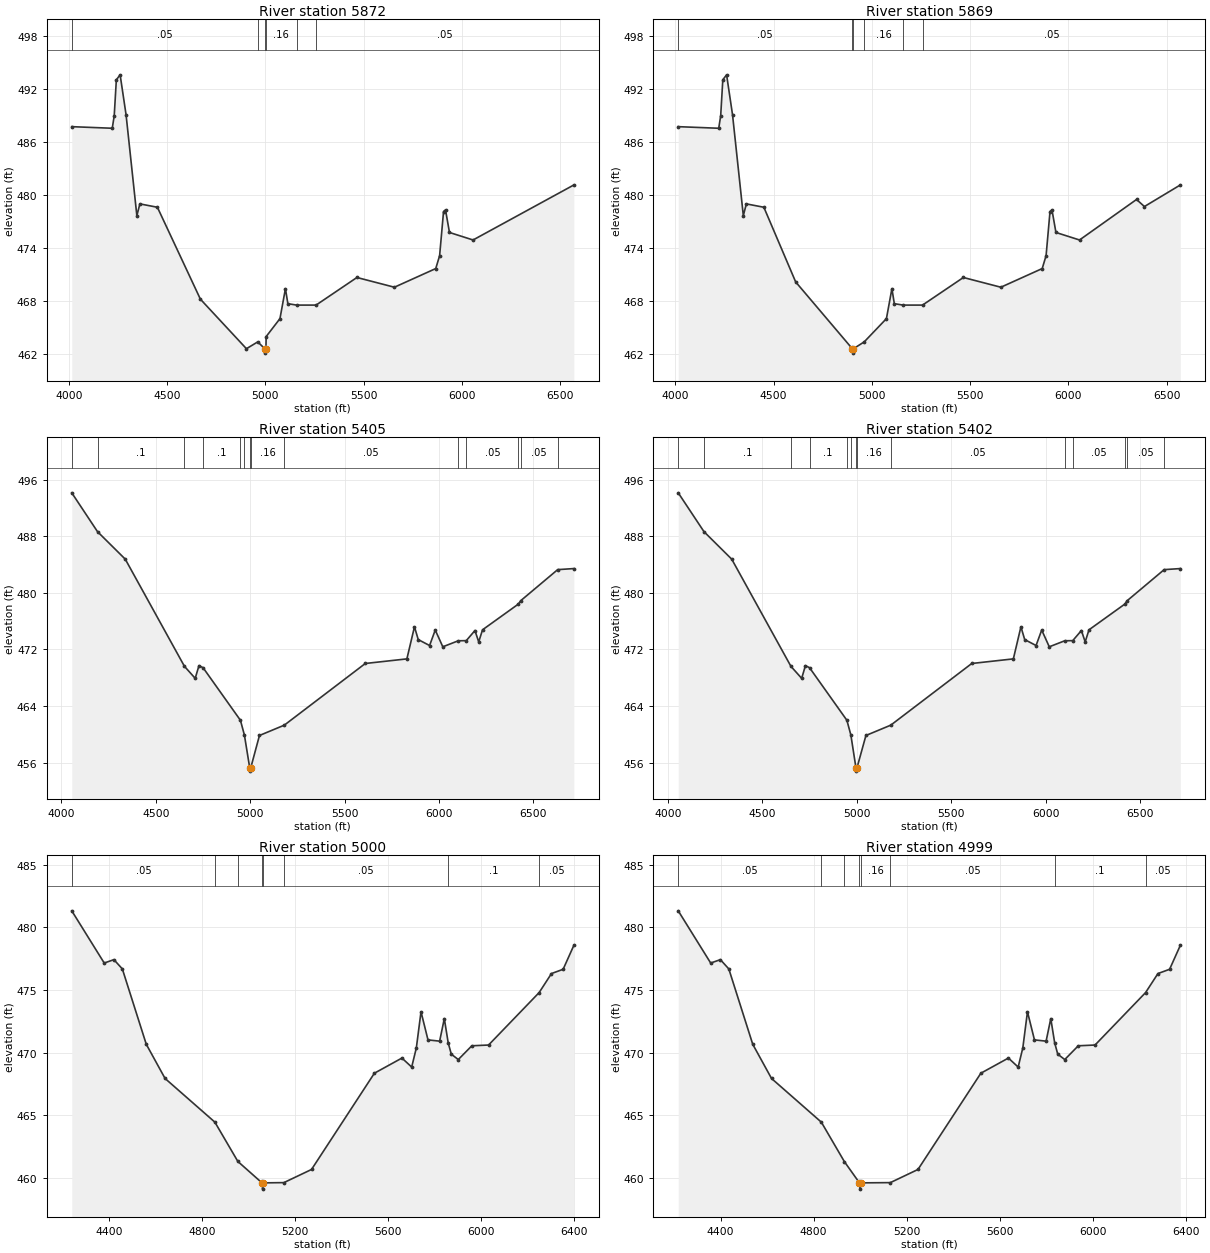
Type RM Length L Ch R = 1 ,5872    ,467,467,467
BEGIN DESCRIPTION:
UNT00953 IN CHRS 6.6
END DESCRIPTION:
XS GIS Cut Line= 3
      3496317.29     10586917.17       3494676.7     10586765.26
      3493769.55      10586726.2
#Sta/Elev= 30
  4014.6  487.75  4220.7  487.57  4230.7  488.98  4241.5  493.05  4260.8  493.61
    4291  489.09  4345.9  477.69  4361.3  479.02  4450.4  478.64  4669.3  468.25
  4903.6  462.65  4961.2  463.42    4997  462.65  4999.8  462.15    5003  462.65
    5004  464.02  5074.3  466.05  5102.2  469.44  5114.5  467.74  5159.1  467.58
  5258.1  467.58    5466   470.7  5656.8   469.6  5867.3  471.71    5887  473.17
    5907  478.16    5917  478.34  5937.1  475.79  6057.2  474.94  6570.2  481.16
#Mann= 6 ,-1 , 0
  4014.6     .05       0  4961.2     .16       0    4997     .07       0
    5003     .16       0  5159.1      .1       0  5258.1     .05       0
Bank Sta=4997,5003
XS Rating Curve= 0 ,0
Exp/Cntr=0.3,0.1

Type RM Length L Ch R = 1 ,5869    ,467,467,467
BEGIN DESCRIPTION:
UNT00953 IN CHRS 6.6
END DESCRIPTION:
XS GIS Cut Line= 3
      3496317.29     10586917.17       3494676.7     10586765.26
      3493769.55      10586726.2
#Sta/Elev= 30
  4014.6  487.75  4220.7  487.57  4230.7  488.98  4241.5  493.05  4260.8  493.61
    4291  489.09  4345.9  477.69  4361.3  479.02  4450.4  478.64  4612.3   470.2
  4900.6  462.65  4903.3  462.15  4906.6  462.65  4961.2  463.42  5074.3  466.05
  5102.2  469.44  5114.5  467.74  5159.1  467.58  5258.1  467.58    5466   470.7
  5656.8   469.6  5867.3  471.71    5887  473.17    5907  478.16    5917  478.34
  5937.1  475.79  6057.2  474.94  6347.4  479.52  6387.5  478.72  6570.2  481.16
#Mann= 6 ,-1 , 0
  4014.6     .05       0  4900.6     .07       0  4906.6     .05       0
  4961.2     .16       0  5159.1      .1       0  5258.1     .05       0
Bank Sta=4900.6,4906.6
XS Rating Curve= 0 ,0
Exp/Cntr=0.3,0.1

Type RM Length L Ch R = 1 ,5405    ,406,406,406
BEGIN DESCRIPTION:
UNT00953 IN CHRS 6.0
END DESCRIPTION:
XS GIS Cut Line= 2
       3496285.1     10586415.46      3493628.88     10586293.93
#Sta/Elev= 30
  4054.8  494.14  4191.1  488.65  4338.1  484.76  4651.5  469.61  4708.5  467.91
  4728.5  469.71  4750.3  469.41    4948  461.98  4969.1  459.89    4997  455.29
  4999.8  454.79    5003  455.29  5048.8  459.83  5180.4  461.29  5609.4  470.01
  5829.6  470.66  5869.7   475.2  5889.7  473.39  5949.8  472.55  5979.8  474.74
  6019.8  472.37  6101.8  473.22  6144.1  473.24    6190  474.67    6210  473.06
  6230.1  474.77    6420  478.41  6432.5  478.89  6628.2  483.28  6713.8  483.43
#Mann= 14 ,-1 , 0
  4054.8     .05       0  4191.1      .1       0  4651.5     .16       0
  4750.3      .1       0    4948     .12       0  4969.1     .16       0
    4997     .07       0    5003     .16       0  5180.4     .05       0
  6101.8      .1       0  6144.1     .05       0    6420     .08       0
  6432.5     .05       0  6628.2     .15       0
Bank Sta=4997,5003
XS Rating Curve= 0 ,0
Exp/Cntr=0.3,0.1

Type RM Length L Ch R = 1 ,5402    ,402,402,402
BEGIN DESCRIPTION:
UNT00953 IN CHRS 6.0
END DESCRIPTION:
XS GIS Cut Line= 2
       3496285.1     10586415.46      3493628.88     10586293.93
#Sta/Elev= 30
  4054.8  494.14  4191.1  488.65  4338.1  484.76  4651.5  469.61  4708.5  467.91
  4728.5  469.71  4750.3  469.41    4948  461.98  4969.1  459.89  4995.8  455.29
  4998.5  454.79  5001.8  455.29  5048.8  459.83  5180.4  461.29  5609.4  470.01
  5829.6  470.66  5869.7   475.2  5889.7  473.39  5949.8  472.55  5979.8  474.74
  6019.8  472.37  6101.8  473.22  6144.1  473.24    6190  474.67    6210  473.06
  6230.1  474.77    6420  478.41  6432.5  478.89  6628.2  483.28  6713.8  483.43
#Mann= 14 ,-1 , 0
  4054.8     .05       0  4191.1      .1       0  4651.5     .16       0
  4750.3      .1       0    4948     .12       0  4969.1     .16       0
  4995.8     .07       0  5001.8     .16       0  5180.4     .05       0
  6101.8      .1       0  6144.1     .05       0    6420     .08       0
  6432.5     .05       0  6628.2     .15       0
Bank Sta=4995.8,5001.8
XS Rating Curve= 0 ,0
Exp/Cntr=0.3,0.1

Type RM Length L Ch R = 1 ,5000    ,982,982,982
BEGIN DESCRIPTION:
UNT00953 IN CHRS 4.6
END DESCRIPTION:
XS GIS Cut Line= 4
      3496013.47     10586079.49      3495674.97     10585997.03
      3494971.84     10586001.37      3493866.13     10585927.66
#Sta/Elev= 30
  4238.5  481.33  4378.1  477.16  4419.8  477.43    4456  476.69    4559  470.67
  4639.8  467.94  4854.1  464.45    4953  461.31  5056.8   459.6  5059.5   459.1
  5062.8   459.6  5150.9  459.62  5269.8  460.67  5540.3  468.36  5658.7  469.57
  5700.7  468.85  5720.7  470.38  5740.8  473.27  5770.8  471.02  5820.9  470.92
    5841  472.72  5857.8  470.78  5871.1  469.88  5901.1  469.45  5959.4  470.55
  6031.4  470.61  6248.9   474.8    6302  476.32  6352.1  476.66  6398.2  478.57
#Mann= 8 ,-1 , 0
  4238.5     .05       0  4854.1      .1       0    4953     .16       0
  5056.8     .07       0  5062.8     .16       0  5150.9     .05       0
  5857.8      .1       0  6248.9     .05       0
Bank Sta=5056.8,5062.8
XS Rating Curve= 0 ,0
Exp/Cntr=0.3,0.1

Type RM Length L Ch R = 1 ,4999    ,981,981,981
BEGIN DESCRIPTION:
UNT00953 IN CHRS 4.6
END DESCRIPTION:
XS GIS Cut Line= 4
      3496013.54      10586079.5      3495674.97     10585997.03
      3494971.84     10586001.37       3493866.1     10585927.66
#Sta/Elev= 30
  4217.4  481.33    4357  477.16  4398.7  477.43    4435  476.69  4537.9  470.67
  4618.7  467.94    4833  464.45    4932   461.3    4997   459.6  4999.8   459.1
    5003   459.6  5129.9  459.62  5248.7  460.67  5519.3  468.36  5637.7  469.57
  5679.7  468.85  5699.7  470.38  5719.7  473.27  5749.8  471.02  5799.9  470.92
    5820  472.72  5836.8  470.78    5850  469.88  5880.1  469.45  5938.3  470.55
  6010.4  470.61  6227.8   474.8    6281  476.32  6331.1  476.66  6377.2  478.57
#Mann= 8 ,-1 , 0
  4217.4     .05       0    4833      .1       0    4932     .16       0
    4997     .07       0    5003     .16       0  5129.9     .05       0
  5836.8      .1       0  6227.8     .05       0
Bank Sta=4997,5003
XS Rating Curve= 0 ,0
Exp/Cntr=0.3,0.1

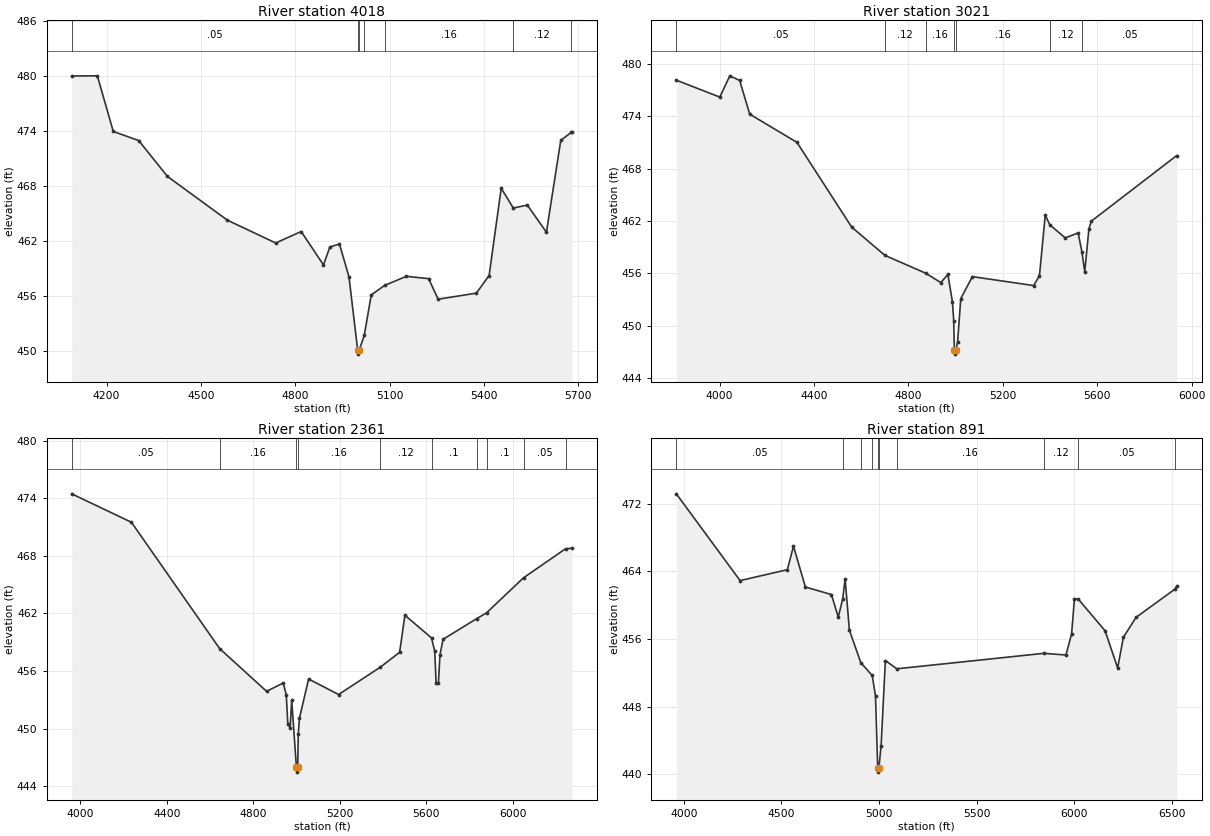
Type RM Length L Ch R = 1 ,4018    ,997,997,997
BEGIN DESCRIPTION:
UNT00953 IN CHRS 4.0
END DESCRIPTION:
XS GIS Cut Line= 2
      3495972.68     10584896.36      3494401.51     10585152.44
#Sta/Elev= 30
  4088.9  479.97  4170.5  479.99  4221.2  473.93  4302.2  472.94  4393.4  469.04
  4584.4  464.27  4737.9  461.79    4819  463.04  4889.9   459.4  4910.2  461.35
  4940.6  461.68    4971  458.11  4998.4  450.19  5001.1  449.69  5004.4  450.19
  5019.7  451.76  5041.9  456.14  5084.4  457.17  5153.3  458.16  5224.3  457.91
  5254.7  455.67  5376.2  456.33  5416.8  458.25  5455.3  467.75  5493.8  465.59
  5538.3  465.92  5599.1  462.96  5644.8  472.97  5678.1  473.83  5680.8  473.83
#Mann= 7 ,-1 , 0
  4088.9     .05       0  4998.4    .035       0  5004.4     .05       0
  5019.7     .12       0  5084.4     .16       0  5493.8     .12       0
  5678.1      .1       0
Bank Sta=4998.4,5004.4
XS Rating Curve= 0 ,0
Exp/Cntr=0.3,0.1

Type RM Length L Ch R = 1 ,3021    ,660,660,660
BEGIN DESCRIPTION:
UNT00953 IN CHRS 2.0
END DESCRIPTION:
XS GIS Cut Line= 4
      3496206.99     10584753.13      3495425.77     10584492.72
      3494579.42      10584167.2      3494197.49     10584245.32
#Sta/Elev= 30
  3816.8   478.1  4001.1  476.17  4043.3   478.6  4085.2  478.07  4127.6  474.22
  4327.9  470.99  4559.6  461.31  4700.4  458.07  4872.8  456.04  4937.3  454.96
  4967.3  455.89  4986.6  452.75  4991.9  450.62  4994.8  447.28  4997.5  446.78
  5000.8  447.28  5008.5  448.17  5021.9  453.14  5071.2  455.64  5330.5  454.62
  5355.2  455.74  5379.8  462.67  5399.1  461.56  5464.4  460.07  5519.1  460.64
  5535.5  458.42  5547.1  456.18  5564.7  461.09  5574.9  461.98  5936.9  469.49
#Mann= 7 ,-1 , 0
  3816.8     .05       0  4700.4     .12       0  4872.8     .16       0
  4994.8     .07       0  5000.8     .16       0  5399.1     .12       0
  5535.5     .05       0
Bank Sta=4994.8,5000.8
XS Rating Curve= 0 ,0
Exp/Cntr=0.3,0.1

Type RM Length L Ch R = 1 ,2361    ,1470,1470,1470
BEGIN DESCRIPTION:
UNT00953 IN CHRS 3.0
END DESCRIPTION:
XS GIS Cut Line= 3
      3496228.72     10584201.92      3494957.02     10583728.83
      3494067.31     10584080.38
#Sta/Elev= 30
  3960.2  474.45  4236.4  471.49  4644.2  458.34  4861.3  453.89  4938.2  454.76
  4952.3  453.51  4959.5  450.44  4970.2  450.09  4977.3  452.99  4999.2  445.98
    5002  445.48  5005.2  445.98  5007.7  449.42    5013  451.08  5055.6  455.17
  5194.3  453.56  5386.1  456.39  5476.3  457.95  5500.7  461.81  5623.8  459.45
  5638.6  458.06  5644.9  454.76  5655.7  454.77  5662.9   457.7  5677.2  459.31
  5832.9  461.46  5878.1  462.06    6049  465.71  6243.3  468.73  6273.7  468.79
#Mann= 10 ,-1 , 0
  3960.2     .05       0  4644.2     .16       0  4999.2     .07       0
  5005.2     .16       0  5386.1     .12       0  5623.8      .1       0
  5832.9     .05       0  5878.1      .1       0    6049     .05       0
  6243.3      .1       0
Bank Sta=4999.2,5005.2
XS Rating Curve= 0 ,0
Exp/Cntr=0.3,0.1

Type RM Length L Ch R = 1 ,891     ,0,0,0
BEGIN DESCRIPTION:
UNT00953 IN CHRS 1.0
END DESCRIPTION:
XS GIS Cut Line= 5
      3496568.95     10583769.31      3495887.56     10583461.17
      3495544.68     10583166.03      3495227.84     10583252.83
      3494395.82     10583868.18
#Sta/Elev= 30
  3961.3  473.18  4287.9  462.91    4530   464.2  4561.5  466.98  4622.4  462.15
  4755.7  461.26  4790.8  458.59  4813.9  460.77  4825.9  463.13  4847.8  457.06
  4906.2   453.2  4964.8  451.68  4981.7  449.24    4993  440.74  4995.7  440.24
    4999  440.74  5010.3  443.33  5032.2  453.45    5091  452.47  5843.8   454.3
  5957.4   454.1  5986.3  456.62  6000.9  460.78  6020.7  460.71  6157.5  456.98
  6222.2  452.57  6251.5  456.19  6316.2  458.56  6516.9  461.92  6524.9  462.28
#Mann= 10 ,-1 , 0
  3961.3     .05       0  4813.9     .12       0  4906.2     .16       0
  4964.8     .12       0    4993     .07       0    4999     .12       0
    5091     .16       0  5843.8     .12       0  6020.7     .05       0
  6516.9      .1       0
Bank Sta=4993,4999
XS Rating Curve= 0 ,0
Exp/Cntr=0.3,0.1

Chan Stop Cuts=-1
Use User Specified Reach Order=0
Composite Channel Slope=5