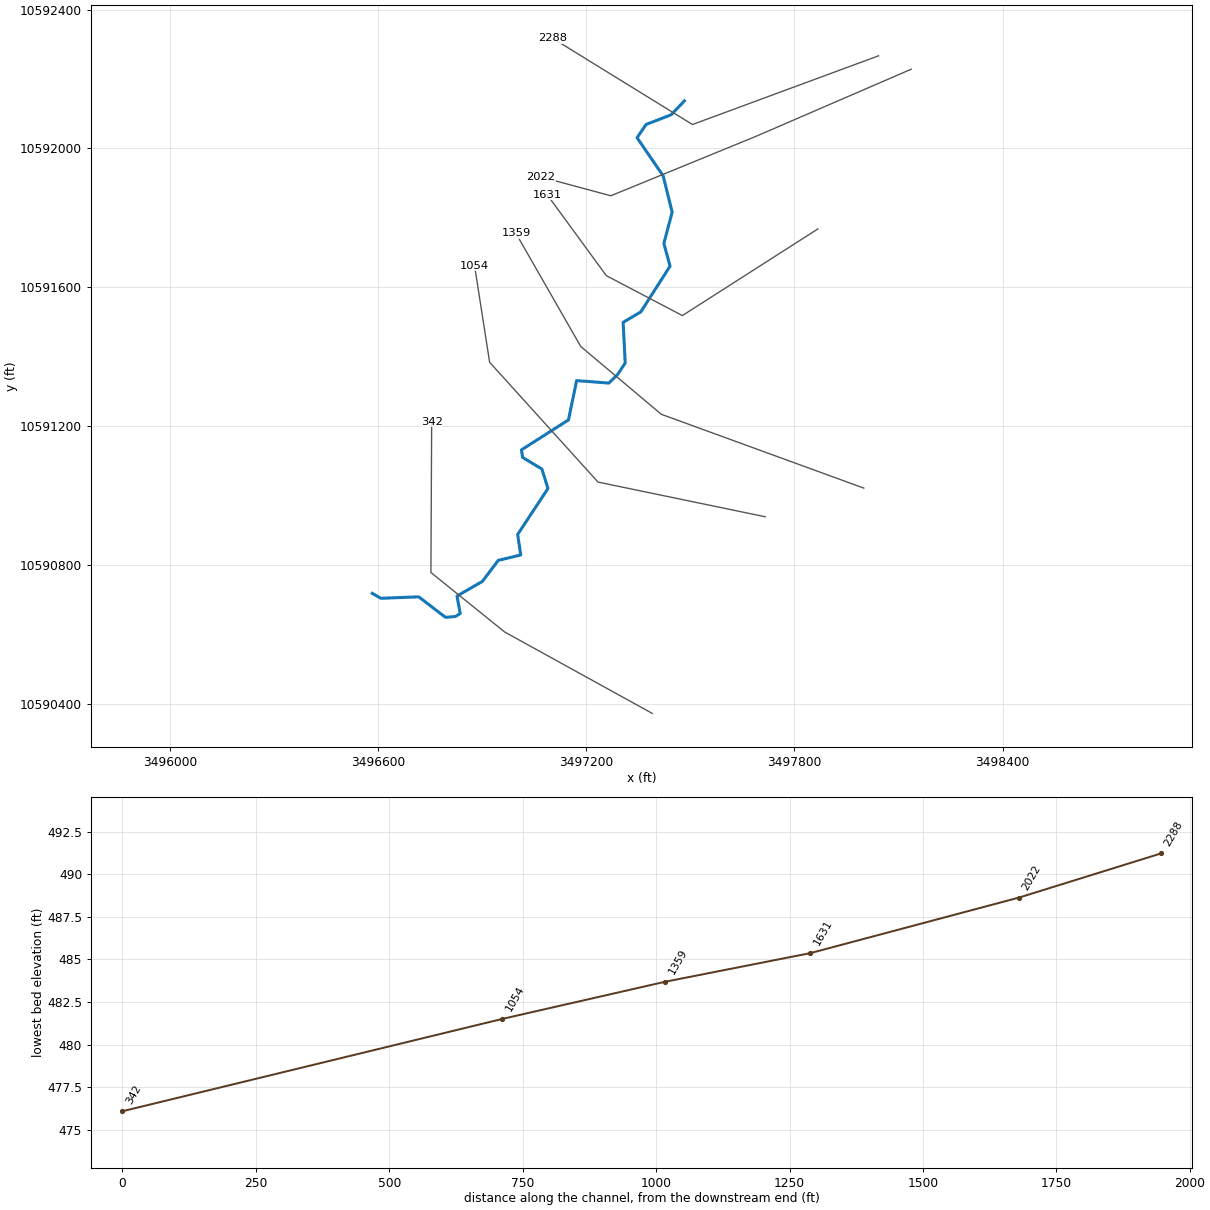
--- UNT00955 IN CHRS.prj (project) ---

Proj Title=UNT00955 IN CHRS Base Level Engineering
Current Plan=p01
Default Exp/Contr=0.3,0.1
English Units
Geom File=g01
Flow File=f01
Plan File=p01
Y Axis Title=Elevation
X Axis Title(PF)=Main Channel Distance
X Axis Title(XS)=Station
BEGIN DESCRIPTION:
UNT00955 IN CHRS
END DESCRIPTION:
DSS Export Rating Curves= 0
DSS Export Rating Curve Sorted= 0
DSS Export Volume Flow Curves= 0
DXF OffsetX= 0
DXF OffsetY= 0
DXF ScaleX= 1
DXF ScaleY= 10

--- UNT00955 IN CHRS.p01 (plan) ---

Plan Title=Multiple Run
Short Identifier=Multiple
Geom File=g01
Flow File=f01
Subcritical Flow
K Sum by GR= 0
Std Step Tol= 0.01
Critical Tol= 0.01
Num of Std Step Trials= 20
Max Error Tol= 0.3
Flow Tol Ratio= 0.001
Split Flow NTrial= 30
Split Flow Tol= 0.02
Split Flow Ratio= 0.02
Log Output Level= 0
Friction Slope Method= 1
Unsteady Friction Slope Method= 2
Unsteady Bridges Friction Slope Method= 1
Parabolic Critical Depth
Global Vel Dist=  1 , 1 , 1
Global Log Level= 0
CheckData=True
Encroach Param= -1, 0, 0, 0
BEGIN DESCRIPTION:
Multiple Run
END DESCRIPTION:

--- UNT00955 IN CHRS.f01 (steady flow) ---

Flow Title=Multiple
Number of Profiles=7
Profile Names=10-year,25-year,50-year,1pct_min,100-year,1pct_plu,500-year
River Rch & RM= UNT00955 IN CHRS,Reach-1,2288
     160     189     208     168     227     308     270
Boundary for River Rch & Prof#=UNT00955 IN CHRS,Reach-1,1
Up Type=0
Dn Type=3
Dn Slope=0.005
Boundary for River Rch & Prof#=UNT00955 IN CHRS,Reach-1,2
Up Type=0
Dn Type=3
Dn Slope=0.005
Boundary for River Rch & Prof#=UNT00955 IN CHRS,Reach-1,3
Up Type=0
Dn Type=3
Dn Slope=0.005
Boundary for River Rch & Prof#=UNT00955 IN CHRS,Reach-1,4
Up Type=0
Dn Type=3
Dn Slope=0.005
Boundary for River Rch & Prof#=UNT00955 IN CHRS,Reach-1,5
Up Type=0
Dn Type=3
Dn Slope=0.005
Boundary for River Rch & Prof#=UNT00955 IN CHRS,Reach-1,6
Up Type=0
Dn Type=3
Dn Slope=0.005
Boundary for River Rch & Prof#=UNT00955 IN CHRS,Reach-1,7
Up Type=0
Dn Type=3
Dn Slope=0.005

--- UNT00955 IN CHRS.g01 (geometry) ---

Geom Title=Existing Conditions
Program Version=4.10

River Reach=UNT00955 IN CHRS,Reach-1
Reach XY= 30
      3497482.73     10592136.97      3497444.63     10592097.06
      3497372.22     10592069.12      3497346.35     10592030.81
      3497421.45     10591921.26      3497447.48     10591816.51
      3497423.55     10591726.55      3497441.41     10591661.11
      3497356.99      10591529.2      3497306.17      10591499.2
      3497312.11     10591381.64      3497289.39     10591347.91
      3497264.76     10591324.25      3497171.99     10591331.33
      3497148.61     10591218.19      3497012.88      10591131.7
      3497016.33     10591110.12      3497071.97     10591076.64
      3497089.39     10591020.56      3497002.05     10590888.15
      3497011.05     10590829.17      3496946.09     10590813.54
       3496900.6      10590753.1      3496827.24     10590710.88
      3496836.57     10590660.32      3496822.25     10590651.86
      3496794.03     10590649.47      3496717.02     10590708.53
      3496607.75     10590704.35      3496583.08     10590718.51

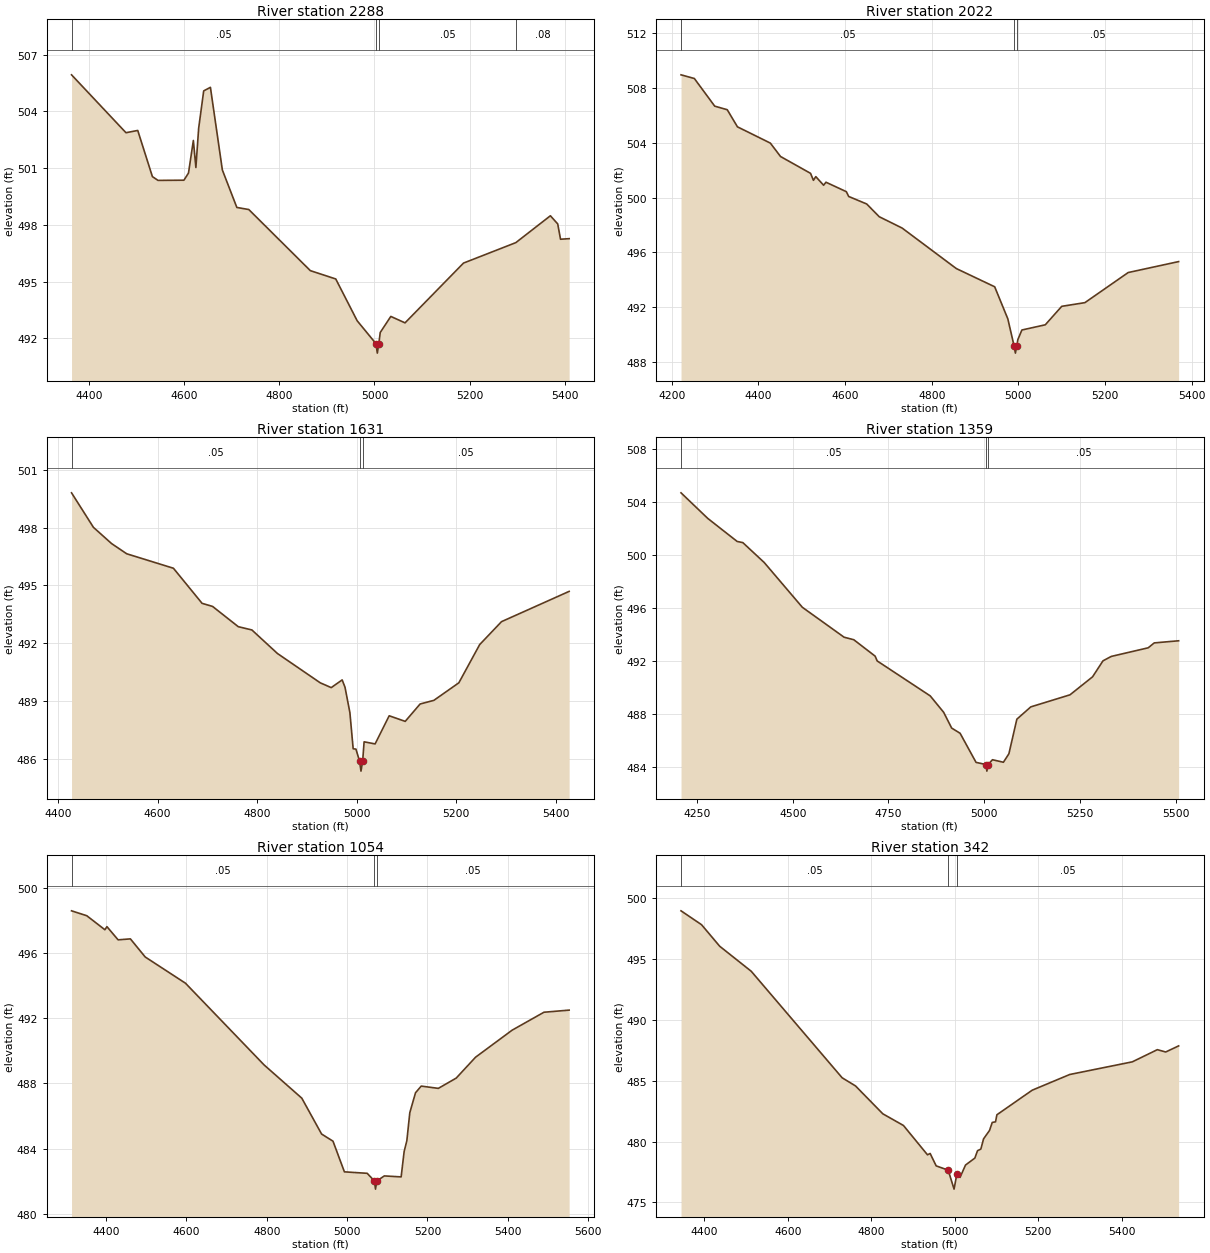
Type RM Length L Ch R = 1 ,2288    ,266,266,266
BEGIN DESCRIPTION:
UNT00955 IN CHRS 4.9
END DESCRIPTION:
XS GIS Cut Line= 3
      3498042.48     10592266.88      3497506.03     10592068.97
      3497103.24     10592317.14
#Sta/Elev= 30
  4363.9  505.93  4478.2  502.87  4502.9  502.99  4533.7  500.55  4545.5  500.35
  4599.9  500.36  4609.5  500.74  4619.7  502.46    4625  501.03  4630.8   503.1
  4641.4  505.08  4655.5  505.27  4680.6   500.9    4711  498.92  4736.1  498.81
  4865.3  495.58  4918.7  495.14  4963.7  492.93  5003.2  491.72    5006  491.22
  5009.2  491.72  5012.1  492.31  5034.3  493.16  5064.2  492.82    5187  495.98
  5296.8  497.06  5369.4  498.48  5384.8  498.05  5390.7  497.24  5408.8  497.27
#Mann= 4 ,-1 , 0
  4363.9     .05       0  5003.2     .03       0  5009.2     .05       0
  5296.8     .08       0
Bank Sta=5003.2,5009.2
XS Rating Curve= 0 ,0
Exp/Cntr=0.3,0.1

Type RM Length L Ch R = 1 ,2022    ,391,391,391
BEGIN DESCRIPTION:
UNT00955 IN CHRS 4.0
END DESCRIPTION:
XS GIS Cut Line= 4
      3498136.63      10592228.3      3497689.55     10592035.15
      3497270.71     10591863.71      3497068.86     10591917.97
#Sta/Elev= 30
  4221.4  508.97  4252.2   508.7  4299.2  506.68  4328.1  506.42  4351.6  505.17
  4427.6  503.98  4451.1     503  4520.4  501.77    4527  501.26  4532.5  501.53
  4550.5   500.9    4556  501.12    4603  500.43  4608.4  500.08    4650  499.53
  4678.9   498.6  4731.8  497.77  4856.9  494.81  4945.4  493.48  4975.8  491.13
  4990.4  489.13  4993.2  488.63  4996.4  489.13  4998.8  489.61  5008.2  490.32
  5062.2   490.7  5100.2  492.05  5153.7  492.32  5253.6  494.52    5370  495.32
#Mann= 3 ,-1 , 0
  4221.4     .05       0  4990.4     .03       0  4996.4     .05       0
Bank Sta=4990.4,4996.4
XS Rating Curve= 0 ,0
Exp/Cntr=0.3,0.1

Type RM Length L Ch R = 1 ,1631    ,272,272,272
BEGIN DESCRIPTION:
UNT00955 IN CHRS 3.5
END DESCRIPTION:
XS GIS Cut Line= 4
       3497867.5     10591768.22      3497476.88     10591518.66
      3497257.69     10591633.67      3497087.17     10591866.79
#Sta/Elev= 30
    4427   499.8    4471  498.01  4507.4  497.17  4537.8  496.64  4631.7  495.89
  4689.3  494.07  4710.4  493.91    4762  492.86  4789.4  492.69  4840.7  491.47
  4926.7  489.95  4948.8   489.7  4970.8   490.1  4976.5  489.72  4986.3  488.41
  4992.9  486.53  4998.5  486.51  5005.9  485.87  5008.6  485.37  5011.9  485.87
  5014.9  486.89    5037  486.78  5065.3  488.24  5097.5  487.95  5127.4  488.85
  5155.1  489.04  5205.3  489.95  5247.1  491.93    5291  493.12  5426.9  494.69
#Mann= 3 ,-1 , 0
    4427     .05       0  5005.9     .03       0  5011.9     .05       0
Bank Sta=5005.9,5011.9
XS Rating Curve= 0 ,0
Exp/Cntr=0.3,0.1

Type RM Length L Ch R = 1 ,1359    ,305,305,305
BEGIN DESCRIPTION:
UNT00955 IN CHRS 3.0
END DESCRIPTION:
XS GIS Cut Line= 4
      3497999.85     10591021.71      3497416.11     10591234.37
      3497183.91     10591429.68      3496997.28     10591755.19
#Sta/Elev= 30
  4208.1   504.7  4277.9  502.77  4354.7  501.03  4369.6  500.94  4425.4  499.44
    4525  496.06  4634.1   493.8  4659.4  493.61  4715.2  492.37  4720.5  492.01
  4859.1  489.37  4894.2  488.13  4915.1  486.94  4937.1  486.55  4978.8  484.35
  5004.4  484.19  5007.1  483.69  5010.4  484.19  5021.7  484.55  5050.3  484.36
  5064.6     485  5085.4  487.61  5121.8  488.54  5224.2  489.45  5283.2  490.81
  5310.5  492.02  5332.1  492.35  5428.5     493  5444.3  493.37    5508  493.53
#Mann= 3 ,-1 , 0
  4208.1     .05       0  5004.4     .03       0  5010.4     .05       0
Bank Sta=5004.4,5010.4
XS Rating Curve= 0 ,0
Exp/Cntr=0.3,0.1

Type RM Length L Ch R = 1 ,1054    ,712,712,712
BEGIN DESCRIPTION:
UNT00955 IN CHRS 2.0
END DESCRIPTION:
XS GIS Cut Line= 4
      3497715.55     10590939.24      3497233.82     10591039.05
      3496921.32     10591384.11      3496877.93     10591661.84
#Sta/Elev= 30
    4314  498.58  4351.9  498.28    4397  497.42  4402.1  497.61  4429.9   496.8
  4460.5  496.86  4497.3  495.75  4597.6  494.14  4793.2  489.13  4887.1  487.09
  4936.4  484.89  4964.8  484.45  4993.2  482.57  5049.9  482.48  5067.9  482.01
  5070.6  481.51  5073.9  482.01  5092.5  482.32  5134.4  482.26  5141.9  483.82
  5148.6  484.48    5156   486.2  5170.2  487.42  5184.4  487.83    5227  487.69
  5271.5  488.32  5319.6   489.6  5410.7  491.26  5489.9  492.36  5552.6  492.49
#Mann= 3 ,-1 , 0
    4314     .05       0  5067.9     .03       0  5073.9     .05       0
Bank Sta=5067.9,5073.9
XS Rating Curve= 0 ,0
Exp/Cntr=0.3,0.1

Type RM Length L Ch R = 1 ,342     ,0,0,0
BEGIN DESCRIPTION:
UNT00955 IN CHRS 1.0
END DESCRIPTION:
XS GIS Cut Line= 4
      3497390.04     10590372.84      3496964.72      10590607.2
      3496752.05     10590778.64      3496754.22     10591212.66
#Sta/Elev= 30
  4344.1  498.96  4393.3  497.82  4436.8  496.05  4512.5  493.99  4730.3  485.24
  4762.4  484.57  4827.8  482.28  4877.3  481.32  4934.9  478.91  4941.3  479.02
  4955.7     478  4984.5  477.65  4998.6  476.09  5005.3  477.33  5012.9  477.05
  5026.1  478.07  5048.4  478.64  5054.9  479.25  5062.8  479.38  5069.3  480.22
  5083.6  480.91  5090.1  481.57    5098  481.62  5101.3   482.2  5185.9  484.22
  5275.9  485.51  5425.9  486.55  5485.9  487.55  5505.9  487.36  5536.9  487.86
#Mann= 3 , 0 , 0
  4344.1     .05       0  4984.5     .03       0  5005.3     .05       0
Bank Sta=4984.5,5005.3
XS Rating Curve= 0 ,0
Exp/Cntr=0.3,0.1

Chan Stop Cuts=-1
Use User Specified Reach Order=0
Composite Channel Slope=5