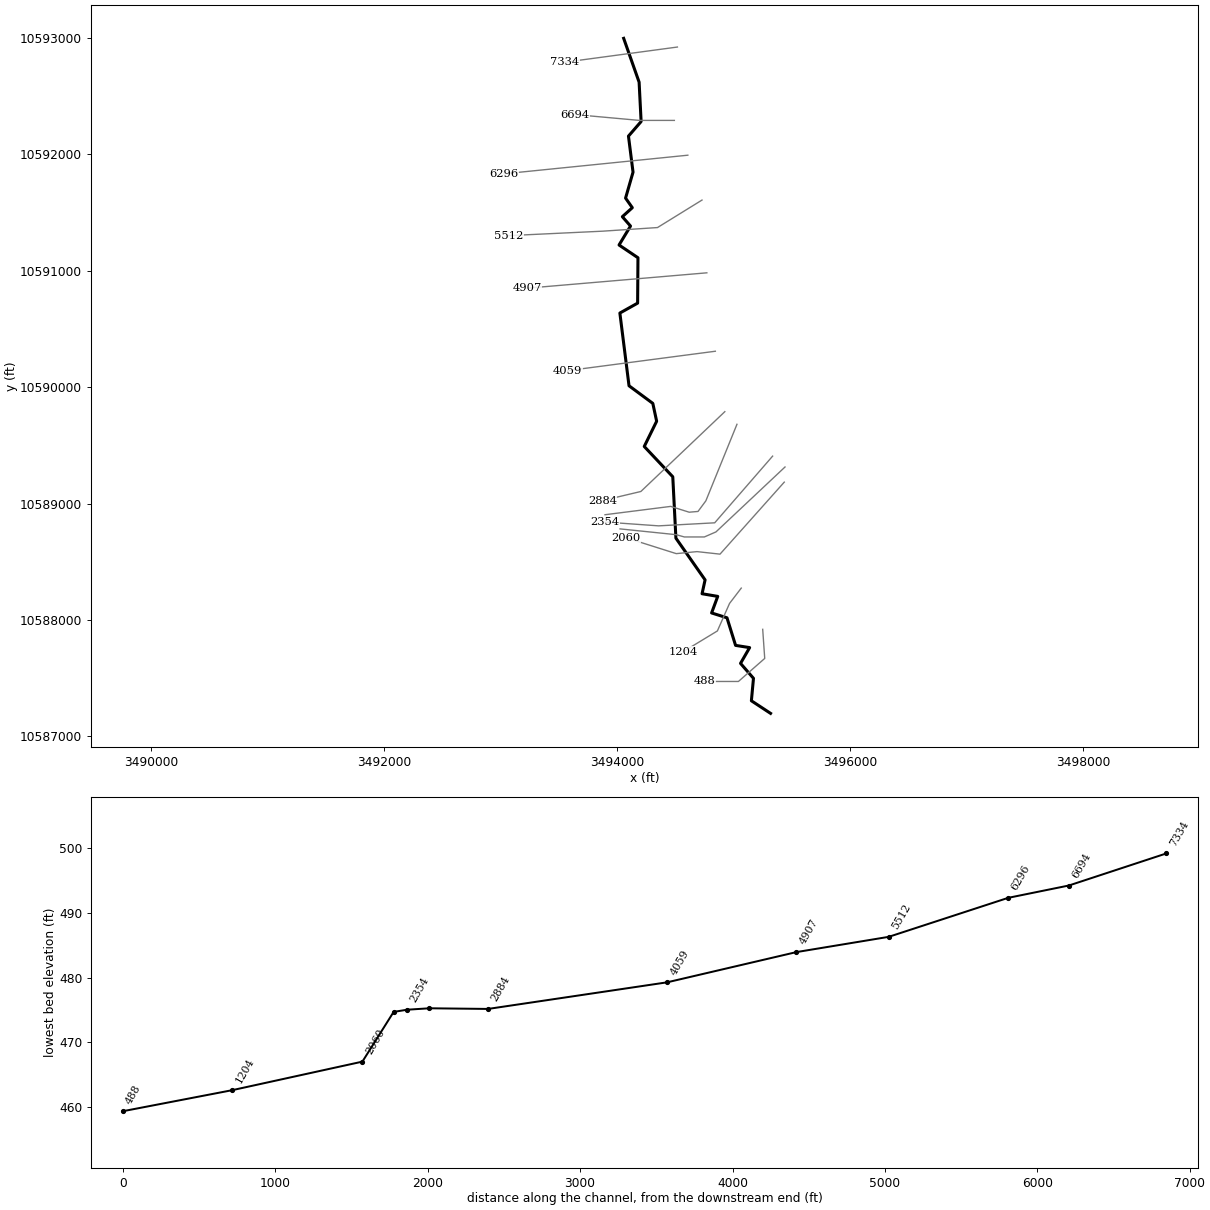
--- UNT00957 IN CHRS.prj (project) ---

Proj Title=UNT00957 IN CHRS Base Level Engineering
Current Plan=p01
Default Exp/Contr=0.3,0.1
English Units
Geom File=g01
Flow File=f01
Plan File=p01
BEGIN DESCRIPTION:
UNT00957 IN CHRS
END DESCRIPTION:

--- UNT00957 IN CHRS.p01 (plan) ---

Plan Title=Multiple Run
Short Identifier=Multiple
Geom File=g01
Flow File=f01
Subcritical Flow
K Sum by GR= 0
Std Step Tol= 0.01
Critical Tol= 0.01
Num of Std Step Trials= 20
Max Error Tol= 0.3
Flow Tol Ratio= 0.001
Split Flow NTrial= 30
Split Flow Tol= 0.02
Split Flow Ratio= 0.02
Log Output Level= 0
Friction Slope Method= 1
Unsteady Friction Slope Method= 2
Unsteady Bridges Friction Slope Method= 1
Parabolic Critical Depth
Global Vel Dist=  1 , 1 , 1
Global Log Level= 0
CheckData=True
Encroach Param= -1, 0, 0, 0
BEGIN DESCRIPTION:
Multiple Run
END DESCRIPTION:

--- UNT00957 IN CHRS.f01 (steady flow) ---

Flow Title=Multiple
Number of Profiles=7
Profile Names=10-year,25-year,50-year,1pct_min,100-year,1pct_plu,500-year
River Rch & RM= UNT00957 IN CHRS,Reach-1,7334
     216     259     289     236     319     431     386
Boundary for River Rch & Prof#=UNT00957 IN CHRS,Reach-1,1
Up Type=0
Dn Type=3
Dn Slope=0.005
Boundary for River Rch & Prof#=UNT00957 IN CHRS,Reach-1,2
Up Type=0
Dn Type=3
Dn Slope=0.005
Boundary for River Rch & Prof#=UNT00957 IN CHRS,Reach-1,3
Up Type=0
Dn Type=3
Dn Slope=0.005
Boundary for River Rch & Prof#=UNT00957 IN CHRS,Reach-1,4
Up Type=0
Dn Type=3
Dn Slope=0.005
Boundary for River Rch & Prof#=UNT00957 IN CHRS,Reach-1,5
Up Type=0
Dn Type=3
Dn Slope=0.005
Boundary for River Rch & Prof#=UNT00957 IN CHRS,Reach-1,6
Up Type=0
Dn Type=3
Dn Slope=0.005
Boundary for River Rch & Prof#=UNT00957 IN CHRS,Reach-1,7
Up Type=0
Dn Type=3
Dn Slope=0.005

--- UNT00957 IN CHRS.g01 (geometry) ---

Geom Title=Existing Conditions

River Reach=UNT00957 IN CHRS,Reach-1
Reach XY= 30
      3494057.11     10592996.64      3494189.61     10592620.23
      3494206.85     10592281.93      3494098.29     10592156.64
      3494137.47     10591847.06      3494073.41     10591624.15
      3494131.36     10591541.74      3494045.71     10591464.44
      3494115.84     10591383.98      3494017.37     10591221.29
      3494179.76     10591111.80      3494176.84     10590721.98
      3494024.51     10590636.69      3494103.07     10590011.94
      3494307.20     10589860.81      3494340.07     10589707.43
      3494233.70     10589490.63      3494478.57     10589230.18
      3494505.35     10588703.09      3494755.78     10588344.62
      3494729.81     10588225.56      3494864.18     10588202.83
      3494811.66     10588060.54      3494943.60     10588018.87
      3495017.39     10587781.89      3495138.05     10587762.79
      3495059.92     10587627.38      3495171.03     10587498.91
      3495153.07     10587306.11      3495317.59     10587197.85

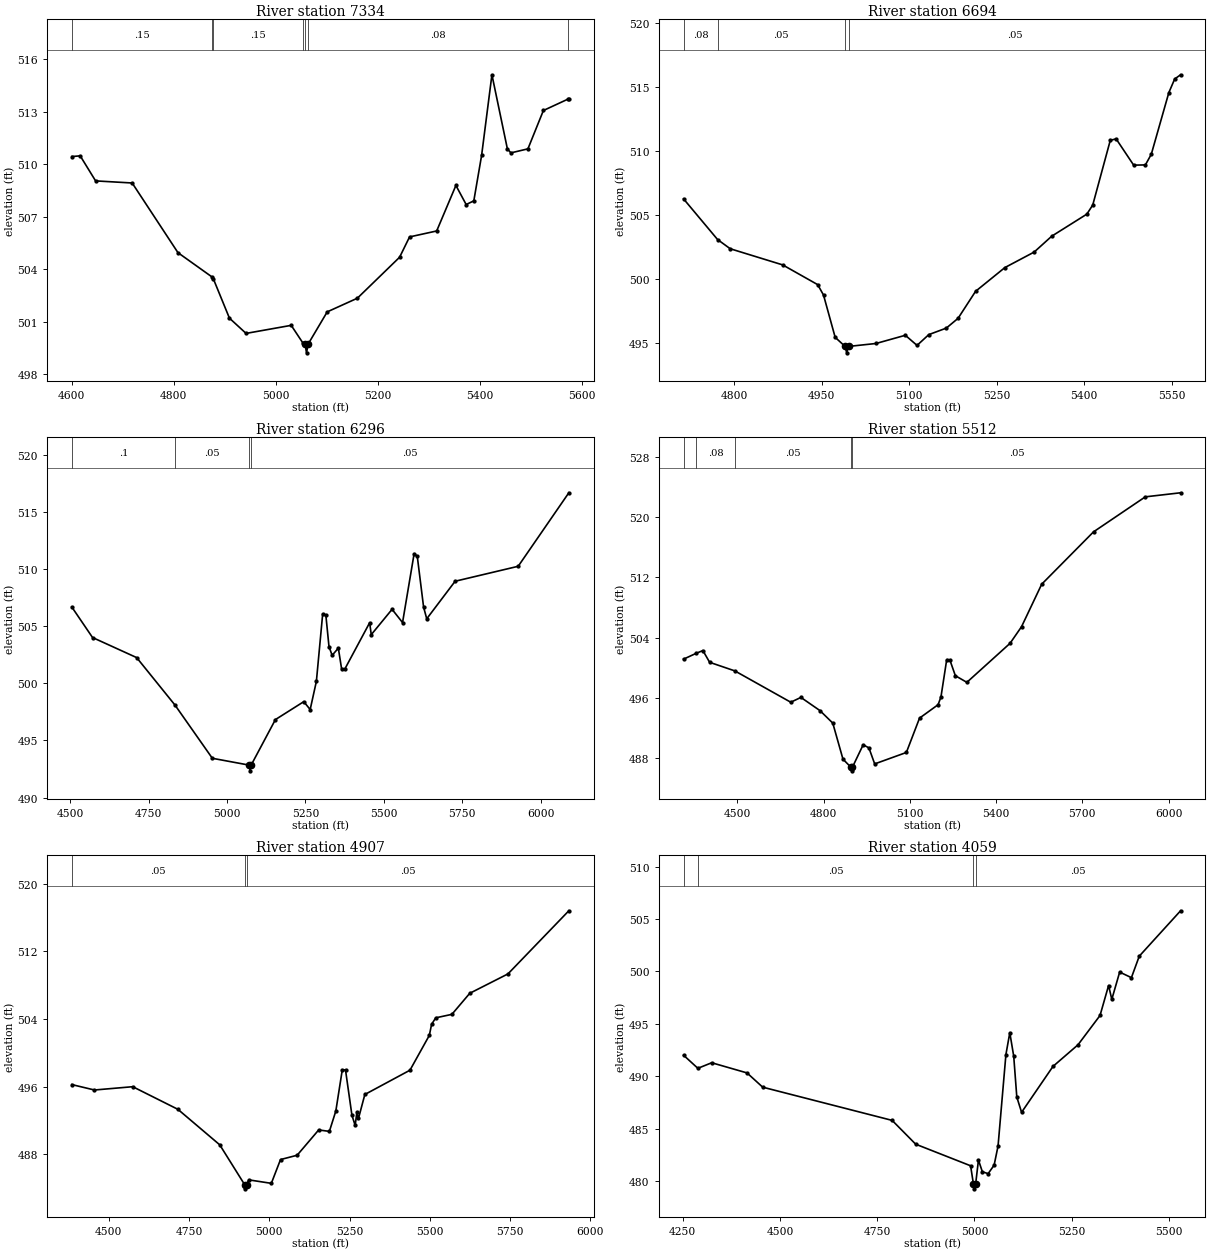
Type RM Length L Ch R = 1,7334,640,640,640
BEGIN DESCRIPTION:
UNT00957 IN CHRS 14.5
END DESCRIPTION:
XS GIS Cut Line= 2
      3494518.32     10592921.92      3493552.66     10592791.72
#Sta/Elev= 30
  4600.5  510.43  4616.9  510.47  4647.1  509.04  4718.8  508.92  4808.6  504.94
  4876.0  503.54  4877.9  503.45  4909.5  501.20  4942.1  500.33  5030.6  500.79
  5053.1  499.80  5057.8  499.72  5060.6  499.22  5063.8  499.72  5101.2  501.56
  5160.3  502.34  5243.1  504.68  5262.6  505.84  5315.8  506.18  5353.5  508.78
  5373.6  507.69  5388.6  507.90  5403.9  510.50  5424.1  515.10  5454.4  510.87
  5461.3  510.64  5494.7  510.87  5525.0  513.06  5572.5  513.70  5574.9  513.70
#Mann=7,-1,0
  4600.5    0.15       0  4876.0    0.08       0  4877.9    0.15       0
  5053.1    0.08       0  5057.8    0.07       0  5063.8    0.08       0
  5572.5     0.1       0
Bank Sta=5057.8,5063.8
Exp/Cntr=0.3,0.1

Type RM Length L Ch R = 1,6694,398,398,398
BEGIN DESCRIPTION:
UNT00957 IN CHRS 14.0
END DESCRIPTION:
XS GIS Cut Line= 3
      3494492.11     10592291.64      3494192.11     10592291.64
      3493642.08     10592341.64
#Sta/Elev= 30
  4712.9  506.26  4771.2  503.09  4792.9  502.37  4882.9  501.11  4942.9  499.57
  4952.9  498.76  4972.9  495.46  4989.9  494.75  4992.7  494.25  4995.9  494.75
  5043.0  494.98  5093.2  495.62  5113.3  494.83  5133.4  495.67  5163.5  496.18
  5183.6  496.94  5213.7  499.05  5263.9  500.90  5314.1  502.11  5344.3  503.35
  5404.5  505.07  5414.6  505.78  5444.7  510.83  5454.7  510.94  5484.8  508.89
  5504.9  508.91  5515.0  509.74  5545.1  514.55  5555.1  515.61  5565.2  515.94
#Mann=4,-1,0
  4712.9    0.08       0  4771.2    0.05       0  4989.9   0.035       0
  4995.9    0.05       0
Bank Sta=4989.9,4995.9
Exp/Cntr=0.3,0.1

Type RM Length L Ch R = 1,6296,784,784,784
BEGIN DESCRIPTION:
UNT00957 IN CHRS 13.0
END DESCRIPTION:
XS GIS Cut Line= 2
      3494607.76     10591992.75      3493031.43     10591833.04
#Sta/Elev= 30
  4505.5  506.69  4571.5  504.02  4712.2  502.26  4834.4  498.10  4953.4  493.44
  5071.1  492.84  5073.8  492.34  5077.1  492.84  5154.5  496.83  5244.9  498.40
  5265.3  497.71  5285.1  500.18  5305.2  506.09  5315.3  505.98  5325.3  503.22
  5335.4  502.46  5355.1  503.09  5365.5  501.27  5375.6  501.25  5455.0  505.32
  5460.0  504.27  5526.4  506.49  5559.8  505.33  5596.7  511.37  5606.8  511.12
  5626.9  506.68  5636.9  505.66  5727.4  508.95  5928.4  510.26  6089.9  516.70
#Mann=4,-1,0
  4505.5     0.1       0  4834.4    0.05       0  5071.1   0.035       0
  5077.1    0.05       0
Bank Sta=5071.1,5077.1
Exp/Cntr=0.3,0.1

Type RM Length L Ch R = 1,5512,605,605,605
BEGIN DESCRIPTION:
UNT00957 IN CHRS 11.0
END DESCRIPTION:
XS GIS Cut Line= 4
      3494729.32     10591607.33      3494347.39     10591371.23
      3493875.17     10591339.98      3493069.65     10591301.79
#Sta/Elev= 30
  4312.9  501.13  4357.7  501.92  4380.2  502.27  4403.6  500.71  4491.3  499.57
  4685.8  495.41  4721.1  496.05  4787.3  494.30  4831.9  492.64  4867.4  487.85
  4894.5  486.80  4897.3  486.30  4900.5  486.80  4937.6  489.76  4957.6  489.35
  4977.7  487.22  5087.9  488.74  5133.7  493.30  5198.2  495.08  5208.2  496.11
  5228.2  501.06  5239.2  501.02  5258.3  498.93  5298.3  498.05  5448.5  503.23
  5488.5  505.44  5558.6  511.08  5738.8  518.03  5919.0  522.68  6041.6  523.22
#Mann=5,-1,0
  4312.9    0.05       0  4357.7    0.08       0  4491.3    0.05       0
  4894.5   0.035       0  4900.5    0.05       0
Bank Sta=4894.5,4900.5
Exp/Cntr=0.3,0.1

Type RM Length L Ch R = 1,4907,848,848,848
BEGIN DESCRIPTION:
UNT00957 IN CHRS 10.0
END DESCRIPTION:
XS GIS Cut Line= 2
      3494770.97     10590982.34      3493229.31     10590850.39
#Sta/Elev= 30
  4385.4  496.26  4455.9  495.62  4575.0  496.01  4715.5  493.34  4845.9  489.14
  4923.3  484.44  4926.0  483.94  4929.3  484.44  4936.3  485.00  5006.5  484.59
  5035.1  487.40  5086.8  487.91  5153.9  490.90  5187.2  490.73  5207.3  493.14
  5227.3  497.98  5237.4  498.00  5257.4  492.64  5267.5  491.43  5272.8  492.98
  5277.8  492.26  5297.6  495.09  5438.1  497.96  5498.3  502.07  5505.5  503.39
  5518.4  504.15  5568.6  504.56  5624.3  507.05  5743.2  509.34  5932.7  516.80
#Mann=3,-1,0
  4385.4    0.05       0  4923.3   0.035       0  4929.3    0.05       0
Bank Sta=4923.3,4929.3
Exp/Cntr=0.3,0.1

Type RM Length L Ch R = 1,4059,1175,1175,1175
BEGIN DESCRIPTION:
UNT00957 IN CHRS 8.0
END DESCRIPTION:
XS GIS Cut Line= 2
      3494843.89     10590308.73      3493576.80     10590142.10
#Sta/Elev= 30
  4252.1  492.01  4288.9  490.76  4324.5  491.29  4415.3  490.32  4455.6  488.96
  4788.5  485.79  4849.0  483.52  4990.2  481.46  4997.3  479.76  5000.0  479.26
  5003.3  479.76  5010.4  482.01  5020.4  480.89  5035.3  480.71  5050.7  481.52
  5060.8  483.35  5081.0  492.07  5091.0  494.16  5101.1  491.91  5109.0  488.02
  5121.3  486.56  5202.0  490.94  5266.3  493.00  5323.0  495.80  5345.0  498.66
  5353.3  497.34  5373.5  499.94  5403.7  499.41  5423.9  501.46  5530.1  505.79
#Mann=4,-1,0
  4252.1    0.08       0  4288.9    0.05       0  4997.3   0.035       0
  5003.3    0.05       0
Bank Sta=4997.3,5003.3
Exp/Cntr=0.3,0.1

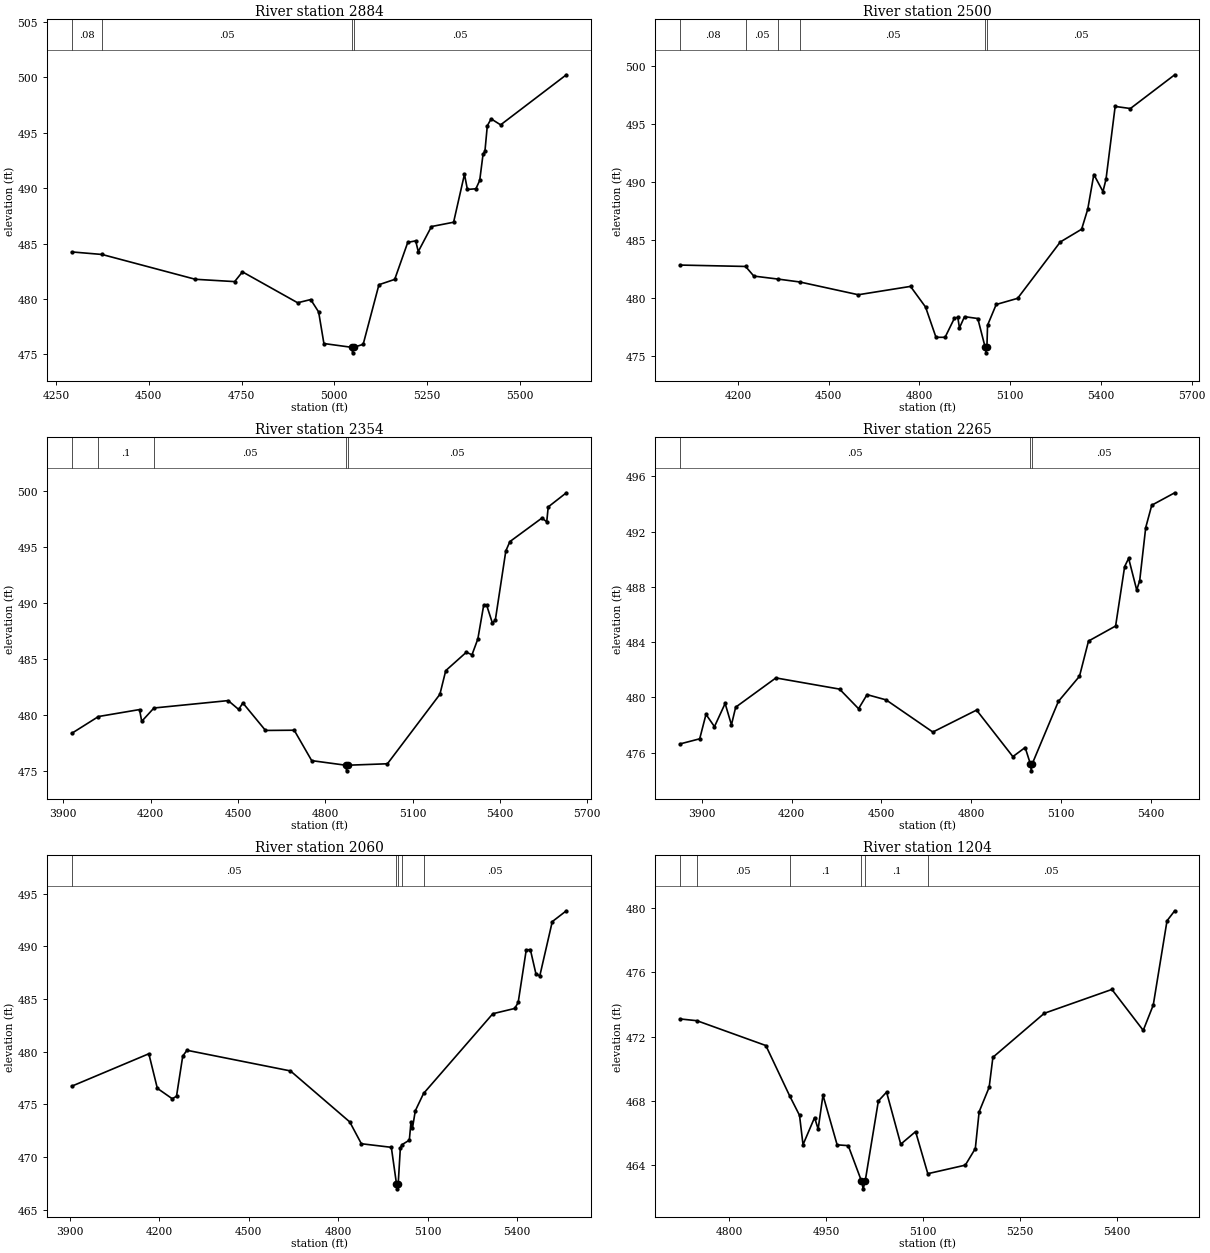
Type RM Length L Ch R = 1,2884,384,384,384
BEGIN DESCRIPTION:
UNT00957 IN CHRS 6.0
END DESCRIPTION:
XS GIS Cut Line= 3
      3494925.15     10589789.68      3494204.66     10589103.91
      3493874.77     10589025.78
#Sta/Elev= 30
  4292.0  484.25  4373.7  484.02  4625.3  481.78  4731.3  481.57  4752.4  482.45
  4901.2  479.66  4936.4  479.95  4957.8  478.83  4972.0  475.98  5046.6  475.64
  5049.4  475.14  5052.6  475.64  5077.9  475.91  5120.4  481.29  5162.9  481.77
  5198.1  485.11  5219.5  485.25  5226.4  484.28  5262.0  486.54  5321.7  486.93
  5351.0  491.26  5358.9  489.89  5381.8  489.95  5392.1  490.70  5401.1  493.07
  5406.2  493.34  5412.6  495.64  5422.9  496.26  5448.5  495.72  5625.7  500.24
#Mann=4,-1,0
  4292.0    0.08       0  4373.7    0.05       0  5046.6   0.035       0
  5052.6    0.05       0
Bank Sta=5046.6,5052.6
Exp/Cntr=0.3,0.1

Type RM Length L Ch R = 1,2500,146,146,146
BEGIN DESCRIPTION:
UNT00957 IN CHRS 4.9
END DESCRIPTION:
XS GIS Cut Line= 6
      3495029.32     10589681.20      3494762.38     10589023.61
      3494695.11     10588932.47      3494619.16     10588925.96
      3494460.74     10588975.87      3493896.79     10588904.29
#Sta/Elev= 30
  4008.6  482.81  4225.2  482.69  4252.4  481.86  4332.8  481.60  4404.7  481.35
  4597.9  480.25  4770.5  480.97  4820.2  479.19  4854.7  476.58  4884.8  476.58
  4915.7  478.23  4926.8  478.30  4932.3  477.39  4949.0  478.36  4992.9  478.20
  5017.1  475.74  5019.9  475.24  5023.1  475.74  5025.2  477.62  5053.8  479.41
  5124.6  479.94  5265.7  484.80  5336.2  485.90  5356.4  487.62  5376.6  490.62
  5406.8  489.15  5416.9  490.22  5447.1  496.49  5497.5  496.31  5644.0  499.22
#Mann=6,-1,0
  4008.6    0.08       0  4225.2    0.05       0  4332.8    0.08       0
  4404.7    0.05       0  5017.1   0.033       0  5023.1    0.05       0
Bank Sta=5017.1,5023.1
Exp/Cntr=0.3,0.1

Type RM Length L Ch R = 1,2354,89,89,89
BEGIN DESCRIPTION:
UNT00957 IN CHRS 4.4
END DESCRIPTION:
XS GIS Cut Line= 4
      3495335.30     10589407.73      3494838.34     10588834.81
      3494356.57     10588808.77      3493898.62     10588841.33
#Sta/Elev= 30
  3928.7  478.36  4020.7  479.86  4161.8  480.48  4169.3  479.43  4211.3  480.62
  4466.5  481.28  4502.6  480.49  4516.9  481.07  4594.7  478.62  4693.4  478.64
  4753.5  475.93  4870.6  475.52  4873.4  475.02  4876.6  475.52  5013.8  475.65
  5194.1  481.84  5214.2  483.95  5285.0  485.59  5304.4  485.36  5324.5  486.77
  5344.5  489.76  5354.5  489.80  5374.6  488.19  5384.6  488.45  5420.7  494.62
  5434.7  495.45  5545.0  497.55  5561.3  497.21  5566.4  498.54  5628.7  499.80
#Mann=5,-1,0
  3928.7    0.05       0  4020.7     0.1       0  4211.3    0.05       0
  4870.6   0.033       0  4876.6    0.05       0
Bank Sta=4870.6,4876.6
Exp/Cntr=0.3,0.1

Type RM Length L Ch R = 1,2265,205,205,205
BEGIN DESCRIPTION:
UNT00957 IN CHRS 4.6
END DESCRIPTION:
XS GIS Cut Line= 6
      3495441.66     10589314.43      3494849.19     10588756.69
      3494749.36     10588713.28      3494577.92     10588713.28
      3494508.48     10588732.82      3494025.87     10588782.59
#Sta/Elev= 30
  3827.6  476.63  3893.1  477.00  3914.1  478.77  3942.4  477.88  3978.0  479.56
  3999.1  478.01  4013.2  479.29  4147.5  481.41  4360.0  480.60  4423.5  479.18
  4451.8  480.20  4515.3  479.82  4671.4  477.49  4817.4  479.08  4938.6  475.71
  4979.6  476.37  4997.1  475.18  4999.9  474.68  5003.1  475.18  5090.6  479.71
  5161.0  481.53  5191.1  484.08  5281.6  485.17  5311.8  489.48  5325.1  490.07
  5352.0  487.78  5362.0  488.45  5382.1  492.30  5402.3  493.92  5478.9  494.82
#Mann=3,-1,0
  3827.6    0.05       0  4997.1   0.035       0  5003.1    0.05       0
Bank Sta=4997.1,5003.1
Exp/Cntr=0.3,0.1

Type RM Length L Ch R = 1,2060,856,856,856
BEGIN DESCRIPTION:
UNT00957 IN CHRS 4.5
END DESCRIPTION:
XS GIS Cut Line= 5
      3495435.16     10589184.24      3494883.91     10588565.72
      3494686.43     10588587.42      3494508.48     10588570.06
      3494077.06     10588706.63
#Sta/Elev= 30
  3907.0  476.72  4165.6  479.80  4194.1  476.52  4244.2  475.53  4258.4  475.77
  4279.3  479.58  4293.5  480.13  4640.5  478.17  4839.3  473.33  4878.2  471.26
  4978.7  470.92  4995.8  467.48  4998.6  466.98  5001.8  467.48  5008.9  470.87
  5014.9  471.18  5039.0  471.60  5044.6  473.31  5049.6  472.76  5059.1  474.39
  5086.7  476.03  5319.0  483.60  5392.4  484.10  5404.0  484.67  5431.0  489.65
  5444.8  489.69  5463.3  487.41  5476.3  487.17  5518.3  492.34  5565.5  493.37
#Mann=5,-1,0
  3907.0    0.05       0  4995.8   0.035       0  5001.8    0.05       0
  5014.9     0.1       0  5086.7    0.05       0
Bank Sta=4995.8,5001.8
Exp/Cntr=0.3,0.1

Type RM Length L Ch R = 1,1204,716,716,716
BEGIN DESCRIPTION:
UNT00957 IN CHRS 2.0
END DESCRIPTION:
XS GIS Cut Line= 4
      3495066.17     10588274.04      3494965.45     10588142.06
      3494861.28     10587905.95      3494569.61     10587728.87
#Sta/Elev= 30
  4724.4  473.09  4750.5  472.98  4857.1  471.44  4893.8  468.33  4909.2  467.11
  4914.6  465.29  4932.5  466.97  4938.0  466.26  4945.5  468.36  4967.4  465.28
  4984.6  465.23  5004.9  463.05  5007.7  462.55  5010.9  463.05  5031.2  468.00
  5043.9  468.55  5065.8  465.32  5088.8  466.10  5107.7  463.49  5165.7  464.02
  5181.2  465.05  5187.1  467.33  5202.6  468.85  5208.4  470.71  5287.9  473.44
  5392.5  474.92  5441.0  472.38  5456.5  473.95  5477.8  479.18  5489.7  479.80
#Mann=6,-1,0
  4724.4     0.1       0  4750.5    0.05       0  4893.8     0.1       0
  5004.9    0.07       0  5010.9     0.1       0  5107.7    0.05       0
Bank Sta=5004.9,5010.9
Exp/Cntr=0.3,0.1

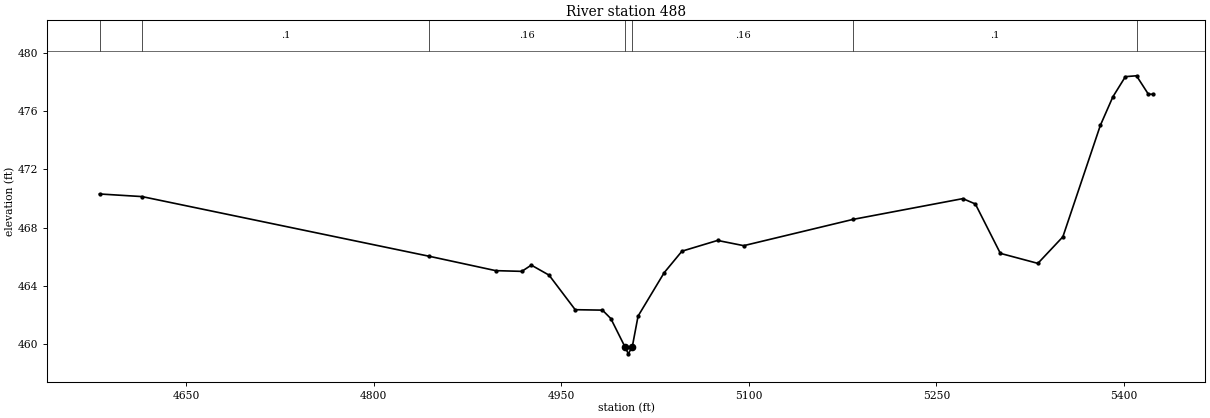
Type RM Length L Ch R = 1,488,0,0,0
BEGIN DESCRIPTION:
UNT00957 IN CHRS 1.0
END DESCRIPTION:
XS GIS Cut Line= 4
      3495250.17     10587919.89      3495267.53     10587669.84
      3495041.84     10587471.93      3494750.16     10587471.93
#Sta/Elev= 30
  4580.6  470.31  4614.6  470.13  4844.3  466.02  4897.5  465.03  4918.4  464.98
  4926.0  465.41  4940.2  464.72  4961.1  462.34  4982.9  462.31  4989.6  461.73
  5000.8  459.80  5003.6  459.30  5006.8  459.80  5011.4  461.90  5032.3  464.89
  5046.5  466.37  5075.0  467.11  5095.9  466.75  5183.4  468.56  5271.2  469.99
  5281.2  469.62  5301.2  466.22  5331.2  465.53  5351.2  467.36  5381.2  475.04
  5391.2  477.00  5401.2  478.39  5410.1  478.45  5419.6  477.18  5423.1  477.18
#Mann=7,-1,0
  4580.6    0.16       0  4614.6     0.1       0  4844.3    0.16       0
  5000.8    0.07       0  5006.8    0.16       0  5183.4     0.1       0
  5410.1    0.05       0
Bank Sta=5000.8,5006.8
Exp/Cntr=0.3,0.1

Chan Stop Cuts=-1