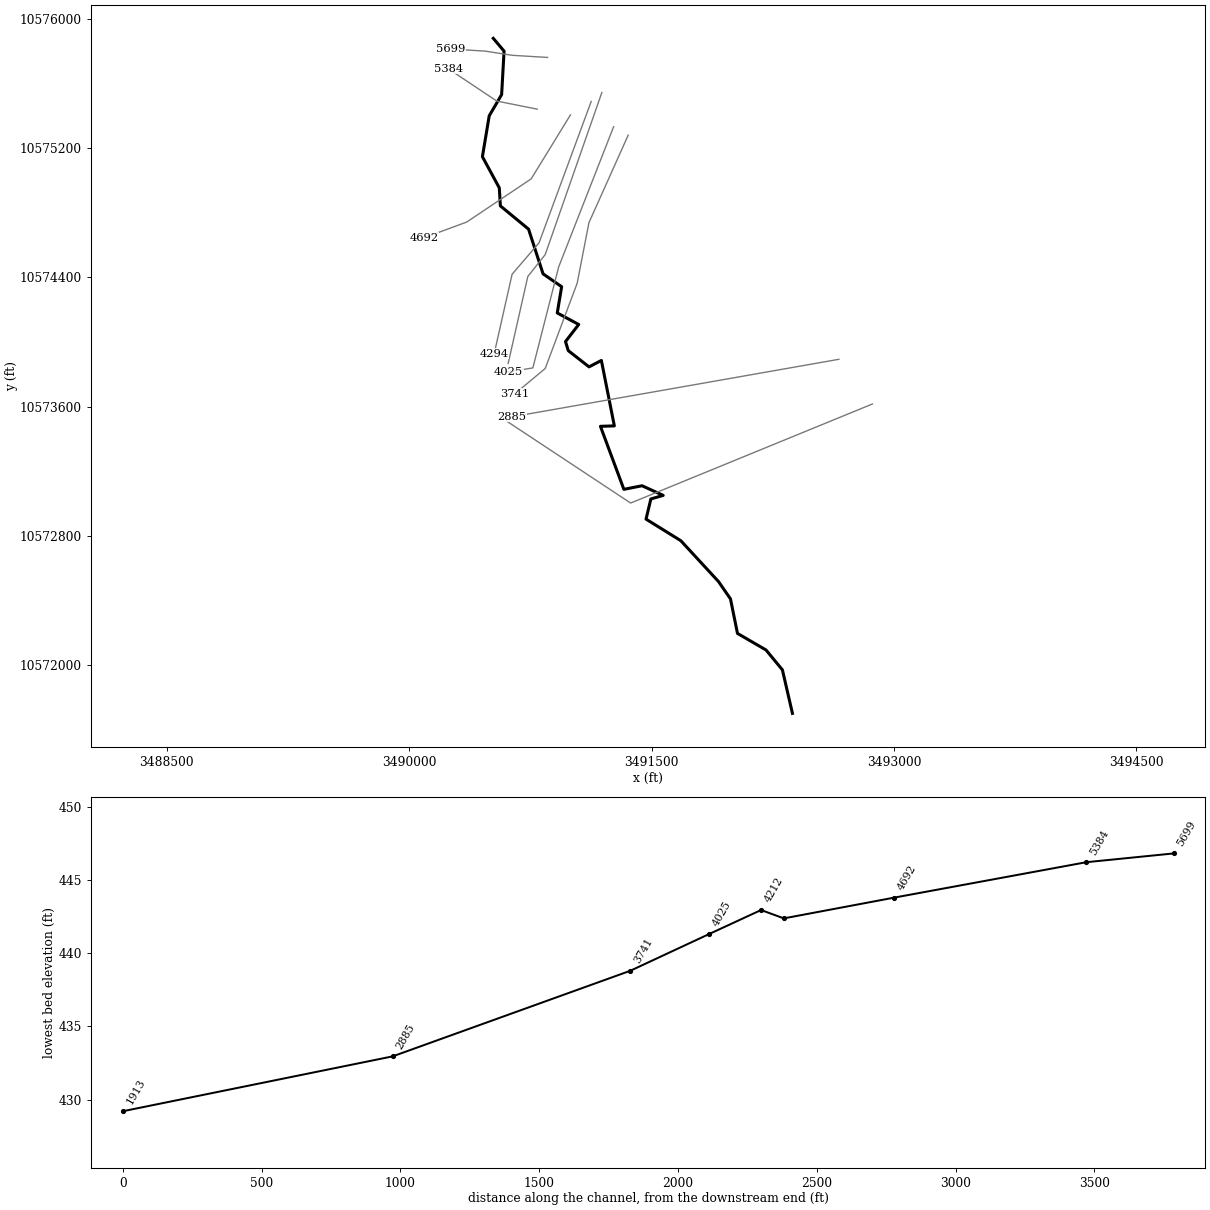
--- UNT00975 IN CHRS.prj (project) ---

Proj Title=UNT00975 IN CHRS Base Level Engineering
Current Plan=p01
Default Exp/Contr=0.3,0.1
English Units
Geom File=g01
Flow File=f01
Plan File=p01
BEGIN DESCRIPTION:
UNT00975 IN CHRS
END DESCRIPTION:

--- UNT00975 IN CHRS.p01 (plan) ---

Plan Title=Multiple Run
Short Identifier=Multiple
Geom File=g01
Flow File=f01
Subcritical Flow
K Sum by GR= 0
Std Step Tol= 0.01
Critical Tol= 0.01
Num of Std Step Trials= 20
Max Error Tol= 0.3
Flow Tol Ratio= 0.001
Split Flow NTrial= 30
Split Flow Tol= 0.02
Split Flow Ratio= 0.02
Log Output Level= 0
Friction Slope Method= 1
Unsteady Friction Slope Method= 2
Unsteady Bridges Friction Slope Method= 1
Parabolic Critical Depth
Global Vel Dist=  1 , 1 , 1
Global Log Level= 0
CheckData=True
Encroach Param= -1, 0, 0, 0
BEGIN DESCRIPTION:
Multiple Run
END DESCRIPTION:

--- UNT00975 IN CHRS.f01 (steady flow) ---

Flow Title=Multiple
Number of Profiles=7
Profile Names=10-year,25-year,50-year,1pct_min,100-year,1pct_plu,500-year
River Rch & RM= UNT00975 IN CHRS,Reach-1,5699
     331     409     465     385     521     704     651
Boundary for River Rch & Prof#=UNT00975 IN CHRS,Reach-1,1
Up Type=0
Dn Type=3
Dn Slope=0.005
Boundary for River Rch & Prof#=UNT00975 IN CHRS,Reach-1,2
Up Type=0
Dn Type=3
Dn Slope=0.005
Boundary for River Rch & Prof#=UNT00975 IN CHRS,Reach-1,3
Up Type=0
Dn Type=3
Dn Slope=0.005
Boundary for River Rch & Prof#=UNT00975 IN CHRS,Reach-1,4
Up Type=0
Dn Type=3
Dn Slope=0.005
Boundary for River Rch & Prof#=UNT00975 IN CHRS,Reach-1,5
Up Type=0
Dn Type=3
Dn Slope=0.005
Boundary for River Rch & Prof#=UNT00975 IN CHRS,Reach-1,6
Up Type=0
Dn Type=3
Dn Slope=0.005
Boundary for River Rch & Prof#=UNT00975 IN CHRS,Reach-1,7
Up Type=0
Dn Type=3
Dn Slope=0.005

--- UNT00975 IN CHRS.g01 (geometry) ---

Geom Title=Existing Conditions

River Reach=UNT00975 IN CHRS,Reach-1
Reach XY= 30
      3490520.37     10575879.92      3490587.18     10575800.81
      3490572.06     10575531.60      3490495.26     10575400.35
      3490453.10     10575147.16      3490557.60     10574954.63
      3490564.32     10574842.72      3490738.81     10574698.89
      3490828.51     10574422.08      3490943.50     10574342.64
      3490916.41     10574180.14      3491049.23     10574108.79
      3490967.45     10574003.06      3490984.64     10573946.81
      3491113.04     10573846.37      3491189.47     10573886.15
      3491269.75     10573481.09      3491183.70     10573478.44
      3491328.73     10573088.35      3491441.36     10573110.59
      3491572.08     10573050.91      3491495.79     10573028.79
      3491465.87     10572903.93      3491681.10     10572770.51
      3491914.25     10572517.85      3491988.58     10572410.12
      3492031.93     10572196.61      3492208.58     10572094.01
      3492310.03     10571970.80      3492372.11     10571701.64

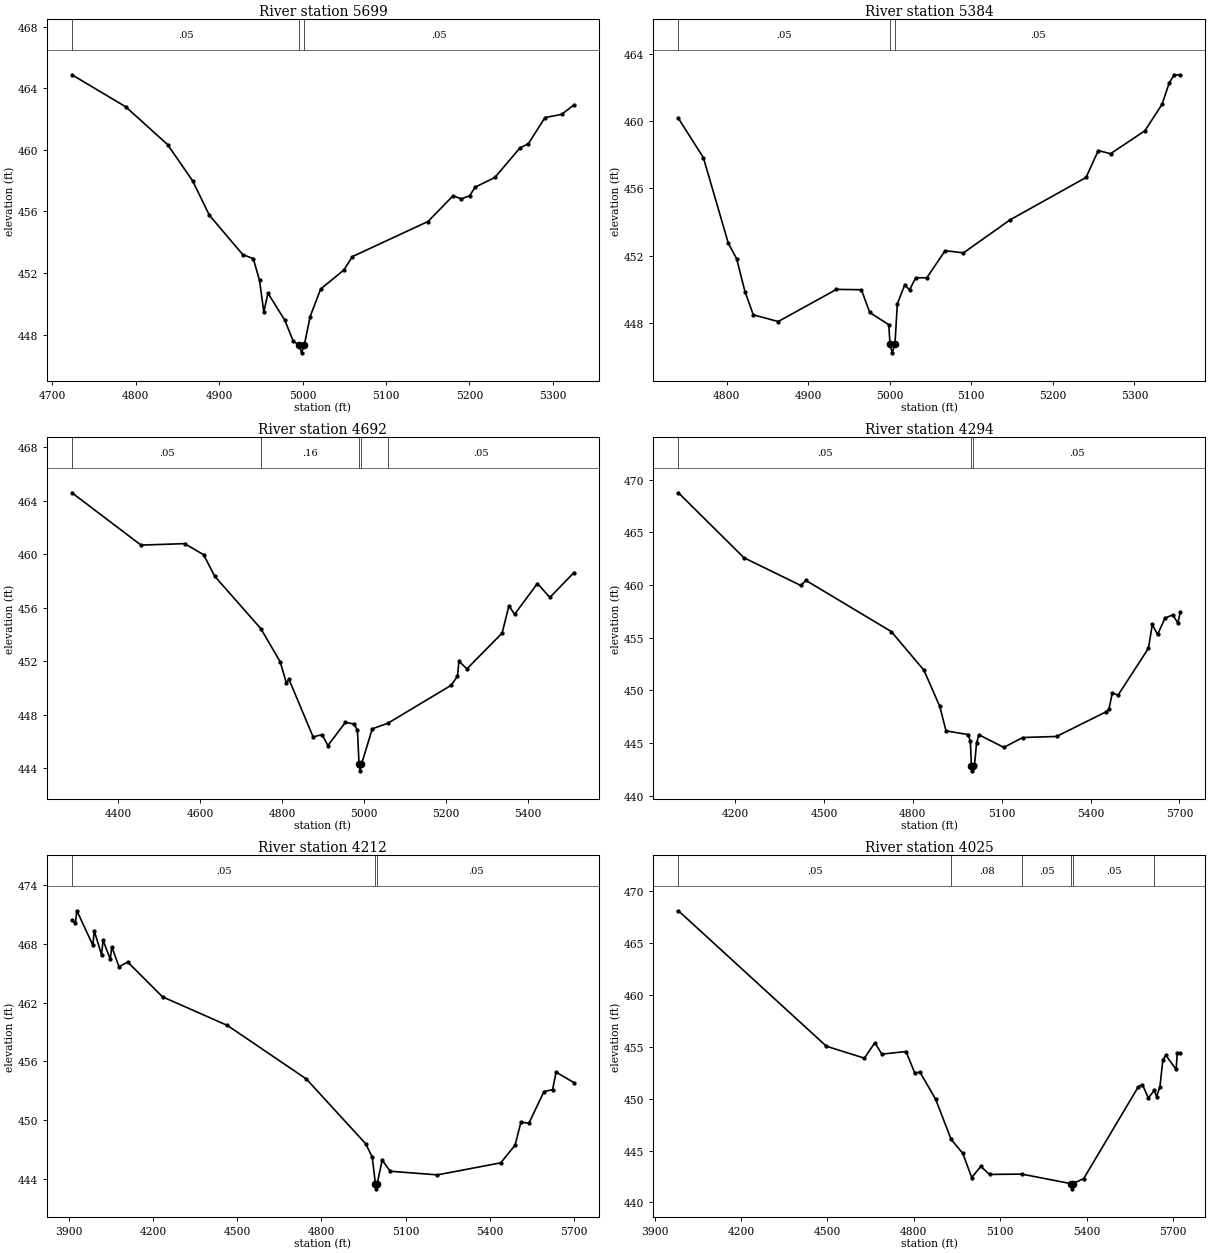
Type RM Length L Ch R = 1,5699,315,315,315
BEGIN DESCRIPTION:
UNT00975 IN CHRS 7.1
END DESCRIPTION:
XS GIS Cut Line= 4
      3490856.50     10575761.71      3490639.49     10575774.73
      3490470.22     10575800.77      3490257.58     10575813.79
#Sta/Elev= 30
  4723.6  464.88  4788.1  462.80  4838.2  460.35  4868.3  457.99  4888.3  455.76
  4928.4  453.20  4941.0  452.94  4948.5  451.52  4953.6  449.48  4958.6  450.69
  4978.8  448.94  4988.9  447.58  4996.1  447.32  4998.8  446.82  5002.1  447.32
  5009.2  449.18  5021.8  450.97  5049.6  452.20  5059.8  453.07  5150.4  455.35
  5180.5  457.02  5190.5  456.82  5200.5  457.03  5206.9  457.58  5230.6  458.21
  5260.7  460.13  5270.7  460.40  5290.7  462.10  5310.7  462.31  5325.3  462.92
#Mann=3,-1,0
  4723.6    0.05       0  4996.1   0.035       0  5002.1    0.05       0
Bank Sta=4996.1,5002.1
Exp/Cntr=0.3,0.1

Type RM Length L Ch R = 1,5384,692,692,692
BEGIN DESCRIPTION:
UNT00975 IN CHRS 7.0
END DESCRIPTION:
XS GIS Cut Line= 3
      3490792.14     10575441.64      3490542.11     10575491.64
      3490242.14     10575691.62
#Sta/Elev= 30
  4740.8  460.15  4771.4  457.82  4802.0  452.73  4812.2  451.81  4822.4  449.86
  4832.6  448.48  4863.2  448.08  4934.6  449.99  4965.2  449.97  4975.4  448.62
  4998.8  447.89  5000.3  446.72  5003.0  446.22  5006.3  446.72  5009.3  449.13
  5018.3  450.26  5024.3  449.96  5031.8  450.68  5045.4  450.68  5067.9  452.29
  5090.4  452.16  5147.5  454.12  5240.7  456.64  5255.7  458.24  5270.7  458.05
  5312.8  459.41  5333.8  460.98  5342.8  462.27  5348.8  462.73  5356.3  462.74
#Mann=3,-1,0
  4740.8    0.05       0  5000.3   0.035       0  5006.3    0.05       0
Bank Sta=5000.3,5006.3
Exp/Cntr=0.3,0.1

Type RM Length L Ch R = 1,4692,398,398,398
BEGIN DESCRIPTION:
UNT00975 IN CHRS 6.0
END DESCRIPTION:
XS GIS Cut Line= 4
      3490998.00     10575405.81      3490754.95     10575009.97
      3490355.64     10574742.61      3490093.42     10574646.00
#Sta/Elev= 30
  4287.7  464.58  4456.2  460.67  4562.7  460.78  4608.9  459.95  4636.1  458.34
  4748.7  454.42  4795.9  451.94  4810.9  450.35  4817.0  450.65  4876.0  446.34
  4898.0  446.50  4912.1  445.69  4955.0  447.43  4976.1  447.29  4984.3  446.83
  4988.1  444.30  4990.8  443.80  4994.1  444.30  5020.4  446.94  5058.6  447.36
  5213.2  450.20  5228.2  450.87  5231.9  451.99  5251.3  451.42  5337.3  454.10
  5353.7  456.13  5367.7  455.50  5423.3  457.80  5453.7  456.76  5512.2  458.61
#Mann=5,-1,0
  4287.7    0.05       0  4748.7    0.16       0  4988.1    0.07       0
  4994.1    0.16       0  5058.6    0.05       0
Bank Sta=4988.1,4994.1
Exp/Cntr=0.3,0.1

Type RM Length L Ch R = 1,4294,82,82,82
BEGIN DESCRIPTION:
UNT00975 IN CHRS 5.0
END DESCRIPTION:
XS GIS Cut Line= 4
      3491126.47     10575489.14      3490803.56     10574614.14
      3490636.89     10574419.69      3490525.78     10573926.65
#Sta/Elev= 30
  4008.7  468.75  4229.9  462.59  4421.7  459.96  4438.9  460.44  4727.2  455.59
  4837.5  451.92  4890.8  448.50  4912.1  446.17  4986.4  445.82  4994.1  445.20
  4997.7  442.88  5000.4  442.38  5003.7  442.88  5008.4  442.98  5014.9  444.98
  5022.6  445.81  5107.1  444.60  5170.8  445.54  5285.1  445.64  5451.8  447.97
  5462.0  448.24  5473.4  449.77  5492.8  449.56  5595.3  454.00  5608.3  456.26
  5626.0  455.31  5651.5  456.87  5677.3  457.17  5694.8  456.40  5702.9  457.46
#Mann=3,-1,0
  4008.7    0.05       0  4997.7   0.035       0  5003.7    0.05       0
Bank Sta=4997.7,5003.7
Exp/Cntr=0.3,0.1

Type RM Length L Ch R = 1,4212,187,187,187
BEGIN DESCRIPTION:
UNT00975 IN CHRS 5.1
END DESCRIPTION:
XS GIS Cut Line= 4
      3491192.44     10575544.67      3490841.75     10574541.22
      3490734.11     10574405.80      3490612.58     10573867.60
#Sta/Elev= 30
  3911.6  470.47  3923.9  470.13  3929.2  471.41  3986.0  467.89  3991.3  469.34
  4017.1  466.89  4022.4  468.39  4048.1  466.45  4053.4  467.73  4079.2  465.68
  4110.2  466.17  4234.4  462.60  4465.6  459.67  4746.3  454.20  4958.3  447.55
  4981.2  446.19  4992.6  443.45  4995.4  442.95  4998.6  443.45  5016.5  445.89
  5045.3  444.75  5213.3  444.38  5438.9  445.61  5490.1  447.43  5510.6  449.76
  5539.4  449.68  5592.9  452.91  5623.4  453.10  5636.1  454.89  5699.3  453.83
#Mann=3,-1,0
  3911.6    0.05       0  4992.6   0.035       0  4998.6    0.05       0
Bank Sta=4992.6,4998.6
Exp/Cntr=0.3,0.1

Type RM Length L Ch R = 1,4025,284,284,284
BEGIN DESCRIPTION:
UNT00975 IN CHRS 4.0
END DESCRIPTION:
XS GIS Cut Line= 5
      3491265.36     10575332.89      3490925.08     10574464.83
      3490765.36     10573839.83      3490609.11     10573815.53
      3490616.03     10573815.53
#Sta/Elev= 30
  3982.8  468.12  4496.5  455.06  4628.6  453.91  4664.6  455.40  4689.0  454.30
  4773.1  454.55  4802.9  452.51  4821.9  452.54  4875.6  449.96  4929.6  446.08
  4970.1  444.73  5001.0  442.40  5032.7  443.47  5063.0  442.70  5174.9  442.73
  5346.0  441.81  5348.8  441.31  5352.0  441.81  5389.9  442.30  5579.9  451.17
  5593.9  451.36  5614.2  450.07  5635.1  450.81  5642.8  450.20  5654.6  451.17
  5664.8  453.77  5674.9  454.19  5710.7  452.82  5714.8  454.42  5725.3  454.42
#Mann=6,-1,0
  3982.8    0.05       0  4929.6    0.08       0  5174.9    0.05       0
  5346.0    0.07       0  5352.0    0.05       0  5635.1    0.05       0
Bank Sta=5346,5352
Exp/Cntr=0.3,0.1

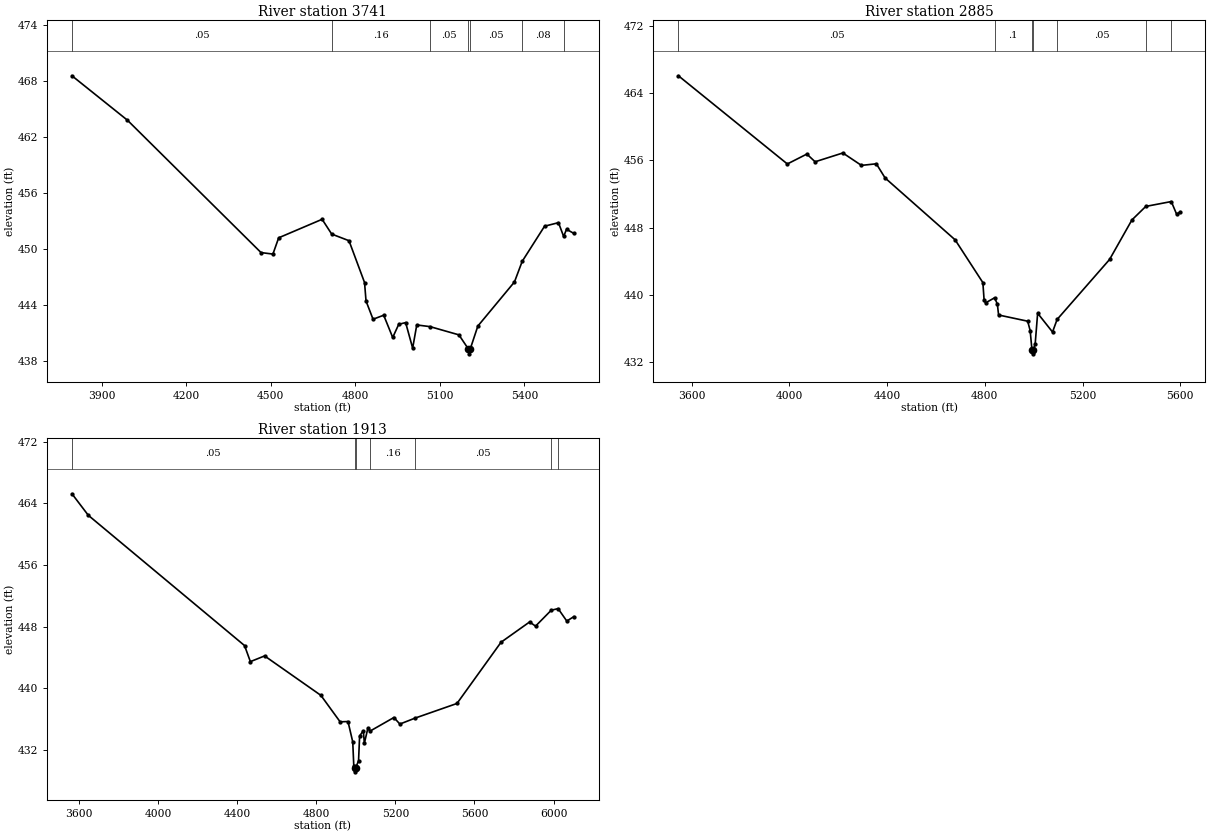
Type RM Length L Ch R = 1,3741,856,856,856
BEGIN DESCRIPTION:
UNT00975 IN CHRS 2.0
END DESCRIPTION:
XS GIS Cut Line= 5
      3491355.65     10575280.82      3491112.58     10574739.14
      3491039.67     10574364.14      3490841.75     10573836.36
      3490655.69     10573681.31
#Sta/Elev= 30
  3793.9  468.54  3990.8  463.79  4465.1  449.63  4507.3  449.47  4527.7  451.21
  4681.9  453.19  4715.9  451.61  4777.3  450.90  4832.5  446.43  4837.8  444.45
  4862.7  442.50  4900.5  442.93  4932.5  440.55  4953.9  441.96  4978.4  442.14
  5003.3  439.41  5017.9  441.89  5065.0  441.71  5167.5  440.83  5201.5  439.30
  5204.2  438.80  5207.5  439.30  5234.7  441.77  5364.7  446.49  5392.1  448.69
  5471.5  452.45  5520.9  452.83  5539.2  451.36  5549.6  452.12  5575.5  451.68
#Mann=7,-1,0
  3793.9    0.05       0  4715.9    0.16       0  5065.0    0.05       0
  5201.5    0.07       0  5207.5    0.05       0  5392.1    0.08       0
  5539.2    0.05       0
Bank Sta=5201.5,5207.5
Exp/Cntr=0.3,0.1

Type RM Length L Ch R = 1,2885,972,972,972
BEGIN DESCRIPTION:
UNT00975 IN CHRS 1.1
END DESCRIPTION:
XS GIS Cut Line= 2
      3492659.62     10573893.28      3490637.09     10573537.38
#Sta/Elev= 30
  3546.2  466.09  3991.9  455.58  4071.7  456.76  4105.5  455.84  4219.0  456.89
  4295.0  455.41  4356.0  455.60  4391.9  453.91  4678.3  446.54  4791.9  441.44
  4796.9  439.38  4802.7  439.02  4839.8  439.63  4851.2  438.88  4856.2  437.58
  4975.3  436.84  4985.5  435.71  4992.6  433.45  4995.4  432.95  4998.6  433.45
  5005.8  434.08  5016.0  437.79  5076.9  435.55  5095.7  437.05  5310.4  444.20
  5401.8  448.91  5458.5  450.52  5562.8  451.10  5584.6  449.60  5599.8  449.87
#Mann=7,-1,0
  3546.2    0.05       0  4839.8     0.1       0  4992.6    0.07       0
  4998.6     0.1       0  5095.7    0.05       0  5458.5    0.08       0
  5562.8    0.05       0
Bank Sta=4992.6,4998.6
Exp/Cntr=0.3,0.1

Type RM Length L Ch R = 1,1913,0,0,0
BEGIN DESCRIPTION:
UNT00975 IN CHRS 1.0
END DESCRIPTION:
XS GIS Cut Line= 3
      3492867.08     10573616.63      3491370.52     10573003.51
      3490602.27     10573511.33
#Sta/Elev= 30
  3564.7  465.23  3647.5  462.44  4437.6  445.56  4467.0  443.48  4539.0  444.22
  4823.6  439.11  4920.9  435.68  4960.7  435.72  4984.7  433.08  4990.1  429.93
  4993.6  429.70  4996.3  429.20  4999.6  429.70  5014.1  430.65  5019.5  433.85
  5038.1  434.53  5043.5  432.91  5061.4  434.87  5072.4  434.48  5192.9  436.24
  5223.0  435.39  5298.6  436.15  5511.9  438.06  5734.6  445.99  5879.1  448.62
  5909.2  448.08  5988.5  450.14  6023.3  450.35  6067.1  448.74  6102.9  449.31
#Mann=7,-1,0
  3564.7    0.05       0  4993.6   0.035       0  4999.6    0.05       0
  5072.4    0.16       0  5298.6    0.05       0  5988.5    0.08       0
  6023.3    0.05       0
Bank Sta=4993.6,4999.6
Exp/Cntr=0.3,0.1

Chan Stop Cuts=-1