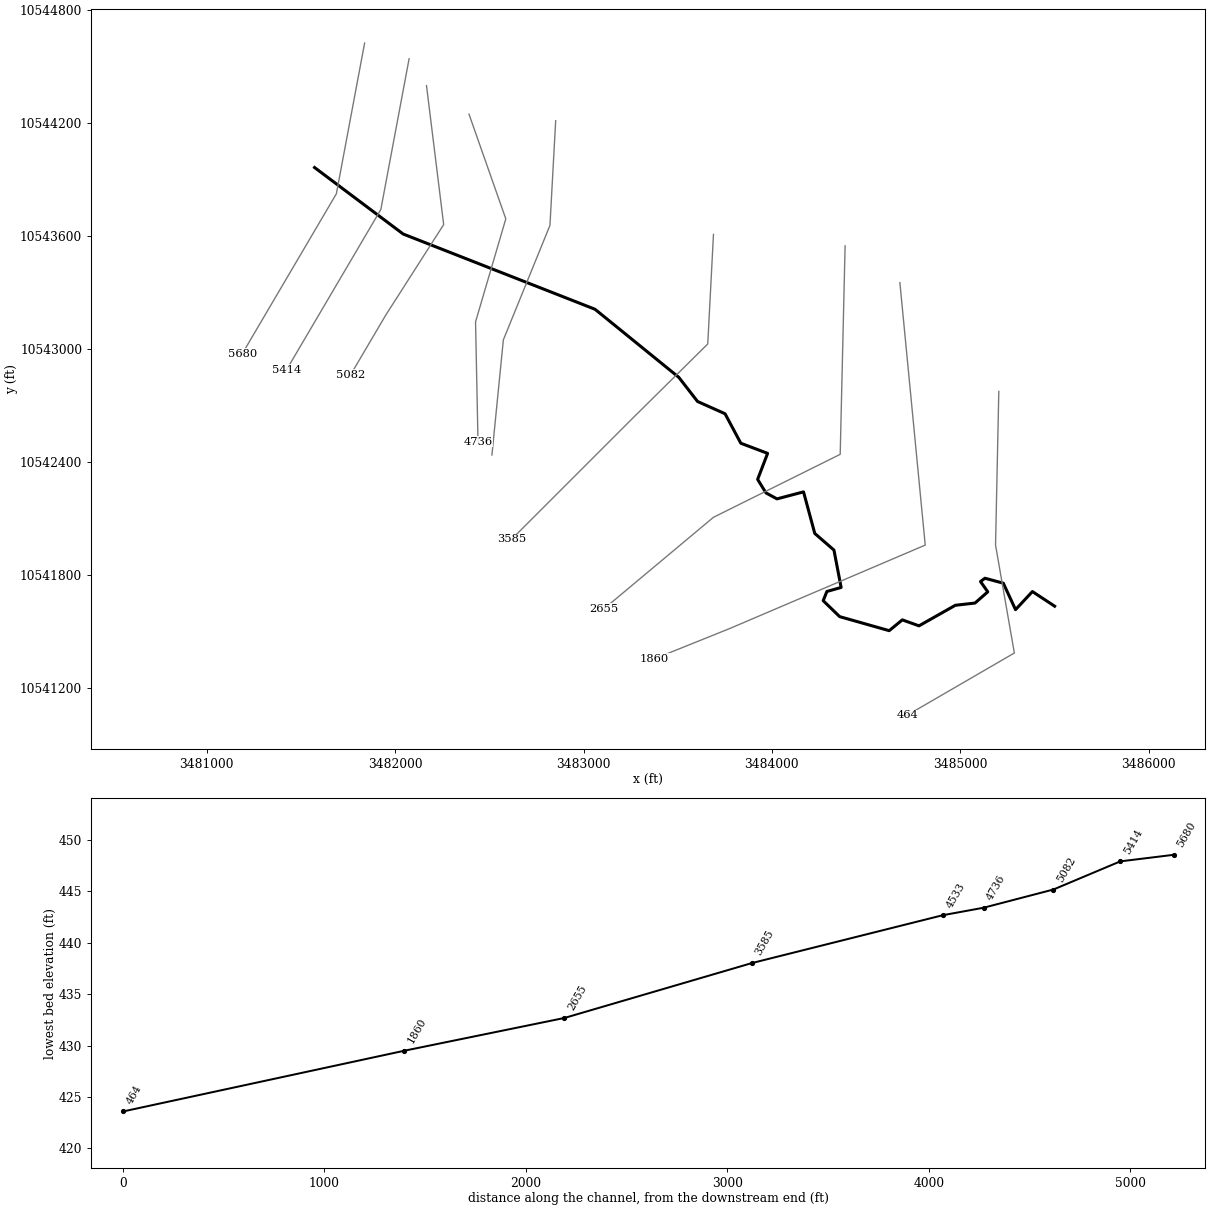
--- UNT01041 IN CHRS.prj (project) ---

Proj Title=UNT01041 IN CHRS Base Level Engineering
Current Plan=p01
Default Exp/Contr=0.3,0.1
English Units
Geom File=g01
Flow File=f01
Plan File=p01
BEGIN DESCRIPTION:
UNT01041 IN CHRS
END DESCRIPTION:

--- UNT01041 IN CHRS.p01 (plan) ---

Plan Title=Multiple Run
Short Identifier=Multiple
Geom File=g01
Flow File=f01
Subcritical Flow
K Sum by GR= 0
Std Step Tol= 0.01
Critical Tol= 0.01
Num of Std Step Trials= 20
Max Error Tol= 0.3
Flow Tol Ratio= 0.001
Split Flow NTrial= 30
Split Flow Tol= 0.02
Split Flow Ratio= 0.02
Log Output Level= 0
Friction Slope Method= 1
Unsteady Friction Slope Method= 2
Unsteady Bridges Friction Slope Method= 1
Parabolic Critical Depth
Global Vel Dist=  1 , 1 , 1
Global Log Level= 0
CheckData=True
Encroach Param= -1, 0, 0, 0
BEGIN DESCRIPTION:
Multiple Run
END DESCRIPTION:

--- UNT01041 IN CHRS.f01 (steady flow) ---

Flow Title=Multiple
Number of Profiles=7
Profile Names=10-year,25-year,50-year,1pct_min,100-year,1pct_plu,500-year
River Rch & RM= UNT01041 IN CHRS,Reach-1,5680
     186     221     244     197     267     361     317
River Rch & RM= UNT01041 IN CHRS,Reach-1,4736
     260     315     353     289     391     529     477
Boundary for River Rch & Prof#=UNT01041 IN CHRS,Reach-1,1
Up Type=0
Dn Type=3
Dn Slope=0.005
Boundary for River Rch & Prof#=UNT01041 IN CHRS,Reach-1,2
Up Type=0
Dn Type=3
Dn Slope=0.005
Boundary for River Rch & Prof#=UNT01041 IN CHRS,Reach-1,3
Up Type=0
Dn Type=3
Dn Slope=0.005
Boundary for River Rch & Prof#=UNT01041 IN CHRS,Reach-1,4
Up Type=0
Dn Type=3
Dn Slope=0.005
Boundary for River Rch & Prof#=UNT01041 IN CHRS,Reach-1,5
Up Type=0
Dn Type=3
Dn Slope=0.005
Boundary for River Rch & Prof#=UNT01041 IN CHRS,Reach-1,6
Up Type=0
Dn Type=3
Dn Slope=0.005
Boundary for River Rch & Prof#=UNT01041 IN CHRS,Reach-1,7
Up Type=0
Dn Type=3
Dn Slope=0.005

--- UNT01041 IN CHRS.g01 (geometry) ---

Geom Title=Existing Conditions

River Reach=UNT01041 IN CHRS,Reach-1
Reach XY= 30
      3481572.11     10543961.64      3482042.60     10543608.62
      3483061.07     10543209.14      3483505.61     10542848.05
      3483605.47     10542719.54      3483751.39     10542654.49
      3483834.94     10542498.05      3483977.25     10542444.16
      3483924.34     10542306.12      3483968.38     10542234.42
      3484026.94     10542202.57      3484167.95     10542239.79
      3484227.63     10542019.12      3484329.42     10541930.83
      3484367.56     10541732.37      3484291.97     10541711.04
      3484272.35     10541662.20      3484359.61     10541577.56
      3484622.72     10541502.98      3484692.37     10541560.30
      3484780.94     10541528.59      3484973.71     10541637.69
      3485078.36     10541649.59      3485146.01     10541709.05
      3485107.43     10541763.83      3485131.06     10541781.31
      3485228.55     10541754.99      3485293.43     10541614.54
      3485383.01     10541710.61      3485501.07     10541632.88

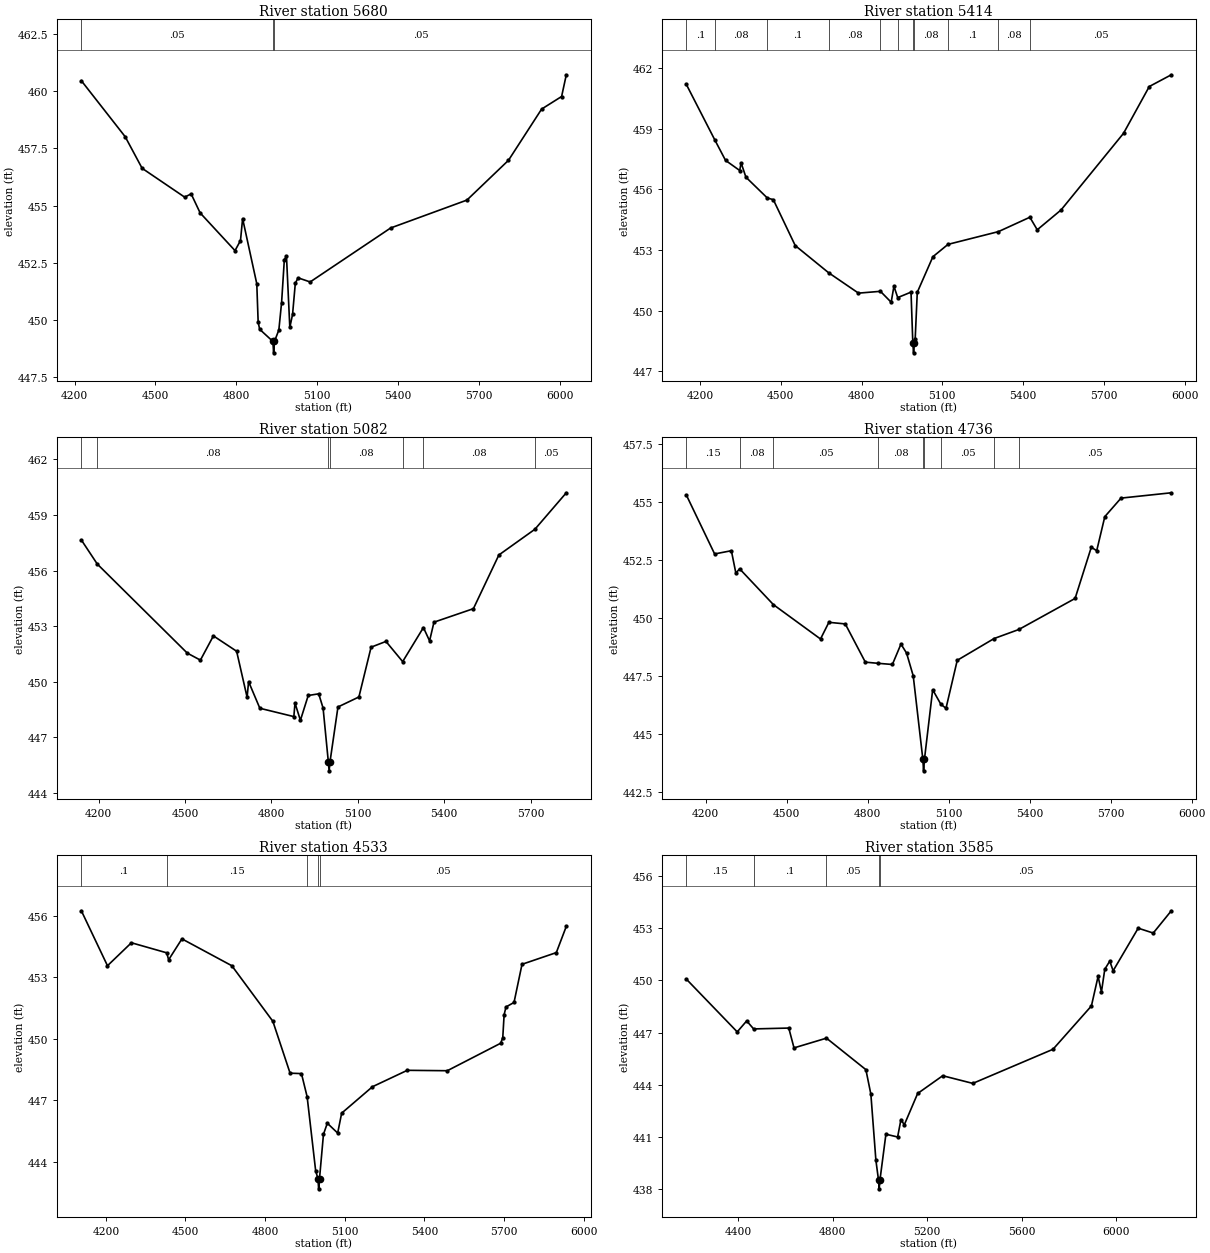
Type RM Length L Ch R = 1,5680,266,266,266
BEGIN DESCRIPTION:
UNT01041 IN CHRS 10.0
END DESCRIPTION:
XS GIS Cut Line= 3
      3481837.94     10544622.23      3481687.94     10543822.20
      3481187.95     10542972.22
#Sta/Elev= 30
  4225.1  460.46  4387.9  458.01  4450.7  456.63  4608.4  455.37  4632.7  455.51
  4666.0  454.68  4795.5  453.03  4815.8  453.47  4823.7  454.43  4876.3  451.58
  4881.4  449.90  4887.0  449.59  4936.0  449.06  4938.8  448.56  4942.0  449.06
  4958.2  449.56  4968.4  450.76  4978.6  452.64  4986.5  452.79  4998.9  449.67
  5009.1  450.24  5019.3  451.60  5029.5  451.84  5074.4  451.66  5373.2  454.02
  5656.3  455.24  5810.6  456.98  5933.6  459.22  6007.8  459.77  6025.2  460.72
#Mann=3,-1,0
  4225.1    0.05       0  4936.0    0.04       0  4942.0    0.05       0
Bank Sta=4936,4942
Exp/Cntr=0.3,0.1

Type RM Length L Ch R = 1,5414,332,332,332
BEGIN DESCRIPTION:
UNT01041 IN CHRS 10.1
END DESCRIPTION:
XS GIS Cut Line= 3
      3482074.04     10544538.83      3481924.05     10543738.86
      3481424.03     10542888.83
#Sta/Elev= 30
  4149.8  461.18  4255.4  458.44  4295.2  457.43  4347.8  456.93  4352.9  457.31
  4370.8  456.60  4450.4  455.57  4472.5  455.49  4553.9  453.22  4677.6  451.88
  4788.7  450.87  4870.1  450.96  4910.0  450.42  4920.2  451.21  4934.3  450.65
  4983.7  450.92  4990.3  448.42  4993.1  447.92  4996.3  448.42  4999.1  448.59
  5006.9  450.91  5064.9  452.67  5121.0  453.28  5308.2  453.91  5424.8  454.62
  5452.2  454.00  5540.6  454.98  5772.6  458.77  5868.1  461.08  5949.9  461.66
#Mann=11,-1,0
  4149.8     0.1       0  4255.4    0.08       0  4450.4     0.1       0
  4677.6    0.08       0  4870.1     0.1       0  4934.3    0.08       0
  4990.3    0.07       0  4996.3    0.08       0  5121.0     0.1       0
  5308.2    0.08       0  5424.8    0.05       0
Bank Sta=4990.3,4996.3
Exp/Cntr=0.3,0.1

Type RM Length L Ch R = 1,5082,346,346,346
BEGIN DESCRIPTION:
UNT01041 IN CHRS 10.2
END DESCRIPTION:
XS GIS Cut Line= 4
      3482166.43     10544396.51      3482257.58     10543658.65
      3481949.42     10543176.88      3481762.78     10542860.02
#Sta/Elev= 30
  4140.4  457.65  4195.7  456.35  4508.0  451.54  4553.6  451.16  4598.7  452.47
  4679.3  451.64  4715.7  449.15  4720.8  450.00  4759.9  448.56  4877.9  448.11
  4881.9  448.84  4900.7  447.91  4927.8  449.25  4964.2  449.34  4979.4  448.57
  4997.5  445.68  5000.3  445.18  5003.5  445.68  5031.0  448.63  5103.7  449.17
  5146.0  451.86  5197.6  452.17  5255.6  451.08  5327.6  452.92  5349.0  452.20
  5364.2  453.21  5501.1  453.94  5589.5  456.84  5714.6  458.23  5823.5  460.20
#Mann=7,-1,0
  4140.4     0.1       0  4195.7    0.08       0  4997.5    0.07       0
  5003.5    0.08       0  5255.6     0.1       0  5327.6    0.08       0
  5714.6    0.05       0
Bank Sta=4997.5,5003.5
Exp/Cntr=0.3,0.1

Type RM Length L Ch R = 1,4736,203,203,203
BEGIN DESCRIPTION:
UNT01041 IN CHRS 9.0
END DESCRIPTION:
XS GIS Cut Line= 4
      3482392.13     10544244.58      3482587.44     10543689.03
      3482426.85     10543142.15      3482439.84     10542505.43
#Sta/Elev= 30
  4129.0  455.31  4233.6  452.77  4295.6  452.91  4312.3  451.94  4326.1  452.13
  4451.5  450.58  4625.7  449.10  4656.7  449.82  4717.4  449.75  4791.7  448.10
  4839.1  448.05  4891.8  448.00  4923.6  448.88  4944.4  448.49  4969.0  447.51
  5004.6  443.91  5007.3  443.41  5010.6  443.91  5041.0  446.91  5071.5  446.28
  5090.4  446.11  5132.0  448.18  5268.5  449.12  5360.1  449.51  5568.4  450.85
  5628.4  453.06  5648.4  452.91  5678.4  454.38  5738.5  455.18  5924.7  455.41
#Mann=9,-1,0
  4129.0    0.15       0  4326.1    0.08       0  4451.5    0.05       0
  4839.1    0.08       0  5004.6    0.07       0  5010.6    0.08       0
  5071.5    0.05       0  5268.5    0.08       0  5360.1    0.05       0
Bank Sta=5004.6,5010.6
Exp/Cntr=0.3,0.1

Type RM Length L Ch R = 1,4533,948,948,948
BEGIN DESCRIPTION:
UNT01041 IN CHRS 8.0
END DESCRIPTION:
XS GIS Cut Line= 4
      3482852.20     10544209.90      3482821.81     10543654.31
      3482574.42     10543046.67      3482513.75     10542435.67
#Sta/Elev= 30
  4107.8  456.24  4206.2  453.56  4296.3  454.68  4429.3  454.19  4436.5  453.85
  4486.6  454.87  4674.6  453.56  4829.1  450.85  4894.0  448.32  4936.8  448.30
  4958.2  447.17  4990.3  443.56  4998.8  443.18  5001.6  442.68  5004.8  443.18
  5019.7  445.34  5034.2  445.88  5073.2  445.40  5088.2  446.37  5204.3  447.66
  5335.4  448.46  5486.1  448.44  5687.1  449.78  5695.0  450.05  5700.1  451.17
  5707.2  451.55  5737.4  451.77  5767.5  453.63  5896.7  454.20  5934.3  455.48
#Mann=5,-1,0
  4107.8     0.1       0  4429.3    0.15       0  4958.2    0.05       0
  4998.8    0.03       0  5004.8    0.05       0
Bank Sta=4998.8,5004.8
Exp/Cntr=0.3,0.1

Type RM Length L Ch R = 1,3585,930,930,930
BEGIN DESCRIPTION:
UNT01041 IN CHRS 6.0
END DESCRIPTION:
XS GIS Cut Line= 4
      3483689.87     10543606.52      3483659.49     10543024.97
      3483264.52     10542634.34      3482617.84     10541987.66
#Sta/Elev= 30
  4181.5  450.07  4396.7  447.04  4436.7  447.67  4466.2  447.21  4614.9  447.26
  4637.0  446.12  4774.4  446.68  4941.2  444.87  4962.3  443.46  4983.6  439.66
  4994.7  438.52  4997.5  438.02  5000.7  438.52  5026.0  441.16  5075.5  441.00
  5089.6  442.00  5103.8  441.70  5160.3  443.50  5266.4  444.52  5393.7  444.08
  5733.1  446.04  5895.7  448.53  5924.0  450.23  5938.2  449.34  5952.3  450.64
  5973.5  451.11  5987.6  450.55  6093.7  453.00  6157.4  452.72  6233.9  454.00
#Mann=5,-1,0
  4181.5    0.15       0  4466.2     0.1       0  4774.4    0.05       0
  4994.7    0.03       0  5000.7    0.05       0
Bank Sta=4994.7,5000.7
Exp/Cntr=0.3,0.1

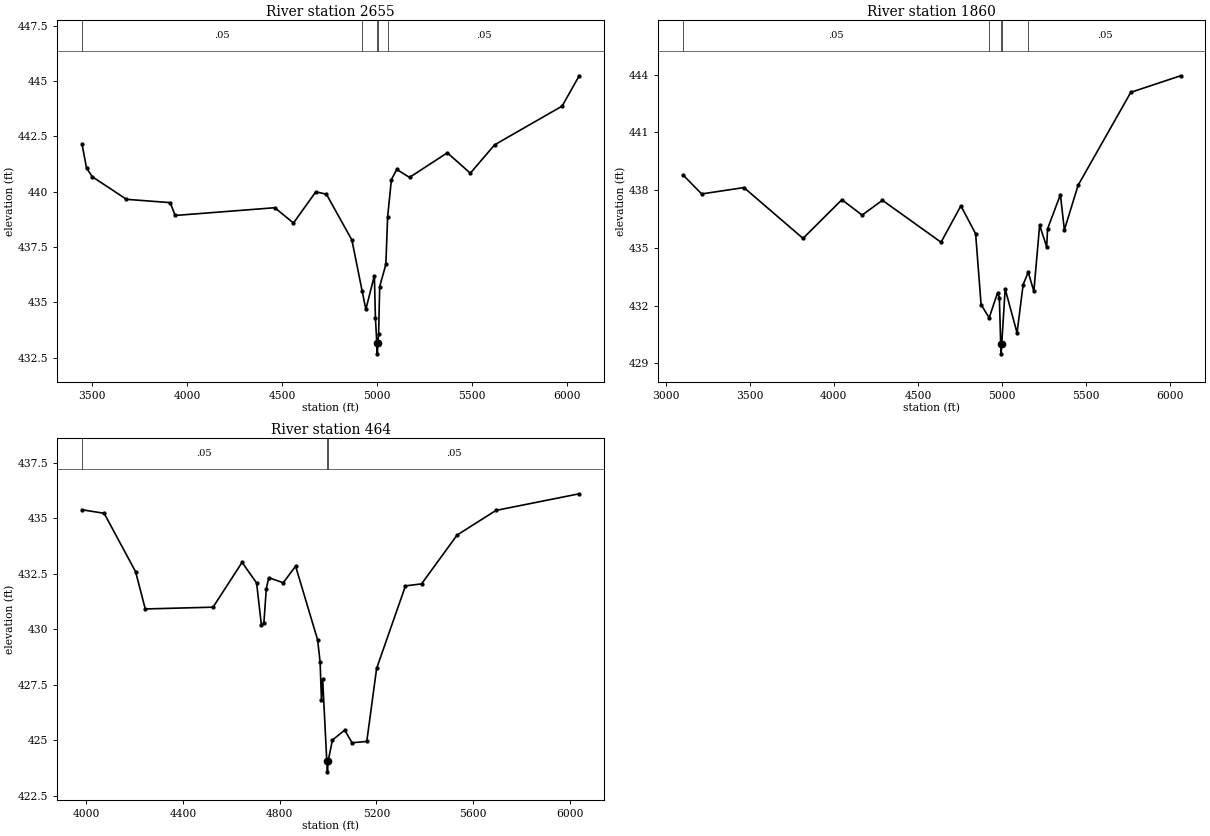
Type RM Length L Ch R = 1,2655,795,795,795
BEGIN DESCRIPTION:
UNT01041 IN CHRS 4.0
END DESCRIPTION:
XS GIS Cut Line= 4
      3484388.65     10543545.82      3484362.61     10542439.03
      3483689.87     10542104.83      3483108.25     10541618.70
#Sta/Elev= 30
  3446.6  442.16  3470.8  441.07  3500.8  440.68  3680.8  439.66  3910.9  439.51
  3936.7  438.93  4461.1  439.28  4559.4  438.59  4677.1  440.00  4732.9  439.89
  4866.9  437.82  4921.1  435.50  4940.3  434.69  4985.1  436.21  4990.7  434.28
  4997.9  433.18  5000.6  432.68  5003.9  433.18  5007.5  433.59  5013.1  435.72
  5045.6  436.72  5054.9  438.88  5074.8  440.55  5102.7  441.01  5170.0  440.65
  5369.0  441.76  5490.0  440.84  5617.6  442.12  5972.9  443.87  6062.9  445.24
#Mann=5,-1,0
  3446.6    0.05       0  4921.1    0.12       0  4997.9    0.07       0
  5003.9    0.12       0  5054.9    0.05       0
Bank Sta=4997.9,5003.9
Exp/Cntr=0.3,0.1

Type RM Length L Ch R = 1,1860,1396,1396,1396
BEGIN DESCRIPTION:
UNT01041 IN CHRS 3.0
END DESCRIPTION:
XS GIS Cut Line= 4
      3484679.45     10543350.53      3484814.00     10541957.26
      3483776.67     10541514.55      3483377.36     10541353.96
#Sta/Elev= 30
  3104.5  438.77  3213.9  437.80  3465.1  438.13  3816.7  435.49  4047.8  437.50
  4168.3  436.70  4288.9  437.47  4637.7  435.29  4755.8  437.18  4843.4  435.73
  4876.0  432.05  4923.9  431.36  4973.8  432.66  4984.6  432.41  4992.6  429.99
  4995.3  429.49  4998.6  429.99  5019.1  432.86  5089.9  430.58  5126.1  433.09
  5156.5  433.73  5189.8  432.74  5224.2  436.17  5266.0  435.06  5271.5  435.99
  5347.7  437.76  5371.3  435.93  5453.1  438.25  5766.4  443.08  6062.5  443.94
#Mann=5,-1,0
  3104.5    0.05       0  4923.9    0.16       0  4992.6    0.07       0
  4998.6    0.16       0  5156.5    0.05       0
Bank Sta=4992.6,4998.6
Exp/Cntr=0.3,0.1

Type RM Length L Ch R = 1,464,0,0,0
BEGIN DESCRIPTION:
UNT01041 IN CHRS 1.0
END DESCRIPTION:
XS GIS Cut Line= 4
      3485204.62     10542773.22      3485187.26     10541957.26
      3485287.09     10541384.34      3484718.54     10541054.50
#Sta/Elev= 30
  3983.1  435.39  4074.7  435.23  4204.7  432.60  4244.7  430.92  4524.8  431.00
  4644.8  433.02  4704.8  432.09  4724.8  430.18  4734.8  430.27  4744.9  431.83
  4754.9  432.33  4815.1  432.10  4865.9  432.85  4957.2  429.52  4967.4  428.51
  4972.8  426.83  4977.8  427.76  4994.8  424.08  4997.6  423.58  5000.8  424.08
  5018.1  425.01  5068.9  425.46  5099.3  424.89  5160.2  424.95  5200.8  428.24
  5320.1  431.96  5386.6  432.05  5533.4  434.25  5694.0  435.36  6038.1  436.11
#Mann=3,-1,0
  3983.1    0.05       0  4994.8   0.035       0  5000.8    0.05       0
Bank Sta=4994.8,5000.8
Exp/Cntr=0.3,0.1

Chan Stop Cuts=-1