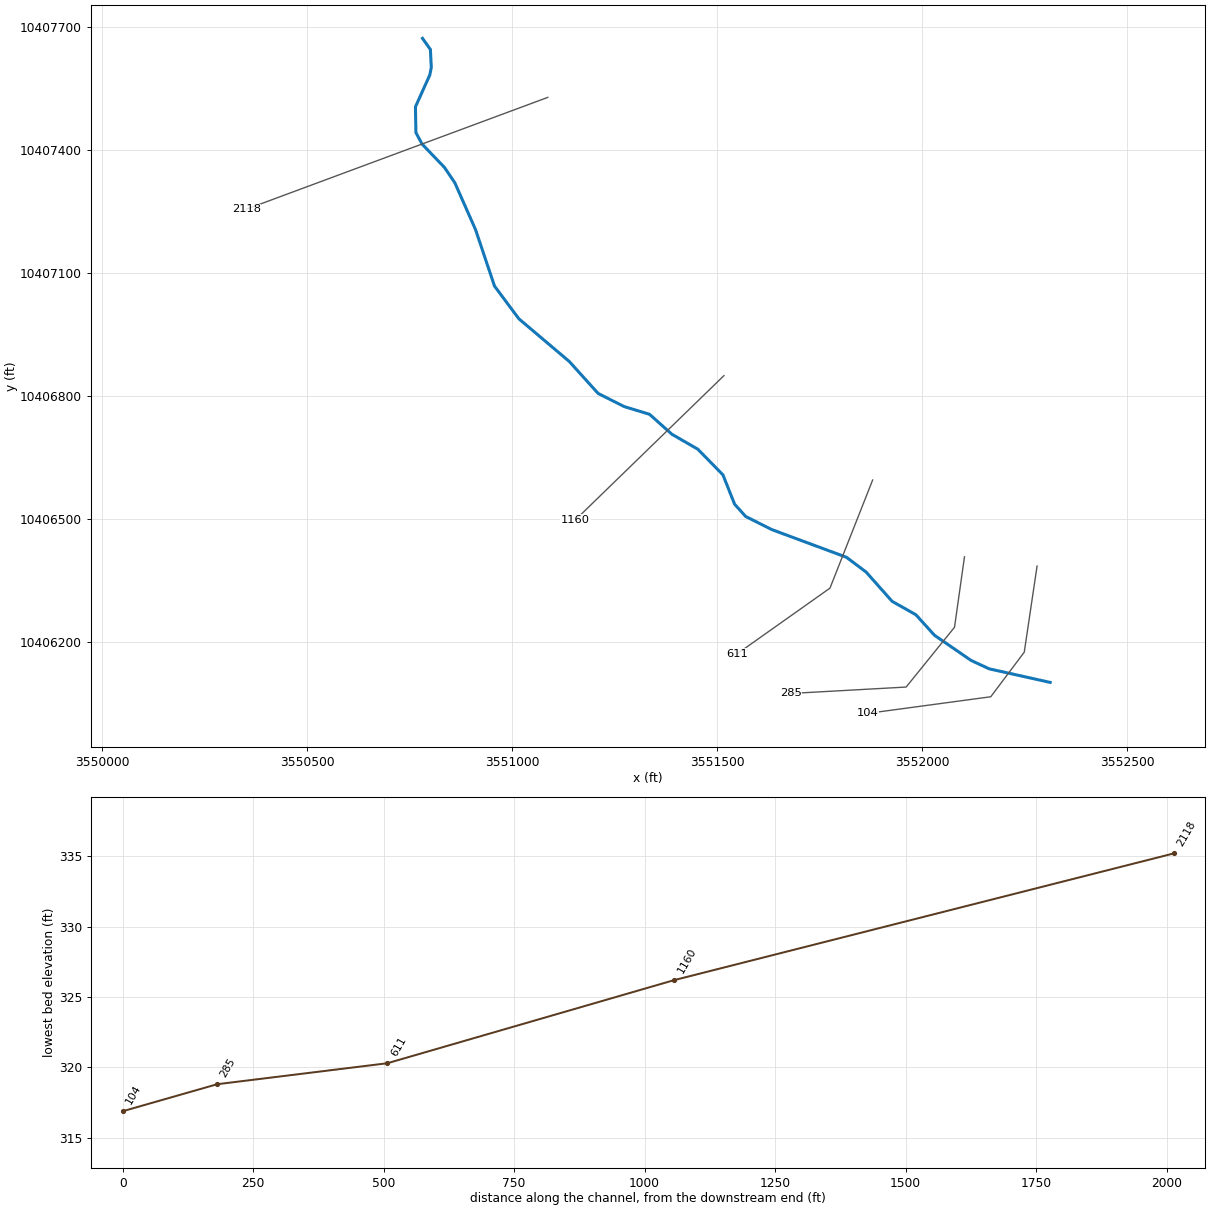
--- ALUM BRANCH TRIB 1.prj (project) ---

Proj Title=ALUM BRANCH TRIB 1 Base Level Engineering
Current Plan=p01
Default Exp/Contr=0.3,0.1
English Units
Geom File=g01
Flow File=f01
Plan File=p01
BEGIN DESCRIPTION:
ALUM BRANCH TRIB 1
END DESCRIPTION:

--- ALUM BRANCH TRIB 1.p01 (plan) ---

Plan Title=Multiple Run
Short Identifier=Multiple
Geom File=g01
Flow File=f01
Subcritical Flow
K Sum by GR= 0
Std Step Tol= 0.01
Critical Tol= 0.01
Num of Std Step Trials= 20
Max Error Tol= 0.3
Flow Tol Ratio= 0.001
Split Flow NTrial= 30
Split Flow Tol= 0.02
Split Flow Ratio= 0.02
Log Output Level= 0
Friction Slope Method= 1
Unsteady Friction Slope Method= 2
Unsteady Bridges Friction Slope Method= 1
Parabolic Critical Depth
Global Vel Dist=  1 , 1 , 1
Global Log Level= 0
CheckData=True
Encroach Param= -1, 0, 0, 0
BEGIN DESCRIPTION:
Multiple Run
END DESCRIPTION:

--- ALUM BRANCH TRIB 1.f01 (steady flow) ---

Flow Title=Multiple
Number of Profiles=7
Profile Names=10-year,25-year,50-year,1pct_min,100-year,1pct_plu,500-year
River Rch & RM= ALUM BRANCH TRIB,Reach-1,2118
     421     551     653     567     767    1037    1052
Boundary for River Rch & Prof#=ALUM BRANCH TRIB,Reach-1,1
Up Type=0
Dn Type=3
Dn Slope=0.005
Boundary for River Rch & Prof#=ALUM BRANCH TRIB,Reach-1,2
Up Type=0
Dn Type=3
Dn Slope=0.005
Boundary for River Rch & Prof#=ALUM BRANCH TRIB,Reach-1,3
Up Type=0
Dn Type=3
Dn Slope=0.005
Boundary for River Rch & Prof#=ALUM BRANCH TRIB,Reach-1,4
Up Type=0
Dn Type=3
Dn Slope=0.005
Boundary for River Rch & Prof#=ALUM BRANCH TRIB,Reach-1,5
Up Type=0
Dn Type=3
Dn Slope=0.005
Boundary for River Rch & Prof#=ALUM BRANCH TRIB,Reach-1,6
Up Type=0
Dn Type=3
Dn Slope=0.005
Boundary for River Rch & Prof#=ALUM BRANCH TRIB,Reach-1,7
Up Type=0
Dn Type=3
Dn Slope=0.005

--- ALUM BRANCH TRIB 1.g01 (geometry) ---

Geom Title=Existing Conditions

River Reach=ALUM BRANCH TRIB,Reach-1
Reach XY= 30
      3550780.86     10407672.88      3550800.12     10407645.66
      3550802.29     10407601.92      3550798.59     10407583.30
      3550763.62     10407505.82      3550764.77     10407442.87
      3550779.74     10407414.94      3550834.17     10407358.26
      3550859.69     10407320.64      3550910.37     10407205.92
      3550956.43     10407068.71      3551015.90     10406988.69
      3551138.76     10406884.75      3551209.33     10406806.51
      3551273.25     10406774.43      3551334.65     10406755.74
      3551389.33     10406706.98      3551452.38     10406670.69
      3551513.74     10406608.04      3551542.18     10406536.49
      3551569.19     10406506.45      3551633.21     10406474.37
      3551814.92     10406407.04      3551863.21     10406370.73
      3551926.35     10406299.57      3551984.70     10406266.52
      3552029.71     10406216.76      3552118.94     10406155.39
      3552163.40     10406134.76      3552312.11     10406101.64

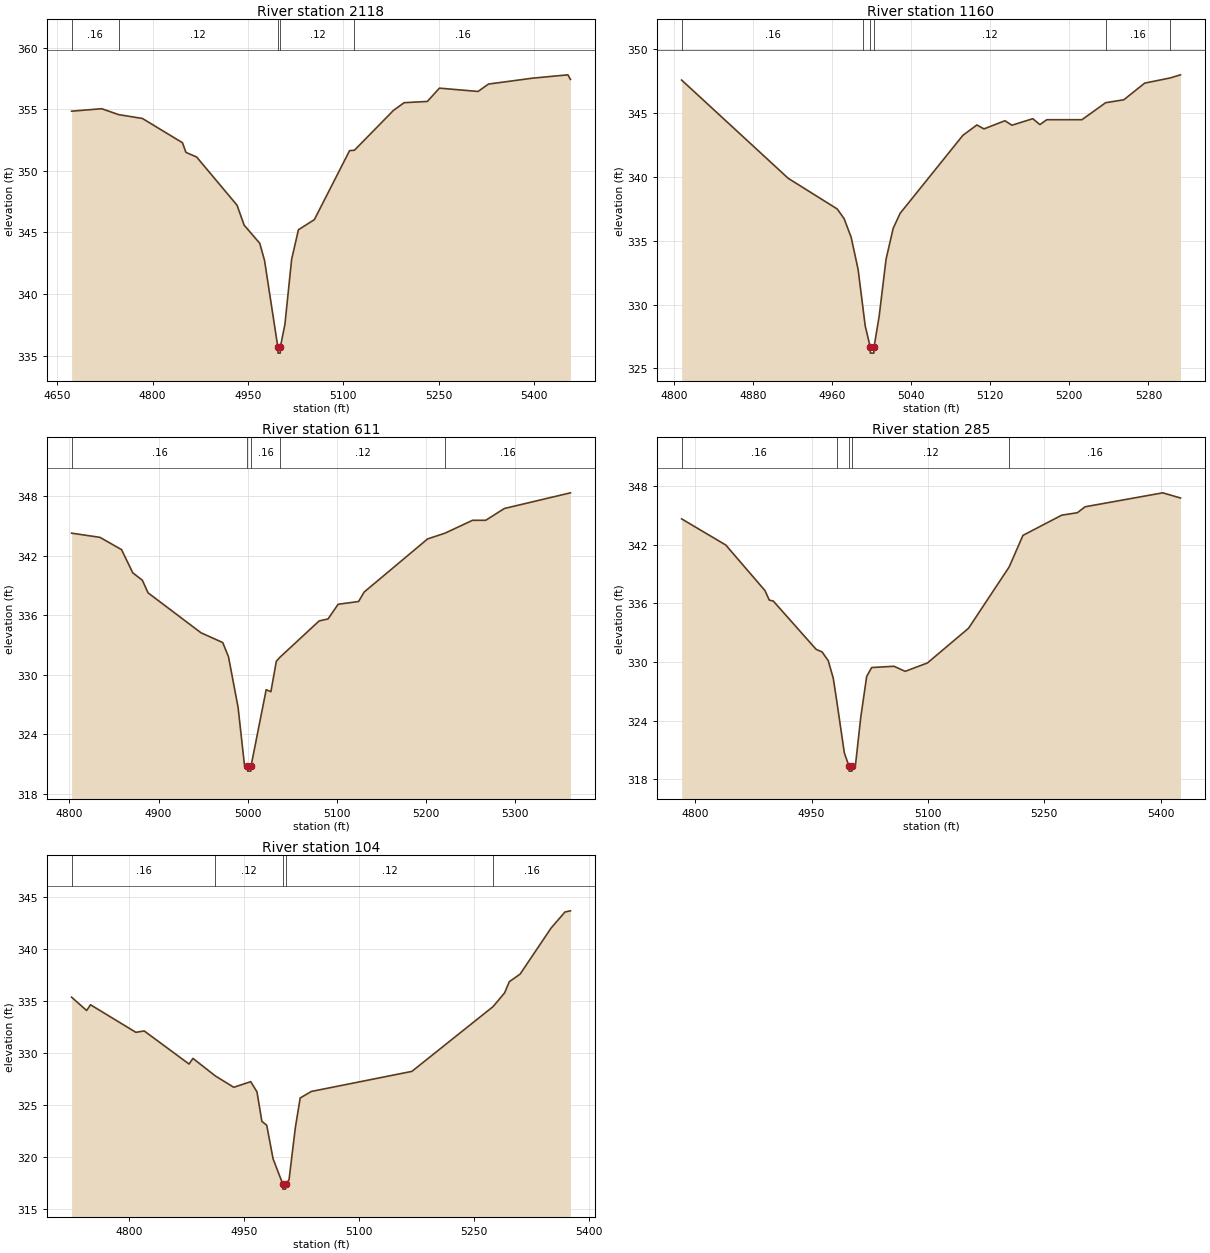
Type RM Length L Ch R = 1,2118,958,958,958
BEGIN DESCRIPTION:
ALUM BRANCH TRIB 1 3 0
END DESCRIPTION:
XS GIS Cut Line= 2
      3551086.46     10407528.82      3550351.23     10407256.03
#Sta/Elev= 30
  4672.8  354.84  4720.1  355.04  4746.8  354.56  4784.1  354.25  4847.1  352.28
  4852.5  351.50  4869.4  351.12  4932.9  347.21  4944.1  345.59  4968.6  344.12
  4976.1  342.73  4997.0  335.71  4997.3  335.21  5000.8  335.21  5001.0  335.71
  5008.1  337.53  5018.7  342.82  5029.4  345.22  5054.4  346.04  5109.8  351.64
  5117.4  351.67  5178.7  354.90  5195.6  355.53  5232.1  355.63  5251.0  356.71
  5311.8  356.44  5328.1  357.04  5397.6  357.52  5453.0  357.79  5457.0  357.42
#Mann=5,-1,0
  4672.8    0.16       0  4746.8    0.12       0  4997.0    0.07       0
  5001.0    0.12       0  5117.4    0.16       0
Bank Sta=4997,5001
Exp/Cntr=0.3,0.1

Type RM Length L Ch R = 1,1160,549,549,549
BEGIN DESCRIPTION:
ALUM BRANCH TRIB 1 2 0
END DESCRIPTION:
XS GIS Cut Line= 2
      3551516.18     10406850.02      3551154.21     10406498.46
#Sta/Elev= 30
  4807.8  347.55  4915.6  339.87  4965.2  337.47  4972.2  336.71  4979.3  335.25
  4986.3  332.75  4991.6  329.50  4993.5  328.33  4998.5  326.70  4998.7  326.20
  5002.2  326.20  5002.5  326.70  5007.6  329.08  5014.6  333.55  5021.8  335.96
  5028.8  337.13  5092.3  343.23  5106.5  344.04  5113.6  343.73  5134.8  344.37
  5141.9  344.02  5163.0  344.53  5170.2  344.07  5177.2  344.45  5212.7  344.45
  5236.7  345.78  5255.1  346.01  5276.2  347.31  5302.2  347.72  5312.4  347.96
#Mann=6,-1,0
  4807.8    0.16       0  4991.6    0.12       0  4998.5    0.07       0
  5002.5    0.12       0  5236.7    0.16       0  5302.2    0.05       0
Bank Sta=4998.5,5002.5
Exp/Cntr=0.3,0.1

Type RM Length L Ch R = 1,611,326,326,326
BEGIN DESCRIPTION:
Mapping XS e2ec6e57
END DESCRIPTION:
XS GIS Cut Line= 3
      3551879.04     10406595.50      3551774.88     10406331.65
      3551549.16     10406171.90
#Sta/Elev= 30
  4802.4  344.30  4834.2  343.88  4858.5  342.64  4871.1  340.30  4881.8  339.56
  4888.3  338.28  4947.8  334.25  4972.1  333.27  4978.6  331.83  4989.3  326.77
  4996.5  320.93  4999.9  320.80  5000.1  320.30  5003.6  320.30  5003.9  320.80
  5020.9  328.51  5026.2  328.31  5032.3  331.38  5036.3  331.78  5080.4  335.45
  5090.4  335.65  5101.7  337.13  5124.7  337.41  5130.9  338.36  5202.2  343.72
  5221.7  344.30  5252.7  345.60  5267.5  345.60  5288.4  346.79  5362.6  348.37
#Mann=5,-1,0
  4802.4    0.16       0  4999.9    0.07       0  5003.9    0.16       0
  5036.3    0.12       0  5221.7    0.16       0
Bank Sta=4999.9,5003.9
Exp/Cntr=0.3,0.1

Type RM Length L Ch R = 1,285,181,181,181
BEGIN DESCRIPTION:
Mapping XS cbdc392a
END DESCRIPTION:
XS GIS Cut Line= 4
      3552103.01     10406408.03      3552078.70     10406236.16
      3551960.65     10406090.33      3551679.39     10406074.70
#Sta/Elev= 30
  4782.6  344.67  4839.5  341.99  4890.0  337.32  4895.6  336.34  4900.7  336.25
  4955.9  331.30  4963.6  331.03  4971.5  330.14  4978.0  328.34  4982.2  326.17
  4992.3  320.68  4998.3  319.31  4998.5  318.81  5002.0  318.81  5002.3  319.31
  5006.7  319.47  5013.5  324.36  5021.1  328.52  5027.5  329.43  5056.3  329.56
  5070.7  329.04  5099.4  329.90  5152.4  333.46  5204.7  339.74  5222.5  342.98
  5272.5  345.05  5292.6  345.30  5302.6  345.91  5402.7  347.34  5425.5  346.81
#Mann=5,-1,0
  4782.6    0.16       0  4982.2    0.12       0  4998.3    0.07       0
  5002.3    0.12       0  5204.7    0.16       0
Bank Sta=4998.3,5002.3
Exp/Cntr=0.3,0.1

Type RM Length L Ch R = 1,104,0,0,0
BEGIN DESCRIPTION:
ALUM BRANCH TRIB 1 1 0
END DESCRIPTION:
XS GIS Cut Line= 4
      3552280.09     10406385.42      3552248.84     10406175.40
      3552167.11     10406066.64      3551867.01     10406026.11
#Sta/Elev= 30
  4724.9  335.36  4744.5  334.08  4749.6  334.63  4808.8  331.98  4819.7  332.11
  4878.2  328.93  4883.3  329.47  4912.6  327.78  4936.6  326.69  4958.7  327.23
  4966.9  326.25  4973.3  323.41  4979.6  323.04  4987.9  319.81  5000.5  317.39
  5000.7  316.89  5004.2  316.89  5004.5  317.39  5008.7  317.77  5017.0  322.82
  5023.3  325.66  5037.9  326.29  5169.1  328.22  5275.2  334.46  5290.2  335.78
  5296.3  336.85  5310.4  337.58  5350.8  342.01  5369.0  343.56  5376.1  343.67
#Mann=5,-1,0
  4724.9    0.16       0  4912.6    0.12       0  5000.5    0.07       0
  5004.5    0.12       0  5275.2    0.16       0
Bank Sta=5000.5,5004.5
Exp/Cntr=0.3,0.1

Chan Stop Cuts=-1