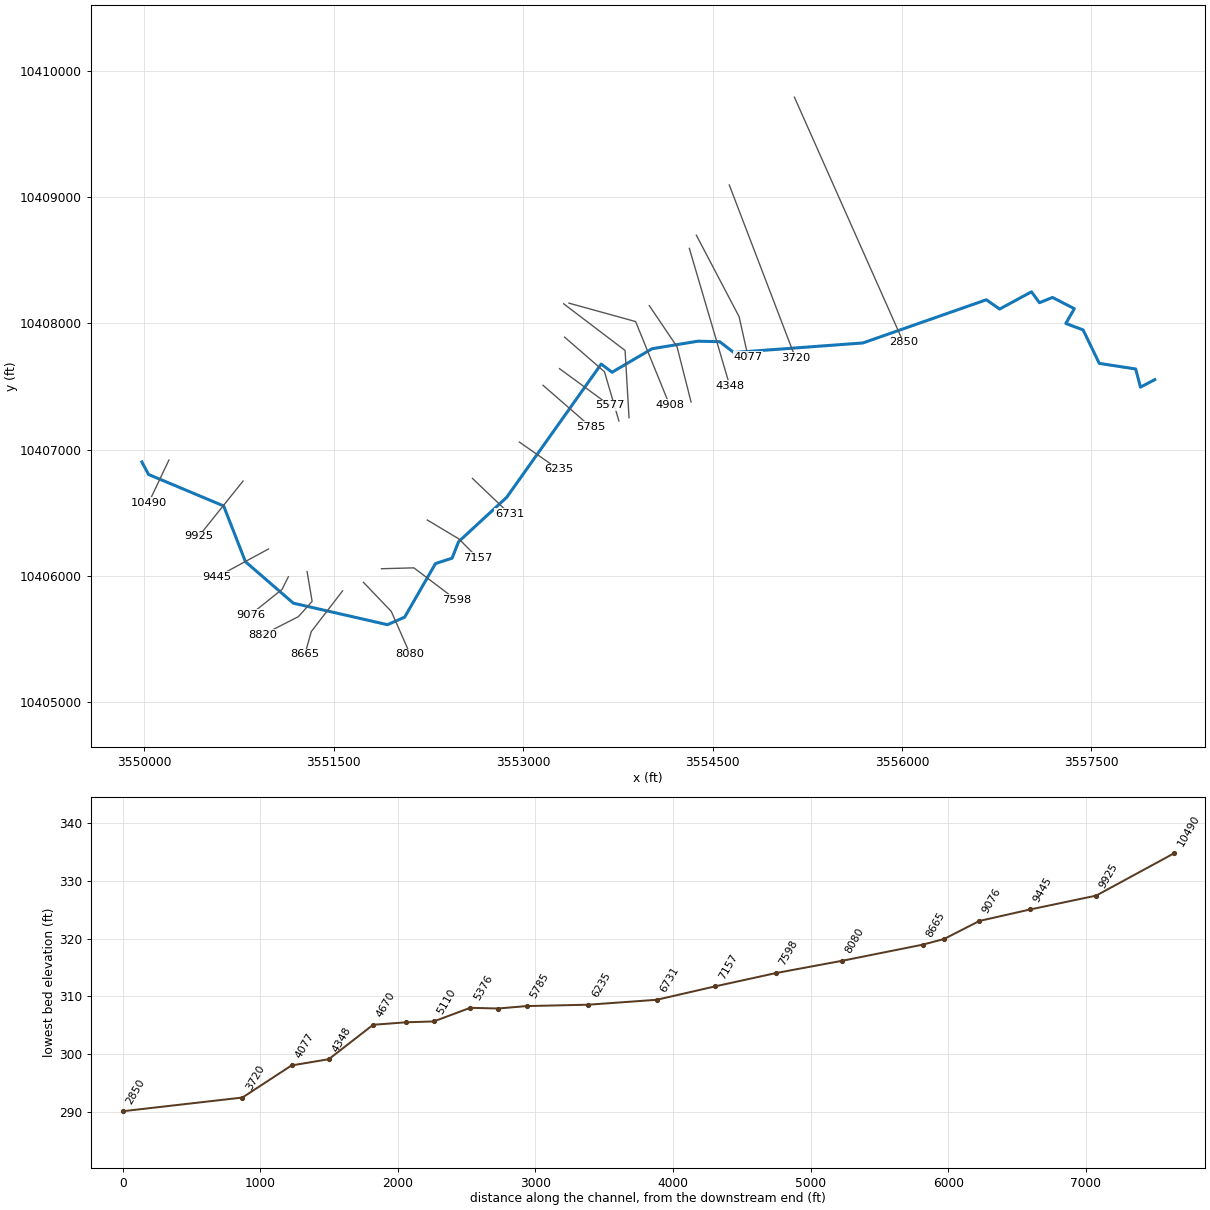
--- ALUM BRANCH.prj (project) ---

Proj Title=ALUM BRANCH Base Level Engineering
Current Plan=p01
Default Exp/Contr=0.3,0.1
English Units
Geom File=g01
Flow File=f01
Plan File=p01
Y Axis Title=Elevation
X Axis Title(PF)=Main Channel Distance
X Axis Title(XS)=Station
BEGIN DESCRIPTION:
ALUM BRANCH
END DESCRIPTION:
DSS Export Rating Curves= 0
DSS Export Rating Curve Sorted= 0
DSS Export Volume Flow Curves= 0
DXF OffsetX= 0
DXF OffsetY= 0
DXF ScaleX= 1
DXF ScaleY= 10

--- ALUM BRANCH.p01 (plan) ---

Plan Title=Multiple Run
Short Identifier=Multiple
Geom File=g01
Flow File=f01
Subcritical Flow
K Sum by GR= 0
Std Step Tol= 0.01
Critical Tol= 0.01
Num of Std Step Trials= 20
Max Error Tol= 0.3
Flow Tol Ratio= 0.001
Split Flow NTrial= 30
Split Flow Tol= 0.02
Split Flow Ratio= 0.02
Log Output Level= 0
Friction Slope Method= 1
Unsteady Friction Slope Method= 2
Unsteady Bridges Friction Slope Method= 1
Parabolic Critical Depth
Global Vel Dist=  1 , 1 , 1
Global Log Level= 0
CheckData=True
Encroach Param= -1, 0, 0, 0
BEGIN DESCRIPTION:
Multiple Run
END DESCRIPTION:

--- ALUM BRANCH.f01 (steady flow) ---

Flow Title=Multiple
Program Version=4.10
Number of Profiles= 7
Profile Names=10-year,25-year,50-year,1pct_min,100-year,1pct_plu,500-year
River Rch & RM=ALUM BRANCH,Reach-1         ,10490
     730     988    1198    1063    1437    1943    2058
River Rch & RM=ALUM BRANCH,Reach-1         ,7157
    1269    1771    2190    1976    2672    3614    3966
Boundary for River Rch & Prof#=ALUM BRANCH,Reach-1         , 1
Up Type= 0
Dn Type= 3
Dn Slope=0.008
Boundary for River Rch & Prof#=ALUM BRANCH,Reach-1         , 2
Up Type= 0
Dn Type= 3
Dn Slope=0.008
Boundary for River Rch & Prof#=ALUM BRANCH,Reach-1         , 3
Up Type= 0
Dn Type= 3
Dn Slope=0.008
Boundary for River Rch & Prof#=ALUM BRANCH,Reach-1         , 4
Up Type= 0
Dn Type= 3
Dn Slope=0.008
Boundary for River Rch & Prof#=ALUM BRANCH,Reach-1         , 5
Up Type= 0
Dn Type= 3
Dn Slope=0.008
Boundary for River Rch & Prof#=ALUM BRANCH,Reach-1         , 6
Up Type= 0
Dn Type= 3
Dn Slope=0.008
Boundary for River Rch & Prof#=ALUM BRANCH,Reach-1         , 7
Up Type= 0
Dn Type= 3
Dn Slope=0.008
DSS Import GetInterval= 0
DSS Import GetPeak= 0
DSS Import FillOption= 0

--- ALUM BRANCH.g01 (geometry) ---

Geom Title=Existing Conditions
Program Version=4.10

River Reach=ALUM BRANCH     ,Reach-1
Reach XY= 30
      3549982.11     10406901.64      3550035.55     10406802.45
      3550630.01     10406552.95      3550802.58     10406111.28
      3551181.92      10405782.5      3551926.88      10405612.2
      3552062.95     10405672.13      3552307.26     10406096.78
      3552438.39     10406139.16      3552489.59     10406269.43
      3552870.76     10406621.36      3553618.96      10407677.4
       3553704.9     10407612.29      3554021.31     10407798.49
      3554384.59     10407858.39      3554556.46     10407854.48
      3554668.44     10407768.54      3555691.01      10407844.5
      3556667.57     10408186.51      3556772.61     10408112.73
      3557025.36     10408249.67      3557087.98     10408163.27
      3557191.62     10408204.99      3557364.28     10408115.94
      3557297.21     10407998.95      3557433.92     10407947.64
      3557561.78     10407682.49      3557850.07     10407638.15
      3557887.76     10407494.15      3558001.16     10407553.75

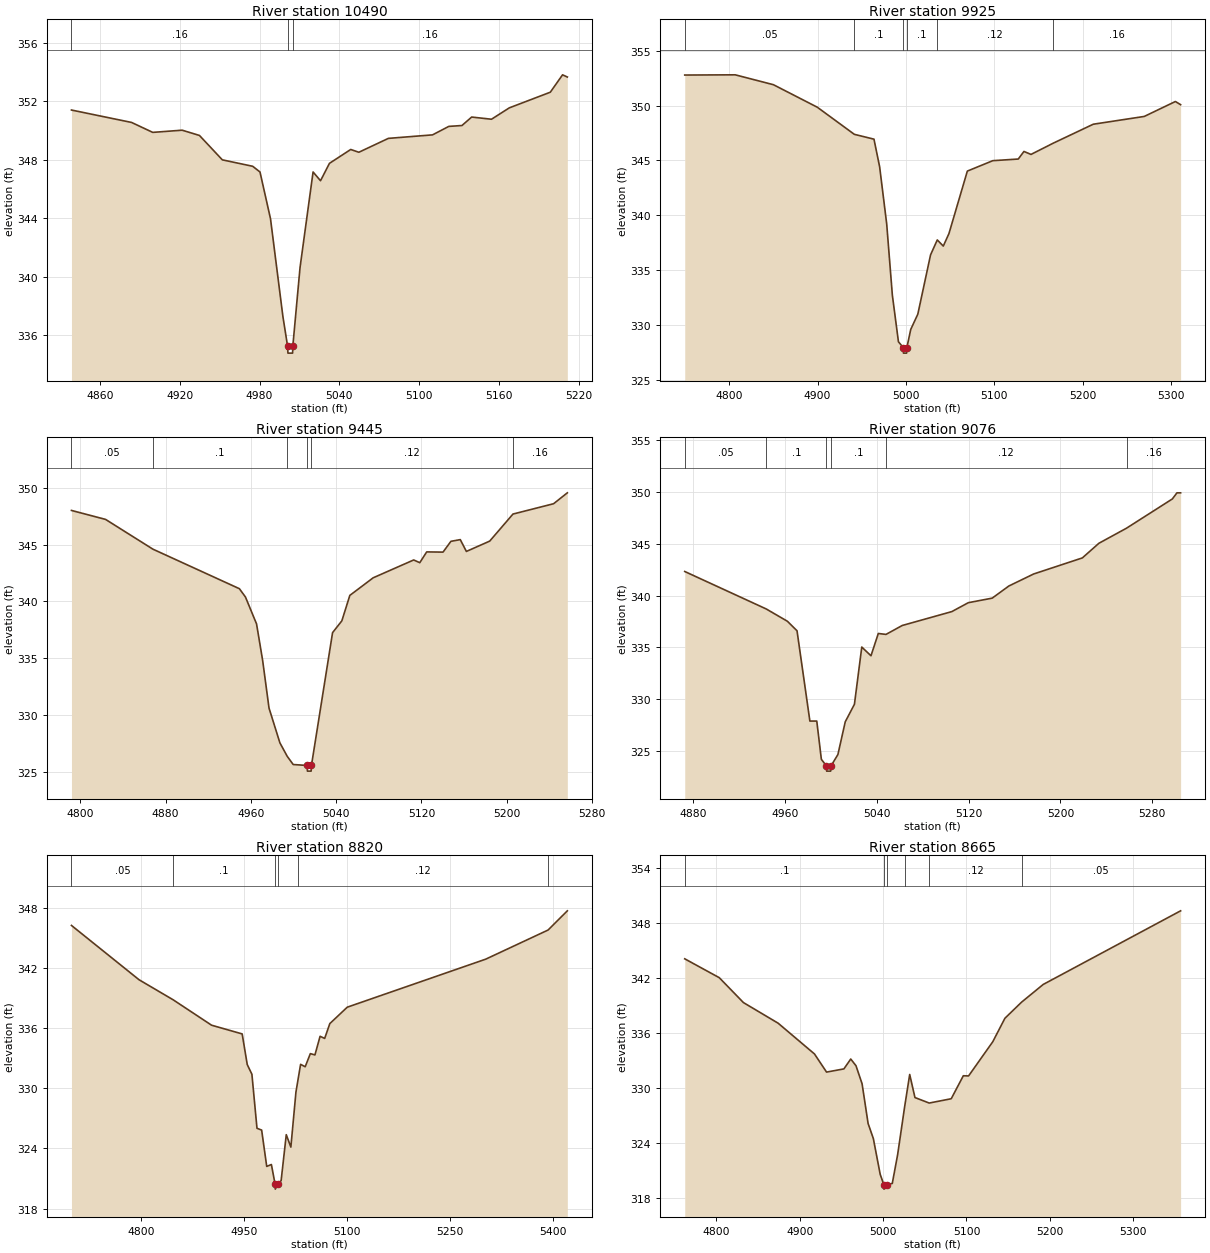
Type RM Length L Ch R = 1 ,10490   ,565,565,565
BEGIN DESCRIPTION:
ALUM BRANCH 2 1
END DESCRIPTION:
XS GIS Cut Line= 2
      3550196.78     10406916.85      3550037.08      10406580.1
#Sta/Elev= 30
  4838.6   351.4  4883.8  350.55  4899.7  349.87  4921.8  350.02  4934.8  349.66
    4952  347.99  4974.8  347.55  4980.3  347.16  4988.2  343.96  4997.5  337.28
    5001  335.26  5001.3  334.76  5004.8  334.76    5005  335.26  5010.4  340.62
  5020.2  347.16  5025.8  346.56  5032.5  347.75  5048.5   348.7  5054.6  348.51
  5076.8  349.46    5110   349.7  5122.2  350.28  5132.1  350.34  5139.4  350.92
  5154.3  350.77  5167.7  351.55  5198.5  352.62  5207.7  353.81  5211.3  353.66
#Mann= 3 ,-1 , 0
  4838.6     .16       0    5001     .07       0    5005     .16       0
Bank Sta=5001,5005
XS Rating Curve= 0 ,0
Exp/Cntr=0.3,0.1

Type RM Length L Ch R = 1 ,9925    ,480,480,480
BEGIN DESCRIPTION:
ALUM BRANCH 2 0
END DESCRIPTION:
XS GIS Cut Line= 2
      3550783.62     10406750.24      3550432.87     10406312.66
#Sta/Elev= 30
  4749.8  352.78  4806.9   352.8  4850.1   351.9  4899.7  349.85  4941.6  347.38
  4963.8  346.94  4970.2  344.43  4978.2  339.22  4984.6  332.73  4991.5  328.48
    4997  327.95  4997.2  327.45  5000.7  327.45    5001  327.95  5005.4  329.61
  5013.4     331  5027.8   336.4  5035.4  337.76  5042.2   337.2  5048.6  338.34
  5069.4  344.03  5098.2  344.98    5127  345.13  5133.4  345.82  5141.4  345.55
  5166.7  346.58  5211.8   348.3  5269.5  349.01  5304.7  350.37  5310.6  350.08
#Mann= 6 ,-1 , 0
  4749.8     .05       0  4941.6      .1       0    4997     .07       0
    5001      .1       0  5035.4     .12       0  5166.7     .16       0
Bank Sta=4997,5001
XS Rating Curve= 0 ,0
Exp/Cntr=0.3,0.1

Type RM Length L Ch R = 1 ,9445    ,369,369,369
BEGIN DESCRIPTION:
ALUM BRANCH 14 0
END DESCRIPTION:
XS GIS Cut Line= 2
      3550984.99     10406212.01      3550576.15     10405990.27
#Sta/Elev= 30
  4791.7     348  4823.7  347.21  4868.1  344.59  4949.2  341.11  4954.9  340.38
  4965.3  338.01    4971  334.81    4977   330.6  4987.2  327.54  4994.1  326.35
  4999.7  325.63  5012.8  325.55    5013  325.05  5016.5  325.05  5016.8  325.55
  5036.6  337.24  5045.3  338.28  5052.8  340.52  5074.7  342.07  5112.7  343.64
  5118.4   343.4  5124.9  344.35  5140.2  344.33  5147.6  345.28  5156.4  345.43
  5162.1  344.39    5184   345.3  5205.8  347.68  5243.9  348.59  5256.8  349.55
#Mann= 6 ,-1 , 0
  4791.7     .05       0  4868.1      .1       0  4994.1     .12       0
  5012.8     .07       0  5016.8     .12       0  5205.8     .16       0
Bank Sta=5012.8,5016.8
XS Rating Curve= 0 ,0
Exp/Cntr=0.3,0.1

Type RM Length L Ch R = 1 ,9076    ,256,256,256
BEGIN DESCRIPTION:
ALUM BRANCH 13 1
END DESCRIPTION:
XS GIS Cut Line= 3
      3551142.09     10405991.61      3551092.11     10405891.64
      3550842.12     10405691.66
#Sta/Elev= 30
  4872.8  342.32  4943.7  338.71  4962.2  337.52  4970.6   336.6  4981.8  327.89
  4987.8  327.89  4991.8   324.2  4996.2  323.56  4996.4  323.06  4999.9  323.06
  5000.2  323.56  5006.2  324.66  5012.6  327.82  5020.6  329.51    5027  335.03
    5035  334.19  5041.4  336.34  5048.1  336.25  5062.2  337.11  5105.4  338.45
  5119.8  339.31  5140.6  339.75  5155.1  340.92  5176.7  342.08  5219.1  343.63
  5233.5  345.04  5257.6   346.5  5297.5  349.32  5301.5  349.91  5304.7  349.91
#Mann= 6 ,-1 , 0
  4872.8     .05       0  4943.7      .1       0  4996.2     .07       0
  5000.2      .1       0  5048.1     .12       0  5257.6     .16       0
Bank Sta=4996.2,5000.2
XS Rating Curve= 0 ,0
Exp/Cntr=0.3,0.1

Type RM Length L Ch R = 1 ,8820    ,155,155,155
BEGIN DESCRIPTION:
Mapping XS 936c7510
END DESCRIPTION:
XS GIS Cut Line= 4
      3551290.51     10406033.04      3551330.44     10405796.93
      3551221.07      10405675.4      3550935.86      10405530.2
#Sta/Elev= 30
  4698.5  346.29  4797.1  340.86    4847  338.85  4902.8  336.32  4947.4  335.45
  4954.8  332.39  4961.6  331.42    4969  326.02  4975.8  325.84  4983.2  322.21
    4990   322.4  4995.4  320.44  4995.7  319.94  4999.4  320.44  5004.2  320.79
  5011.7  325.38  5018.4  324.14  5025.8  329.64  5028.3  330.66  5032.6  332.41
  5039.3  332.17  5046.8  333.48  5053.5  333.35    5061  335.21  5067.7     335
  5075.2  336.48  5100.6  338.12  5302.5  342.92  5393.4  345.83  5421.5  347.75
#Mann= 6 ,-1 , 0
  4698.5     .05       0    4847      .1       0  4995.4     .07       0
  4999.4      .1       0  5028.3     .12       0  5393.4     .05       0
Bank Sta=4995.4,4999.4
XS Rating Curve= 0 ,0
Exp/Cntr=0.3,0.1

Type RM Length L Ch R = 1 ,8665    ,585,585,585
BEGIN DESCRIPTION:
ALUM BRANCH 12 1
END DESCRIPTION:
XS GIS Cut Line= 3
      3551571.74     10405880.23       3551323.5     10405557.34
      3551273.16     10405376.82
#Sta/Elev= 30
  4762.1  344.11  4803.5  342.05  4832.5  339.33  4874.1  337.08  4917.7  333.72
  4932.2  331.74    4953  332.09  4961.2  333.17  4967.5  332.43  4974.8  330.46
    4982  326.13  4988.3  324.48  4996.5  320.58  5000.8  319.46  5001.1  318.96
  5004.8  319.46    5011  319.58  5017.4  322.71  5025.9     328  5031.9  331.48
  5038.2  328.96  5055.3  328.36  5081.7  328.83  5096.2  331.34  5102.5  331.32
  5131.5  335.05  5146.1  337.62  5166.1  339.38    5192  341.31  5356.8  349.35
#Mann= 6 ,-1 , 0
  4762.1      .1       0  5000.8     .07       0  5004.8      .1       0
  5025.9     .16       0  5055.3     .12       0  5166.1     .05       0
Bank Sta=5000.8,5004.8
XS Rating Curve= 0 ,0
Exp/Cntr=0.3,0.1

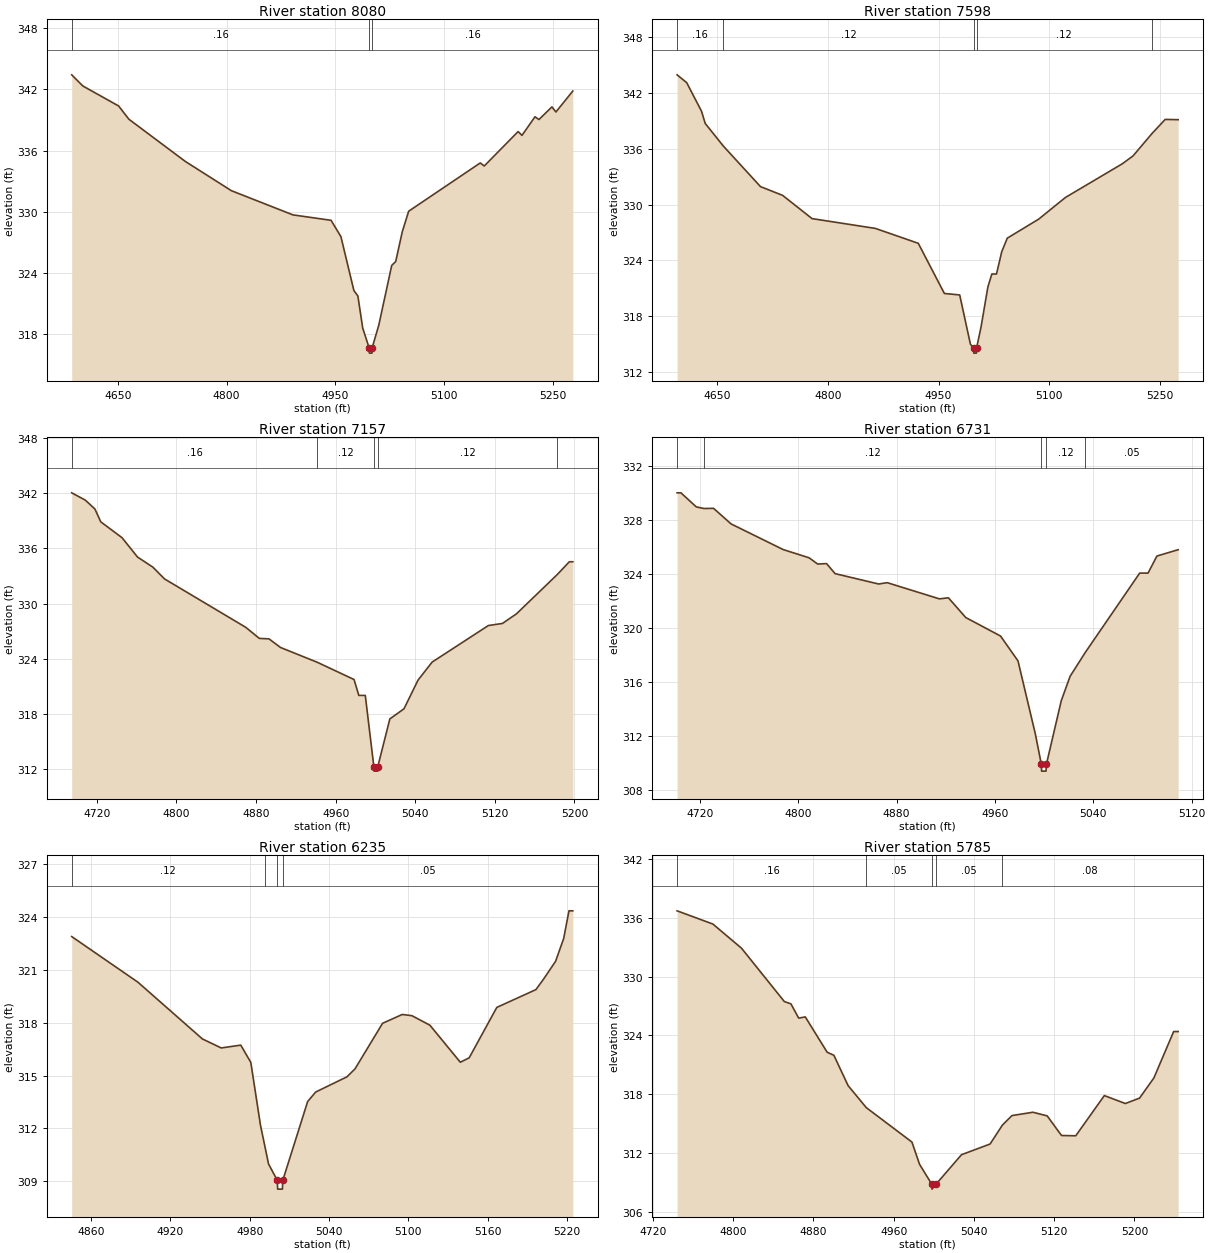
Type RM Length L Ch R = 1 ,8080    ,482,482,482
BEGIN DESCRIPTION:
ALUM BRANCH 11
END DESCRIPTION:
XS GIS Cut Line= 3
      3551736.71     10405947.94      3551957.18     10405717.06
      3552106.93     10405376.25
#Sta/Elev= 30
  4586.3  343.43  4601.6  342.34    4651  340.38  4665.2  339.08  4743.2  334.94
  4806.7  332.08  4891.6  329.71  4944.2  329.18  4957.8  327.58  4975.7   322.3
  4981.2  321.77  4987.9  318.62  4996.8  316.67  4997.1  316.17  5000.6  316.17
  5000.8  316.67    5010  318.89  5027.9  324.76  5033.4  325.14  5042.5  328.06
  5051.3  330.07  5150.1   334.8  5155.6   334.5  5202.3  337.87  5207.7   337.5
  5225.6  339.32  5231.1  339.05    5249  340.29  5254.5  339.79  5277.8  341.84
#Mann= 3 ,-1 , 0
  4586.3     .16       0  4996.8     .07       0  5000.8     .16       0
Bank Sta=4996.8,5000.8
XS Rating Curve= 0 ,0
Exp/Cntr=0.3,0.1

Type RM Length L Ch R = 1 ,7598    ,441,441,441
BEGIN DESCRIPTION:
ALUM BRANCH 10
END DESCRIPTION:
XS GIS Cut Line= 3
      3551879.08     10406055.61        3552136.     10406062.55
      3552472.81     10405807.33
#Sta/Elev= 30
  4595.3  343.94  4608.3   343.1  4628.3  340.05  4633.5  338.71  4658.1  336.28
  4708.4  331.93  4738.4  330.99  4778.4  328.49  4864.2  327.44  4922.4  325.84
  4957.8  320.45  4978.6  320.29  4993.1  315.01  4997.4  314.54  4997.7  314.04
  5001.2  314.04  5001.4  314.54  5007.7  316.92  5016.8  321.14  5022.2  322.54
  5028.5  322.54  5035.6  324.93  5043.1  326.39  5085.8  328.44  5122.1  330.77
  5199.1  334.38  5213.7  335.23  5239.6  337.65  5257.3  339.15  5274.9  339.12
#Mann= 5 ,-1 , 0
  4595.3     .16       0  4658.1     .12       0  4997.4     .07       0
  5001.4     .12       0  5239.6     .05       0
Bank Sta=4997.4,5001.4
XS Rating Curve= 0 ,0
Exp/Cntr=0.3,0.1

Type RM Length L Ch R = 1 ,7157    ,426,426,426
BEGIN DESCRIPTION:
ALUM BRANCH 9 0
END DESCRIPTION:
XS GIS Cut Line= 3
      3552242.09     10406441.65      3552492.11     10406291.64
      3552642.11     10406141.64
#Sta/Elev= 30
  4694.7  342.06  4708.3  341.27    4718   340.3  4723.9   338.9  4745.3  337.17
  4760.8  335.07  4776.3  333.96    4788  332.68  4869.6  327.41  4883.3   326.2
    4893  326.15  4904.6  325.21  4941.5   323.6  4978.5  321.72  4983.3  319.99
  4989.8  319.99  4998.4  312.24  4998.7  311.74  5002.2  311.74  5002.4  312.24
  5014.5  317.43  5028.7  318.53  5042.8  321.65    5057  323.62  5113.5   327.6
  5127.7  327.83  5141.8  328.88  5182.9  333.17  5194.9  334.55  5198.4  334.55
#Mann= 5 ,-1 , 0
  4694.7     .16       0  4941.5     .12       0  4998.4     .07       0
  5002.4     .12       0  5182.9     .05       0
Bank Sta=4998.4,5002.4
XS Rating Curve= 0 ,0
Exp/Cntr=0.3,0.1

Type RM Length L Ch R = 1 ,6731    ,496,496,496
BEGIN DESCRIPTION:
ALUM BRANCH 8 0
END DESCRIPTION:
XS GIS Cut Line= 3
       3552599.6       10406771.      3552876.97     10406506.77
      3552894.31     10406489.44
#Sta/Elev= 30
  4701.4  330.01  4704.5  330.01    4717  328.97  4723.2  328.85  4731.1  328.86
  4745.3  327.71  4787.7  325.81  4808.8   325.2  4815.7  324.74    4823  324.77
  4829.9  324.03  4865.4  323.26  4872.3  323.36  4914.8  322.16  4922.1  322.24
  4936.2  320.78  4964.5  319.41  4978.7  317.57  4992.8  312.17  4997.7  309.91
  4997.9  309.41  5001.5  309.41  5001.8  309.91  5013.9  314.62  5021.1  316.43
  5033.4  318.19  5077.7  324.07  5084.5  324.07  5091.7  325.33    5109   325.8
#Mann= 5 ,-1 , 0
  4701.4     .16       0  4723.2     .12       0  4997.7     .07       0
  5001.8     .12       0  5033.4     .05       0
Bank Sta=4997.7,5001.8
XS Rating Curve= 0 ,0
Exp/Cntr=0.3,0.1

Type RM Length L Ch R = 1 ,6235    ,450,450,450
BEGIN DESCRIPTION:
ALUM BRANCH 5 2
END DESCRIPTION:
XS GIS Cut Line= 2
      3552971.05     10407059.09      3553281.86     10406842.04
#Sta/Elev= 30
  4845.3  322.89  4895.4   320.3  4944.2  317.08  4958.4  316.57  4973.2  316.73
  4980.8  315.75  4988.1  312.19  4991.3  311.04  4994.2  309.99  5000.8  309.06
  5001.1  308.56  5004.7  308.56    5005  309.06  5023.8  313.53  5029.9  314.07
  5053.5  314.93  5059.6  315.38  5080.5  317.97  5095.4  318.47  5102.7   318.4
  5116.3  317.86  5139.3  315.76    5146  316.01  5166.9  318.87  5196.5  319.88
  5202.6  320.51  5211.4  321.49  5217.5  322.78  5221.5  324.35  5224.4  324.35
#Mann= 4 ,-1 , 0
  4845.3     .12       0  4991.3     .05       0  5000.8     .04       0
    5005     .05       0
Bank Sta=5000.8,5005
XS Rating Curve= 0 ,0
Exp/Cntr=0.3,0.1

Type RM Length L Ch R = 1 ,5785    ,208,208,208
BEGIN DESCRIPTION:
ALUM BRANCH 7 1
END DESCRIPTION:
XS GIS Cut Line= 2
       3553158.6      10407508.7      3553535.26     10407180.64
#Sta/Elev= 30
  4744.1   336.7  4779.8  335.35  4808.3  332.89    4851  327.45  4857.6  327.21
  4865.3  325.76  4871.9  325.88  4893.7  322.28  4900.4  321.97  4914.6  318.87
  4932.7  316.63  4978.2  313.12  4985.8  310.85    4998  308.82  4998.2  308.32
  5002.2  308.82  5027.6  311.83  5056.1  312.92  5068.4  314.85  5077.9  315.82
  5098.8  316.16    5113  315.79  5127.3  313.79  5141.5  313.76    5170  317.86
  5190.9  317.05  5205.1   317.6  5219.4  319.66  5239.1  324.39  5243.6  324.39
#Mann= 5 ,-1 , 0
  4744.1     .16       0  4932.7     .05       0    4998     .04       0
  5002.2     .05       0  5068.4     .08       0
Bank Sta=4998,5002.2
XS Rating Curve= 0 ,0
Exp/Cntr=0.3,0.1

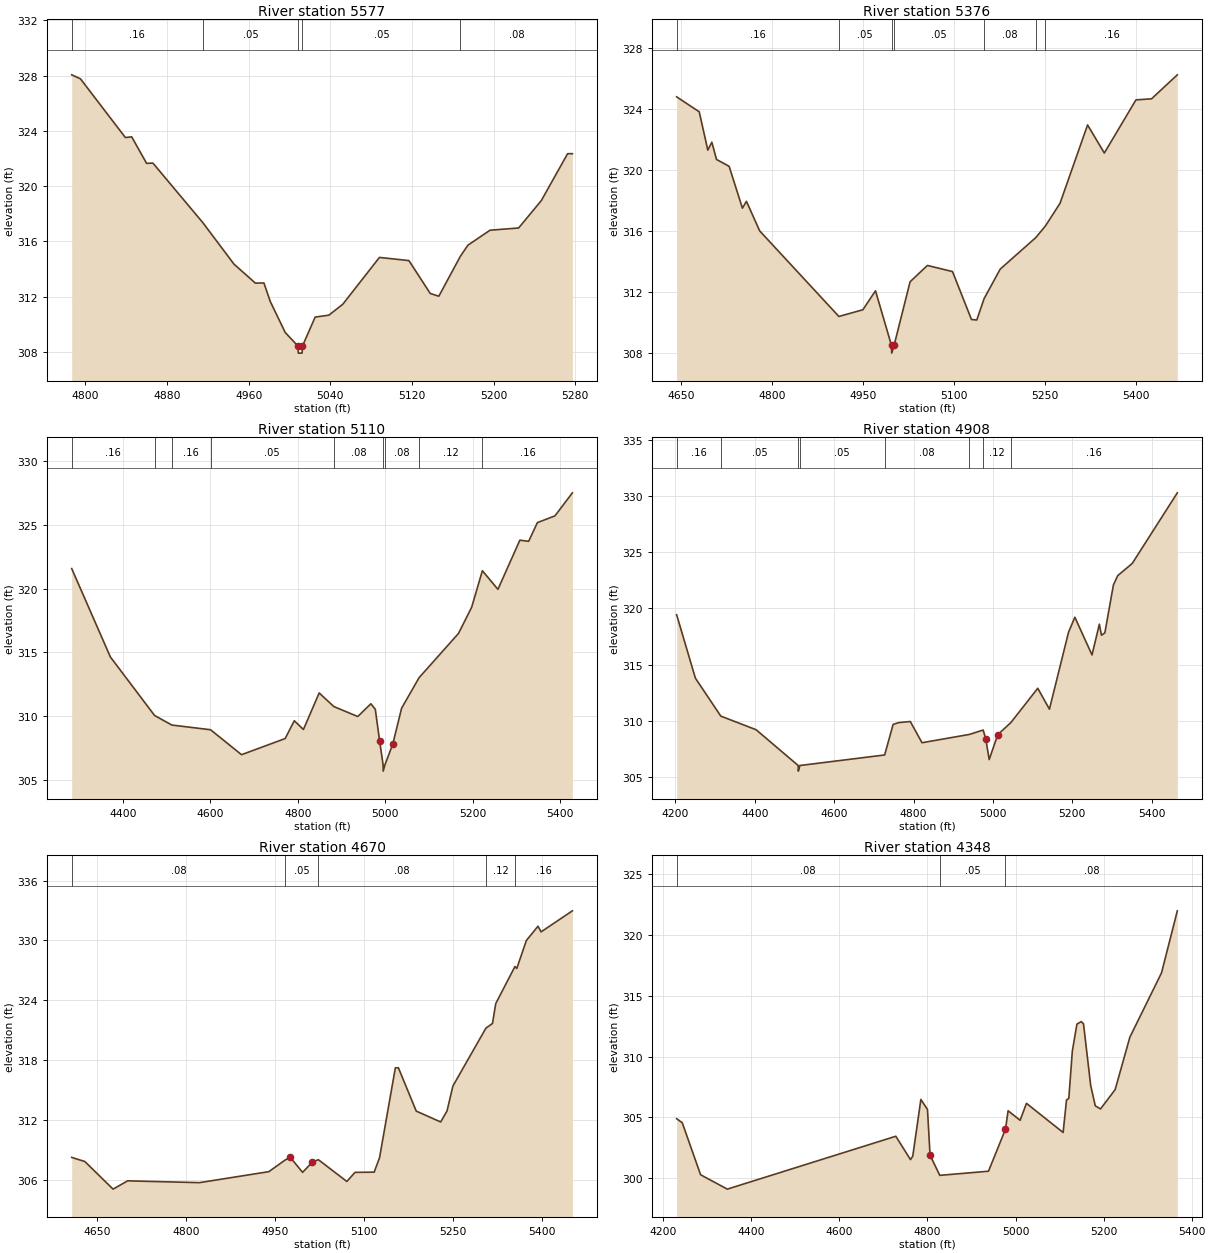
Type RM Length L Ch R = 1 ,5577    ,201,201,201
BEGIN DESCRIPTION:
ALUM BRANCH 6 0
END DESCRIPTION:
XS GIS Cut Line= 2
      3553288.76     10407640.68      3553684.63     10407350.73
#Sta/Elev= 30
  4786.5  328.05  4795.1  327.76  4839.1  323.51  4845.3  323.56  4859.9  321.64
  4866.1  321.66  4915.1  317.34  4945.6  314.34  4966.5  312.97  4974.9  312.98
  4981.1  311.64  4995.8  309.39  5008.4   308.4  5008.6   307.9  5012.3   307.9
  5012.6   308.4  5025.1  310.51  5038.6  310.65  5052.2  311.44  5088.1  314.83
    5117   314.6  5137.9  312.22  5146.3  312.02  5167.4  314.91  5174.9  315.72
  5196.5   316.8  5224.5  316.96  5246.7  318.94  5272.5  322.34  5277.2  322.34
#Mann= 5 ,-1 , 0
  4786.5     .16       0  4915.1     .05       0  5008.4     .04       0
  5012.6     .05       0  5167.4     .08       0
Bank Sta=5008.4,5012.6
XS Rating Curve= 0 ,0
Exp/Cntr=0.3,0.1

Type RM Length L Ch R = 1 ,5376    ,266,266,266
BEGIN DESCRIPTION:
ALUM BRANCH 6 1
END DESCRIPTION:
XS GIS Cut Line= 3
      3553328.69     10407890.69      3553644.68     10407616.37
      3553759.14     10407226.16
#Sta/Elev= 30
  4642.5   324.8  4679.7  323.82  4693.9  321.31  4700.5  321.83  4708.2   320.7
    4729  320.25  4750.9  317.51  4757.5  317.96  4779.4  316.02  4909.9  310.42
  4949.4  310.86  4970.2   312.1  4996.6  308.52  4996.9  308.02  5000.8  308.52
  5027.2  312.69  5055.7  313.76  5097.1  313.36  5128.4  310.22  5137.1  310.19
  5149.2  311.59  5175.7  313.52  5234.5  315.59  5250.3  316.35  5274.3  317.83
  5319.7  322.96  5347.3  321.12  5399.4   324.6  5425.1  324.67  5467.6  326.24
#Mann= 7 ,-1 , 0
  4642.5     .16       0  4909.9     .05       0  4996.6     .04       0
  5000.8     .05       0  5149.2     .08       0  5234.5     .05       0
  5250.3     .16       0
Bank Sta=4996.6,5000.8
XS Rating Curve= 0 ,0
Exp/Cntr=0.3,0.1

Type RM Length L Ch R = 1 ,5110    ,202,202,202
BEGIN DESCRIPTION:
Mapping XS e46bcd5d
END DESCRIPTION:
XS GIS Cut Line= 3
      3553321.76     10408154.57      3553807.87     10407784.77
      3553839.12     10407251.77
#Sta/Elev= 30
  4282.9  321.57  4371.3  314.63  4472.4  310.03  4511.8  309.28  4600.4  308.91
  4671.2  306.95    4771  308.22  4791.8  309.62  4812.7  308.93  4848.7   311.8
  4882.3  310.73  4936.9  309.95  4966.9  310.95    4977  310.52    4987  308.01
  4994.8  306.16  4995.1  305.66  4999.1  306.16    5017  307.78  5037.1   310.6
  5077.1     313  5167.3  316.48  5197.3  318.53  5221.8   321.4  5257.4  319.94
  5307.5   323.8  5327.6  323.71  5347.6  325.18  5387.7  325.71  5427.6  327.52
#Mann= 9 ,-1 , 0
  4282.9     .16       0  4472.4     .05       0  4511.8     .16       0
  4600.4     .05       0  4882.3     .08       0  4994.8     .07       0
  4999.1     .08       0  5077.1     .12       0  5221.8     .16       0
Bank Sta=4987,5017
XS Rating Curve= 0 ,0
Exp/Cntr=0.3,0.1

Type RM Length L Ch R = 1 ,4908    ,238,238,238
BEGIN DESCRIPTION:
ALUM BRANCH 5 1
END DESCRIPTION:
XS GIS Cut Line= 3
       3553363.4     10408159.78       3553891.2     10408013.94
      3554160.31     10407352.46
#Sta/Elev= 30
  4203.1  319.44  4250.4  313.79  4314.4  310.41  4403.3   309.2  4509.4  306.01
  4509.7  305.51  4513.7  306.01  4727.3  306.95  4748.6  309.67  4762.5  309.83
  4791.9  309.93  4821.4  308.04  4940.9  308.78  4975.5  309.17    4982  308.39
  4990.7  306.54  5012.3  308.76  5045.2  309.83  5113.1  312.89  5142.5  311.03
  5190.7  317.89  5206.6  319.22  5249.8  315.86  5268.3   318.6  5273.7  317.61
  5282.2  317.83  5303.7  322.09  5314.5  322.92  5351.2  324.01  5464.8   330.3
#Mann= 8 ,-1 , 0
  4203.1     .16       0  4314.4     .05       0  4509.4     .07       0
  4513.7     .05       0  4727.3     .08       0  4940.9     .16       0
  4975.5     .12       0  5045.2     .16       0
Bank Sta=4982,5012.3
XS Rating Curve= 0 ,0
Exp/Cntr=0.3,0.1

Type RM Length L Ch R = 1 ,4670    ,322,322,322
BEGIN DESCRIPTION:
ALUM BRANCH 5 0
END DESCRIPTION:
XS GIS Cut Line= 3
      3553999.69     10408139.97      3554219.22     10407814.12
      3554330.32     10407376.29
#Sta/Elev= 30
  4607.1  308.26  4629.2  307.85  4676.9  305.08  4701.5  305.91  4822.7  305.73
  4939.6  306.83  4966.8  307.98  4975.6  308.28  4996.6  306.76  5012.9  307.78
  5023.2  308.03  5071.2  305.85  5085.1  306.76  5117.3  306.78  5126.4  308.23
  5153.1  317.24  5158.2  317.24  5188.3   312.9  5229.5  311.81  5240.2  312.91
  5250.2  315.42  5305.9  321.22  5316.9  321.68  5322.4  323.67  5354.8  327.39
  5357.9  327.19    5374  329.99  5393.7  331.43  5398.9  330.86  5451.7  332.97
#Mann= 5 ,-1 , 0
  4607.1     .08       0  4966.8     .05       0  5023.2     .08       0
  5305.9     .12       0  5354.8     .16       0
Bank Sta=4975.6,5012.9
XS Rating Curve= 0 ,0
Exp/Cntr=0.3,0.1

Type RM Length L Ch R = 1 ,4348    ,271,271,271
BEGIN DESCRIPTION:
Mapping XS 68e69a66
END DESCRIPTION:
XS GIS Cut Line= 2
      3554316.55     10408593.82      3554637.43     10407502.82
#Sta/Elev= 30
  4230.3   304.9    4243  304.57  4284.7   300.3  4345.4  299.12  4728.1  303.46
  4761.4  301.54  4766.6  301.83    4785  306.48    4800  305.66  4805.9   301.9
    4828  300.25  4938.6  300.59  4977.2  304.04  4983.1  305.55  5010.5  304.77
  5024.8  306.16  5108.1  303.77  5115.8  306.44    5121  306.56    5129  310.44
  5139.4  312.66  5149.2  312.87  5154.4  312.69  5170.7  307.63  5181.1  305.96
    5193   305.7  5226.3  307.29  5259.7  311.59  5331.6  316.87  5367.5  321.96
#Mann= 3 ,-1 , 0
  4230.3     .08       0    4828     .05       0  4977.2     .08       0
Bank Sta=4805.9,4977.2
XS Rating Curve= 0 ,0
Exp/Cntr=0.3,0.1

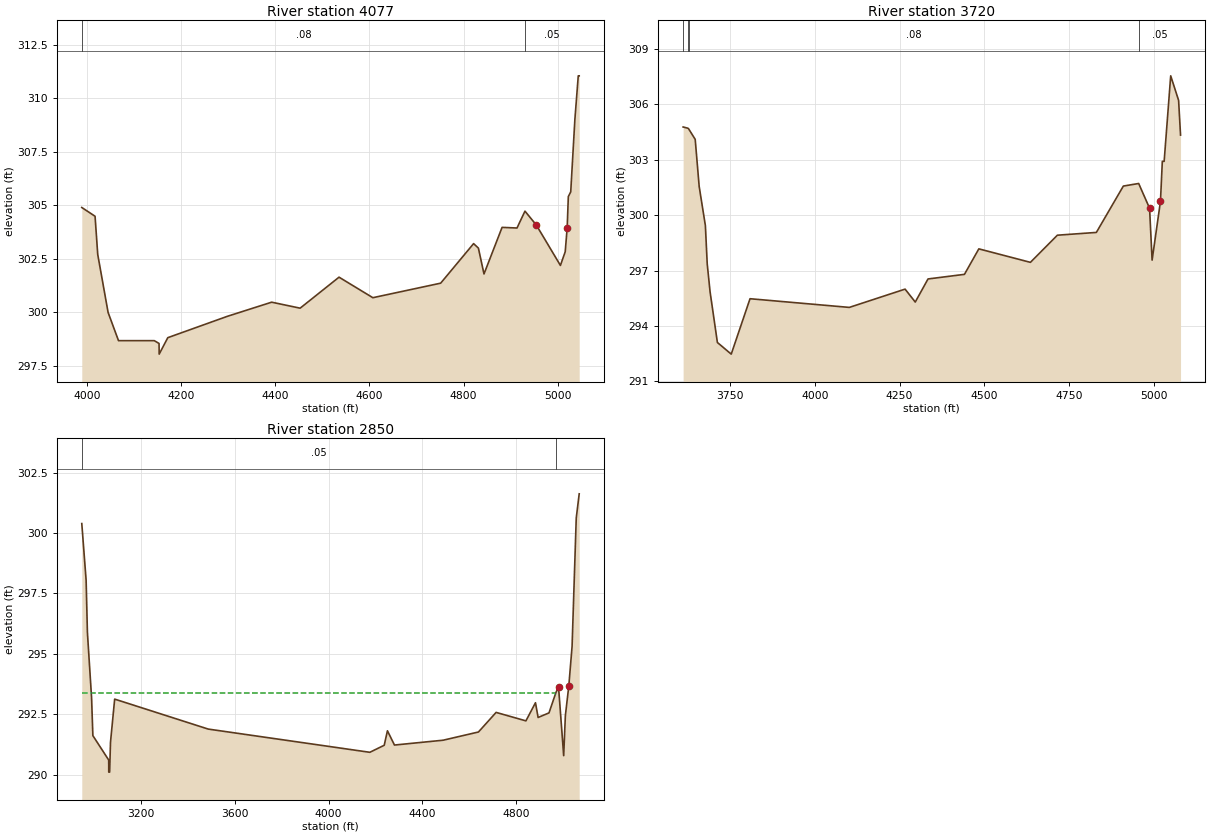
Type RM Length L Ch R = 1 ,4077    ,357,357,357
BEGIN DESCRIPTION:
Mapping XS 1175b6f3
END DESCRIPTION:
XS GIS Cut Line= 3
      3554372.09       10408698.      3554710.65     10408052.13
      3554781.83     10407732.69
#Sta/Elev= 30
    3989   304.9  4017.2  304.49  4022.9   302.7  4044.9  299.99    4067  298.67
    4143  298.67  4153.1  298.54  4153.4  298.04  4171.7  298.81  4298.4  299.81
  4392.3  300.47  4452.8  300.19  4535.4  301.64  4607.2  300.68  4751.3  301.36
  4821.2  303.21  4831.4     303  4843.3  301.79  4881.7  303.97  4913.4  303.94
  4930.3  304.73  4954.4  304.08  5005.6  302.19  5015.8  302.83    5020  303.96
  5022.4  305.41  5027.5  305.63  5036.3  309.01  5043.5  311.06  5045.5  311.06
#Mann= 2 ,-1 , 0
    3989     .08       0  4930.3     .05       0
#XS Ineff= 2 , 0
       0 4785.08  302.04               0
Permanent Ineff=
       T       F
Bank Sta=4954.4,5020
XS Rating Curve= 0 ,0
Exp/Cntr=0.3,0.1

Type RM Length L Ch R = 1 ,3720    ,870,870,870
BEGIN DESCRIPTION:
ALUM BRANCH 4 1
END DESCRIPTION:
XS GIS Cut Line= 2
      3554632.88     10409095.85      3555156.22     10407726.33
#Sta/Elev= 30
  3612.2  304.78  3626.7  304.71  3628.4  304.68  3647.8  304.11  3659.5  301.56
  3677.8  299.44  3683.2  297.37  3691.6  295.86  3713.2  293.11    3754  292.48
  3809.4  295.48    4102  295.01  4266.4     296  4296.4   295.3    4334  296.55
  4441.4   296.8  4483.8  298.18  4635.8  297.45  4715.3  298.92  4830.2  299.07
  4909.7  301.58  4954.9  301.72    4987  300.38  4994.5  297.57  5019.1  300.75
  5024.6  302.92    5030  302.92  5049.3  307.55  5072.6  306.22  5078.3  304.34
#Mann= 4 ,-1 , 0
  3612.2     .05       0  3626.7     .08       0  3628.4     .08       0
  4954.9     .05       0
#XS Ineff= 2 , 0
       0 4719.17  298.86               0
Permanent Ineff=
       T       F
Bank Sta=4987,5019.1
XS Rating Curve= 0 ,0
Exp/Cntr=0.3,0.1

Type RM Length L Ch R = 1 ,2850    ,0,0,0
BEGIN DESCRIPTION:
ALUM BRANCH 2 2
END DESCRIPTION:
XS GIS Cut Line= 2
      3555148.51     10409791.17      3556010.46     10407851.13
#Sta/Elev= 30
  2946.5  300.39    2965  298.05  2970.5  295.89  2988.3  293.18  2993.8  291.62
  3061.4  290.61  3061.6  290.11  3065.4  290.11    3069  291.34  3086.8  293.13
  3486.3  291.89  4175.8  290.93  4237.2  291.22    4251  291.82    4281  291.23
  4488.9  291.43  4639.5  291.77  4714.8  292.58    4842  292.23  4882.8  292.98
    4894  292.37  4940.5  292.56  4970.4  293.41  4981.3  293.62  5003.2  290.79
  5010.3  292.44  5025.1  293.68    5039  295.31  5056.8  300.62  5069.4  301.62
#Mann= 2 ,-1 , 0
  2946.5     .05       0  4970.4     .03       0
#XS Ineff= 2 , 0
       0 4966.96   293.4               0
Permanent Ineff=
       T       F
Bank Sta=4981.3,5025.1
XS Rating Curve= 0 ,0
Exp/Cntr=0.3,0.1

Chan Stop Cuts=-1
Use User Specified Reach Order=0
Composite Channel Slope=5