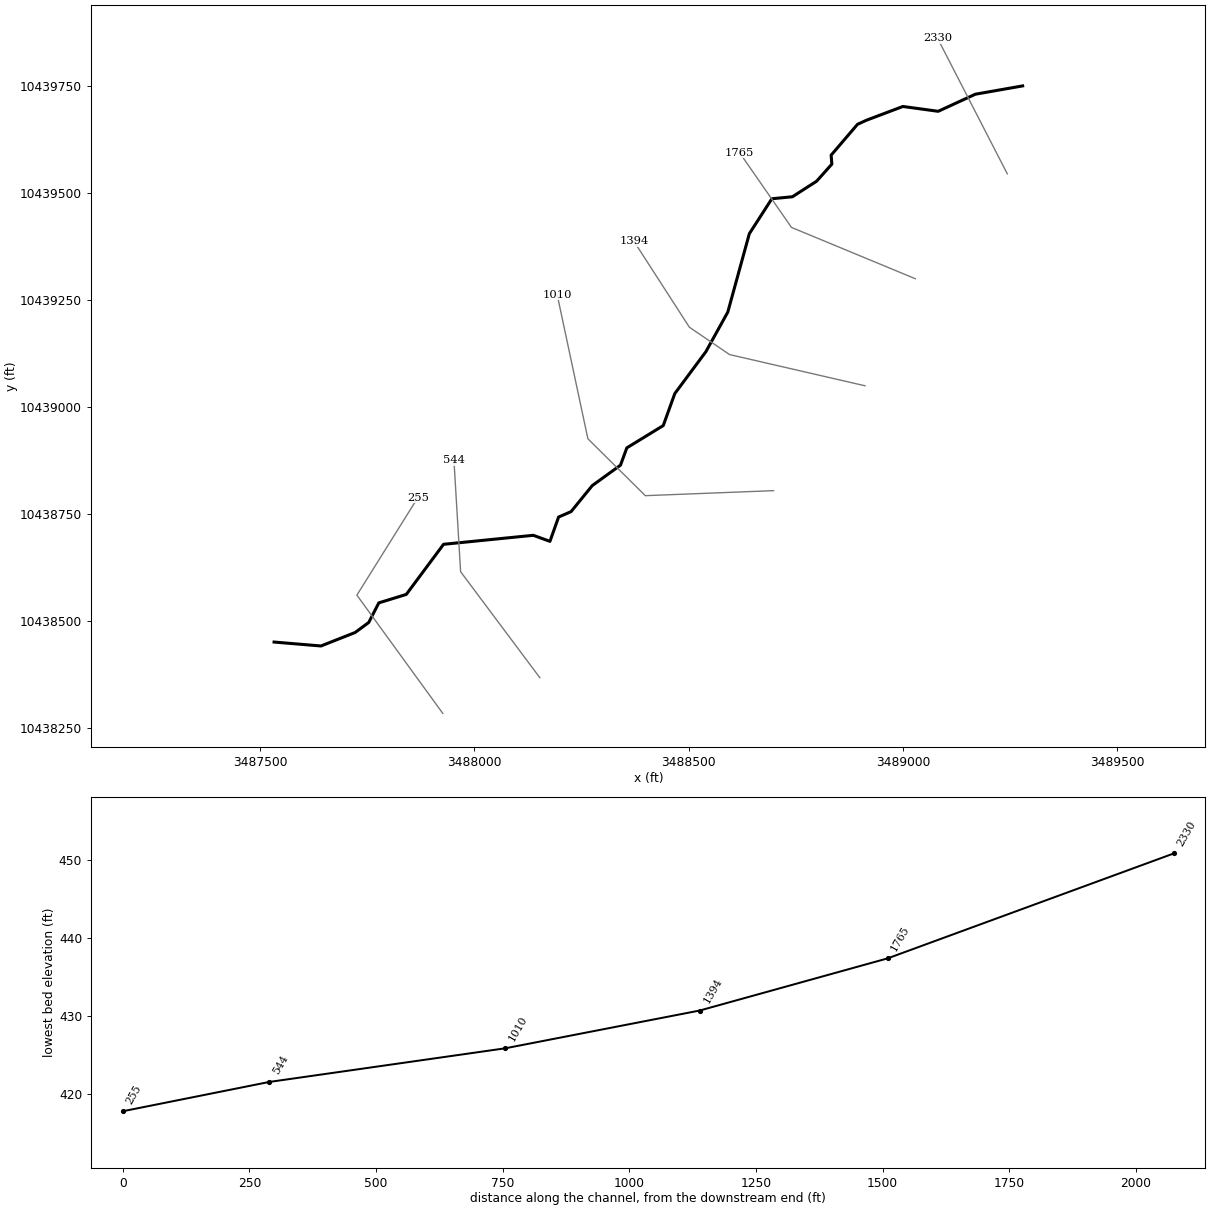
--- BEAR CREEK TRIB 1 1.prj (project) ---

Proj Title=BEAR CREEK TRIB 1 1 Base Level Engineering
Current Plan=p01
Default Exp/Contr=0.3,0.1
English Units
Geom File=g01
Flow File=f01
Plan File=p01
BEGIN DESCRIPTION:
BEAR CREEK TRIB 1 1
END DESCRIPTION:

--- BEAR CREEK TRIB 1 1.p01 (plan) ---

Plan Title=Multiple Run
Short Identifier=Multiple
Geom File=g01
Flow File=f01
Subcritical Flow
K Sum by GR= 0
Std Step Tol= 0.01
Critical Tol= 0.01
Num of Std Step Trials= 20
Max Error Tol= 0.3
Flow Tol Ratio= 0.001
Split Flow NTrial= 30
Split Flow Tol= 0.02
Split Flow Ratio= 0.02
Log Output Level= 0
Friction Slope Method= 1
Unsteady Friction Slope Method= 2
Unsteady Bridges Friction Slope Method= 1
Parabolic Critical Depth
Global Vel Dist=  1 , 1 , 1
Global Log Level= 0
CheckData=True
Encroach Param= -1, 0, 0, 0
BEGIN DESCRIPTION:
Multiple Run
END DESCRIPTION:

--- BEAR CREEK TRIB 1 1.f01 (steady flow) ---

Flow Title=Multiple
Number of Profiles=7
Profile Names=10-year,25-year,50-year,1pct_min,100-year,1pct_plu,500-year
River Rch & RM= BEAR CREEK TRIB ,Reach-1,2330
     252     319     369     315     425     575     560
Boundary for River Rch & Prof#=BEAR CREEK TRIB ,Reach-1,1
Up Type=0
Dn Type=3
Dn Slope=0.005
Boundary for River Rch & Prof#=BEAR CREEK TRIB ,Reach-1,2
Up Type=0
Dn Type=3
Dn Slope=0.005
Boundary for River Rch & Prof#=BEAR CREEK TRIB ,Reach-1,3
Up Type=0
Dn Type=3
Dn Slope=0.005
Boundary for River Rch & Prof#=BEAR CREEK TRIB ,Reach-1,4
Up Type=0
Dn Type=3
Dn Slope=0.005
Boundary for River Rch & Prof#=BEAR CREEK TRIB ,Reach-1,5
Up Type=0
Dn Type=3
Dn Slope=0.005
Boundary for River Rch & Prof#=BEAR CREEK TRIB ,Reach-1,6
Up Type=0
Dn Type=3
Dn Slope=0.005
Boundary for River Rch & Prof#=BEAR CREEK TRIB ,Reach-1,7
Up Type=0
Dn Type=3
Dn Slope=0.005

--- BEAR CREEK TRIB 1 1.g01 (geometry) ---

Geom Title=Existing Conditions

River Reach=BEAR CREEK TRIB ,Reach-1
Reach XY= 30
      3489279.78     10439750.04      3489169.44     10439730.66
      3489082.63     10439690.73      3489000.17     10439702.01
      3488915.10     10439669.89      3488894.27     10439660.34
      3488832.63     10439588.30      3488834.37     10439567.46
      3488798.78     10439527.53      3488742.26     10439491.23
      3488694.23     10439486.58      3488641.71     10439404.98
      3488591.36     10439221.82      3488540.15     10439129.38
      3488467.66     10439031.72      3488440.75     10438957.07
      3488355.69     10438904.98      3488340.93     10438864.62
      3488274.96     10438816.88      3488225.48     10438756.11
      3488196.40     10438743.52      3488176.16     10438686.71
      3488137.32     10438700.85      3487927.84     10438679.87
      3487840.80     10438562.83      3487776.68     10438543.12
      3487753.11     10438497.33      3487721.37     10438473.92
      3487641.61     10438442.47      3487532.11     10438451.64

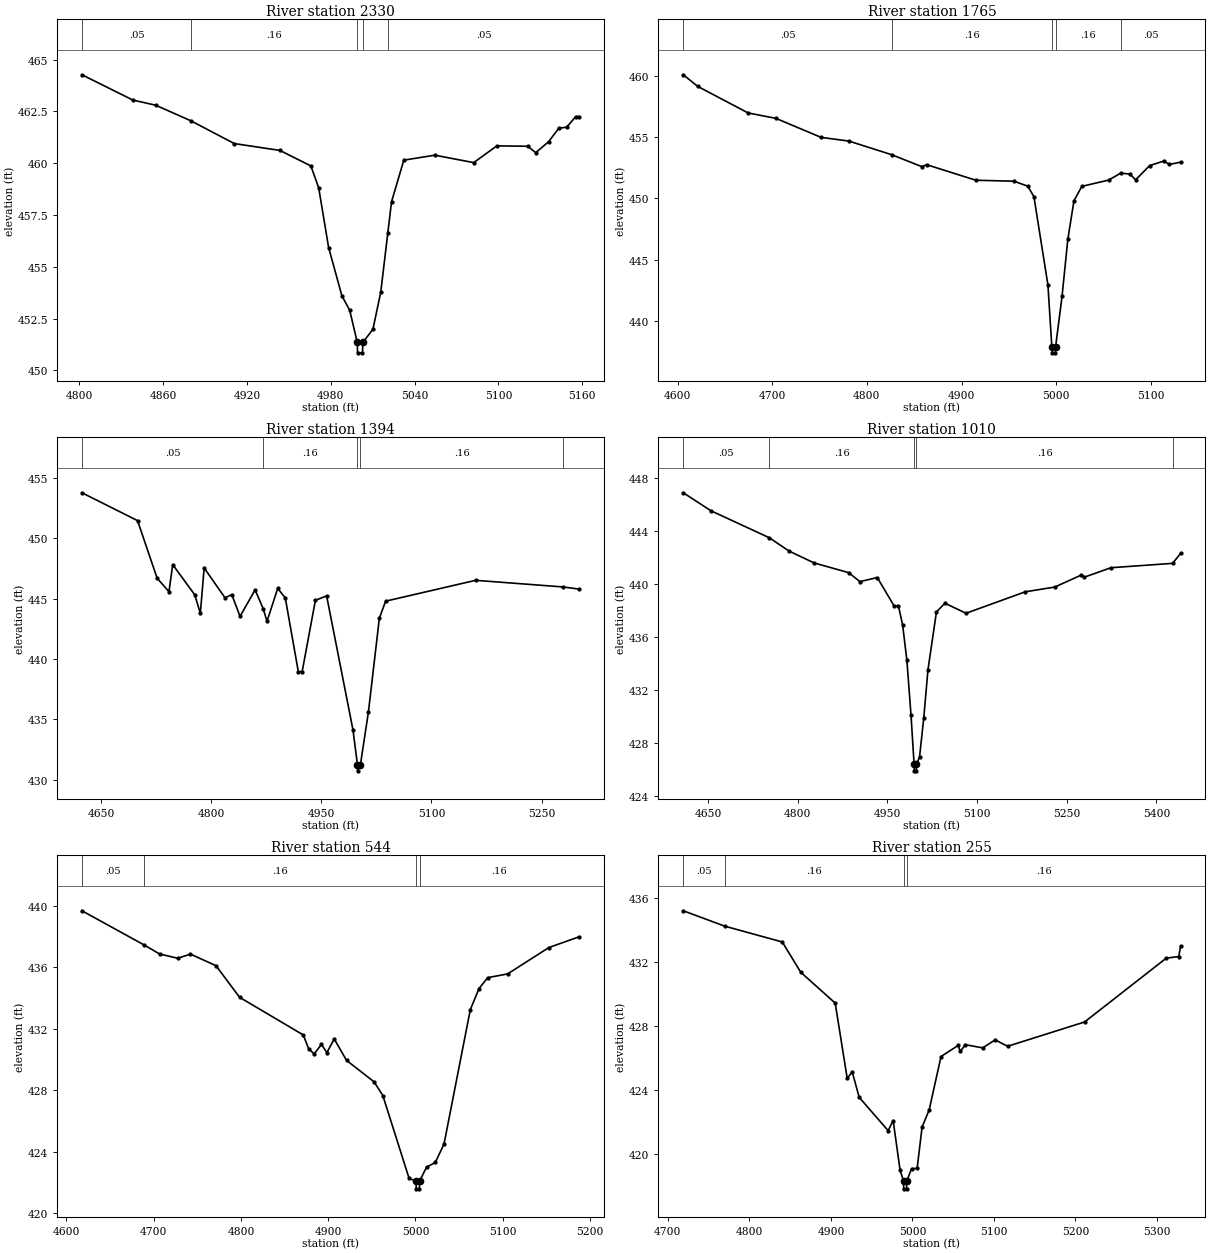
Type RM Length L Ch R = 1,2330,565,565,565
BEGIN DESCRIPTION:
BEAR CREEK TRIB 1 11 0
END DESCRIPTION:
XS GIS Cut Line= 2
      3489243.94     10439544.70      3489081.19     10439861.09
#Sta/Elev= 30
  4802.0  464.27  4838.4  463.05  4854.8  462.80  4879.9  462.05  4911.0  460.95
  4943.6  460.62  4965.8  459.87  4971.4  458.81  4978.5  455.93  4988.0  453.60
  4993.6  452.90  4999.0  451.35  4999.2  450.85  5002.7  450.85  5003.0  451.35
  5010.2  451.99  5015.8  453.78  5020.8  456.61  5023.5  458.14  5032.3  460.15
  5054.5  460.39  5082.3  460.03  5098.9  460.84  5121.0  460.82  5126.7  460.51
  5135.9  461.04  5143.2  461.69  5148.8  461.74  5155.3  462.25  5157.8  462.25
#Mann=5,-1,0
  4802.0    0.05       0  4879.9    0.16       0  4999.0    0.07       0
  5003.0    0.16       0  5020.8    0.05       0
Bank Sta=4999,5003
Exp/Cntr=0.3,0.1

Type RM Length L Ch R = 1,1765,371,371,371
BEGIN DESCRIPTION:
BEAR CREEK TRIB 1 10 0
END DESCRIPTION:
XS GIS Cut Line= 3
      3489029.12     10439299.89      3488740.04     10439419.69
      3488618.95     10439594.17
#Sta/Elev= 30
  4606.1  460.06  4621.4  459.11  4674.6  456.95  4703.9  456.51  4751.7  454.96
  4781.0  454.66  4826.2  453.55  4858.0  452.58  4863.4  452.73  4915.2  451.47
  4955.5  451.39  4970.1  450.98  4976.5  450.13  4991.3  442.93  4995.4  437.91
  4995.7  437.41  4999.2  437.41  4999.4  437.91  5006.2  442.00  5012.3  446.65
  5018.8  449.80  5027.1  450.97  5055.3  451.48  5068.1  452.04  5077.8  451.98
  5083.9  451.50  5098.7  452.66  5113.6  453.03  5119.7  452.76  5131.4  452.94
#Mann=5,-1,0
  4606.1    0.05       0  4826.2    0.16       0  4995.4    0.07       0
  4999.4    0.16       0  5068.1    0.05       0
Bank Sta=4995.4,4999.4
Exp/Cntr=0.3,0.1

Type RM Length L Ch R = 1,1394,384,384,384
BEGIN DESCRIPTION:
BEAR CREEK TRIB 1 1 5 0
END DESCRIPTION:
XS GIS Cut Line= 4
      3488911.91     10439049.90      3488595.51     10439122.81
      3488501.76     10439186.62      3488372.13     10439387.54
#Sta/Elev= 30
  4624.0  453.79  4699.7  451.48  4726.4  446.70  4742.5  445.59  4747.6  447.83
  4777.7  445.32  4785.2  443.78  4790.4  447.56  4818.8  445.08  4828.0  445.35
  4839.3  443.54  4859.8  445.74  4870.9  444.16  4876.0  443.13  4890.6  445.86
  4900.9  445.07  4918.7  438.94  4923.9  438.96  4941.9  444.87  4957.2  445.24
  4993.1  434.12  4999.2  431.23  4999.4  430.73  5003.2  431.23  5014.1  435.60
  5029.0  443.38  5037.5  444.80  5160.1  446.53  5279.3  445.98  5301.2  445.80
#Mann=5,-1,0
  4624.0    0.05       0  4870.9    0.16       0  4999.2    0.07       0
  5003.2    0.16       0  5279.3    0.05       0
Bank Sta=4999.2,5003.2
Exp/Cntr=0.3,0.1

Type RM Length L Ch R = 1,1010,466,466,466
BEGIN DESCRIPTION:
BEAR CREEK TRIB 1 1 3 0
END DESCRIPTION:
XS GIS Cut Line= 4
      3488698.37     10438805.10      3488398.90     10438793.39
      3488264.78     10438926.20      3488193.17     10439262.10
#Sta/Elev= 30
  4608.4  446.89  4654.7  445.53  4752.5  443.49  4784.8  442.50  4827.3  441.59
  4884.9  440.86  4904.0  440.18  4932.9  440.49  4961.1  438.34  4968.2  438.37
  4975.3  436.91  4982.4  434.26  4989.4  430.07  4994.5  426.39  4994.8  425.89
  4998.3  425.89  4998.5  426.39  5003.6  426.93  5010.7  429.89  5017.7  433.52
  5031.9  437.89  5046.0  438.55  5081.4  437.79  5180.4  439.41  5229.9  439.77
  5274.3  440.68  5279.5  440.52  5323.9  441.23  5427.0  441.56  5440.3  442.31
#Mann=5,-1,0
  4608.4    0.05       0  4752.5    0.16       0  4994.5    0.07       0
  4998.5    0.16       0  5427.0    0.05       0
Bank Sta=4994.5,4998.5
Exp/Cntr=0.3,0.1

Type RM Length L Ch R = 1,544,289,289,289
BEGIN DESCRIPTION:
BEAR CREEK TRIB 1 1 2 0
END DESCRIPTION:
XS GIS Cut Line= 3
      3488152.56     10438368.46      3487967.67     10438615.85
      3487952.05     10438876.23
#Sta/Elev= 30
  4617.9  439.67  4689.0  437.45  4706.8  436.86  4727.6  436.58  4742.2  436.85
  4771.4  436.10  4798.5  434.04  4871.5  431.59  4877.7  430.68  4884.0  430.36
  4892.3  430.98  4898.5  430.44  4906.9  431.33  4921.0  429.94  4952.6  428.54
  4962.6  427.65  4992.7  422.26  5000.7  422.08  5000.9  421.58  5004.4  421.58
  5004.7  422.08  5012.7  422.99  5022.7  423.30  5032.7  424.49  5062.8  433.23
  5072.8  434.61  5082.8  435.32  5105.5  435.56  5152.9  437.28  5187.6  437.98
#Mann=4,-1,0
  4617.9    0.05       0  4689.0    0.16       0  5000.7    0.07       0
  5004.7    0.16       0
Bank Sta=5000.7,5004.7
Exp/Cntr=0.3,0.1

Type RM Length L Ch R = 1,255,0,0,0
BEGIN DESCRIPTION:
BEAR CREEK TRIB 1 1 1 0
END DESCRIPTION:
XS GIS Cut Line= 3
      3487926.00     10438285.12      3487725.48     10438561.16
      3487867.91     10438789.03
#Sta/Elev= 30
  4719.0  435.21  4769.7  434.25  4840.4  433.26  4863.0  431.37  4905.3  429.44
  4920.0  424.74  4926.2  425.14  4934.7  423.55  4970.2  421.47  4976.4  422.10
  4984.9  418.99  4989.1  418.33  4989.3  417.83  4992.8  417.83  4993.1  418.33
  4999.0  419.09  5005.8  419.11  5011.9  421.70  5020.5  422.75  5035.1  426.10
  5056.0  426.79  5058.8  426.42  5064.9  426.84  5086.2  426.64  5101.5  427.14
  5116.8  426.74  5211.2  428.26  5311.4  432.25  5326.7  432.35  5328.9  432.99
#Mann=4,-1,0
  4719.0    0.05       0  4769.7    0.16       0  4989.1    0.07       0
  4993.1    0.16       0
Bank Sta=4989.1,4993.1
Exp/Cntr=0.3,0.1

Chan Stop Cuts=-1