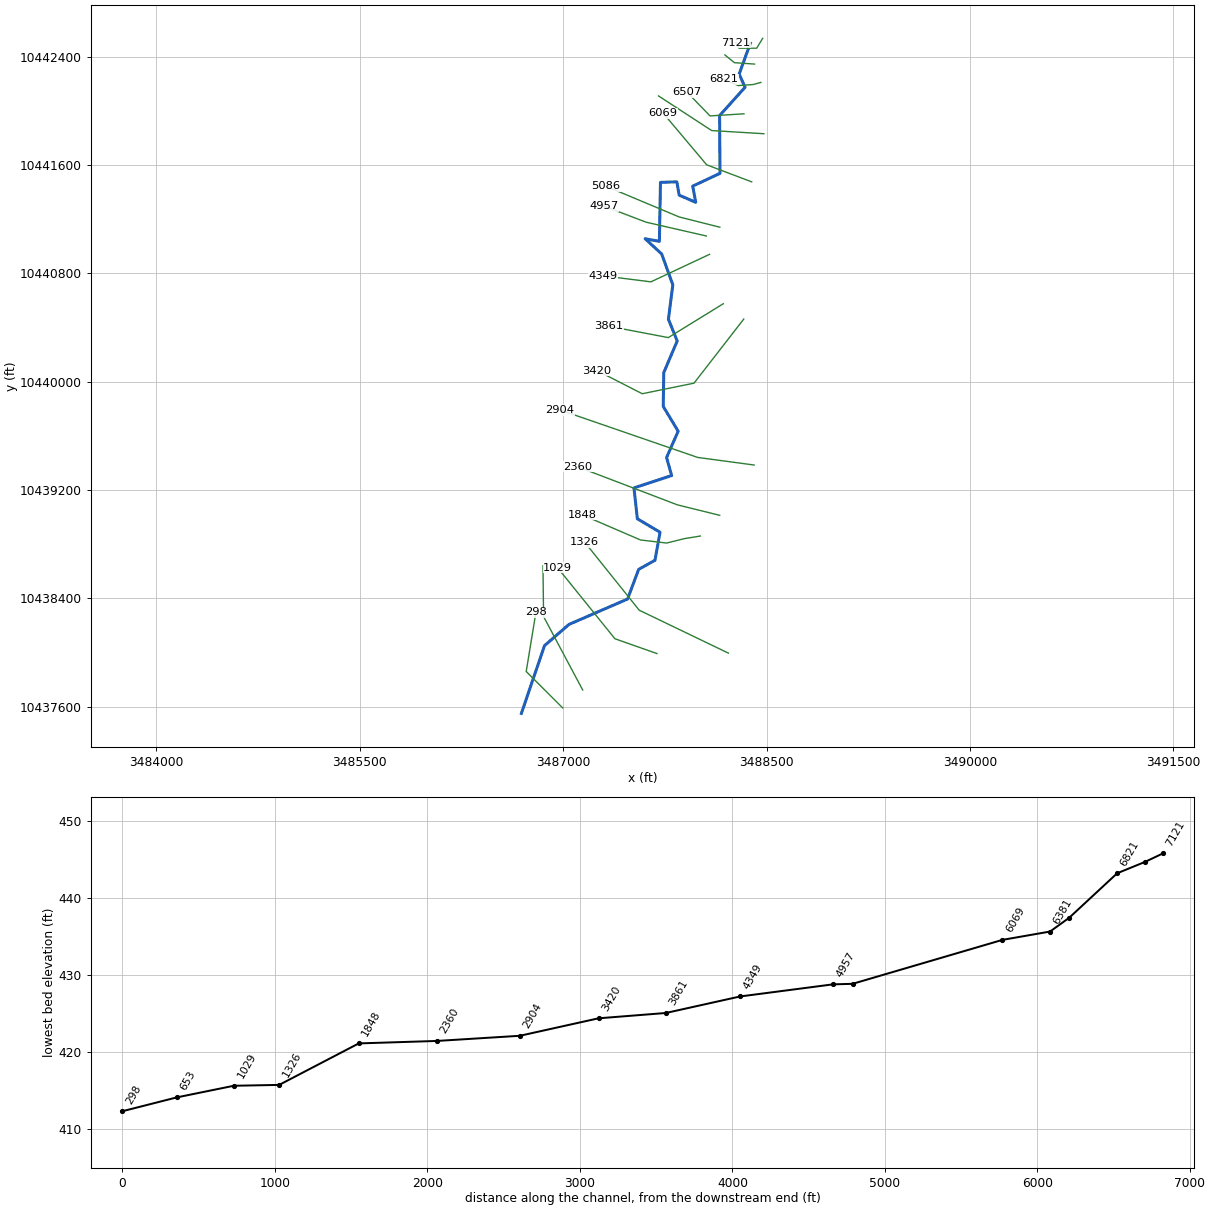
--- BEAR CREEK TRIB 1.prj (project) ---

Proj Title=BEAR CREEK TRIB 1 Base Level Engineering
Current Plan=p01
Default Exp/Contr=0.3,0.1
English Units
Geom File=g01
Flow File=f01
Plan File=p01
Y Axis Title=Elevation
X Axis Title(PF)=Main Channel Distance
X Axis Title(XS)=Station
BEGIN DESCRIPTION:
BEAR CREEK TRIB 1
END DESCRIPTION:
DSS Export Rating Curves= 0
DSS Export Rating Curve Sorted= 0
DSS Export Volume Flow Curves= 0
DXF OffsetX= 0
DXF OffsetY= 0
DXF ScaleX= 1
DXF ScaleY= 10

--- BEAR CREEK TRIB 1.p01 (plan) ---

Plan Title=Multiple Run
Short Identifier=Multiple
Geom File=g01
Flow File=f01
Subcritical Flow
K Sum by GR= 0
Std Step Tol= 0.01
Critical Tol= 0.01
Num of Std Step Trials= 20
Max Error Tol= 0.3
Flow Tol Ratio= 0.001
Split Flow NTrial= 30
Split Flow Tol= 0.02
Split Flow Ratio= 0.02
Log Output Level= 0
Friction Slope Method= 1
Unsteady Friction Slope Method= 2
Unsteady Bridges Friction Slope Method= 1
Parabolic Critical Depth
Global Vel Dist=  1 , 1 , 1
Global Log Level= 0
CheckData=True
Encroach Param= -1, 0, 0, 0
BEGIN DESCRIPTION:
Multiple Run
END DESCRIPTION:

--- BEAR CREEK TRIB 1.f01 (steady flow) ---

Flow Title=Multiple
Program Version=4.10
Number of Profiles= 7
Profile Names=10-year,25-year,50-year,1pct_min,100-year,1pct_plu,500-year
River Rch & RM=BEAR CREEK TRIB,Reach-1         ,7121
     746    1015    1236    1099    1486    2010    2144
River Rch & RM=BEAR CREEK TRIB,Reach-1         ,1326
     881    1210    1481    1324    1790    2421    2608
Boundary for River Rch & Prof#=BEAR CREEK TRIB,Reach-1         , 1
Up Type= 0
Dn Type= 3
Dn Slope=0.005
Boundary for River Rch & Prof#=BEAR CREEK TRIB,Reach-1         , 2
Up Type= 0
Dn Type= 3
Dn Slope=0.005
Boundary for River Rch & Prof#=BEAR CREEK TRIB,Reach-1         , 3
Up Type= 0
Dn Type= 3
Dn Slope=0.005
Boundary for River Rch & Prof#=BEAR CREEK TRIB,Reach-1         , 4
Up Type= 0
Dn Type= 3
Dn Slope=0.005
Boundary for River Rch & Prof#=BEAR CREEK TRIB,Reach-1         , 5
Up Type= 0
Dn Type= 3
Dn Slope=0.005
Boundary for River Rch & Prof#=BEAR CREEK TRIB,Reach-1         , 6
Up Type= 0
Dn Type= 3
Dn Slope=0.005
Boundary for River Rch & Prof#=BEAR CREEK TRIB,Reach-1         , 7
Up Type= 0
Dn Type= 3
Dn Slope=0.005
DSS Import GetInterval= 0
DSS Import GetPeak= 0
DSS Import FillOption= 0

--- BEAR CREEK TRIB 1.g01 (geometry) ---

Geom Title=Existing Conditions
Program Version=4.10

River Reach=BEAR CREEK TRIB ,Reach-1
Reach XY= 30
      3488380.62     10442500.37      3488298.15     10442272.51
      3488341.55     10442174.85      3488153.81     10441965.92
      3488156.74     10441539.47      3487955.57     10441445.02
      3487977.84     10441325.45      3487855.65     10441378.54
      3487838.59     10441476.72      3487717.79     10441472.76
      3487709.85     10441037.44       3487604.6     10441056.72
      3487726.69     10440944.07       3487808.9     10440716.48
      3487776.41     10440462.41      3487841.07     10440301.23
      3487742.01     10440067.84      3487738.25     10439818.21
      3487848.28     10439635.08      3487762.87      10439441.2
      3487800.31     10439307.78      3487522.28     10439216.79
      3487547.24     10438988.72      3487714.76     10438889.18
       3487677.1     10438682.29      3487556.69     10438614.88
      3487475.17     10438396.17      3487043.19     10438208.53
      3486862.52     10438051.55      3486692.11     10437551.64

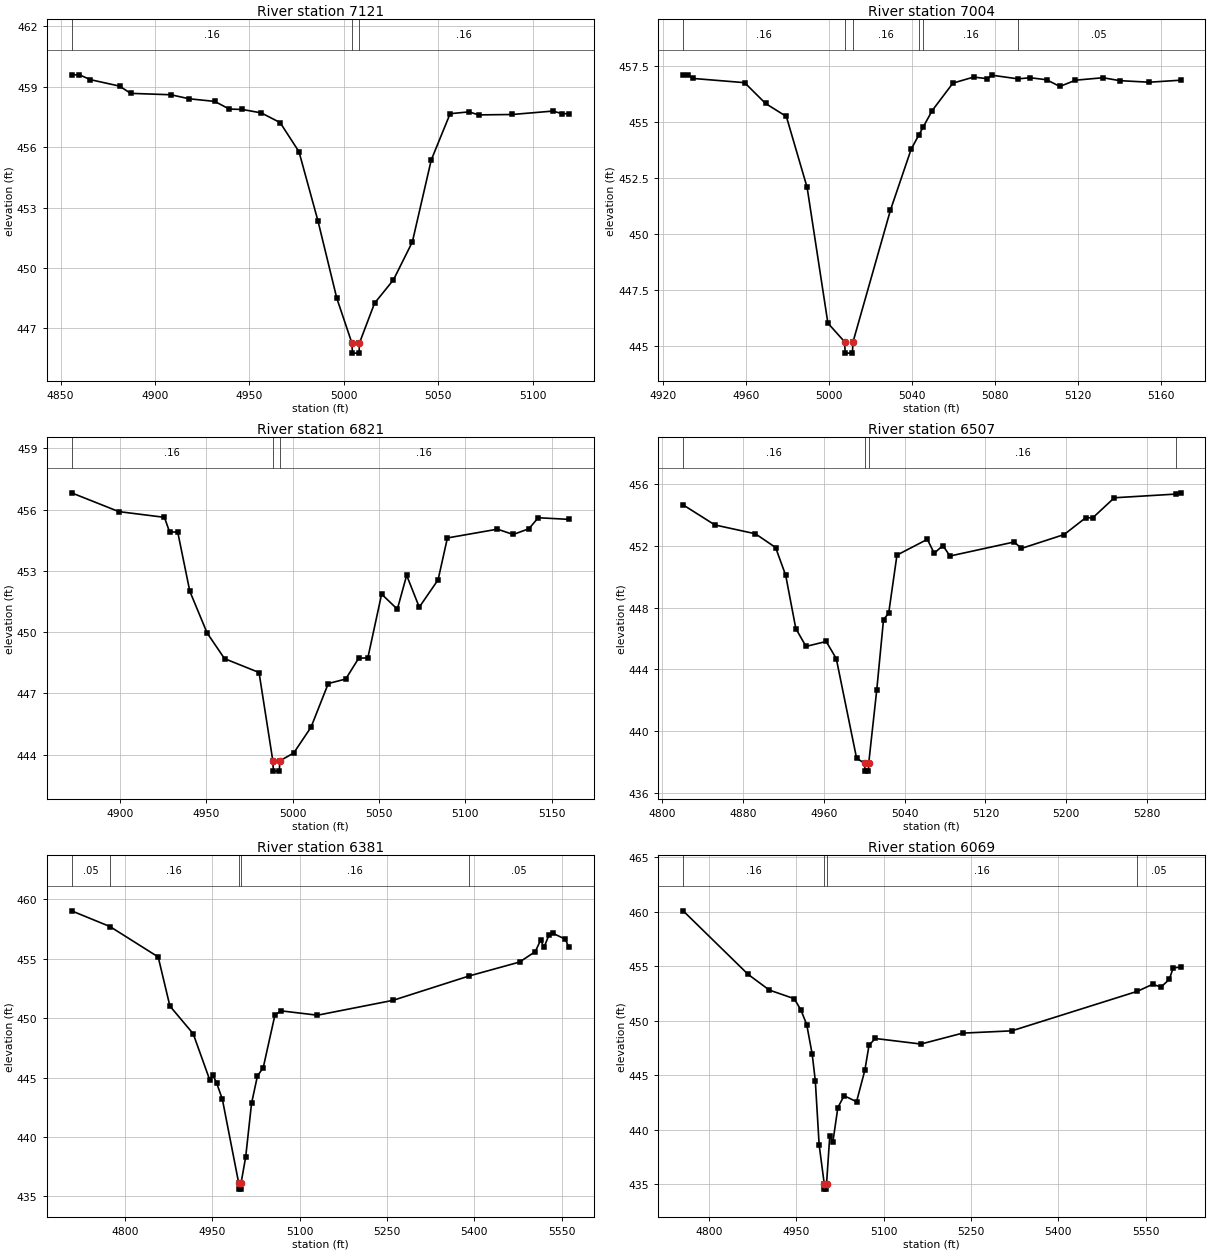
Type RM Length L Ch R = 1 ,7121    ,117,117,117
BEGIN DESCRIPTION:
BEAR CREEK TRIB 1 3 0
END DESCRIPTION:
XS GIS Cut Line= 4
      3488471.51     10442536.41      3488427.24     10442463.51
      3488297.04     10442463.51       3488273.6     10442505.18
#Sta/Elev= 30
  4855.8  459.59    4860  459.59  4865.8  459.35  4881.2  459.03  4887.1  458.67
  4908.4   458.6  4918.1   458.4  4931.6  458.27  4939.3  457.89  4946.2  457.87
  4956.2   457.7  4966.2  457.22  4976.2  455.77  4986.2  452.35  4996.2   448.5
  5004.2  446.27  5004.5  445.77    5008  445.77  5008.2  446.27  5016.2  448.25
  5026.2  449.41  5036.2  451.29  5046.2  455.36  5056.2  457.66  5066.2  457.75
  5071.3   457.6    5089  457.62  5110.6  457.79  5115.5  457.66  5119.1  457.66
#Mann= 3 ,-1 , 0
  4855.8     .16       0  5004.2     .07       0  5008.2     .16       0
Bank Sta=5004.2,5008.2
XS Rating Curve= 0 ,0
Exp/Cntr=0.3,0.1

Type RM Length L Ch R = 1 ,7004    ,183,183,183
BEGIN DESCRIPTION:
Mapping XS d07dd4cd
END DESCRIPTION:
XS GIS Cut Line= 3
      3488411.67     10442346.32      3488263.18     10442356.74
      3488192.91       10442414.
#Sta/Elev= 30
  4929.8   457.1  4932.1   457.1  4934.4  456.94  4959.4  456.75  4969.5  455.82
  4979.5  455.24  4989.5  452.07  4999.5  446.01  5007.6  445.17  5007.8  444.67
  5011.3  444.67  5011.6  445.17  5029.6  451.05  5039.6  453.78  5043.4  454.43
  5045.4  454.77  5049.7   455.5  5059.7  456.73  5069.7     457    5076  456.93
  5078.7  457.08    5091  456.92  5096.9  456.97  5104.8  456.88  5111.2  456.58
  5118.7  456.86    5132  456.97    5140  456.84  5154.3  456.77  5169.3  456.86
#Mann= 6 ,-1 , 0
  4929.8     .16       0  5007.6     .07       0  5011.6     .16       0
  5043.4     .05       0  5045.4     .16       0    5091     .05       0
Bank Sta=5007.6,5011.6
XS Rating Curve= 0 ,0
Exp/Cntr=0.3,0.1

Type RM Length L Ch R = 1 ,6821    ,314,314,314
BEGIN DESCRIPTION:
Mapping XS a9f3418e
END DESCRIPTION:
XS GIS Cut Line= 4
      3488458.51     10442210.91       3488401.2     10442195.28
      3488291.83     10442187.47      3488182.41     10442234.36
#Sta/Elev= 30
  4871.9  456.82  4899.3   455.9  4925.7  455.62  4928.7   454.9  4933.4   454.9
  4940.4     452  4950.4  449.96  4960.5   448.7  4980.5  448.02  4988.5  443.69
  4988.8  443.19  4992.3  443.19  4992.5  443.69  5000.6  444.08  5010.6  445.34
  5020.6  447.48  5030.7   447.7  5038.3  448.73  5043.5  448.73  5051.5  451.86
  5060.6  451.12    5066  452.78  5073.3  451.22  5084.2  452.56  5089.6  454.61
  5118.6  455.04  5127.7  454.78  5136.8  455.06  5142.2   455.6    5160  455.52
#Mann= 3 ,-1 , 0
  4871.9     .16       0  4988.5     .07       0  4992.5     .16       0
Bank Sta=4988.5,4992.5
XS Rating Curve= 0 ,0
Exp/Cntr=0.3,0.1

Type RM Length L Ch R = 1 ,6507    ,126,126,126
BEGIN DESCRIPTION:
Mapping XS f15393e2
END DESCRIPTION:
XS GIS Cut Line= 3
      3488333.53     10441979.14      3488083.49     10441963.51
      3487914.86     10442137.33
#Sta/Elev= 30
  4820.6  454.65  4852.1  453.35  4892.2  452.78  4912.2  451.89  4922.2  450.09
  4932.2  446.65  4942.3  445.49  4962.3  445.81  4972.3   444.7  4992.4  438.26
  5000.4  437.92  5000.6  437.42  5004.1  437.42  5004.4  437.92  5012.4  442.68
  5019.1  447.23  5024.2  447.64  5032.4   451.4  5062.5  452.42  5069.3  451.52
  5077.9  452.02  5084.9  451.34  5148.6  452.25  5155.6  451.83    5198  452.73
  5219.4  453.82  5226.3  453.81  5247.7  455.11    5309  455.35  5313.3  455.43
#Mann= 4 ,-1 , 0
  4820.6     .16       0  5000.4     .07       0  5004.4     .16       0
    5309     .05       0
Bank Sta=5000.4,5004.4
XS Rating Curve= 0 ,0
Exp/Cntr=0.3,0.1

Type RM Length L Ch R = 1 ,6381    ,312,312,312
BEGIN DESCRIPTION:
BEAR CREEK TRIB 1 3 0
END DESCRIPTION:
XS GIS Cut Line= 3
      3488480.67       10441832.      3488095.28     10441855.43
      3487703.28     10442111.27
#Sta/Elev= 30
  4708.2  459.03  4774.1  457.71    4857  455.15  4877.1  451.02  4917.1  448.69
  4945.8  444.77  4950.9  445.21  4957.2  444.57  4967.2  443.18  4995.3  436.12
  4995.5  435.62    4999  435.62  4999.3  436.12  5007.3  438.34  5017.3  442.83
  5027.4  445.13  5037.4  445.84  5057.4  450.25  5067.4  450.62  5130.5  450.25
  5260.2   451.5  5391.6  453.56  5477.5  454.72  5504.6   455.6  5513.7  456.56
  5519.7  455.97    5528  456.99  5534.8  457.14  5555.9  456.65  5562.4  455.96
#Mann= 5 ,-1 , 0
  4708.2     .05       0  4774.1     .16       0  4995.3     .07       0
  4999.3     .16       0  5391.6     .05       0
Bank Sta=4995.3,4999.3
XS Rating Curve= 0 ,0
Exp/Cntr=0.3,0.1

Type RM Length L Ch R = 1 ,6069    ,983,983,983
BEGIN DESCRIPTION:
BEAR CREEK TRIB 1 2 0
END DESCRIPTION:
XS GIS Cut Line= 3
      3488390.55      10441476.6      3488058.47     10441602.49
      3487737.28     10441984.45
#Sta/Elev= 30
  4755.9  460.07  4867.7  454.23    4904   452.8  4946.7  452.01  4958.1  450.98
  4968.1  449.64  4977.6   446.9  4982.9  444.47  4989.5  438.59  4998.2  435.04
  4998.5  434.54    5002  434.54  5002.2  435.04  5007.7   439.4  5013.1  438.88
  5021.6  442.02  5032.3  443.11  5053.7  442.56    5068  445.45  5075.1  447.74
  5085.8  448.36  5164.3  447.85  5235.8  448.85  5320.3  449.06  5536.1  452.69
  5562.2  453.33  5576.5  453.08  5590.8  453.78  5597.4  454.83  5610.1  454.91
#Mann= 4 ,-1 , 0
  4755.9     .16       0  4998.2     .07       0  5002.2     .16       0
  5536.1     .05       0
Bank Sta=4998.2,5002.2
XS Rating Curve= 0 ,0
Exp/Cntr=0.3,0.1

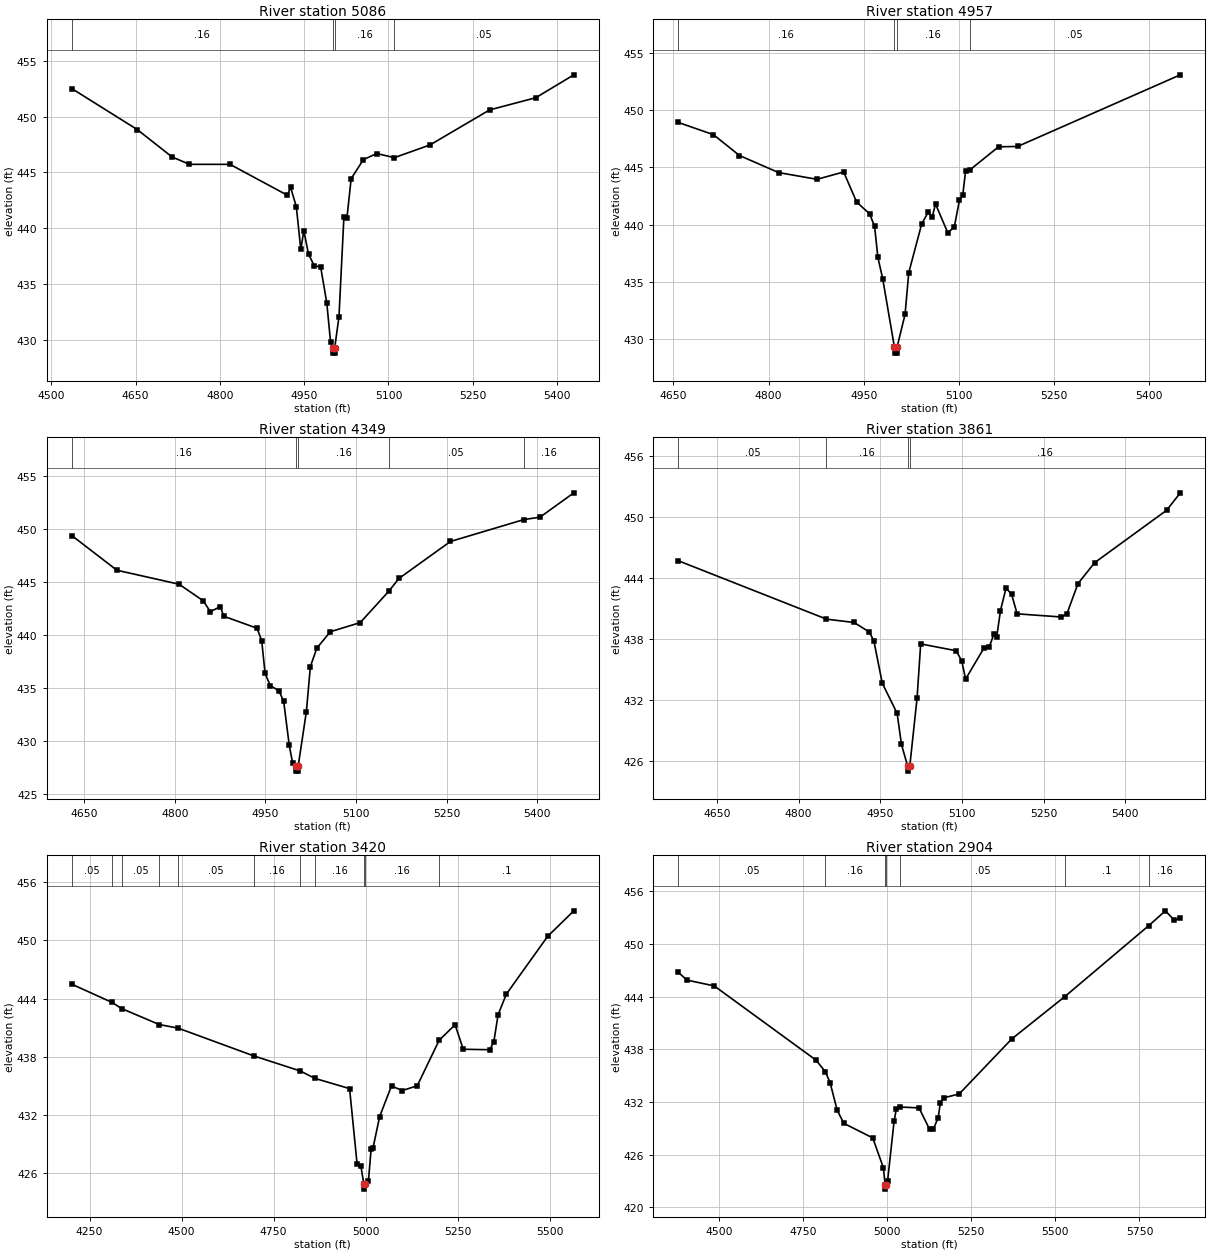
Type RM Length L Ch R = 1 ,5086    ,129,129,129
BEGIN DESCRIPTION:
BEAR CREEK TRIB 1 12 0
END DESCRIPTION:
XS GIS Cut Line= 3
      3488155.15      10441141.9      3487855.69     10441217.41
      3487316.88     10441443.87
#Sta/Elev= 30
  4536.5   452.5  4653.1  448.83  4714.7  446.39  4745.9  445.72  4818.1  445.72
  4920.3  442.95  4925.7  443.68    4936  441.94    4944  438.11  4949.4  439.78
  4957.7  437.69  4967.8  436.66  4979.4  436.52  4990.2  433.33  4996.9  429.85
  5000.4  429.33  5000.6  428.83  5004.1  428.83  5004.4  429.33  5011.9  432.08
  5020.7  441.02  5026.1  440.94  5033.6  444.44  5055.3  446.14    5079  446.69
  5110.5  446.32    5174  447.46  5279.9  450.59    5362  451.68  5429.8  453.73
#Mann= 4 ,-1 , 0
  4536.5     .16       0  5000.4     .07       0  5004.4     .16       0
  5110.5     .05       0
Bank Sta=5000.4,5004.4
XS Rating Curve= 0 ,0
Exp/Cntr=0.3,0.1

Type RM Length L Ch R = 1 ,4957    ,608,608,608
BEGIN DESCRIPTION:
BEAR CREEK TRIB 1 21 0
END DESCRIPTION:
XS GIS Cut Line= 3
      3488056.19     10441076.79      3487612.72     10441178.61
      3487298.39     10441298.14
#Sta/Elev= 30
  4657.6  448.92  4713.1  447.85  4754.1  446.03  4815.7  444.54  4876.3  443.95
  4918.3  444.59  4938.8  441.96  4959.3  440.93  4967.1  439.83  4972.2  437.14
  4979.9  435.25  4998.4  429.26  4998.6  428.76  5002.1  428.76  5002.4  429.26
  5015.1  432.15  5020.9  435.79  5041.4  440.07  5051.7  441.09    5058  440.68
  5063.1  441.79  5082.5  439.27  5092.7  439.79  5100.8  442.12    5106  442.55
  5110.4  444.64    5117  444.76  5162.4  446.79  5192.5  446.82  5448.9  453.08
#Mann= 4 ,-1 , 0
  4657.6     .16       0  4998.4     .07       0  5002.4     .16       0
    5117     .05       0
Bank Sta=4998.4,5002.4
XS Rating Curve= 0 ,0
Exp/Cntr=0.3,0.1

Type RM Length L Ch R = 1 ,4349    ,488,488,488
BEGIN DESCRIPTION:
BEAR CREEK TRIB 1 20 0
END DESCRIPTION:
XS GIS Cut Line= 3
      3488079.69     10440941.39      3487647.36     10440738.24
      3487296.41     10440782.44
#Sta/Elev= 30
  4629.3  449.41    4704  446.14    4807  444.82  4847.1  443.25  4858.7  442.23
  4875.4  442.71  4880.9   441.8    4936  440.67  4943.8  439.51  4949.4   436.4
  4958.1  435.25  4972.2  434.78  4980.2  433.78  4989.4  429.63    4995  427.96
  5000.3  427.69  5000.5  427.19    5004  427.19  5004.3  427.69  5017.8  432.81
  5024.4  437.05  5035.1  438.79  5057.5  440.34    5107   441.2    5154  444.14
    5171  445.36  5256.3  448.85  5378.1  450.92  5404.6  451.14  5460.7  453.44
#Mann= 5 ,-1 , 0
  4629.3     .16       0  5000.3     .07       0  5004.3     .16       0
    5154     .05       0  5378.1     .16       0
Bank Sta=5000.3,5004.3
XS Rating Curve= 0 ,0
Exp/Cntr=0.3,0.1

Type RM Length L Ch R = 1 ,3861    ,441,441,441
BEGIN DESCRIPTION:
BEAR CREEK TRIB 1 9 0
END DESCRIPTION:
XS GIS Cut Line= 3
      3488181.17     10440576.76      3487775.81     10440326.56
      3487337.46     10440410.12
#Sta/Elev= 30
  4578.8  445.68  4851.2  439.95  4901.8  439.62  4930.2  438.68  4938.4  437.78
  4953.7  433.67    4981  430.71    4989  427.66  5000.3  425.54  5000.5  425.04
  5004.3  425.54  5017.7  432.22  5024.3  437.52  5089.5  436.85  5099.7  435.86
  5106.9  434.07  5140.4   437.1  5150.6  437.25    5159  438.51  5164.1  438.23
  5170.9  440.78  5181.1  442.99  5191.3  442.41  5201.5  440.47  5282.9  440.16
  5293.1  440.48  5313.4  443.44    5344  445.49  5476.3  450.63  5501.4  452.34
#Mann= 4 ,-1 , 0
  4578.8     .05       0  4851.2     .16       0  5000.3     .07       0
  5004.3     .16       0
Bank Sta=5000.3,5004.3
XS Rating Curve= 0 ,0
Exp/Cntr=0.3,0.1

Type RM Length L Ch R = 1 ,3420    ,516,516,516
BEGIN DESCRIPTION:
BEAR CREEK TRIB 1 8 0
END DESCRIPTION:
XS GIS Cut Line= 4
      3488331.93     10440463.18      3487965.16     10439990.07
      3487583.21     10439911.95        3487249.      10440083.4
#Sta/Elev= 30
  4201.8  445.49  4311.4  443.61  4337.2  442.98  4439.5  441.33  4490.6  440.96
  4695.8   438.1  4822.5  436.54  4862.8  435.77  4956.6  434.72  4977.1  426.91
  4987.3  426.73  4995.5  424.85  4995.7  424.35  4999.5  424.85  5007.7  425.15
    5015  428.45  5020.1  428.57  5038.3  431.84  5070.5     435  5099.5  434.52
  5140.4  435.01  5199.9   439.7  5243.2  441.31  5265.4  438.78  5337.6  438.73
  5348.6  439.57  5360.1  442.35  5382.6  444.47    5495  450.44  5565.9  453.06
#Mann= 11 ,-1 , 0
  4201.8     .05       0  4311.4     .16       0  4337.2     .05       0
  4439.5     .16       0  4490.6     .05       0  4695.8     .16       0
  4822.5     .05       0  4862.8     .16       0  4995.5     .03       0
  4999.5     .16       0  5199.9      .1       0
Bank Sta=4995.5,4999.5
XS Rating Curve= 0 ,0
Exp/Cntr=0.3,0.1

Type RM Length L Ch R = 1 ,2904    ,544,544,544
BEGIN DESCRIPTION:
BEAR CREEK TRIB 1 7 0
END DESCRIPTION:
XS GIS Cut Line= 3
      3488408.12      10439385.6      3487992.11     10439441.64
      3486977.53     10439791.86
#Sta/Elev= 30
  4378.3  446.77  4404.6  445.88  4485.3  445.22    4788  436.77  4815.8  435.45
  4829.8  434.22    4851  431.06  4870.8  429.57  4956.8  427.91  4988.5   424.5
  4993.5  422.58  4993.8  422.08  4997.5  422.58  5000.8  422.98  5020.2  429.79
  5026.7  431.19  5037.2  431.43  5094.4  431.33    5126  428.87  5136.6  428.89
  5151.5  430.22  5157.8  431.93  5168.3  432.48  5213.9  432.92  5369.8  439.17
  5528.1  444.01  5776.8  452.06  5827.1  453.77    5853  452.72  5871.4   452.9
#Mann= 7 ,-1 , 0
  4378.3     .05       0  4815.8     .16       0  4993.5     .07       0
  4997.5     .16       0  5037.2     .05       0  5528.1      .1       0
  5776.8     .16       0
Bank Sta=4993.5,4997.5
XS Rating Curve= 0 ,0
Exp/Cntr=0.3,0.1

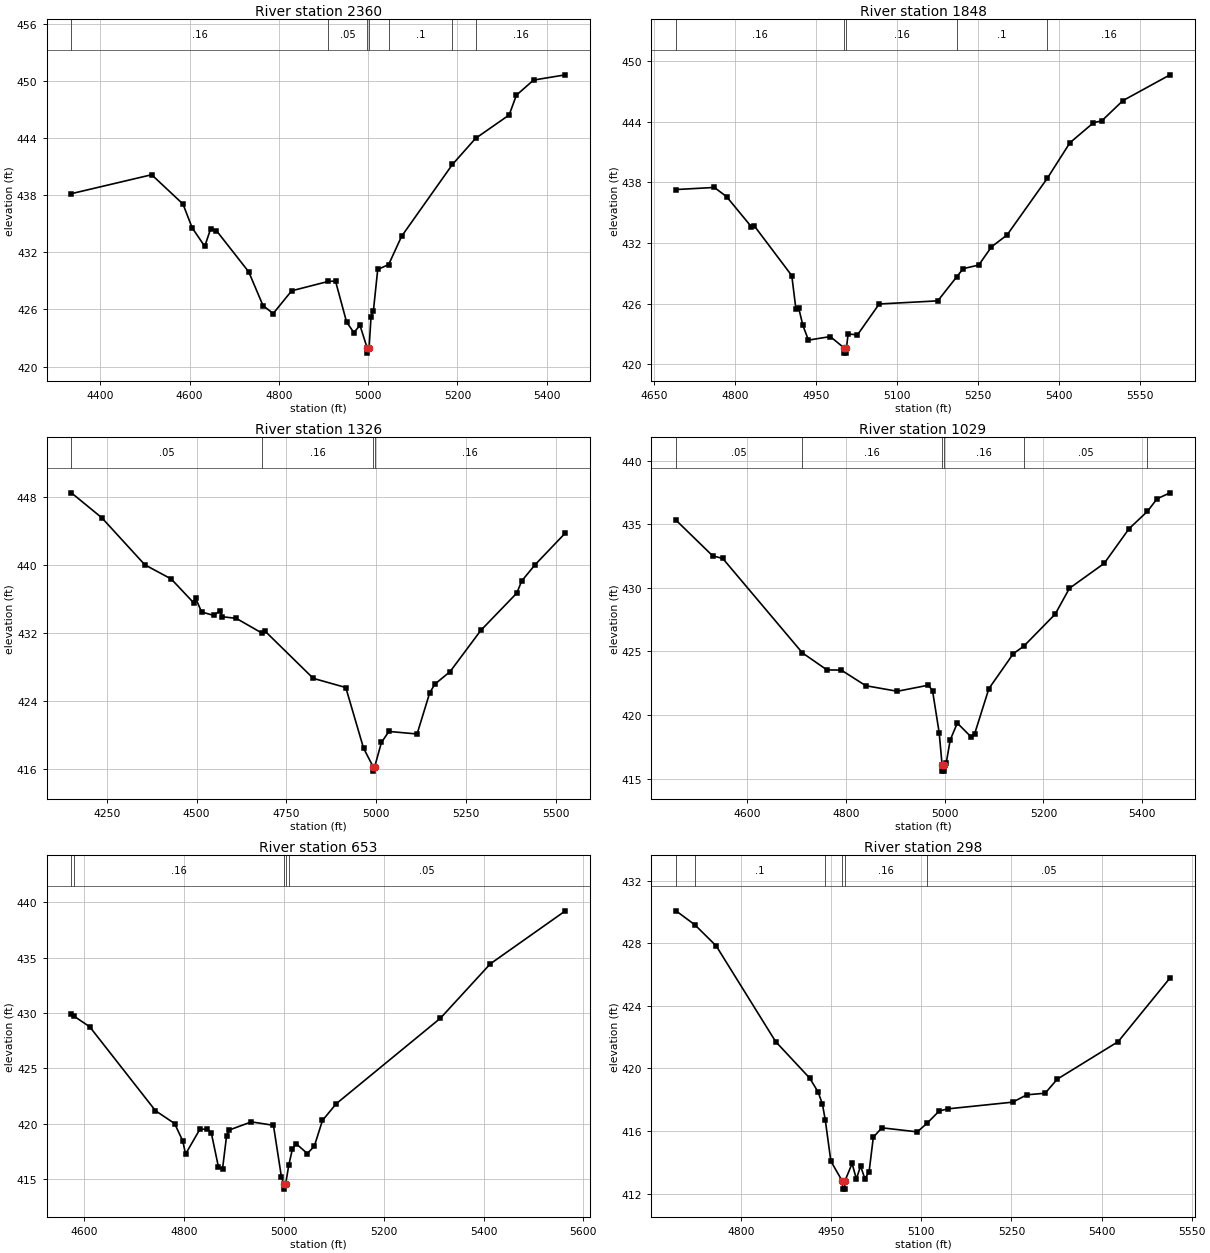
Type RM Length L Ch R = 1 ,2360    ,512,512,512
BEGIN DESCRIPTION:
BEAR CREEK TRIB 1 6 0
END DESCRIPTION:
XS GIS Cut Line= 3
      3488154.63     10439014.08      3487842.11     10439091.64
      3487109.52     10439371.71
#Sta/Elev= 30
  4335.4  438.17  4515.2  440.16  4585.3  437.08  4605.9  434.58  4634.1  432.63
  4647.1  434.46  4660.1  434.29  4732.6  429.95  4764.5  426.41  4787.3  425.57
  4828.7  427.96    4911  428.95  4926.9  428.98  4951.6  424.69  4967.9  423.57
  4981.7  424.33    4998  421.91  4998.2  421.41    5002  421.91  5006.4  425.24
  5011.8  425.89  5021.4   430.2  5045.9  430.72  5074.9  433.69  5188.7  441.24
  5240.5  443.98  5315.7  446.44  5331.9  448.52  5370.4  450.11  5441.7  450.66
#Mann= 7 ,-1 , 0
  4335.4     .16       0    4911     .05       0    4998     .03       0
    5002     .05       0  5045.9      .1       0  5188.7     .05       0
  5240.5     .16       0
Bank Sta=4998,5002
XS Rating Curve= 0 ,0
Exp/Cntr=0.3,0.1

Type RM Length L Ch R = 1 ,1848    ,522,522,522
BEGIN DESCRIPTION:
BEAR CREEK TRIB 1 5 0
END DESCRIPTION:
XS GIS Cut Line= 5
      3488012.31      10438861.3      3487892.11     10438841.64
       3487763.1     10438809.39      3487570.82     10438832.07
      3487141.81     10439017.09
#Sta/Elev= 30
    4690   437.3  4761.1  437.51  4783.7   436.6  4829.8  433.61    4835  433.71
  4904.6  428.77  4912.3  425.44  4917.5  425.54  4925.2  423.83  4935.5  422.38
    4976  422.73  5001.9  421.59  5002.2  421.09  5005.7  421.09  5005.9  421.59
    5009  422.99  5026.3   422.9  5066.6  425.96  5175.2  426.27  5210.4  428.66
  5222.2  429.46  5251.1  429.82  5274.7  431.62  5303.6   432.8  5378.2  438.42
  5420.1  441.94  5463.7  443.92  5479.1  444.11  5518.2  446.11  5605.6  448.67
#Mann= 5 ,-1 , 0
    4690     .16       0  5001.9     .07       0  5005.9     .16       0
  5210.4      .1       0  5378.2     .16       0
Bank Sta=5001.9,5005.9
XS Rating Curve= 0 ,0
Exp/Cntr=0.3,0.1

Type RM Length L Ch R = 1 ,1326    ,297,297,297
BEGIN DESCRIPTION:
BEAR CREEK TRIB 1 4 0
END DESCRIPTION:
XS GIS Cut Line= 3
      3488218.65     10437996.43      3487560.87     10438313.68
      3487157.68     10438817.41
#Sta/Elev= 30
  4151.3  448.52  4236.3  445.57  4355.9  440.03  4429.3  438.36  4491.6  435.56
  4497.1  436.11  4513.8  434.47  4547.9  434.06    4565  434.63  4570.5  433.91
  4610.2  433.72  4681.9  431.98  4691.5  432.17  4824.8  426.64  4915.3  425.56
  4964.9  418.39  4991.7   416.2    4992   415.7  4995.7   416.2  5014.5  419.08
  5035.4  420.38  5113.8  420.08    5149  424.94  5163.4  425.96  5205.6  427.43
  5291.5  432.31  5391.3  436.69  5405.1  438.12  5441.9  440.02  5526.8  443.79
#Mann= 4 ,-1 , 0
  4151.3     .05       0  4681.9     .16       0  4991.7     .07       0
  4995.7     .16       0
Bank Sta=4991.7,4995.7
XS Rating Curve= 0 ,0
Exp/Cntr=0.3,0.1

Type RM Length L Ch R = 1 ,1029    ,376,376,376
BEGIN DESCRIPTION:
BEAR CREEK TRIB 1 22 0
END DESCRIPTION:
XS GIS Cut Line= 3
      3487691.66     10437993.44      3487381.73     10438102.83
      3486959.89     10438626.23
#Sta/Elev= 30
  4455.6  435.33    4530  432.52  4550.3  432.32  4711.7  424.89  4761.5  423.55
  4790.4  423.54    4840  422.31    4904  421.87  4966.9  422.35  4975.4  421.91
  4988.8  418.61  4994.7  416.09    4995  415.59  4998.5  415.59  4998.7  416.09
  5003.2  416.25  5011.1  418.03  5025.5  419.37  5052.7  418.31  5060.7  418.53
  5089.5  422.08  5139.1  424.83  5160.3  425.42  5223.9  427.94  5252.7  429.97
  5323.1  431.93  5373.5  434.66  5410.7  436.02  5430.2  437.01  5456.5  437.48
#Mann= 6 ,-1 , 0
  4455.6     .05       0  4711.7     .16       0  4994.7     .07       0
  4998.7     .16       0  5160.3     .05       0  5410.7     .16       0
Bank Sta=4994.7,4998.7
XS Rating Curve= 0 ,0
Exp/Cntr=0.3,0.1

Type RM Length L Ch R = 1 ,653     ,355,355,355
BEGIN DESCRIPTION:
Mapping XS 16f07089
END DESCRIPTION:
XS GIS Cut Line= 3
      3487144.32      10437724.2      3486855.71     10438266.69
      3486851.37     10438642.08
#Sta/Elev= 30
  4574.2  429.86  4579.6   429.7  4610.9  428.75  4742.7  421.16    4781     420
  4797.3  418.44    4803  417.24  4831.8  419.49  4846.9  419.49  4854.5  419.17
  4868.9  416.07  4877.1  415.91  4885.2  418.89  4890.9  419.42  4934.8  420.15
  4979.1  419.84  4995.1  415.16  4999.7  414.57    5000  414.07  5003.7  414.57
  5009.7  416.21  5017.1   417.7  5024.4  418.18    5047  417.29    5061  417.95
  5077.3  420.28  5104.9  421.79  5313.6  429.52  5413.7  434.44  5564.1  439.23
#Mann= 5 ,-1 , 0
  4574.2     .05       0  4579.6     .16       0  4999.7     .07       0
  5003.7     .16       0  5009.7     .05       0
Bank Sta=4999.7,5003.7
XS Rating Curve= 0 ,0
Exp/Cntr=0.3,0.1

Type RM Length L Ch R = 1 ,298     ,0,0,0
BEGIN DESCRIPTION:
BEAR CREEK TRIB 1 1 0
END DESCRIPTION:
XS GIS Cut Line= 3
       3486996.8     10437591.75      3486727.67     10437860.88
      3486799.25     10438296.83
#Sta/Elev= 30
  4691.6  430.07  4723.2  429.17  4758.5  427.83  4857.5  421.71  4914.1  419.38
  4928.2  418.49  4935.3  417.72    4940  416.73  4949.4  414.07  4968.6  412.78
  4968.9  412.28  4972.4  412.28  4972.6  412.78  4984.8  413.92  4991.8  412.93
  4998.9  413.75    5006  412.95    5013  413.37  5020.1   415.6  5034.3   416.2
  5093.3  415.94  5109.8   416.5  5129.6  417.27  5143.9  417.41  5252.1  417.84
  5275.7  418.31  5306.1  418.41  5326.3  419.31  5427.7  421.71    5514  425.78
#Mann= 6 ,-1 , 0
  4691.6     .16       0  4723.2      .1       0    4940     .16       0
  4968.6     .07       0  4972.6     .16       0  5109.8     .05       0
Bank Sta=4968.6,4972.6
XS Rating Curve= 0 ,0
Exp/Cntr=0.3,0.1

Chan Stop Cuts=-1
Use User Specified Reach Order=0
Composite Channel Slope=5