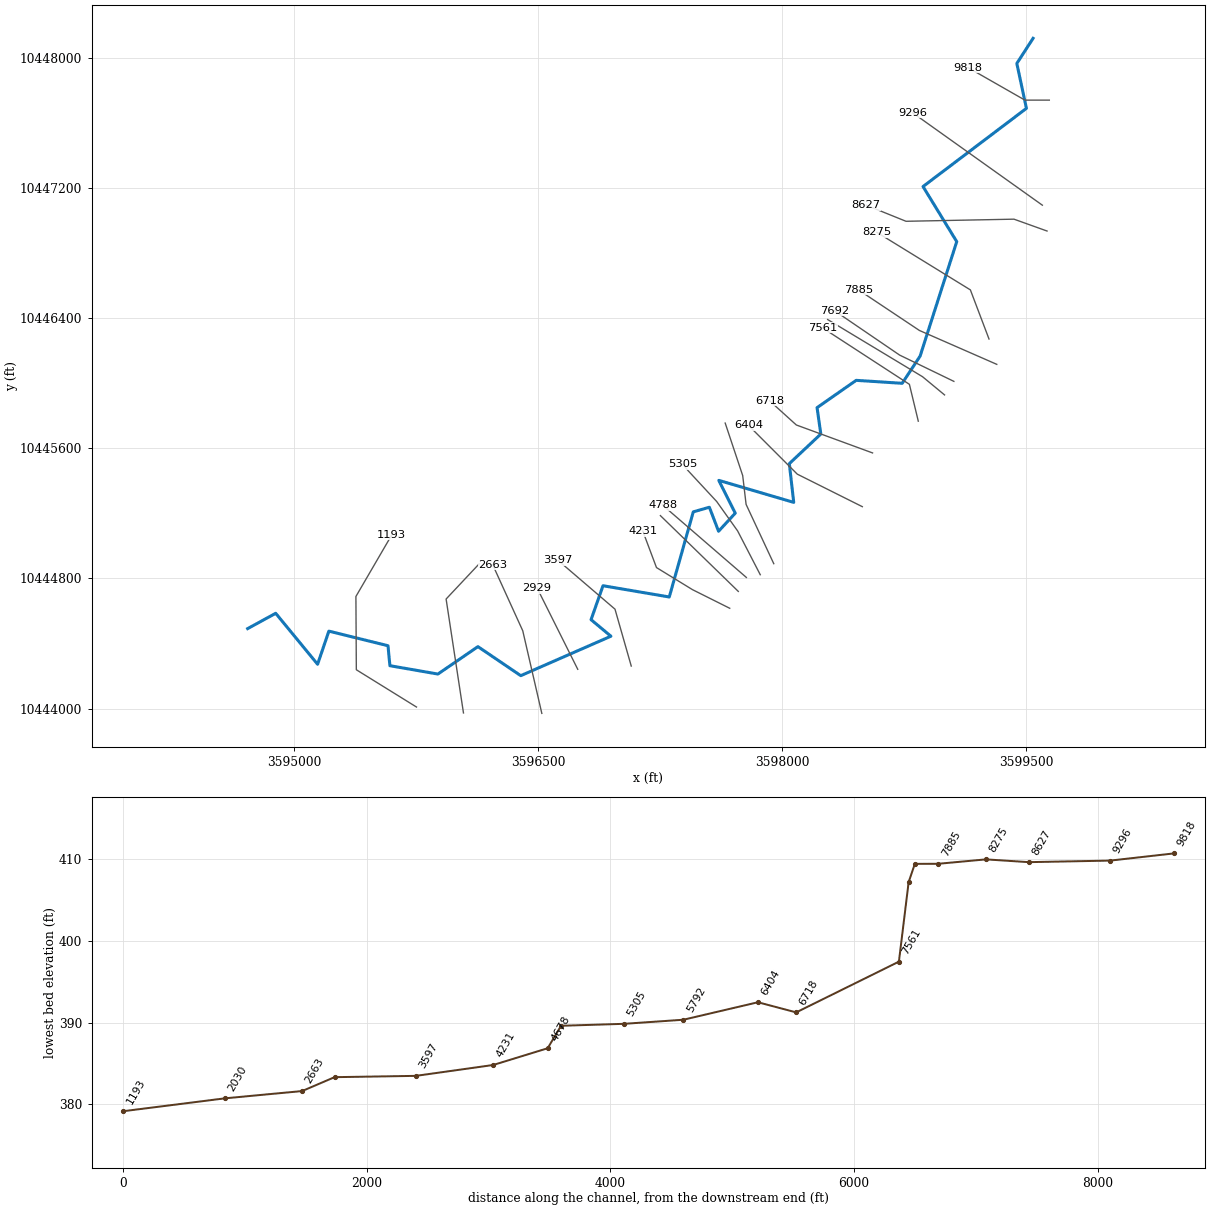
--- BIG BRANCH.prj (project) ---

Proj Title=BIG BRANCH Base Level Engineering
Current Plan=p01
Default Exp/Contr=0.3,0.1
English Units
Geom File=g01
Flow File=f01
Plan File=p01
Y Axis Title=Elevation
X Axis Title(PF)=Main Channel Distance
X Axis Title(XS)=Station
BEGIN DESCRIPTION:
BIG BRANCH
END DESCRIPTION:
DSS Export Rating Curves= 0
DSS Export Rating Curve Sorted= 0
DSS Export Volume Flow Curves= 0
DXF OffsetX= 0
DXF OffsetY= 0
DXF ScaleX= 1
DXF ScaleY= 10

--- BIG BRANCH.p01 (plan) ---

Plan Title=Multiple Run
Short Identifier=Multiple
Geom File=g01
Flow File=f01
Subcritical Flow
K Sum by GR= 0
Std Step Tol= 0.01
Critical Tol= 0.01
Num of Std Step Trials= 20
Max Error Tol= 0.3
Flow Tol Ratio= 0.001
Split Flow NTrial= 30
Split Flow Tol= 0.02
Split Flow Ratio= 0.02
Log Output Level= 0
Friction Slope Method= 1
Unsteady Friction Slope Method= 2
Unsteady Bridges Friction Slope Method= 1
Parabolic Critical Depth
Global Vel Dist=  1 , 1 , 1
Global Log Level= 0
CheckData=True
Encroach Param= -1, 0, 0, 0
BEGIN DESCRIPTION:
Multiple Run
END DESCRIPTION:

--- BIG BRANCH.f01 (steady flow) ---

Flow Title=Multiple
Number of Profiles=7
Profile Names=10-year,25-year,50-year,1pct_min,100-year,1pct_plu,500-year
River Rch & RM= BIG BRANCH,Reach-1,9818
    1639    2329    2917    2663    3601    4870    5478
Boundary for River Rch & Prof#=BIG BRANCH,Reach-1,1
Up Type=0
Dn Type=3
Dn Slope=0.005
Boundary for River Rch & Prof#=BIG BRANCH,Reach-1,2
Up Type=0
Dn Type=3
Dn Slope=0.005
Boundary for River Rch & Prof#=BIG BRANCH,Reach-1,3
Up Type=0
Dn Type=3
Dn Slope=0.005
Boundary for River Rch & Prof#=BIG BRANCH,Reach-1,4
Up Type=0
Dn Type=3
Dn Slope=0.005
Boundary for River Rch & Prof#=BIG BRANCH,Reach-1,5
Up Type=0
Dn Type=3
Dn Slope=0.005
Boundary for River Rch & Prof#=BIG BRANCH,Reach-1,6
Up Type=0
Dn Type=3
Dn Slope=0.005
Boundary for River Rch & Prof#=BIG BRANCH,Reach-1,7
Up Type=0
Dn Type=3
Dn Slope=0.005

--- BIG BRANCH.g01 (geometry) ---

Geom Title=Existing Conditions
Program Version=4.10

River Reach=BIG BRANCH      ,Reach-1
Reach XY= 30
      3599542.11     10448121.64      3599442.27     10447967.21
      3599501.23     10447690.99      3598865.34      10447210.2
      3599072.71     10446871.52      3598847.52     10446167.81
      3598737.27     10446000.28      3598454.29     10446018.51
      3598213.84     10445850.54      3598236.84     10445688.21
      3598043.26     10445506.35      3598070.17     10445268.07
      3597609.24     10445403.49       3597710.8     10445201.67
      3597608.11     10445090.56      3597551.51     10445238.12
      3597452.55     10445209.65      3597305.01      10444686.3
       3596897.5     10444755.49      3596823.98      10444546.8
      3596946.13     10444445.03      3596391.72      10444202.4
      3596128.41     10444380.94      3595882.12     10444212.35
        3595587.     10444263.71      3595575.23     10444386.51
      3595211.72     10444476.25      3595142.35     10444272.51
      3594884.76       10444586.      3594712.11     10444491.64

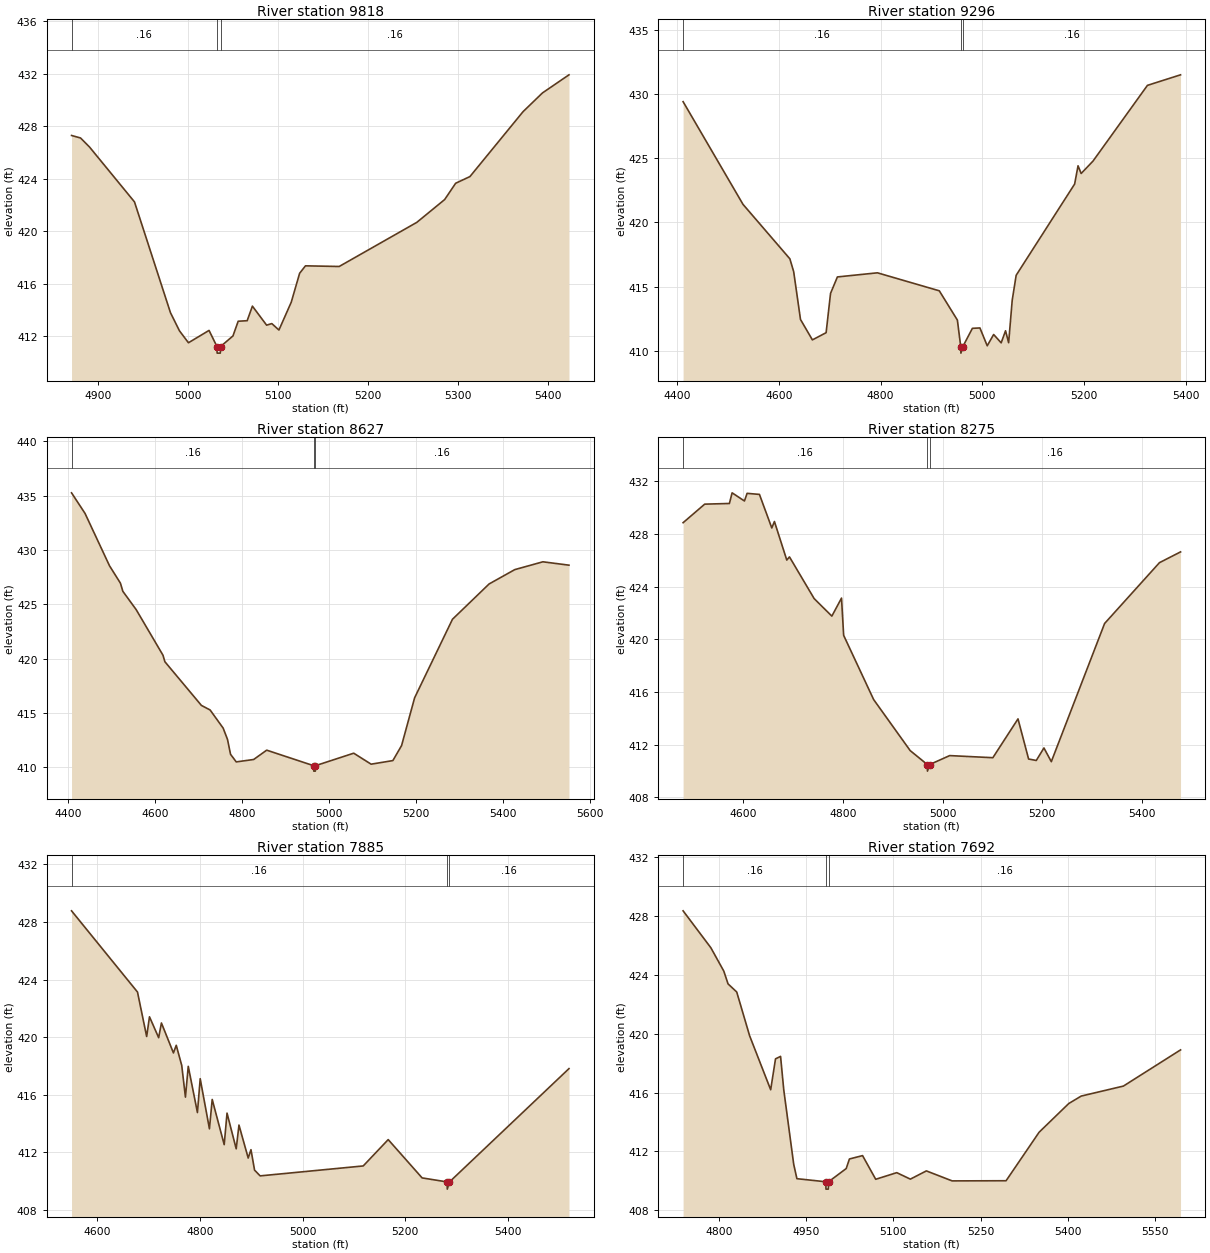
Type RM Length L Ch R = 1 ,9818    ,522,522,522
BEGIN DESCRIPTION:
UNT0280 IN DUCK CR 3 0
END DESCRIPTION:
XS GIS Cut Line= 3
      3599642.09     10447741.64      3599492.11     10447741.64
       3599142.1     10447941.64
#Sta/Elev= 30
  4870.6  427.29  4880.6   427.1  4890.6  426.41  4940.6  422.23  4980.6  413.79
  4990.6  412.41  5000.6   411.5  5023.5  412.44  5032.3  411.21  5032.5  410.71
    5036  410.71  5036.3  411.21  5050.1  412.02  5055.9  413.14  5065.9  413.18
  5071.7  414.29  5087.5  412.84  5093.3  412.96  5101.2  412.47  5114.9  414.59
  5124.2  416.79  5130.7  417.36  5168.2  417.31  5254.5  420.67  5285.5  422.41
  5297.7  423.65  5313.6  424.16  5372.6   429.1  5394.2  430.53  5423.7  431.91
#Mann= 3 ,-1 , 0
  4870.6     .16       0  5032.3     .07       0  5036.3     .16       0
Bank Sta=5032.3,5036.3
XS Rating Curve= 0 ,0
Exp/Cntr=0.3,0.1

Type RM Length L Ch R = 1 ,9296    ,669,669,669
BEGIN DESCRIPTION:
UNT0280 IN DUCK CR 2 0
END DESCRIPTION:
XS GIS Cut Line= 2
      3599599.28     10447095.57      3598802.42     10447663.27
#Sta/Elev= 30
  4411.5   429.4  4529.3  421.41  4621.5  417.17    4629  416.17  4642.4  412.45
  4665.8  410.86  4692.8  411.42  4701.5  414.48    4715  415.76  4793.7  416.08
  4915.4  414.68    4951   412.4  4957.6  410.33  4957.9  409.83  4961.6  410.33
  4980.5  411.76  4995.3  411.79  5009.7   410.4  5022.3  411.28  5037.1  410.63
  5045.7  411.57  5051.8  410.64  5058.8  413.94  5066.6  415.89  5181.6  422.99
  5188.3  424.41  5194.4  423.81  5217.8  424.78  5324.8  430.67  5389.9  431.49
#Mann= 3 ,-1 , 0
  4411.5     .16       0  4957.6     .07       0  4961.6     .16       0
Bank Sta=4957.6,4961.6
XS Rating Curve= 0 ,0
Exp/Cntr=0.3,0.1

Type RM Length L Ch R = 1 ,8627    ,352,352,352
BEGIN DESCRIPTION:
UNT0280 IN DUCK CR 17 0
END DESCRIPTION:
XS GIS Cut Line= 4
      3599627.94      10446936.7      3599424.83     10447009.61
      3598760.77     10446996.59      3598516.55     10447095.32
#Sta/Elev= 30
  4407.6  435.26  4438.7  433.36  4494.8  428.55    4520  426.94  4525.6  426.19
  4556.3   424.5  4617.8  420.31  4622.2  419.71  4706.1  415.69  4726.1  415.27
  4756.1   413.6  4766.1  412.56  4773.1  411.19  4786.2  410.49  4826.2  410.71
  4856.2  411.57  4964.1  410.14  4964.4  409.64    4968  409.64  4968.2  410.14
  5056.2  411.29  5096.2  410.28  5146.2  410.61  5166.2  411.99  5196.2  416.39
  5283.2  423.62  5367.4  426.87  5426.4  428.19  5491.1  428.91    5551   428.6
#Mann= 3 ,-1 , 0
  4407.6     .16       0  4964.1     .07       0  4968.2     .16       0
Bank Sta=4964.1,4968.2
XS Rating Curve= 0 ,0
Exp/Cntr=0.3,0.1

Type RM Length L Ch R = 1 ,8275    ,390,390,390
BEGIN DESCRIPTION:
UNT0280 IN DUCK CR 16 0
END DESCRIPTION:
XS GIS Cut Line= 3
       3599271.2     10446272.59       3599156.6     10446574.72
      3598581.08     10446928.89
#Sta/Elev= 30
  4478.8  428.86  4522.2  430.27  4571.8  430.32  4577.2  431.13    4602  430.51
  4607.3  431.09  4632.1  431.01  4656.9  428.46  4662.2  428.95    4687  426.02
  4692.4  426.26    4742  423.09  4777.5  421.76  4796.9  423.13  4801.2   420.3
  4861.4  415.42  4934.8  411.54  4969.2  410.48  4969.5  409.98  4973.9  410.48
  5014.1  411.16  5100.8     411  5151.3  413.95  5172.6   410.9    5188  410.79
  5203.4  411.74  5218.2   410.7  5325.2   421.2  5435.3  425.82  5477.7  426.64
#Mann= 3 ,-1 , 0
  4478.8     .16       0  4969.2     .07       0  4973.9     .16       0
Bank Sta=4969.2,4973.9
XS Rating Curve= 0 ,0
Exp/Cntr=0.3,0.1

Type RM Length L Ch R = 1 ,7885    ,193,193,193
BEGIN DESCRIPTION:
UNT0280 IN DUCK CR 15 0
END DESCRIPTION:
XS GIS Cut Line= 3
      3599318.99     10446116.85      3598843.33     10446325.17
       3598468.3     10446575.19
#Sta/Elev= 30
  4549.4  428.77    4678  423.13  4695.9  420.04  4701.4  421.41  4719.3  419.96
  4724.7  420.98  4748.1   418.9  4753.6  419.43  4764.3  418.03  4771.5  415.83
    4777  417.97  4794.9  414.76  4800.3  417.11  4818.3  413.63  4823.7  415.67
  4847.1  412.53  4852.6  414.72  4870.5  412.24  4875.9  413.89  4893.9   411.6
  4899.3  412.18  4906.3  410.76  4917.2  410.36  5118.2  411.05  5166.9  412.88
    5233  410.22  5281.7  409.94  5282.1  409.44  5286.4  409.94  5519.4  417.81
#Mann= 3 ,-1 , 0
  4549.4     .16       0  5281.7     .07       0  5286.4     .16       0
Bank Sta=5281.7,5286.4
XS Rating Curve= 0 ,0
Exp/Cntr=0.3,0.1

Type RM Length L Ch R = 1 ,7692    ,51,51,51
BEGIN DESCRIPTION:
UNT0280 IN DUCK CR 14 0
END DESCRIPTION:
XS GIS Cut Line= 3
      3599055.07      10446012.2       3598721.7     10446173.68
        3598321.     10446446.89
#Sta/Elev= 30
  4738.5  428.36  4786.2  425.85  4808.5  424.26  4815.8  423.39  4830.7  422.84
  4852.9  419.86  4889.1  416.19  4897.4  418.29  4906.1  418.46  4911.6  416.18
  4928.7  411.12  4934.2  410.14  4983.9  409.93  4984.2  409.43  4988.2  409.43
  4988.6  409.93    5019  410.83  5024.5  411.48  5047.1  411.71  5069.7   410.1
  5105.9  410.55  5129.3  410.11  5156.8  410.67  5201.1  409.99  5293.9     410
  5350.7   413.3  5401.6  415.25  5423.1  415.76  5495.7  416.44  5593.9   418.9
#Mann= 3 ,-1 , 0
  4738.5     .16       0  4983.9     .07       0  4988.6     .16       0
Bank Sta=4983.9,4988.6
XS Rating Curve= 0 ,0
Exp/Cntr=0.3,0.1

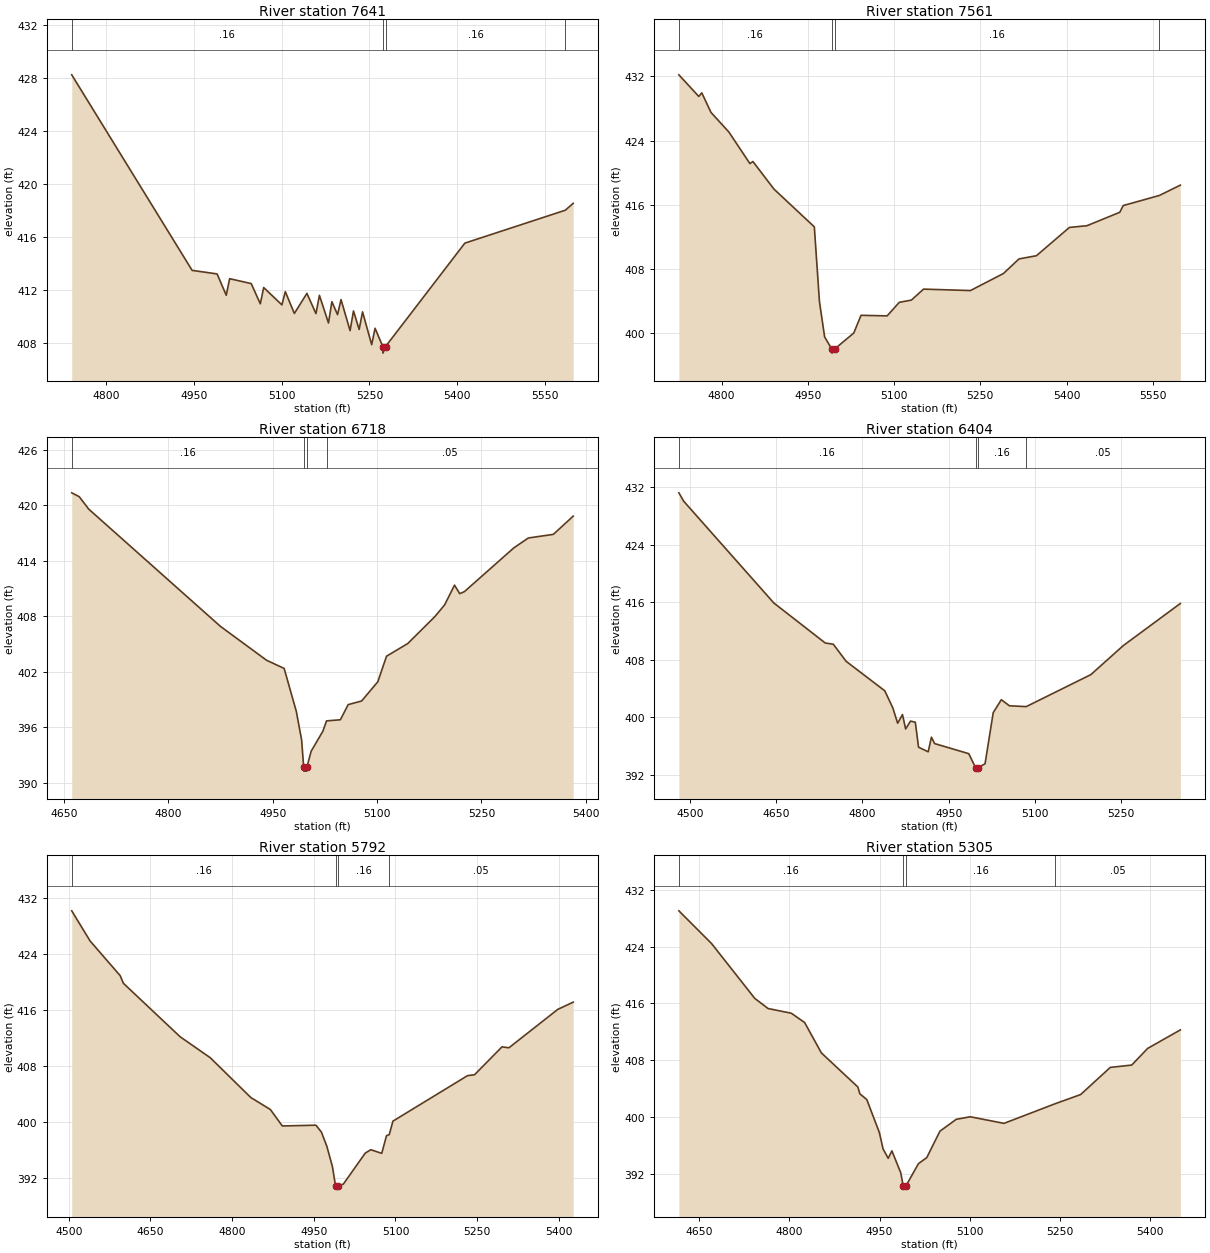
Type RM Length L Ch R = 1 ,7641    ,80,80,80
BEGIN DESCRIPTION:
UNT0280 IN DUCK CR 13.1
END DESCRIPTION:
XS GIS Cut Line= 3
      3598997.73      10445928.9      3598862.33     10446040.86
      3598278.98     10446392.44
#Sta/Elev= 30
  4741.4  428.26  4947.1  413.47  4989.8   413.2  5005.4  411.59  5011.2  412.84
  5048.1  412.47  5063.6  410.94  5069.4  412.17  5100.5  410.86  5106.3  411.86
  5121.8  410.21  5143.2  411.73  5158.7   410.2  5164.6  411.58  5180.1  409.49
  5185.9   411.1  5195.6  410.12  5201.5  411.26    5217  408.91  5222.8   410.4
  5232.5     409  5238.3  410.33  5253.9  407.85  5259.7  409.09  5272.9  407.71
  5273.2  407.21  5277.6  407.71  5413.1  415.53  5584.8  418.02  5598.2  418.54
#Mann= 4 ,-1 , 0
  4741.4     .16       0  5272.9     .07       0  5277.6     .16       0
  5584.8     .05       0
Bank Sta=5272.9,5277.6
XS Rating Curve= 0 ,0
Exp/Cntr=0.3,0.1

Type RM Length L Ch R = 1 ,7561    ,843,843,843
BEGIN DESCRIPTION:
UNT0280 IN DUCK CR 13 0
END DESCRIPTION:
XS GIS Cut Line= 3
       3598836.3     10445767.39       3598781.6     10445993.99
      3598246.13     10446342.31
#Sta/Elev= 30
  4725.9   432.2  4760.5   429.5  4765.7  429.95  4781.7  427.51  4812.7  425.07
  4849.4  421.12  4854.6  421.38  4891.3  417.93  4961.4  413.22  4970.3   403.9
  4979.3  399.48  4991.8  397.96  4992.1  397.46  4996.5  397.96    5030  399.97
  5042.6  402.18    5088  402.11  5109.1   403.8  5130.2  404.08  5151.3  405.45
  5232.8  405.27  5290.2   407.4  5317.3  409.22  5347.6  409.62  5404.9  413.15
  5435.2  413.36  5492.5  415.04  5498.5  415.88  5561.3  417.14  5597.8  418.43
#Mann= 4 ,-1 , 0
  4725.9     .16       0  4991.8     .07       0  4996.5     .16       0
  5561.3     .05       0
Bank Sta=4991.8,4996.5
XS Rating Curve= 0 ,0
Exp/Cntr=0.3,0.1

Type RM Length L Ch R = 1 ,6718    ,314,314,314
BEGIN DESCRIPTION:
UNT0280 IN DUCK CR 12 0
END DESCRIPTION:
XS GIS Cut Line= 3
      3598555.03     10445572.12      3598086.29     10445743.99
      3597922.23     10445892.42
#Sta/Elev= 30
  4661.3  421.33  4672.1  420.91  4685.7  419.57  4874.9   406.9  4941.3  403.23
  4966.5  402.35    4984   397.7  4991.6  394.62  4994.5  391.75  4994.9  391.25
    4999  391.25  4999.4  391.75  5005.3   393.4  5022.1  395.56  5027.4  396.68
  5047.3   396.8  5058.5  398.44  5077.8  398.83  5101.1  400.91  5113.6  403.67
  5144.1  405.04  5182.9  407.94  5197.1  409.22  5211.3  411.35  5218.8  410.43
  5225.5  410.65  5296.5  415.38  5317.4  416.45  5353.3  416.84  5381.8  418.81
#Mann= 4 ,-1 , 0
  4661.3     .16       0  4994.5     .07       0  4999.4     .16       0
  5027.4     .05       0
Bank Sta=4994.5,4999.4
XS Rating Curve= 0 ,0
Exp/Cntr=0.3,0.1

Type RM Length L Ch R = 1 ,6404    ,612,612,612
BEGIN DESCRIPTION:
UNT0280 IN DUCK CR 20
END DESCRIPTION:
XS GIS Cut Line= 3
      3598492.14     10445241.62      3598092.11     10445441.64
      3597792.12     10445741.63
#Sta/Elev= 30
    4481  431.22  4489.4  430.05    4646  415.89  4735.4  410.32  4749.4  410.15
  4771.7  407.77  4838.8  403.67  4852.8  401.29  4861.2  399.16  4869.6  400.36
  4875.1  398.36  4883.5  399.45  4891.9   399.3  4897.5  395.82  4914.3  395.18
  4919.9  397.21  4925.5  396.32  4984.8  394.92  4996.5  392.99  4996.9  392.49
  5001.1  392.49  5001.4  392.99  5013.1  393.51  5027.3  400.63  5041.4  402.43
  5055.5  401.58  5084.7  401.47    5197  405.92  5253.5  409.97  5352.5  415.82
#Mann= 4 ,-1 , 0
    4481     .16       0  4996.5     .07       0  5001.4     .16       0
  5084.7     .05       0
Bank Sta=4996.5,5001.4
XS Rating Curve= 0 ,0
Exp/Cntr=0.3,0.1

Type RM Length L Ch R = 1 ,5792    ,487,487,487
BEGIN DESCRIPTION:
UNT0280 IN DUCK CR 10
END DESCRIPTION:
XS GIS Cut Line= 4
      3597947.51     10444891.11      3597777.36     10445255.72
      3597756.53     10445432.81      3597648.87     10445755.77
#Sta/Elev= 30
  4505.4  430.18  4539.1  425.87  4594.3  420.91  4600.4   419.8  4704.6  412.15
  4759.8  409.16  4834.5  403.45  4870.2  401.75  4892.2  399.39    4954   399.5
  4964.1   398.5  4974.1  396.46  4984.2  393.59  4989.9  390.85  4990.3  390.35
  4994.5  390.35  4994.8  390.85  5004.3  391.07  5044.6  395.51  5054.7  395.99
  5074.8  395.47  5083.6     398  5088.6  398.14  5095.4  400.08  5232.4  406.59
  5245.3  406.72  5295.7  410.71  5308.5  410.58  5398.1  416.07  5426.5  417.11
#Mann= 4 ,-1 , 0
  4505.4     .16       0  4989.9     .07       0  4994.8     .16       0
  5088.6     .05       0
Bank Sta=4989.9,4994.8
XS Rating Curve= 0 ,0
Exp/Cntr=0.3,0.1

Type RM Length L Ch R = 1 ,5305    ,517,517,517
BEGIN DESCRIPTION:
UNT0280 IN DUCK CR 9 0
END DESCRIPTION:
XS GIS Cut Line= 5
      3597864.47     10444823.21      3597725.28     10445092.53
       3597596.8     10445273.08      3597419.72     10445464.06
      3597388.44     10445502.29
#Sta/Elev= 30
    4616  429.04  4670.3  424.44  4742.3  416.71  4764.5  415.28  4803.1  414.62
  4825.3  413.31  4853.1  409.04  4913.9  404.23  4917.2  403.27  4928.7  402.47
  4949.6  397.84  4955.8  395.52  4964.4  394.19  4970.5  395.24  4985.3  392.15
  4989.2  390.35  4989.6  389.85  4994.2  390.35  5014.8  393.45  5028.5  394.28
  5050.5  398.01  5077.6  399.68  5100.9  400.04  5157.1  399.11  5242.7  401.89
  5284.7  403.17    5334  406.99  5369.7  407.32  5396.1  409.66  5450.6  412.27
#Mann= 4 ,-1 , 0
    4616     .16       0  4989.2     .07       0  4994.2     .16       0
  5242.7     .05       0
Bank Sta=4989.2,4994.2
XS Rating Curve= 0 ,0
Exp/Cntr=0.3,0.1

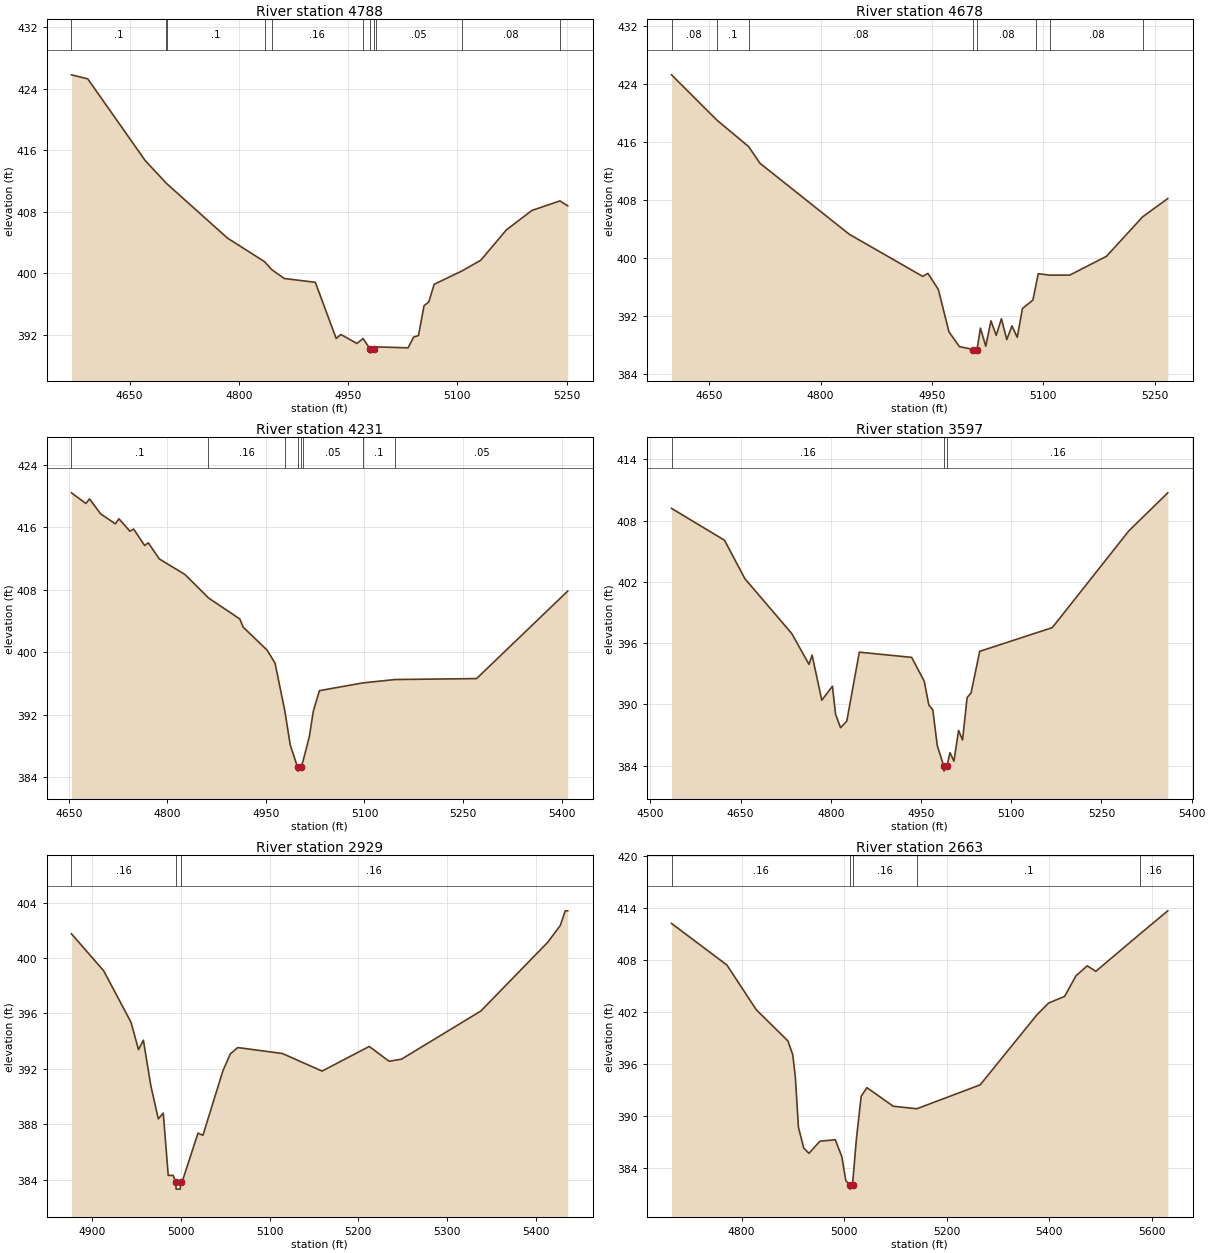
Type RM Length L Ch R = 1 ,4788    ,110,110,110
BEGIN DESCRIPTION:
UNT0280 IN DUCK CR 8 1
END DESCRIPTION:
XS GIS Cut Line= 2
      3597779.02     10444806.47      3597263.39     10445251.78
#Sta/Elev= 30
  4570.2  425.81  4592.5  425.29  4671.4  414.66  4700.1  411.74  4701.3  411.63
  4784.4  404.57  4835.3  401.51  4844.9  400.49  4862.3  399.32    4905  398.82
  4933.6  391.52  4940.2  392.03  4962.1  390.87  4970.5  391.51  4980.4  390.11
  4980.8  389.61  4985.4  390.11  4988.6  390.42  5032.3   390.3    5040  391.71
  5046.6  391.89  5054.2  395.77  5060.8  396.28  5068.2  398.57  5105.7  400.27
  5132.1  401.69  5167.2  405.63  5202.3  408.17  5240.8  409.41  5251.5  408.77
#Mann= 11 ,-1 , 0
  4570.2      .1       0  4700.1     .08       0  4701.3      .1       0
  4835.3     .08       0  4844.9     .16       0  4970.5     .08       0
  4980.4     .03       0  4985.4     .08       0  4988.6     .05       0
  5105.7     .08       0  5240.8     .05       0
Bank Sta=4980.4,4985.4
XS Rating Curve= 0 ,0
Exp/Cntr=0.3,0.1

Type RM Length L Ch R = 1 ,4678    ,447,447,447
BEGIN DESCRIPTION:
UNT0280 IN DUCK CR 8 0
END DESCRIPTION:
XS GIS Cut Line= 2
      3597729.53     10444720.54      3597250.37     10445186.68
#Sta/Elev= 30
  4599.1  425.23  4660.2  418.99  4703.1  415.32  4718.3  413.03  4838.5  403.25
  4937.5  397.44  4944.5  397.86  4958.6  395.62  4972.8   389.8  4986.9  387.76
  5005.7  387.36  5006.1  386.86  5010.7  387.36  5015.2  390.31  5022.4  387.81
  5029.4  391.31  5036.5   389.3  5043.5  391.61  5050.7  388.72  5057.7  390.62
  5064.8  389.04  5071.8  393.02  5085.9  394.17  5090.3  396.39  5093.1  397.81
    5109  397.61  5135.6  397.62    5185  400.21  5233.7  405.65  5267.6  408.17
#Mann= 8 ,-1 , 0
  4599.1     .08       0  4660.2      .1       0  4703.1     .08       0
  5005.7     .07       0  5010.7     .08       0  5090.3     .05       0
    5109     .08       0  5233.7     .05       0
Bank Sta=5005.7,5010.7
XS Rating Curve= 0 ,0
Exp/Cntr=0.3,0.1

Type RM Length L Ch R = 1 ,4231    ,634,634,634
BEGIN DESCRIPTION:
UNT0280 IN DUCK CR 7 0
END DESCRIPTION:
XS GIS Cut Line= 4
      3597676.71     10444616.82       3597447.5     10444731.42
      3597226.27     10444867.21      3597142.12     10445091.61
#Sta/Elev= 30
  4653.9  420.39  4675.8  419.03  4681.4  419.61  4698.2  417.71  4720.6  416.43
  4726.2  417.07  4742.9  415.48  4748.5  415.76  4765.3  413.65  4770.9     414
  4787.6  411.94  4826.7  409.95  4862.5  406.95  4910.2  404.26  4915.4  403.21
  4951.7  400.28  4963.8  398.62  4978.7  392.52  4986.9  388.18  4998.1  385.31
  4998.5  384.81  5003.1  385.31  5006.3  386.05    5016  389.21  5022.1  392.47
  5031.4   395.1  5097.6  396.09  5146.4  396.52  5270.6  396.64  5409.4  407.83
#Mann= 8 ,-1 , 0
  4653.9      .1       0  4862.5     .16       0  4978.7      .1       0
  4998.1     .07       0  5003.1      .1       0  5006.3     .05       0
  5097.6      .1       0  5146.4     .05       0
Bank Sta=4998.1,5003.1
XS Rating Curve= 0 ,0
Exp/Cntr=0.3,0.1

Type RM Length L Ch R = 1 ,3597    ,668,668,668
BEGIN DESCRIPTION:
UNT0280 IN DUCK CR 6 0
END DESCRIPTION:
XS GIS Cut Line= 3
      3597071.18     10444261.41      3596971.19     10444611.38
      3596621.15     10444911.42
#Sta/Elev= 30
  4535.3  409.19  4623.4  406.07  4657.2  402.31  4735.2  396.94  4763.8  393.93
    4769  394.83  4785.1  390.42  4802.8  391.79    4808  389.05  4816.3  387.73
  4826.7  388.38  4847.5  395.12  4934.5  394.61  4955.4  392.28  4963.1  389.94
  4969.7  389.47  4977.1  385.97  4987.8  383.98  4988.2  383.48  4993.3  383.98
  4998.2  385.29  5004.8  384.46  5012.5  387.46  5019.1  386.53  5026.7  390.68
  5033.3  391.13  5047.6   395.2  5168.3  397.52  5295.6  406.99  5360.3  410.71
#Mann= 3 ,-1 , 0
  4535.3     .16       0  4987.8     .07       0  4993.3     .16       0
Bank Sta=4987.8,4993.3
XS Rating Curve= 0 ,0
Exp/Cntr=0.3,0.1

Type RM Length L Ch R = 1 ,2929    ,266,266,266
BEGIN DESCRIPTION:
UNT0280 IN DUCK CR 5 0
END DESCRIPTION:
XS GIS Cut Line= 3
       3596742.1     10444241.65      3596692.11     10444341.64
      3596492.11     10444741.64
#Sta/Elev= 30
  4876.9  401.75  4913.2  399.08    4944  395.36  4952.4  393.39  4957.9  394.07
  4966.3  390.79  4974.7  388.39  4980.3  388.81  4985.9  384.31  4991.5  384.31
  4994.3  383.82  4994.8  383.32  4999.4  383.32  4999.8  383.82  5002.7  384.07
  5019.4  387.36    5025  387.21  5047.4  391.85  5055.8  393.08  5064.2  393.54
  5114.5  393.11  5159.2  391.84  5212.3  393.62  5234.7  392.55  5248.6   392.7
  5338.1  396.18  5413.5  401.15  5427.5  402.35  5433.1  403.41  5435.9  403.41
#Mann= 3 ,-1 , 0
  4876.9     .16       0  4994.3     .07       0  4999.8     .16       0
Bank Sta=4994.3,4999.8
XS Rating Curve= 0 ,0
Exp/Cntr=0.3,0.1

Type RM Length L Ch R = 1 ,2663    ,633,633,633
BEGIN DESCRIPTION:
UNT0280 IN DUCK CR 4 0
END DESCRIPTION:
XS GIS Cut Line= 3
      3596521.19     10443970.53        3596404.     10444478.36
      3596219.11     10444884.59
#Sta/Elev= 30
  4663.5   412.2  4771.5  407.41  4828.8  402.26  4890.4  398.68  4899.8   397.1
  4904.9  394.52  4910.9  388.75  4921.2  386.35  4931.5  385.74  4952.8  387.14
  4982.8   387.3  4995.6  385.34  5003.3  382.59  5010.8  382.12  5011.2  381.62
  5016.4  382.12  5023.8  387.32  5033.2   392.3  5044.4   393.3  5095.7  391.16
  5141.7  390.87  5265.2  393.62  5375.4  401.65  5398.5  403.03    5430  403.81
    5452  406.17  5473.9  407.32  5490.7  406.69  5577.3  411.01    5631  413.65
#Mann= 5 ,-1 , 0
  4663.5     .16       0  5010.8     .07       0  5016.4     .16       0
  5141.7      .1       0  5577.3     .16       0
Bank Sta=5010.8,5016.4
XS Rating Curve= 0 ,0
Exp/Cntr=0.3,0.1

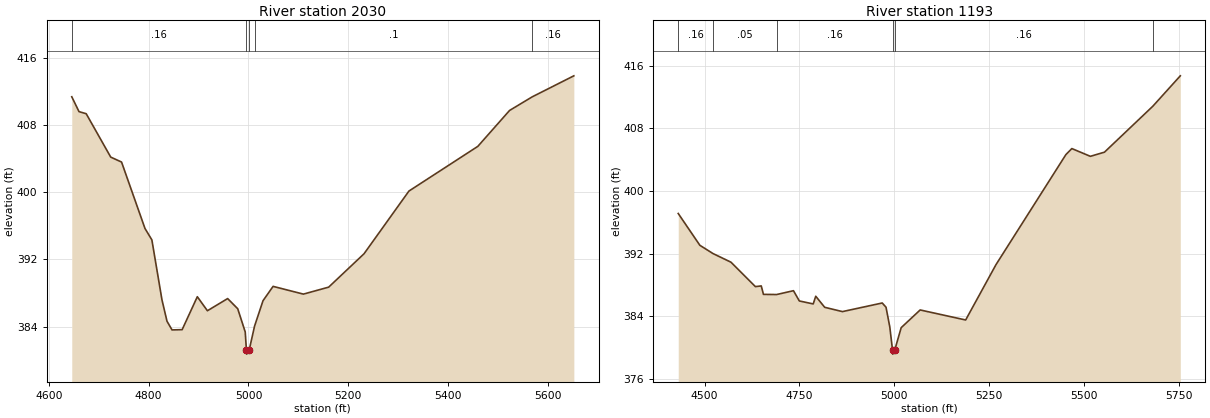
Type RM Length L Ch R = 1 ,2030    ,837,837,837
BEGIN DESCRIPTION:
UNT0280 IN DUCK CR 1 1
END DESCRIPTION:
XS GIS Cut Line= 3
      3596039.42     10443973.12      3595932.64     10444673.68
      3596135.79     10444889.85
#Sta/Elev= 30
  4646.2  411.35  4660.7  409.58  4675.1  409.33  4724.2  404.17  4745.9  403.58
  4792.8  395.68  4806.6  394.32  4826.8  387.19  4836.9  384.64    4847  383.61
  4867.2  383.64  4897.6  387.56  4917.8  385.89  4958.3  387.34  4978.5  386.13
  4993.5  383.37  4995.9  381.23  4996.4  380.73  5001.5  381.23  5012.2  384.06
  5029.1  387.08  5049.3  388.79    5110  387.87  5160.6   388.7  5231.4  392.67
  5321.3  400.13  5459.3  405.45  5522.8  409.72  5568.5  411.35  5651.5  413.84
#Mann= 5 ,-1 , 0
  4646.2     .16       0  4995.9     .07       0  5001.5     .16       0
  5012.2      .1       0  5568.5     .16       0
Bank Sta=4995.9,5001.5
XS Rating Curve= 0 ,0
Exp/Cntr=0.3,0.1

Type RM Length L Ch R = 1 ,1193    ,938,938,938
BEGIN DESCRIPTION:
UNT0280 IN DUCK CR 21 0
END DESCRIPTION:
XS GIS Cut Line= 4
      3595750.35     10444009.62      3595380.56     10444238.78
      3595377.95      10444689.3       3595598.5     10445068.11
#Sta/Elev= 30
  4430.7  397.11  4487.7  393.05  4522.5  391.99  4569.8  390.89  4634.2  387.77
  4649.6  387.86  4655.4  386.78  4690.2  386.76  4734.6  387.25    4750  385.94
  4786.6  385.56  4793.3  386.54  4816.9  385.13  4863.7  384.58  4968.6  385.68
  4978.6  385.14  4988.6  382.61  4995.8  379.65  4996.2  379.15  5001.5  379.65
  5018.6  382.53  5068.6  384.79  5188.6  383.51  5268.6  390.58  5452.9  404.63
  5468.6   405.4  5517.4  404.41  5554.6  404.94    5682   410.8  5754.6  414.69
#Mann= 6 ,-1 , 0
  4430.7     .16       0  4522.5     .05       0  4690.2     .16       0
  4995.8     .07       0  5001.5     .16       0    5682      .1       0
Bank Sta=4995.8,5001.5
XS Rating Curve= 0 ,0
Exp/Cntr=0.3,0.1

Chan Stop Cuts=-1
Use User Specified Reach Order=0
Composite Channel Slope=5