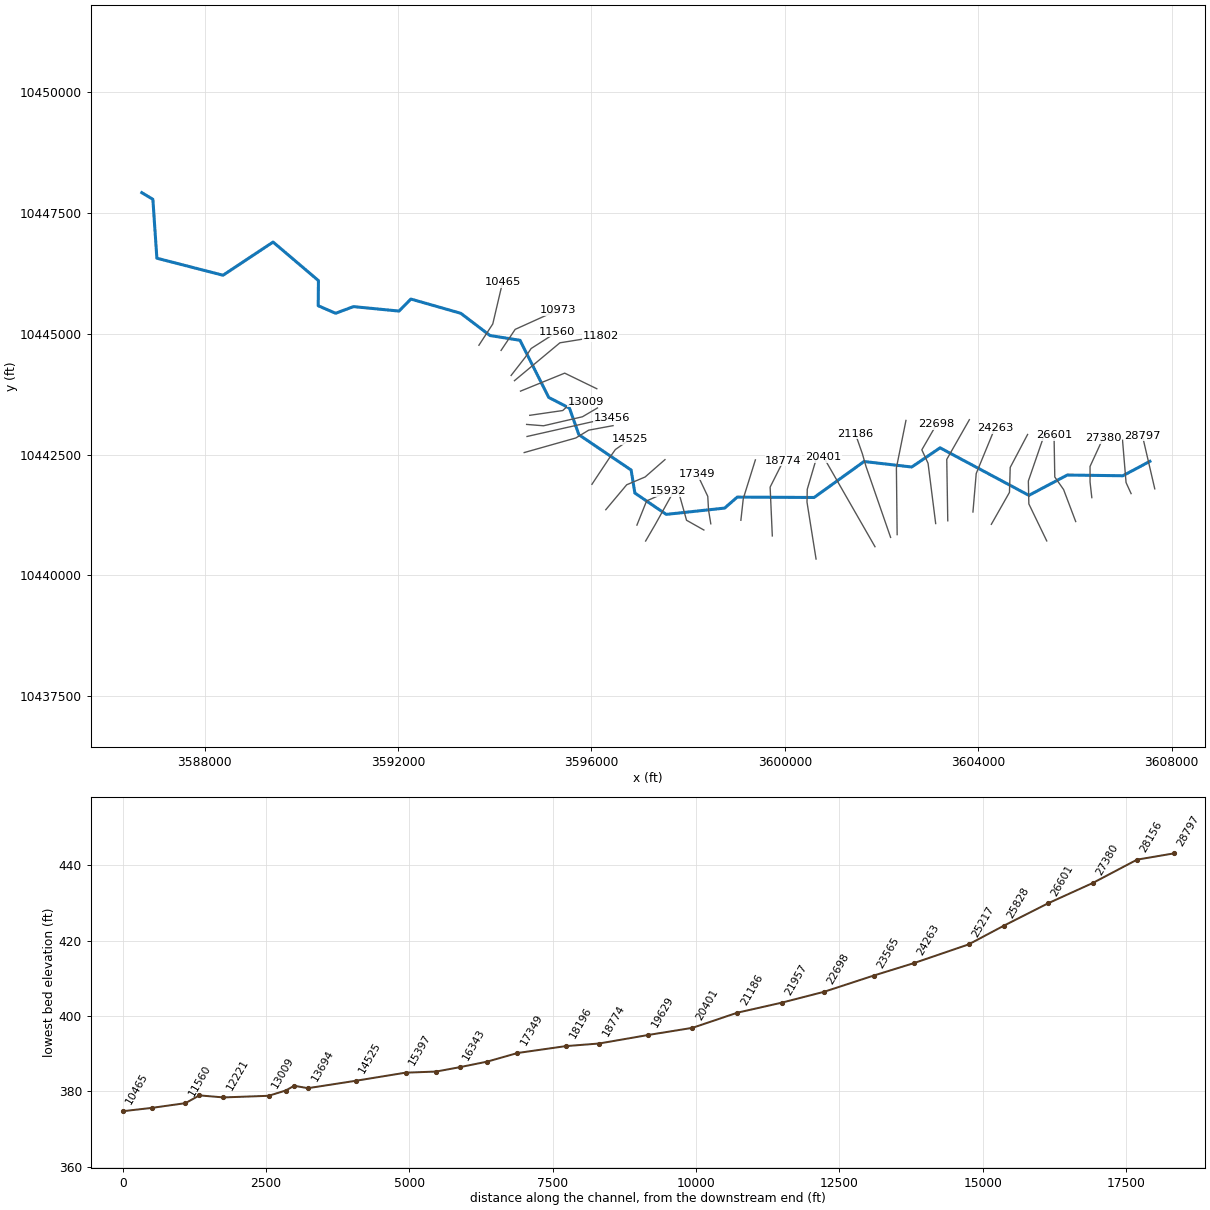
--- BUCK CREEK.prj (project) ---

Proj Title=BUCK CREEK Base Level Engineering
Current Plan=p01
Default Exp/Contr=0.3,0.1
English Units
Geom File=g01
Flow File=f01
Plan File=p01
Y Axis Title=Elevation
X Axis Title(PF)=Main Channel Distance
X Axis Title(XS)=Station
BEGIN DESCRIPTION:
BUCK CREEK
END DESCRIPTION:
DSS Export Rating Curves= 0
DSS Export Rating Curve Sorted= 0
DSS Export Volume Flow Curves= 0
DXF OffsetX= 0
DXF OffsetY= 0
DXF ScaleX= 1
DXF ScaleY= 10

--- BUCK CREEK.p01 (plan) ---

Plan Title=Multiple Run
Short Identifier=Multiple
Geom File=g01
Flow File=f01
Subcritical Flow
K Sum by GR= 0
Std Step Tol= 0.01
Critical Tol= 0.01
Num of Std Step Trials= 20
Max Error Tol= 0.3
Flow Tol Ratio= 0.001
Split Flow NTrial= 30
Split Flow Tol= 0.02
Split Flow Ratio= 0.02
Log Output Level= 0
Friction Slope Method= 1
Unsteady Friction Slope Method= 2
Unsteady Bridges Friction Slope Method= 1
Parabolic Critical Depth
Global Vel Dist=  1 , 1 , 1
Global Log Level= 0
CheckData=True
Encroach Param= -1, 0, 0, 0
BEGIN DESCRIPTION:
Multiple Run
END DESCRIPTION:

--- BUCK CREEK.f01 (steady flow) ---

Flow Title=Multiple
Program Version=4.10
Number of Profiles= 7
Profile Names=10-year,25-year,50-year,1pct_min,100-year,1pct_plu,500-year
River Rch & RM=BUCK CREEK,Reach-1         ,28797
    1940    2774    3489    3198    4325    5849    6629
River Rch & RM=BUCK CREEK,Reach-1         ,21186
    2462    3560    4512    4162    5628    7612    8741
River Rch & RM=BUCK CREEK,Reach-1         ,17349
    2562    3706    4698    4333    5860    7926    9101
River Rch & RM=BUCK CREEK,Reach-1         ,16343
    4491    6646    8554    7999   10818   14630   17266
River Rch & RM=BUCK CREEK,Reach-1         ,11802
    5412    8049   10394    9743   13177   17820   21139
River Rch & RM=BUCK CREEK,Reach-1         ,10973
    5412    8049   10394    9743   13177   17820   21139
River Rch & RM=BUCK CREEK,Reach-1         ,5432
    5418    8040   10365    9700   13118   17741   20972
Boundary for River Rch & Prof#=BUCK CREEK,Reach-1         , 1
Up Type= 0
Dn Type= 3
Dn Slope=0.004
Boundary for River Rch & Prof#=BUCK CREEK,Reach-1         , 2
Up Type= 0
Dn Type= 3
Dn Slope=0.004
Boundary for River Rch & Prof#=BUCK CREEK,Reach-1         , 3
Up Type= 0
Dn Type= 3
Dn Slope=0.004
Boundary for River Rch & Prof#=BUCK CREEK,Reach-1         , 4
Up Type= 0
Dn Type= 3
Dn Slope=0.004
Boundary for River Rch & Prof#=BUCK CREEK,Reach-1         , 5
Up Type= 0
Dn Type= 3
Dn Slope=0.004
Boundary for River Rch & Prof#=BUCK CREEK,Reach-1         , 6
Up Type= 0
Dn Type= 3
Dn Slope=0.004
Boundary for River Rch & Prof#=BUCK CREEK,Reach-1         , 7
Up Type= 0
Dn Type= 3
Dn Slope=0.004
DSS Import GetInterval= 0
DSS Import GetPeak= 0
DSS Import FillOption= 0

--- BUCK CREEK.g01 (geometry) ---

Geom Title=Existing Conditions
Program Version=4.10

River Reach=BUCK CREEK      ,Reach-1
Reach XY= 30
      3607552.11     10442361.64      3606992.37     10442062.84
      3605843.65     10442078.03      3605048.54     10441657.42
      3603211.98     10442640.72      3602626.14     10442244.08
      3601639.38     10442357.67      3600606.62     10441613.28
      3599017.07     10441621.33      3598756.52     10441393.72
      3597547.91     10441263.49      3596899.56     10441705.05
      3596822.28      10442181.3      3595742.43     10442911.57
      3595546.64     10443462.21      3595117.41     10443684.79
      3594524.69     10444866.23      3593903.57     10444965.19
      3593298.94     10445425.37      3592266.36     10445719.85
      3592021.62       10445471.      3591079.81     10445563.26
      3590710.97     10445425.59      3590350.49     10445581.05
      3590355.04     10446101.86      3589416.86     10446899.61
      3588381.59     10446212.62      3587013.47     10446565.18
       3586930.8     10447784.26      3586702.11     10447921.64

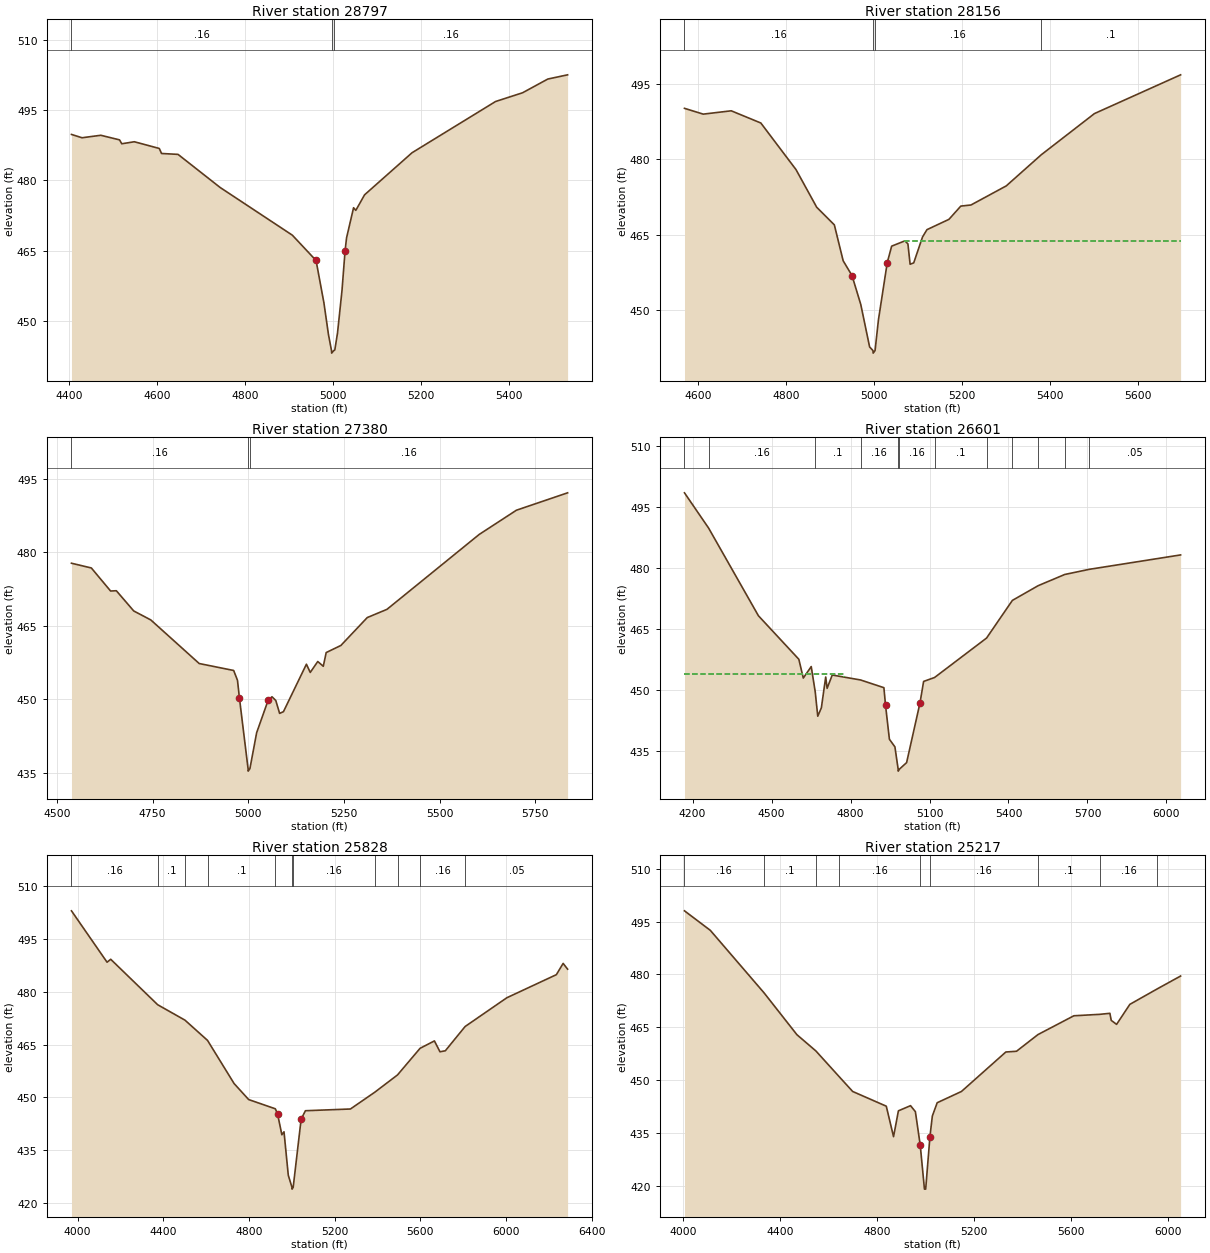
Type RM Length L Ch R = 1 ,28797   ,641,641,641
BEGIN DESCRIPTION:
UNT0277 IN DUCK CR 5 0
END DESCRIPTION:
XS GIS Cut Line= 2
      3607652.34     10441792.38      3607397.13     10442891.33
#Sta/Elev= 30
  4405.6  489.79  4429.6  489.08  4472.3  489.61  4514.9  488.63    4520   487.8
  4548.6  488.23  4605.3   486.8  4610.4  485.73  4647.9  485.54  4743.6  478.49
  4907.9  468.32  4961.8  462.93  4979.7  453.89    4990  447.15    4997  443.69
  4997.3  443.19  5001.6  443.69  5004.4  443.85  5010.5  447.41  5020.8  456.57
 5027.74  464.94  5031.1  467.73  5047.1  474.17  5052.2  473.61  5072.1  476.92
  5180.1  485.89  5369.9   496.8  5431.5  498.67  5488.8  501.59  5533.8  502.49
#Mann= 3 ,-1 , 0
  4405.6     .16       0    4997     .07       0  5001.6     .16       0
Bank Sta=4961.8,5027.74
XS Rating Curve= 0 ,0
Exp/Cntr=0.3,0.1

Type RM Length L Ch R = 1 ,28156   ,776,776,776
BEGIN DESCRIPTION:
UNT0277 IN DUCK CR 4 0
END DESCRIPTION:
XS GIS Cut Line= 3
      3607162.77     10441693.38      3607058.59     10441922.57
      3606985.72     10442797.08
#Sta/Elev= 30
  4568.6  490.12  4611.3  488.97    4675  489.63  4742.4  487.21  4822.4  477.97
  4869.6  470.49  4909.7     467  4929.8  459.87  4949.9  456.94  4969.9   451.2
    4990  442.77  4997.7  442.04  4998.1  441.54  5002.4  442.04  5010.1  448.15
  5030.2  459.52  5040.2  462.77  5070.3  463.82  5077.2  463.22  5082.2  459.18
  5090.4  459.45  5110.4  464.58  5120.5  466.04  5170.6  468.09  5197.6  470.72
  5220.8  470.94  5301.1  474.73  5380.8  480.91  5501.8  489.08  5697.9  496.77
#Mann= 4 ,-1 , 0
  4568.6     .16       0  4997.7     .07       0  5002.4     .16       0
  5380.8      .1       0
#XS Ineff= 2 , 0
                         5068.46          463.88
Permanent Ineff=
       F       F
Bank Sta=4949.9,5030.2
XS Rating Curve= 0 ,0
Exp/Cntr=0.3,0.1

Type RM Length L Ch R = 1 ,27380   ,779,779,779
BEGIN DESCRIPTION:
UNT0277 IN DUCK CR 37 0
END DESCRIPTION:
XS GIS Cut Line= 4
      3606350.26     10441610.12       3606313.8     10441932.99
       3606313.8     10442255.91      3606584.63     10442844.44
#Sta/Elev= 30
  4538.3  477.78  4590.2  476.81  4640.5   472.1  4655.5  472.16  4700.9  468.03
  4745.4   466.2  4871.9  457.29  4961.9  455.87  4971.9  453.86 4977.07  450.17
  4999.5  435.81  4999.8  435.31  5004.3  435.81  5021.9  443.15  5051.9  449.78
  5061.9   450.5  5071.9  449.74  5081.9  447.11  5091.9  447.45  5151.9  457.15
  5161.9  455.47  5181.5   457.7    5196  456.73  5203.5  459.53  5241.9  460.98
  5310.8  466.68  5362.3  468.36    5603  483.65  5700.4  488.61    5834  492.16
#Mann= 3 ,-1 , 0
  4538.3     .16       0  4999.5     .07       0  5004.3     .16       0
Bank Sta=4977.07,5051.9
XS Rating Curve= 0 ,0
Exp/Cntr=0.3,0.1

Type RM Length L Ch R = 1 ,26601   ,773,773,773
BEGIN DESCRIPTION:
UNT0277 IN DUCK CR 36 0
END DESCRIPTION:
XS GIS Cut Line= 4
      3606016.94     10441115.25      3605766.93     10441776.74
      3605584.63     10442037.16      3605569.01     10442896.58
#Sta/Elev= 30
  4169.2  498.49  4260.8  489.81  4450.1   468.2  4603.6  457.48  4620.5  452.85
  4650.7  455.68  4665.8  449.48  4675.5  443.45  4689.2  445.53  4705.7  453.11
    4711  450.32  4730.5   453.6  4838.1  452.38  4926.7  450.48  4932.8  446.21
  4947.6  437.78  4968.6  435.89  4980.8  430.42  4981.2  429.92  4985.9  430.42
    5013  432.02  5063.6  446.66  5077.6  452.02  5119.2  452.99  5316.6   462.7
  5414.7  471.98  5512.7  475.61  5613.6  478.37  5706.9  479.64  6053.8  483.19
#Mann= 12 ,-1 , 0
  4169.2     .05       0  4260.8     .16       0  4665.8      .1       0
  4838.1     .16       0  4980.8     .07       0  4985.9     .16       0
  5119.2      .1       0  5316.6     .05       0  5414.7      .1       0
  5512.7     .05       0  5613.6      .1       0  5706.9     .05       0
#XS Ineff= 2 , 0
         4773.84  453.79
Permanent Ineff=
       F       F
Bank Sta=4932.8,5063.6
XS Rating Curve= 0 ,0
Exp/Cntr=0.3,0.1

Type RM Length L Ch R = 1 ,25828   ,611,611,611
BEGIN DESCRIPTION:
UNT0277 IN DUCK CR 34 0
END DESCRIPTION:
XS GIS Cut Line= 4
      3605417.99      10440714.2      3605048.18     10441479.86
      3605037.76     10441953.82      3605360.67      10442891.3
#Sta/Elev= 30
  3971.4  502.94  4137.5  488.36  4154.6  489.19  4373.8  476.29  4501.3  471.91
  4606.5  466.17  4730.7  453.91  4798.5  449.38    4923  446.76  4933.5  445.27
  4953.5  439.39  4963.5  440.23  4983.5   427.9  5000.8  424.46  5001.2  423.96
  5006.3  424.46  5043.5  443.83  5063.5  446.21  5273.6   446.7  5388.1   451.5
  5493.4  456.37  5598.6  463.92  5665.6  466.02  5691.5  462.94  5716.5  463.22
    5809  470.11  6003.7  478.27  6234.8  484.82  6266.5  488.02  6287.3  486.39
#Mann= 11 ,-1 , 0
  3971.4     .16       0  4373.8      .1       0  4501.3     .16       0
  4606.5      .1       0    4923     .16       0  5000.8     .07       0
  5006.3     .16       0  5388.1      .1       0  5493.4     .05       0
  5598.6     .16       0    5809     .05       0
Bank Sta=4933.5,5043.5
XS Rating Curve= 0 ,0
Exp/Cntr=0.3,0.1

Type RM Length L Ch R = 1 ,25217   ,954,954,954
BEGIN DESCRIPTION:
UNT0277 IN DUCK CR 30 0
END DESCRIPTION:
XS GIS Cut Line= 4
      3604272.12     10441057.96      3604647.13     10441719.45
      3604662.76     10442235.07      3605021.95     10442917.01
#Sta/Elev= 30
  4006.9  498.07  4113.6  492.52  4335.5  474.75  4470.9  462.88  4549.2  458.26
  4646.4  450.87  4700.8  446.76  4839.5  442.58  4869.5  433.92  4889.5  441.26
  4939.6  442.73  4959.6  441.02  4979.6  431.53    4997  419.02  5002.1  419.02
  5019.6  433.92  5029.6   439.8  5049.6  443.56  5149.7  446.76  5332.8  457.97
  5376.8  458.18  5465.4  462.92  5613.5  468.26  5720.6  468.67  5762.1  468.96
  5767.7  466.95  5789.8  465.82  5844.4   471.5  5956.5  475.86  6053.9  479.55
#Mann= 9 ,-1 , 0
  4006.9     .16       0  4335.5      .1       0  4549.2     .05       0
  4646.4     .16       0  4979.6     .07       0  5019.6     .16       0
  5465.4      .1       0  5720.6     .16       0  5956.5     .05       0
#XS Ineff= 2 , 0
          4938.6  442.53
Permanent Ineff=
       F       F
Bank Sta=4979.6,5019.6
XS Rating Curve= 0 ,0
Exp/Cntr=0.3,0.1

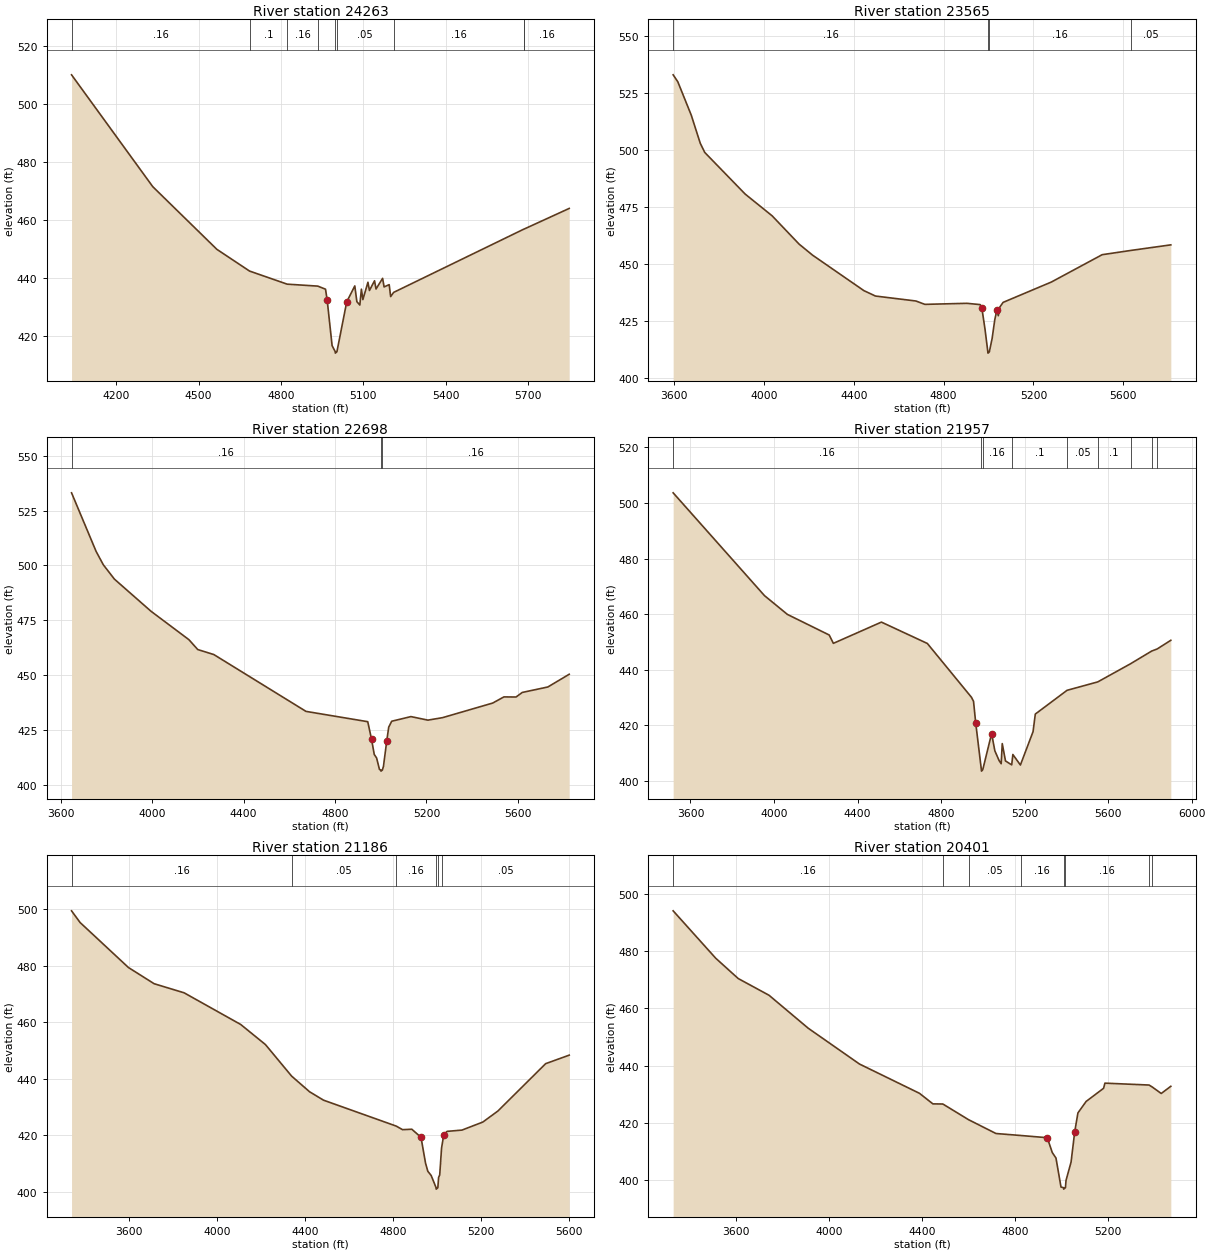
Type RM Length L Ch R = 1 ,24263   ,698,698,698
BEGIN DESCRIPTION:
UNT0277 IN DUCK CR 3 0
END DESCRIPTION:
XS GIS Cut Line= 3
      3603891.93     10441313.25      3603959.63     10442110.07
      3604344.85     10443047.08
#Sta/Elev= 30
  4037.4  510.16  4333.3  471.53  4566.8  449.89  4685.8  442.39  4822.8  437.87
  4934.4  437.19  4962.5  436.13  4968.5  432.43  4986.5  416.65  4997.9  414.55
  4998.4  414.05  5004.1  414.55  5039.8  431.77  5069.2  437.26  5076.7  431.82
  5087.5  430.66  5093.2  436.14  5098.6  432.54  5117.1  438.53  5122.5  435.68
  5141.1  439.04  5146.5  436.19  5170.5  439.89  5175.9  436.91  5194.4   437.7
  5199.8  433.59  5210.8  435.03  5684.3  456.84  5685.4  456.87  5850.2  464.02
#Mann= 9 ,-1 , 0
  4037.4     .16       0  4685.8      .1       0  4822.8     .16       0
  4934.4     .05       0  4997.9     .04       0  5004.1     .05       0
  5210.8     .16       0  5684.3     .05       0  5685.4     .16       0
Bank Sta=4968.5,5039.8
XS Rating Curve= 0 ,0
Exp/Cntr=0.3,0.1

Type RM Length L Ch R = 1 ,23565   ,867,867,867
BEGIN DESCRIPTION:
UNT0277 IN DUCK CR 29 0
END DESCRIPTION:
XS GIS Cut Line= 3
      3603371.09     10441130.94      3603350.26     10442401.74
      3603818.06     10443222.98
#Sta/Elev= 30
  3595.7  533.07  3616.4  530.02  3676.4  515.32  3716.4  502.99  3736.4  498.96
  3916.4  480.66  4036.5   471.1  4156.5  458.67  4216.5  453.82  4445.3  438.21
  4496.5  435.85  4676.5  433.67  4716.6  432.19  4903.8  432.65  4962.8  432.09
  4970.1  430.76  4984.5   421.2  4997.1  411.26  4997.6  410.76  5003.5  411.26
  5016.2  417.27  5027.7  425.34  5037.8  429.89  5043.5  427.19  5050.7  431.05
  5065.1  433.07  5279.8     442  5506.1  454.02  5633.8  455.89  5811.8  458.34
#Mann= 4 ,-1 , 0
  3595.7     .16       0  4997.1     .07       0  5003.5     .16       0
  5633.8     .05       0
Bank Sta=4970.1,5037.8
XS Rating Curve= 0 ,0
Exp/Cntr=0.3,0.1

Type RM Length L Ch R = 1 ,22698   ,741,741,741
BEGIN DESCRIPTION:
UNT0277 IN DUCK CR 27 0
END DESCRIPTION:
XS GIS Cut Line= 4
      3603121.09     10441073.66      3602963.46     10442320.84
      3602834.63     10442599.66      3603141.95     10443130.94
#Sta/Elev= 30
  3646.7  533.06  3754.3  506.39  3785.8  500.31  3834.5  493.78  3994.9  479.14
  4160.4  466.24    4199  461.76  4269.6  459.47  4672.8  433.62    4943  428.93
  4959.8  420.84  4971.5  414.02  4981.8  412.43  4994.4  407.17  5000.5  406.94
    5001  406.44  5007.1  406.94  5011.8  408.64  5025.9  419.99  5034.8  426.44
  5047.9  429.14    5132  431.25  5206.3  429.64  5270.5  430.77  5490.1  437.42
  5538.9  440.21    5592  440.16  5619.3  442.24  5731.2  444.72  5824.7  450.51
#Mann= 3 ,-1 , 0
  3646.7     .16       0  5000.5     .07       0  5007.1     .16       0
Bank Sta=4959.8,5025.9
XS Rating Curve= 0 ,0
Exp/Cntr=0.3,0.1

Type RM Length L Ch R = 1 ,21957   ,771,771,771
BEGIN DESCRIPTION:
UNT0277 IN DUCK CR 25 0
END DESCRIPTION:
XS GIS Cut Line= 3
      3602324.22     10440844.47      3602308.59     10442224.66
      3602506.26     10443207.81
#Sta/Elev= 30
  3517.1  503.62  3954.3  466.66  4064.3  459.89  4264.3  452.49  4284.3  449.49
  4514.3  457.13  4734.3  449.45  4945.5   430.1  4955.5  428.65  4965.7  421.02
    4993  404.04  4993.5  403.54  4999.6  404.04  5042.1  417.05  5057.5  410.85
  5077.9  407.35  5087.9   406.2    5093  413.44  5108.5  407.21  5138.3  405.78
  5143.8  409.52  5179.9  405.74  5240.5  417.73  5251.3  424.06  5403.3   432.6
  5550.5  435.63  5707.5  442.16  5808.4  446.71  5834.9  447.47  5900.2  450.59
#Mann= 9 ,-1 , 0
  3517.1     .16       0    4993     .07       0  4999.6     .16       0
  5138.3      .1       0  5403.3     .05       0  5550.5      .1       0
  5707.5     .05       0  5808.4      .1       0  5834.9     .05       0
Bank Sta=4965.7,5042.1
XS Rating Curve= 0 ,0
Exp/Cntr=0.3,0.1

Type RM Length L Ch R = 1 ,21186   ,785,785,785
BEGIN DESCRIPTION:
UNT0277 IN DUCK CR 24 0
END DESCRIPTION:
XS GIS Cut Line= 4
      3602188.81     10440787.12      3601678.38     10442261.11
      3601605.47     10442516.32      3601459.65     10442932.95
#Sta/Elev= 30
  3336.5  499.51  3375.3  495.38  3595.3  479.44  3712.7  473.68  3849.2  470.46
  4107.1  459.23  4219.6  452.12    4339  440.93  4420.7  435.39  4484.2  432.41
  4815.2  423.23  4844.2  421.96  4886.3  422.11  4928.1  419.27  4948.9  410.07
  4959.3  407.21  4974.4  405.74    4997  401.39  4997.5  400.89  5004.9  401.39
  5008.2  405.01  5013.4  405.93  5021.8  415.46  5032.1  420.24  5047.2  421.36
  5114.8  421.81  5209.8  424.66  5278.3  428.56  5495.9  445.35  5603.2  448.37
#Mann= 6 ,-1 , 0
  3336.5     .16       0    4339     .05       0  4815.2     .16       0
    4997     .07       0  5004.9     .16       0  5021.8     .05       0
Bank Sta=4928.1,5032.1
XS Rating Curve= 0 ,0
Exp/Cntr=0.3,0.1

Type RM Length L Ch R = 1 ,20401   ,772,772,772
BEGIN DESCRIPTION:
UNT0277 IN DUCK CR 2 1
END DESCRIPTION:
XS GIS Cut Line= 2
      3601865.86     10440594.49      3600803.97      10442447.6
#Sta/Elev= 30
  3332.3  494.13    3515  477.56  3611.4  470.47  3743.9  464.61  3912.1  453.09
  4132.2  440.57  4389.4  430.35    4447  426.66  4489.7  426.61  4600.3  421.12
  4717.7   416.3  4824.6   415.6  4937.8  414.83  4959.4  409.64  4975.2  407.73
  4996.8  397.58  5007.7  397.36  5008.2  396.86  5015.8  397.36  5018.4  399.91
    5040  406.31  5055.8  416.97  5069.4  423.49  5104.7  427.51  5179.5   432.1
  5185.3   433.9  5374.7  433.24  5389.2  432.51    5427  430.29  5468.1   432.8
#Mann= 8 ,-1 , 0
  3332.3     .16       0  4489.7      .1       0  4600.3     .05       0
  4824.6     .16       0  5007.7     .07       0  5015.8     .16       0
  5374.7      .1       0  5389.2     .05       0
Bank Sta=4937.8,5055.8
XS Rating Curve= 0 ,0
Exp/Cntr=0.3,0.1

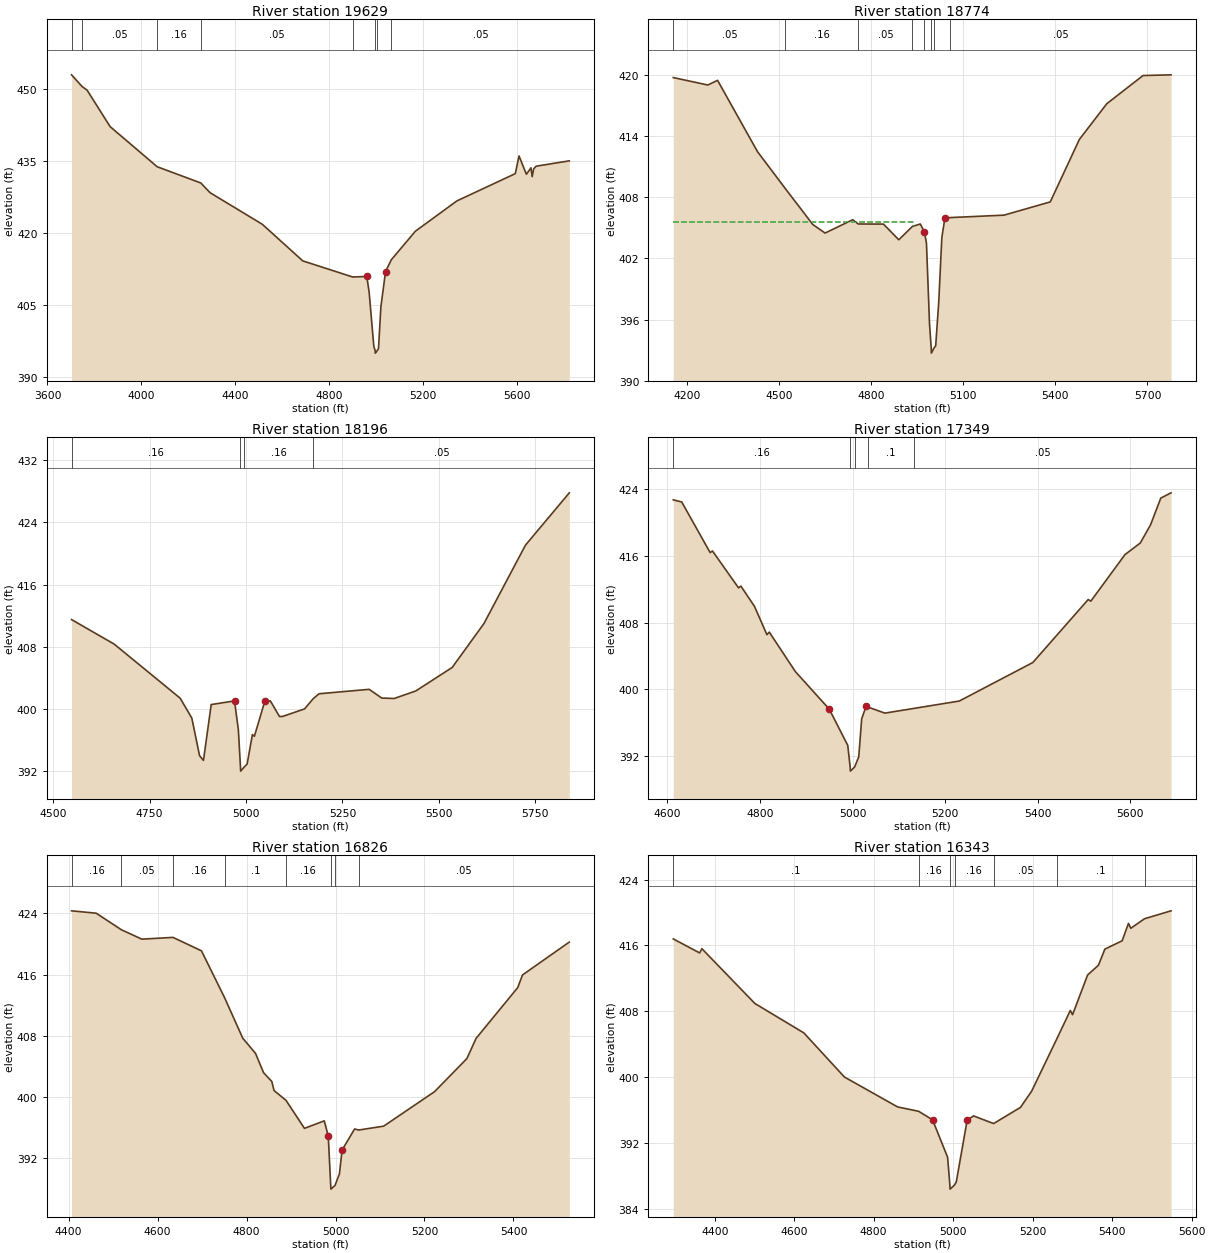
Type RM Length L Ch R = 1 ,19629   ,855,855,855
BEGIN DESCRIPTION:
UNT0277 IN DUCK CR 2 0
END DESCRIPTION:
XS GIS Cut Line= 4
      3600647.13     10440339.27      3600459.63     10441516.32
      3600464.84     10441781.95      3600652.24     10442417.01
#Sta/Elev= 30
  3702.7  453.01  3748.1  450.54  3768.7  449.83  3867.1   442.2  4067.3  433.84
  4253.3  430.45  4292.4  428.43  4515.2  421.83  4687.3   414.2  4900.1  410.84
  4959.9  410.95  4969.9  407.71  4989.9   396.4  4995.7  395.46  4996.2  394.96
  5004.1  395.46  5009.9  395.91  5019.9  404.59  5039.9  411.98  5064.7  414.45
  5166.7  420.38  5343.7  426.71  5592.4   432.4  5608.3  436.09  5639.6  432.27
  5659.1  433.61  5664.3  431.78  5670.8  433.41  5681.3  433.95  5822.4  435.07
#Mann= 8 ,-1 , 0
  3702.7     .16       0  3748.1     .05       0  4067.3     .16       0
  4253.3     .05       0  4900.1     .16       0  4995.7     .07       0
  5004.1     .16       0  5064.7     .05       0
Bank Sta=4959.9,5039.9
XS Rating Curve= 0 ,0
Exp/Cntr=0.3,0.1

Type RM Length L Ch R = 1 ,18774   ,578,578,578
BEGIN DESCRIPTION:
UNT0277 IN DUCK CR 19 0
END DESCRIPTION:
XS GIS Cut Line= 3
      3599742.28     10440817.53      3599697.14     10441827.96
      3599971.44      10442373.1
#Sta/Elev= 30
    4155  419.78  4267.6  419.05  4299.3  419.51  4429.4   412.5  4520.6  408.85
  4609.6  405.34  4649.6   404.5  4739.7  405.81  4757.7  405.39  4839.8  405.38
  4889.8  403.84    4934  405.15  4959.9  405.39    4973  404.63  4979.9  403.51
  4989.9  395.55  4995.4   393.2  4995.9   392.7  5004.5   393.2    5010  393.42
    5020  397.77    5030  404.06    5040  405.99  5056.6  406.02  5232.6  406.26
  5383.2  407.56  5478.1   413.7  5567.4  417.21  5685.5  419.98  5776.7  420.05
#Mann= 8 ,-1 , 0
    4155     .05       0  4520.6     .16       0  4757.7     .05       0
    4934     .16       0    4973      .1       0  4995.4     .07       0
  5004.5      .1       0  5056.6     .05       0
#XS Ineff= 2 , 0
         4937.43   405.6
Permanent Ineff=
       F       F
Bank Sta=4973,5040
XS Rating Curve= 0 ,0
Exp/Cntr=0.3,0.1

Type RM Length L Ch R = 1 ,18196   ,847,847,847
BEGIN DESCRIPTION:
UNT0277 IN DUCK CR 17 0
END DESCRIPTION:
XS GIS Cut Line= 3
      3599092.11     10441141.65      3599142.11     10441591.64
       3599392.1     10442391.63
#Sta/Elev= 30
  4547.5   411.5  4658.2  408.34  4829.2  401.39  4859.4  398.83  4879.5     394
  4889.6  393.39  4909.7  400.57  4970.1  401.04  4980.1  397.35  4985.6  392.51
  4986.1  392.01  4994.7  392.51  5002.9  392.93  5016.5  396.71  5021.7  396.49
    5049  401.05  5063.1  401.04  5086.7  399.04  5094.6  399.04  5151.7  400.01
  5174.7  401.35  5189.4  401.96  5319.3  402.53  5351.8  401.41  5384.2  401.35
  5440.3  402.32  5534.6  405.34  5616.8  410.97  5724.7  421.07  5838.4   427.8
#Mann= 4 ,-1 , 0
  4547.5     .16       0  4985.6     .07       0  4994.7     .16       0
  5174.7     .05       0
Bank Sta=4970.1,5049
XS Rating Curve= 0 ,0
Exp/Cntr=0.3,0.1

Type RM Length L Ch R = 1 ,17349   ,523,523,523
BEGIN DESCRIPTION:
UNT0277 IN DUCK CR 16 0
END DESCRIPTION:
XS GIS Cut Line= 4
      3598470.05     10441068.44      3598423.18     10441354.86
      3598407.55     10441636.11      3598192.11     10442091.62
#Sta/Elev= 30
  4612.6  422.72  4630.9  422.46  4692.3  416.39  4697.4  416.58  4753.6  412.16
  4758.7  412.37  4788.1  409.94    4815  406.54  4820.1  406.85  4876.4  402.12
  4949.7  397.61  4989.7  393.26  4994.9  390.67  4995.4  390.17  5004.6  390.67
  5013.5  391.89  5019.8  396.44  5029.8  398.02  5034.1  397.84  5069.9  397.13
  5132.2  397.69  5230.8  398.58  5389.7   403.2  5509.4  410.76    5515  410.56
  5588.9  416.15    5622  417.54  5644.2  419.73  5666.3  422.93  5688.4  423.56
#Mann= 5 ,-1 , 0
  4612.6     .16       0  4994.9     .07       0  5004.6     .16       0
  5034.1      .1       0  5132.2     .05       0
Bank Sta=4949.7,5029.8
XS Rating Curve= 0 ,0
Exp/Cntr=0.3,0.1

Type RM Length L Ch R = 1 ,16826   ,483,483,483
BEGIN DESCRIPTION:
UNT0277 IN DUCK CR 14 0
END DESCRIPTION:
XS GIS Cut Line= 3
      3598326.52     10440940.06      3597968.41     10441141.91
      3597777.42     10441823.37
#Sta/Elev= 30
  4406.7  424.35  4462.1  424.04  4518.7  421.87  4564.7  420.64  4634.7  420.87
  4698.7  419.11  4750.8  412.96  4791.5  407.67  4820.2  405.68  4838.3  403.15
  4856.8     402  4861.9  400.81  4888.7  399.53  4930.2  395.86  4974.7  396.84
  4983.7  394.86  4989.2   388.4  4989.7   387.9    4999   388.4  5008.8   389.9
  5014.8  393.02  5042.9  395.78  5052.3  395.64  5108.3  396.15  5222.5  400.66
  5295.2  404.99    5316  407.65  5409.5  414.29  5420.3  415.95  5525.5  420.26
#Mann= 8 ,-1 , 0
  4406.7     .16       0  4518.7     .05       0  4634.7     .16       0
  4750.8      .1       0  4888.7     .16       0  4989.2     .07       0
    4999     .16       0  5052.3     .05       0
Bank Sta=4983.7,5014.8
XS Rating Curve= 0 ,0
Exp/Cntr=0.3,0.1

Type RM Length L Ch R = 1 ,16343   ,411,411,411
BEGIN DESCRIPTION:
UNT0277 IN DUCK CR 13 0
END DESCRIPTION:
XS GIS Cut Line= 3
      3597122.07     10440712.25       3597321.7      10441055.1
      3597737.75     10441802.69
#Sta/Elev= 30
  4295.8  416.79  4362.1  415.09  4367.9   415.6  4501.1  408.95  4624.3  405.38
  4726.4  400.02  4860.2  396.39  4913.1  395.86  4948.2  394.82    4986  390.28
  4991.7  386.91  4992.2  386.41  5003.4  386.91  5007.7  387.26  5035.2  394.78
  5051.2   395.3  5101.8  394.37  5169.2  396.33  5197.5  398.31  5261.2   404.7
  5294.7   408.1  5300.4  407.59  5338.2  412.41  5365.6   413.6  5381.6  415.55
  5425.1  416.56  5441.1  418.68  5446.8  418.08  5481.5  419.24  5548.1   420.2
#Mann= 7 ,-1 , 0
  4295.8      .1       0  4913.1     .16       0  4991.7     .07       0
  5003.4     .16       0  5101.8     .05       0  5261.2      .1       0
  5481.5     .05       0
Bank Sta=4948.2,5035.2
XS Rating Curve= 0 ,0
Exp/Cntr=0.3,0.1

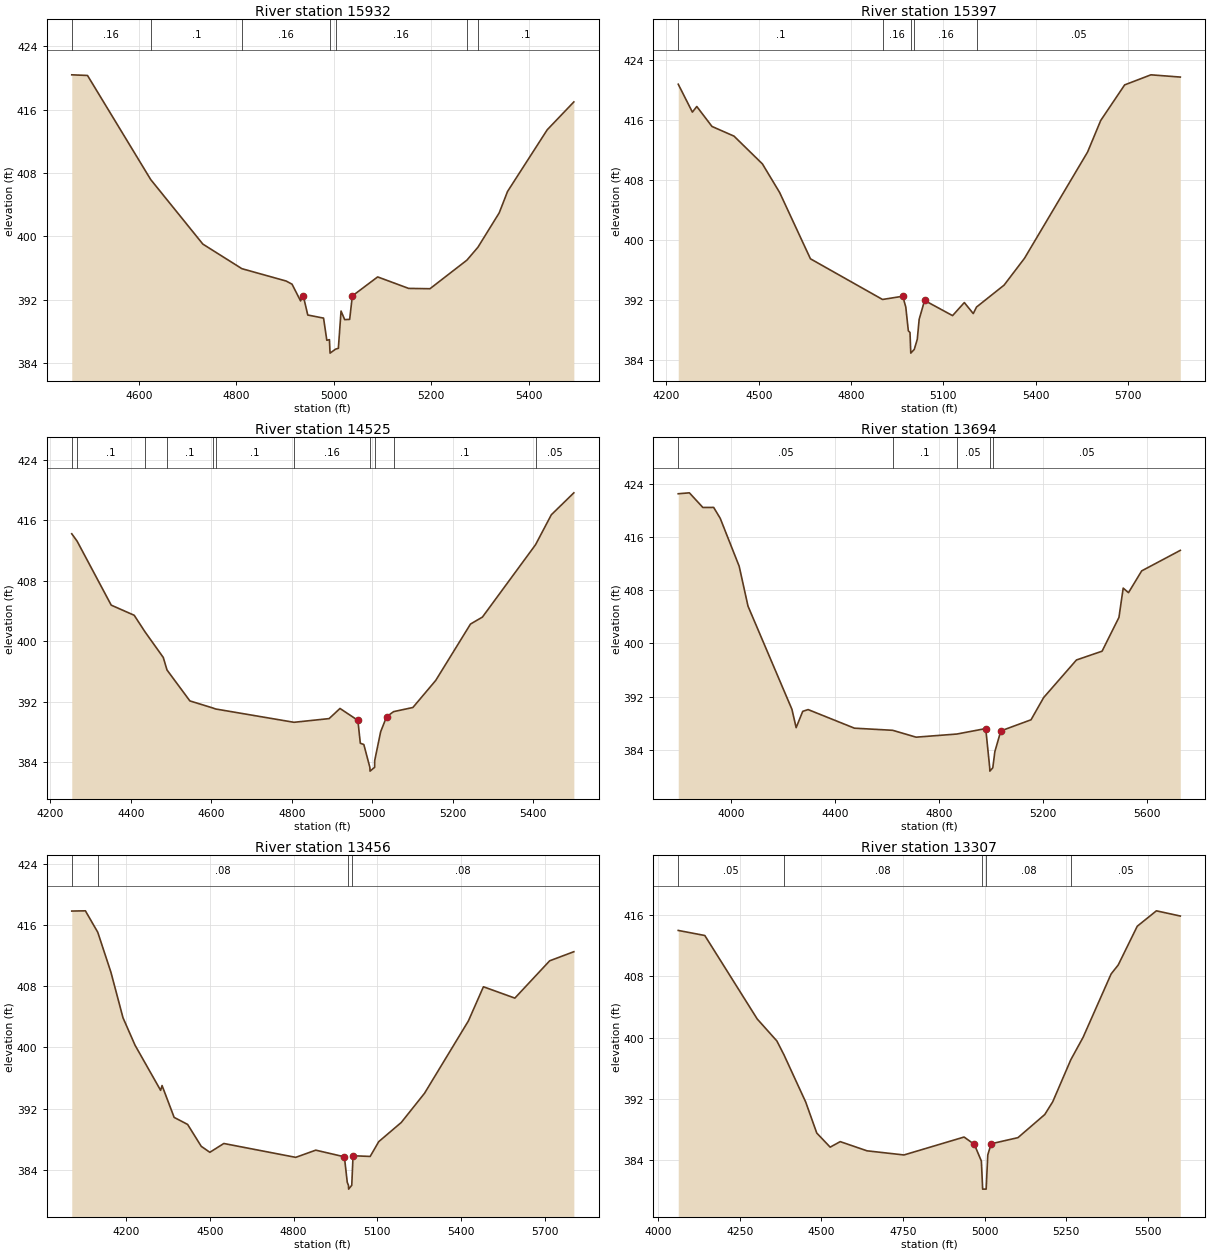
Type RM Length L Ch R = 1 ,15932   ,535,535,535
BEGIN DESCRIPTION:
UNT0277 IN DUCK CR 10 0
END DESCRIPTION:
XS GIS Cut Line= 3
      3596942.11     10441041.67      3597142.11     10441541.64
      3597592.07     10441741.63
#Sta/Elev= 30
  4461.8  420.38  4494.1   420.3    4624  407.15    4731  399.01  4811.1  395.91
    4902  394.35  4914.1  393.95  4931.6  391.84    4937  392.52  4946.4  390.06
  4978.8  389.67  4985.5  386.87  4990.9  386.95  4991.7  385.75  4992.2  385.25
  5003.4  385.75  5009.2  385.86  5014.7  390.56  5022.2  389.48  5032.4  389.51
  5037.9  392.47  5089.9  394.87  5153.5  393.42  5197.3  393.38  5273.2  396.99
  5295.7  398.61  5339.5  402.96  5356.6  405.66    5438  413.44  5492.7  416.96
#Mann= 7 ,-1 , 0
  4461.8     .16       0    4624      .1       0  4811.1     .16       0
  4991.7     .07       0  5003.4     .16       0  5273.2     .05       0
  5295.7      .1       0
Bank Sta=4937,5037.9
XS Rating Curve= 0 ,0
Exp/Cntr=0.3,0.1

Type RM Length L Ch R = 1 ,15397   ,872,872,872
BEGIN DESCRIPTION:
UNT0277 IN DUCK CR 21 1
END DESCRIPTION:
XS GIS Cut Line= 4
      3596298.28     10441360.56       3596730.6     10441876.22
      3597112.03     10442037.95      3597522.03     10442396.85
#Sta/Elev= 30
  4238.4  420.79  4284.4  417.07  4298.7  417.82  4348.1  415.16  4419.7  413.87
    4512  410.17    4568  406.36  4668.2  397.52  4902.5   392.1  4968.2  392.53
  4978.1  391.09  4986.4  387.92  4991.8   387.7  4993.9  385.45  4994.4  384.95
  5005.7  385.45  5015.5   386.8  5021.6  389.46  5039.2  391.97  5130.2  389.95
  5168.4  391.69  5197.5  390.22    5208  391.09  5297.6  394.01    5364  397.59
  5569.1  411.75  5611.8  415.96  5689.6   420.7    5775  422.04  5870.5  421.74
#Mann= 5 ,-1 , 0
  4238.4      .1       0  4902.5     .16       0  4993.9     .07       0
  5005.7     .16       0    5208     .05       0
Bank Sta=4968.2,5039.2
XS Rating Curve= 0 ,0
Exp/Cntr=0.3,0.1

Type RM Length L Ch R = 1 ,14525   ,831,831,831
BEGIN DESCRIPTION:
UNT0277 IN DUCK CR 9 0
END DESCRIPTION:
XS GIS Cut Line= 4
      3596011.87     10441886.66      3596371.22      10442428.3
      3596496.22     10442605.39      3596807.89     10442823.55
#Sta/Elev= 30
  4253.4  414.19  4266.6  413.22  4351.4  404.75  4408.5  403.41  4435.3  401.22
  4480.7  397.83    4490  396.17  4546.8  392.08  4604.1  391.14  4610.9  391.01
  4805.5  389.25  4892.7  389.74  4919.7  391.08  4964.1  389.51  4970.2  386.48
  4978.9  386.31  4993.9  383.29  4994.4  382.79  5005.7  383.29  5005.9  384.18
  5020.7     388  5035.5  389.99  5052.9  390.66  5100.8  391.21  5157.5  394.79
  5243.9  402.25  5273.5  403.17  5405.4  412.74  5444.7  416.71  5500.6  419.61
#Mann= 11 ,-1 , 0
  4253.4     .05       0  4266.6      .1       0  4435.3     .05       0
    4490      .1       0  4604.1     .16       0  4610.9      .1       0
  4805.5     .16       0  4993.9     .07       0  5005.7     .16       0
  5052.9      .1       0  5405.4     .05       0
Bank Sta=4964.1,5035.5
XS Rating Curve= 0 ,0
Exp/Cntr=0.3,0.1

Type RM Length L Ch R = 1 ,13694   ,238,238,238
BEGIN DESCRIPTION:
UNT0277 IN DUCK CR 8 0
END DESCRIPTION:
XS GIS Cut Line= 4
      3594610.81     10442542.89      3595678.52     10442844.97
      3595944.14     10443006.43      3596448.27     10443099.98
#Sta/Elev= 30
  3795.6  422.48  3838.5  422.62  3890.5  420.42    3932  420.43  3957.2   418.8
  4030.3  411.59  4064.2  405.61  4233.4  390.11  4249.6  387.36    4275  389.81
  4295.8  390.07  4474.1  387.28  4621.3  386.96  4711.5  385.93  4868.5   386.4
  4979.6  387.22    4995  381.33  4995.5  380.83  5006.8  381.33  5014.7  383.75
  5037.7  386.87    5154  388.54  5202.5  391.87  5328.9  397.52  5427.6  398.84
  5492.5  403.91  5508.9  408.31  5529.3  407.63  5580.1   410.9  5728.8  413.98
#Mann= 5 ,-1 , 0
  3795.6     .05       0  4621.3      .1       0  4868.5     .05       0
    4995     .03       0  5006.8     .05       0
Bank Sta=4979.6,5037.7
XS Rating Curve= 0 ,0
Exp/Cntr=0.3,0.1

Type RM Length L Ch R = 1 ,13456   ,149,149,149
BEGIN DESCRIPTION:
UNT0277 IN DUCK CR 6 0
END DESCRIPTION:
XS GIS Cut Line= 3
      3594669.78     10442875.84      3596015.28     10443179.67
      3596427.36     10443253.41
#Sta/Elev= 30
  4005.9   417.8  4054.7  417.83    4099  415.03  4146.2   409.8  4189.4  403.86
  4232.6  400.27  4324.1  394.38  4329.3  395.01  4372.5  390.85  4420.8  389.93
  4469.6  387.07  4500.4  386.29  4550.4  387.44  4807.9  385.63  4879.7  386.57
  4982.2   385.7  4992.5  382.36  4996.8  381.98  4997.3  381.48  5008.6  381.98
  5013.2  385.84  5074.5  385.75  5105.2  387.68    5186  390.19  5269.2     394
  5426.3  403.45  5480.1  407.91  5592.7  406.43  5717.3   411.3  5803.9  412.49
#Mann= 4 ,-1 , 0
  4005.9     .05       0    4099     .08       0  4996.8     .07       0
  5008.6     .08       0
Bank Sta=4982.2,5013.2
XS Rating Curve= 0 ,0
Exp/Cntr=0.3,0.1

Type RM Length L Ch R = 1 ,13307   ,298,298,298
BEGIN DESCRIPTION:
UNT0277 IN DUCK CR 32 0
END DESCRIPTION:
XS GIS Cut Line= 4
      3594661.07     10443125.42      3595010.51      10443097.2
      3595815.63     10443283.83        3596126.     10443466.15
#Sta/Elev= 30
  4061.8  413.98  4143.1  413.32  4303.6  402.42  4363.8  399.55  4385.4  397.75
  4452.1  391.57  4485.9  387.53  4526.9  385.69  4557.7  386.41  4639.8  385.21
  4752.8  384.67  4936.9  387.01  4968.3  386.05  4989.8  383.87  4993.2  380.71
  4993.7  380.21  5004.5  380.21    5005  380.71  5009.4  384.67  5019.7  386.13
  5101.8  386.93  5183.9  389.95  5208.3  391.62  5263.7  397.11  5301.1  400.02
    5387   408.3  5408.7  409.47    5467  414.53  5525.6  416.54  5598.8  415.86
#Mann= 5 ,-1 , 0
  4061.8     .05       0  4385.4     .08       0  4993.2     .07       0
    5005     .08       0  5263.7     .05       0
Bank Sta=4968.3,5019.7
XS Rating Curve= 0 ,0
Exp/Cntr=0.3,0.1

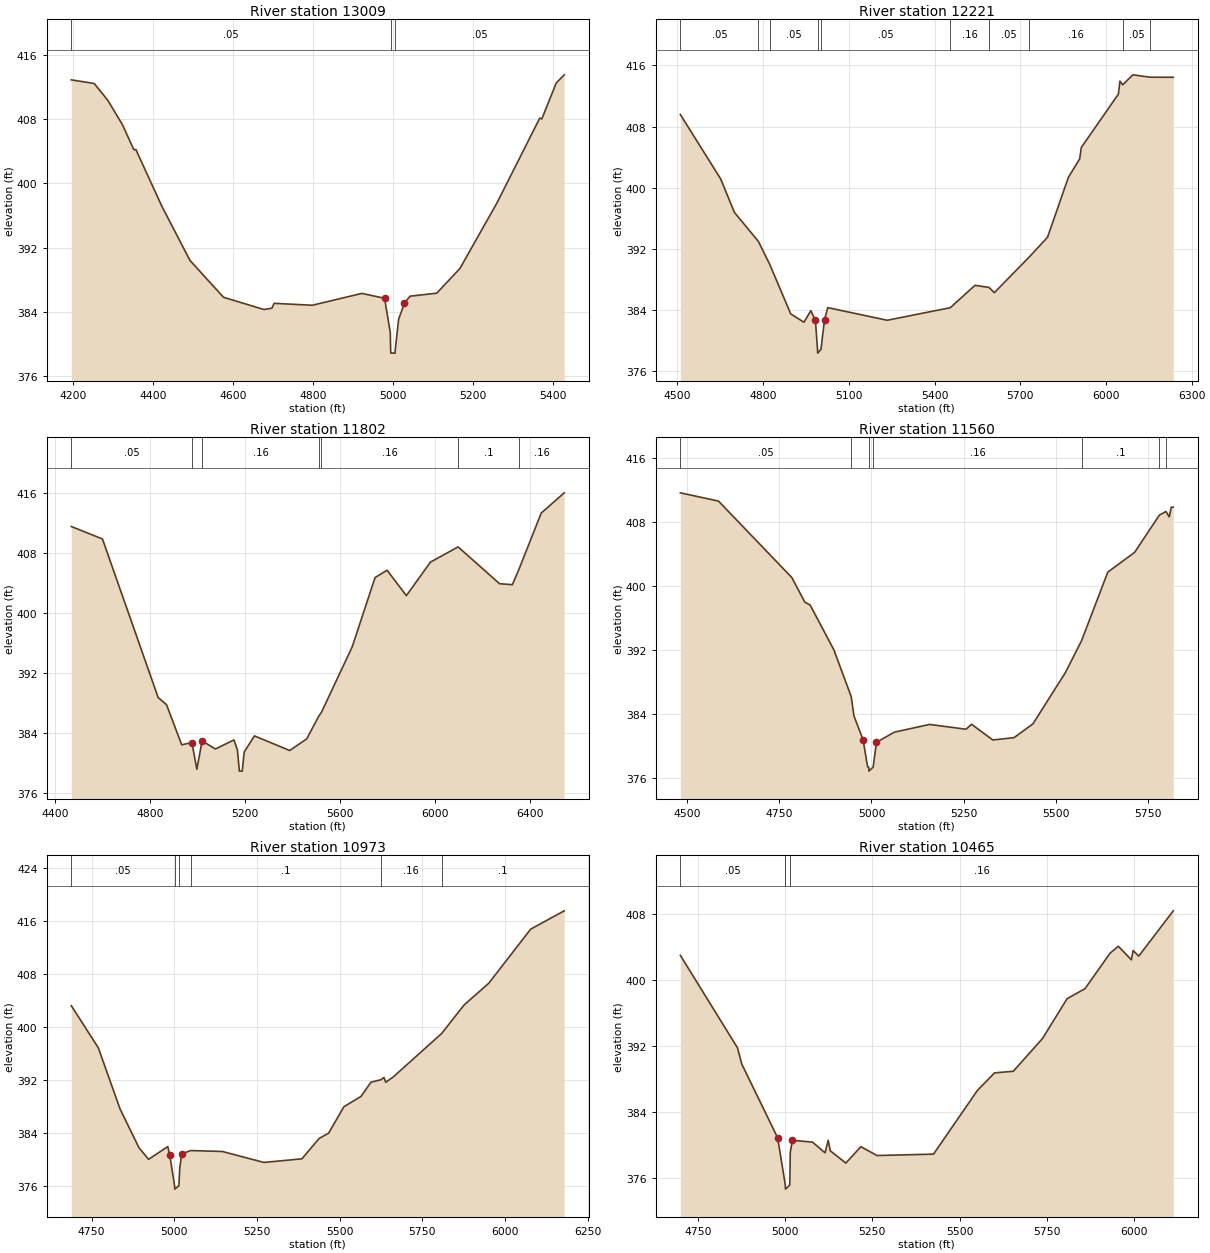
Type RM Length L Ch R = 1 ,13009   ,788,788,788
BEGIN DESCRIPTION:
UNT0277 IN DUCK CR 21 0
END DESCRIPTION:
XS GIS Cut Line= 4
      3594725.39     10443313.72      3595407.68     10443412.68
      3595574.35     10443563.72      3595892.07     10443591.64
#Sta/Elev= 30
  4195.6  412.94  4252.9  412.49    4287  410.38  4323.6  407.34  4352.1  404.22
  4357.2  404.23  4422.3  397.14  4492.5  390.39  4576.3  385.79  4677.3  384.26
  4697.5  384.42  4703.1  385.03  4798.6  384.79  4922.7  386.27  4979.5  385.66
  4993.7  381.37  4994.5  379.31    4995  378.81  5005.8  378.81  5006.3  379.31
  5014.6  383.05  5028.8  385.01    5043  385.92    5110   386.3  5167.9  389.38
  5260.4  397.55  5367.8  408.17  5372.8  408.06  5408.9  412.55  5428.9  413.57
#Mann= 3 ,-1 , 0
  4195.6     .05       0  4994.5     .03       0  5006.3     .05       0
Bank Sta=4979.5,5028.8
XS Rating Curve= 0 ,0
Exp/Cntr=0.3,0.1

Type RM Length L Ch R = 1 ,12221   ,419,419,419
BEGIN DESCRIPTION:
UNT0277 IN DUCK CR 22 0
END DESCRIPTION:
XS GIS Cut Line= 3
      3594534.21      10443814.3      3595448.27      10444186.7
      3596112.31     10443863.79
#Sta/Elev= 30
  4510.2  409.59  4651.3  401.17  4699.4  396.79  4783.3     393  4822.6  390.03
  4896.7  383.51  4942.9  382.42  4966.9  383.93    4983  382.67  4990.4  378.88
  4990.9  378.38  5002.4  378.88    5015  382.77  5026.2  384.33  5234.4  382.68
    5455  384.32  5541.7  387.25  5590.7  386.97  5609.4  386.29  5729.6  390.88
  5795.4  393.53  5868.6  401.38  5908.1  403.79  5913.7  405.28  6043.5  412.25
    6049  413.96  6058.7  413.47  6094.1  414.78  6154.5  414.47  6235.6  414.46
#Mann= 10 ,-1 , 0
  4510.2     .05       0  4783.3      .1       0  4822.6     .05       0
  4990.4     .03       0  5002.4     .05       0    5455     .16       0
  5590.7     .05       0  5729.6     .16       0  6058.7     .05       0
  6154.5     .16       0
Bank Sta=4983,5015
XS Rating Curve= 0 ,0
Exp/Cntr=0.3,0.1

Type RM Length L Ch R = 1 ,11802   ,242,242,242
BEGIN DESCRIPTION:
UNT0277 IN DUCK CR 1 0
END DESCRIPTION:
XS GIS Cut Line= 3
       3594409.2     10444030.45      3595349.31      10444814.3
      3596187.53     10444949.67
#Sta/Elev= 30
  4469.6  411.54  4600.6  409.88  4834.9  388.73  4870.1  387.78  4933.9  382.43
  4976.8  382.73  4997.6  379.17  5019.8  382.95  5075.7  381.87  5153.8  383.08
  5168.2  381.73  5176.5  378.92  5188.5  378.92  5196.8  381.47  5239.7  383.62
  5388.1  381.67  5459.7  383.22  5510.6  386.27  5521.5  386.75  5651.1   395.5
  5747.1  404.73  5797.8  405.71  5878.8  402.32  5980.1  406.79  6096.3  408.82
  6270.8  403.91  6324.5  403.78  6352.1  405.82    6446  413.33  6542.7  416.03
#Mann= 7 ,-1 , 0
  4469.6     .05       0  4976.8     .03       0  5019.8     .16       0
  5510.6      .1       0  5521.5     .16       0  6096.3      .1       0
  6352.1     .16       0
Bank Sta=4976.8,5019.8
XS Rating Curve= 0 ,0
Exp/Cntr=0.3,0.1

Type RM Length L Ch R = 1 ,11560   ,587,587,587
BEGIN DESCRIPTION:
BUCK CREEK 4 0
END DESCRIPTION:
XS GIS Cut Line= 4
      3594340.31     10444139.15      3594631.99     10444514.17
      3594754.39     10444696.46      3595296.05     10445042.82
#Sta/Elev= 30
  4481.4   411.6  4584.9  410.57    4784  401.02  4819.3  397.95  4833.7  397.59
    4898     392    4945  386.18  4952.5  383.76  4977.5  380.74  4989.6  377.39
  4992.6  377.36  4993.1  376.86  5004.6  377.36  5013.6  380.45  5061.9  381.72
  5157.6  382.69  5256.5  382.09  5271.7  382.71  5329.3  380.75    5387  381.04
  5438.4  382.77  5526.3  389.16  5570.3  393.15  5641.3   401.7  5714.1  404.16
  5781.4  408.82  5799.2  409.27    5808   408.6  5813.7  409.81    5819  409.81
#Mann= 7 ,-1 , 0
  4481.4     .05       0    4945     .16       0  4992.6     .07       0
  5004.6     .16       0  5570.3      .1       0  5781.4     .16       0
  5799.2      .1       0
Bank Sta=4977.5,5013.6
XS Rating Curve= 0 ,0
Exp/Cntr=0.3,0.1

Type RM Length L Ch R = 1 ,10973   ,508,508,508
BEGIN DESCRIPTION:
BUCK CREEK 3 1
END DESCRIPTION:
XS GIS Cut Line= 3
      3594132.58      10444657.6      3594424.25      10445092.5
      3595304.42     10445490.92
#Sta/Elev= 30
  4688.9  403.28  4770.4  396.94  4836.4  387.68  4893.5  381.84  4922.5   380.1
  4980.5  382.02  4986.5   380.7  5001.1   376.1  5001.6   375.6    5014   376.1
  5016.5  378.69  5022.5  380.91  5049.6  381.42  5145.6  381.28  5270.8  379.63
  5385.8  380.17    5438  383.25  5466.6  384.04  5512.8  388.04  5564.5  389.59
  5594.4  391.73  5624.8  392.11  5633.8  392.45  5639.3  391.73  5662.4  392.55
  5808.5   399.1  5875.8  403.38  5950.6  406.67  6077.4  414.84  6178.7   417.6
#Mann= 6 ,-1 , 0
  4688.9     .05       0  5001.1     .03       0    5014     .05       0
  5049.6      .1       0  5624.8     .16       0  5808.5      .1       0
Bank Sta=4986.5,5022.5
XS Rating Curve= 0 ,0
Exp/Cntr=0.3,0.1

Type RM Length L Ch R = 1 ,10465   ,475,475,475
BEGIN DESCRIPTION:
BUCK CREEK 19 0
END DESCRIPTION:
XS GIS Cut Line= 3
      3593674.22     10444764.33      3593960.71     10445204.48
      3594163.54     10446067.81
#Sta/Elev= 30
  4700.3  402.96  4864.1  391.78  4876.3  389.82    4979  380.92  5000.2  375.42
  5000.9  375.21  5001.4  374.71  5013.8  375.21  5015.2  379.14  5021.2  380.61
  5078.9  380.39  5114.8   379.1  5123.9  380.61  5129.9  379.34  5174.4  377.86
  5217.5  379.84  5263.6  378.77  5425.6  378.94  5551.3  386.64  5600.4  388.76
    5654  388.95  5737.8  392.91  5808.1  397.72  5859.4  398.93  5931.3  403.22
    5955  404.06  5992.3  402.42  5997.4  403.54  6013.5  402.87  6112.3  408.34
#Mann= 4 ,-1 , 0
  4700.3     .05       0  5000.2     .16       0  5000.9     .03       0
  5013.8     .16       0
Bank Sta=4979,5021.2
XS Rating Curve= 0 ,0
Exp/Cntr=0.3,0.1