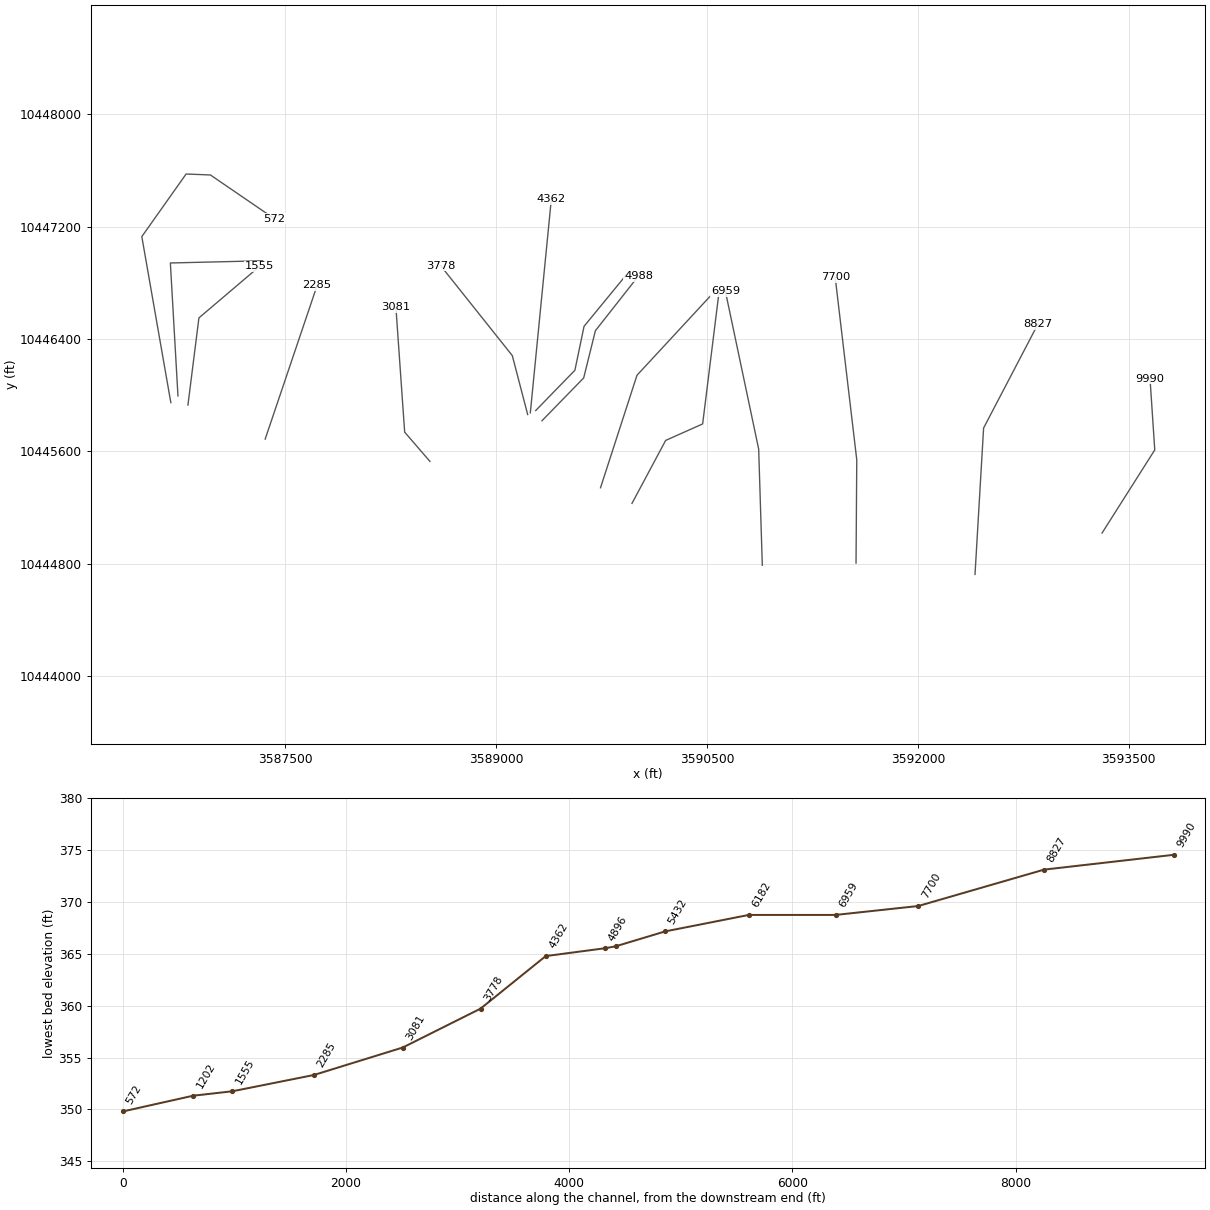
HEC-RAS study BUCK CREEK.prj: BUCK CREEK Base Level Engineering

--- BUCK CREEK.g01 (geometry) --- (continued)

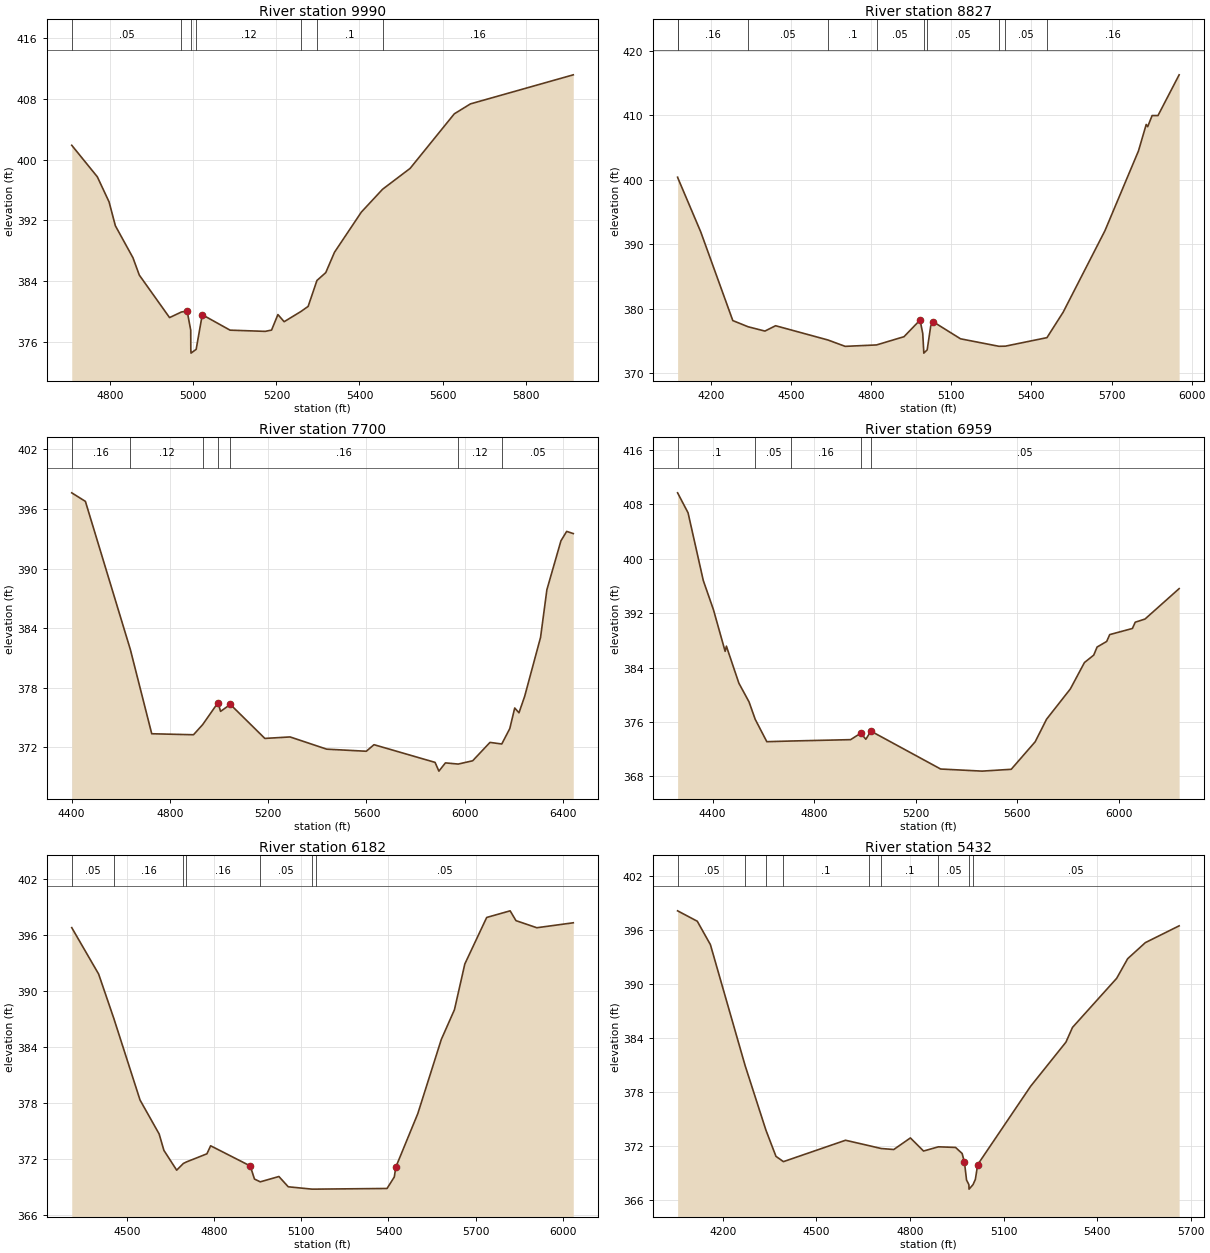
Type RM Length L Ch R = 1 ,9990    ,1163,1163,1163
BEGIN DESCRIPTION:
BUCK CREEK 18 0
END DESCRIPTION:
XS GIS Cut Line= 3
      3593309.68      10445019.6      3593684.67     10445610.73
      3593650.88     10446117.57
#Sta/Elev= 30
  4706.9  401.88  4768.5  397.74  4796.8  394.44    4812   391.3  4854.4  387.09
  4869.6  384.82  4942.5  379.23  4971.2  379.97  4984.9  380.08  4993.5  377.57
  4993.7  375.06  4994.2  374.56  5006.6  375.06  5021.3  379.61  5088.2  377.58
  5172.9  377.42  5188.2  377.59  5203.5  379.63  5218.5  378.69  5258.3  380.01
  5276.3   380.7  5297.5  384.11  5318.7  385.14  5339.8  387.82  5404.5   393.1
  5455.6   396.1  5521.9  398.84  5628.3  406.01  5667.2  407.32  5914.9  411.14
#Mann= 7 ,-1 , 0
  4706.9     .05       0  4971.2     .12       0  4993.7     .07       0
  5006.6     .12       0  5258.3     .16       0  5297.5      .1       0
  5455.6     .16       0
Bank Sta=4984.9,5021.3
XS Rating Curve= 0 ,0
Exp/Cntr=0.3,0.1

Type RM Length L Ch R = 1 ,8827    ,1127,1127,1127
BEGIN DESCRIPTION:
BUCK CREEK 17 0
END DESCRIPTION:
XS GIS Cut Line= 3
      3592406.02     10444725.32      3592467.11     10445766.64
      3592853.92     10446506.52
#Sta/Elev= 30
  4075.2  400.42  4076.1   400.3  4161.7  391.95  4281.9  378.18  4339.1  377.22
  4402.1  376.55  4442.1  377.38  4638.8  375.16  4702.6  374.18  4820.1   374.4
    4923  375.68  4983.1  378.26  4993.1  376.19  4996.6  373.63  4997.1  373.13
  5009.7  373.63  5023.1  377.35  5033.2  377.97  5134.7  375.35  5278.5  374.19
  5302.4  374.21  5458.2  375.53  5518.9  379.48  5675.4  392.12    5801   404.5
  5829.9   408.6  5835.5  408.26    5852  409.98    5874  409.98  5953.2   416.3
#Mann= 10 ,-1 , 0
  4075.2     .05       0  4076.1     .16       0  4339.1     .05       0
  4638.8      .1       0  4820.1     .05       0  4996.6     .03       0
  5009.7     .05       0  5278.5      .1       0  5302.4     .05       0
  5458.2     .16       0
Bank Sta=4983.1,5033.2
XS Rating Curve= 0 ,0
Exp/Cntr=0.3,0.1

Type RM Length L Ch R = 1 ,7700    ,741,741,741
BEGIN DESCRIPTION:
BUCK CREEK 16 0
END DESCRIPTION:
XS GIS Cut Line= 3
      3591559.67     10444806.06      3591564.88     10445540.42
      3591411.42      10446838.3
#Sta/Elev= 30
  4400.4  397.62    4456  396.76    4639  381.85    4726  373.38    4896  373.28
  4933.6  374.31    4996  376.52    5006  375.63    5046  376.33  5186.4  372.91
  5289.1  373.06  5438.1  371.83  5599.2  371.62  5630.6  372.28  5879.2   370.5
  5894.8  369.62  5921.4  370.45  5973.1  370.33  6032.2  370.66  6102.7  372.51
  6150.7  372.35  6183.3   373.9  6203.4  375.97  6220.7  375.49  6243.7  377.13
  6308.6  383.08  6334.3  387.87  6391.5  392.79  6414.9  393.74  6441.7  393.52
#Mann= 7 ,-1 , 0
  4400.4     .16       0    4639     .12       0  4933.6     .16       0
    4996     .07       0    5046     .16       0  5973.1     .12       0
  6150.7     .05       0
Bank Sta=4996,5046
XS Rating Curve= 0 ,0
Exp/Cntr=0.3,0.1

Type RM Length L Ch R = 1 ,6959    ,777,777,777
BEGIN DESCRIPTION:
BUCK CREEK 14 0
END DESCRIPTION:
XS GIS Cut Line= 3
        3590893.     10444790.46      3590867.11     10445616.64
      3590629.98     10446740.92
#Sta/Elev= 30
    4262  409.69  4303.2  406.75  4363.2  396.79  4403.3  392.49  4449.2  386.38
  4454.2  387.14  4503.3   381.7  4543.3  378.95  4567.7  376.38  4613.4  373.09
  4710.3  373.19  4943.5  373.39  4983.5  374.34  5003.5  373.45  5023.6  374.64
  5298.1  369.07  5461.6  368.76  5576.2  369.03  5670.6  373.08  5715.3  376.39
  5809.1  380.85  5864.6  384.73  5901.1  385.82  5914.4  387.01  5952.2  387.83
  5964.2  388.84  6053.5  389.74  6064.6  390.66  6103.3  391.13  6237.6   395.6
#Mann= 5 ,-1 , 0
    4262      .1       0  4567.7     .05       0  4710.3     .16       0
  4983.5     .07       0  5023.6     .05       0
Bank Sta=4983.5,5023.6
XS Rating Curve= 0 ,0
Exp/Cntr=0.3,0.1

Type RM Length L Ch R = 1 ,6182    ,750,750,750
BEGIN DESCRIPTION:
BUCK CREEK 13 0
END DESCRIPTION:
XS GIS Cut Line= 4
       3589965.9      10445230.5       3590205.5     10445678.44
      3590468.52     10445795.62      3590583.05     10446717.09
#Sta/Elev= 30
    4311  396.75  4403.5  391.78  4455.7  387.03  4545.8   378.3  4611.6  374.66
  4627.9  372.91  4671.8  370.79  4694.9  371.51  4705.4  371.67  4775.8  372.54
  4788.6   373.4  4924.8  371.24  4939.3  369.84  4959.2  369.54  5023.3  370.11
  5055.5  369.01  5136.6  368.76  5149.8  368.76  5395.2  368.83  5420.1  370.06
  5425.4  371.12  5500.9  376.84  5581.7  384.78  5626.9  387.96  5662.6  392.86
  5737.8  397.84  5818.4  398.55  5838.5   397.5  5910.2  396.74  6035.5  397.27
#Mann= 7 ,-1 , 0
    4311     .05       0  4455.7     .16       0  4694.9      .1       0
  4705.4     .16       0  4959.2     .05       0  5136.6    .033       0
  5149.8     .05       0
Bank Sta=4924.8,5425.4
XS Rating Curve= 0 ,0
Exp/Cntr=0.3,0.1

Type RM Length L Ch R = 1 ,5432    ,444,444,444
BEGIN DESCRIPTION:
BUCK CREEK 11 0
END DESCRIPTION:
XS GIS Cut Line= 3
      3589742.11     10445341.66      3590001.43     10446141.84
       3590522.3     10446704.38
#Sta/Elev= 30
    4055  398.15  4118.1  396.99  4160.1  394.39  4271.3  380.94  4338.1  373.74
  4370.3  370.82  4394.3  370.23  4593.3  372.61  4667.2  372.02  4707.8  371.69
  4747.9  371.58  4801.3  372.87  4843.4  371.41  4891.1  371.88  4946.1  371.81
  4967.1  371.14  4974.5  370.18  4981.3  368.18  4988.8  367.67  4989.3  367.17
  5002.1  367.67  5009.6  368.26    5017   369.9  5186.5  378.61  5299.9  383.53
  5320.9  385.17  5462.6  390.64  5497.8  392.82  5554.5  394.61  5662.8  396.48
#Mann= 9 ,-1 , 0
    4055     .05       0  4271.3      .1       0  4338.1     .05       0
  4394.3      .1       0  4667.2     .16       0  4707.8      .1       0
  4891.1     .05       0  4988.8     .03       0  5002.1     .05       0
Bank Sta=4974.5,5017
XS Rating Curve= 0 ,0
Exp/Cntr=0.3,0.1

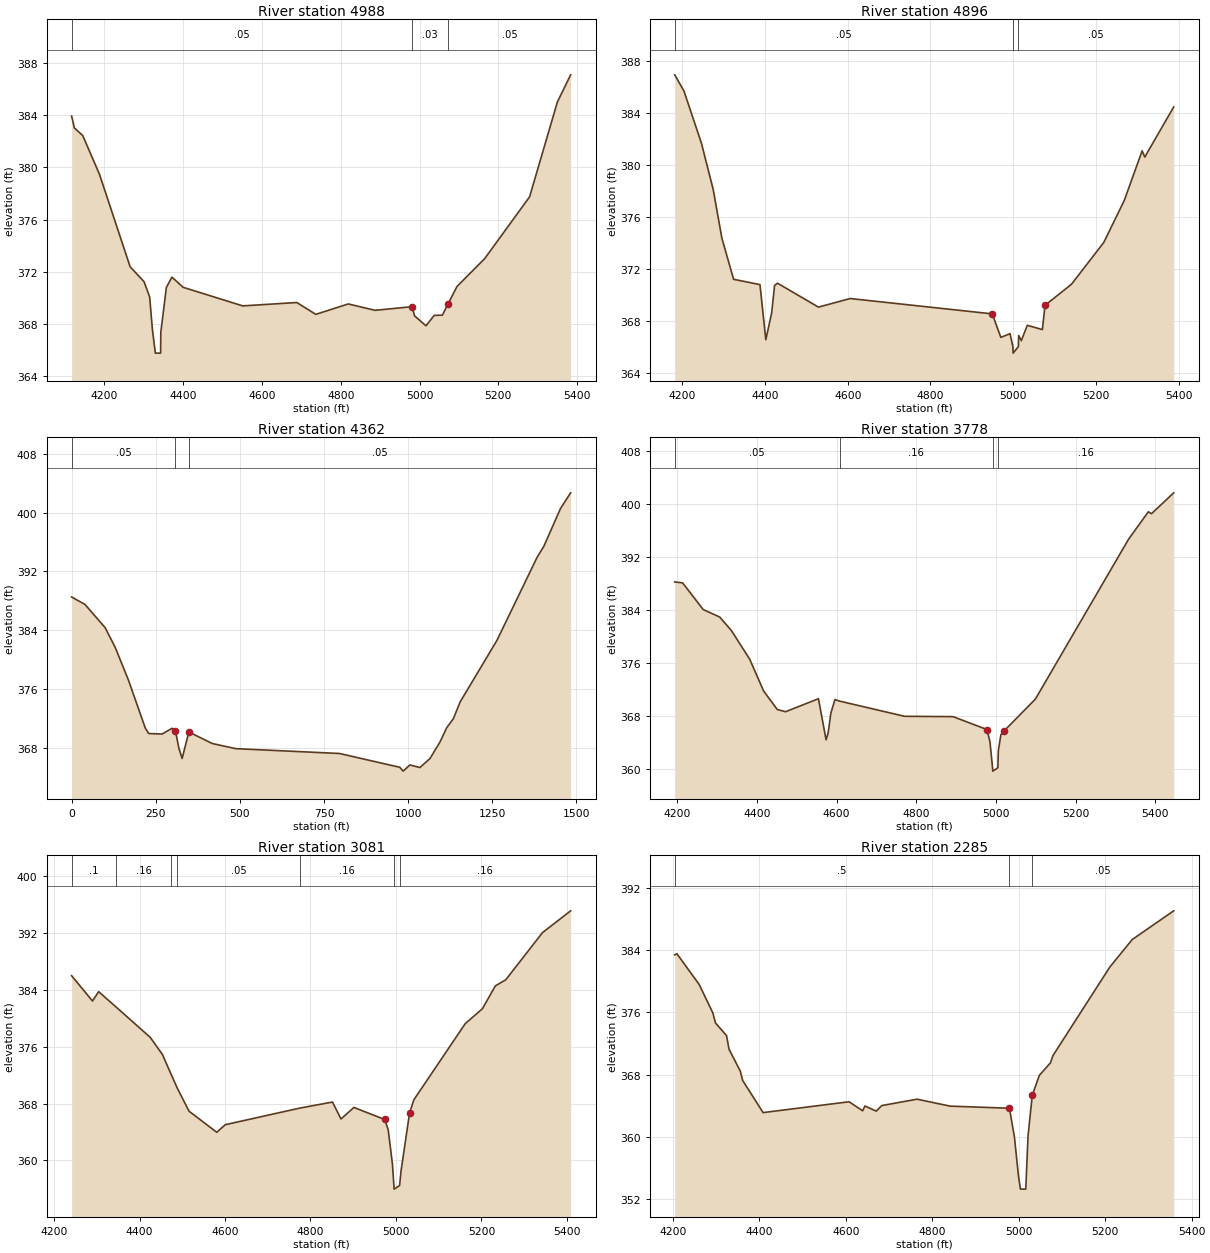
Type RM Length L Ch R = 1 ,4988    ,92,92,92
BEGIN DESCRIPTION:
Mapping XS 2918efaf
END DESCRIPTION:
XS GIS Cut Line= 4
       3589325.5     10445818.23      3589622.34     10446122.88
      3589705.67     10446458.82      3590011.86     10446848.04
#Sta/Elev= 30
  4116.8  383.95  4123.8  383.04  4145.1  382.45  4187.6  379.47  4265.3  372.37
  4300.7  371.22  4314.9  370.05  4321.9  367.55  4329.4  365.73  4342.7  365.73
  4343.2  367.33  4357.3  370.78  4371.5  371.57  4399.8  370.79  4551.2  369.36
  4688.4  369.62  4736.6  368.71  4819.1  369.51  4887.2  369.02  4980.9   369.3
  4987.5  368.59  5016.4  367.83  5037.2  368.63    5058  368.65  5072.4  369.51
    5095  370.85  5165.5     373  5279.3  377.74  5349.9  385.03  5383.5  387.12
#Mann= 3 , 0 , 0
  4116.8     .05       0  4980.9     .03       0  5072.4     .05       0
Bank Sta=4980.9,5072.4
XS Rating Curve= 0 ,0
Exp/Cntr=0.3,0.1

Type RM Length L Ch R = 1 ,4896    ,534,534,534
BEGIN DESCRIPTION:
BUCK CREEK 10 0
END DESCRIPTION:
XS GIS Cut Line= 4
      3589281.17     10445891.08      3589559.84     10446177.57
      3589624.95     10446490.07      3589934.42     10446867.16
#Sta/Elev= 30
  4181.6  386.96  4203.9  385.72  4246.3  381.69  4274.6  378.15  4295.7  374.39
    4324  371.23  4387.8  370.82  4401.9  366.58  4416.1  368.65  4423.1  370.76
  4430.2  370.93  4529.2  369.09  4605.9  369.75  4949.5  368.57  4970.3  366.76
  4992.5  367.05  4999.4  366.05  4999.9  365.55  5012.7  366.05  5013.3  366.91
  5019.8  366.51  5034.2  367.69  5070.7  367.36  5077.2  369.23  5141.1  370.85
  5219.3  374.07  5268.8   377.3  5311.9  381.11  5318.3  380.63  5388.3  384.49
#Mann= 3 ,-1 , 0
  4181.6     .05       0  4999.4     .03       0  5012.7     .05       0
Bank Sta=4949.5,5077.2
XS Rating Curve= 0 ,0
Exp/Cntr=0.3,0.1

Type RM Length L Ch R = 1 ,4362    ,584,584,584
XS GIS Cut Line= 2
     3589242.754    10445875.165     3589392.076    10447393.058
#Sta/Elev= 30
       0   388.5   39.81  387.48   99.53  384.33  129.38  381.65  169.19  377.15
  218.96  370.65  228.91  369.91  268.72  369.84  298.58  370.62  308.53  370.32
  318.48  367.96  328.43  366.51  348.34  370.12  418.01  368.55  487.67  367.85
   796.2  367.19  975.35  365.31   985.3  364.79 1005.21  365.63 1035.06  365.28
 1064.92   366.5 1094.78  368.76 1114.68   370.7 1134.59  371.94 1154.49   374.2
 1263.97  382.59  1383.4  393.91 1403.31   395.4 1453.07  400.56 1482.93  402.68
#Mann= 3 , 0 , 0
       0     .05       0  308.53     .03       0  348.34     .05       0
Bank Sta=308.53,348.34
XS Rating Curve= 0 ,0
Exp/Cntr=0.3,0.1

Type RM Length L Ch R = 1 ,3778    ,697,697,697
BEGIN DESCRIPTION:
BUCK CREEK 9 0
END DESCRIPTION:
XS GIS Cut Line= 3
       3589223.9     10445862.48      3589114.53     10446281.74
      3588604.11     10446922.37
#Sta/Elev= 30
  4193.6  388.22  4213.4  388.09  4265.2  384.06  4306.4  382.94  4335.8  380.91
  4381.5  376.62  4416.8  371.79  4451.1     369  4471.8  368.67  4554.4  370.63
  4573.5  364.44  4578.7  365.46  4585.5  368.45  4595.8   370.5  4607.4  370.27
  4770.5  367.98  4892.2  367.93  4977.1  365.99  4984.8  364.15  4991.3  360.22
  4991.8  359.72  5004.6  360.22  5005.9  362.84  5012.3  365.21  5020.3  365.78
  5098.8  370.57  5332.6  394.65  5382.3  398.79  5390.3  398.51    5446  401.65
#Mann= 4 ,-1 , 0
  4193.6     .05       0  4607.4     .16       0  4991.3     .07       0
  5004.6     .16       0
Bank Sta=4977.1,5020.3
XS Rating Curve= 0 ,0
Exp/Cntr=0.3,0.1

Type RM Length L Ch R = 1 ,3081    ,796,796,796
BEGIN DESCRIPTION:
BUCK CREEK 7 0
END DESCRIPTION:
XS GIS Cut Line= 3
      3588528.62      10445529.1       3588348.9     10445737.46
      3588286.45     10446627.41
#Sta/Elev= 30
  4241.2  385.97  4290.1  382.41  4304.4  383.73  4345.2  381.57    4425  377.31
  4453.6   374.9  4473.3   372.2  4487.9  370.23  4515.8  366.93  4580.7  363.96
  4600.8  365.03    4775  367.36  4851.4  368.21  4871.4  365.83  4901.5  367.45
  4973.6  365.76  4981.7  364.34  4991.7  359.47  4995.1  356.47  4995.6  355.97
  5008.4  356.47  5011.8  358.53  5031.8  366.69  5041.8  368.53  5162.1  379.24
  5202.2  381.33  5232.3  384.53  5256.8   385.4  5342.6  392.02  5408.5  395.09
#Mann= 7 ,-1 , 0
  4241.2      .1       0  4345.2     .16       0  4473.3      .1       0
  4487.9     .05       0    4775     .16       0  4995.1     .07       0
  5008.4     .16       0
Bank Sta=4973.6,5031.8
XS Rating Curve= 0 ,0
Exp/Cntr=0.3,0.1

Type RM Length L Ch R = 1 ,2285    ,730,730,730
BEGIN DESCRIPTION:
BUCK CREEK 6 0
END DESCRIPTION:
XS GIS Cut Line= 2
       3587356.7     10445687.94       3587726.5     10446781.72
#Sta/Elev= 30
  4203.9  383.38  4209.1  383.52  4260.6  379.57  4292.3  375.91  4298.2  374.65
  4323.9  373.01  4329.6  371.27  4355.6  368.47  4361.1  367.27  4408.4  363.14
  4607.4  364.53  4638.8  363.37  4644.1  363.99  4670.2  363.33  4682.8  364.04
  4764.6  364.86  4841.2  363.97  4978.4   363.7    4990  359.98  4999.5   354.9
  5003.9  353.32  5016.2  353.32  5021.4  360.14  5031.2  365.36  5047.6  367.92
  5073.4  369.53    5079  370.45  5210.6  381.81  5262.4  385.34  5358.5  389.03
#Mann= 3 , 0 , 0
  4203.9      .5       0  4978.4     .03       0  5031.2     .05       0
Bank Sta=4978.4,5031.2
XS Rating Curve= 0 ,0
Exp/Cntr=0.3,0.1

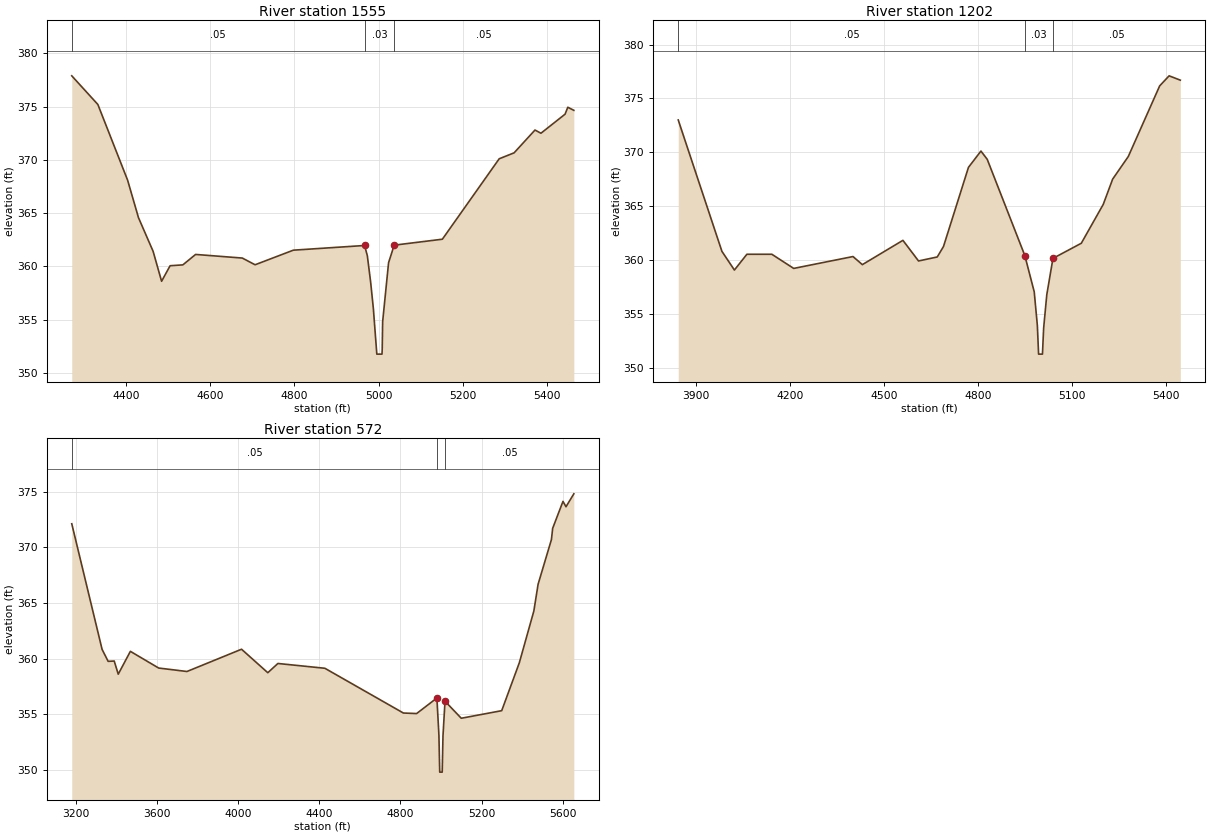
Type RM Length L Ch R = 1 ,1555    ,353,353,353
BEGIN DESCRIPTION:
BUCK CREEK 3 0
END DESCRIPTION:
XS GIS Cut Line= 3
      3586807.24     10445930.19      3586885.36     10446549.96
      3587317.09     10446916.63
#Sta/Elev= 30
  4271.7  377.88  4333.6  375.19  4404.2  368.08    4430  364.56  4464.7   361.4
  4484.8  358.59    4505  360.05  4535.2  360.13  4565.5  361.11  4676.3  360.77
  4706.6  360.14  4797.3  361.51  4966.4  361.95  4972.9  360.99  4980.7  358.53
  4987.2  356.03  4995.4  351.75  5007.7  351.75  5008.2  352.25  5009.2  354.79
  5023.3  360.34  5036.6  361.98  5150.9  362.54  5285.7  370.09  5321.1  370.65
  5370.6  372.79  5384.8  372.49    5442  374.28  5448.5  374.93  5462.8  374.64
#Mann= 3 , 0 , 0
  4271.7     .05       0  4966.4     .03       0  5036.6     .05       0
Bank Sta=4966.4,5036.6
XS Rating Curve= 0 ,0
Exp/Cntr=0.3,0.1

Type RM Length L Ch R = 1 ,1202    ,630,630,630
BEGIN DESCRIPTION:
BUCK CREEK 2 0
END DESCRIPTION:
XS GIS Cut Line= 3
     3586736.269    10445995.156      3586682.23     10446940.59
      3587337.84      10446956.2
#Sta/Elev= 30
 3844.51  373.01 3983.86  360.84 4023.67  359.11 4063.49  360.57 4143.12  360.57
 4212.79  359.26 4401.91  360.36 4431.77  359.61 4561.17  361.86 4610.94  359.95
 4670.66  360.32 4690.56  361.29 4770.19  368.62    4810  370.13    4830  369.37
    4950  360.45    4980  357.09    4990  353.95  4993.9  351.32  5006.2  351.32
    5010  353.73    5020  356.82  5039.7  360.19  5130.1  361.59  5200.1  365.19
  5230.1  367.53  5280.1  369.63  5380.1  376.17  5410.2   377.1  5445.9   376.7
#Mann= 3 , 0 , 0
 3844.51     .05       0    4950     .03       0  5039.7     .05       0
Bank Sta=4950,5039.7
XS Rating Curve= 0 ,0
Exp/Cntr=0.3,0.1

Type RM Length L Ch R = 1 ,572     ,0,0,0
BEGIN DESCRIPTION:
BUCK CREEK 1 0
END DESCRIPTION:
XS GIS Cut Line= 5
     3586685.607    10445947.159      3586479.14     10447128.13
      3586794.22      10447573.4      3586967.11     10447566.64
      3587421.11     10447256.18
#Sta/Elev= 30
    3180  372.11 3329.44  360.83 3359.33  359.75 3389.22  359.78 3409.15   358.6
 3468.92  360.65  3608.4  359.15 3747.88  358.84 4016.88  360.84  4146.4  358.73
 4196.21  359.56  4427.7  359.13  4814.7  355.11    4880  355.06    4980  356.46
    4990   353.1  4993.9   349.8  5006.2   349.8    5010  353.06    5020  356.17
  5100.1  354.64  5299.5  355.32  5386.1  359.61  5457.9  364.27  5478.9  366.68
  5544.6  370.69  5550.7   371.7  5601.5  374.12  5616.4  373.64  5655.1   374.8
#Mann= 3 , 0 , 0
    3180     .05       0    4980     .03       0    5020     .05       0
Bank Sta=4980,5020
XS Rating Curve= 0 ,0
Exp/Cntr=0.3,0.1

Chan Stop Cuts=-1
Use User Specified Reach Order=0
Composite Channel Slope=5