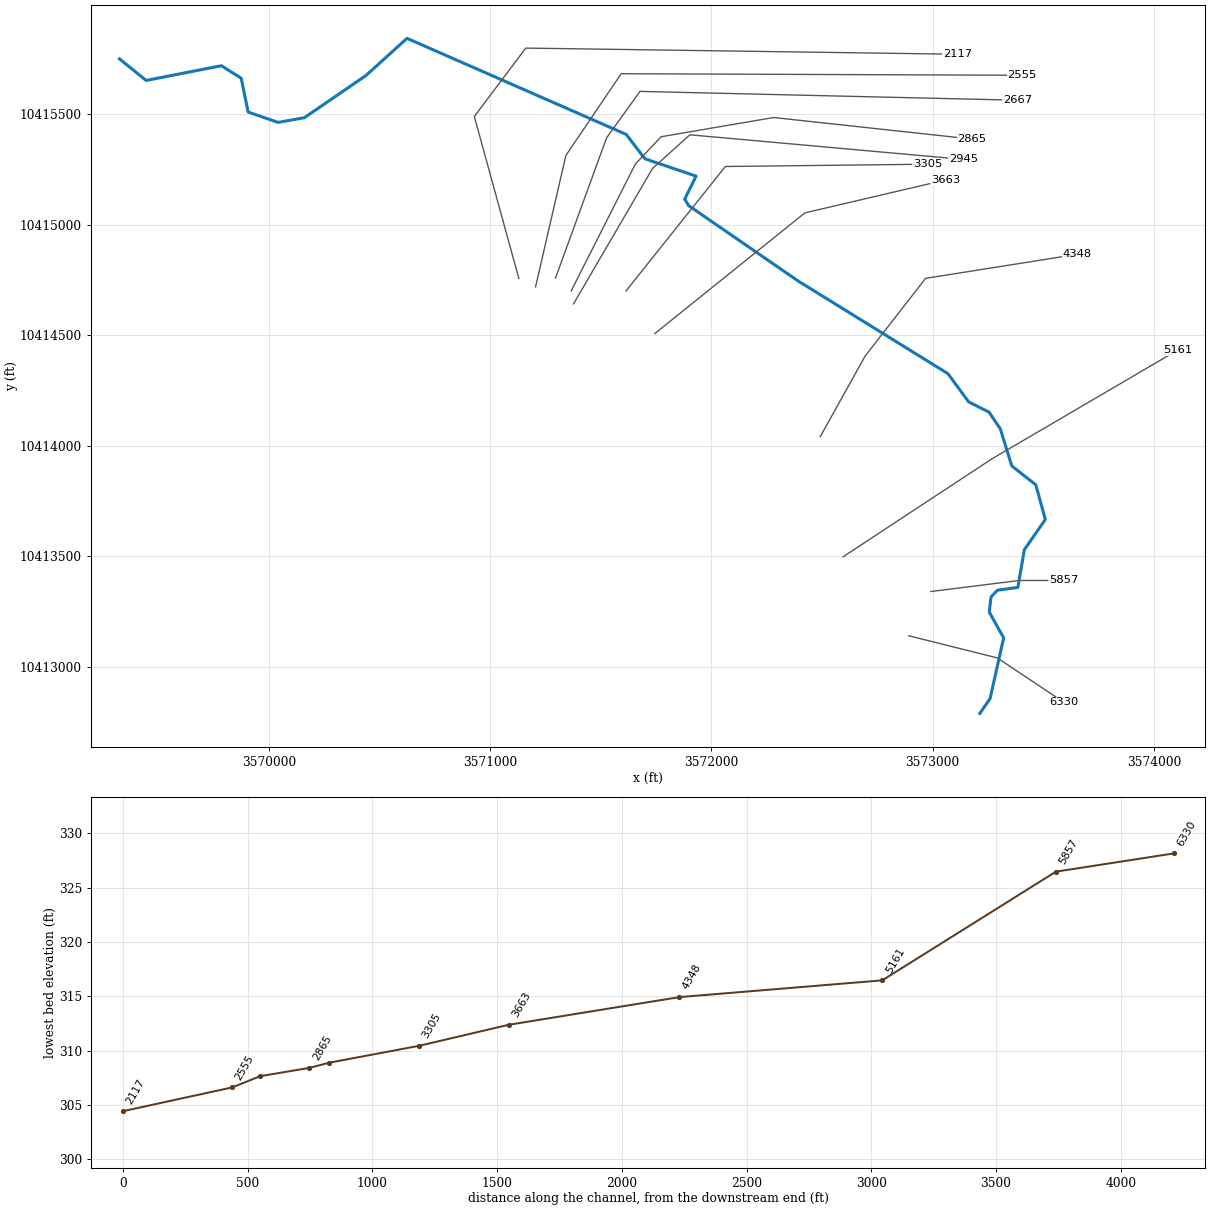
--- COPPERAS BRANCH.prj (project) ---

Proj Title=COPPERAS BRANCH Base Level Engineering
Current Plan=p01
Default Exp/Contr=0.3,0.1
English Units
Geom File=g01
Flow File=f01
Plan File=p01
BEGIN DESCRIPTION:
COPPERAS BRANCH
END DESCRIPTION:

--- COPPERAS BRANCH.p01 (plan) ---

Plan Title=Multiple Run
Short Identifier=Multiple
Geom File=g01
Flow File=f01
Subcritical Flow
K Sum by GR= 0
Std Step Tol= 0.01
Critical Tol= 0.01
Num of Std Step Trials= 20
Max Error Tol= 0.3
Flow Tol Ratio= 0.001
Split Flow NTrial= 30
Split Flow Tol= 0.02
Split Flow Ratio= 0.02
Log Output Level= 0
Friction Slope Method= 1
Unsteady Friction Slope Method= 2
Unsteady Bridges Friction Slope Method= 1
Parabolic Critical Depth
Global Vel Dist=  1 , 1 , 1
Global Log Level= 0
CheckData=True
Encroach Param= -1, 0, 0, 0
BEGIN DESCRIPTION:
Multiple Run
END DESCRIPTION:

--- COPPERAS BRANCH.f01 (steady flow) ---

Flow Title=Multiple
Number of Profiles=7
Profile Names=10-year,25-year,50-year,1pct_min,100-year,1pct_plu,500-year
River Rch & RM= COPPERAS BRANCH,Reach-1,6330
    1173    1634    2020    1823    2465    3333    3659
Boundary for River Rch & Prof#=COPPERAS BRANCH,Reach-1,1
Up Type=0
Dn Type=3
Dn Slope=0.005
Boundary for River Rch & Prof#=COPPERAS BRANCH,Reach-1,2
Up Type=0
Dn Type=3
Dn Slope=0.005
Boundary for River Rch & Prof#=COPPERAS BRANCH,Reach-1,3
Up Type=0
Dn Type=3
Dn Slope=0.005
Boundary for River Rch & Prof#=COPPERAS BRANCH,Reach-1,4
Up Type=0
Dn Type=3
Dn Slope=0.005
Boundary for River Rch & Prof#=COPPERAS BRANCH,Reach-1,5
Up Type=0
Dn Type=3
Dn Slope=0.005
Boundary for River Rch & Prof#=COPPERAS BRANCH,Reach-1,6
Up Type=0
Dn Type=3
Dn Slope=0.005
Boundary for River Rch & Prof#=COPPERAS BRANCH,Reach-1,7
Up Type=0
Dn Type=3
Dn Slope=0.005

--- COPPERAS BRANCH.g01 (geometry) ---

Geom Title=Existing Conditions

River Reach=COPPERAS BRANCH,Reach-1
Reach XY= 30
      3573213.34     10412790.90      3573259.68     10412857.93
      3573320.93     10413132.09      3573255.89     10413248.72
      3573263.89     10413316.95      3573293.11     10413347.60
      3573385.04     10413360.17      3573414.55     10413530.70
      3573509.29     10413667.30      3573466.04     10413823.96
      3573357.66     10413909.15      3573305.86     10414076.42
      3573255.34     10414151.94      3573162.64     10414198.81
      3573068.89     10414326.42      3572393.22     10414744.33
      3571897.98     10415085.10      3571879.53     10415114.85
      3571930.79     10415218.94      3571699.44     10415297.45
      3571615.39     10415407.38      3570624.38     10415841.70
      3570438.16     10415673.18      3570160.56     10415483.07
      3570041.81     10415461.72      3569906.39     10415508.59
      3569875.14     10415661.20      3569785.56     10415717.97
      3569445.45     10415651.30      3569324.96     10415749.09

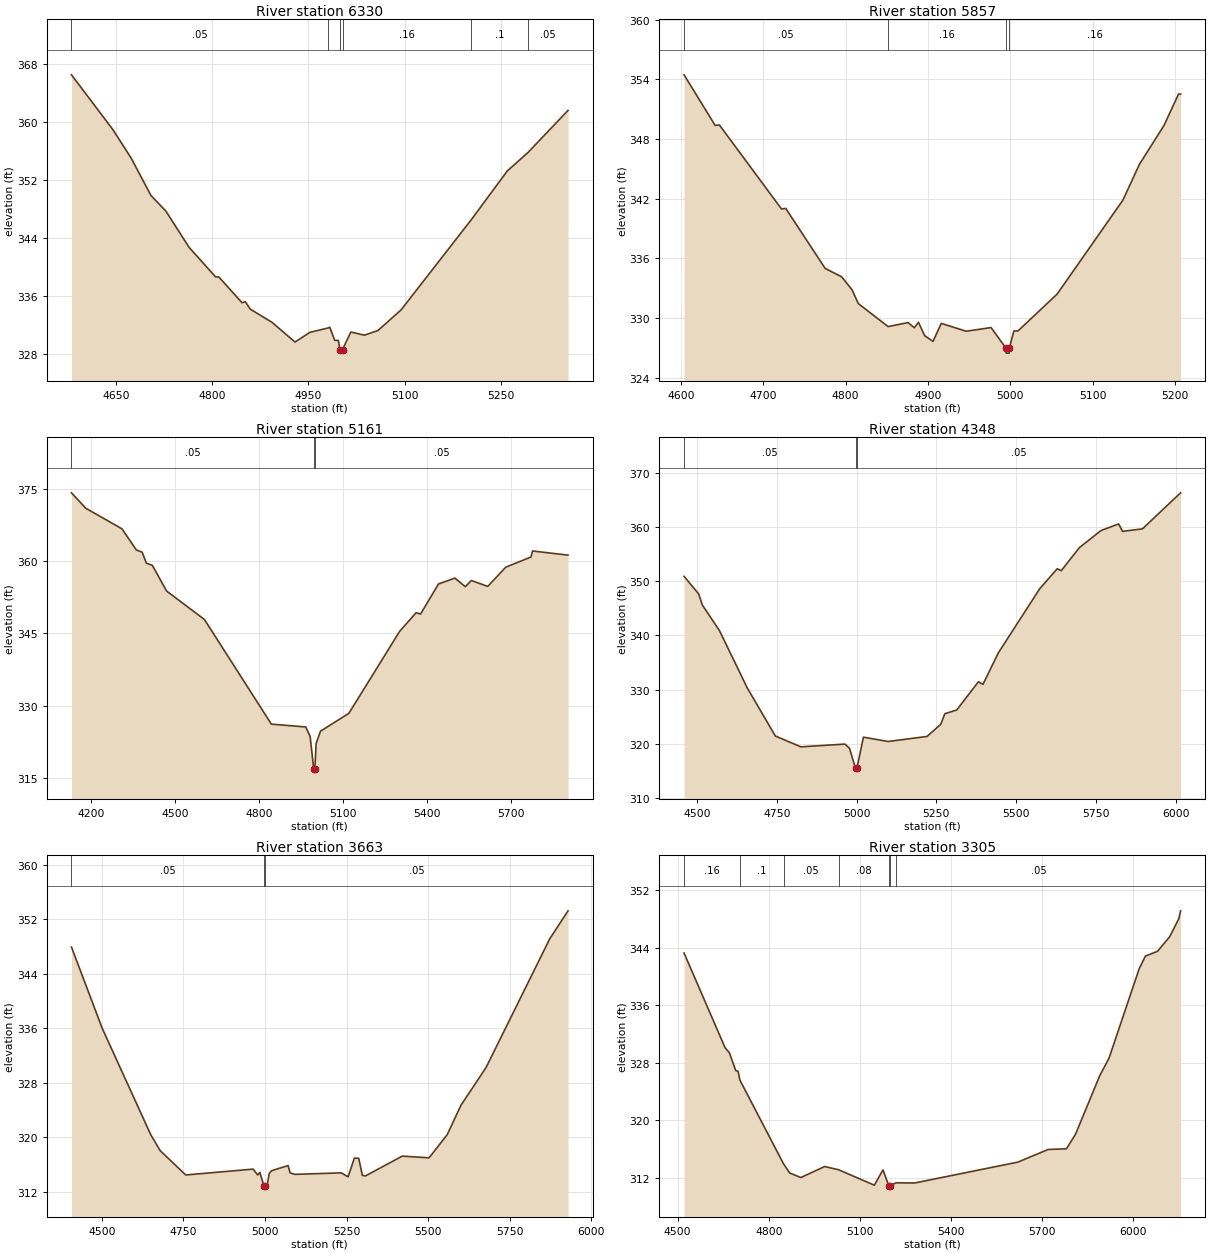
Type RM Length L Ch R = 1,6330,473,473,473
BEGIN DESCRIPTION:
COPPERAS BRANCH 2 1
END DESCRIPTION:
XS GIS Cut Line= 3
      3572892.13     10413141.64      3573292.11     10413041.64
      3573592.07     10412841.66
#Sta/Elev= 30
  4581.2  366.56  4645.6  359.00  4673.9  355.09  4704.9  349.90  4728.1  347.75
  4764.1  342.76  4805.4  338.67  4810.5  338.66  4846.6  335.10  4851.8  335.23
  4859.5  334.21  4893.0  332.41  4929.1  329.67  4952.3  331.01  4980.9  331.62
  4983.2  331.72  4990.9  329.90  4996.5  329.90  4999.0  328.64  4999.2  328.14
  5002.7  328.14  5003.0  328.64  5016.0  331.05  5037.0  330.62  5058.1  331.26
  5094.1  334.10  5203.7  346.59  5259.4  353.28  5291.6  355.83  5354.0  361.65
#Mann=6,-1,0
  4581.2    0.05       0  4980.9    0.16       0  4999.0    0.07       0
  5003.0    0.16       0  5203.7     0.1       0  5291.6    0.05       0
Bank Sta=4999,5003
Exp/Cntr=0.3,0.1

Type RM Length L Ch R = 1,5857,696,696,696
BEGIN DESCRIPTION:
COPPERAS BRANCH 2 0
END DESCRIPTION:
XS GIS Cut Line= 3
      3572992.07     10413341.64      3573392.11     10413391.64
      3573592.06     10413391.64
#Sta/Elev= 30
  4603.8  354.44  4641.6  349.35  4646.7  349.40  4722.2  340.95  4727.3  341.01
  4775.2  334.98  4795.3  334.13  4807.9  332.82  4815.5  331.44  4851.6  329.13
  4875.9  329.53  4883.5  329.01  4888.5  329.56  4896.1  328.21  4906.2  327.64
  4916.2  329.45  4946.5  328.66  4976.7  329.03  4994.8  326.96  4995.1  326.46
  4998.7  326.46  4998.9  326.96  5004.4  328.69  5009.4  328.69  5056.9  332.39
  5136.9  341.85  5156.9  345.44  5186.9  349.37  5204.4  352.51  5206.9  352.51
#Mann=4,-1,0
  4603.8    0.05       0  4851.6    0.16       0  4994.8    0.07       0
  4998.9    0.16       0
Bank Sta=4994.8,4998.9
Exp/Cntr=0.3,0.1

Type RM Length L Ch R = 1,5161,813,813,813
BEGIN DESCRIPTION:
COPPERAS BRANCH 8 2
END DESCRIPTION:
XS GIS Cut Line= 3
      3572594.89     10413498.30      3573267.67     10413941.04
      3574105.37     10414431.50
#Sta/Elev= 30
  4129.1  374.13  4180.1  370.94  4309.7  366.67  4360.9  362.30  4381.9  361.83
  4397.0  359.54  4418.1  359.12  4469.3  353.78  4604.8  347.87  4844.0  326.20
  4967.0  325.61  4982.7  323.66  4995.5  316.96  4995.7  316.46  4999.7  316.96
  5004.2  322.20  5019.8  324.73  5121.5  328.45  5303.2  345.45  5361.9  349.29
  5377.6  349.00  5442.0  355.25  5500.7  356.46  5537.9  354.68  5559.4  355.96
  5618.0  354.74  5682.5  358.72  5772.5  360.83  5778.3  362.08  5905.2  361.22
#Mann=3,-1,0
  4129.1    0.05       0  4995.5   0.035       0  4999.7    0.05       0
Bank Sta=4995.5,4999.7
Exp/Cntr=0.3,0.1

Type RM Length L Ch R = 1,4348,685,685,685
BEGIN DESCRIPTION:
COPPERAS BRANCH 8 1
END DESCRIPTION:
XS GIS Cut Line= 4
      3572492.09     10414041.61      3572694.76     10414405.45
      3572968.19     10414757.01      3573653.91     10414865.51
#Sta/Elev= 30
  4459.4  350.94  4505.2  347.69  4516.7  345.64  4570.3  340.91  4657.2  330.34
  4745.6  321.41  4825.7  319.41  4963.6  319.92  4978.1  319.13  4996.7  315.42
  4997.0  314.92  5001.0  315.42  5021.5  321.20  5099.1  320.40  5220.6  321.33
  5263.8  323.57  5276.7  325.54  5313.8  326.22  5381.9  331.44  5396.1  330.96
  5444.3  336.78  5574.1  348.65  5628.9  352.34  5641.5  351.99  5698.8  356.27
  5766.2  359.41  5821.3  360.63  5833.6  359.25  5896.0  359.72  6015.5  366.38
#Mann=3,-1,0
  4459.4    0.05       0  4996.7   0.035       0  5001.0    0.05       0
Bank Sta=4996.7,5001
Exp/Cntr=0.3,0.1

Type RM Length L Ch R = 1,3663,358,358,358
BEGIN DESCRIPTION:
COPPERAS BRANCH 8 0
END DESCRIPTION:
XS GIS Cut Line= 3
      3571744.20     10414507.27      3572422.58     10415052.84
      3573056.69     10415201.28
#Sta/Elev= 30
  4406.9  347.93  4501.1  336.00  4649.9  320.36  4678.6  318.03  4757.0  314.45
  4963.4  315.31  4977.8  314.45  4984.2  314.83  4996.5  312.87  4996.8  312.37
  5000.8  312.87  5006.6  312.95  5013.0  314.67  5020.2  315.08  5070.6  315.83
  5077.0  314.75  5091.4  314.54  5233.8  314.76  5254.6  314.17  5273.9  316.93
  5287.2  316.90  5298.4  314.38  5307.8  314.31  5420.7  317.22  5502.9  316.97
  5558.4  320.37  5600.9  324.72  5677.5  330.24  5872.6  349.14  5928.7  353.26
#Mann=3,-1,0
  4406.9    0.05       0  4996.5    0.03       0  5000.8    0.05       0
Bank Sta=4996.5,5000.8
Exp/Cntr=0.3,0.1

Type RM Length L Ch R = 1,3305,360,360,360
BEGIN DESCRIPTION:
Mapping XS a840a7e2
END DESCRIPTION:
XS GIS Cut Line= 3
      3571613.98     10414699.96      3572063.21     10415262.47
      3572977.87     10415272.88
#Sta/Elev= 30
  4521.2  343.24  4656.1  330.10  4670.5  329.38  4691.3  326.91  4699.3  326.80
  4705.0  325.59  4848.7  313.95  4869.0  312.68  4905.8  312.05  4984.1  313.58
  5029.9  313.13  5147.6  310.99  5176.0  313.11  5195.1  310.94  5195.4  310.44
  5199.4  310.94  5220.0  311.32  5280.0  311.29  5620.0  314.19  5720.0  315.95
  5780.0  316.04  5810.0  318.07  5890.0  326.23  5920.0  328.61  6020.0  341.11
  6040.0  342.81  6080.0  343.48  6120.0  345.51  6150.0  348.01  6155.8  349.10
#Mann=7,-1,0
  4521.2    0.16       0  4705.0     0.1       0  4848.7    0.05       0
  5029.9    0.08       0  5195.1    0.03       0  5199.4    0.08       0
  5220.0    0.05       0
Bank Sta=5195.1,5199.4
Exp/Cntr=0.3,0.1

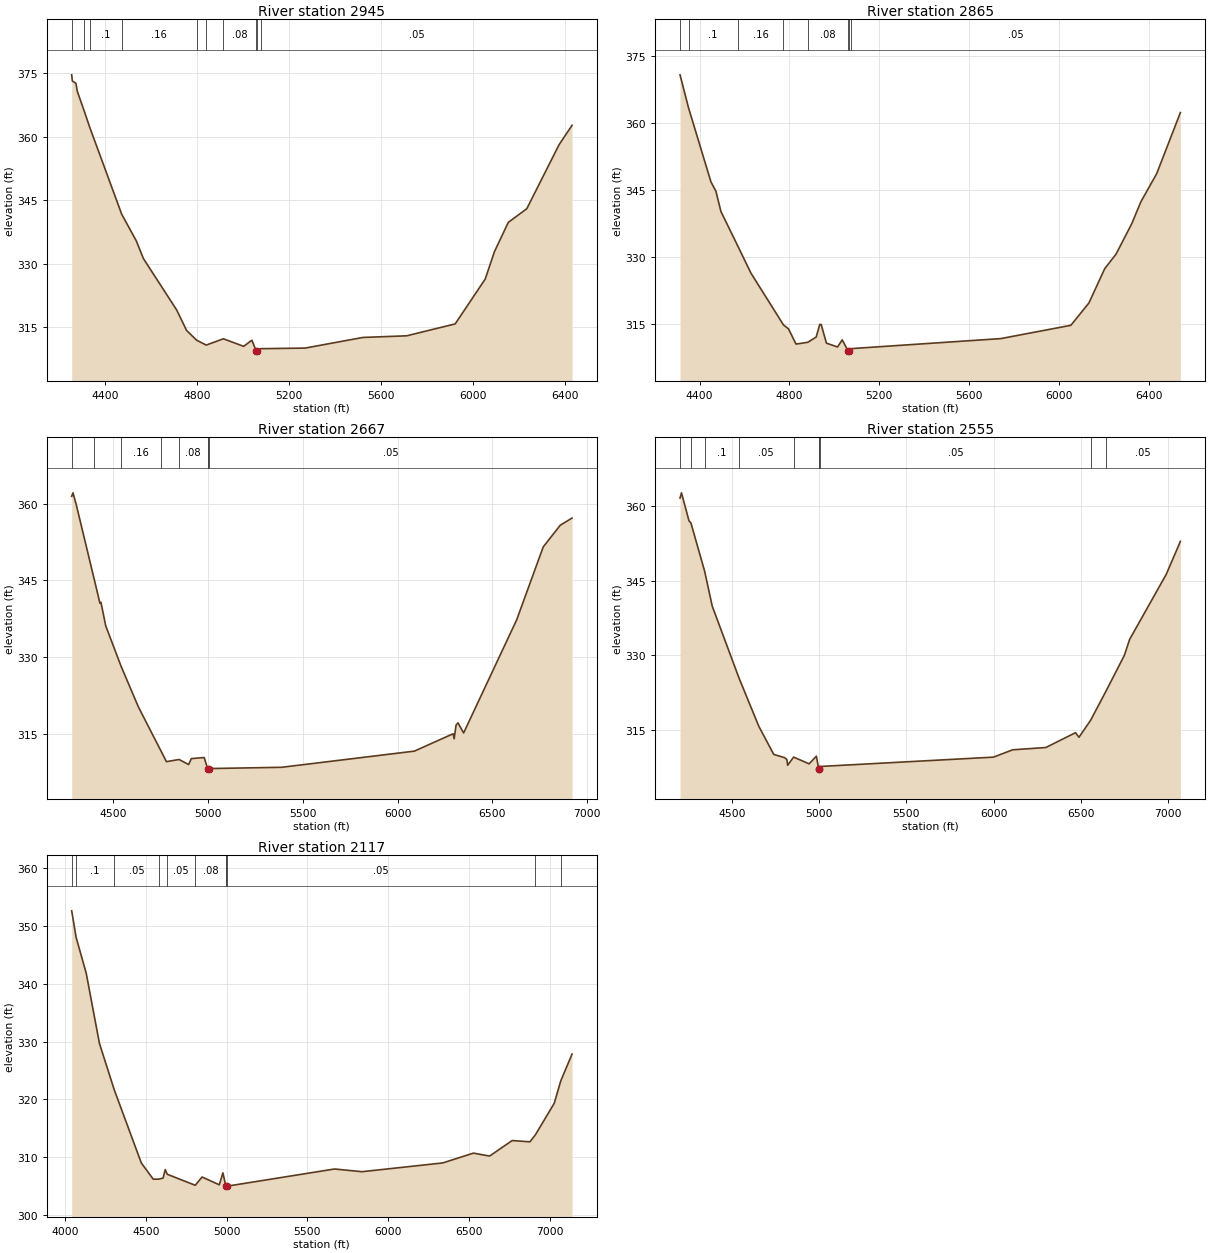
Type RM Length L Ch R = 1,2945,80,80,80
BEGIN DESCRIPTION:
COPPERAS BRANCH 7 0
END DESCRIPTION:
XS GIS Cut Line= 4
      3571377.05     10414641.86      3571734.67     10415254.66
      3571903.07     10415405.71      3573138.16     10415294.69
#Sta/Elev= 30
  4253.4  374.60  4256.2  373.15  4271.9  372.59  4277.7  370.73  4307.0  366.20
  4331.6  362.26  4471.1  341.66  4534.0  335.44  4565.5  331.20  4710.2  319.06
  4753.2  314.23  4796.9  311.94  4838.4  310.79  4913.2  312.28  5001.2  310.49
  5037.1  311.94  5055.8  309.39  5056.1  308.89  5060.1  309.39  5075.4  309.94
  5268.5  310.08  5519.5  312.59  5710.3  312.98  5921.1  315.79  6051.6  326.37
  6091.8  332.85  6152.0  339.77  6232.4  342.98  6372.9  358.11  6429.2  362.68
#Mann=10,-1,0
  4253.4    0.05       0  4307.0    0.16       0  4331.6     0.1       0
  4471.1    0.16       0  4796.9    0.05       0  4838.4     0.1       0
  4913.2    0.08       0  5055.8    0.07       0  5060.1    0.08       0
  5075.4    0.05       0
Bank Sta=5055.8,5060.1
Exp/Cntr=0.3,0.1

Type RM Length L Ch R = 1,2865,198,198,198
BEGIN DESCRIPTION:
COPPERAS BRANCH 5 0
END DESCRIPTION:
XS GIS Cut Line= 5
      3571366.61     10414700.56      3571656.54     10415273.76
      3571772.86     10415397.02      3572281.54     10415483.83
      3573177.11     10415386.64
#Sta/Elev= 30
  4312.8  370.82  4350.7  363.41  4450.5  346.81  4472.7  344.70  4495.0  340.16
  4570.2  332.42  4628.7  326.35  4773.4  314.74  4795.8  313.86  4829.5  310.44
  4881.8  310.84  4919.2  312.01  4935.1  314.85  4941.6  314.82  4964.8  310.65
  5014.2  309.79  5035.2  311.38  5061.4  308.91  5061.7  308.41  5065.7  308.91
  5072.5  309.41  5741.8  311.67  6053.6  314.65  6134.1  319.66  6204.5  327.36
  6254.8  330.60  6325.2  337.47  6365.5  342.35  6435.9  348.65  6541.5  362.36
#Mann=8,-1,0
  4312.8    0.05       0  4350.7     0.1       0  4570.2    0.16       0
  4773.4    0.05       0  4881.8    0.08       0  5061.4    0.07       0
  5065.7    0.08       0  5072.5    0.05       0
Bank Sta=5061.4,5065.7
Exp/Cntr=0.3,0.1

Type RM Length L Ch R = 1,2667,112,112,112
BEGIN DESCRIPTION:
COPPERAS BRANCH 3 0
END DESCRIPTION:
XS GIS Cut Line= 4
      3571295.45     10414758.18      3571526.34     10415391.82
      3571677.38     10415601.89      3573383.98     10415561.95
#Sta/Elev= 30
  4280.5  361.40  4287.4  362.09  4305.5  359.64  4400.3  345.04  4429.6  340.49
  4435.0  340.66  4460.2  336.06  4540.6  328.21  4633.0  320.16  4752.6  311.52
  4780.5  309.49  4847.1  309.92  4897.5  308.93  4912.1  310.09  4979.4  310.30
  4997.4  308.21  5000.5  308.14  5000.8  307.64  5004.8  308.14  5388.4  308.39
  6088.6  311.55  6293.2  314.95  6298.7  313.97  6308.7  316.63  6318.7  317.09
  6348.7  315.11  6628.7  337.25  6768.8  351.52  6858.8  355.76  6920.7  357.15
#Mann=8,-1,0
  4280.5    0.05       0  4400.3     0.1       0  4540.6    0.16       0
  4752.6    0.05       0  4847.1    0.08       0  4997.4    0.05       0
  5000.5    0.03       0  5004.8    0.05       0
Bank Sta=5000.5,5004.8
Exp/Cntr=0.3,0.1

Type RM Length L Ch R = 1,2555,438,438,438
BEGIN DESCRIPTION:
COPPERAS BRANCH 2 2
END DESCRIPTION:
XS GIS Cut Line= 4
      3571205.32     10414718.25      3571342.31     10415311.96
      3571592.31     10415681.75      3573403.12     10415674.80
#Sta/Elev= 30
  4203.4  361.68  4211.7  362.73  4254.5  357.11  4265.8  356.65  4344.2  346.94
  4387.9  339.88  4540.8  325.42  4654.7  315.65  4740.3  309.98  4802.1  309.33
  4815.5  308.95  4819.8  307.79  4854.2  309.44  4942.7  308.08  4984.7  309.62
  4997.5  307.11  4997.8  306.61  5001.8  307.11  5006.7  307.55  5998.9  309.43
  6108.9  310.91  6298.9  311.37  6468.9  314.36  6488.9  313.44  6555.6  316.87
  6642.4  322.65  6748.9  329.96  6778.9  333.16  6988.9  346.30  7069.9  352.94
#Mann=10,-1,0
  4203.4    0.16       0  4265.8    0.05       0  4344.2     0.1       0
  4540.8    0.05       0  4854.2    0.08       0  4997.5    0.07       0
  5001.8    0.08       0  5006.7    0.05       0  6555.6    0.16       0
  6642.4    0.05       0
Bank Sta=4997.5,5001.8
Exp/Cntr=0.3,0.1

Type RM Length L Ch R = 1,2117,0,0,0
BEGIN DESCRIPTION:
COPPERAS BRANCH 3 1
END DESCRIPTION:
XS GIS Cut Line= 4
      3571130.00     10414755.93      3570928.62     10415488.56
      3571161.25     10415797.59      3573112.64     10415769.81
#Sta/Elev= 30
  4040.8  352.66  4067.9  348.11  4131.0  341.82  4212.7  329.68  4304.1  321.66
  4471.9  308.96  4546.0  306.14  4579.6  306.15  4606.8  306.34  4620.0  307.81
  4632.9  306.99  4805.7  305.09  4848.1  306.52  4954.7  305.17  4977.2  307.24
  4995.2  304.98  4995.9  304.92  4996.2  304.42  5000.2  304.92  5668.3  307.91
  5838.3  307.44  6338.4  308.96  6528.4  310.66  6628.4  310.15  6768.4  312.84
  6878.4  312.62  6912.5  313.86  7028.5  319.28  7069.5  323.20  7139.0  327.83
#Mann=11,-1,0
  4040.8    0.16       0  4067.9     0.1       0  4304.1    0.05       0
  4579.6     0.1       0  4632.9    0.05       0  4805.7    0.08       0
  4995.2    0.05       0  4995.9    0.03       0  5000.2    0.05       0
  6912.5    0.16       0  7069.5    0.05       0
Bank Sta=4995.9,5000.2
Exp/Cntr=0.3,0.1

Chan Stop Cuts=-1