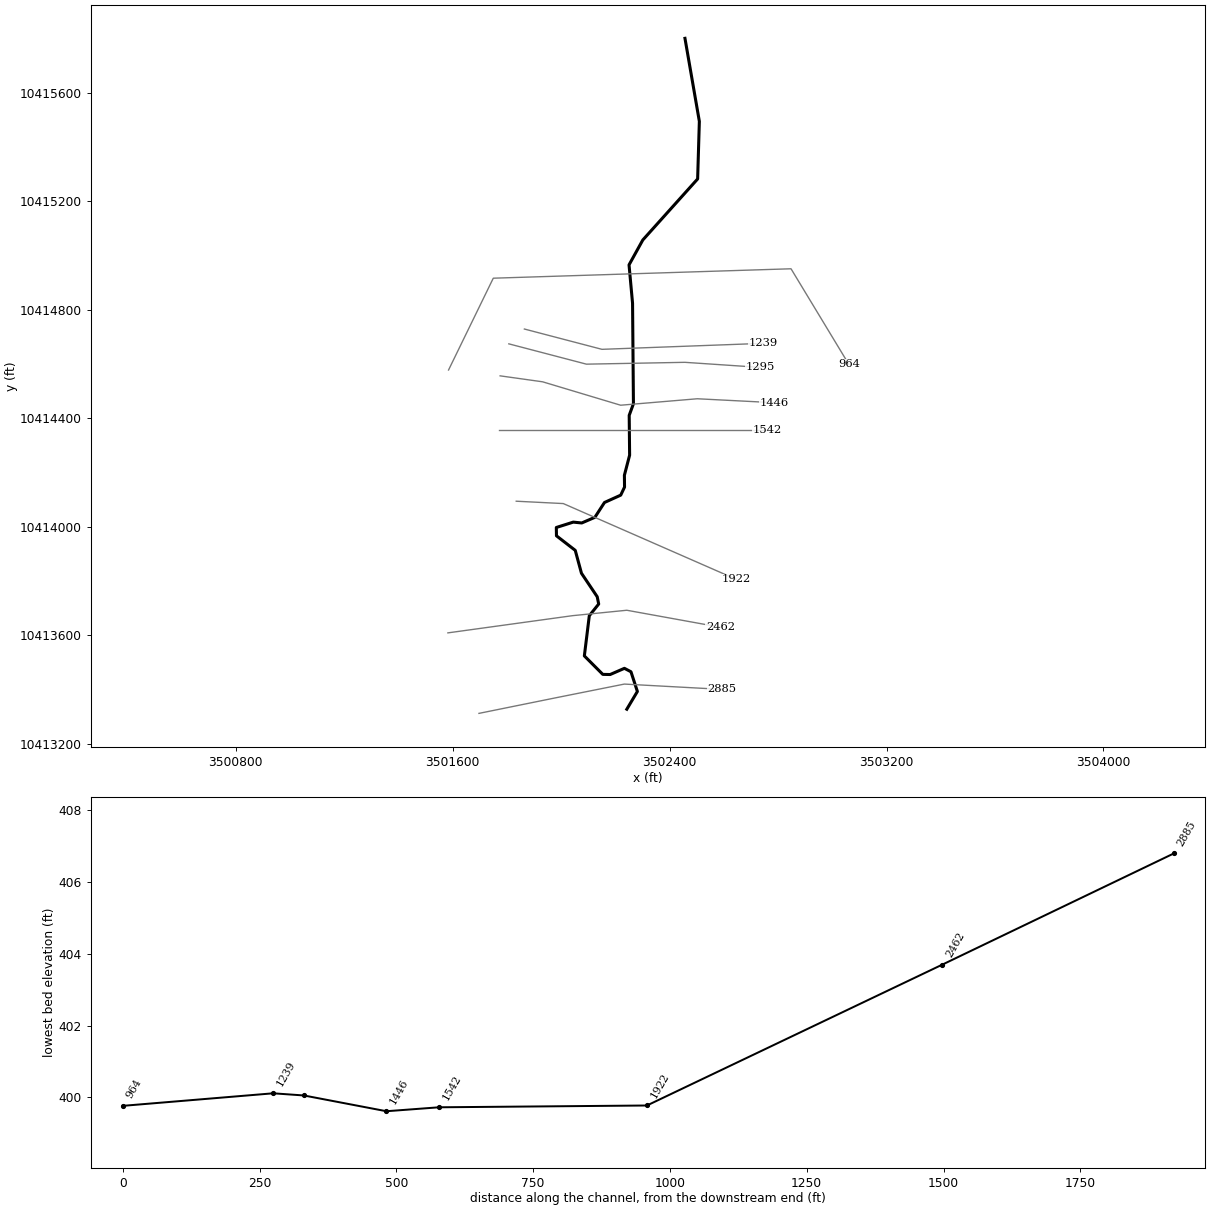
--- DOGWOOD CR WEST TRIB 3.prj (project) ---

Proj Title=DOGWOOD CR WEST TRIB 3 Base Level Engineering
Current Plan=p01
Default Exp/Contr=0.3,0.1
English Units
Geom File=g01
Flow File=f01
Plan File=p01
Y Axis Title=Elevation
X Axis Title(PF)=Main Channel Distance
X Axis Title(XS)=Station
BEGIN DESCRIPTION:
DOGWOOD CR WEST TRIB 3
END DESCRIPTION:
DSS Export Rating Curves= 0
DSS Export Rating Curve Sorted= 0
DSS Export Volume Flow Curves= 0
DXF OffsetX= 0
DXF OffsetY= 0
DXF ScaleX= 1
DXF ScaleY= 10

--- DOGWOOD CR WEST TRIB 3.p01 (plan) ---

Plan Title=Multiple Run
Short Identifier=Multiple
Geom File=g01
Flow File=f01
Subcritical Flow
K Sum by GR= 0
Std Step Tol= 0.01
Critical Tol= 0.01
Num of Std Step Trials= 20
Max Error Tol= 0.3
Flow Tol Ratio= 0.001
Split Flow NTrial= 30
Split Flow Tol= 0.02
Split Flow Ratio= 0.02
Log Output Level= 0
Friction Slope Method= 1
Unsteady Friction Slope Method= 2
Unsteady Bridges Friction Slope Method= 1
Parabolic Critical Depth
Global Vel Dist=  1 , 1 , 1
Global Log Level= 0
CheckData=True
Encroach Param= -1, 0, 0, 0
BEGIN DESCRIPTION:
Multiple Run
END DESCRIPTION:

--- DOGWOOD CR WEST TRIB 3.f01 (steady flow) ---

Flow Title=Multiple
Number of Profiles=7
Profile Names=10-year,25-year,50-year,1pct_min,100-year,1pct_plu,500-year
River Rch & RM= DOGWOOD CR WEST ,Reach-1,2885
     280     356     413     352     475     643     626
Boundary for River Rch & Prof#=DOGWOOD CR WEST ,Reach-1,1
Up Type=0
Dn Type=3
Dn Slope=0.005
Boundary for River Rch & Prof#=DOGWOOD CR WEST ,Reach-1,2
Up Type=0
Dn Type=3
Dn Slope=0.005
Boundary for River Rch & Prof#=DOGWOOD CR WEST ,Reach-1,3
Up Type=0
Dn Type=3
Dn Slope=0.005
Boundary for River Rch & Prof#=DOGWOOD CR WEST ,Reach-1,4
Up Type=0
Dn Type=3
Dn Slope=0.005
Boundary for River Rch & Prof#=DOGWOOD CR WEST ,Reach-1,5
Up Type=0
Dn Type=3
Dn Slope=0.005
Boundary for River Rch & Prof#=DOGWOOD CR WEST ,Reach-1,6
Up Type=0
Dn Type=3
Dn Slope=0.005
Boundary for River Rch & Prof#=DOGWOOD CR WEST ,Reach-1,7
Up Type=0
Dn Type=3
Dn Slope=0.005

--- DOGWOOD CR WEST TRIB 3.g01 (geometry) ---

Geom Title=Existing Conditions

River Reach=DOGWOOD CR WEST ,Reach-1
Reach XY= 30
      3502242.11     10413326.64      3502281.12     10413392.11
      3502257.43     10413464.79      3502233.25     10413477.44
      3502180.68     10413454.62      3502153.57     10413455.12
      3502085.52     10413523.28      3502103.78     10413671.46
      3502138.41     10413714.58      3502132.93     10413741.51
      3502074.87     10413828.12      3502051.95     10413912.50
      3501982.68     10413966.14      3501982.16     10413996.87
      3502044.66     10414016.66      3502075.91     10414013.54
      3502124.35     10414034.37      3502159.77     10414089.06
      3502219.66     10414116.14      3502233.72     10414145.83
      3502233.20     10414189.58      3502252.47     10414263.54
      3502250.91     10414410.41      3502266.54     10414453.12
      3502263.30     10414823.81      3502250.31     10414965.42
      3502301.09     10415057.17      3502503.29     10415282.30
      3502509.64     10415494.61      3502456.58     10415800.83

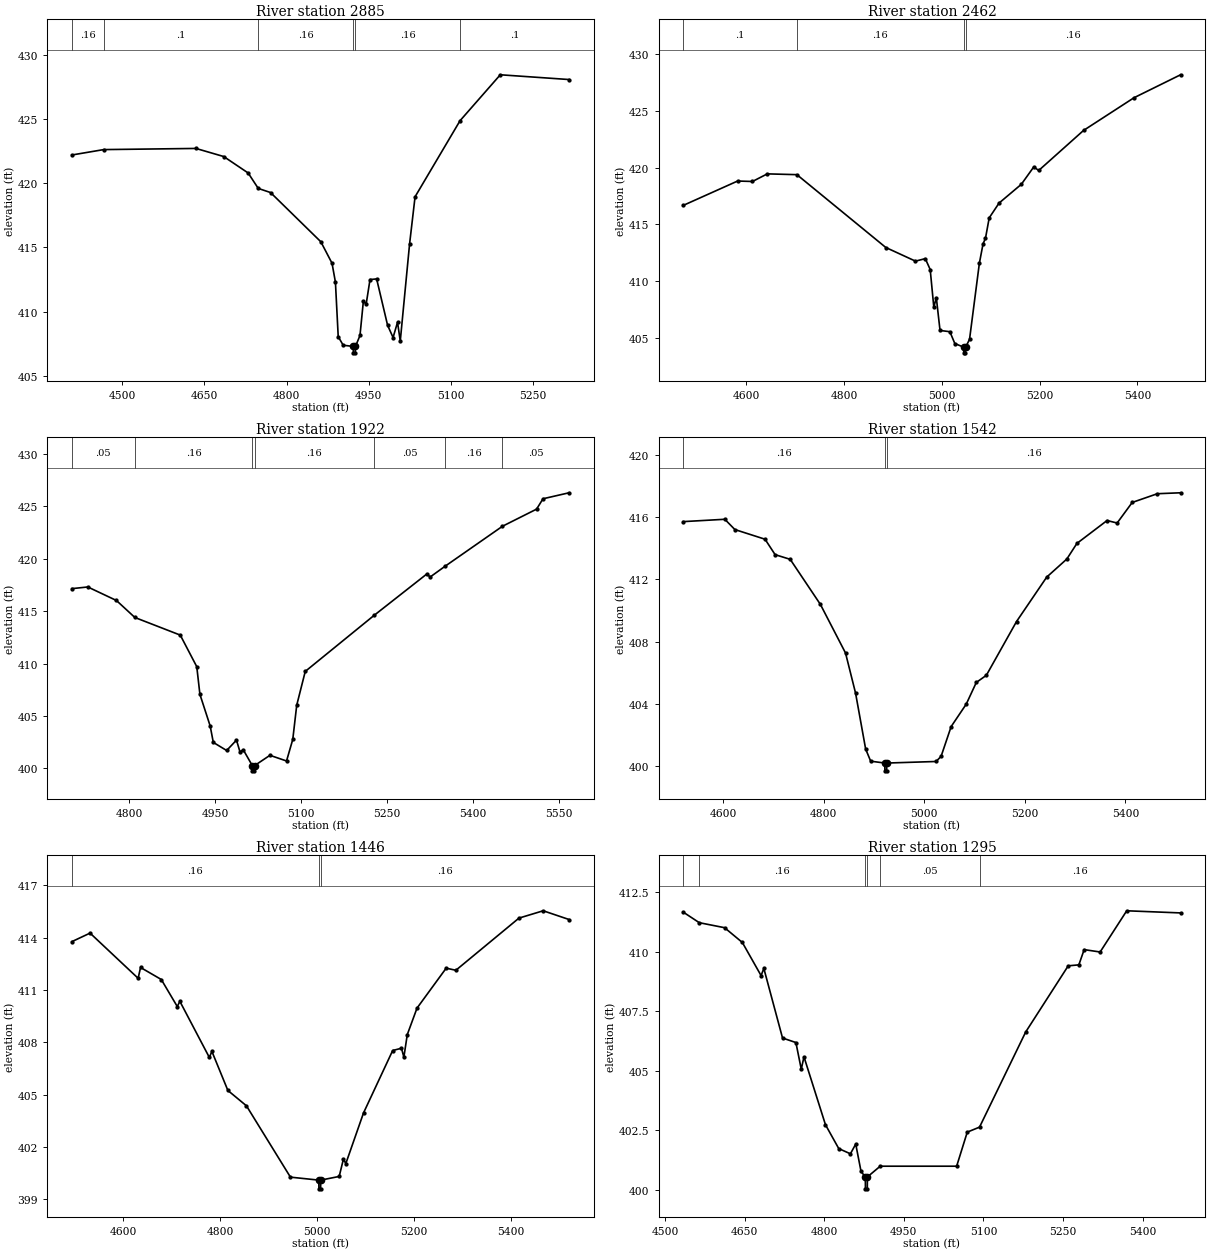
Type RM Length L Ch R = 1,2885,423,423,423
BEGIN DESCRIPTION:
DOGWOOD CR WEST TRIB 3 6
END DESCRIPTION:
XS GIS Cut Line= 4
      3501696.81     10413311.32      3501983.02     10413369.37
      3502233.02     10413419.37      3502592.61     10413399.86
#Sta/Elev= 30
  4408.1  422.19  4466.2  422.61  4634.5  422.70  4685.2  422.07  4729.8  420.79
  4748.2  419.59  4770.6  419.27  4862.4  415.44  4882.8  413.77  4889.0  412.30
  4894.1  408.06  4903.2  407.39  4921.6  407.30  4921.8  406.80  4925.3  406.80
  4925.6  407.30  4933.8  408.15  4940.0  410.82  4945.1  410.59  4952.1  412.50
  4964.2  412.55  4984.2  408.94  4994.2  407.99  5002.3  409.18  5007.3  407.72
  5024.3  415.27  5034.3  418.94  5116.4  424.86  5189.8  428.43  5315.2  428.06
#Mann=6,-1,0
  4408.1    0.16       0  4466.2     0.1       0  4748.2    0.16       0
  4921.6    0.07       0  4925.6    0.16       0  5116.4     0.1       0
Bank Sta=4921.6,4925.6
Exp/Cntr=0.3,0.1

Type RM Length L Ch R = 1,2462,540,540,540
BEGIN DESCRIPTION:
DOGWOOD CR WEST TRIB 3 5
END DESCRIPTION:
XS GIS Cut Line= 4
      3501582.25     10413608.20      3502042.43     10413671.71
      3502242.11     10413691.64      3502587.26     10413629.06
#Sta/Elev= 30
  4472.0  416.68  4582.9  418.82  4613.2  418.78  4643.5  419.45  4704.0  419.38
  4885.7  412.97  4946.3  411.77  4966.4  411.99  4976.4  411.03  4983.8  407.71
  4988.9  408.56  4996.5  405.67  5016.6  405.56  5026.7  404.52  5044.8  404.20
  5045.0  403.70  5048.5  403.70  5048.8  404.20  5056.8  404.89  5076.9  411.59
  5084.4  413.29  5089.4  413.79  5097.0  415.58  5117.1  416.88  5162.6  418.53
  5188.0  420.06  5198.2  419.75  5289.7  423.27  5392.9  426.15  5488.0  428.17
#Mann=4,-1,0
  4472.0     0.1       0  4704.0    0.16       0  5044.8    0.07       0
  5048.8    0.16       0
Bank Sta=5044.8,5048.8
Exp/Cntr=0.3,0.1

Type RM Length L Ch R = 1,1922,380,380,380
BEGIN DESCRIPTION:
DOGWOOD CR WEST TRIB 3 4 1
END DESCRIPTION:
XS GIS Cut Line= 3
      3501834.27     10414093.76      3502007.90     10414085.08
      3502644.08     10413806.39
#Sta/Elev= 30
  4699.4  417.14  4727.3  417.30  4777.3  416.01  4809.5  414.39  4888.8  412.71
  4917.6  409.70  4923.1  407.06  4941.0  404.05  4946.5  402.48  4969.8  401.71
  4987.0  402.70  4993.2  401.55  4998.7  401.79  5014.6  400.27  5014.8  399.77
  5018.3  399.77  5018.6  400.27  5045.4  401.25  5074.4  400.71  5085.3  402.77
  5092.2  406.03  5107.1  409.25  5227.3  414.59  5319.0  418.52  5325.5  418.26
  5351.7  419.29  5451.6  423.09  5511.1  424.72  5522.4  425.71  5567.8  426.28
#Mann=7,-1,0
  4699.4    0.05       0  4809.5    0.16       0  5014.6    0.07       0
  5018.6    0.16       0  5227.3    0.05       0  5351.7    0.16       0
  5451.6    0.05       0
Bank Sta=5014.6,5018.6
Exp/Cntr=0.3,0.1

Type RM Length L Ch R = 1,1542,96,96,96
BEGIN DESCRIPTION:
DOGWOOD CR WEST TRIB 3 3 0
END DESCRIPTION:
XS GIS Cut Line= 2
      3501769.68     10414358.19      3502758.18     10414358.19
#Sta/Elev= 30
  4521.3  415.71  4603.7  415.86  4623.7  415.20  4683.7  414.58  4703.7  413.59
  4733.7  413.29  4793.7  410.40  4843.7  407.28  4863.7  404.70  4883.7  401.12
  4893.7  400.34  4921.7  400.22  4922.0  399.72  4925.5  399.72  4925.7  400.22
  5023.7  400.32  5033.7  400.65  5053.7  402.56  5083.7  404.00  5103.7  405.39
  5123.7  405.85  5183.7  409.30  5243.7  412.15  5283.7  413.31  5303.7  414.31
  5363.7  415.78  5383.7  415.62  5413.7  416.94  5463.7  417.50  5509.8  417.56
#Mann=3,-1,0
  4521.3    0.16       0  4921.7    0.07       0  4925.7    0.16       0
Bank Sta=4921.7,4925.7
Exp/Cntr=0.3,0.1

Type RM Length L Ch R = 1,1446,151,151,151
BEGIN DESCRIPTION:
DOGWOOD CR WEST TRIB 3 4 0
END DESCRIPTION:
XS GIS Cut Line= 5
      3501774.90     10414556.11      3501931.70     10414534.10
      3502219.35     10414447.79      3502502.02     10414471.60
      3502785.32     10414457.15
#Sta/Elev= 30
  4494.5  413.78  4532.1  414.27  4631.3  411.68  4636.3  412.30  4679.1  411.61
  4712.1  410.06  4717.4  410.36  4778.3  407.14  4783.5  407.49  4816.5  405.25
  4854.8  404.37  4945.6  400.28  5004.1  400.11  5004.4  399.61  5007.9  399.61
  5008.1  400.11  5046.2  400.32  5054.9  401.31  5059.9  401.06  5096.4  403.96
  5156.6  407.54  5174.7  407.67  5179.7  407.16  5186.7  408.45  5206.8  409.97
  5267.0  412.26  5287.0  412.14  5417.2  415.13  5467.2  415.55  5520.5  415.05
#Mann=3,-1,0
  4494.5    0.16       0  5004.1    0.07       0  5008.1    0.16       0
Bank Sta=5004.1,5008.1
Exp/Cntr=0.3,0.1

Type RM Length L Ch R = 1,1295,56,56,56
BEGIN DESCRIPTION:
DOGWOOD CR WEST TRIB 3 2 0
END DESCRIPTION:
XS GIS Cut Line= 4
      3501807.00     10414674.10      3502093.16     10414599.21
      3502456.35     10414605.98      3502733.28     10414587.36
#Sta/Elev= 30
  4534.8  411.66  4564.8  411.22  4612.4  411.01  4645.9  410.39  4681.2  409.00
  4686.4  409.30  4721.6  406.38  4746.8  406.19  4756.9  405.07  4762.0  405.59
  4802.5  402.74  4827.5  401.74  4849.5  401.52  4859.5  401.93  4869.5  400.78
  4877.5  400.55  4877.8  400.05  4881.3  400.05  4881.5  400.55  4905.6  401.00
  5049.6  401.00  5069.6  402.43  5092.7  402.64  5179.6  406.63  5259.8  409.41
  5279.8  409.45  5289.8  410.09  5319.9  409.99  5370.0  411.72  5471.4  411.63
#Mann=6,-1,0
  4534.8     0.1       0  4564.8    0.16       0  4877.5   0.033       0
  4881.5    0.16       0  4905.6    0.05       0  5092.7    0.16       0
Bank Sta=4877.5,4881.5
Exp/Cntr=0.3,0.1

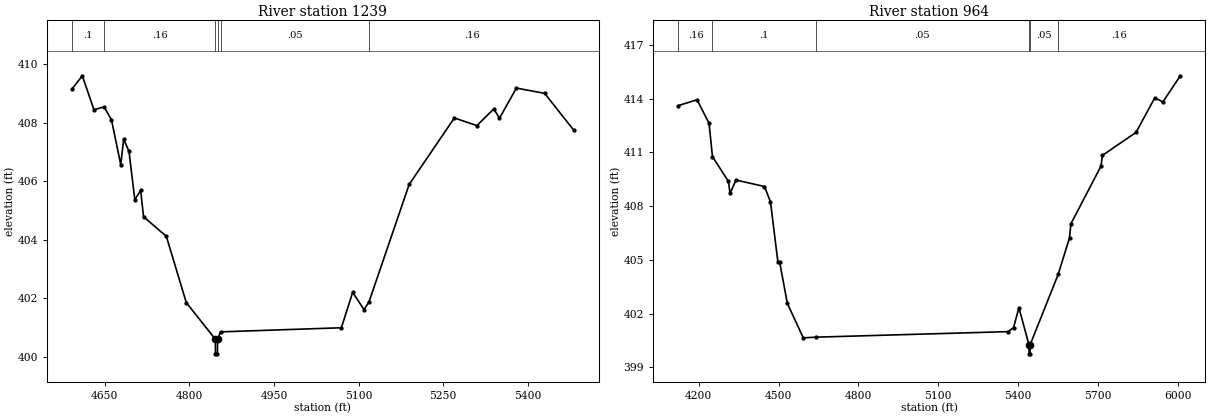
Type RM Length L Ch R = 1,1239,275,275,275
BEGIN DESCRIPTION:
DOGWOOD CR WEST TRIB 3 2 1
END DESCRIPTION:
XS GIS Cut Line= 3
      3501864.34     10414728.78      3502150.45     10414653.90
      3502743.70     10414675.90
#Sta/Elev= 30
  4591.9  409.15  4610.3  409.60  4630.9  408.44  4648.8  408.54  4661.9  408.10
  4678.4  406.57  4683.6  407.44  4693.0  407.02  4703.3  405.37  4713.6  405.69
  4718.8  404.79  4759.2  404.12  4794.5  401.86  4846.0  400.61  4846.3  400.11
  4849.8  400.11  4850.0  400.61  4855.3  400.86  5069.4  401.00  5089.4  402.21
  5109.5  401.62  5118.5  401.89  5189.5  405.89  5269.6  408.16  5309.6  407.90
  5339.6  408.47  5349.6  408.15  5379.6  409.18  5429.7  409.00  5481.3  407.74
#Mann=6,-1,0
  4591.9     0.1       0  4648.8    0.16       0  4846.0   0.033       0
  4850.0    0.16       0  4855.3    0.05       0  5118.5    0.16       0
Bank Sta=4846,4850
Exp/Cntr=0.3,0.1

Type RM Length L Ch R = 1,964,0,0,0
BEGIN DESCRIPTION:
DOGWOOD CR WEST TRIB 3 1 0
END DESCRIPTION:
XS GIS Cut Line= 4
      3501584.71     10414577.68      3501749.65     10414916.24
      3502847.74     10414950.97      3503060.40     10414599.43
#Sta/Elev= 30
  4123.6  413.62  4193.4  413.94  4238.5  412.63  4251.3  410.77  4311.6  409.38
  4317.2  408.71  4339.7  409.46  4446.9  409.10  4469.4  408.24  4497.3  404.88
  4503.9  404.88  4532.7  402.58  4592.7  400.65  4639.1  400.69  5363.1  401.00
  5383.1  401.23  5403.1  402.33  5441.1  400.26  5441.4  399.76  5444.9  399.76
  5445.1  400.26  5550.5  404.19  5593.2  406.23  5598.5  407.02  5711.3  410.23
  5717.2  410.84  5843.2  412.12  5913.6  414.05  5944.1  413.82  6009.7  415.28
#Mann=6,-1,0
  4123.6    0.16       0  4251.3     0.1       0  4639.1    0.05       0
  5441.1   0.033       0  5445.1    0.05       0  5550.5    0.16       0
Bank Sta=5441.1,5445.1
Exp/Cntr=0.3,0.1

Chan Stop Cuts=-1