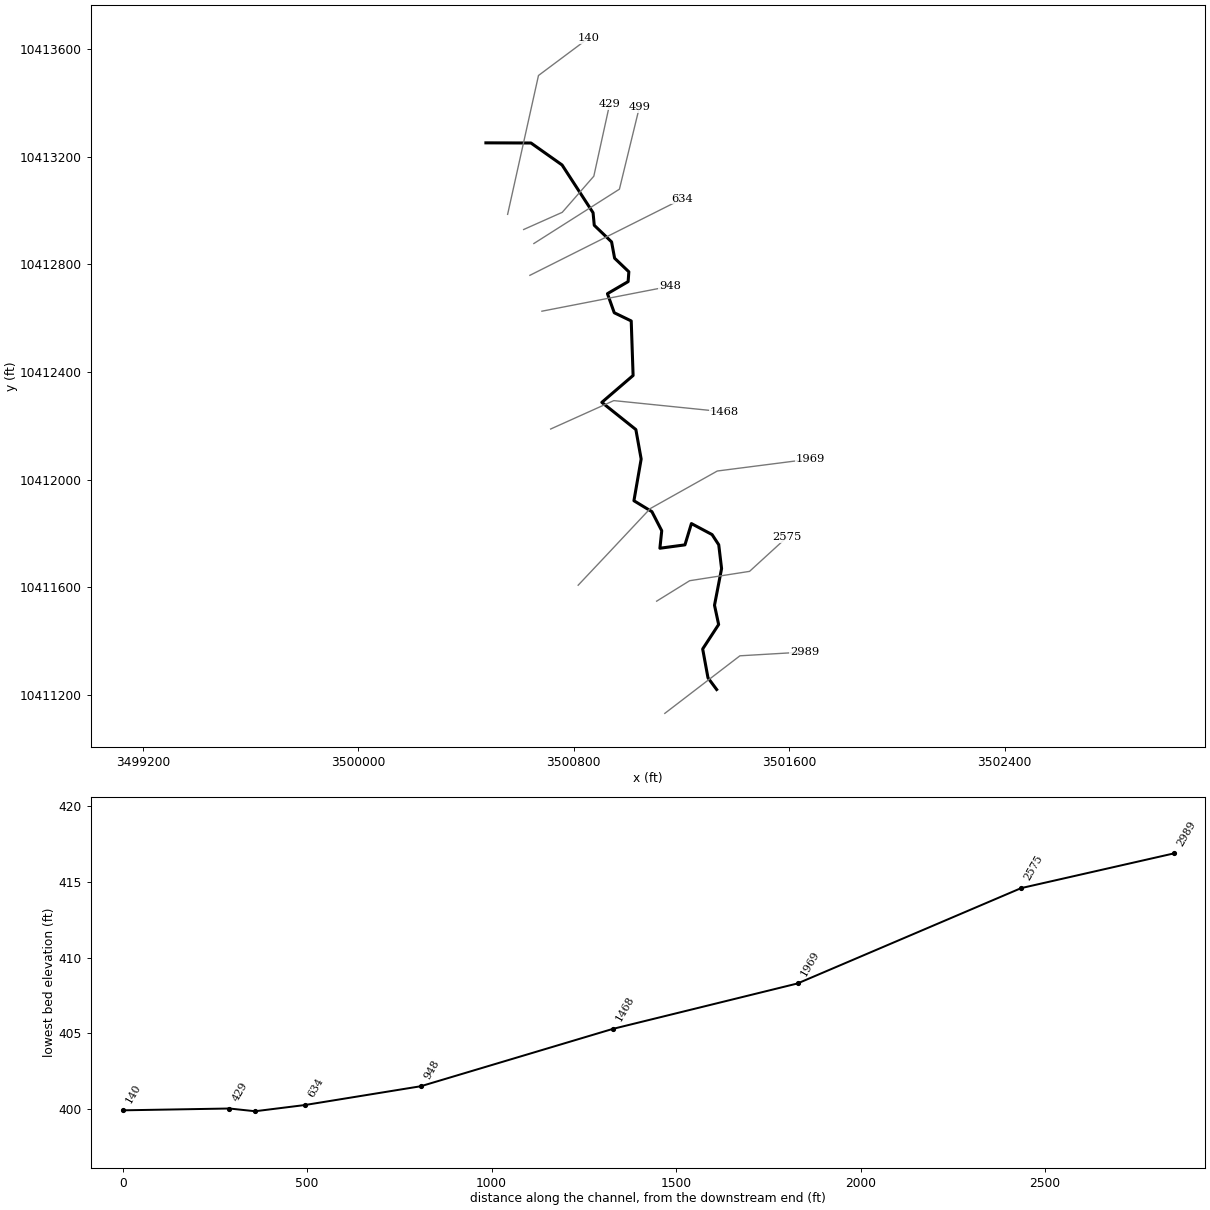
--- DOGWOOD CR WEST TRIB 4.prj (project) ---

Proj Title=DOGWOOD CR WEST TRIB 4 Base Level Engineering
Current Plan=p01
Default Exp/Contr=0.3,0.1
English Units
Geom File=g01
Flow File=f01
Plan File=p01
BEGIN DESCRIPTION:
DOGWOOD CR WEST TRIB 4
END DESCRIPTION:

--- DOGWOOD CR WEST TRIB 4.p01 (plan) ---

Plan Title=Multiple Run
Short Identifier=Multiple
Geom File=g01
Flow File=f01
Subcritical Flow
K Sum by GR= 0
Std Step Tol= 0.01
Critical Tol= 0.01
Num of Std Step Trials= 20
Max Error Tol= 0.3
Flow Tol Ratio= 0.001
Split Flow NTrial= 30
Split Flow Tol= 0.02
Split Flow Ratio= 0.02
Log Output Level= 0
Friction Slope Method= 1
Unsteady Friction Slope Method= 2
Unsteady Bridges Friction Slope Method= 1
Parabolic Critical Depth
Global Vel Dist=  1 , 1 , 1
Global Log Level= 0
CheckData=True
Encroach Param= -1, 0, 0, 0
BEGIN DESCRIPTION:
Multiple Run
END DESCRIPTION:

--- DOGWOOD CR WEST TRIB 4.f01 (steady flow) ---

Flow Title=Multiple
Number of Profiles=7
Profile Names=10-year,25-year,50-year,1pct_min,100-year,1pct_plu,500-year
River Rch & RM= DOGWOOD CR WEST ,Reach-1,2989
     380     493     580     500     677     915     916
Boundary for River Rch & Prof#=DOGWOOD CR WEST ,Reach-1,1
Up Type=0
Dn Type=3
Dn Slope=0.005
Boundary for River Rch & Prof#=DOGWOOD CR WEST ,Reach-1,2
Up Type=0
Dn Type=3
Dn Slope=0.005
Boundary for River Rch & Prof#=DOGWOOD CR WEST ,Reach-1,3
Up Type=0
Dn Type=3
Dn Slope=0.005
Boundary for River Rch & Prof#=DOGWOOD CR WEST ,Reach-1,4
Up Type=0
Dn Type=3
Dn Slope=0.005
Boundary for River Rch & Prof#=DOGWOOD CR WEST ,Reach-1,5
Up Type=0
Dn Type=3
Dn Slope=0.005
Boundary for River Rch & Prof#=DOGWOOD CR WEST ,Reach-1,6
Up Type=0
Dn Type=3
Dn Slope=0.005
Boundary for River Rch & Prof#=DOGWOOD CR WEST ,Reach-1,7
Up Type=0
Dn Type=3
Dn Slope=0.005

--- DOGWOOD CR WEST TRIB 4.g01 (geometry) ---

Geom Title=Existing Conditions

River Reach=DOGWOOD CR WEST ,Reach-1
Reach XY= 30
      3501330.92     10411220.80      3501298.68     10411264.25
      3501278.95     10411371.41      3501338.25     10411462.25
      3501322.90     10411533.82      3501349.17     10411669.93
      3501338.61     10411758.32      3501313.93     10411796.17
      3501237.15     10411837.05      3501213.13     10411758.01
      3501120.09     10411745.48      3501126.93     10411810.46
      3501090.40     10411881.33      3501023.68     10411921.91
      3501050.53     10412076.70      3501030.85     10412186.22
      3500904.46     10412287.21      3501020.59     10412387.03
      3501013.61     10412589.53      3500950.59     10412620.00
      3500925.33     10412690.83      3501002.15     10412735.62
      3501004.76     10412772.08      3500951.89     10412822.60
      3500940.69     10412883.02      3500876.37     10412944.74
      3500871.94     10412991.35      3500756.81     10413168.76
      3500641.35     10413250.35      3500473.99     10413250.91

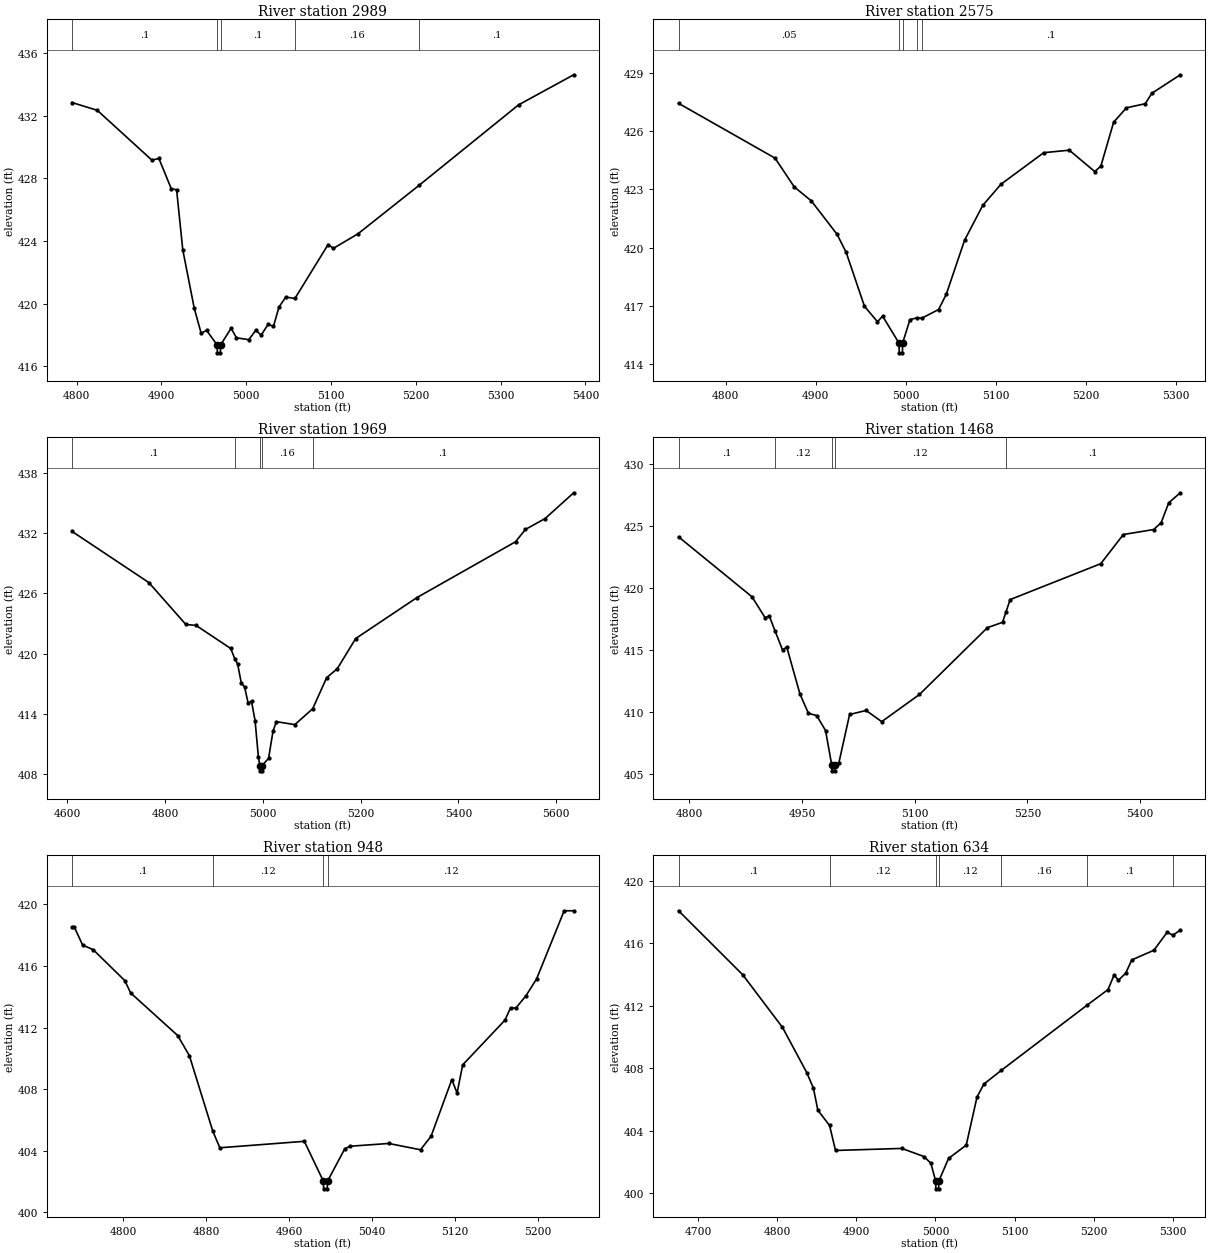
Type RM Length L Ch R = 1,2989,414,414,414
BEGIN DESCRIPTION:
DOGWOOD CR WEST TRIB 4 8 0
END DESCRIPTION:
XS GIS Cut Line= 3
      3501138.37     10411132.24      3501417.26     10411346.03
      3501657.04     10411360.13
#Sta/Elev= 30
  4794.6  432.85  4824.5  432.35  4888.9  429.17  4897.1  429.28  4911.7  427.35
  4918.0  427.28  4925.3  423.44  4938.8  419.72  4947.0  418.11  4953.3  418.31
  4965.8  417.37  4966.1  416.87  4969.6  416.87  4969.8  417.37  4982.3  418.44
  4988.6  417.83  5003.1  417.71  5011.4  418.31  5017.7  418.00  5025.9  418.69
  5032.2  418.56  5038.7  419.79  5046.7  420.43  5057.5  420.34  5096.6  423.78
  5102.9  423.54  5131.9  424.47  5204.3  427.58  5321.2  432.70  5386.2  434.62
#Mann=5,-1,0
  4794.6     0.1       0  4965.8    0.07       0  4969.8     0.1       0
  5057.5    0.16       0  5204.3     0.1       0
Bank Sta=4965.8,4969.8
Exp/Cntr=0.3,0.1

Type RM Length L Ch R = 1,2575,606,606,606
BEGIN DESCRIPTION:
DOGWOOD CR WEST TRIB 4 7 0
END DESCRIPTION:
XS GIS Cut Line= 4
      3501108.01     10411548.93      3501230.63     10411624.89
      3501453.07     10411659.61      3501591.93     10411786.54
#Sta/Elev= 30
  4747.7  427.42  4854.9  424.60  4876.2  423.12  4895.2  422.40  4923.8  420.68
  4933.9  419.75  4954.2  416.98  4968.7  416.18  4974.4  416.47  4992.6  415.08
  4992.9  414.58  4996.4  414.58  4996.6  415.08  5004.8  416.29  5012.4  416.38
  5018.2  416.37  5036.6  416.81  5045.2  417.60  5065.5  420.38  5085.7  422.17
  5106.0  423.26  5153.4  424.88  5181.8  425.01  5210.1  423.91  5216.9  424.19
  5231.1  426.45  5245.3  427.19  5266.2  427.40  5273.6  427.94  5305.2  428.89
#Mann=5,-1,0
  4747.7    0.05       0  4992.6   0.035       0  4996.6    0.05       0
  5012.4    0.16       0  5018.2     0.1       0
Bank Sta=4992.6,4996.6
Exp/Cntr=0.3,0.1

Type RM Length L Ch R = 1,1969,501,501,501
BEGIN DESCRIPTION:
DOGWOOD CR WEST TRIB 4 6 0
END DESCRIPTION:
XS GIS Cut Line= 5
      3500816.60     10411608.20      3500921.82     10411719.77
      3501083.86     10411892.50      3501333.27     10412032.27
      3501680.02     10412076.79
#Sta/Elev= 30
  4609.8  432.19  4767.0  427.08  4842.6  422.90  4863.6  422.80  4934.4  420.50
  4943.1  419.42  4948.6  418.94  4955.9  417.07  4962.7  416.66  4970.0  415.05
  4976.9  415.24  4984.2  413.28  4991.0  409.65  4994.0  408.79  4994.2  408.29
  4997.7  408.29  4998.0  408.79  5011.8  409.54  5020.9  412.27  5027.8  413.20
  5065.4  412.90  5102.0  414.49  5130.5  417.59  5152.2  418.48  5189.8  421.49
  5315.0  425.58  5516.6  431.15  5536.8  432.38  5577.1  433.47  5635.5  436.04
#Mann=5,-1,0
  4609.8     0.1       0  4943.1    0.16       0  4994.0    0.07       0
  4998.0    0.16       0  5102.0     0.1       0
Bank Sta=4994,4998
Exp/Cntr=0.3,0.1

Type RM Length L Ch R = 1,1468,520,520,520
BEGIN DESCRIPTION:
DOGWOOD CR WEST TRIB 4 4 0
END DESCRIPTION:
XS GIS Cut Line= 3
      3500714.52     10412188.24      3500948.94     10412293.72
      3501357.47     10412252.09
#Sta/Elev= 30
  4785.9  424.13  4883.5  419.31  4901.1  417.62  4906.6  417.76  4914.5  416.52
  4924.3  415.01  4929.8  415.27  4947.4  411.48  4958.7  409.92  4969.7  409.74
  4981.5  408.53  4989.6  405.79  4989.9  405.29  4993.4  405.29  4993.6  405.79
  4999.2  405.93  5013.5  409.83  5035.5  410.15  5056.2  409.25  5106.5  411.44
  5196.9  416.82  5217.0  417.25  5221.8  418.12  5227.1  419.08  5347.7  421.97
  5377.8  424.32  5418.1  424.72  5428.1  425.27  5438.2  426.88  5453.6  427.68
#Mann=5,-1,0
  4785.9     0.1       0  4914.5    0.12       0  4989.6    0.07       0
  4993.6    0.12       0  5221.8     0.1       0
Bank Sta=4989.6,4993.6
Exp/Cntr=0.3,0.1

Type RM Length L Ch R = 1,948,314,314,314
BEGIN DESCRIPTION:
DOGWOOD CR WEST TRIB 4 2 2
END DESCRIPTION:
XS GIS Cut Line= 2
      3500682.01     10412625.76      3501157.21     10412718.19
#Sta/Elev= 30
  4750.3  418.53  4752.6  418.53  4760.6  417.36  4770.8  417.06  4801.3  415.05
  4806.9  414.25  4852.3  411.48  4863.6  410.17  4886.3  405.24  4893.0  404.18
  4974.5  404.60  4992.9  402.01  4993.1  401.51  4996.6  401.51  4996.9  402.01
  5013.5  404.11  5018.6  404.28  5056.0  404.46  5086.6  404.05  5096.8  404.93
  5116.8  408.61  5121.9  407.74  5127.3  409.57  5168.1  412.48  5173.5  413.28
  5178.6  413.26  5188.5  414.08  5198.6  415.16  5225.2  419.59  5234.4  419.59
#Mann=4,-1,0
  4750.3     0.1       0  4886.3    0.12       0  4992.9    0.07       0
  4996.9    0.12       0
Bank Sta=4992.9,4996.9
Exp/Cntr=0.3,0.1

Type RM Length L Ch R = 1,634,135,135,135
BEGIN DESCRIPTION:
DOGWOOD CR WEST TRIB 4 5 0
END DESCRIPTION:
XS GIS Cut Line= 2
      3500637.37     10412758.99      3501203.73     10413043.26
#Sta/Elev= 30
  4675.6  418.09  4756.6  413.99  4806.8  410.62  4837.5  407.72  4845.9  406.72
  4851.5  405.31  4866.3  404.33  4873.8  402.73  4957.6  402.86  4985.5  402.34
  4994.2  401.91  5000.3  400.77  5000.5  400.27  5004.0  400.27  5004.3  400.77
  5016.6  402.22  5038.9  403.07  5052.5  406.15  5061.3  406.99  5083.1  407.86
  5191.5  412.04  5218.0  413.04  5225.6  413.97  5231.2  413.64  5240.3  414.09
  5248.0  414.94  5275.9  415.56  5292.6  416.71  5299.9  416.53  5309.3  416.85
#Mann=7,-1,0
  4675.6     0.1       0  4866.3    0.12       0  5000.3    0.07       0
  5004.3    0.12       0  5083.1    0.16       0  5191.5     0.1       0
  5299.9    0.16       0
Bank Sta=5000.3,5004.3
Exp/Cntr=0.3,0.1

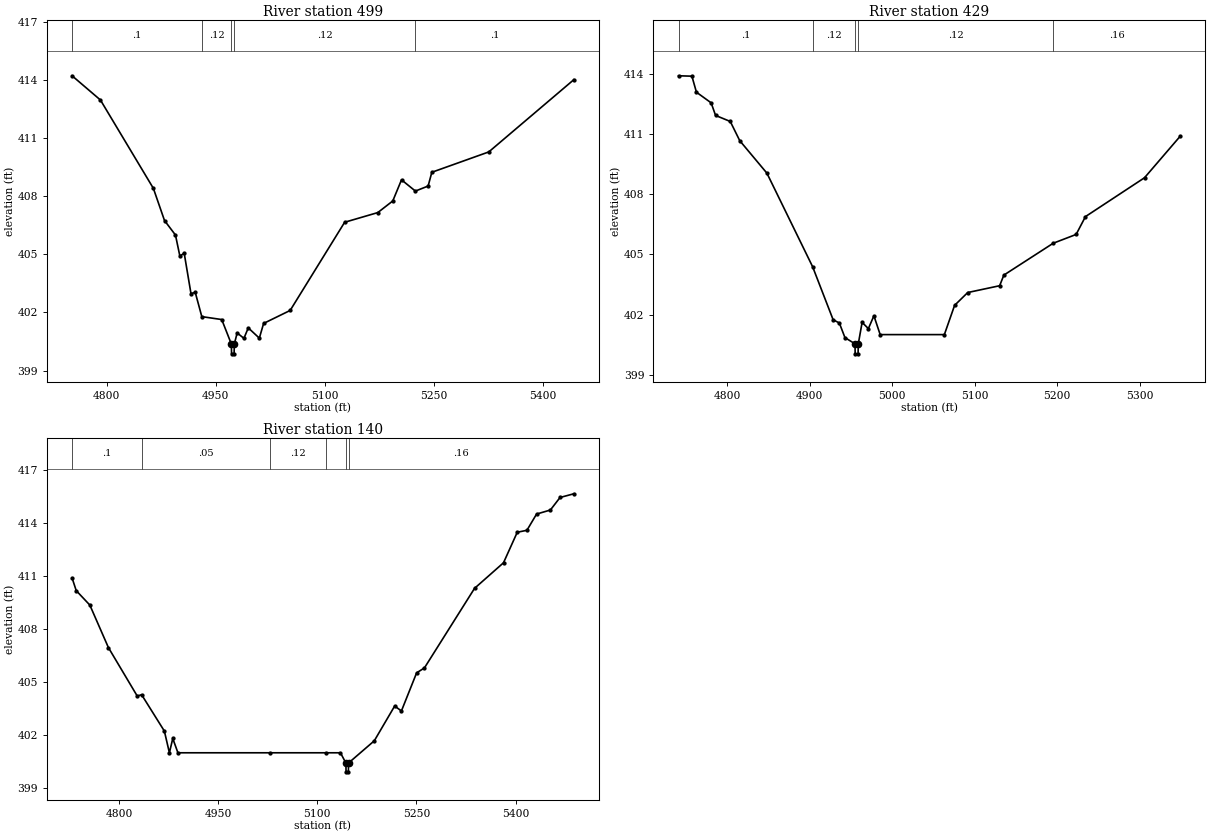
Type RM Length L Ch R = 1,499,70,70,70
BEGIN DESCRIPTION:
DOGWOOD CR WEST TRIB 4 3 1
END DESCRIPTION:
XS GIS Cut Line= 3
      3500652.09     10412877.07      3500969.78     10413078.88
      3501044.00     10413383.61
#Sta/Elev= 30
  4752.6  414.21  4791.6  412.96  4864.4  408.40  4879.7  406.74  4894.8  405.99
  4900.8  404.91  4906.8  405.05  4916.1  402.97  4922.0  403.03  4931.0  401.78
  4958.4  401.63  4971.7  400.36  4971.9  399.86  4975.4  399.86  4975.7  400.36
  4979.6  400.94  4988.9  400.66  4994.9  401.20  5010.1  400.67  5016.0  401.43
  5052.5  402.10  5127.4  406.65  5173.0  407.15  5193.6  407.75  5205.6  408.84
  5224.7  408.26  5242.2  408.52  5247.3  409.23  5325.6  410.28  5442.6  414.01
#Mann=5,-1,0
  4752.6     0.1       0  4931.0    0.12       0  4971.7    0.07       0
  4975.7    0.12       0  5224.7     0.1       0
Bank Sta=4971.7,4975.7
Exp/Cntr=0.3,0.1

Type RM Length L Ch R = 1,429,289,289,289
BEGIN DESCRIPTION:
DOGWOOD CR WEST TRIB 4 3 0
END DESCRIPTION:
XS GIS Cut Line= 4
      3500614.30     10412929.14      3500757.54     10412992.94
      3500874.72     10413127.06      3500933.32     10413393.99
#Sta/Elev= 30
  4741.2  413.92  4757.4  413.90  4762.9  413.10  4780.7  412.57  4786.1  411.94
  4803.9  411.64  4815.4  410.68  4848.3  409.06  4903.7  404.39  4928.6  401.74
  4936.1  401.58  4942.9  400.85  4955.1  400.54  4955.3  400.04  4958.8  400.04
  4959.1  400.54  4963.7  401.61  4971.3  401.30  4978.0  401.94  4985.6  401.00
  5063.4  401.00  5075.8  402.46  5091.7  403.10  5130.4  403.44  5135.5  403.97
  5195.3  405.56  5223.1  406.00  5234.4  406.89  5306.0  408.83  5349.4  410.91
#Mann=5,-1,0
  4741.2     0.1       0  4903.7    0.12       0  4955.1    0.07       0
  4959.1    0.12       0  5195.3    0.16       0
Bank Sta=4955.1,4959.1
Exp/Cntr=0.3,0.1

Type RM Length L Ch R = 1,140,0,0,0
BEGIN DESCRIPTION:
DOGWOOD CR WEST TRIB 4 1 0
END DESCRIPTION:
XS GIS Cut Line= 3
      3500554.63     10412985.40      3500669.21     10413501.02
      3500854.08     10413639.03
#Sta/Elev= 30
  4729.2  410.91  4735.5  410.19  4756.1  409.37  4784.2  406.96  4827.7  404.22
  4834.4  404.29  4868.8  402.23  4876.4  401.00  4881.5  401.81  4889.3  401.00
  5028.0  401.00  5113.9  401.00  5135.1  401.00  5143.3  400.42  5143.6  399.92
  5147.1  399.92  5147.3  400.42  5186.3  401.68  5217.1  403.65  5227.3  403.37
  5250.3  405.53  5262.1  405.81  5337.9  410.32  5381.7  411.77  5402.5  413.50
  5417.1  413.61  5431.7  414.53  5452.6  414.76  5467.2  415.47  5488.1  415.68
#Mann=6,-1,0
  4729.2     0.1       0  4834.4    0.05       0  5028.0    0.12       0
  5113.9    0.16       0  5143.3   0.033       0  5147.3    0.16       0
Bank Sta=5143.3,5147.3
Exp/Cntr=0.3,0.1

Chan Stop Cuts=-1