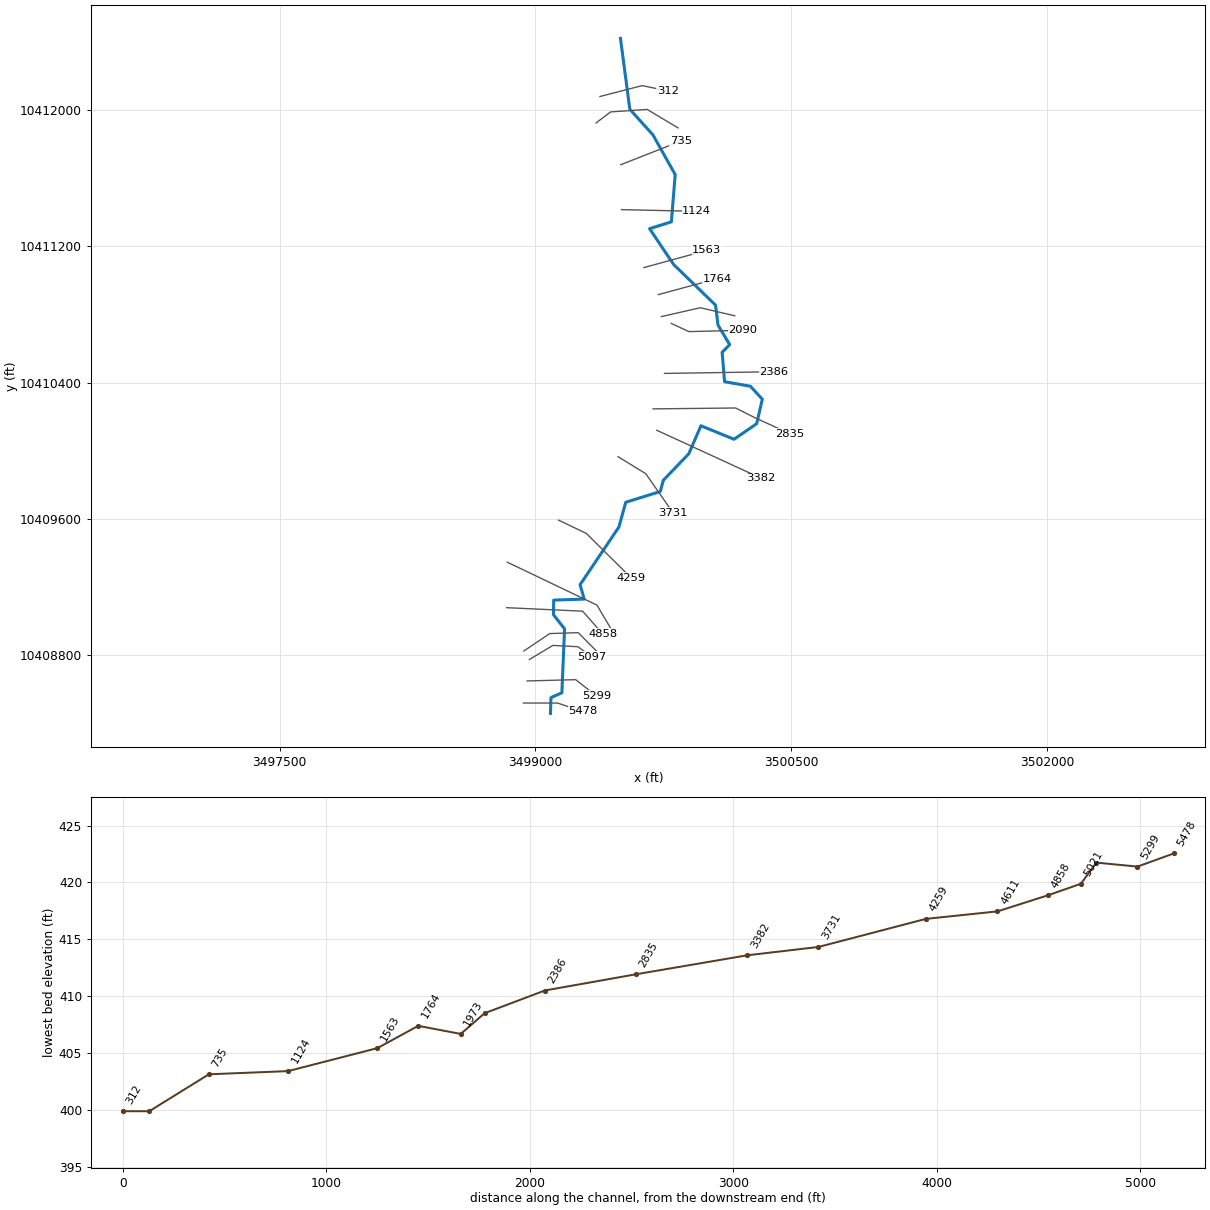
--- DOGWOOD CR WEST TRIB 5.prj (project) ---

Proj Title=DOGWOOD CR WEST TRIB 5 Base Level Engineering
Current Plan=p01
Default Exp/Contr=0.3,0.1
English Units
Geom File=g01
Flow File=f01
Plan File=p01
Y Axis Title=Elevation
X Axis Title(PF)=Main Channel Distance
X Axis Title(XS)=Station
BEGIN DESCRIPTION:
DOGWOOD CR WEST TRIB 5
END DESCRIPTION:
DSS Export Rating Curves= 0
DSS Export Rating Curve Sorted= 0
DSS Export Volume Flow Curves= 0
DXF OffsetX= 0
DXF OffsetY= 0
DXF ScaleX= 1
DXF ScaleY= 10

--- DOGWOOD CR WEST TRIB 5.p01 (plan) ---

Plan Title=Multiple Run
Short Identifier=Multiple
Geom File=g01
Flow File=f01
Subcritical Flow
K Sum by GR= 0
Std Step Tol= 0.01
Critical Tol= 0.01
Num of Std Step Trials= 20
Max Error Tol= 0.3
Flow Tol Ratio= 0.001
Split Flow NTrial= 30
Split Flow Tol= 0.02
Split Flow Ratio= 0.02
Log Output Level= 0
Friction Slope Method= 1
Unsteady Friction Slope Method= 2
Unsteady Bridges Friction Slope Method= 1
Parabolic Critical Depth
Global Vel Dist=  1 , 1 , 1
Global Log Level= 0
CheckData=True
Encroach Param= -1, 0, 0, 0
BEGIN DESCRIPTION:
Multiple Run
END DESCRIPTION:

--- DOGWOOD CR WEST TRIB 5.f01 (steady flow) ---

Flow Title=Multiple
Number of Profiles=7
Profile Names=10-year,25-year,50-year,1pct_min,100-year,1pct_plu,500-year
River Rch & RM= DOGWOOD CR WEST ,Reach-1,5478
     842    1154    1410    1259    1702    2302    2474
Boundary for River Rch & Prof#=DOGWOOD CR WEST ,Reach-1,1
Up Type=0
Dn Type=3
Dn Slope=0.005
Boundary for River Rch & Prof#=DOGWOOD CR WEST ,Reach-1,2
Up Type=0
Dn Type=3
Dn Slope=0.005
Boundary for River Rch & Prof#=DOGWOOD CR WEST ,Reach-1,3
Up Type=0
Dn Type=3
Dn Slope=0.005
Boundary for River Rch & Prof#=DOGWOOD CR WEST ,Reach-1,4
Up Type=0
Dn Type=3
Dn Slope=0.005
Boundary for River Rch & Prof#=DOGWOOD CR WEST ,Reach-1,5
Up Type=0
Dn Type=3
Dn Slope=0.005
Boundary for River Rch & Prof#=DOGWOOD CR WEST ,Reach-1,6
Up Type=0
Dn Type=3
Dn Slope=0.005
Boundary for River Rch & Prof#=DOGWOOD CR WEST ,Reach-1,7
Up Type=0
Dn Type=3
Dn Slope=0.005

--- DOGWOOD CR WEST TRIB 5.g01 (geometry) ---

Geom Title=Existing Conditions

River Reach=DOGWOOD CR WEST ,Reach-1
Reach XY= 30
      3499088.45     10408460.25      3499091.35     10408552.53
      3499155.41     10408581.18      3499171.25     10408955.76
      3499106.27     10409038.74      3499107.42     10409124.43
      3499286.39     10409130.39      3499262.24     10409214.90
      3499489.62     10409552.67      3499530.03     10409698.19
      3499732.45     10409761.25      3499750.38     10409827.29
      3499899.69     10409982.64      3499970.75     10410146.77
      3500164.89     10410067.76      3500297.54     10410158.60
      3500330.94     10410302.30      3500260.85     10410378.61
      3500109.54     10410405.03      3500095.25     10410577.66
      3500139.52     10410622.36      3500070.94     10410737.38
      3500056.45     10410854.29      3499810.39     10411092.90
      3499669.68     10411302.54      3499797.54     10411342.64
      3499819.99     10411619.80      3499688.74     10411853.48
      3499554.02     10412002.43      3499498.94     10412418.67

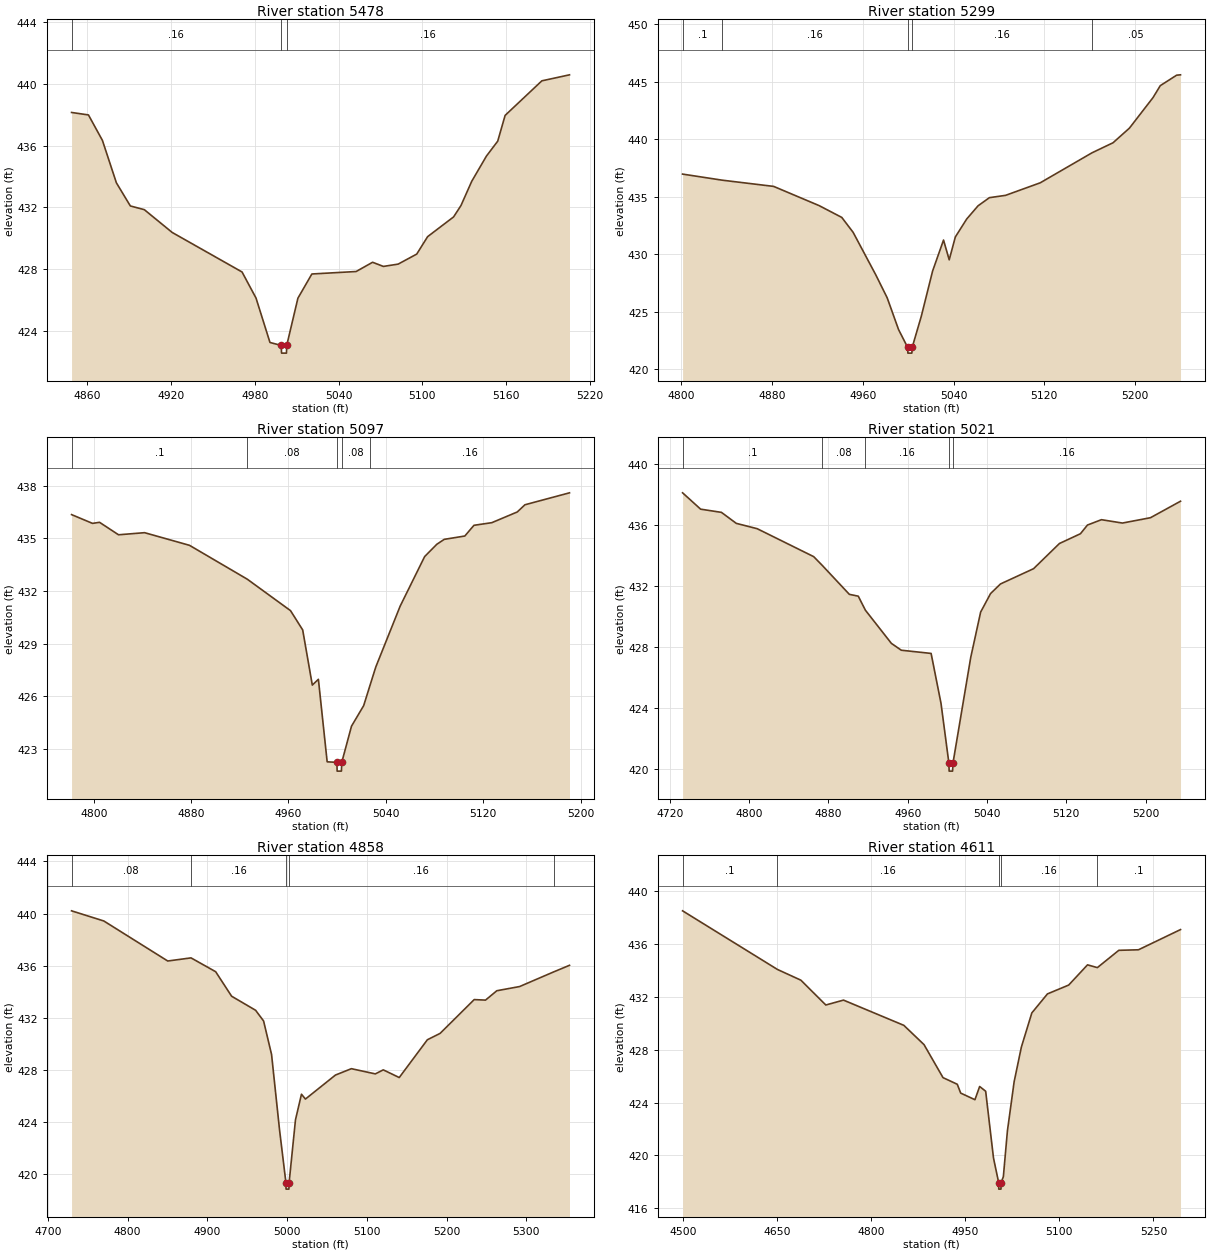
Type RM Length L Ch R = 1,5478,179,179,179
BEGIN DESCRIPTION:
DOGWOOD CR TRIB 5 2 1
END DESCRIPTION:
XS GIS Cut Line= 3
      3498929.97     10408520.81      3499129.95     10408520.81
      3499278.53     10408471.28
#Sta/Elev= 30
  4848.8  438.15  4860.9  437.99  4870.9  436.34  4880.9  433.59  4890.9  432.09
  4900.9  431.85  4920.9  430.37  4970.9  427.81  4980.9  426.12  4990.9  423.24
  4998.9  423.05  4999.2  422.55  5002.7  422.55  5002.9  423.05  5010.9  426.11
  5020.9  427.68  5052.6  427.84  5064.4  428.44  5072.1  428.17  5082.7  428.32
  5096.0  428.97  5103.8  430.10  5122.4  431.38  5127.7  432.12  5135.4  433.69
  5145.9  435.32  5154.0  436.29  5159.3  437.96  5185.6  440.20  5205.4  440.59
#Mann=3,-1,0
  4848.8    0.16       0  4998.9    0.07       0  5002.9    0.16       0
Bank Sta=4998.9,5002.9
Exp/Cntr=0.3,0.1

Type RM Length L Ch R = 1,5299,202,202,202
BEGIN DESCRIPTION:
DOGWOOD CR TRIB 5 10 4
END DESCRIPTION:
XS GIS Cut Line= 3
      3498951.98     10408650.38      3499236.28     10408657.98
      3499357.45     10408562.77
#Sta/Elev= 30
  4801.4  436.97  4836.4  436.44  4881.6  435.90  4921.6  434.23  4941.6  433.20
  4951.6  431.90  4971.6  428.19  4981.6  426.20  4991.6  423.44  4999.6  421.89
  4999.8  421.39  5003.3  421.39  5003.6  421.89  5011.6  424.59  5021.6  428.54
  5031.2  431.23  5036.2  429.51  5041.6  431.50  5051.6  433.06  5061.6  434.21
  5071.6  434.92  5085.8  435.12  5116.3  436.21  5161.9  438.82  5180.5  439.70
  5194.9  440.97  5215.7  443.63  5222.1  444.67  5236.5  445.58  5239.9  445.61
#Mann=5,-1,0
  4801.4     0.1       0  4836.4    0.16       0  4999.6    0.07       0
  5003.6    0.16       0  5161.9    0.05       0
Bank Sta=4999.6,5003.6
Exp/Cntr=0.3,0.1

Type RM Length L Ch R = 1,5097,76,76,76
BEGIN DESCRIPTION:
DOGWOOD CR TRIB 5 10 3
END DESCRIPTION:
XS GIS Cut Line= 4
      3498965.00     10408776.24      3499102.82     10408858.72
      3499249.31     10408851.12      3499331.78     10408791.43
#Sta/Elev= 30
  4781.8  436.35  4799.0  435.85  4804.8  435.91  4820.4  435.20  4841.8  435.32
  4878.7  434.60  4926.2  432.67  4961.7  430.88  4971.7  429.78  4979.6  426.64
  4984.6  426.97  4991.8  422.27  4999.8  422.24  5000.0  421.74  5003.5  421.74
  5003.8  422.24  5011.8  424.30  5021.8  425.47  5027.3  426.69  5031.8  427.68
  5051.8  431.14  5071.9  433.96  5081.9  434.66  5088.0  434.94  5104.9  435.13
  5112.4  435.74  5127.1  435.89  5148.0  436.50  5154.3  436.91  5190.9  437.59
#Mann=5,-1,0
  4781.8     0.1       0  4926.2    0.08       0  4999.8    0.07       0
  5003.8    0.08       0  5027.3    0.16       0
Bank Sta=4999.8,5003.8
Exp/Cntr=0.3,0.1

Type RM Length L Ch R = 1,5021,163,163,163
BEGIN DESCRIPTION:
DOGWOOD CR TRIB 5 12 0
END DESCRIPTION:
XS GIS Cut Line= 4
      3498932.45     10408826.16      3499084.37     10408928.16
      3499251.48     10408933.59      3499358.64     10408825.35
#Sta/Elev= 30
  4732.8  438.11  4751.0  437.04  4772.0  436.83  4787.0  436.11  4808.1  435.76
  4865.1  433.93  4873.7  433.36  4901.1  431.46  4910.1  431.34  4917.3  430.42
  4943.5  428.25  4953.5  427.80  4983.6  427.59  4993.6  424.32  5001.6  420.38
  5001.8  419.88  5005.3  419.88  5005.6  420.38  5023.6  427.33  5033.6  430.30
  5043.6  431.51  5053.6  432.14  5087.0  433.14  5113.1  434.79  5134.3  435.43
  5141.4  436.00  5155.5  436.35  5176.7  436.13  5205.0  436.48  5235.3  437.56
#Mann=5,-1,0
  4732.8     0.1       0  4873.7    0.08       0  4917.3    0.16       0
  5001.6    0.07       0  5005.6    0.16       0
Bank Sta=5001.6,5005.6
Exp/Cntr=0.3,0.1

Type RM Length L Ch R = 1,4858,247,247,247
BEGIN DESCRIPTION:
DOGWOOD CR TRIB 5 13 0
END DESCRIPTION:
XS GIS Cut Line= 3
      3498831.60     10409080.07      3499277.52     10409059.45
      3499395.04     10408925.76
#Sta/Elev= 30
  4729.8  440.21  4770.3  439.43  4850.4  436.36  4879.6  436.60  4910.5  435.54
  4930.5  433.66  4960.6  432.58  4970.6  431.76  4980.6  429.19  4990.6  423.41
  4998.6  419.36  4998.8  418.86  5002.3  418.86  5002.6  419.36  5010.6  424.18
  5018.1  426.14  5023.1  425.77  5060.7  427.61  5080.7  428.10  5110.7  427.70
  5120.7  428.01  5140.7  427.42  5176.0  430.32  5192.0  430.81  5234.7  433.40
  5248.9  433.36  5263.1  434.08  5291.6  434.40  5334.2  435.52  5354.2  436.03
#Mann=5,-1,0
  4729.8    0.08       0  4879.6    0.16       0  4998.6    0.07       0
  5002.6    0.16       0  5334.2     0.1       0
Bank Sta=4998.6,5002.6
Exp/Cntr=0.3,0.1

Type RM Length L Ch R = 1,4611,352,352,352
BEGIN DESCRIPTION:
DOGWOOD CR TRIB 5 10 2
END DESCRIPTION:
XS GIS Cut Line= 3
      3498834.82     10409346.99      3499361.07     10409095.26
      3499468.49     10408914.06
#Sta/Elev= 30
  4499.1  438.52  4650.4  434.08  4687.7  433.27  4727.5  431.39  4755.7  431.76
  4851.9  429.85  4884.1  428.39  4914.4  425.89  4937.1  425.39  4942.6  424.72
  4965.3  424.22  4972.8  425.22  4982.4  424.86  4994.9  419.80  5003.1  417.95
  5003.3  417.45  5006.8  417.45  5007.1  417.95  5010.6  418.39  5017.1  421.87
  5027.8  425.58  5039.3  428.20  5056.0  430.79  5080.9  432.23  5114.8  432.90
  5144.8  434.43  5160.5  434.22  5194.7  435.53  5226.0  435.57  5293.1  437.10
#Mann=5,-1,0
  4499.1     0.1       0  4650.4    0.16       0  5003.1    0.07       0
  5007.1    0.16       0  5160.5     0.1       0
Bank Sta=5003.1,5007.1
Exp/Cntr=0.3,0.1

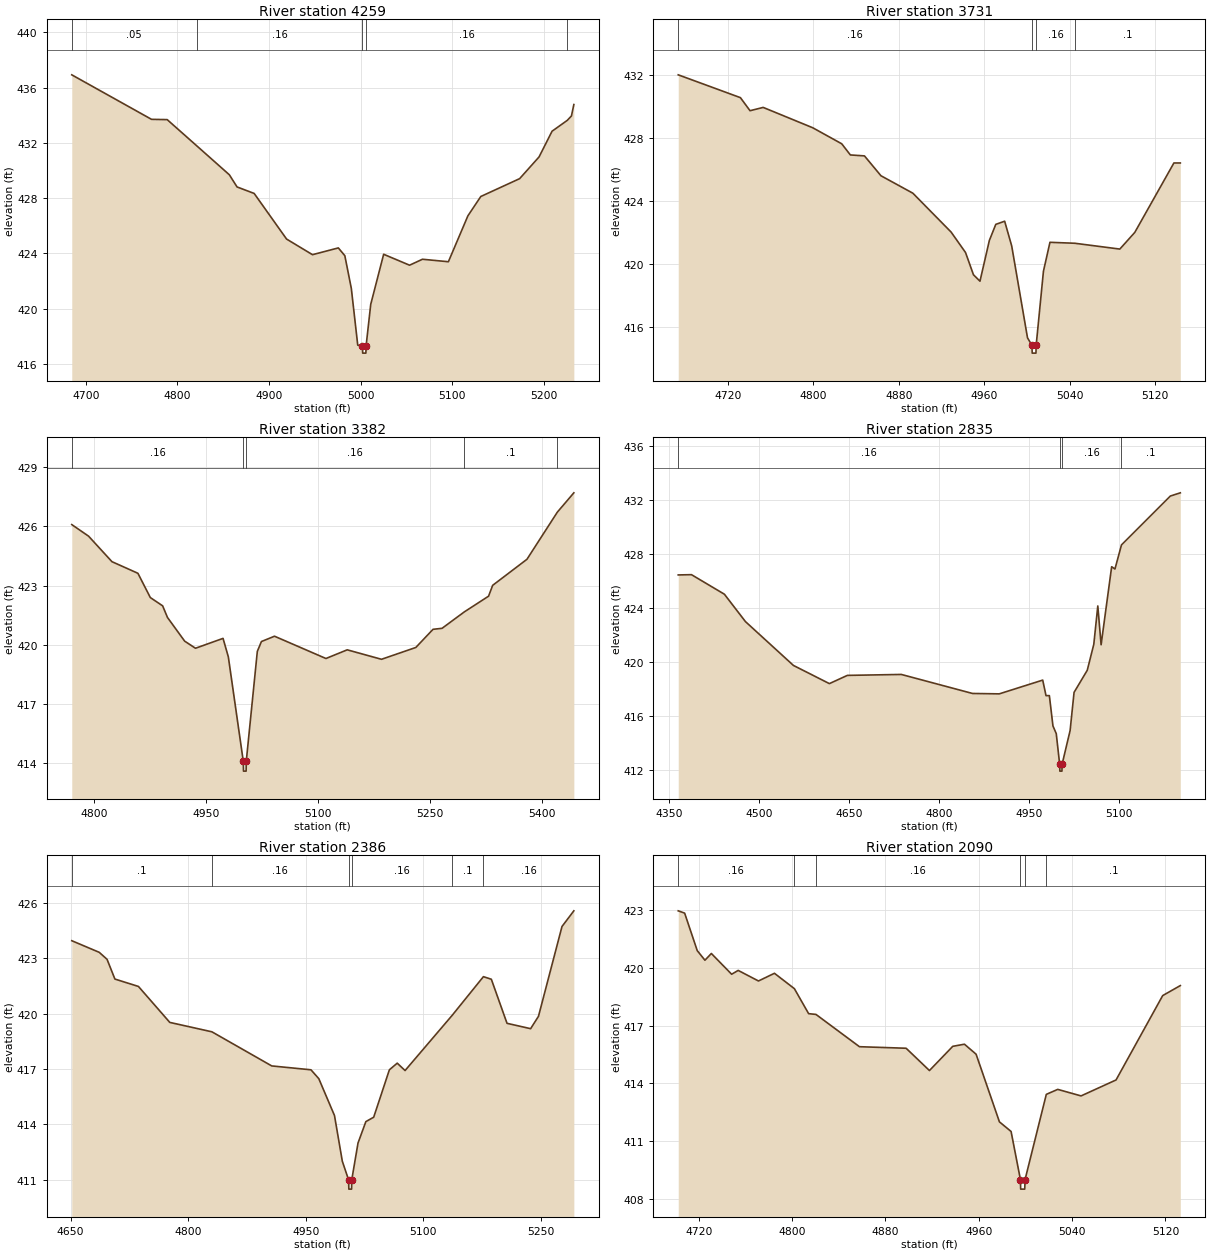
Type RM Length L Ch R = 1,4259,528,528,528
BEGIN DESCRIPTION:
DOGWOOD CR TRIB 5 11 0
END DESCRIPTION:
XS GIS Cut Line= 3
      3499136.47     10409593.31      3499299.22     10409515.18
      3499560.35     10409256.22
#Sta/Elev= 30
  4684.6  436.92  4771.7  433.70  4788.8  433.68  4821.0  431.79  4856.7  429.69
  4865.1  428.81  4883.8  428.34  4919.2  425.04  4947.5  423.91  4975.7  424.40
  4982.8  423.84  4989.9  421.47  4996.9  417.37  5002.0  417.29  5002.3  416.79
  5005.8  416.79  5006.0  417.29  5011.1  420.32  5025.2  423.94  5053.5  423.15
  5067.6  423.58  5095.9  423.40  5117.2  426.72  5131.3  428.12  5173.7  429.41
  5194.9  430.98  5209.1  432.84  5225.8  433.63  5230.3  433.95  5232.9  434.77
#Mann=5,-1,0
  4684.6    0.05       0  4821.0    0.16       0  5002.0    0.07       0
  5006.0    0.16       0  5225.8     0.1       0
Bank Sta=5002,5006
Exp/Cntr=0.3,0.1

Type RM Length L Ch R = 1,3731,349,349,349
BEGIN DESCRIPTION:
DOGWOOD CR TRIB 5 10 0
END DESCRIPTION:
XS GIS Cut Line= 3
      3499484.81     10409965.46      3499647.53     10409865.66
      3499807.02     10409636.73
#Sta/Elev= 30
  4673.6  432.00  4731.8  430.55  4740.8  429.72  4753.1  429.93  4799.4  428.64
  4826.6  427.62  4834.7  426.91  4847.9  426.85  4863.3  425.59  4893.2  424.48
  4929.0  422.01  4942.5  420.71  4949.9  419.30  4956.0  418.89  4964.8  421.48
  4970.8  422.50  4979.1  422.70  4985.7  421.13  5000.5  415.29  5004.6  414.82
  5004.9  414.32  5008.4  414.32  5008.6  414.82  5015.4  419.52  5021.5  421.36
  5044.7  421.30  5086.9  420.93  5100.9  421.99  5137.5  426.40  5143.5  426.40
#Mann=4,-1,0
  4673.6    0.16       0  5004.6    0.07       0  5008.6    0.16       0
  5044.7     0.1       0
Bank Sta=5004.6,5008.6
Exp/Cntr=0.3,0.1

Type RM Length L Ch R = 1,3382,547,547,547
BEGIN DESCRIPTION:
DOGWOOD CR TRIB 5 9 0
END DESCRIPTION:
XS GIS Cut Line= 2
      3499711.58     10410120.64      3500322.44     10409839.62
#Sta/Elev= 30
  4770.5  426.09  4793.1  425.50  4824.3  424.21  4859.1  423.62  4875.7  422.39
  4892.2  421.97  4898.7  421.38  4921.7  420.18  4936.2  419.82  4973.1  420.32
  4980.2  419.38  5000.2  414.09  5000.5  413.59  5004.0  413.59  5004.2  414.09
  5019.0  419.66  5024.5  420.16  5042.0  420.43  5110.9  419.30  5139.4  419.74
  5185.3  419.26  5231.3  419.86  5254.3  420.78  5266.4  420.83  5296.1  421.66
  5328.7  422.46  5334.2  423.01  5380.1  424.33  5420.8  426.72  5442.9  427.70
#Mann=5,-1,0
  4770.5    0.16       0  5000.2    0.07       0  5004.2    0.16       0
  5296.1     0.1       0  5420.8    0.05       0
Bank Sta=5000.2,5004.2
Exp/Cntr=0.3,0.1

Type RM Length L Ch R = 1,2835,449,449,449
BEGIN DESCRIPTION:
DOGWOOD CR TRIB 5 8 0
END DESCRIPTION:
XS GIS Cut Line= 4
      3499690.02     10410245.82      3500174.42     10410251.02
      3500292.11     10410191.64      3500493.51     10410100.29
#Sta/Elev= 30
  4364.6  426.47  4386.7  426.49  4441.6  425.04  4476.7  423.01  4556.7  419.76
  4616.7  418.41  4646.7  419.02  4736.7  419.09  4855.4  417.68  4900.0  417.65
  4972.5  418.67  4978.0  417.52  4983.6  417.52  4989.6  415.27  4995.1  414.70
  5000.8  412.42  5001.1  411.92  5004.6  411.92  5004.8  412.42  5018.2  414.93
  5024.8  417.76  5046.8  419.40  5057.7  421.32  5064.4  424.17  5069.9  421.29
  5087.5  427.08  5093.0  426.91  5103.9  428.70  5185.3  432.32  5202.0  432.56
#Mann=4,-1,0
  4364.6    0.16       0  5000.8    0.07       0  5004.8    0.16       0
  5103.9     0.1       0
Bank Sta=5000.8,5004.8
Exp/Cntr=0.3,0.1

Type RM Length L Ch R = 1,2386,296,296,296
BEGIN DESCRIPTION:
DOGWOOD CR TRIB 5 5 1
END DESCRIPTION:
XS GIS Cut Line= 2
      3499757.12     10410453.77      3500397.25     10410463.53
#Sta/Elev= 30
  4651.6  423.96  4686.6  423.33  4696.6  422.95  4706.6  421.88  4736.6  421.48
  4776.6  419.53  4830.3  419.02  4906.6  417.17  4956.6  416.96  4966.6  416.48
  4986.6  414.48  4996.6  412.00  5004.6  410.99  5004.9  410.49  5008.4  410.49
  5008.6  410.99  5016.6  412.99  5026.6  414.15  5036.6  414.39  5056.6  416.96
  5066.6  417.32  5076.6  416.92  5136.6  419.91  5176.5  422.01  5186.6  421.87
  5206.6  419.48  5236.7  419.19  5246.7  419.86  5276.7  424.73  5291.8  425.58
#Mann=6,-1,0
  4651.6     0.1       0  4830.3    0.16       0  5004.6    0.07       0
  5008.6    0.16       0  5136.6     0.1       0  5176.5    0.16       0
Bank Sta=5004.6,5008.6
Exp/Cntr=0.3,0.1

Type RM Length L Ch R = 1,2090,117,117,117
BEGIN DESCRIPTION:
DOGWOOD CR TRIB 5 7 0
END DESCRIPTION:
XS GIS Cut Line= 3
      3499797.28     10410746.73      3499900.35     10410698.99
      3500217.17     10410706.59
#Sta/Elev= 30
  4702.3  422.97  4707.8  422.85  4718.6  420.90  4725.2  420.40  4730.7  420.75
  4748.1  419.67  4753.7  419.87  4771.1  419.32  4784.8  419.72  4801.9  418.92
  4814.1  417.62  4820.4  417.58  4857.7  415.90  4897.7  415.82  4917.7  414.66
  4937.7  415.92  4947.7  416.03  4957.7  415.51  4977.7  411.99  4987.7  411.49
  4995.7  408.99  4995.9  408.49  4999.4  408.49  4999.7  408.99  5017.9  413.42
  5027.7  413.68  5047.7  413.34  5077.7  414.17  5117.7  418.56  5132.8  419.08
#Mann=6,-1,0
  4702.3    0.16       0  4801.9     0.1       0  4820.4    0.16       0
  4995.7    0.07       0  4999.7    0.16       0  5017.9     0.1       0
Bank Sta=4995.7,4999.7
Exp/Cntr=0.3,0.1

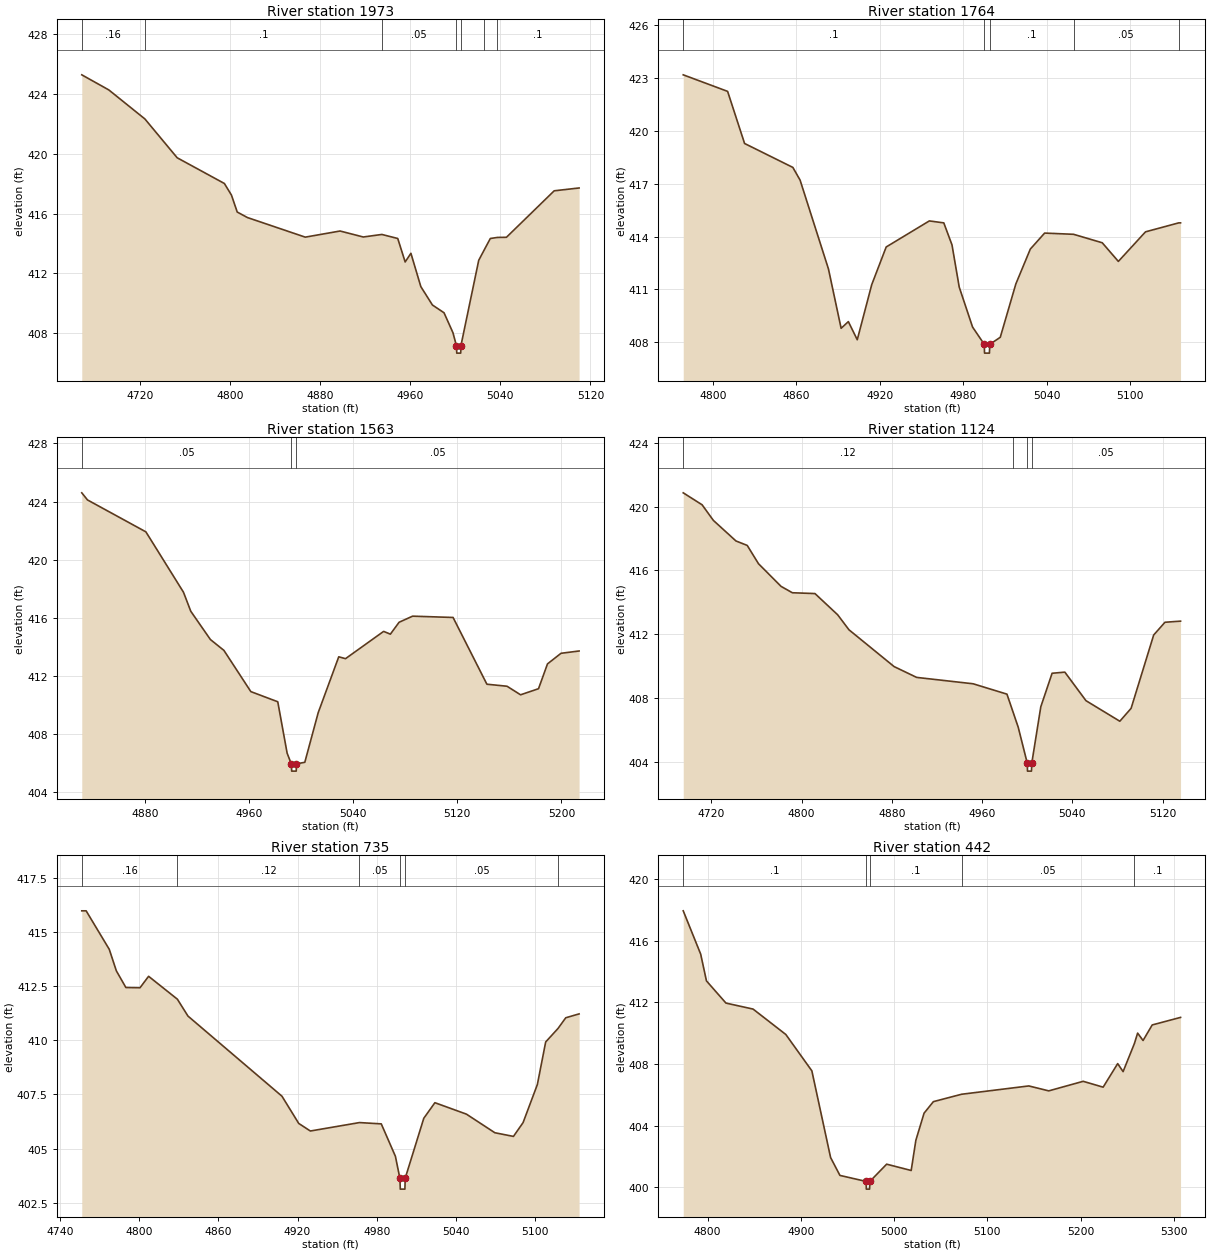
Type RM Length L Ch R = 1,1973,209,209,209
BEGIN DESCRIPTION:
DOGWOOD CR TRIB 5 4 1
END DESCRIPTION:
XS GIS Cut Line= 3
      3499738.69     10410786.89      3499967.62     10410838.97
      3500168.85     10410791.62
#Sta/Elev= 30
  4668.4  425.29  4692.4  424.28  4724.4  422.34  4753.1  419.74  4795.0  418.02
  4801.3  417.24  4806.4  416.11  4815.5  415.74  4866.8  414.43  4897.7  414.84
  4918.3  414.44  4934.8  414.61  4948.9  414.34  4955.5  412.77  4960.6  413.35
  4969.4  411.12  4979.7  409.89  4990.0  409.37  4997.9  408.04  5001.0  407.17
  5001.3  406.67  5004.8  406.67  5005.0  407.17  5020.8  412.88  5025.5  413.55
  5031.1  414.34  5037.3  414.41  5045.4  414.42  5087.8  417.53  5109.9  417.72
#Mann=7,-1,0
  4668.4    0.16       0  4724.4     0.1       0  4934.8    0.05       0
  5001.0    0.03       0  5005.0    0.05       0  5025.5    0.16       0
  5037.3     0.1       0
Bank Sta=5001,5005
Exp/Cntr=0.3,0.1

Type RM Length L Ch R = 1,1764,201,201,201
BEGIN DESCRIPTION:
DOGWOOD CR TRIB 5 6 0
END DESCRIPTION:
XS GIS Cut Line= 2
      3499721.30     10410916.01      3500066.41     10411009.34
#Sta/Elev= 30
  4778.8  423.19  4810.7  422.25  4822.9  419.29  4857.6  417.93  4862.8  417.21
  4883.2  412.16  4892.3  408.79  4897.5  409.17  4903.9  408.14  4914.3  411.27
  4924.7  413.41  4955.7  414.89  4966.1  414.78  4972.0  413.53  4977.2  411.13
  4986.8  408.86  4995.2  407.88  4995.4  407.38  4998.9  407.38  4999.2  407.88
  5006.7  408.28  5017.9  411.31  5028.3  413.29  5038.6  414.20  5059.4  414.13
  5080.0  413.65  5091.6  412.59  5111.1  414.27  5135.0  414.78  5136.3  414.78
#Mann=5,-1,0
  4778.8     0.1       0  4995.2    0.07       0  4999.2     0.1       0
  5059.4    0.05       0  5135.0     0.1       0
Bank Sta=4995.2,4999.2
Exp/Cntr=0.3,0.1

Type RM Length L Ch R = 1,1563,439,439,439
BEGIN DESCRIPTION:
DOGWOOD CR TRIB 5 3 2
END DESCRIPTION:
XS GIS Cut Line= 2
      3499636.71     10411074.44      3500005.56     10411175.33
#Sta/Elev= 30
  4831.2  424.60  4835.6  424.11  4880.5  421.91  4909.4  417.75  4915.0  416.44
  4930.1  414.49  4940.5  413.74  4961.2  410.90  4981.9  410.20  4989.1  406.66
  4992.3  405.92  4992.6  405.42  4996.1  405.42  4996.3  405.92  5002.7  406.03
  5013.0  409.45  5028.8  413.30  5034.0  413.17  5063.3  415.05  5068.5  414.86
  5075.2  415.68  5085.6  416.10  5116.7  416.01  5142.7  411.41  5158.2  411.27
  5168.6  410.68  5182.4  411.10  5189.3  412.81  5199.7  413.54  5213.6  413.70
#Mann=3,-1,0
  4831.2    0.05       0  4992.3    0.03       0  4996.3    0.05       0
Bank Sta=4992.3,4996.3
Exp/Cntr=0.3,0.1

Type RM Length L Ch R = 1,1124,389,389,389
BEGIN DESCRIPTION:
DOGWOOD CR TRIB 5 2 2
END DESCRIPTION:
XS GIS Cut Line= 2
      3499505.39     10411414.06      3499945.88     10411404.29
#Sta/Elev= 30
  4695.2  420.86  4711.9  420.11  4721.9  419.13  4741.9  417.84  4751.9  417.56
  4761.9  416.41  4781.9  414.99  4791.9  414.59  4811.9  414.54  4832.0  413.21
  4842.0  412.27  4882.0  409.96  4902.0  409.28  4952.0  408.88  4982.0  408.23
  4987.3  407.13  4992.0  406.15  5000.0  403.90  5000.2  403.40  5003.7  403.40
  5004.0  403.90  5012.0  407.44  5022.0  409.54  5033.3  409.61  5052.0  407.82
  5082.0  406.53  5092.0  407.34  5112.0  411.94  5122.0  412.74  5135.8  412.81
#Mann=4,-1,0
  4695.2    0.12       0  4987.3    0.05       0  5000.0    0.03       0
  5004.0    0.05       0
Bank Sta=5000,5004
Exp/Cntr=0.3,0.1

Type RM Length L Ch R = 1,735,293,293,293
BEGIN DESCRIPTION:
DOGWOOD CR TRIB 5 5 0
END DESCRIPTION:
XS GIS Cut Line= 2
      3499501.04     10411677.73      3499851.53     10411815.53
#Sta/Elev= 30
  4756.6  416.00  4759.9  416.00  4777.4  414.22  4782.8  413.22  4790.0  412.45
  4800.7  412.44  4807.2  412.97  4829.0  411.91  4837.0  411.13  4908.2  407.42
  4920.9  406.16  4929.7  405.81  4966.9  406.20  4983.4  406.14  4994.1  404.64
  4997.5  403.62  4997.8  403.12  5001.3  403.12  5001.5  403.62  5015.6  406.40
  5024.0  407.12  5047.9  406.59  5069.4  405.73  5083.5  405.56  5090.8  406.20
  5101.6  407.96  5107.9  409.93  5117.3  410.56  5123.1  411.05  5133.2  411.23
#Mann=6,-1,0
  4756.6    0.16       0  4829.0    0.12       0  4966.9    0.05       0
  4997.5    0.03       0  5001.5    0.05       0  5117.3     0.1       0
Bank Sta=4997.5,5001.5
Exp/Cntr=0.3,0.1

Type RM Length L Ch R = 1,442,130,130,130
BEGIN DESCRIPTION:
DOGWOOD CR TRIB 5 4 0
END DESCRIPTION:
XS GIS Cut Line= 4
      3499355.95     10411922.56      3499441.31     10411987.20
      3499655.31     10412001.83      3499836.99     10411893.31
#Sta/Elev= 30
  4773.9  417.94  4792.6  415.13  4798.8  413.39  4819.7  411.95  4848.8  411.56
  4883.9  409.91  4911.8  407.55  4931.9  401.92  4941.9  400.76  4970.0  400.37
  4970.2  399.87  4973.7  399.87  4974.0  400.37  4992.0  401.49  5018.3  401.08
  5023.3  403.04  5032.1  404.80  5042.1  405.55  5072.3  406.03  5144.4  406.57
  5165.8  406.25  5202.7  406.87  5224.1  406.49  5239.7  408.02  5245.5  407.50
  5257.6  409.32  5261.1  410.00  5266.9  409.52  5276.7  410.53  5307.1  411.02
#Mann=5,-1,0
  4773.9     0.1       0  4970.0    0.07       0  4974.0     0.1       0
  5072.3    0.05       0  5257.6     0.1       0
Bank Sta=4970,4974
Exp/Cntr=0.3,0.1

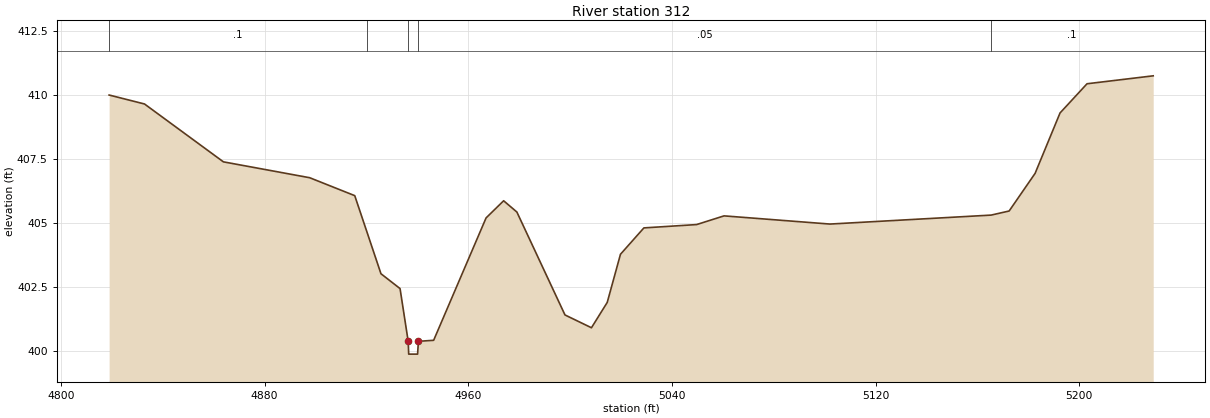
Type RM Length L Ch R = 1,312,0,0,0
BEGIN DESCRIPTION:
DOGWOOD CR TRIB 5 3 1
END DESCRIPTION:
XS GIS Cut Line= 3
      3499378.64     10412077.55      3499626.43     10412141.36
      3499777.58     10412110.19
#Sta/Elev= 30
  4818.9  409.99  4832.8  409.64  4863.8  407.38  4897.7  406.76  4915.4  406.06
  4920.2  404.64  4925.7  403.01  4933.2  402.43  4936.4  400.37  4936.6  399.87
  4940.1  399.87  4940.4  400.37  4946.4  400.41  4967.0  405.19  4973.9  405.86
  4979.1  405.42  4998.0  401.40  5008.4  400.90  5014.6  401.89  5019.8  403.77
  5029.0  404.80  5049.7  404.93  5060.5  405.27  5102.1  404.95  5165.4  405.30
  5172.5  405.46  5182.7  406.93  5192.5  409.29  5203.1  410.43  5229.1  410.74
#Mann=5,-1,0
  4818.9     0.1       0  4920.2    0.05       0  4936.4    0.03       0
  4940.4    0.05       0  5165.4     0.1       0
Bank Sta=4936.4,4940.4
Exp/Cntr=0.3,0.1

Chan Stop Cuts=-1