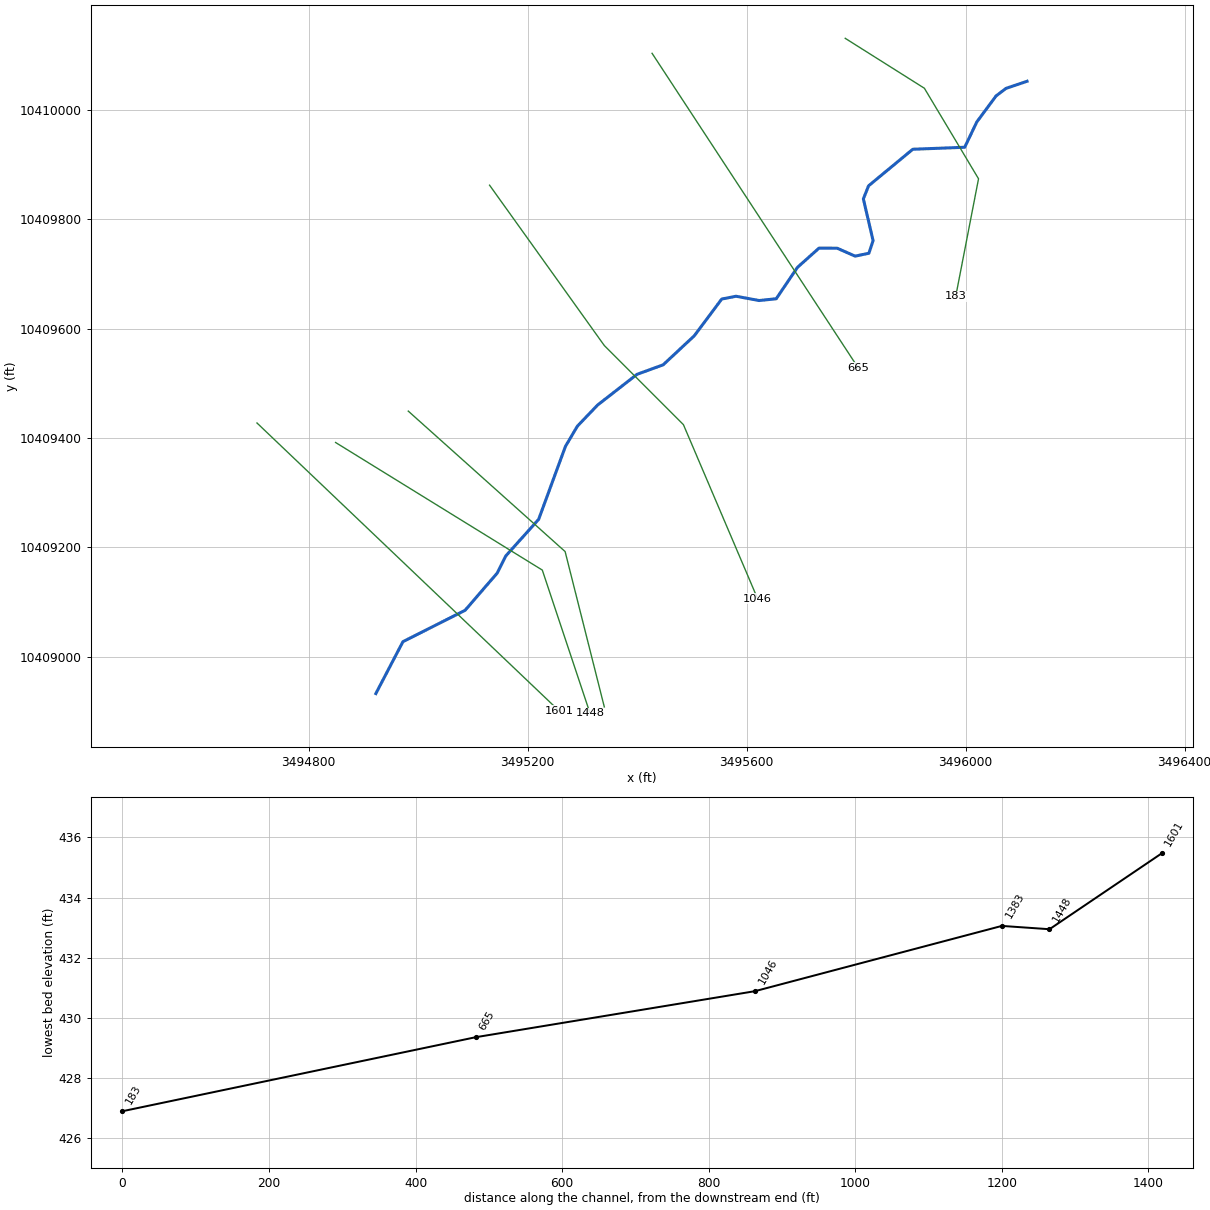
--- DOGWOOD CR WEST TRIB 6.prj (project) ---

Proj Title=DOGWOOD CR WEST TRIB 6 Base Level Engineering
Current Plan=p01
Default Exp/Contr=0.3,0.1
English Units
Geom File=g01
Flow File=f01
Plan File=p01
Y Axis Title=Elevation
X Axis Title(PF)=Main Channel Distance
X Axis Title(XS)=Station
BEGIN DESCRIPTION:
DOGWOOD CR WEST TRIB 6
END DESCRIPTION:
DSS Export Rating Curves= 0
DSS Export Rating Curve Sorted= 0
DSS Export Volume Flow Curves= 0
DXF OffsetX= 0
DXF OffsetY= 0
DXF ScaleX= 1
DXF ScaleY= 10

--- DOGWOOD CR WEST TRIB 6.p01 (plan) ---

Plan Title=Multiple Run
Short Identifier=Multiple
Geom File=g01
Flow File=f01
Subcritical Flow
K Sum by GR= 0
Std Step Tol= 0.01
Critical Tol= 0.01
Num of Std Step Trials= 20
Max Error Tol= 0.3
Flow Tol Ratio= 0.001
Split Flow NTrial= 30
Split Flow Tol= 0.02
Split Flow Ratio= 0.02
Log Output Level= 0
Friction Slope Method= 1
Unsteady Friction Slope Method= 2
Unsteady Bridges Friction Slope Method= 1
Parabolic Critical Depth
Global Vel Dist=  1 , 1 , 1
Global Log Level= 0
CheckData=True
Encroach Param= -1, 0, 0, 0
BEGIN DESCRIPTION:
Multiple Run
END DESCRIPTION:

--- DOGWOOD CR WEST TRIB 6.f01 (steady flow) ---

Flow Title=Multiple
Number of Profiles=7
Profile Names=10-year,25-year,50-year,1pct_min,100-year,1pct_plu,500-year
River Rch & RM= DOGWOOD CR WEST ,Reach-1,1601
     266     339     394     337     456     617     606
Boundary for River Rch & Prof#=DOGWOOD CR WEST ,Reach-1,1
Up Type=0
Dn Type=3
Dn Slope=0.005
Boundary for River Rch & Prof#=DOGWOOD CR WEST ,Reach-1,2
Up Type=0
Dn Type=3
Dn Slope=0.005
Boundary for River Rch & Prof#=DOGWOOD CR WEST ,Reach-1,3
Up Type=0
Dn Type=3
Dn Slope=0.005
Boundary for River Rch & Prof#=DOGWOOD CR WEST ,Reach-1,4
Up Type=0
Dn Type=3
Dn Slope=0.005
Boundary for River Rch & Prof#=DOGWOOD CR WEST ,Reach-1,5
Up Type=0
Dn Type=3
Dn Slope=0.005
Boundary for River Rch & Prof#=DOGWOOD CR WEST ,Reach-1,6
Up Type=0
Dn Type=3
Dn Slope=0.005
Boundary for River Rch & Prof#=DOGWOOD CR WEST ,Reach-1,7
Up Type=0
Dn Type=3
Dn Slope=0.005

--- DOGWOOD CR WEST TRIB 6.g01 (geometry) ---

Geom Title=Existing Conditions

River Reach=DOGWOOD CR WEST ,Reach-1
Reach XY= 30
      3494922.64     10408933.17      3494972.12     10409027.96
      3495085.66     10409085.25      3495144.51     10409153.48
      3495160.14     10409184.73      3495220.04     10409251.40
      3495268.99     10409384.73      3495290.87     10409421.71
      3495327.61     10409460.15      3495399.63     10409516.26
      3495447.58     10409533.77      3495504.41     10409586.81
      3495554.47     10409653.85      3495580.63     10409658.96
      3495622.81     10409651.14      3495654.02     10409654.39
      3495692.76     10409711.66      3495732.13     10409746.85
      3495765.46     10409746.70      3495798.10     10409732.25
      3495823.29     10409737.47      3495830.96     10409760.57
      3495813.20     10409836.79      3495822.71     10409860.68
      3495903.49     10409927.48      3495998.32     10409931.11
      3496020.41     10409977.33      3496055.62     10410024.86
      3496073.72     10410038.66      3496112.11     10410051.64

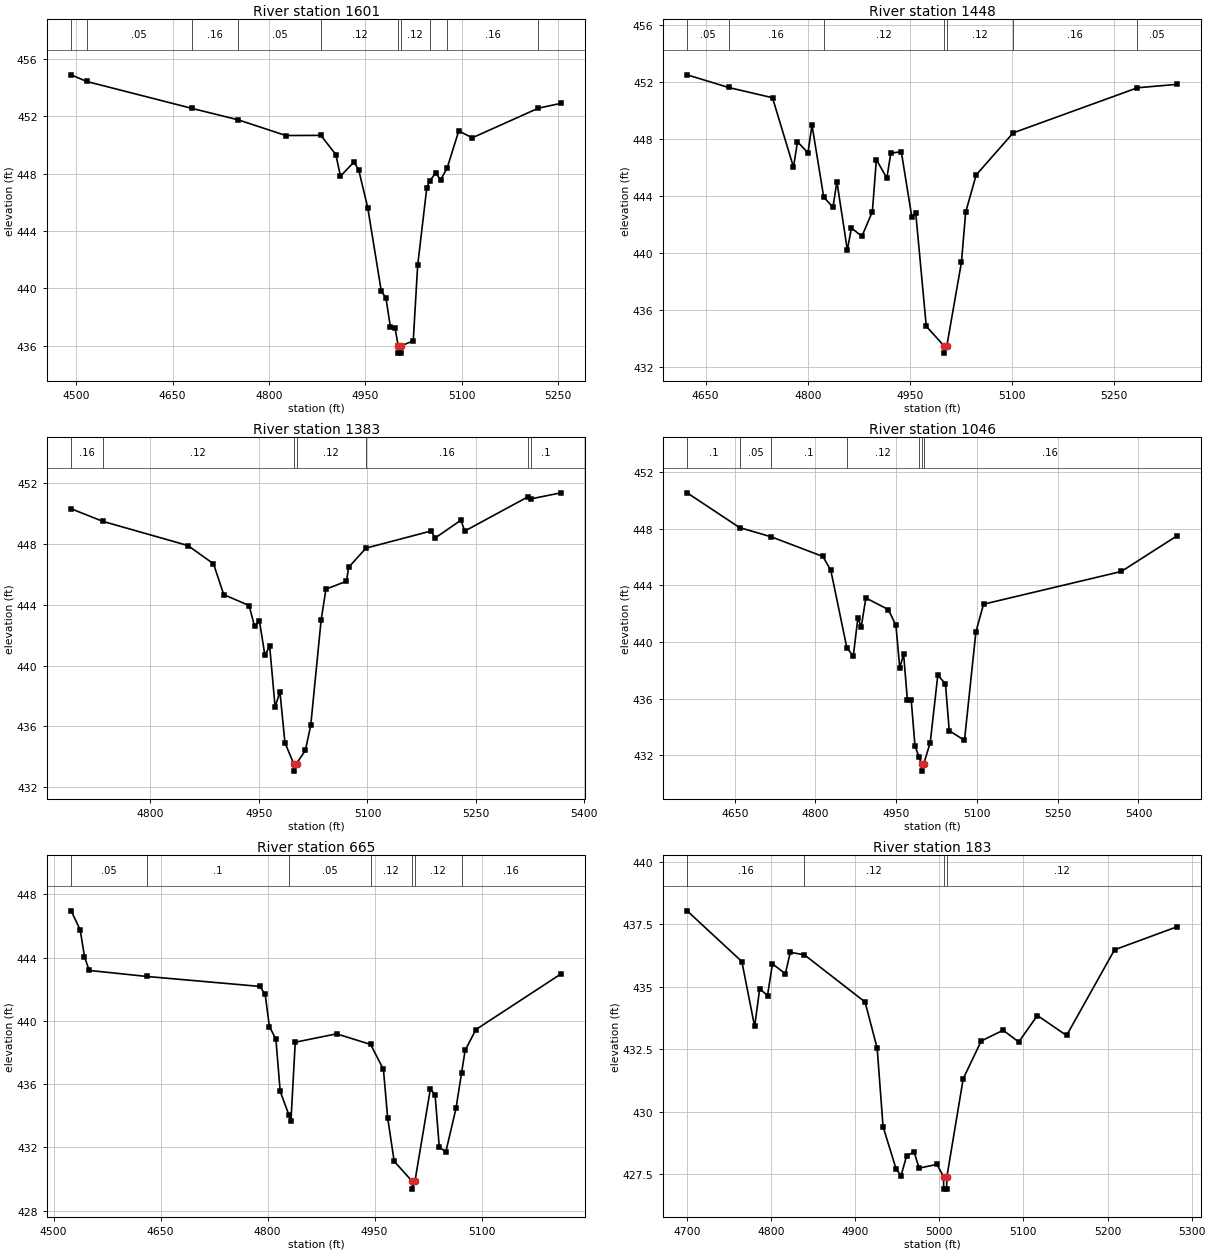
Type RM Length L Ch R = 1,1601,153,153,153
BEGIN DESCRIPTION:
DOGWOOD CR WEST TRIB 6 2
END DESCRIPTION:
XS GIS Cut Line= 2
      3494705.51     10409427.45      3495257.32     10408901.66
#Sta/Elev= 30
  4492.2  454.91  4516.1  454.45  4679.8  452.57  4751.9  451.77  4826.3  450.67
  4880.8  450.68  4904.0  449.34  4911.3  447.83  4932.3  448.82  4939.6  448.27
  4953.7  445.63  4974.8  439.79  4982.0  439.33  4989.0  437.28  4996.2  437.22
  5001.1  435.97  5001.4  435.47  5004.9  435.47  5005.1  435.97  5024.5  436.33
  5031.4  441.60  5045.6  447.03  5049.8  447.47  5059.7  448.07  5067.0  447.55
  5077.4  448.42  5095.3  450.99  5116.3  450.51  5219.2  452.58  5254.4  452.92
#Mann=10,-1,0
  4492.2    0.16       0  4516.1    0.05       0  4679.8    0.16       0
  4751.9    0.05       0  4880.8    0.12       0  5001.1    0.07       0
  5005.1    0.12       0  5049.8    0.05       0  5077.4    0.16       0
  5219.2    0.05       0
Bank Sta=5001.1,5005.1
Exp/Cntr=0.3,0.1

Type RM Length L Ch R = 1,1448,65,65,65
BEGIN DESCRIPTION:
Mapping XS 83bd8c10
END DESCRIPTION:
XS GIS Cut Line= 3
      3494849.07     10409391.84      3495226.72     10409158.74
      3495313.97     10408896.99
#Sta/Elev= 30
  4622.8  452.51  4683.8  451.62  4748.3  450.90  4779.1  446.02  4785.0  447.80
  4800.4  447.03  4806.3  448.99  4823.5  443.92  4837.1  443.20  4842.9  445.00
  4858.3  440.19  4864.2  441.75  4879.6  441.16  4895.0  442.89  4900.9  446.55
  4916.3  445.25  4922.1  447.00  4937.5  447.11  4952.9  442.55  4958.8  442.77
  4974.2  434.84  5000.4  433.45  5000.7  432.95  5004.4  433.45  5025.9  439.34
  5032.1  442.85  5047.5  445.47  5101.9  448.43  5284.5  451.60  5342.5  451.84
#Mann=7,-1,0
  4622.8    0.05       0  4683.8    0.16       0  4823.5    0.12       0
  5000.4    0.07       0  5004.4    0.12       0  5101.9    0.16       0
  5284.5    0.05       0
Bank Sta=5000.4,5004.4
Exp/Cntr=0.3,0.1

Type RM Length L Ch R = 1,1383,337,337,337
BEGIN DESCRIPTION:
Mapping XS 046e8bbd
END DESCRIPTION:
XS GIS Cut Line= 3
      3494981.89     10409449.14      3495268.38     10409192.59
      3495339.99     10408908.76
#Sta/Elev= 30
  4690.3  450.33  4734.2  449.50  4851.7  447.91  4887.1  446.71  4901.3  444.68
  4936.4  443.96  4943.9  442.59  4950.6  442.97  4958.1  440.70  4964.8  441.27
  4972.3  437.28  4979.0  438.28  4985.9  434.93  4997.9  433.56  4998.2  433.06
  5001.9  433.56  5014.1  434.42  5021.6  436.08  5035.9  442.99  5042.6  445.04
  5071.0  445.56  5074.0  446.48  5098.0  447.74  5188.2  448.87  5193.4  448.40
  5229.3  449.58  5234.4  448.86  5321.6  451.11  5325.8  450.98  5367.6  451.38
#Mann=7,-1,0
  4690.3    0.16       0  4734.2    0.12       0  4997.9    0.07       0
  5001.9    0.12       0  5098.0    0.16       0  5321.6    0.05       0
  5325.8     0.1       0
Bank Sta=4997.9,5001.9
Exp/Cntr=0.3,0.1

Type RM Length L Ch R = 1,1046,381,381,381
BEGIN DESCRIPTION:
DOGWOOD CR WEST TRIB 6 4
END DESCRIPTION:
XS GIS Cut Line= 4
      3495130.38     10409861.84      3495340.00     10409568.89
      3495484.53     10409424.36      3495619.96     10409106.63
#Sta/Elev= 30
  4561.5  450.53  4658.9  448.08  4718.2  447.42  4813.7  446.04  4828.5  445.06
  4858.2  439.61  4870.2  438.99  4878.8  441.71  4885.0  441.06  4893.6  443.11
  4935.4  442.29  4949.5  441.17  4956.6  438.16  4963.7  439.16  4970.8  435.89
  4977.8  435.94  4984.9  432.66  4992.2  431.90  4997.0  431.39  4997.3  430.89
  5001.0  431.39  5013.2  432.91  5027.3  437.67  5041.5  437.04  5048.5  433.75
  5076.8  433.06  5098.0  440.70  5112.2  442.67  5368.2  444.98  5471.5  447.49
#Mann=7,-1,0
  4561.5     0.1       0  4658.9    0.05       0  4718.2     0.1       0
  4858.2    0.12       0  4992.2    0.16       0  4997.0    0.07       0
  5001.0    0.16       0
Bank Sta=4997,5001
Exp/Cntr=0.3,0.1

Type RM Length L Ch R = 1,665,482,482,482
BEGIN DESCRIPTION:
DOGWOOD CR WEST TRIB 6 3
END DESCRIPTION:
XS GIS Cut Line= 2
      3495427.22     10410102.78      3495803.56     10409528.51
#Sta/Elev= 30
  4524.7  446.96  4537.4  445.75  4543.4  444.05  4550.0  443.19  4630.6  442.81
  4789.1  442.18  4796.6  441.68  4802.6  439.64  4811.7  438.84  4817.7  435.54
  4830.1  434.03  4832.8  433.69  4838.8  438.65  4896.7  439.18  4944.5  438.51
  4962.4  436.93  4968.4  433.85  4977.5  431.12  5002.6  429.86  5002.8  429.36
  5006.6  429.86  5028.2  435.69  5034.8  435.33  5040.7  432.01  5049.9  431.72
  5064.1  434.46  5072.0  436.73  5076.9  438.13  5092.0  439.45  5211.3  442.97
#Mann=7,-1,0
  4524.7    0.05       0  4630.6     0.1       0  4830.1    0.05       0
  4944.5    0.12       0  5002.6    0.07       0  5006.6    0.12       0
  5072.0    0.16       0
Bank Sta=5002.6,5006.6
Exp/Cntr=0.3,0.1

Type RM Length L Ch R = 1,183,0,0,0
BEGIN DESCRIPTION:
DOGWOOD CR WEST TRIB 6 1 0
END DESCRIPTION:
XS GIS Cut Line= 4
      3495780.10     10410130.10      3495924.63     10410038.95
      3496023.59     10409873.58      3495981.93     10409658.77
#Sta/Elev= 30
  4700.1  438.04  4765.2  436.01  4780.4  433.41  4786.4  434.92  4795.7  434.65
  4801.6  435.92  4816.9  435.52  4822.8  436.38  4839.5  436.28  4911.7  434.39
  4926.1  432.54  4933.1  429.40  4948.6  427.71  4954.5  427.44  4961.1  428.23
  4970.0  428.39  4975.9  427.74  4997.2  427.89  5005.0  427.40  5005.2  426.90
  5008.7  426.90  5009.0  427.40  5028.4  431.32  5049.8  432.83  5075.9  433.26
  5094.4  432.79  5116.6  433.85  5151.3  433.05  5208.3  436.48  5282.5  437.40
#Mann=4,-1,0
  4700.1    0.16       0  4839.5    0.12       0  5005.0    0.07       0
  5009.0    0.12       0
Bank Sta=5005,5009
Exp/Cntr=0.3,0.1

Chan Stop Cuts=-1