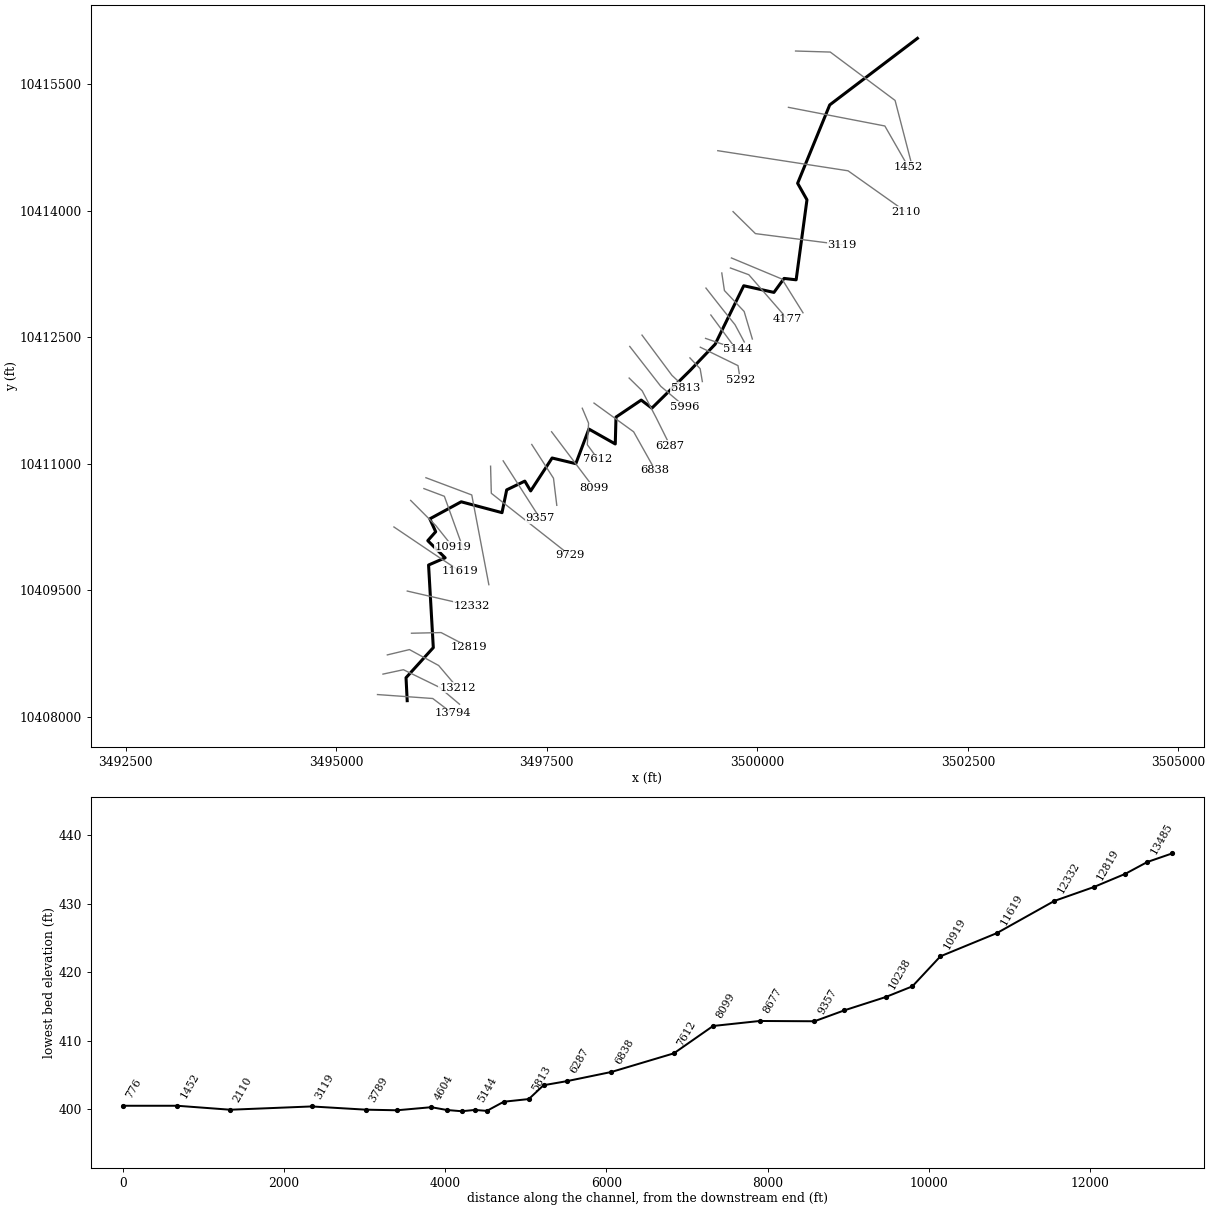
--- DOGWOOD CREEK WEST.prj (project) ---

Proj Title=DOGWOOD CREEK WEST Base Level Engineering
Current Plan=p01
Default Exp/Contr=0.3,0.1
English Units
Geom File=g01
Flow File=f01
Plan File=p01
Y Axis Title=Elevation
X Axis Title(PF)=Main Channel Distance
X Axis Title(XS)=Station
BEGIN DESCRIPTION:
DOGWOOD CREEK WEST
END DESCRIPTION:
DSS Export Rating Curves= 0
DSS Export Rating Curve Sorted= 0
DSS Export Volume Flow Curves= 0
DXF OffsetX= 0
DXF OffsetY= 0
DXF ScaleX= 1
DXF ScaleY= 10

--- DOGWOOD CREEK WEST.p01 (plan) ---

Plan Title=Multiple Run
Short Identifier=Multiple
Geom File=g01
Flow File=f01
Subcritical Flow
K Sum by GR= 0
Std Step Tol= 0.01
Critical Tol= 0.01
Num of Std Step Trials= 20
Max Error Tol= 0.3
Flow Tol Ratio= 0.001
Split Flow NTrial= 30
Split Flow Tol= 0.02
Split Flow Ratio= 0.02
Log Output Level= 0
Friction Slope Method= 1
Unsteady Friction Slope Method= 2
Unsteady Bridges Friction Slope Method= 1
Parabolic Critical Depth
Global Vel Dist=  1 , 1 , 1
Global Log Level= 0
CheckData=True
Encroach Param= -1, 0, 0, 0
BEGIN DESCRIPTION:
Multiple Run
END DESCRIPTION:

--- DOGWOOD CREEK WEST.f01 (steady flow) ---

Flow Title=Multiple
Program Version=4.10
Number of Profiles= 7
Profile Names=10-year,25-year,50-year,1pct_min,100-year,1pct_plu,500-year
River Rch & RM=DOGWOOD CREEK WE,Reach-1         ,13794
     407     535     635     553     748    1012    1033
River Rch & RM=DOGWOOD CREEK WE,Reach-1         ,11619
     958    1322    1623    1454    1966    2659    2879
River Rch & RM=DOGWOOD CREEK WE,Reach-1         ,10919
     958    1322    1623    1454    1966    2659    2879
River Rch & RM=DOGWOOD CREEK WE,Reach-1         ,5292
    1504    2125    2650    2407    3255    4403    4906
River Rch & RM=DOGWOOD CREEK WE,Reach-1         ,5144
    1504    2125    2650    2407    3255    4403    4906
River Rch & RM=DOGWOOD CREEK WE,Reach-1         ,3119
    1716    2430    3033    2756    3727    5040    5619
Boundary for River Rch & Prof#=DOGWOOD CREEK WE,Reach-1         , 1
Up Type= 0
Dn Type= 3
Dn Slope=0.005
Boundary for River Rch & Prof#=DOGWOOD CREEK WE,Reach-1         , 2
Up Type= 0
Dn Type= 3
Dn Slope=0.005
Boundary for River Rch & Prof#=DOGWOOD CREEK WE,Reach-1         , 3
Up Type= 0
Dn Type= 3
Dn Slope=0.005
Boundary for River Rch & Prof#=DOGWOOD CREEK WE,Reach-1         , 4
Up Type= 0
Dn Type= 3
Dn Slope=0.005
Boundary for River Rch & Prof#=DOGWOOD CREEK WE,Reach-1         , 5
Up Type= 0
Dn Type= 3
Dn Slope=0.005
Boundary for River Rch & Prof#=DOGWOOD CREEK WE,Reach-1         , 6
Up Type= 0
Dn Type= 3
Dn Slope=0.005
Boundary for River Rch & Prof#=DOGWOOD CREEK WE,Reach-1         , 7
Up Type= 0
Dn Type= 3
Dn Slope=0.005
DSS Import GetInterval= 0
DSS Import GetPeak= 0
DSS Import FillOption= 0

--- DOGWOOD CREEK WEST.g01 (geometry) ---

Geom Title=Existing Conditions

River Reach=DOGWOOD CREEK WE,Reach-1
Reach XY= 30
      3495841.14     10408191.87      3495827.34     10408464.09
      3496151.24     10408821.03      3496094.99     10409800.50
      3496291.98     10409886.02      3496085.62     10410089.32
      3496179.62     10410195.36      3496109.83     10410347.88
      3496482.54     10410550.24      3496967.36     10410421.45
      3497022.82     10410691.42      3497238.09     10410795.55
      3497307.67     10410679.01      3497562.22     10411069.48
      3497843.86     10411002.44      3497998.86     10411412.96
      3498312.40     10411235.87      3498321.08     10411554.62
      3498620.73     10411756.36      3498746.77     10411660.53
      3499200.23     10412106.59      3499498.94     10412418.67
      3499838.35     10413112.16      3500196.86     10413033.17
      3500317.52     10413198.97      3500460.74     10413182.47
      3500589.21     10414131.10      3500478.33     10414327.25
      3500859.60     10415256.47      3501901.24     10416045.98

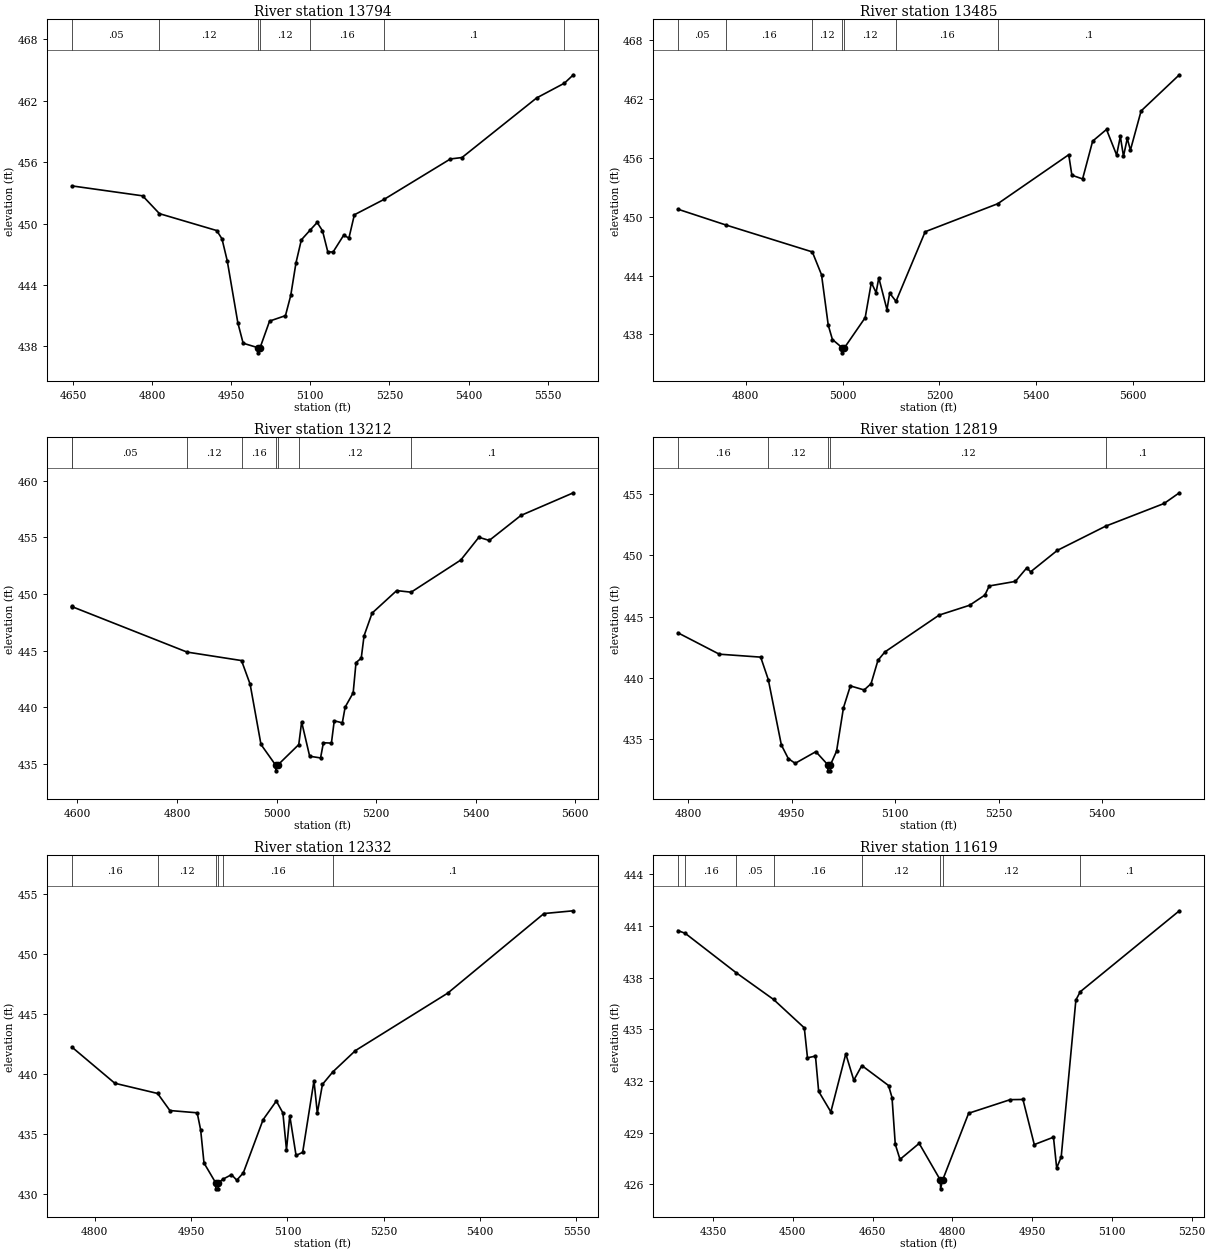
Type RM Length L Ch R = 1,13794,309,309,309
BEGIN DESCRIPTION:
DOGWOOD CREEK WEST 4 0
END DESCRIPTION:
XS GIS Cut Line= 3
      3495488.45     10408264.44      3496144.72     10408217.57
      3496378.06     10408041.26
#Sta/Elev= 30
  4648.2  453.68  4782.2  452.71  4814.1  450.97  4922.6  449.32  4932.6  448.51
  4942.6  446.36  4962.7  440.30  4972.7  438.32  5000.8  437.88  5001.0  437.38
  5004.8  437.88  5022.8  440.48  5052.9  441.01  5062.9  442.98  5072.9  446.18
  5083.0  448.41  5100.3  449.40  5113.0  450.11  5123.1  449.30  5133.1  447.25
  5143.1  447.22  5163.2  448.86  5173.2  448.59  5183.5  450.86  5239.7  452.36
  5365.5  456.31  5387.5  456.45  5529.0  462.27  5581.6  463.71  5598.6  464.53
#Mann=7,-1,0
  4648.2    0.05       0  4814.1    0.12       0  5000.8    0.07       0
  5004.8    0.12       0  5100.3    0.16       0  5239.7     0.1       0
  5581.6    0.05       0
Bank Sta=5000.8,5004.8
Exp/Cntr=0.3,0.1

Type RM Length L Ch R = 1,13485,273,273,273
BEGIN DESCRIPTION:
DOGWOOD CREEK WEST 3 0
END DESCRIPTION:
XS GIS Cut Line= 4
      3495553.33     10408506.88      3495796.38     10408558.97
      3496223.90     10408350.63      3496462.40     10408149.88
#Sta/Elev= 30
  4659.7  450.78  4758.8  449.17  4937.4  446.42  4956.4  444.09  4970.3  438.94
  4978.9  437.48  4999.5  436.62  4999.7  436.12  5003.5  436.62  5046.6  439.71
  5059.3  443.29  5069.1  442.27  5074.7  443.77  5091.6  440.53  5097.2  442.21
  5110.3  441.38  5170.5  448.48  5320.5  451.34  5467.1  456.34  5473.6  454.25
  5495.7  453.87  5516.5  457.73  5545.1  458.92  5566.0  456.31  5573.7  458.21
  5580.2  456.18  5588.0  458.00  5594.5  456.81  5616.6  460.81  5695.6  464.50
#Mann=7,-1,0
  4659.7    0.05       0  4758.8    0.16       0  4937.4    0.12       0
  4999.5    0.07       0  5003.5    0.12       0  5110.3    0.16       0
  5320.5     0.1       0
Bank Sta=4999.5,5003.5
Exp/Cntr=0.3,0.1

Type RM Length L Ch R = 1,13212,393,393,393
BEGIN DESCRIPTION:
DOGWOOD CREEK WEST 28 0
END DESCRIPTION:
XS GIS Cut Line= 4
      3495605.42     10408734.75      3495868.00     10408797.68
      3496214.93     10408608.85      3496436.42     10408347.74
#Sta/Elev= 30
  4588.9  448.91  4589.8  448.88  4820.1  444.88  4929.6  444.13  4946.9  442.04
  4968.7  436.72  4998.2  434.89  4998.5  434.39  5002.2  434.89  5044.6  436.71
  5050.4  438.71  5066.5  435.68  5088.4  435.53  5094.1  436.87  5110.2  436.84
  5115.9  438.81  5132.1  438.63  5137.8  440.02  5153.9  441.28  5159.6  443.95
  5170.1  444.34  5175.8  446.32  5191.9  448.32  5241.3  450.31  5270.4  450.17
  5370.1  453.01  5406.4  455.02  5427.3  454.74  5491.0  456.95  5596.3  458.95
#Mann=8,-1,0
  4588.9    0.16       0  4589.8    0.05       0  4820.1    0.12       0
  4929.6    0.16       0  4998.2    0.07       0  5002.2    0.16       0
  5044.6    0.12       0  5270.4     0.1       0
Bank Sta=4998.2,5002.2
Exp/Cntr=0.3,0.1

Type RM Length L Ch R = 1,12819,487,487,487
BEGIN DESCRIPTION:
DOGWOOD CREEK WEST 27 1
END DESCRIPTION:
XS GIS Cut Line= 3
      3495892.15     10408991.64      3496243.43     10408999.51
      3496576.68     10408826.39
#Sta/Elev= 30
  4784.8  443.68  4844.8  441.94  4904.8  441.70  4915.8  439.88  4934.8  434.55
  4944.8  433.45  4954.8  433.06  4984.8  434.01  5002.0  432.95  5002.3  432.45
  5005.8  432.45  5006.0  432.95  5014.8  434.05  5024.8  437.58  5034.8  439.36
  5054.8  439.03  5064.8  439.54  5074.8  441.44  5084.8  442.12  5163.5  445.12
  5207.7  445.92  5229.8  446.75  5236.1  447.49  5274.0  447.86  5290.5  448.96
  5296.1  448.64  5334.7  450.38  5404.7  452.35  5489.6  454.20  5511.7  455.07
#Mann=5,-1,0
  4784.8    0.16       0  4915.8    0.12       0  5002.0    0.07       0
  5006.0    0.12       0  5404.7     0.1       0
Bank Sta=5002,5006
Exp/Cntr=0.3,0.1

Type RM Length L Ch R = 1,12332,713,713,713
BEGIN DESCRIPTION:
DOGWOOD CREEK WEST 27 0
END DESCRIPTION:
XS GIS Cut Line= 2
      3495842.06     10409491.65      3496602.77     10409316.59
#Sta/Elev= 30
  4764.6  442.23  4831.4  439.22  4898.0  438.37  4917.1  436.95  4959.6  436.76
  4965.0  435.33  4970.2  432.58  4988.4  430.93  4988.6  430.43  4992.1  430.43
  4992.4  430.93  4999.9  431.24  5013.0  431.61  5021.2  431.15  5031.4  431.76
  5062.2  436.19  5082.8  437.74  5093.0  436.75  5098.6  433.68  5103.7  436.52
  5113.5  433.21  5123.8  433.47  5141.4  439.43  5146.6  436.74  5154.6  439.13
  5170.8  440.17  5205.9  441.94  5349.5  446.72  5499.4  453.35  5545.2  453.58
#Mann=6,-1,0
  4764.6    0.16       0  4898.0    0.12       0  4988.4    0.07       0
  4992.4    0.12       0  4999.9    0.16       0  5170.8     0.1       0
Bank Sta=4988.4,4992.4
Exp/Cntr=0.3,0.1

Type RM Length L Ch R = 1,11619,700,700,700
BEGIN DESCRIPTION:
DOGWOOD CREEK WEST 26 0
END DESCRIPTION:
XS GIS Cut Line= 3
      3495683.56     10410251.66      3496141.43     10409943.52
      3496467.40     10409728.14
#Sta/Elev= 30
  4284.2  440.73  4298.0  440.57  4393.8  438.28  4464.0  436.73  4521.8  435.08
  4527.8  433.34  4542.8  433.44  4548.8  431.39  4571.7  430.20  4599.8  433.57
  4614.8  432.04  4630.0  432.89  4680.2  431.73  4686.7  431.03  4692.8  428.32
  4701.7  427.44  4737.7  428.37  4777.7  426.23  4778.0  425.73  4781.7  426.23
  4830.7  430.12  4908.9  430.91  4932.8  430.92  4954.1  428.30  4990.2  428.73
  4996.2  426.94  5004.7  427.58  5032.3  436.70  5040.6  437.18  5226.8  441.88
#Mann=8,-1,0
  4284.2    0.05       0  4298.0    0.16       0  4393.8    0.05       0
  4464.0    0.16       0  4630.0    0.12       0  4777.7    0.07       0
  4781.7    0.12       0  5040.6     0.1       0
Bank Sta=4777.7,4781.7
Exp/Cntr=0.3,0.1

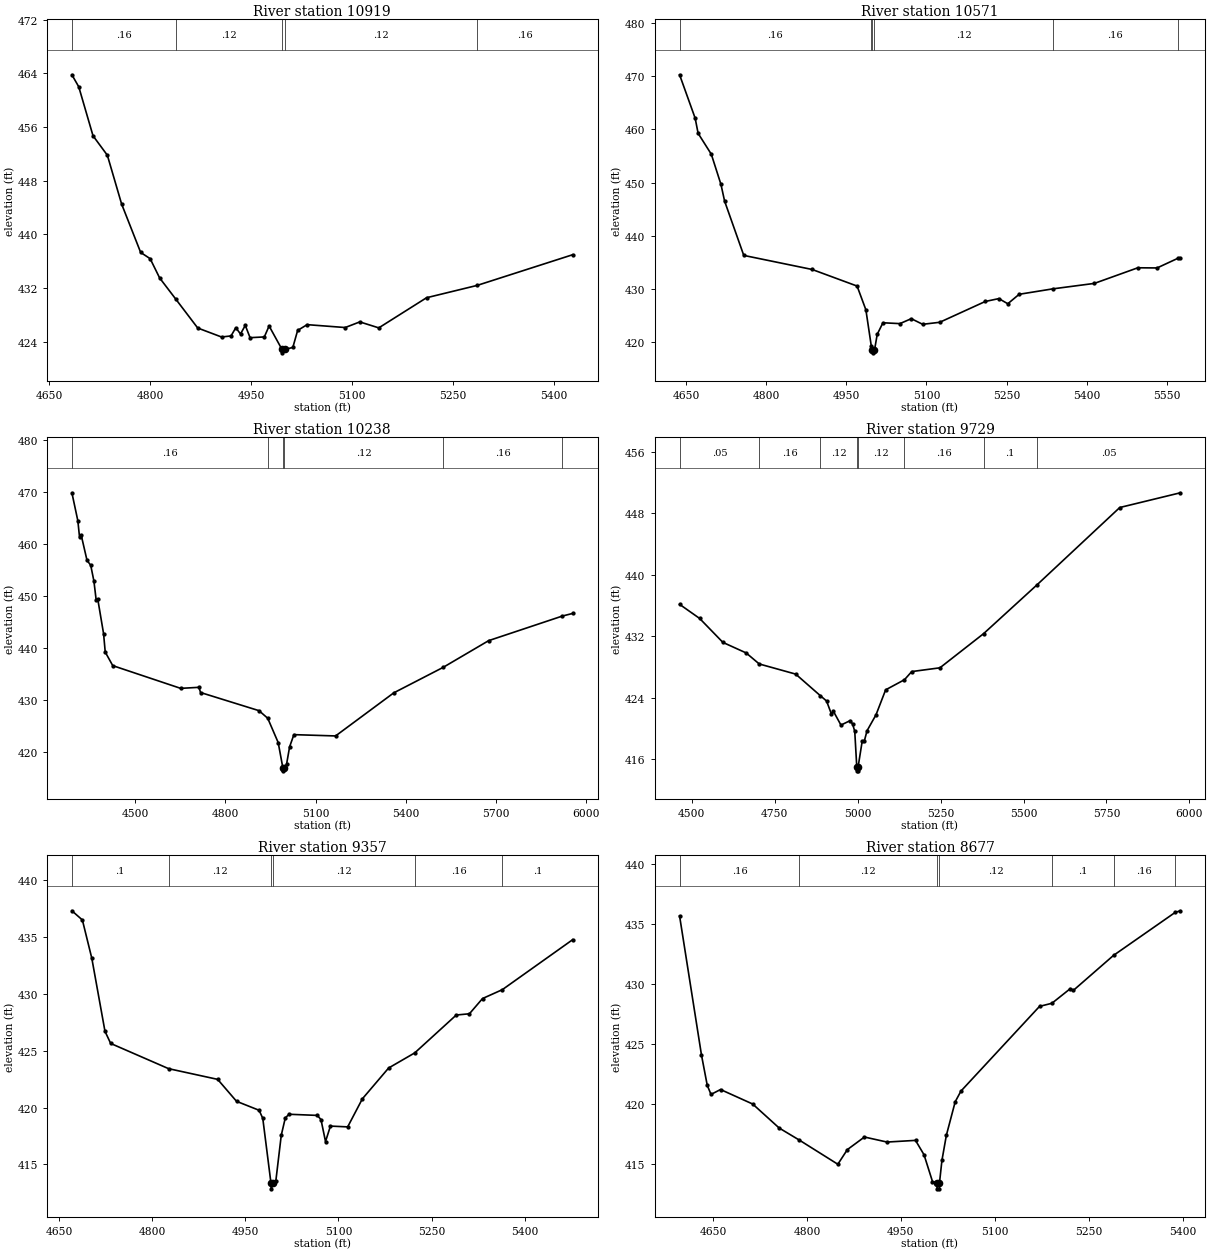
Type RM Length L Ch R = 1,10919,348,348,348
BEGIN DESCRIPTION:
DOGWOOD CREEK WEST 24 1
END DESCRIPTION:
XS GIS Cut Line= 3
      3495882.51     10410566.52      3496182.48     10410266.54
      3496382.43     10410016.61
#Sta/Elev= 30
  4683.3  463.77  4693.5  461.98  4714.7  454.68  4736.0  451.78  4757.2  444.51
  4785.5  437.30  4799.6  436.37  4813.7  433.50  4838.1  430.29  4870.3  426.04
  4905.7  424.70  4919.8  424.86  4926.9  426.08  4933.9  425.15  4941.0  426.43
  4948.1  424.60  4969.3  424.71  4976.4  426.34  4995.6  422.84  4995.8  422.34
  4999.6  422.84  5011.7  423.15  5018.8  425.68  5032.9  426.54  5089.5  426.11
  5111.2  426.95  5139.4  426.06  5210.4  430.55  5285.7  432.39  5427.6  436.96
#Mann=5,-1,0
  4683.3    0.16       0  4838.1    0.12       0  4995.6    0.07       0
  4999.6    0.12       0  5285.7    0.16       0
Bank Sta=4995.6,4999.6
Exp/Cntr=0.3,0.1

Type RM Length L Ch R = 1,10571,333,333,333
BEGIN DESCRIPTION:
DOGWOOD CREEK WEST 24 0
END DESCRIPTION:
XS GIS Cut Line= 3
      3496039.57     10410706.80      3496282.60     10410615.66
      3496512.64     10409977.62
#Sta/Elev= 30
  4637.8  470.29  4667.0  462.11  4672.5  459.27  4697.2  455.34  4715.3  449.65
  4722.1  446.51  4758.0  436.29  4886.1  433.64  4970.2  430.52  4986.7  426.04
  4996.8  419.23  4998.8  418.45  4999.1  417.95  5002.8  418.45  5007.9  421.43
  5018.6  423.61  5050.4  423.45  5071.7  424.38  5093.0  423.32  5124.9  423.70
  5210.3  427.62  5235.7  428.16  5252.4  427.19  5273.7  428.97  5336.5  429.99
  5414.5  431.02  5495.9  433.96  5532.0  433.93  5571.0  435.75  5575.6  435.75
#Mann=6,-1,0
  4637.8    0.16       0  4996.8    0.12       0  4998.8    0.07       0
  5002.8    0.12       0  5336.5    0.16       0  5571.0     0.1       0
Bank Sta=4998.8,5002.8
Exp/Cntr=0.3,0.1

Type RM Length L Ch R = 1,10238,509,509,509
BEGIN DESCRIPTION:
DOGWOOD CREEK WEST 23 1
END DESCRIPTION:
XS GIS Cut Line= 3
      3496063.53     10410835.63      3496608.01     10410631.45
      3496810.90     10409567.43
#Sta/Elev= 30
  4289.8  469.85  4309.6  464.46  4315.2  461.32  4320.5  461.77  4340.1  456.84
  4352.4  455.91  4363.0  452.86  4370.4  449.28  4375.7  449.43  4395.1  442.76
  4400.6  439.22  4425.6  436.61  4651.4  432.24  4712.1  432.44  4717.5  431.44
  4911.8  427.95  4940.8  426.49  4975.6  421.81  4991.3  416.88  4991.5  416.38
  4995.3  416.88  5003.5  417.69  5013.6  421.02  5027.8  423.34  5166.3  423.09
  5359.8  431.38  5523.7  436.27  5675.3  441.42  5920.4  446.15  5954.5  446.65
#Mann=6,-1,0
  4289.8    0.16       0  4940.8    0.12       0  4991.3    0.07       0
  4995.3    0.12       0  5523.7    0.16       0  5920.4     0.1       0
Bank Sta=4991.3,4995.3
Exp/Cntr=0.3,0.1

Type RM Length L Ch R = 1,9729,372,372,372
BEGIN DESCRIPTION:
DOGWOOD CREEK WEST 22 0
END DESCRIPTION:
XS GIS Cut Line= 3
      3496831.54     10410972.15      3496840.22     10410650.98
      3497774.25     10409916.52
#Sta/Elev= 30
  4463.3  436.14  4523.8  434.30  4593.9  431.18  4663.9  429.81  4703.5  428.37
  4813.3  427.05  4887.8  424.23  4906.3  423.55  4920.8  421.87  4927.2  422.19
  4949.7  420.41  4977.8  421.00  4985.0  420.52  4991.3  419.60  4997.4  414.95
  4997.7  414.45  5001.2  414.45  5001.4  414.95  5013.9  418.36  5020.2  418.34
  5028.3  419.67  5055.5  421.76  5084.4  425.00  5141.2  426.32  5163.0  427.38
  5248.0  427.87  5379.4  432.31  5539.7  438.64  5790.1  448.75  5972.8  450.67
#Mann=8,-1,0
  4463.3    0.05       0  4703.5    0.16       0  4887.8    0.12       0
  4997.4    0.07       0  5001.4    0.12       0  5141.2    0.16       0
  5379.4     0.1       0  5539.7    0.05       0
Bank Sta=4997.4,5001.4
Exp/Cntr=0.3,0.1

Type RM Length L Ch R = 1,9357,680,680,680
BEGIN DESCRIPTION:
DOGWOOD CREEK WEST 20 0
END DESCRIPTION:
XS GIS Cut Line= 2
      3496980.94     10411035.57      3497417.01     10410356.52
#Sta/Elev= 30
  4670.5  437.31  4687.4  436.50  4702.6  433.13  4723.8  426.71  4733.0  425.64
  4826.4  423.42  4905.4  422.48  4935.8  420.55  4972.2  419.76  4978.1  419.05
  4991.3  413.35  4991.6  412.85  4995.3  413.35  4999.2  413.57  5007.9  417.57
  5014.4  419.09  5020.4  419.41  5066.0  419.31  5071.9  418.94  5079.2  417.01
  5087.1  418.37  5114.9  418.30  5138.6  420.77  5180.9  423.48  5223.0  424.81
  5289.9  428.14  5311.1  428.25  5332.2  429.59  5364.1  430.37  5477.5  434.77
#Mann=6,-1,0
  4670.5     0.1       0  4826.4    0.12       0  4991.3    0.07       0
  4995.3    0.12       0  5223.0    0.16       0  5364.1     0.1       0
Bank Sta=4991.3,4995.3
Exp/Cntr=0.3,0.1

Type RM Length L Ch R = 1,8677,578,578,578
BEGIN DESCRIPTION:
DOGWOOD CREEK WEST 2 0
END DESCRIPTION:
XS GIS Cut Line= 3
      3497320.55     10411229.82      3497578.80     10410829.42
      3497617.87     10410508.25
#Sta/Elev= 30
  4596.5  435.64  4631.5  424.04  4640.7  421.52  4646.7  420.76  4661.9  421.17
  4713.3  419.96  4755.6  417.96  4787.9  416.95  4849.3  414.94  4864.5  416.16
  4891.8  417.21  4927.9  416.79  4973.4  416.93  4987.0  415.73  5000.5  413.50
  5007.7  413.39  5007.9  412.89  5011.4  412.89  5011.7  413.39  5015.6  415.26
  5022.7  417.36  5036.8  420.15  5046.0  421.04  5171.5  428.10  5191.3  428.36
  5220.7  429.58  5225.7  429.44  5289.7  432.35  5388.1  435.93  5396.5  436.07
#Mann=7,-1,0
  4596.5    0.16       0  4787.9    0.12       0  5007.7    0.07       0
  5011.7    0.12       0  5191.3     0.1       0  5289.7    0.16       0
  5388.1     0.1       0
Bank Sta=5007.7,5011.7
Exp/Cntr=0.3,0.1

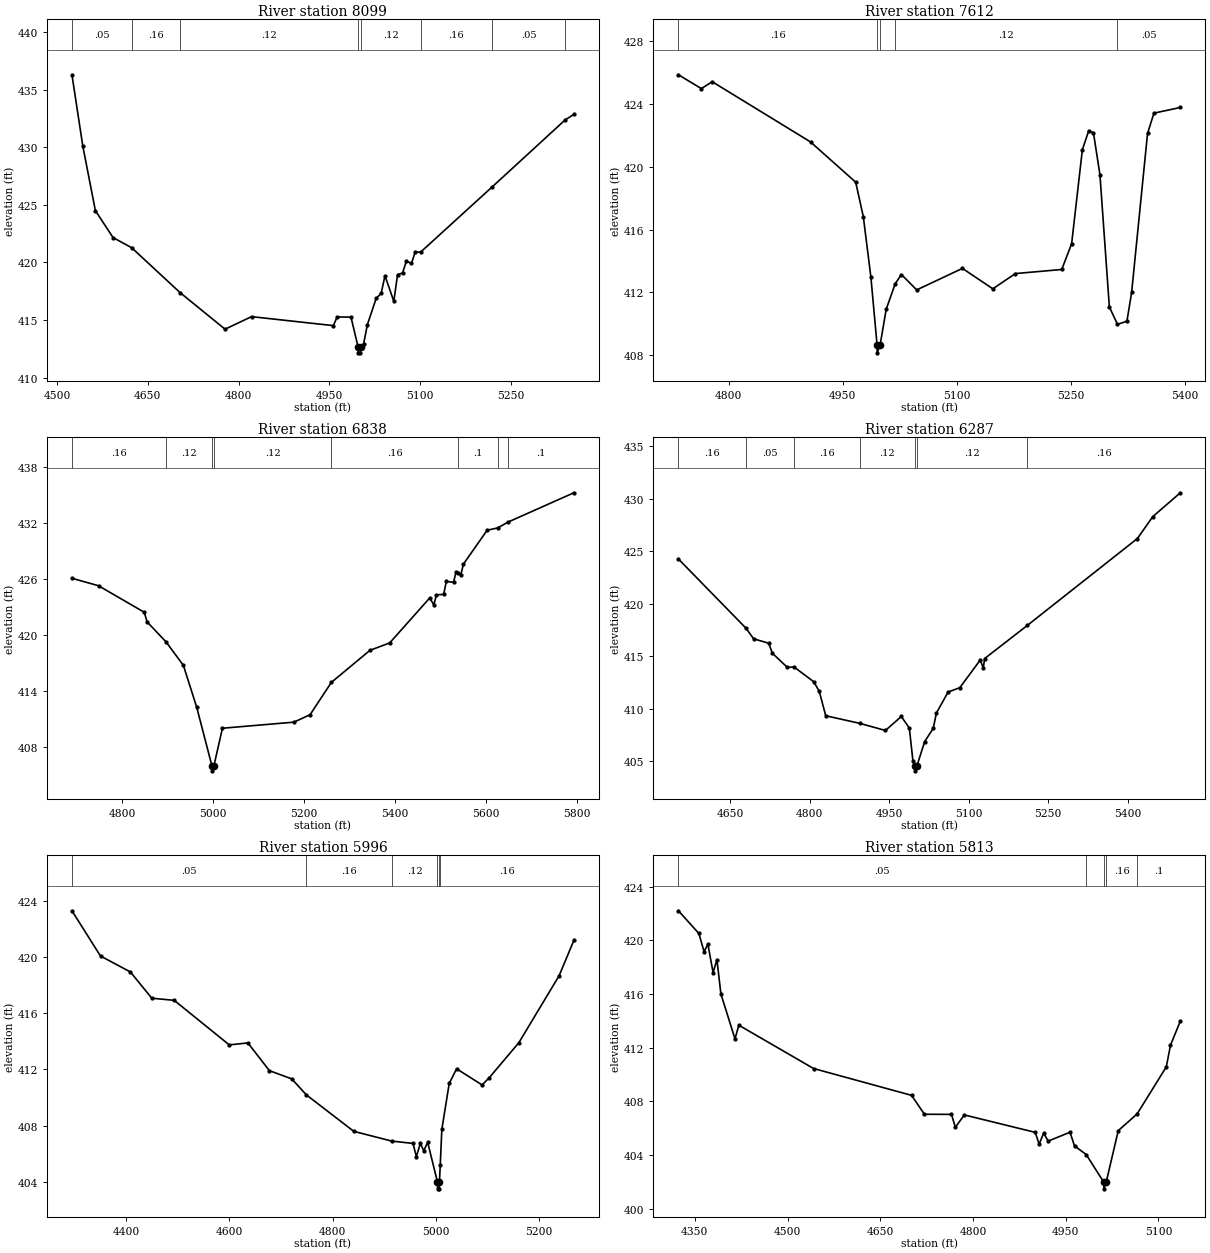
Type RM Length L Ch R = 1,8099,487,487,487
BEGIN DESCRIPTION:
DOGWOOD CREEK WEST 19 0
END DESCRIPTION:
XS GIS Cut Line= 2
      3497556.04     10411380.60      3498056.23     10410718.75
#Sta/Elev= 30
  4524.6  436.28  4542.5  430.11  4563.3  424.50  4592.5  422.16  4623.3  421.28
  4703.2  417.39  4777.7  414.21  4821.4  415.30  4956.7  414.52  4962.9  415.27
  4985.8  415.26  4997.6  412.66  4997.9  412.16  5001.4  412.16  5001.6  412.66
  5006.6  412.91  5012.9  414.60  5027.4  416.88  5035.7  417.32  5042.0  418.85
  5056.6  416.63  5062.8  418.94  5071.1  419.09  5077.4  420.12  5085.7  419.91
  5091.9  420.89  5101.2  420.91  5218.7  426.53  5340.1  432.38  5354.2  432.84
#Mann=8,-1,0
  4524.6    0.05       0  4623.3    0.16       0  4703.2    0.12       0
  4997.6    0.07       0  5001.6    0.12       0  5101.2    0.16       0
  5218.7    0.05       0  5340.1     0.1       0
Bank Sta=4997.6,5001.6
Exp/Cntr=0.3,0.1

Type RM Length L Ch R = 1,7612,774,774,774
BEGIN DESCRIPTION:
DOGWOOD CREEK WEST 18 0
END DESCRIPTION:
XS GIS Cut Line= 4
      3497920.61     10411659.49      3497995.47     10411482.63
      3497980.28     10411227.64      3498105.98     10411056.42
#Sta/Elev= 30
  4734.1  425.84  4764.3  424.96  4778.5  425.40  4907.8  421.57  4967.2  419.01
  4977.2  416.82  4987.2  412.96  4995.3  408.66  4995.5  408.16  4999.3  408.66
  5007.3  410.93  5019.2  412.56  5027.3  413.14  5047.4  412.16  5107.5  413.53
  5147.5  412.23  5177.1  413.20  5238.1  413.46  5251.1  415.10  5265.2  421.07
  5273.6  422.29  5279.8  422.15  5288.3  419.49  5300.7  411.08  5311.4  409.97
  5323.8  410.17  5330.0  412.01  5350.9  422.11  5359.3  423.40  5394.0  423.76
#Mann=5,-1,0
  4734.1    0.16       0  4995.3    0.07       0  4999.3    0.16       0
  5019.2    0.12       0  5311.4    0.05       0
Bank Sta=4995.3,4999.3
Exp/Cntr=0.3,0.1

Type RM Length L Ch R = 1,6838,551,551,551
BEGIN DESCRIPTION:
DOGWOOD CREEK WEST 17 0
END DESCRIPTION:
XS GIS Cut Line= 3
      3498059.83     10411720.87      3498530.76     10411380.15
      3498786.19     10410925.56
#Sta/Elev= 30
  4690.3  426.05  4748.7  425.25  4849.2  422.41  4855.4  421.38  4896.9  419.25
  4935.1  416.73  4964.5  412.23  4998.0  405.94  4998.3  405.44  5002.0  405.94
  5020.9  410.00  5177.9  410.65  5213.5  411.45  5260.3  414.91  5345.1  418.34
  5388.4  419.13  5476.3  423.94  5485.4  423.21  5491.1  424.27  5507.0  424.33
  5512.8  425.71  5528.7  425.62  5534.4  426.77  5538.9  426.62  5544.7  426.42
  5550.4  427.57  5602.5  431.19  5625.6  431.44  5649.1  432.08  5793.0  435.20
#Mann=8,-1,0
  4690.3    0.16       0  4896.9    0.12       0  4998.0    0.07       0
  5002.0    0.12       0  5260.3    0.16       0  5538.9     0.1       0
  5625.6    0.16       0  5649.1     0.1       0
Bank Sta=4998,5002
Exp/Cntr=0.3,0.1

Type RM Length L Ch R = 1,6287,291,291,291
BEGIN DESCRIPTION:
DOGWOOD CREEK WEST 15 0
END DESCRIPTION:
XS GIS Cut Line= 4
      3498477.26     10412017.55      3498632.41     10411865.66
      3498799.51     10411544.48      3498963.67     10411215.08
#Sta/Elev= 30
  4552.0  424.25  4679.1  417.69  4694.0  416.66  4722.3  416.24  4729.3  415.29
  4757.6  413.94  4770.2  413.98  4807.5  412.57  4817.9  411.65  4830.0  409.34
  4894.0  408.62  4942.7  407.94  4972.6  409.27  4987.8  408.17  4994.7  404.99
  4998.3  404.60  4998.6  404.10  5002.3  404.60  5016.8  406.89  5032.9  408.14
  5038.9  409.60  5061.0  411.60  5083.1  412.01  5121.7  414.65  5127.3  413.87
  5129.9  414.78  5210.4  417.93  5418.2  426.20  5447.2  428.28  5499.2  430.55
#Mann=7,-1,0
  4552.0    0.16       0  4679.1    0.05       0  4770.2    0.16       0
  4894.0    0.12       0  4998.3    0.07       0  5002.3    0.12       0
  5210.4    0.16       0
Bank Sta=4998.3,5002.3
Exp/Cntr=0.3,0.1

Type RM Length L Ch R = 1,5996,183,183,183
BEGIN DESCRIPTION:
DOGWOOD CREEK WEST 14 0
END DESCRIPTION:
XS GIS Cut Line= 3
      3498484.55     10412392.26      3498853.50     10411919.14
      3499138.41     10411677.74
#Sta/Elev= 30
  4294.6  423.28  4350.0  420.06  4407.9  418.93  4449.5  417.06  4492.9  416.91
  4599.7  413.74  4635.8  413.88  4677.5  411.91  4720.9  411.32  4749.4  410.18
  4841.2  407.59  4914.4  406.90  4956.0  406.73  4962.6  405.79  4970.3  406.74
  4976.9  406.21  4984.5  406.81  5003.4  404.00  5003.7  403.50  5007.2  403.50
  5007.4  404.00  5008.9  405.22  5012.0  407.74  5026.3  411.00  5040.6  412.04
  5090.0  410.89  5104.3  411.42  5161.4  413.90  5239.4  418.66  5268.0  421.17
#Mann=6,-1,0
  4294.6    0.05       0  4749.4    0.16       0  4914.4    0.12       0
  5003.4    0.07       0  5007.4    0.12       0  5008.9    0.16       0
Bank Sta=5003.4,5007.4
Exp/Cntr=0.3,0.1

Type RM Length L Ch R = 1,5813,310,310,310
BEGIN DESCRIPTION:
DOGWOOD CREEK WEST 13 0
END DESCRIPTION:
XS GIS Cut Line= 3
      3498629.99     10412526.75      3498985.87     10412049.35
      3499144.32     10411901.75
#Sta/Elev= 30
  4323.5  422.21  4356.6  420.52  4365.0  419.16  4371.2  419.72  4379.6  417.60
  4385.8  418.57  4392.2  416.02  4415.0  412.66  4421.2  413.68  4542.2  410.45
  4700.7  408.45  4721.5  407.04  4765.3  407.03  4771.5  406.07  4786.1  406.99
  4900.8  405.69  4907.1  404.81  4914.4  405.63  4921.8  405.04  4957.0  405.70
  4964.3  404.68  4983.2  404.04  5011.6  401.98  5011.9  401.48  5015.6  401.98
  5035.1  405.82  5065.5  407.06  5112.8  410.57  5119.6  412.19  5135.5  413.98
#Mann=5,-1,0
  4323.5    0.05       0  4983.2    0.16       0  5011.6    0.07       0
  5015.6    0.16       0  5065.5     0.1       0
Bank Sta=5011.6,5015.6
Exp/Cntr=0.3,0.1

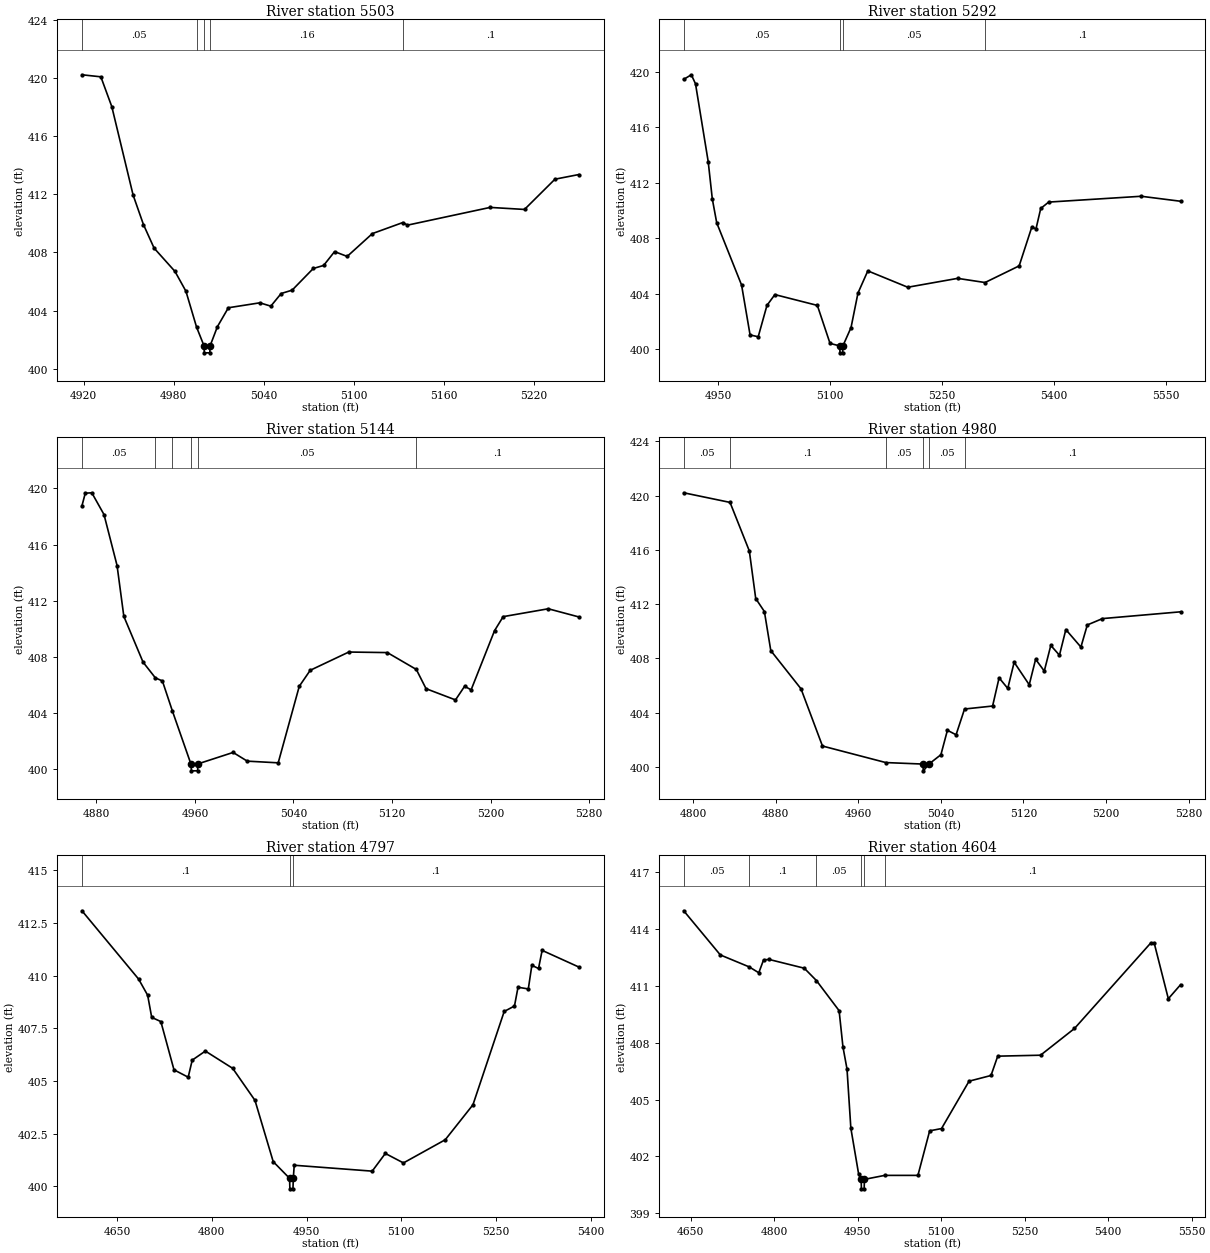
Type RM Length L Ch R = 1,5503,211,211,211
BEGIN DESCRIPTION:
DOGWOOD CREEK WEST 12 2
END DESCRIPTION:
XS GIS Cut Line= 3
      3499199.16     10412256.61      3499320.69     10412128.14
      3499346.63     10411975.98
#Sta/Elev= 30
  4918.9  420.21  4931.5  420.07  4938.8  418.02  4953.0  411.94  4959.9  409.91
  4967.0  408.29  4980.9  406.69  4988.2  405.33  4995.3  402.86  5000.2  401.59
  5000.5  401.09  5004.1  401.09  5004.4  401.59  5009.2  402.89  5016.5  404.19
  5037.5  404.53  5044.8  404.30  5051.7  405.17  5059.0  405.40  5073.1  406.89
  5080.0  407.10  5087.3  408.05  5095.7  407.72  5112.5  409.29  5132.8  410.05
  5135.9  409.87  5191.0  411.09  5213.9  410.95  5234.2  413.03  5250.1  413.35
#Mann=5,-1,0
  4918.9    0.05       0  4995.3    0.16       0  5000.2    0.07       0
  5004.4    0.16       0  5132.8     0.1       0
Bank Sta=5000.2,5004.4
Exp/Cntr=0.3,0.1

Type RM Length L Ch R = 1,5292,148,148,148
BEGIN DESCRIPTION:
DOGWOOD CREEK WEST 12 1
END DESCRIPTION:
XS GIS Cut Line= 3
      3499322.42     10412383.35      3499770.34     10412164.60
      3499796.39     10411999.62
#Sta/Elev= 30
  4904.2  419.47  4914.4  419.80  4920.0  419.15  4937.0  413.54  4942.5  410.85
  4948.4  409.13  4981.7  404.64  4993.1  401.04  5004.0  400.91  5015.7  403.17
  5026.3  403.95  5083.2  403.17  5100.2  400.43  5113.2  400.25  5113.5  399.75
  5117.1  399.75  5117.4  400.25  5128.3  401.57  5137.6  404.06  5150.8  405.66
  5204.3  404.48  5271.1  405.12  5307.8  404.82  5353.5  406.02  5370.5  408.83
  5376.0  408.68  5382.4  410.16  5393.0  410.62  5517.0  411.04  5569.7  410.68
#Mann=4,-1,0
  4904.2    0.05       0  5113.2    0.03       0  5117.4    0.05       0
  5307.8     0.1       0
Bank Sta=5113.2,5117.4
Exp/Cntr=0.3,0.1

Type RM Length L Ch R = 1,5144,164,164,164
BEGIN DESCRIPTION:
DOGWOOD CREEK WEST 11 0
END DESCRIPTION:
XS GIS Cut Line= 2
      3499385.15     10412487.73      3499766.78     10412357.32
#Sta/Elev= 30
  4868.3  418.76  4871.0  419.66  4876.3  419.69  4886.2  418.14  4896.8  414.51
  4902.3  410.89  4917.9  407.63  4927.9  406.51  4933.6  406.29  4941.8  404.13
  4956.7  400.39  4957.2  399.89  4962.1  399.89  4962.6  400.39  4991.0  401.20
  5002.5  400.58  5027.6  400.46  5044.7  405.91  5053.6  407.05  5084.9  408.35
  5116.2  408.31  5139.7  407.11  5147.6  405.74  5171.5  404.94  5178.9  405.91
  5184.2  405.66  5203.2  409.87  5210.2  410.87  5246.8  411.43  5271.6  410.85
#Mann=6,-1,0
  4868.3    0.05       0  4927.9     0.1       0  4941.8    0.05       0
  4956.7    0.03       0  4962.6    0.05       0  5139.7     0.1       0
Bank Sta=4956.7,4962.6
Exp/Cntr=0.3,0.1

Type RM Length L Ch R = 1,4980,183,183,183
BEGIN DESCRIPTION:
DOGWOOD CREEK WEST 10 1
END DESCRIPTION:
XS GIS Cut Line= 2
      3499447.45     10412765.26      3499733.91     10412378.11
#Sta/Elev= 30
  4790.7  420.21  4835.6  419.50  4854.3  415.92  4860.5  412.41  4868.9  411.45
  4875.1  408.57  4904.4  405.75  4925.2  401.53  4986.6  400.31  5022.5  400.20
  5023.0  399.70  5028.4  400.20  5040.0  400.89  5046.3  402.69  5054.7  402.36
  5062.9  404.26  5090.1  404.48  5096.4  406.56  5104.8  405.78  5111.0  407.71
  5125.6  406.05  5131.8  407.93  5140.2  407.06  5146.5  408.95  5154.9  408.23
  5161.1  410.12  5175.7  408.83  5181.9  410.46  5196.6  410.93  5272.3  411.43
#Mann=6,-1,0
  4790.7    0.05       0  4835.6     0.1       0  4986.6    0.05       0
  5022.5    0.03       0  5028.4    0.05       0  5062.9     0.1       0
Bank Sta=5022.5,5028.4
Exp/Cntr=0.3,0.1

Type RM Length L Ch R = 1,4797,193,193,193
BEGIN DESCRIPTION:
DOGWOOD CREEK WEST 9 3
END DESCRIPTION:
XS GIS Cut Line= 4
      3499389.54     10413084.48      3499597.85     10412819.75
      3499734.57     10412650.48      3499844.62     10412445.49
#Sta/Elev= 30
  4594.2  413.08  4683.9  409.84  4698.3  409.07  4704.7  408.02  4719.2  407.82
  4740.0  405.53  4762.5  405.18  4768.9  405.99  4789.7  406.42  4833.0  405.60
  4868.3  404.08  4897.2  401.17  4923.1  400.38  4923.6  399.88  4928.5  399.88
  4929.0  400.38  4930.5  401.00  5054.0  400.72  5074.8  401.56  5103.5  401.11
  5169.7  402.21  5213.6  403.87  5263.1  408.30  5279.4  408.56  5285.0  409.45
  5301.3  409.37  5306.9  410.49  5317.5  410.34  5323.2  411.20  5381.3  410.41
#Mann=3,-1,0
  4594.2     0.1       0  4923.1    0.07       0  4929.0     0.1       0
Bank Sta=4923.1,4929
Exp/Cntr=0.3,0.1

Type RM Length L Ch R = 1,4604,427,427,427
BEGIN DESCRIPTION:
DOGWOOD CREEK WEST 9 1
END DESCRIPTION:
XS GIS Cut Line= 4
      3499577.63     10413263.60      3499608.88     10413055.23
      3499843.26     10412806.96      3499940.48     10412480.56
#Sta/Elev= 30
  4637.6  414.96  4703.4  412.63  4755.2  412.00  4772.5  411.69  4781.1  412.37
  4791.3  412.39  4854.2  411.93  4876.0  411.28  4916.8  409.69  4923.7  407.78
  4931.0  406.61  4937.9  403.49  4952.0  401.05  4956.4  400.79  4956.9  400.29
  4961.8  400.29  4962.3  400.79  4998.7  401.00  5058.4  401.00  5079.5  403.35
  5100.8  403.47  5150.3  405.97  5189.7  406.27  5201.8  407.29  5278.7  407.34
  5339.7  408.75  5477.0  413.27  5482.8  413.27  5508.3  410.32  5530.3  411.06
#Mann=6,-1,0
  4637.6    0.05       0  4755.2     0.1       0  4876.0    0.05       0
  4956.4    0.07       0  4962.3    0.05       0  4998.7     0.1       0
Bank Sta=4956.4,4962.3
Exp/Cntr=0.3,0.1

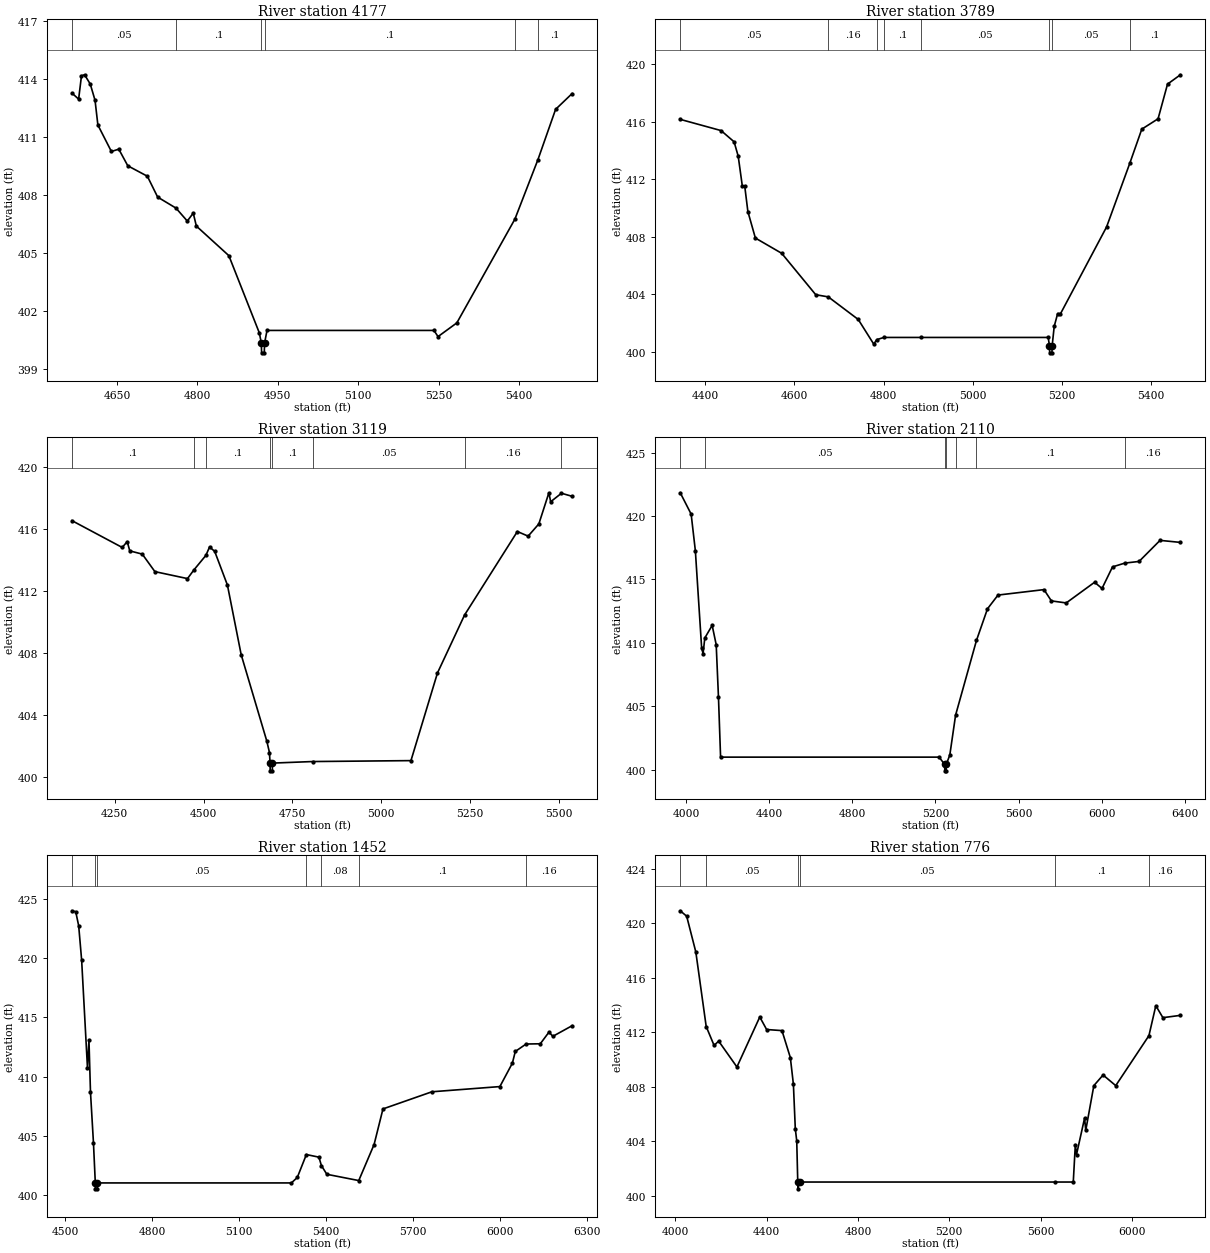
Type RM Length L Ch R = 1,4177,388,388,388
BEGIN DESCRIPTION:
DOGWOOD CREEK WEST 9 2
END DESCRIPTION:
XS GIS Cut Line= 3
      3499680.07     10413322.58      3499898.81     10413242.73
      3500358.87     10412714.96
#Sta/Elev= 30
  4566.2  413.28  4578.6  412.97  4583.9  414.18  4589.7  414.23  4600.3  413.75
  4609.2  412.91  4614.5  411.63  4639.7  410.26  4653.5  410.38  4670.3  409.52
  4706.8  408.98  4726.0  407.90  4760.2  407.33  4781.3  406.66  4792.4  407.07
  4798.2  406.40  4858.8  404.87  4915.7  400.87  4919.4  400.34  4919.9  399.84
  4924.9  399.84  4925.4  400.34  4930.0  401.00  5241.4  401.00  5249.0  400.68
  5284.1  401.39  5392.4  406.76  5435.4  409.84  5468.3  412.44  5499.2  413.26
#Mann=6,-1,0
  4566.2    0.05       0  4760.2     0.1       0  4919.4    0.07       0
  4925.4     0.1       0  5392.4    0.05       0  5435.4     0.1       0
Bank Sta=4919.4,4925.4
Exp/Cntr=0.3,0.1

Type RM Length L Ch R = 1,3789,670,670,670
BEGIN DESCRIPTION:
DOGWOOD CREEK WEST 9 0
END DESCRIPTION:
XS GIS Cut Line= 3
      3499692.07     10413441.66      3500292.11     10413191.64
      3500542.09     10412791.67
#Sta/Elev= 30
  4343.8  416.16  4435.4  415.38  4464.6  414.60  4473.8  413.60  4483.0  411.53
  4488.5  411.50  4495.5  409.75  4512.3  407.91  4571.3  406.85  4647.7  403.97
  4675.8  403.82  4743.0  402.25  4777.7  400.54  4784.7  400.85  4800.5  401.00
  4884.0  401.00  5169.0  401.00  5171.8  400.43  5172.3  399.93  5177.4  399.93
  5177.9  400.43  5182.5  401.77  5190.2  402.66  5196.1  402.62  5299.9  408.68
  5351.9  413.10  5378.9  415.48  5415.4  416.20  5436.6  418.61  5465.5  419.26
#Mann=8,-1,0
  4343.8    0.05       0  4675.8    0.16       0  4784.7    0.05       0
  4800.5     0.1       0  4884.0    0.05       0  5171.8   0.033       0
  5177.9    0.05       0  5351.9     0.1       0
Bank Sta=5171.8,5177.9
Exp/Cntr=0.3,0.1

Type RM Length L Ch R = 1,3119,1009,1009,1009
BEGIN DESCRIPTION:
DOGWOOD CREEK WEST 8 1
END DESCRIPTION:
XS GIS Cut Line= 3
      3499711.41     10413991.08      3499977.15     10413730.31
      3501005.15     10413598.71
#Sta/Elev= 30
  4129.6  416.55  4271.1  414.82  4285.2  415.20  4292.3  414.60  4327.6  414.39
  4363.1  413.26  4454.9  412.81  4473.0  413.37  4506.8  414.31  4517.0  414.85
  4531.5  414.57  4567.4  412.39  4606.1  407.90  4678.3  402.32  4685.8  401.58
  4687.4  400.90  4687.9  400.40  4693.8  400.40  4694.3  400.90  4807.2  401.00
  5084.3  401.06  5159.0  406.72  5235.3  410.46  5384.0  415.85  5414.3  415.55
  5444.5  416.34  5472.8  418.35  5477.8  417.77  5508.2  418.32  5538.3  418.12
#Mann=8,-1,0
  4129.6     0.1       0  4473.0    0.16       0  4506.8     0.1       0
  4687.4   0.033       0  4694.3     0.1       0  4807.2    0.05       0
  5235.3    0.16       0  5508.2     0.1       0
Bank Sta=4687.4,4694.3
Exp/Cntr=0.3,0.1

Type RM Length L Ch R = 1,2110,658,658,658
BEGIN DESCRIPTION:
DOGWOOD CREEK WEST 7 0
END DESCRIPTION:
XS GIS Cut Line= 3
      3499530.18     10414713.65      3501077.20     10414475.26
      3501765.05     10413988.56
#Sta/Elev= 30
  3971.4  421.83  4023.9  420.15  4044.2  417.26  4074.5  409.59  4081.3  409.16
  4089.7  410.39  4125.1  411.38  4144.5  409.86  4155.5  405.70  4165.6  401.00
  5217.9  401.00  5244.5  400.42  5245.0  399.92  5251.5  399.92  5252.0  400.42
  5269.2  401.17  5297.0  404.31  5397.6  410.20  5450.6  412.69  5501.2  413.77
  5722.5  414.20  5758.2  413.31  5829.6  413.15  5966.2  414.78  6001.9  414.29
  6052.4  415.99  6111.9  416.29  6180.3  416.42  6281.3  418.08  6379.3  417.92
#Mann=7,-1,0
  3971.4     0.1       0  4089.7    0.05       0  5244.5   0.033       0
  5252.0    0.05       0  5297.0    0.16       0  5397.6     0.1       0
  6111.9    0.16       0
Bank Sta=5244.5,5252
Exp/Cntr=0.3,0.1

Type RM Length L Ch R = 1,1452,676,676,676
BEGIN DESCRIPTION:
DOGWOOD CREEK WEST 5 0
END DESCRIPTION:
XS GIS Cut Line= 3
      3500369.46     10415227.67      3501514.24     10415006.67
      3501792.34     10414522.47
#Sta/Elev= 30
  4524.2  424.02  4537.1  423.94  4547.3  422.75  4557.5  419.84  4577.6  410.73
  4582.7  413.09  4588.0  408.66  4598.2  404.40  4604.6  401.00  4605.1  400.50
  4611.6  400.50  4612.1  401.00  5280.6  401.00  5300.9  401.46  5332.2  403.40
  5375.5  403.18  5384.0  402.47  5402.8  401.73  5512.8  401.20  5565.7  404.25
  5596.3  407.26  5765.1  408.71  5999.3  409.15  6042.4  411.13  6052.5  412.12
  6089.7  412.75  6138.7  412.77  6168.7  413.76  6181.9  413.40  6248.5  414.30
#Mann=7,-1,0
  4524.2    0.05       0  4604.6   0.033       0  4612.1    0.05       0
  5332.2     0.1       0  5384.0    0.08       0  5512.8     0.1       0
  6089.7    0.16       0
Bank Sta=4604.6,4612.1
Exp/Cntr=0.3,0.1

Type RM Length L Ch R = 1,776,0,0,0
BEGIN DESCRIPTION:
DOGWOOD CREEK WEST 1 0
END DESCRIPTION:
XS GIS Cut Line= 4
      3500453.87     10415895.64      3500866.13     10415883.23
      3501635.91     10415309.61      3501842.03     10414517.43
#Sta/Elev= 30
  4021.7  420.92  4049.9  420.52  4090.0  417.89  4135.4  412.42  4170.0  411.03
  4190.0  411.35  4270.0  409.45  4370.1  413.12  4400.1  412.20  4467.3  412.12
  4504.0  410.14  4517.4  408.18  4525.7  404.92  4532.0  404.02  4536.5  401.00
  4537.0  400.50  4544.2  401.00  5663.3  401.00  5743.4  401.00  5752.4  403.75
  5757.6  403.02  5792.9  405.69  5798.1  404.80  5833.5  408.08  5874.0  408.86
  5929.4  408.08  6074.8  411.75  6105.0  413.95  6136.0  413.07  6212.7  413.24
#Mann=6,-1,0
  4021.7     0.1       0  4135.4    0.05       0  4536.5   0.033       0
  4544.2    0.05       0  5663.3     0.1       0  6074.8    0.16       0
Bank Sta=4536.5,4544.2
Exp/Cntr=0.3,0.1

Chan Stop Cuts=-1