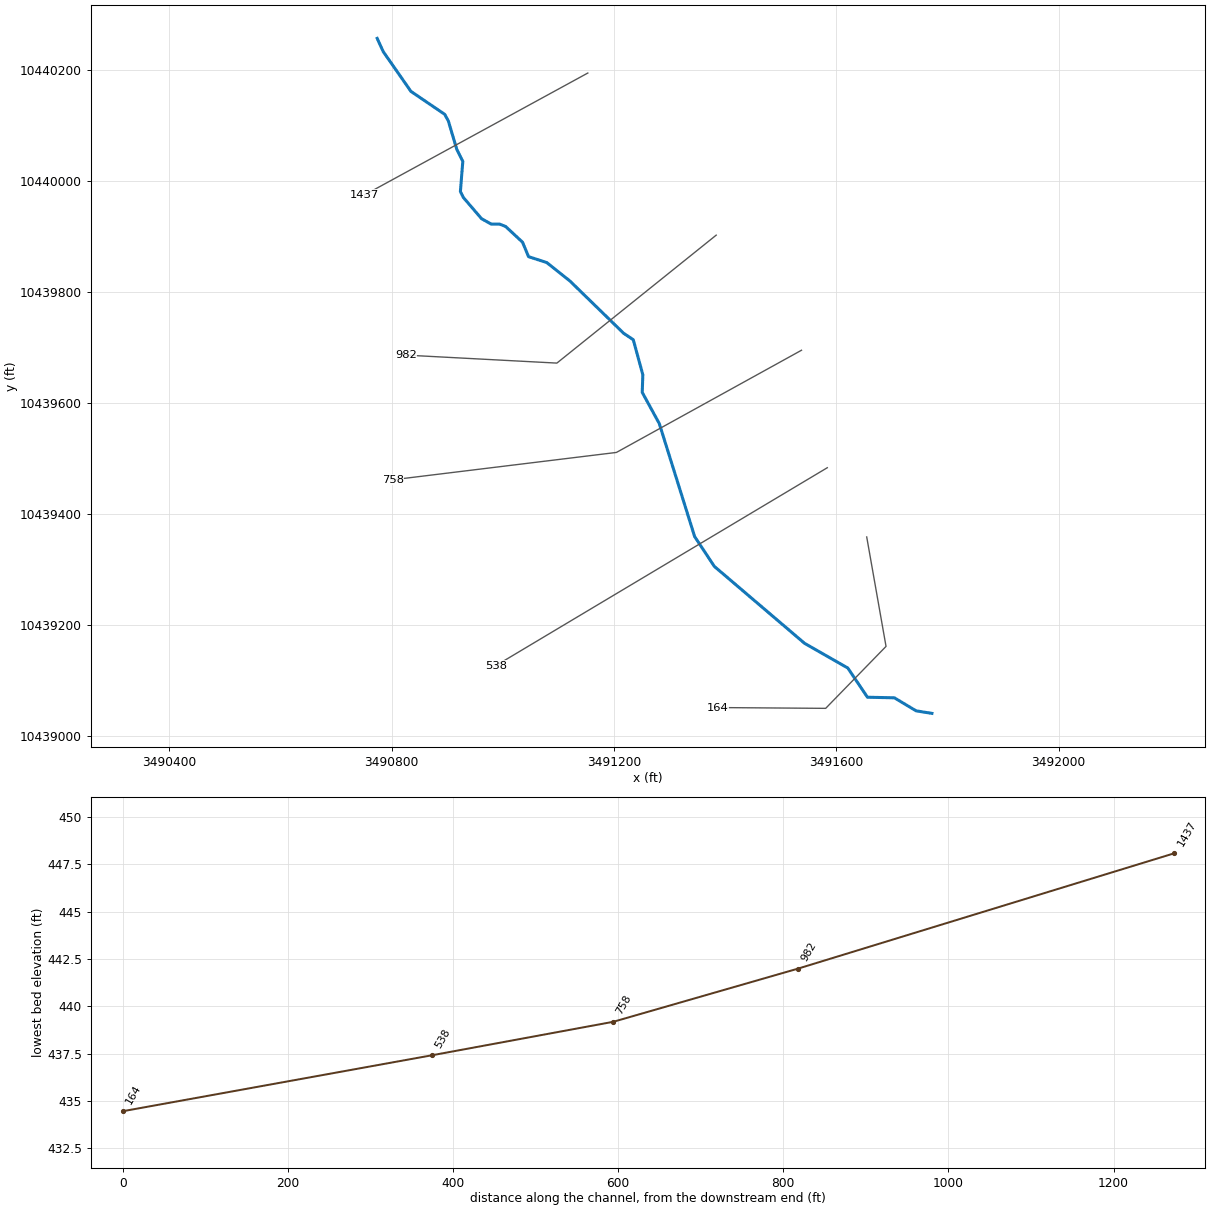
--- DUCK CR TRIB 43 1.prj (project) ---

Proj Title=DUCK CR TRIB 43 1 Base Level Engineering
Current Plan=p01
Default Exp/Contr=0.3,0.1
English Units
Geom File=g01
Flow File=f01
Plan File=p01
BEGIN DESCRIPTION:
DUCK CR TRIB 43 1
END DESCRIPTION:

--- DUCK CR TRIB 43 1.p01 (plan) ---

Plan Title=Multiple Run
Short Identifier=Multiple
Geom File=g01
Flow File=f01
Subcritical Flow
K Sum by GR= 0
Std Step Tol= 0.01
Critical Tol= 0.01
Num of Std Step Trials= 20
Max Error Tol= 0.3
Flow Tol Ratio= 0.001
Split Flow NTrial= 30
Split Flow Tol= 0.02
Split Flow Ratio= 0.02
Log Output Level= 0
Friction Slope Method= 1
Unsteady Friction Slope Method= 2
Unsteady Bridges Friction Slope Method= 1
Parabolic Critical Depth
Global Vel Dist=  1 , 1 , 1
Global Log Level= 0
CheckData=True
Encroach Param= -1, 0, 0, 0
BEGIN DESCRIPTION:
Multiple Run
END DESCRIPTION:

--- DUCK CR TRIB 43 1.f01 (steady flow) ---

Flow Title=Multiple
Number of Profiles=7
Profile Names=10-year,25-year,50-year,1pct_min,100-year,1pct_plu,500-year
River Rch & RM= DUCK CR TRIB 43 ,Reach-1,1437
     220     274     315     266     360     486     465
Boundary for River Rch & Prof#=DUCK CR TRIB 43 ,Reach-1,1
Up Type=0
Dn Type=3
Dn Slope=0.005
Boundary for River Rch & Prof#=DUCK CR TRIB 43 ,Reach-1,2
Up Type=0
Dn Type=3
Dn Slope=0.005
Boundary for River Rch & Prof#=DUCK CR TRIB 43 ,Reach-1,3
Up Type=0
Dn Type=3
Dn Slope=0.005
Boundary for River Rch & Prof#=DUCK CR TRIB 43 ,Reach-1,4
Up Type=0
Dn Type=3
Dn Slope=0.005
Boundary for River Rch & Prof#=DUCK CR TRIB 43 ,Reach-1,5
Up Type=0
Dn Type=3
Dn Slope=0.005
Boundary for River Rch & Prof#=DUCK CR TRIB 43 ,Reach-1,6
Up Type=0
Dn Type=3
Dn Slope=0.005
Boundary for River Rch & Prof#=DUCK CR TRIB 43 ,Reach-1,7
Up Type=0
Dn Type=3
Dn Slope=0.005

--- DUCK CR TRIB 43 1.g01 (geometry) ---

Geom Title=Existing Conditions

River Reach=DUCK CR TRIB 43 ,Reach-1
Reach XY= 30
      3490773.91     10440256.11      3490784.76     10440232.24
      3490834.67     10440160.63      3490895.43     10440119.39
      3490901.94     10440107.46      3490917.13     10440056.46
      3490927.99     10440034.76      3490923.65     10439980.51
      3490929.07     10439969.65      3490961.62     10439931.68
      3490978.98     10439921.91      3490994.17     10439921.91
      3491005.03     10439917.57      3491035.41     10439889.36
      3491046.26     10439863.32      3491079.11     10439852.63
      3491120.61     10439819.60      3491217.48     10439725.33
      3491234.67     10439713.87      3491251.86     10439650.85
      3491250.82     10439619.08      3491281.54     10439562.83
      3491345.09     10439359.70      3491380.50     10439306.06
      3491543.00     10439167.52      3491620.61     10439123.25
      3491656.02     10439070.64      3491704.46     10439069.60
      3491743.52     10439046.16      3491771.95     10439041.59

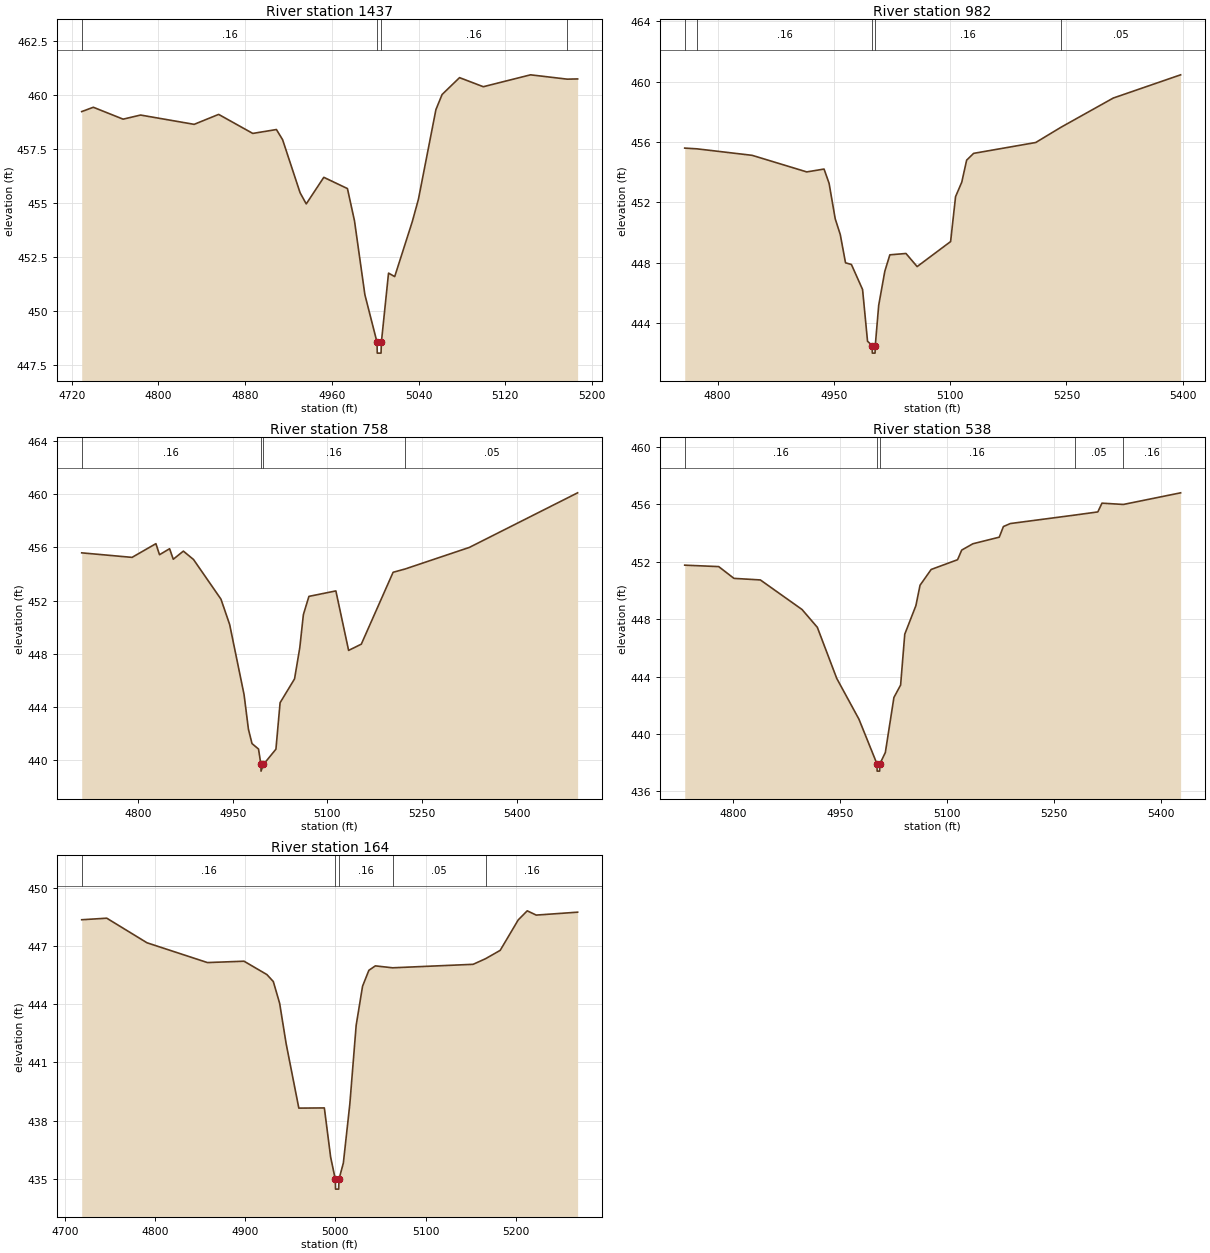
Type RM Length L Ch R = 1,1437,455,455,455
BEGIN DESCRIPTION:
DUCK CR TRIB 43 1 7
END DESCRIPTION:
XS GIS Cut Line= 2
      3491152.93     10440193.70      3490751.46     10439974.52
#Sta/Elev= 30
  4729.3  459.24  4740.0  459.44  4767.5  458.89  4783.6  459.08  4833.0  458.65
  4855.6  459.11  4887.1  458.23  4908.9  458.41  4914.6  457.94  4930.7  455.49
  4936.4  454.97  4952.6  456.20  4974.4  455.68  4980.9  454.19  4990.5  450.77
  5001.7  448.57  5001.9  448.07  5005.4  448.07  5005.7  448.57  5012.3  451.77
  5018.0  451.61  5034.2  454.15  5039.9  455.19  5056.0  459.33  5061.7  460.03
  5077.8  460.81  5099.7  460.39  5143.3  460.94  5177.1  460.74  5186.7  460.75
#Mann=4,-1,0
  4729.3    0.16       0  5001.7    0.07       0  5005.7    0.16       0
  5177.1    0.05       0
Bank Sta=5001.7,5005.7
Exp/Cntr=0.3,0.1

Type RM Length L Ch R = 1,982,224,224,224
BEGIN DESCRIPTION:
DUCK CR TRIB 43 1 6
END DESCRIPTION:
XS GIS Cut Line= 3
      3491383.90     10439902.01      3491097.22     10439671.80
      3490825.37     10439686.18
#Sta/Elev= 30
  4757.5  455.59  4773.4  455.54  4844.5  455.11  4915.0  454.01  4937.3  454.20
  4943.8  453.25  4951.7  450.90  4958.2  449.86  4965.0  447.98  4972.6  447.87
  4987.0  446.21  4993.4  442.78  4999.4  442.49  4999.6  441.99  5003.1  441.99
  5003.4  442.49  5007.8  445.16  5015.7  447.42  5022.2  448.51  5043.0  448.60
  5057.4  447.73  5100.6  449.39  5107.0  452.37  5115.0  453.33  5121.3  454.79
  5130.3  455.24  5210.4  455.96  5243.3  456.98  5310.5  458.91  5397.4  460.45
#Mann=5,-1,0
  4757.5    0.05       0  4773.4    0.16       0  4999.4    0.07       0
  5003.4    0.16       0  5243.3    0.05       0
Bank Sta=4999.4,5003.4
Exp/Cntr=0.3,0.1

Type RM Length L Ch R = 1,758,220,220,220
BEGIN DESCRIPTION:
DUCK CR TRIB 43 1 2 1
END DESCRIPTION:
XS GIS Cut Line= 3
      3491537.37     10439694.94      3491204.37     10439511.07
      3490801.86     10439461.84
#Sta/Elev= 30
  4710.8  455.58  4790.6  455.24  4828.4  456.27  4834.1  455.44  4850.1  455.89
  4855.9  455.10  4871.9  455.71  4888.0  455.08  4931.5  452.10  4945.3  450.19
  4968.1  444.93  4975.0  442.33  4980.7  441.25  4991.0  440.84  4994.8  439.68
  4995.0  439.18  4998.8  439.68  5018.6  440.83  5025.2  444.32  5048.1  446.11
  5056.4  448.45  5062.1  450.94  5070.9  452.31  5113.6  452.72  5133.8  448.25
  5153.9  448.72  5204.3  454.12  5223.5  454.37  5325.2  455.99  5496.7  460.09
#Mann=4,-1,0
  4710.8    0.16       0  4994.8    0.07       0  4998.8    0.16       0
  5223.5    0.05       0
Bank Sta=4994.8,4998.8
Exp/Cntr=0.3,0.1

Type RM Length L Ch R = 1,538,374,374,374
BEGIN DESCRIPTION:
DUCK CR TRIB 43 1 5
END DESCRIPTION:
XS GIS Cut Line= 2
      3491583.76     10439483.57      3490987.21     10439127.38
#Sta/Elev= 30
  4732.3  451.76  4779.9  451.66  4801.3  450.84  4838.3  450.73  4896.7  448.67
  4918.1  447.43  4945.3  443.87  4976.4  441.03  5001.7  437.91  5001.9  437.41
  5005.4  437.41  5005.7  437.91  5013.4  438.71  5025.4  442.54  5034.8  443.41
  5040.6  446.95  5056.2  448.94  5062.0  450.36  5077.6  451.46  5114.6  452.14
  5120.4  452.81  5136.0  453.25  5173.0  453.71  5178.8  454.45  5188.5  454.66
  5278.8  455.25  5311.1  455.47  5316.9  456.08  5346.9  455.99  5427.1  456.80
#Mann=5,-1,0
  4732.3    0.16       0  5001.7    0.07       0  5005.7    0.16       0
  5278.8    0.05       0  5346.9    0.16       0
Bank Sta=5001.7,5005.7
Exp/Cntr=0.3,0.1

Type RM Length L Ch R = 1,164,0,0,0
BEGIN DESCRIPTION:
DUCK CR TRIB 43 1 1 0
END DESCRIPTION:
XS GIS Cut Line= 4
      3491654.69     10439359.03      3491689.44     10439162.11
      3491580.85     10439050.62      3491386.25     10439052.06
#Sta/Elev= 30
  4718.5  448.36  4746.3  448.44  4791.0  447.17  4858.0  446.15  4898.6  446.22
  4924.0  445.53  4931.1  445.17  4938.1  444.05  4945.3  441.97  4959.4  438.64
  4987.7  438.65  4994.7  436.11  4999.9  434.96  5000.1  434.46  5003.6  434.46
  5003.9  434.96  5008.8  435.81  5016.0  438.86  5023.0  442.91  5030.1  444.93
  5037.1  445.75  5044.3  445.98  5063.4  445.88  5152.8  446.06  5166.6  446.35
  5182.8  446.78  5202.8  448.35  5212.8  448.82  5222.8  448.60  5268.7  448.75
#Mann=5,-1,0
  4718.5    0.16       0  4999.9    0.07       0  5003.9    0.16       0
  5063.4    0.05       0  5166.6    0.16       0
Bank Sta=4999.9,5003.9
Exp/Cntr=0.3,0.1

Chan Stop Cuts=-1