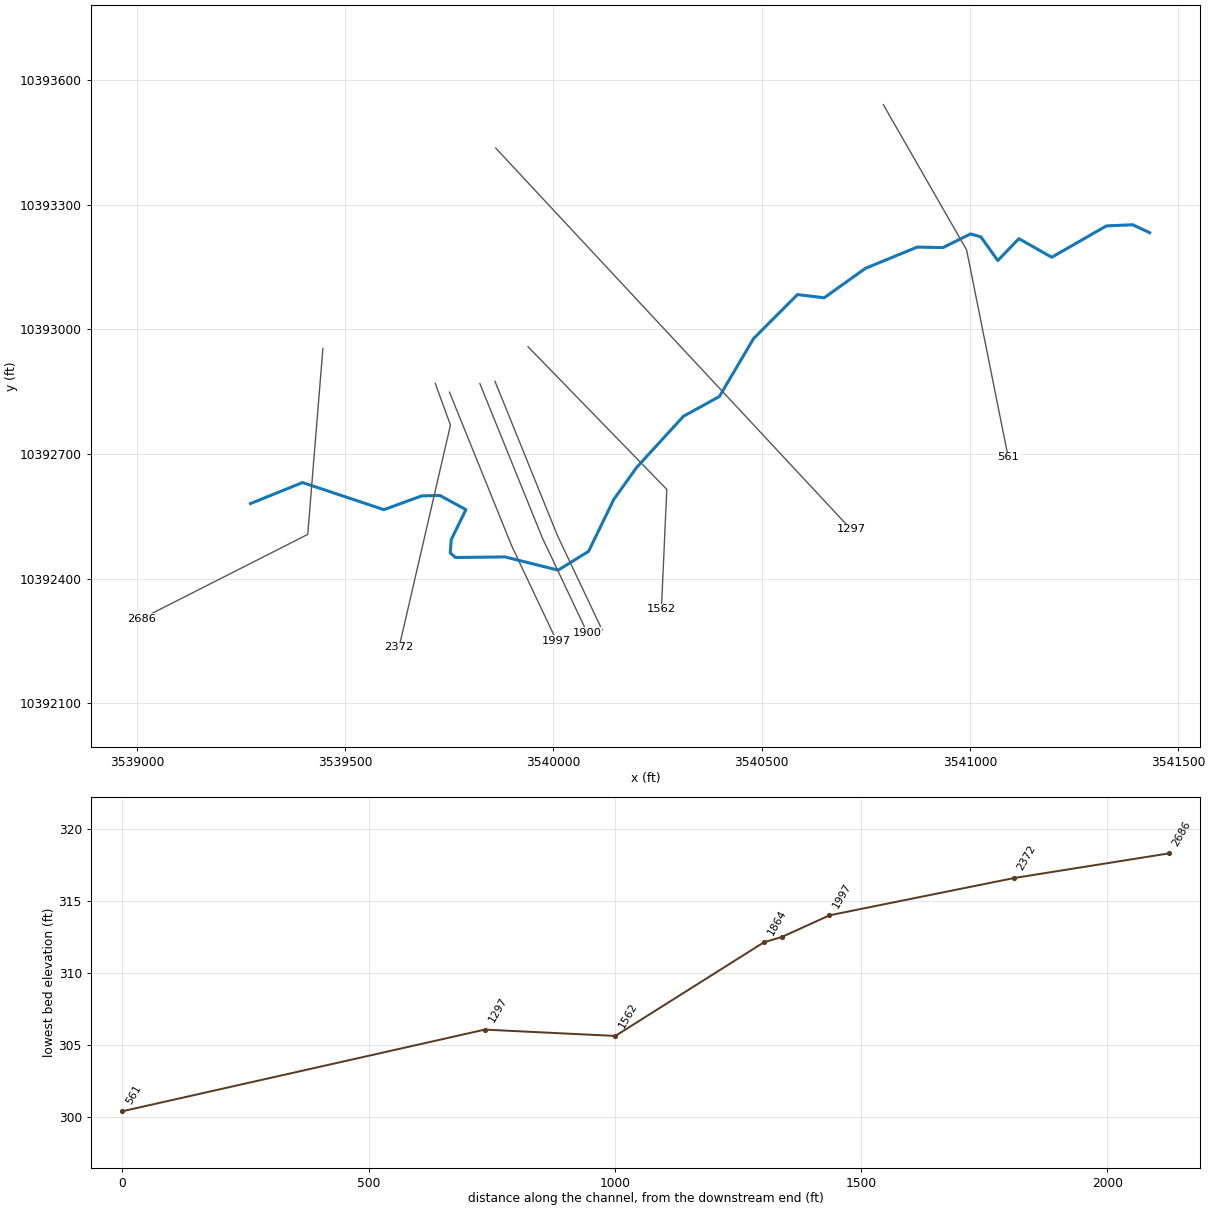
--- DUCK CREEK TRIB 12.prj (project) ---

Proj Title=DUCK CREEK TRIB 12 Base Level Engineering
Current Plan=p01
Default Exp/Contr=0.3,0.1
English Units
Geom File=g01
Flow File=f01
Plan File=p01
BEGIN DESCRIPTION:
DUCK CREEK TRIB 12
END DESCRIPTION:

--- DUCK CREEK TRIB 12.p01 (plan) ---

Plan Title=Multiple Run
Short Identifier=Multiple
Geom File=g01
Flow File=f01
Subcritical Flow
K Sum by GR= 0
Std Step Tol= 0.01
Critical Tol= 0.01
Num of Std Step Trials= 20
Max Error Tol= 0.3
Flow Tol Ratio= 0.001
Split Flow NTrial= 30
Split Flow Tol= 0.02
Split Flow Ratio= 0.02
Log Output Level= 0
Friction Slope Method= 1
Unsteady Friction Slope Method= 2
Unsteady Bridges Friction Slope Method= 1
Parabolic Critical Depth
Global Vel Dist=  1 , 1 , 1
Global Log Level= 0
CheckData=True
Encroach Param= -1, 0, 0, 0
BEGIN DESCRIPTION:
Multiple Run
END DESCRIPTION:

--- DUCK CREEK TRIB 12.f01 (steady flow) ---

Flow Title=Multiple
Number of Profiles=7
Profile Names=10-year,25-year,50-year,1pct_min,100-year,1pct_plu,500-year
River Rch & RM= DUCK CREEK TRIB ,Reach-1,2686
     993    1376    1693    1521    2057    2782    3030
Boundary for River Rch & Prof#=DUCK CREEK TRIB ,Reach-1,1
Up Type=0
Dn Type=3
Dn Slope=0.005
Boundary for River Rch & Prof#=DUCK CREEK TRIB ,Reach-1,2
Up Type=0
Dn Type=3
Dn Slope=0.005
Boundary for River Rch & Prof#=DUCK CREEK TRIB ,Reach-1,3
Up Type=0
Dn Type=3
Dn Slope=0.005
Boundary for River Rch & Prof#=DUCK CREEK TRIB ,Reach-1,4
Up Type=0
Dn Type=3
Dn Slope=0.005
Boundary for River Rch & Prof#=DUCK CREEK TRIB ,Reach-1,5
Up Type=0
Dn Type=3
Dn Slope=0.005
Boundary for River Rch & Prof#=DUCK CREEK TRIB ,Reach-1,6
Up Type=0
Dn Type=3
Dn Slope=0.005
Boundary for River Rch & Prof#=DUCK CREEK TRIB ,Reach-1,7
Up Type=0
Dn Type=3
Dn Slope=0.005

--- DUCK CREEK TRIB 12.g01 (geometry) ---

Geom Title=Existing Conditions

River Reach=DUCK CREEK TRIB ,Reach-1
Reach XY= 30
      3539272.35     10392580.57      3539397.31     10392631.28
      3539592.74     10392565.90      3539683.38     10392599.11
      3539727.03     10392600.19      3539789.61     10392566.06
      3539754.37     10392493.49      3539752.11     10392461.64
      3539764.66     10392450.68      3539883.45     10392452.10
      3540011.26     10392420.26      3540084.32     10392465.61
      3540144.77     10392590.54      3540199.87     10392667.85
      3540311.86     10392790.74      3540398.35     10392838.49
      3540480.44     10392977.99      3540585.95     10393084.10
      3540649.89     10393076.30      3540749.18     10393147.28
      3540873.50     10393198.48      3540935.25     10393197.27
      3541001.54     10393230.15      3541026.39     10393223.11
      3541067.02     10393166.04      3541117.69     10393218.76
      3541196.57     10393173.95      3541327.84     10393249.55
      3541390.97     10393252.27      3541431.82     10393233.14

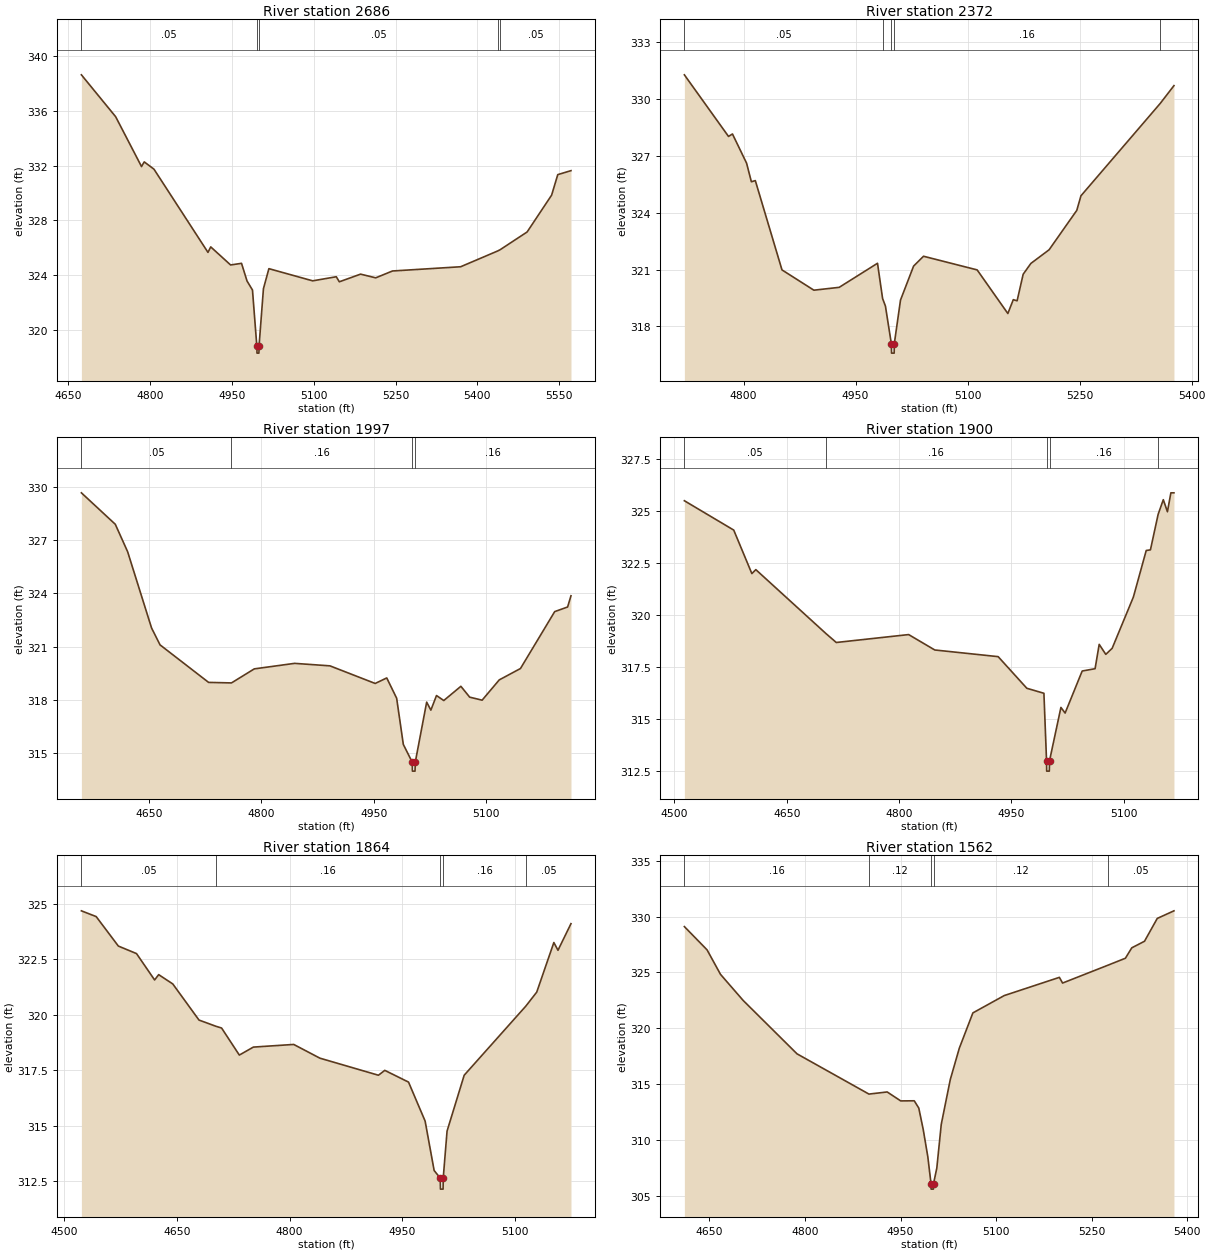
Type RM Length L Ch R = 1,2686,314,314,314
BEGIN DESCRIPTION:
DUCK CREEK TRIB 12 11 0
END DESCRIPTION:
XS GIS Cut Line= 3
      3539446.23     10392954.22      3539409.77     10392506.29
      3539010.48     10392303.17
#Sta/Elev= 30
  4674.1  338.63  4736.9  335.57  4784.3  331.93  4789.3  332.27  4807.1  331.74
  4906.1  325.66  4911.2  326.06  4947.6  324.74  4967.6  324.86  4977.7  323.57
  4987.7  322.91  4995.7  318.80  4996.0  318.30  4999.5  318.30  4999.7  318.80
  5007.8  323.01  5017.8  324.47  5098.1  323.58  5141.3  323.88  5146.9  323.51
  5185.8  324.07  5213.6  323.80  5244.3  324.30  5369.3  324.61  5437.0  325.76
  5441.5  325.85  5491.1  327.15  5536.0  329.84  5547.3  331.34  5571.5  331.63
#Mann=5,-1,0
  4674.1    0.05       0  4995.7    0.03       0  4999.7    0.05       0
  5437.0    0.16       0  5441.5    0.05       0
Bank Sta=4995.7,4999.7
Exp/Cntr=0.3,0.1

Type RM Length L Ch R = 1,2372,375,375,375
BEGIN DESCRIPTION:
DUCK CREEK TRIB 12 6 0
END DESCRIPTION:
XS GIS Cut Line= 3
      3539716.10     10392869.94      3539752.56     10392769.67
      3539629.25     10392234.90
#Sta/Elev= 30
  4720.8  331.27  4779.9  328.02  4785.2  328.15  4804.1  326.61  4810.5  325.63
  4815.8  325.69  4851.5  320.98  4894.2  319.91  4928.1  320.06  4979.4  321.33
  4986.2  319.47  4990.0  319.07  4997.9  317.09  4998.2  316.59  5001.7  316.59
  5001.9  317.09  5010.2  319.39  5027.7  321.18  5041.0  321.70  5112.8  320.98
  5153.9  318.68  5161.2  319.41  5166.3  319.35  5174.4  320.75  5184.7  321.32
  5209.1  322.04  5246.2  324.12  5251.8  324.89  5357.9  329.76  5376.3  330.70
#Mann=5,-1,0
  4720.8    0.05       0  4986.2    0.16       0  4997.9    0.07       0
  5001.9    0.16       0  5357.9    0.05       0
Bank Sta=4997.9,5001.9
Exp/Cntr=0.3,0.1

Type RM Length L Ch R = 1,1997,97,97,97
BEGIN DESCRIPTION:
DUCK CREEK TRIB 12 10
END DESCRIPTION:
XS GIS Cut Line= 3
      3539750.29     10392848.81      3539900.04     10392477.68
      3540007.61     10392249.58
#Sta/Elev= 30
  4560.3  329.65  4605.5  327.88  4621.9  326.34  4653.8  322.05  4665.1  321.10
  4729.8  318.99  4760.3  318.96  4790.7  319.75  4844.4  320.06  4891.5  319.92
  4951.8  318.93  4967.2  319.24  4980.4  318.10  4989.3  315.50  5001.2  314.50
  5001.4  314.00  5004.9  314.00  5005.2  314.50  5020.4  317.88  5026.0  317.43
  5033.5  318.25  5043.2  317.97  5066.0  318.77  5077.7  318.16  5094.3  317.99
  5117.1  319.13  5145.4  319.77  5191.0  322.97  5208.2  323.23  5212.7  323.86
#Mann=4,-1,0
  4560.3    0.05       0  4760.3    0.16       0  5001.2    0.07       0
  5005.2    0.16       0
Bank Sta=5001.2,5005.2
Exp/Cntr=0.3,0.1

Type RM Length L Ch R = 1,1900,36,36,36
BEGIN DESCRIPTION:
DUCK CREEK TRIB 12 4 2
END DESCRIPTION:
XS GIS Cut Line= 3
      3539823.20     10392869.65      3539972.96     10392498.51
      3540081.04     10392269.33
#Sta/Elev= 30
  4513.3  325.48  4579.2  324.07  4603.4  321.98  4608.7  322.17  4702.6  319.09
  4716.1  318.67  4812.7  319.05  4847.6  318.31  4932.2  317.99  4970.5  316.47
  4993.3  316.23  4996.8  312.99  4997.0  312.49  5000.5  312.49  5000.8  312.99
  5016.0  315.55  5021.6  315.28  5044.4  317.30  5061.6  317.41  5067.1  318.58
  5075.9  318.10  5084.4  318.39  5112.7  320.85  5129.9  323.09  5135.5  323.12
  5145.8  324.83  5152.7  325.53  5158.2  324.95  5162.8  325.86  5166.9  325.86
#Mann=5,-1,0
  4513.3    0.05       0  4702.6    0.16       0  4996.8    0.07       0
  5000.8    0.16       0  5145.8    0.05       0
Bank Sta=4996.8,5000.8
Exp/Cntr=0.3,0.1

Type RM Length L Ch R = 1,1864,302,302,302
BEGIN DESCRIPTION:
DUCK CREEK TRIB 12 4 3
END DESCRIPTION:
XS GIS Cut Line= 3
      3539859.69     10392874.77      3540009.42     10392503.72
      3540116.81     10392275.99
#Sta/Elev= 30
  4522.8  324.69  4542.5  324.43  4572.0  323.10  4596.2  322.76  4620.3  321.57
  4625.7  321.81  4644.5  321.39  4679.4  319.76  4701.9  319.48  4709.5  319.40
  4733.1  318.18  4751.8  318.54  4805.5  318.66  4840.4  318.04  4918.3  317.27
  4926.8  317.49  4958.4  316.96  4980.5  315.20  4992.5  312.97  5000.6  312.63
  5000.9  312.13  5004.4  312.13  5004.6  312.63  5009.7  314.75  5032.5  317.27
  5114.6  320.39  5129.1  321.02  5151.9  323.26  5157.4  322.91  5174.7  324.11
#Mann=5,-1,0
  4522.8    0.05       0  4701.9    0.16       0  5000.6    0.07       0
  5004.6    0.16       0  5114.6    0.05       0
Bank Sta=5000.6,5004.6
Exp/Cntr=0.3,0.1

Type RM Length L Ch R = 1,1562,265,265,265
BEGIN DESCRIPTION:
DUCK CREEK TRIB 12 4 1
END DESCRIPTION:
XS GIS Cut Line= 3
      3539938.74     10392958.50      3540272.09     10392614.73
      3540259.12     10392325.47
#Sta/Elev= 30
  4610.7  329.10  4646.3  327.02  4667.4  324.83  4702.9  322.50  4787.5  317.72
  4900.4  314.12  4929.0  314.31  4950.3  313.51  4971.5  313.52  4978.6  312.87
  4985.6  310.95  4992.8  308.51  4997.8  306.12  4998.0  305.62  5001.5  305.62
  5001.8  306.12  5006.9  307.50  5013.9  311.42  5028.1  315.43  5042.2  318.22
  5063.5  321.38  5112.7  322.93  5199.3  324.56  5204.3  324.05  5275.2  325.64
  5302.9  326.27  5312.9  327.20  5332.9  327.79  5352.9  329.83  5379.1  330.51
#Mann=5,-1,0
  4610.7    0.16       0  4900.4    0.12       0  4997.8    0.07       0
  5001.8    0.12       0  5275.2    0.05       0
Bank Sta=4997.8,5001.8
Exp/Cntr=0.3,0.1

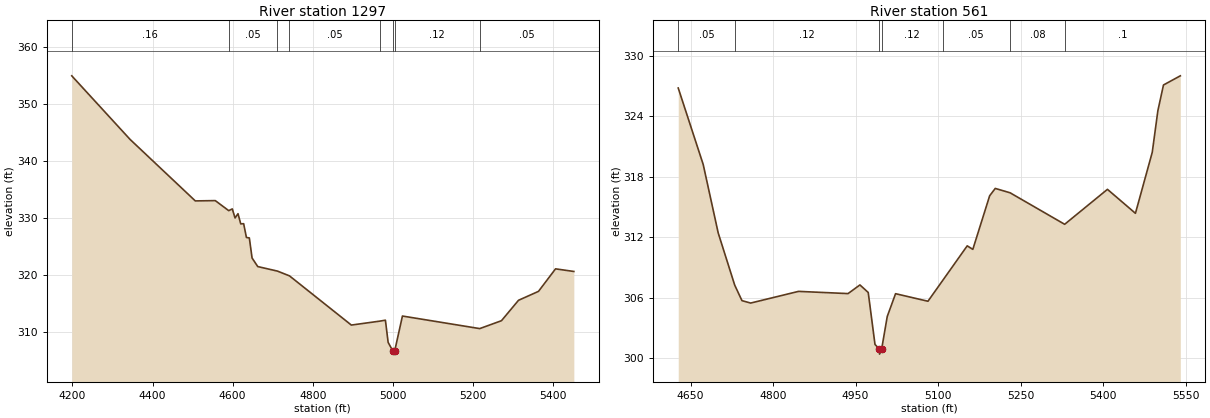
Type RM Length L Ch R = 1,1297,736,736,736
BEGIN DESCRIPTION:
DUCK CREEK TRIB 12 2 1
END DESCRIPTION:
XS GIS Cut Line= 2
      3539861.30     10393436.89      3540714.13     10392518.78
#Sta/Elev= 30
  4198.4  355.01  4344.0  343.82  4506.7  333.01  4556.6  333.06  4590.1  331.30
  4599.1  331.60  4605.9  330.01  4613.3  330.76  4620.1  328.97  4627.4  329.00
  4634.3  326.58  4641.6  326.50  4648.4  322.97  4662.6  321.46  4711.4  320.67
  4741.7  319.83  4896.2  311.17  4967.8  311.87  4981.2  312.03  4988.0  308.13
  5000.2  306.56  5000.4  306.06  5004.2  306.56  5023.7  312.76  5216.6  310.55
  5270.9  311.94  5313.4  315.53  5363.3  317.10  5405.8  321.06  5451.5  320.60
#Mann=8,-1,0
  4198.4    0.16       0  4590.1    0.05       0  4711.4     0.1       0
  4741.7    0.05       0  4967.8    0.12       0  5000.2    0.07       0
  5004.2    0.12       0  5216.6    0.05       0
Bank Sta=5000.2,5004.2
Exp/Cntr=0.3,0.1

Type RM Length L Ch R = 1,561,0,0,0
BEGIN DESCRIPTION:
DUCK CREEK TRIB 12 1 0
END DESCRIPTION:
XS GIS Cut Line= 3
      3540792.10     10393541.66      3540992.11     10393191.64
      3541092.10     10392691.67
#Sta/Elev= 30
  4627.5  326.81  4672.9  319.22  4700.2  312.42  4730.2  307.24  4743.4  305.70
  4759.2  305.46  4846.3  306.62  4936.3  306.40  4957.9  307.26  4973.0  306.51
  4985.3  301.35  4993.4  300.89  4993.6  300.39  4997.4  300.89  5007.6  304.13
  5022.7  306.39  5081.6  305.64  5108.1  307.68  5153.0  311.14  5163.2  310.79
  5193.8  316.11  5204.0  316.84  5230.9  316.41  5330.2  313.28  5408.0  316.75
  5458.9  314.37  5489.5  320.43  5499.7  324.56  5509.9  327.11  5540.5  328.02
#Mann=7,-1,0
  4627.5    0.05       0  4730.2    0.12       0  4993.4    0.07       0
  4997.4    0.12       0  5108.1    0.05       0  5230.9    0.08       0
  5330.2     0.1       0
Bank Sta=4993.4,4997.4
Exp/Cntr=0.3,0.1

Chan Stop Cuts=-1