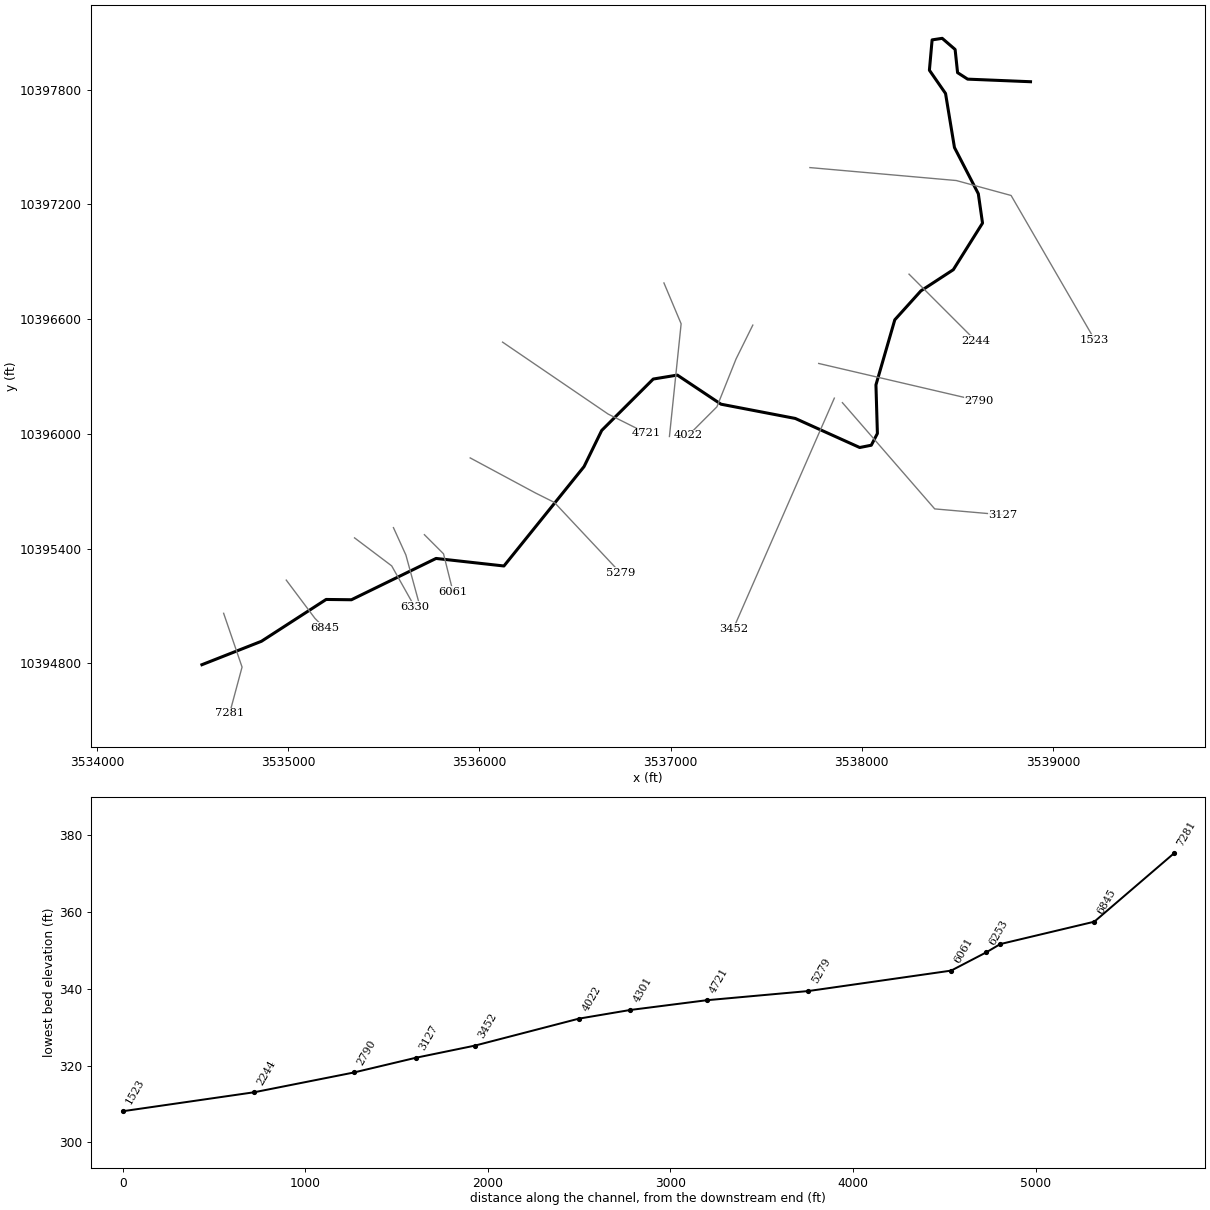
--- DUCK CREEK TRIB 13.prj (project) ---

Proj Title=DUCK CREEK TRIB 13 Base Level Engineering
Current Plan=p01
Default Exp/Contr=0.3,0.1
English Units
Geom File=g01
Flow File=f01
Plan File=p01
BEGIN DESCRIPTION:
DUCK CREEK TRIB 13
END DESCRIPTION:

--- DUCK CREEK TRIB 13.p01 (plan) ---

Plan Title=Multiple Run
Short Identifier=Multiple
Geom File=g01
Flow File=f01
Subcritical Flow
K Sum by GR= 0
Std Step Tol= 0.01
Critical Tol= 0.01
Num of Std Step Trials= 20
Max Error Tol= 0.3
Flow Tol Ratio= 0.001
Split Flow NTrial= 30
Split Flow Tol= 0.02
Split Flow Ratio= 0.02
Log Output Level= 0
Friction Slope Method= 1
Unsteady Friction Slope Method= 2
Unsteady Bridges Friction Slope Method= 1
Parabolic Critical Depth
Global Vel Dist=  1 , 1 , 1
Global Log Level= 0
CheckData=True
Encroach Param= -1, 0, 0, 0
BEGIN DESCRIPTION:
Multiple Run
END DESCRIPTION:

--- DUCK CREEK TRIB 13.f01 (steady flow) ---

Flow Title=Multiple
Number of Profiles=7
Profile Names=10-year,25-year,50-year,1pct_min,100-year,1pct_plu,500-year
River Rch & RM= DUCK CREEK TRIB ,Reach-1,7281
     960    1333    1644    1481    2003    2708    2964
Boundary for River Rch & Prof#=DUCK CREEK TRIB ,Reach-1,1
Up Type=0
Dn Type=3
Dn Slope=0.005
Boundary for River Rch & Prof#=DUCK CREEK TRIB ,Reach-1,2
Up Type=0
Dn Type=3
Dn Slope=0.005
Boundary for River Rch & Prof#=DUCK CREEK TRIB ,Reach-1,3
Up Type=0
Dn Type=3
Dn Slope=0.005
Boundary for River Rch & Prof#=DUCK CREEK TRIB ,Reach-1,4
Up Type=0
Dn Type=3
Dn Slope=0.005
Boundary for River Rch & Prof#=DUCK CREEK TRIB ,Reach-1,5
Up Type=0
Dn Type=3
Dn Slope=0.005
Boundary for River Rch & Prof#=DUCK CREEK TRIB ,Reach-1,6
Up Type=0
Dn Type=3
Dn Slope=0.005
Boundary for River Rch & Prof#=DUCK CREEK TRIB ,Reach-1,7
Up Type=0
Dn Type=3
Dn Slope=0.005

--- DUCK CREEK TRIB 13.g01 (geometry) ---

Geom Title=Existing Conditions

River Reach=DUCK CREEK TRIB ,Reach-1
Reach XY= 30
      3534548.99     10394792.94      3534860.41     10394915.55
      3535198.53     10395134.19      3535330.82     10395132.63
      3535773.41     10395348.67      3536128.34     10395309.25
      3536547.28     10395828.92      3536639.65     10396018.03
      3536909.19     10396286.87      3537035.16     10396307.58
      3537263.49     10396155.31      3537651.94     10396080.77
      3537988.85     10395928.78      3538049.44     10395940.71
      3538081.40     10396002.15      3538073.76     10396256.13
      3538172.36     10396596.61      3538308.82     10396747.89
      3538478.42     10396858.68      3538631.14     10397102.27
      3538609.11     10397255.95      3538484.36     10397497.61
      3538437.72     10397780.21      3538353.32     10397901.86
      3538367.50     10398060.47      3538420.29     10398068.55
      3538487.79     10398010.36      3538500.65     10397889.11
      3538553.25     10397855.18      3538882.11     10397841.64

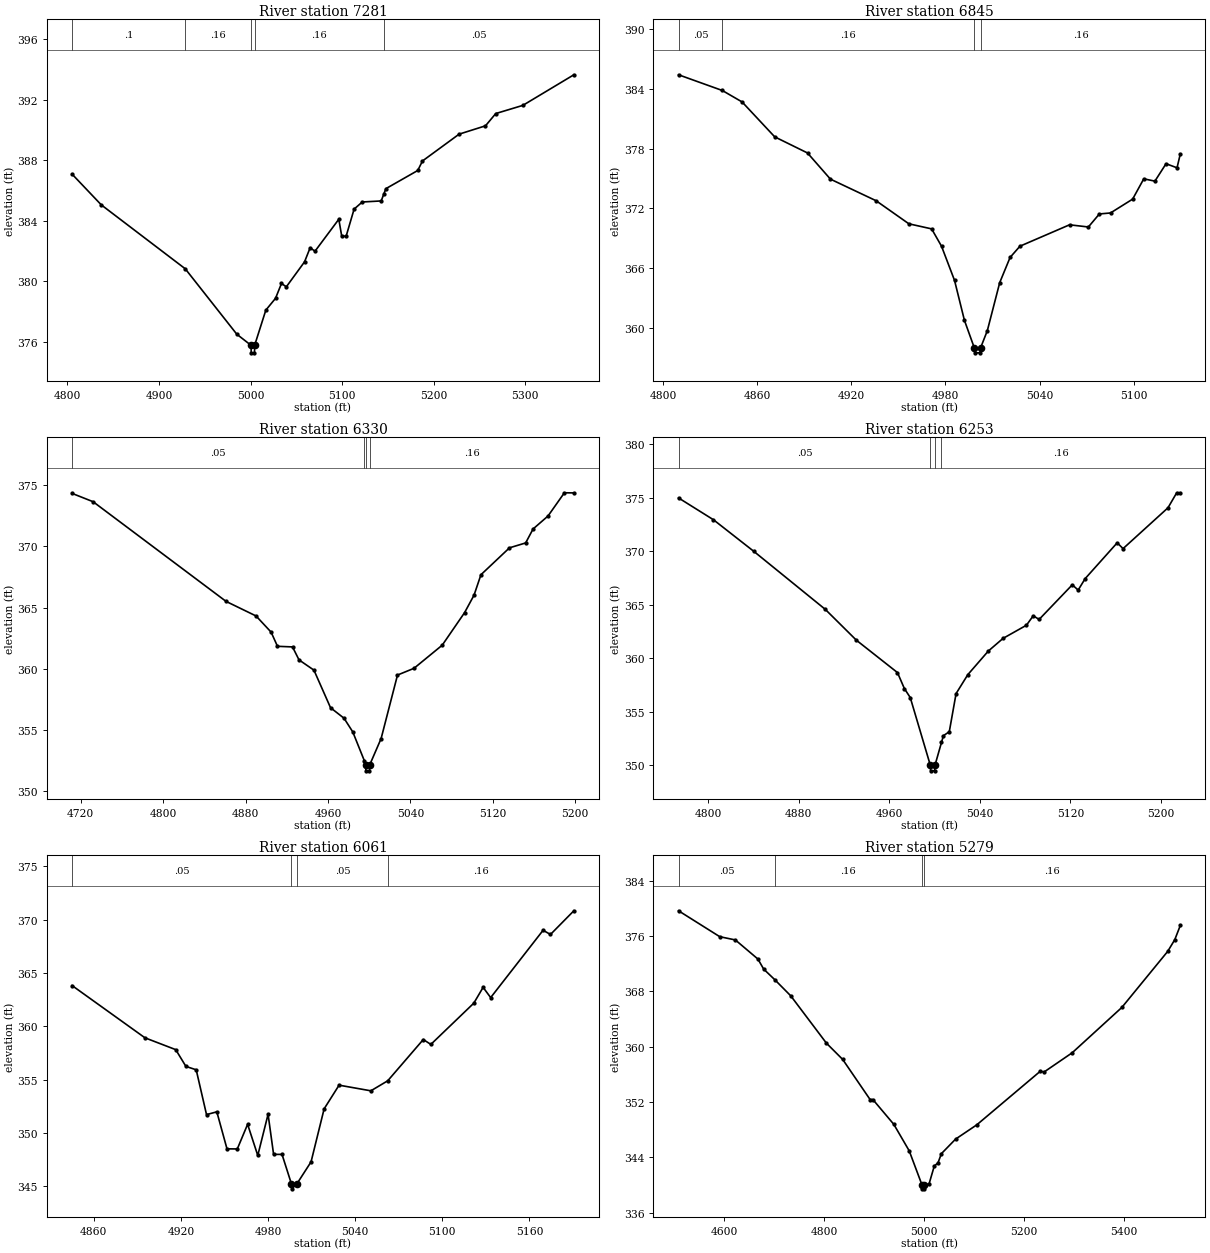
Type RM Length L Ch R = 1,7281,436,436,436
BEGIN DESCRIPTION:
DUCK CREEK TRIB 13 4 0
END DESCRIPTION:
XS GIS Cut Line= 3
      3534662.56     10395061.81      3534758.90     10394780.60
      3534693.81     10394538.45
#Sta/Elev= 30
  4805.0  387.08  4836.9  385.05  4928.6  380.83  4984.9  376.51  5000.4  375.78
  5000.7  375.28  5004.2  375.28  5004.4  375.78  5016.6  378.10  5027.2  378.88
  5033.7  379.86  5039.0  379.64  5058.9  381.29  5065.0  382.22  5070.3  381.99
  5096.3  384.10  5099.5  382.98  5104.3  382.98  5113.0  384.77  5121.9  385.24
  5142.6  385.31  5145.3  385.74  5147.7  386.12  5182.5  387.32  5187.7  387.95
  5227.7  389.72  5256.5  390.27  5267.7  391.08  5297.3  391.62  5353.0  393.64
#Mann=5,-1,0
  4805.0     0.1       0  4928.6    0.16       0  5000.4    0.07       0
  5004.4    0.16       0  5145.3    0.05       0
Bank Sta=5000.4,5004.4
Exp/Cntr=0.3,0.1

Type RM Length L Ch R = 1,6845,515,515,515
BEGIN DESCRIPTION:
DUCK CREEK TRIB 13 14 1
END DESCRIPTION:
XS GIS Cut Line= 3
      3534990.04     10395235.37      3535140.02     10395035.39
      3535189.40     10394986.01
#Sta/Elev= 30
  4809.9  385.44  4837.8  383.86  4850.4  382.71  4871.2  379.20  4892.1  377.58
  4906.7  374.95  4935.8  372.78  4956.7  370.46  4971.2  369.95  4977.5  368.21
  4985.8  364.77  4992.1  360.76  4998.4  357.99  4998.7  357.49  5002.2  357.49
  5002.4  357.99  5006.7  359.72  5014.6  364.55  5021.2  367.08  5027.5  368.21
  5059.1  370.36  5071.1  370.14  5078.1  371.45  5085.2  371.55  5099.3  372.94
  5106.4  374.98  5113.5  374.75  5120.6  376.50  5127.6  376.09  5129.7  377.49
#Mann=4,-1,0
  4809.9    0.05       0  4837.8    0.16       0  4998.4    0.07       0
  5002.4    0.16       0
Bank Sta=4998.4,5002.4
Exp/Cntr=0.3,0.1

Type RM Length L Ch R = 1,6330,77,77,77
BEGIN DESCRIPTION:
DUCK CREEK TRIB 13 16 0
END DESCRIPTION:
XS GIS Cut Line= 3
      3535347.21     10395456.23      3535541.40     10395309.77
      3535660.76     10395097.10
#Sta/Elev= 30
  4711.6  374.34  4732.0  373.66  4861.1  365.51  4890.2  364.32  4904.8  363.00
  4911.0  361.84  4925.6  361.79  4931.9  360.73  4946.4  359.89  4962.5  356.82
  4975.6  355.96  4984.1  354.84  4995.3  352.49  4996.6  352.16  4996.8  351.66
  5000.3  351.66  5000.6  352.16  5011.6  354.30  5027.5  359.49  5043.5  360.04
  5070.9  361.93  5092.6  364.59  5101.8  366.02  5108.5  367.69  5136.2  369.89
  5151.9  370.29  5159.1  371.43  5173.6  372.49  5189.5  374.39  5198.7  374.38
#Mann=4,-1,0
  4711.6    0.05       0  4995.3    0.16       0  4996.6    0.07       0
  5000.6    0.16       0
Bank Sta=4996.6,5000.6
Exp/Cntr=0.3,0.1

Type RM Length L Ch R = 1,6253,192,192,192
BEGIN DESCRIPTION:
Mapping XS 028ee329
END DESCRIPTION:
XS GIS Cut Line= 3
      3535550.58     10395509.74      3535615.67     10395366.53
      3535691.20     10395090.48
#Sta/Elev= 30
  4773.7  374.97  4804.6  372.93  4840.4  369.97  4903.4  364.57  4930.9  361.69
  4967.2  358.67  4973.3  357.18  4978.5  356.34  4996.3  350.00  4996.5  349.50
  5000.0  349.50  5000.3  350.00  5006.1  352.15  5007.8  352.78  5013.0  353.15
  5019.0  356.71  5029.4  358.48  5047.5  360.68  5060.5  361.86  5081.2  363.09
  5087.2  363.97  5092.4  363.63  5121.7  366.86  5126.9  366.37  5133.1  367.44
  5161.4  370.78  5166.6  370.24  5206.3  374.05  5214.0  375.45  5217.2  375.45
#Mann=4,-1,0
  4773.7    0.05       0  4996.3    0.03       0  5000.3    0.05       0
  5006.1    0.16       0
Bank Sta=4996.3,5000.3
Exp/Cntr=0.3,0.1

Type RM Length L Ch R = 1,6061,782,782,782
BEGIN DESCRIPTION:
DUCK CREEK TRIB 13 15 0
END DESCRIPTION:
XS GIS Cut Line= 3
      3535712.42     10395472.89      3535812.42     10395372.89
      3535861.94     10395174.80
#Sta/Elev= 30
  4845.0  363.81  4895.2  358.91  4916.4  357.80  4923.4  356.23  4930.5  355.91
  4937.6  351.71  4944.7  351.97  4951.7  348.50  4958.8  348.49  4965.9  350.80
  4972.9  347.88  4980.0  351.74  4983.8  347.98  4989.6  347.98  4996.0  345.25
  4996.3  344.75  5000.0  345.25  5009.6  347.28  5018.6  352.25  5028.9  354.47
  5050.8  353.94  5062.4  354.88  5086.9  358.75  5092.1  358.29  5121.7  362.16
  5128.1  363.64  5133.3  362.68  5169.4  368.99  5174.5  368.60  5190.6  370.82
#Mann=4,-1,0
  4845.0    0.05       0  4996.0    0.03       0  5000.0    0.05       0
  5062.4    0.16       0
Bank Sta=4996,5000
Exp/Cntr=0.3,0.1

Type RM Length L Ch R = 1,5279,558,558,558
BEGIN DESCRIPTION:
DUCK CREEK TRIB 13 14 0
END DESCRIPTION:
XS GIS Cut Line= 4
      3535951.98     10395874.37      3536292.11     10395691.64
      3536392.11     10395641.64      3536738.42     10395272.46
#Sta/Elev= 30
  4508.3  379.66  4590.8  375.91  4622.0  375.44  4667.1  372.68  4678.7  371.22
  4700.6  369.71  4732.9  367.35  4804.3  360.50  4836.8  358.15  4891.6  352.35
  4897.2  352.35  4939.1  348.76  4969.9  344.93  4995.8  339.93  4996.1  339.43
  4999.6  339.43  4999.8  339.93  5009.6  340.14  5020.1  342.74  5027.5  343.19
  5034.3  344.52  5062.6  346.62  5105.1  348.69  5232.6  356.47  5239.5  356.32
  5296.1  359.12  5395.3  365.67  5487.1  373.78  5501.3  375.48  5512.4  377.54
#Mann=4,-1,0
  4508.3    0.05       0  4700.6    0.16       0  4995.8    0.07       0
  4999.8    0.16       0
Bank Sta=4995.8,4999.8
Exp/Cntr=0.3,0.1

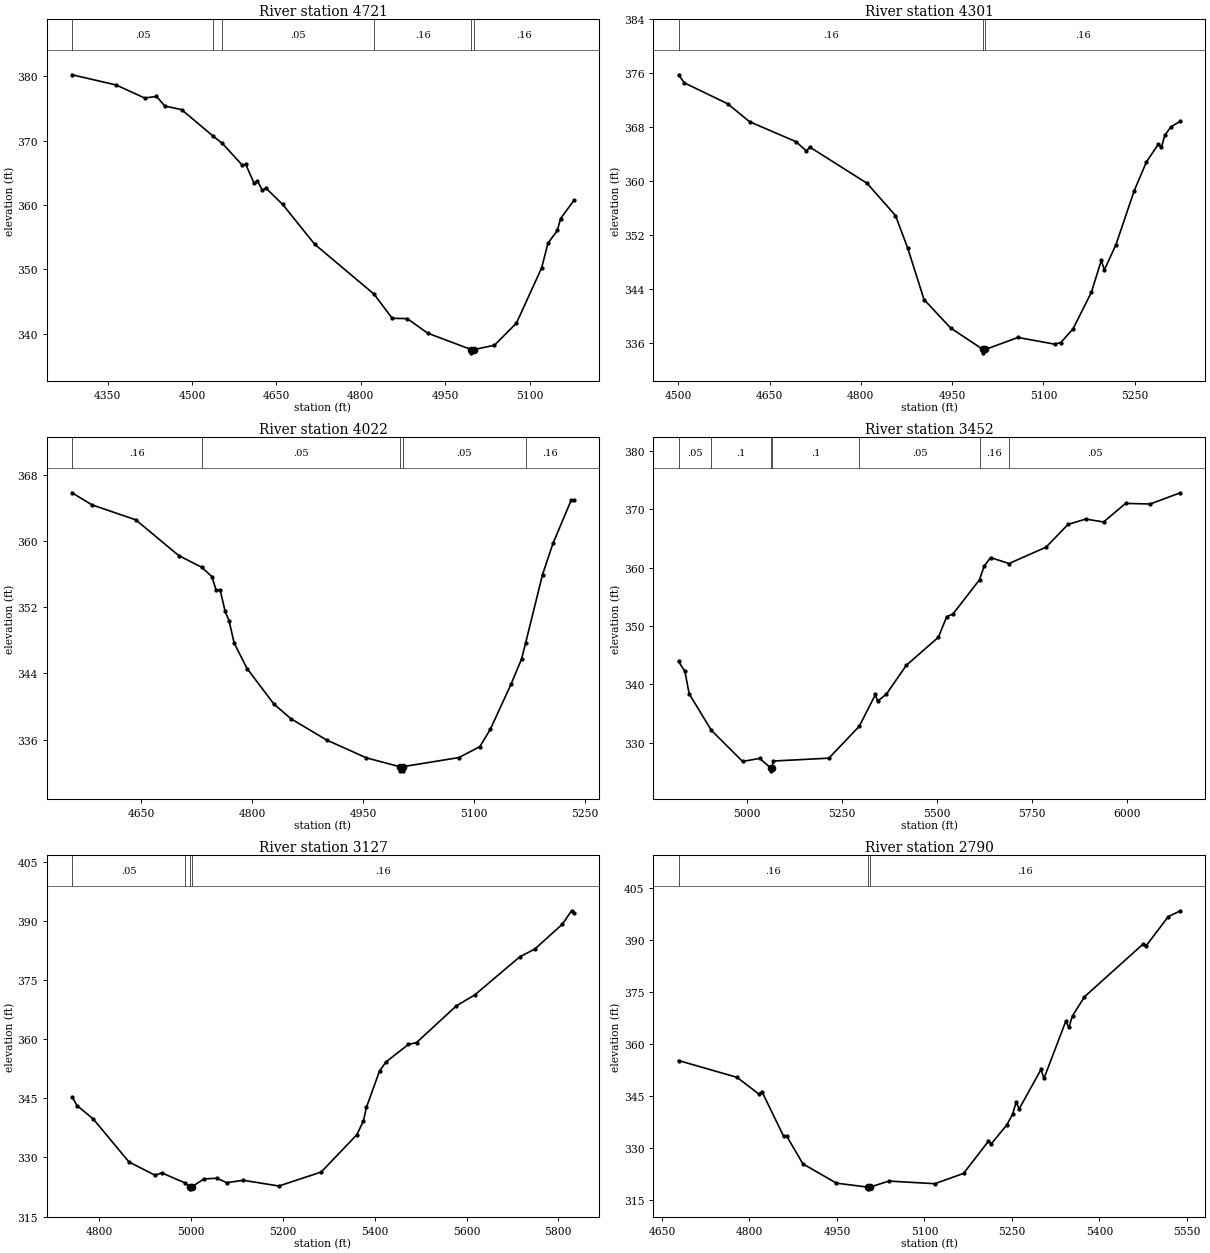
Type RM Length L Ch R = 1,4721,420,420,420
BEGIN DESCRIPTION:
DUCK CREEK TRIB 13 3 0
END DESCRIPTION:
XS GIS Cut Line= 3
      3536121.27     10396479.82      3536673.36     10396103.62
      3536873.37     10396003.61
#Sta/Elev= 30
  4287.0  380.21  4365.2  378.63  4416.0  376.60  4437.0  376.85  4451.9  375.35
  4481.6  374.80  4537.6  370.69  4553.9  369.57  4589.5  366.17  4595.6  366.30
  4610.5  363.36  4616.5  363.67  4625.4  362.27  4631.5  362.61  4661.3  360.07
  4718.2  353.89  4823.8  346.13  4855.8  342.40  4882.8  342.34  4918.8  340.09
  4996.5  337.53  4996.8  337.03  5000.5  337.53  5037.6  338.21  5076.7  341.65
  5121.4  350.21  5132.7  354.06  5149.4  356.03  5155.0  357.87  5178.7  360.69
#Mann=6,-1,0
  4287.0    0.05       0  4537.6    0.16       0  4553.9    0.05       0
  4823.8    0.16       0  4996.5    0.07       0  5000.5    0.16       0
Bank Sta=4996.5,5000.5
Exp/Cntr=0.3,0.1

Type RM Length L Ch R = 1,4301,279,279,279
BEGIN DESCRIPTION:
DUCK CREEK TRIB 13 17 0
END DESCRIPTION:
XS GIS Cut Line= 3
      3536965.15     10396789.28      3537054.99     10396575.75
      3536993.83     10395986.27
#Sta/Elev= 30
  4500.5  375.75  4509.9  374.56  4581.1  371.45  4617.3  368.78  4693.2  365.83
  4710.7  364.44  4716.1  365.02  4810.1  359.65  4856.9  354.86  4877.0  350.02
  4903.8  342.39  4947.4  338.17  5000.5  334.98  5000.8  334.48  5004.5  334.98
  5058.0  336.76  5118.3  335.77  5128.4  336.00  5148.5  338.03  5178.6  343.45
  5195.0  348.20  5200.0  346.78  5218.9  350.50  5249.0  358.53  5269.1  362.81
  5288.6  365.44  5293.7  364.96  5299.3  366.77  5309.3  368.01  5324.8  368.86
#Mann=3,-1,0
  4500.5    0.16       0  5000.5    0.07       0  5004.5    0.16       0
Bank Sta=5000.5,5004.5
Exp/Cntr=0.3,0.1

Type RM Length L Ch R = 1,4022,570,570,570
BEGIN DESCRIPTION:
DUCK CREEK TRIB 13 2 0
END DESCRIPTION:
XS GIS Cut Line= 4
      3537429.83     10396568.84      3537342.11     10396391.64
      3537242.11     10396141.64      3537092.11     10395991.65
#Sta/Elev= 30
  4556.3  365.80  4583.0  364.35  4642.4  362.54  4700.7  358.22  4732.1  356.79
  4745.6  355.67  4751.2  354.06  4756.7  354.06  4763.4  351.51  4768.8  350.36
  4775.6  347.67  4793.1  344.59  4829.4  340.31  4852.3  338.54  4900.8  335.96
  4954.6  333.81  4999.7  332.74  5000.0  332.24  5003.5  332.24  5003.7  332.74
  5079.8  333.84  5108.1  335.16  5122.3  337.25  5150.6  342.74  5164.7  345.76
  5170.2  347.70  5193.0  355.93  5207.1  359.68  5231.9  364.93  5235.4  364.93
#Mann=5,-1,0
  4556.3    0.16       0  4732.1    0.05       0  4999.7    0.03       0
  5003.7    0.05       0  5170.2    0.16       0
Bank Sta=4999.7,5003.7
Exp/Cntr=0.3,0.1

Type RM Length L Ch R = 1,3452,325,325,325
BEGIN DESCRIPTION:
DUCK CREEK TRIB 13 9 0
END DESCRIPTION:
XS GIS Cut Line= 2
      3537856.19     10396187.00      3537327.39     10394979.40
#Sta/Elev= 30
  4820.7  343.93  4837.5  342.23  4848.6  338.40  4906.9  332.15  4988.9  326.82
  5034.0  327.34  5062.5  325.71  5062.7  325.21  5066.5  325.71  5069.9  326.89
  5215.7  327.38  5295.5  332.84  5338.1  338.28  5343.5  337.12  5366.9  338.35
  5419.1  343.27  5503.4  348.07  5525.2  351.59  5541.5  352.04  5611.4  357.91
  5623.5  360.23  5640.5  361.71  5689.0  360.69  5786.2  363.49  5843.9  367.38
  5890.7  368.30  5937.4  367.80  5995.1  370.98  6059.8  370.88  6139.0  372.80
#Mann=7,-1,0
  4820.7    0.05       0  4906.9     0.1       0  5062.5    0.07       0
  5066.5     0.1       0  5295.5    0.05       0  5611.4    0.16       0
  5689.0    0.05       0
Bank Sta=5062.5,5066.5
Exp/Cntr=0.3,0.1

Type RM Length L Ch R = 1,3127,337,337,337
BEGIN DESCRIPTION:
DUCK CREEK TRIB 13 18 0
END DESCRIPTION:
XS GIS Cut Line= 3
      3537898.38     10396163.36      3538381.03     10395607.78
      3538737.23     10395576.66
#Sta/Elev= 30
  4740.3  345.34  4751.4  343.15  4786.5  339.76  4864.4  328.85  4921.4  325.46
  4935.6  326.10  4985.8  323.56  4997.2  322.53  4997.5  322.03  5001.2  322.53
  5027.7  324.55  5056.2  324.72  5077.1  323.59  5113.2  324.20  5191.1  322.75
  5283.2  326.30  5361.0  335.78  5375.3  339.29  5381.9  342.76  5410.4  351.98
  5424.6  354.28  5473.3  358.70  5490.9  359.16  5577.7  368.49  5617.9  371.27
  5716.2  380.96  5748.4  382.89  5808.6  389.20  5828.7  392.63  5833.8  392.04
#Mann=4,-1,0
  4740.3    0.05       0  4985.8    0.16       0  4997.2    0.07       0
  5001.2    0.16       0
Bank Sta=4997.2,5001.2
Exp/Cntr=0.3,0.1

Type RM Length L Ch R = 1,2790,546,546,546
BEGIN DESCRIPTION:
DUCK CREEK TRIB 13 7 0
END DESCRIPTION:
XS GIS Cut Line= 2
      3537774.49     10396368.29      3538612.12     10396172.98
#Sta/Elev= 30
  4678.5  355.20  4778.8  350.35  4816.3  345.52  4821.4  346.26  4858.8  333.32
  4864.0  333.39  4891.7  325.42  4949.1  319.86  5002.6  318.72  5002.9  318.22
  5006.6  318.72  5039.3  320.46  5117.6  319.70  5167.0  322.66  5209.5  331.90
  5214.7  331.22  5240.8  336.55  5251.1  339.70  5257.2  343.21  5262.4  341.26
  5299.8  352.62  5304.9  350.06  5342.3  366.52  5347.5  364.72  5353.8  368.10
  5374.3  373.57  5475.1  388.82  5480.3  388.35  5517.7  396.63  5538.6  398.36
#Mann=3,-1,0
  4678.5    0.16       0  5002.6    0.07       0  5006.6    0.16       0
Bank Sta=5002.6,5006.6
Exp/Cntr=0.3,0.1

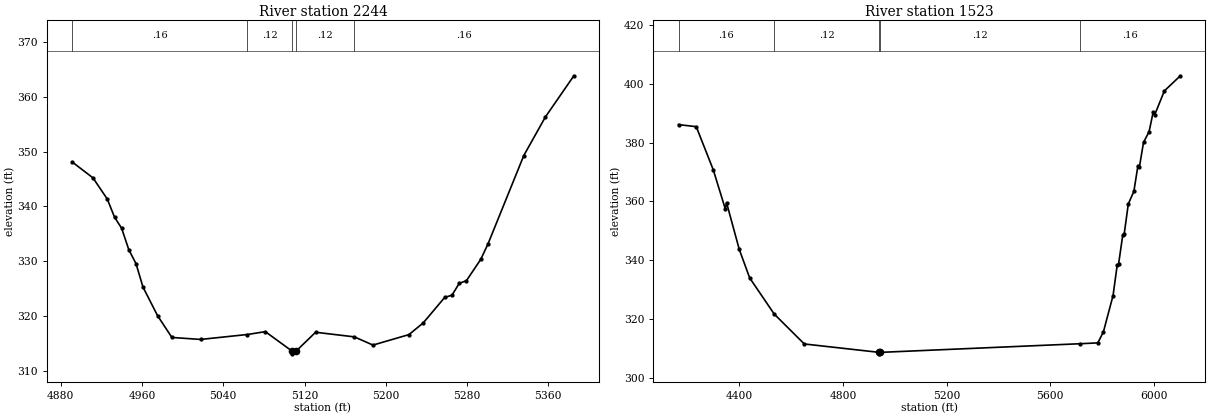
Type RM Length L Ch R = 1,2244,721,721,721
BEGIN DESCRIPTION:
DUCK CREEK TRIB 13 6 0
END DESCRIPTION:
XS GIS Cut Line= 3
      3538246.78     10396835.40      3538296.79     10396785.39
      3538596.16     10396486.02
#Sta/Elev= 30
  4891.1  348.11  4911.7  345.19  4925.8  341.32  4932.9  338.02  4939.9  336.00
  4947.0  332.06  4954.1  329.52  4960.9  325.27  4975.3  320.03  4989.4  316.06
  5017.7  315.70  5063.7  316.60  5081.4  317.12  5107.7  313.57  5107.9  313.07
  5111.7  313.57  5130.9  317.01  5169.0  316.17  5187.4  314.67  5222.8  316.58
  5236.9  318.72  5258.1  323.39  5265.2  323.77  5272.3  325.94  5279.4  326.42
  5293.5  330.31  5300.6  333.11  5335.9  349.27  5357.1  356.29  5385.2  363.83
#Mann=5,-1,0
  4891.1    0.16       0  5063.7    0.12       0  5107.7    0.07       0
  5111.7    0.12       0  5169.0    0.16       0
Bank Sta=5107.7,5111.7
Exp/Cntr=0.3,0.1

Type RM Length L Ch R = 1,1523,0,0,0
BEGIN DESCRIPTION:
DUCK CREEK TRIB 13 1 0
END DESCRIPTION:
XS GIS Cut Line= 4
      3537728.51     10397392.62      3538494.10     10397324.92
      3538780.56     10397246.79      3539217.57     10396492.44
#Sta/Elev= 30
  4164.8  386.13  4233.2  385.43  4298.9  370.74  4345.2  357.48  4350.2  359.55
  4399.3  343.64  4439.5  333.95  4534.4  321.64  4650.3  311.48  4939.7  308.62
  4939.9  308.12  4943.7  308.62  5715.2  311.56  5783.6  311.85  5805.1  315.59
  5842.4  327.96  5858.2  338.20  5863.9  338.77  5879.7  348.47  5885.5  348.93
  5901.2  359.11  5922.8  363.43  5938.5  372.19  5944.3  371.80  5960.0  380.08
  5981.6  383.75  5997.3  390.41  6003.1  389.44  6040.4  397.59  6102.1  402.75
#Mann=5,-1,0
  4164.8    0.16       0  4534.4    0.12       0  4939.7    0.07       0
  4943.7    0.12       0  5715.2    0.16       0
Bank Sta=4939.7,4943.7
Exp/Cntr=0.3,0.1

Chan Stop Cuts=-1