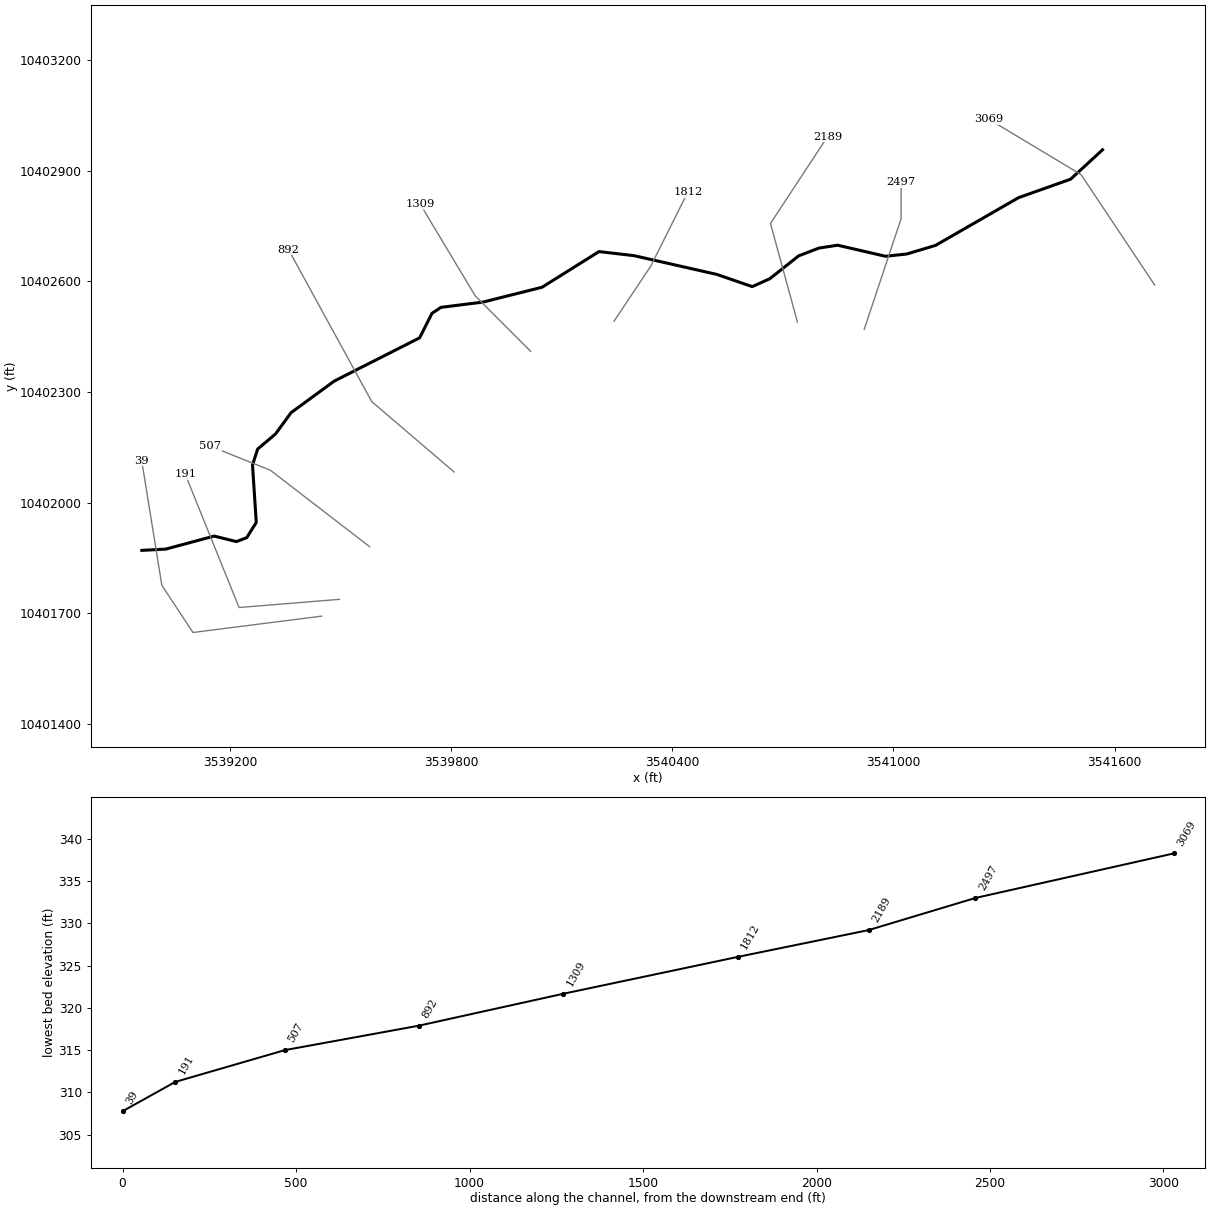
--- DUCK CREEK TRIB 14.prj (project) ---

Proj Title=DUCK CREEK TRIB 14 Base Level Engineering
Current Plan=p01
Default Exp/Contr=0.3,0.1
English Units
Geom File=g01
Flow File=f01
Plan File=p01
BEGIN DESCRIPTION:
DUCK CREEK TRIB 14
END DESCRIPTION:

--- DUCK CREEK TRIB 14.p01 (plan) ---

Plan Title=Multiple Run
Short Identifier=Multiple
Geom File=g01
Flow File=f01
Subcritical Flow
K Sum by GR= 0
Std Step Tol= 0.01
Critical Tol= 0.01
Num of Std Step Trials= 20
Max Error Tol= 0.3
Flow Tol Ratio= 0.001
Split Flow NTrial= 30
Split Flow Tol= 0.02
Split Flow Ratio= 0.02
Log Output Level= 0
Friction Slope Method= 1
Unsteady Friction Slope Method= 2
Unsteady Bridges Friction Slope Method= 1
Parabolic Critical Depth
Global Vel Dist=  1 , 1 , 1
Global Log Level= 0
CheckData=True
Encroach Param= -1, 0, 0, 0
BEGIN DESCRIPTION:
Multiple Run
END DESCRIPTION:

--- DUCK CREEK TRIB 14.f01 (steady flow) ---

Flow Title=Multiple
Number of Profiles=7
Profile Names=10-year,25-year,50-year,1pct_min,100-year,1pct_plu,500-year
River Rch & RM= DUCK CREEK TRIB ,Reach-1,3069
     504     670     803     705     953    1289    1337
Boundary for River Rch & Prof#=DUCK CREEK TRIB ,Reach-1,1
Up Type=0
Dn Type=3
Dn Slope=0.005
Boundary for River Rch & Prof#=DUCK CREEK TRIB ,Reach-1,2
Up Type=0
Dn Type=3
Dn Slope=0.005
Boundary for River Rch & Prof#=DUCK CREEK TRIB ,Reach-1,3
Up Type=0
Dn Type=3
Dn Slope=0.005
Boundary for River Rch & Prof#=DUCK CREEK TRIB ,Reach-1,4
Up Type=0
Dn Type=3
Dn Slope=0.005
Boundary for River Rch & Prof#=DUCK CREEK TRIB ,Reach-1,5
Up Type=0
Dn Type=3
Dn Slope=0.005
Boundary for River Rch & Prof#=DUCK CREEK TRIB ,Reach-1,6
Up Type=0
Dn Type=3
Dn Slope=0.005
Boundary for River Rch & Prof#=DUCK CREEK TRIB ,Reach-1,7
Up Type=0
Dn Type=3
Dn Slope=0.005

--- DUCK CREEK TRIB 14.g01 (geometry) ---

Geom Title=Existing Conditions

River Reach=DUCK CREEK TRIB ,Reach-1
Reach XY= 30
      3541567.11     10402956.64      3541480.45     10402876.93
      3541339.37     10402826.87      3541114.39     10402697.50
      3541036.40     10402674.09      3540978.38     10402667.86
      3540848.52     10402697.90      3540797.87     10402690.11
      3540743.16     10402669.13      3540664.50     10402606.87
      3540616.94     10402585.57      3540520.91     10402618.69
      3540296.21     10402669.57      3540201.43     10402680.62
      3540046.90     10402583.86      3539886.56     10402543.58
      3539772.81     10402529.37      3539748.32     10402513.05
      3539714.77     10402446.63      3539483.09     10402329.26
      3539366.22     10402243.77      3539324.03     10402185.97
      3539275.48     10402144.95      3539261.57     10402101.82
      3539271.76     10401945.94      3539245.84     10401904.65
      3539217.95     10401893.98      3539157.68     10401908.97
      3539026.24     10401873.64      3538961.41     10401870.18

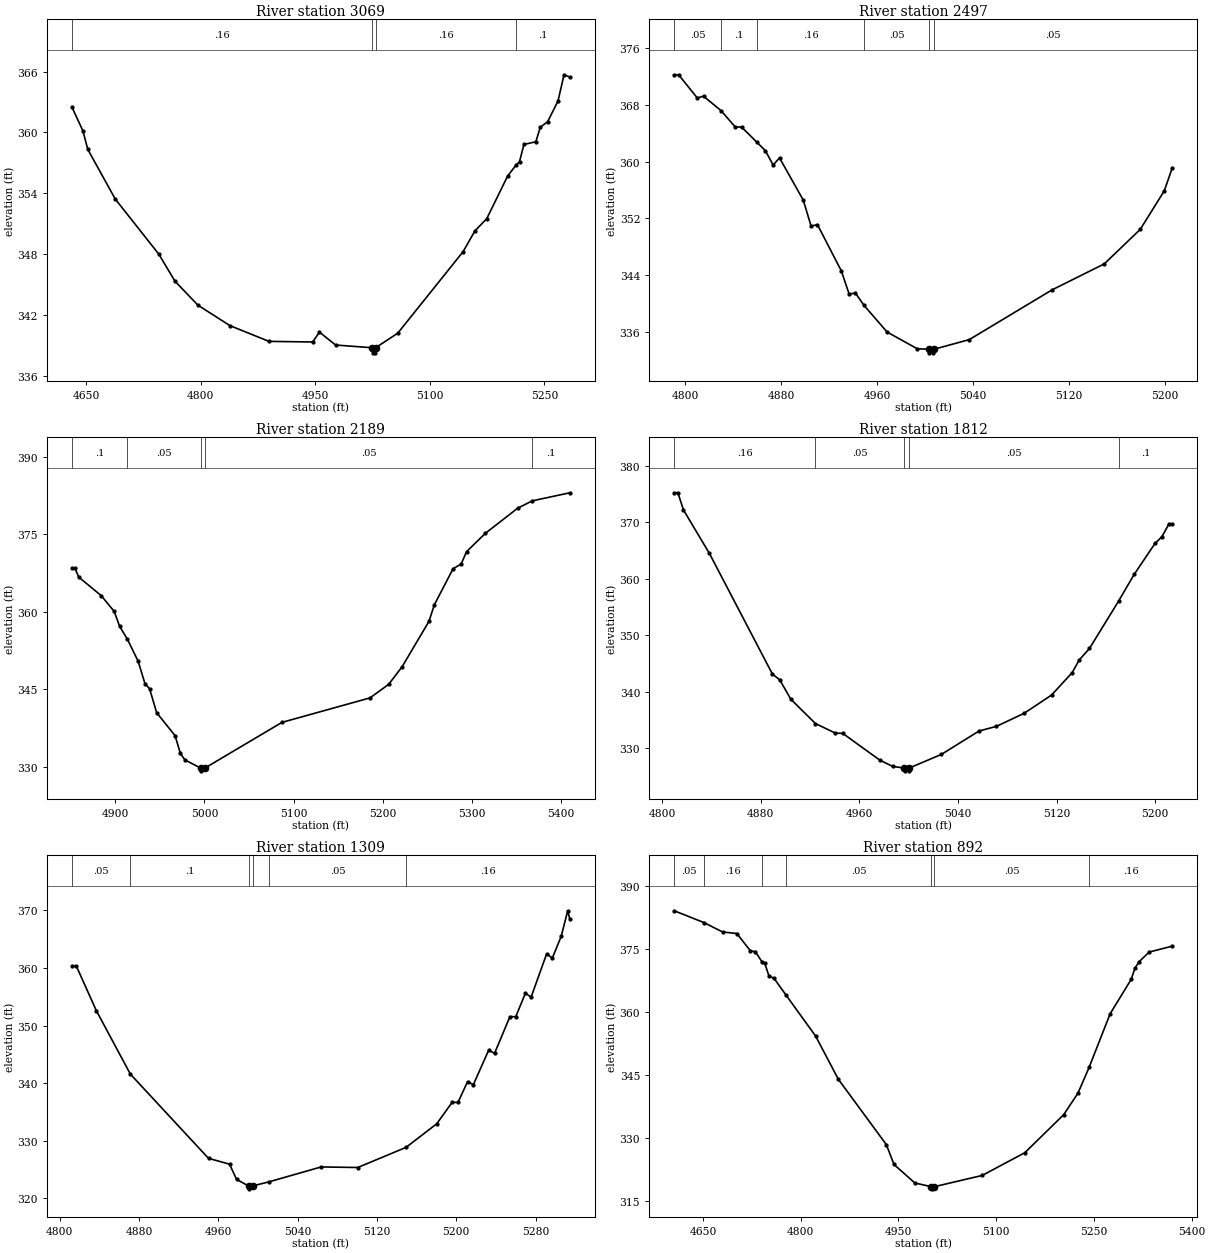
Type RM Length L Ch R = 1,3069,572,572,572
BEGIN DESCRIPTION:
DUCK CREEK TRIB 14 8 0
END DESCRIPTION:
XS GIS Cut Line= 3
      3541708.76     10402589.58      3541508.77     10402889.56
      3541258.75     10403039.57
#Sta/Elev= 30
  4631.2  362.51  4645.7  360.14  4652.0  358.33  4688.0  353.43  4745.1  347.99
  4766.1  345.34  4796.2  342.97  4838.2  340.95  4889.3  339.40  4946.4  339.34
  4955.4  340.31  4976.5  339.04  5024.8  338.77  5025.0  338.27  5028.5  338.27
  5028.8  338.77  5057.8  340.20  5143.4  348.24  5159.0  350.30  5174.4  351.49
  5201.7  355.69  5212.7  356.77  5217.3  357.12  5223.1  358.81  5238.7  359.08
  5244.5  360.50  5254.2  361.06  5267.7  363.09  5275.6  365.68  5283.3  365.45
#Mann=4,-1,0
  4631.2    0.16       0  5024.8    0.07       0  5028.8    0.16       0
  5212.7     0.1       0
Bank Sta=5024.8,5028.8
Exp/Cntr=0.3,0.1

Type RM Length L Ch R = 1,2497,308,308,308
BEGIN DESCRIPTION:
DUCK CREEK TRIB 14 19 0
END DESCRIPTION:
XS GIS Cut Line= 3
      3540920.66     10402469.63      3541020.67     10402769.66
      3541020.67     10402868.20
#Sta/Elev= 30
  4791.1  372.26  4794.8  372.26  4810.3  368.99  4815.5  369.24  4830.1  367.20
  4841.9  364.90  4847.2  364.88  4860.1  362.71  4867.0  361.55  4873.5  359.52
  4878.8  360.53  4898.6  354.56  4905.1  350.90  4910.4  351.10  4930.3  344.57
  4936.8  341.30  4942.0  341.45  4949.1  339.72  4968.4  335.94  4993.5  333.58
  5003.3  333.50  5003.5  333.00  5007.0  333.00  5007.3  333.50  5036.9  334.87
  5105.8  341.89  5149.3  345.56  5179.3  350.44  5199.3  355.88  5205.9  359.10
#Mann=6,-1,0
  4791.1    0.05       0  4830.1     0.1       0  4860.1    0.16       0
  4949.1    0.05       0  5003.3    0.03       0  5007.3    0.05       0
Bank Sta=5003.3,5007.3
Exp/Cntr=0.3,0.1

Type RM Length L Ch R = 1,2189,377,377,377
BEGIN DESCRIPTION:
DUCK CREEK TRIB 14 9 0
END DESCRIPTION:
XS GIS Cut Line= 3
      3540739.39     10402489.95      3540666.47     10402756.88
      3540821.44     10402992.59
#Sta/Elev= 30
  4851.2  368.41  4854.7  368.41  4859.0  366.72  4884.1  363.15  4898.7  360.09
  4904.8  357.18  4913.5  354.70  4925.5  350.46  4933.2  346.10  4938.4  345.11
  4946.3  340.47  4967.0  336.02  4972.9  332.58  4978.1  331.31  4996.1  329.70
  4996.3  329.20  5000.1  329.70  5086.9  338.59  5185.6  343.33  5206.6  345.95
  5221.7  349.36  5251.9  358.18  5257.9  361.38  5278.9  368.36  5288.0  369.28
  5294.0  371.66  5315.1  375.22  5351.3  380.08  5367.8  381.52  5410.0  383.08
#Mann=5,-1,0
  4851.2     0.1       0  4913.5    0.05       0  4996.1    0.03       0
  5000.1    0.05       0  5367.8     0.1       0
Bank Sta=4996.1,5000.1
Exp/Cntr=0.3,0.1

Type RM Length L Ch R = 1,1812,503,503,503
BEGIN DESCRIPTION:
DUCK CREEK TRIB 14 7 0
END DESCRIPTION:
XS GIS Cut Line= 3
      3540242.12     10402491.67      3540342.11     10402641.64
      3540442.13     10402841.69
#Sta/Elev= 30
  4809.9  375.26  4812.9  375.26  4817.4  372.22  4838.4  364.54  4889.5  343.18
  4895.5  342.13  4904.5  338.71  4924.4  334.41  4940.6  332.71  4946.6  332.66
  4976.6  327.93  4987.1  326.81  4996.5  326.53  4996.8  326.03  5000.3  326.03
  5000.5  326.53  5026.5  328.93  5057.2  333.09  5071.2  333.90  5093.6  336.21
  5115.9  339.44  5132.7  343.43  5138.3  345.64  5146.7  347.70  5170.3  356.09
  5183.0  360.83  5199.8  366.28  5205.4  367.48  5211.0  369.69  5213.8  369.69
#Mann=5,-1,0
  4809.9    0.16       0  4924.4    0.05       0  4996.5    0.03       0
  5000.5    0.05       0  5170.3     0.1       0
Bank Sta=4996.5,5000.5
Exp/Cntr=0.3,0.1

Type RM Length L Ch R = 1,1309,417,417,417
BEGIN DESCRIPTION:
DUCK CREEK TRIB 14 6 0
END DESCRIPTION:
XS GIS Cut Line= 3
      3540015.71     10402410.40      3539865.72     10402560.39
      3539716.42     10402809.21
#Sta/Elev= 30
  4812.4  360.36  4816.8  360.36  4837.0  352.60  4871.4  341.57  4950.2  326.96
  4971.4  325.95  4978.5  323.31  4990.6  322.17  4990.9  321.67  4994.6  322.17
  5011.5  322.90  5063.8  325.47  5100.7  325.37  5149.4  328.86  5180.4  332.96
  5195.9  336.67  5201.8  336.66  5211.5  340.27  5217.3  339.74  5232.8  345.73
  5238.7  345.18  5254.2  351.54  5260.1  351.54  5269.8  355.60  5275.6  354.93
  5291.2  362.43  5297.0  361.72  5305.9  365.47  5312.5  369.91  5314.7  368.41
#Mann=6,-1,0
  4812.4    0.05       0  4871.4     0.1       0  4990.6    0.07       0
  4994.6     0.1       0  5011.5    0.05       0  5149.4    0.16       0
Bank Sta=4990.6,4994.6
Exp/Cntr=0.3,0.1

Type RM Length L Ch R = 1,892,385,385,385
BEGIN DESCRIPTION:
Mapping XS e8a9d090
END DESCRIPTION:
XS GIS Cut Line= 3
      3539808.40     10402082.81      3539584.86     10402273.80
      3539359.15     10402686.15
#Sta/Elev= 30
  4606.0  384.20  4652.1  381.36  4680.1  379.15  4702.0  378.78  4722.9  374.66
  4730.6  374.43  4741.2  371.91  4744.8  371.74  4751.4  368.63  4759.0  368.12
  4777.8  364.04  4822.8  354.36  4857.9  344.00  4931.5  328.43  4943.2  323.70
  4975.2  319.29  5000.7  318.39  5000.9  317.89  5004.7  318.39  5078.5  321.08
  5144.0  326.51  5203.7  335.60  5225.5  340.72  5242.6  346.87  5274.8  359.63
  5307.1  367.84  5312.8  370.49  5319.4  372.08  5334.6  374.35  5370.1  375.77
#Mann=7,-1,0
  4606.0    0.05       0  4652.1    0.16       0  4741.2     0.1       0
  4777.8    0.05       0  5000.7    0.03       0  5004.7    0.05       0
  5242.6    0.16       0
Bank Sta=5000.7,5004.7
Exp/Cntr=0.3,0.1

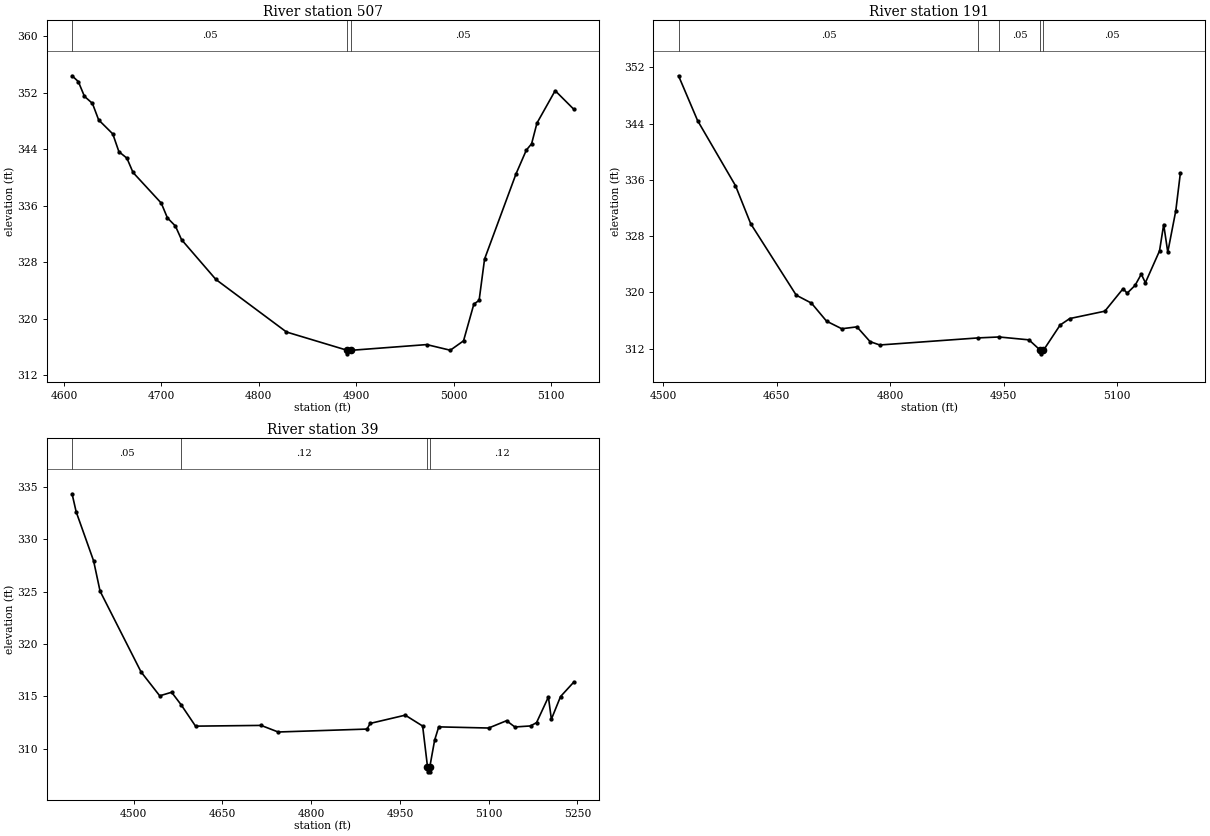
Type RM Length L Ch R = 1,507,316,316,316
BEGIN DESCRIPTION:
DUCK CREEK TRIB 14 4 0
END DESCRIPTION:
XS GIS Cut Line= 3
      3539579.08     10401880.30      3539310.00     10402087.59
      3539146.92     10402152.82
#Sta/Elev= 30
  4608.3  354.38  4614.7  353.56  4621.0  351.47  4629.2  350.47  4635.6  348.13
  4650.1  346.15  4656.4  343.63  4664.6  342.72  4670.9  340.69  4699.9  336.35
  4706.2  334.26  4714.4  333.11  4720.7  331.18  4756.0  325.54  4828.5  318.10
  4890.9  315.51  4891.1  315.01  4894.9  315.51  4972.5  316.32  4996.7  315.52
  5010.3  316.85  5020.9  322.05  5026.3  322.58  5031.9  328.43  5064.2  340.49
  5074.8  343.86  5080.2  344.75  5085.7  347.68  5104.4  352.27  5123.6  349.63
#Mann=3,-1,0
  4608.3    0.05       0  4890.9    0.03       0  4894.9    0.05       0
Bank Sta=4890.9,4894.9
Exp/Cntr=0.3,0.1

Type RM Length L Ch R = 1,191,152,152,152
BEGIN DESCRIPTION:
DUCK CREEK TRIB 14 1 2
END DESCRIPTION:
XS GIS Cut Line= 3
      3539497.20     10401737.35      3539225.07     10401715.21
      3539078.90     10402077.18
#Sta/Elev= 30
  4520.2  350.82  4545.4  344.44  4595.5  335.18  4615.6  329.77  4675.8  319.60
  4695.9  318.47  4715.9  315.90  4736.0  314.82  4756.1  315.09  4773.4  312.99
  4786.2  312.51  4916.7  313.52  4943.9  313.65  4983.5  313.24  4998.6  311.75
  4998.8  311.25  5002.6  311.75  5024.7  315.35  5037.4  316.27  5083.8  317.32
  5107.9  320.52  5113.3  319.88  5123.7  320.98  5132.0  322.59  5137.4  321.37
  5156.1  325.90  5161.6  329.65  5167.0  325.72  5177.6  331.61  5183.6  336.92
#Mann=5,-1,0
  4520.2    0.05       0  4916.7    0.12       0  4943.9    0.05       0
  4998.6    0.03       0  5002.6    0.05       0
Bank Sta=4998.6,5002.6
Exp/Cntr=0.3,0.1

Type RM Length L Ch R = 1,39,0,0,0
BEGIN DESCRIPTION:
DUCK CREEK TRIB 14 1 0
END DESCRIPTION:
XS GIS Cut Line= 4
      3539449.00     10401691.77      3539100.07     10401647.50
      3539015.70     10401775.28      3538961.00     10402113.84
#Sta/Elev= 30
  4396.1  334.37  4403.0  332.65  4432.5  327.95  4443.4  325.06  4512.6  317.34
  4544.2  315.05  4564.3  315.39  4580.4  314.19  4604.7  312.15  4715.5  312.22
  4744.3  311.59  4894.5  311.87  4899.7  312.41  4959.0  313.20  4988.4  312.16
  4996.6  308.28  4996.8  307.78  5000.3  307.78  5000.6  308.28  5008.7  310.82
  5015.6  312.08  5099.9  311.97  5130.2  312.67  5144.2  312.07  5170.8  312.17
  5180.9  312.49  5200.9  314.94  5205.9  312.81  5221.4  314.98  5243.9  316.37
#Mann=4,-1,0
  4396.1    0.05       0  4580.4    0.12       0  4996.6    0.07       0
  5000.6    0.12       0
Bank Sta=4996.6,5000.6
Exp/Cntr=0.3,0.1

Chan Stop Cuts=-1