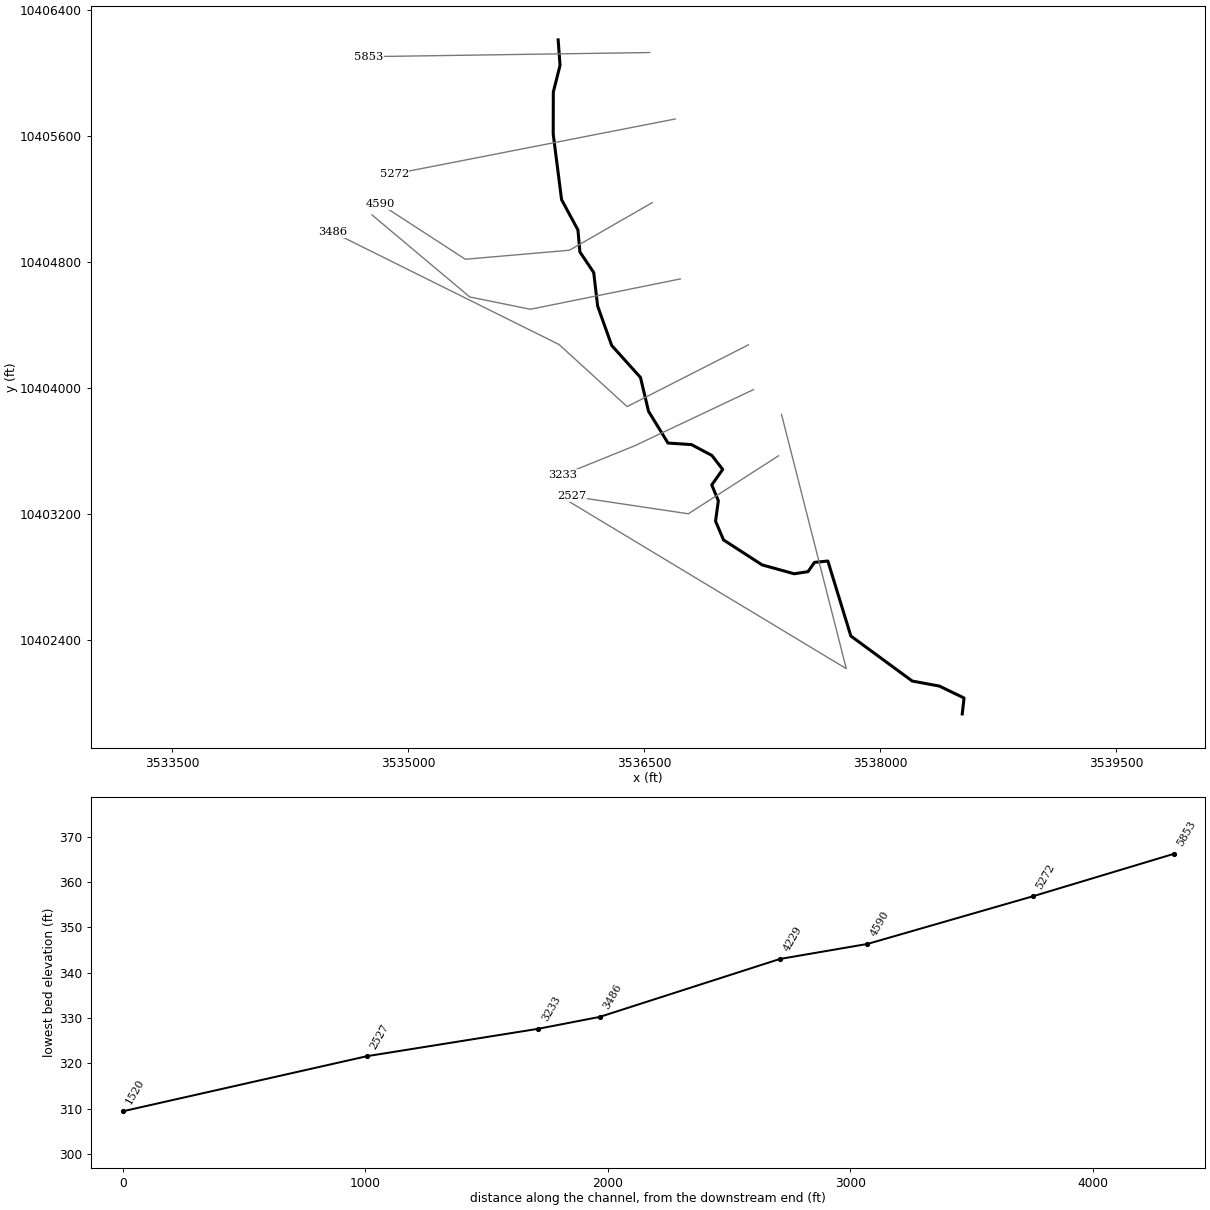
--- DUCK CREEK TRIB 15.prj (project) ---

Proj Title=DUCK CREEK TRIB 15 Base Level Engineering
Current Plan=p01
Default Exp/Contr=0.3,0.1
English Units
Geom File=g01
Flow File=f01
Plan File=p01
Y Axis Title=Elevation
X Axis Title(PF)=Main Channel Distance
X Axis Title(XS)=Station
BEGIN DESCRIPTION:
DUCK CREEK TRIB 15
END DESCRIPTION:
DSS Export Rating Curves= 0
DSS Export Rating Curve Sorted= 0
DSS Export Volume Flow Curves= 0
DXF OffsetX= 0
DXF OffsetY= 0
DXF ScaleX= 1
DXF ScaleY= 10

--- DUCK CREEK TRIB 15.p01 (plan) ---

Plan Title=Multiple Run
Short Identifier=Multiple
Geom File=g01
Flow File=f01
Subcritical Flow
K Sum by GR= 0
Std Step Tol= 0.01
Critical Tol= 0.01
Num of Std Step Trials= 20
Max Error Tol= 0.3
Flow Tol Ratio= 0.001
Split Flow NTrial= 30
Split Flow Tol= 0.02
Split Flow Ratio= 0.02
Log Output Level= 0
Friction Slope Method= 1
Unsteady Friction Slope Method= 2
Unsteady Bridges Friction Slope Method= 1
Parabolic Critical Depth
Global Vel Dist=  1 , 1 , 1
Global Log Level= 0
CheckData=True
Encroach Param= -1, 0, 0, 0
BEGIN DESCRIPTION:
Multiple Run
END DESCRIPTION:

--- DUCK CREEK TRIB 15.f01 (steady flow) ---

Flow Title=Multiple
Number of Profiles=7
Profile Names=10-year,25-year,50-year,1pct_min,100-year,1pct_plu,500-year
River Rch & RM= DUCK CREEK TRIB ,Reach-1,5853
   18928   28341   36768   34492   46646   63084   74859
Boundary for River Rch & Prof#=DUCK CREEK TRIB ,Reach-1,1
Up Type=0
Dn Type=3
Dn Slope=0.005
Boundary for River Rch & Prof#=DUCK CREEK TRIB ,Reach-1,2
Up Type=0
Dn Type=3
Dn Slope=0.005
Boundary for River Rch & Prof#=DUCK CREEK TRIB ,Reach-1,3
Up Type=0
Dn Type=3
Dn Slope=0.005
Boundary for River Rch & Prof#=DUCK CREEK TRIB ,Reach-1,4
Up Type=0
Dn Type=3
Dn Slope=0.005
Boundary for River Rch & Prof#=DUCK CREEK TRIB ,Reach-1,5
Up Type=0
Dn Type=3
Dn Slope=0.005
Boundary for River Rch & Prof#=DUCK CREEK TRIB ,Reach-1,6
Up Type=0
Dn Type=3
Dn Slope=0.005
Boundary for River Rch & Prof#=DUCK CREEK TRIB ,Reach-1,7
Up Type=0
Dn Type=3
Dn Slope=0.005

--- DUCK CREEK TRIB 15.g01 (geometry) ---

Geom Title=Existing Conditions
Program Version=4.10

River Reach=DUCK CREEK TRIB ,Reach-1
Reach XY= 30
      3535953.31     10406207.85      3535965.39      10406046.1
      3535922.58     10405876.36       3535921.9     10405609.72
      3535975.16     10405192.91      3536079.07     10405000.54
      3536091.43     10404861.21      3536179.22     10404730.45
       3536204.2     10404517.51      3536293.59     10404267.18
      3536476.48     10404064.03      3536527.68     10403849.24
      3536651.29      10403647.5      3536800.37     10403637.78
      3536930.18     10403568.82      3536998.92     10403479.96
      3536929.45     10403381.55      3536971.24     10403281.18
      3536953.44     10403151.66      3537004.32     10403032.36
      3537249.33     10402873.97      3537453.15     10402817.37
        3537541.     10402830.91      3537582.32     10402889.94
      3537667.14     10402898.48      3537813.18     10402422.43
      3538203.46     10402136.32      3538375.68     10402104.38
      3538532.63     10402028.68      3538521.03     10401927.46

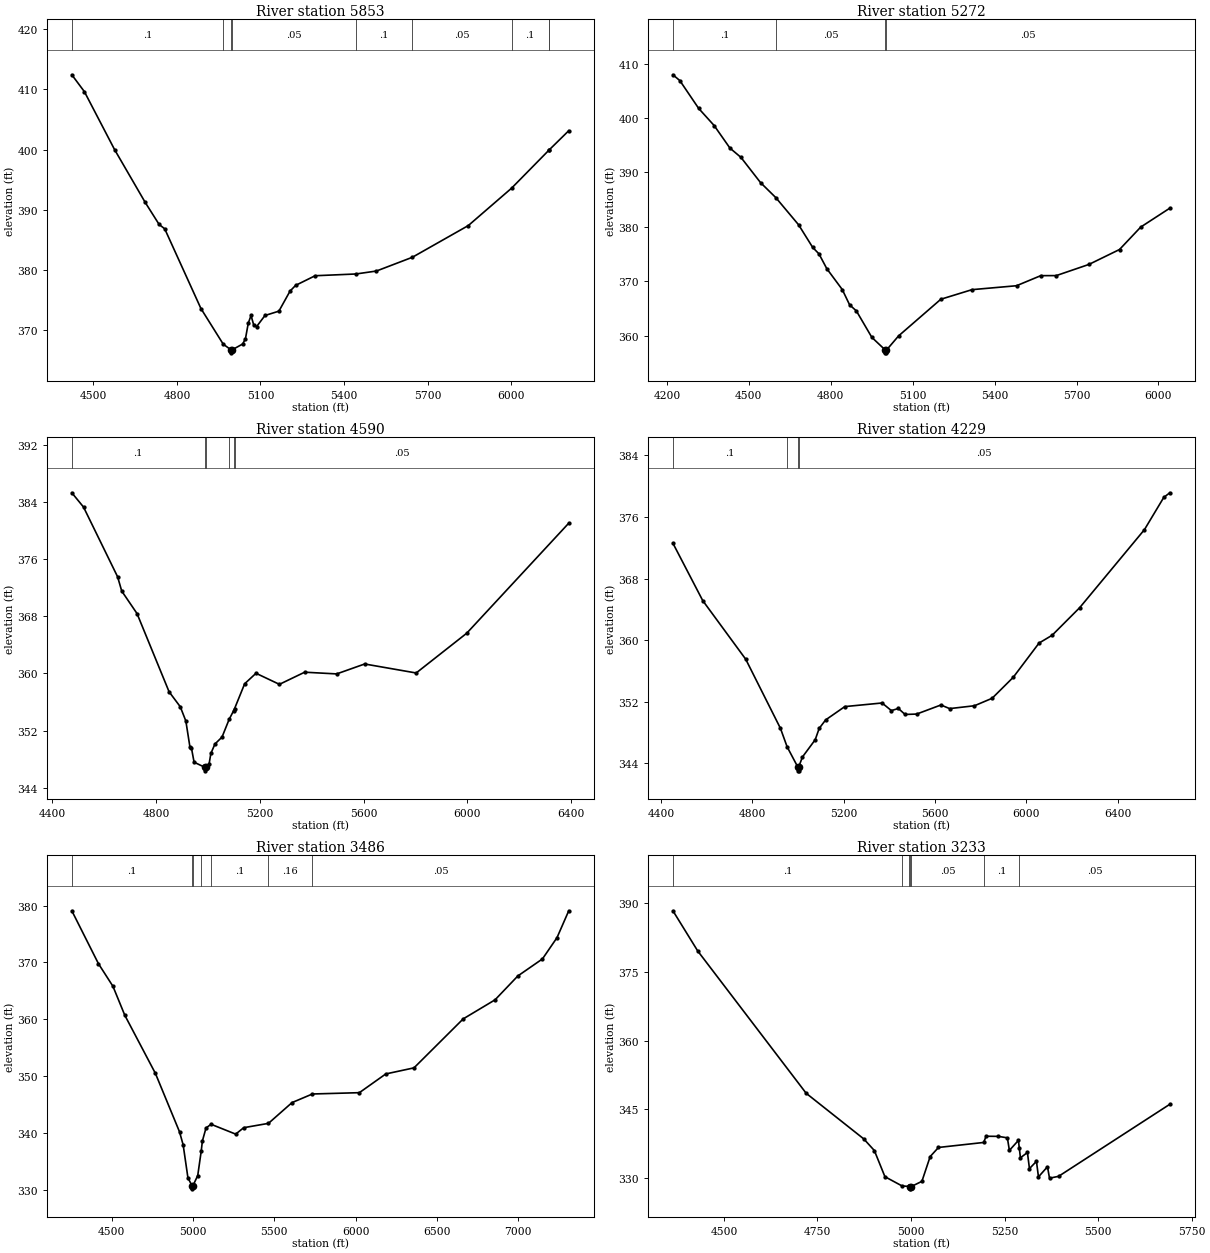
Type RM Length L Ch R = 1 ,5853    ,581,581,581
BEGIN DESCRIPTION:
DUCK CREEK TRIB 15 10
END DESCRIPTION:
XS GIS Cut Line= 2
      3536535.57     10406127.25      3534751.66     10406101.21
#Sta/Elev= 30
  4422.6  412.42  4467.7  409.62  4576.1     400  4686.1  391.23  4736.1  387.57
  4756.1  386.85  4886.1  373.62  4966.2   367.7  4994.1  366.76  4994.4  366.26
  4998.1  366.76  5036.1  367.73  5046.1  368.62  5056.1  371.18  5066.1  372.46
  5076.1  370.81  5086.1  370.62  5116.1  372.46  5166.1  373.18  5206.1  376.51
  5226.1  377.46  5296.2  379.06  5442.4  379.35  5516.2  379.84  5645.1  382.12
  5846.2  387.39  6001.4  393.59  6135.3  399.89  6135.7  399.91  6206.7  403.13
#Mann= 9 ,-1 , 0
  4422.6      .1       0  4966.2     .05       0  4994.1     .03       0
  4998.1     .05       0  5442.4      .1       0  5645.1     .05       0
  6001.4      .1       0  6135.3     .05       0  6135.7      .1       0
Bank Sta=4994.1,4998.1
XS Rating Curve= 0 ,0
Exp/Cntr=0.3,0.1

Type RM Length L Ch R = 1 ,5272    ,682,682,682
BEGIN DESCRIPTION:
DUCK CREEK TRIB 15 1 6
END DESCRIPTION:
XS GIS Cut Line= 2
      3536697.01     10405705.27      3534911.36     10405356.47
#Sta/Elev= 30
  4222.1  407.94  4247.5  406.87  4316.5  401.76  4373.1  398.62  4430.9  394.48
  4471.1  392.78    4543  388.14    4599  385.38  4682.4  380.39    4734  376.24
  4756.9  375.06  4785.6  372.34  4842.2  368.51    4869  365.71  4893.8  364.59
  4950.5  359.73    5000  357.39  5000.2  356.89  5003.7  356.89    5004  357.39
  5048.4     360  5203.1  366.73  5317.3  368.49  5480.3  369.21    5569  371.06
  5625.7  371.07  5745.3  373.12  5857.3  375.86    5935  379.98  6041.5  383.45
#Mann= 4 ,-1 , 0
  4222.1      .1       0    4599     .05       0    5000     .03       0
    5004     .05       0
Bank Sta=5000,5004
XS Rating Curve= 0 ,0
Exp/Cntr=0.3,0.1

Type RM Length L Ch R = 1 ,4590    ,361,361,361
BEGIN DESCRIPTION:
DUCK CREEK TRIB 15 1 5
END DESCRIPTION:
XS GIS Cut Line= 4
       3536551.2     10405174.04      3536025.12     10404871.93
      3535363.67     10404814.64      3534822.24     10405165.77
#Sta/Elev= 30
    4475  385.29  4520.1  383.29  4651.6  373.52  4667.4  371.53  4726.4  368.38
    4850  357.43  4893.2  355.33  4914.7  353.33  4930.5  349.67  4936.3  349.54
  4946.4  347.57  4987.5  346.86  4987.7  346.36  4991.5  346.86  5004.4  347.35
  5011.1  348.79  5026.9  350.12  5054.2  351.09  5081.6  353.57  5099.1  354.79
  5102.4  355.06  5141.4  358.55  5185.1  360.02  5275.4  358.47  5372.8  360.17
  5496.2  359.93  5604.1  361.32  5802.7  360.06  5997.7  365.63  6390.9  381.03
#Mann= 6 ,-1 , 0
    4475      .1       0  4987.5     .07       0  4991.5      .1       0
  5081.6     .05       0  5099.1      .1       0  5102.4     .05       0
Bank Sta=4987.5,4991.5
XS Rating Curve= 0 ,0
Exp/Cntr=0.3,0.1

Type RM Length L Ch R = 1 ,4229    ,743,743,743
BEGIN DESCRIPTION:
DUCK CREEK TRIB 15 1 4
END DESCRIPTION:
XS GIS Cut Line= 4
      3536730.21     10404689.75      3535777.08     10404497.04
      3535391.66     10404575.17      3534770.13     10405096.34
#Sta/Elev= 30
  4452.3  372.59    4583  365.14  4771.3  357.53  4923.5  348.55  4952.6  346.16
  4999.3  343.54  4999.5  343.04    5003  343.04  5003.3  343.54  5019.8  344.84
  5075.7  347.08  5093.1  348.55  5121.3  349.65  5205.3  351.38  5368.6  351.85
  5409.4  350.86    5440  351.14  5469.3  350.36    5520  350.41  5626.4  351.59
  5664.5  351.12  5773.3  351.49  5850.7  352.46  5943.1  355.18  6056.3  359.63
  6113.5  360.64  6234.5  364.23  6518.1  374.36  6602.7  378.54  6629.1  379.14
#Mann= 4 ,-1 , 0
  4452.3      .1       0  4952.6     .05       0  4999.3     .03       0
  5003.3     .05       0
Bank Sta=4999.3,5003.3
XS Rating Curve= 0 ,0
Exp/Cntr=0.3,0.1

Type RM Length L Ch R = 1 ,3486    ,253,253,253
BEGIN DESCRIPTION:
DUCK CREEK TRIB 15 1 3
END DESCRIPTION:
XS GIS Cut Line= 4
      3537162.52     10404271.36      3536391.66     10403878.99
      3535959.37     10404273.08       3534519.6     10404987.24
#Sta/Elev= 30
  4254.2  379.08  4418.1  369.78  4507.1  365.82  4580.1  360.73  4768.4  350.52
  4916.7  340.26  4939.1  337.97  4968.6  332.16  4994.5  330.74  4994.7  330.24
  4998.5  330.74  5028.9  332.58  5050.3  336.87  5057.6  338.66  5079.8  340.93
  5110.9  341.58  5262.4  339.85  5311.7  340.98  5463.9  341.74    5609  345.39
  5734.3   346.9  6023.2  347.13  6185.7  350.42  6359.4  351.49    6662  360.09
  6858.1  363.44  6998.2  367.63  7149.5  370.62  7239.2  374.36  7311.3  379.07
#Mann= 7 ,-1 , 0
  4254.2      .1       0  4994.5     .07       0  4998.5      .1       0
  5050.3     .07       0  5110.9      .1       0  5463.9     .16       0
  5734.3     .05       0
Bank Sta=4994.5,4998.5
XS Rating Curve= 0 ,0
Exp/Cntr=0.3,0.1

Type RM Length L Ch R = 1 ,3233    ,706,706,706
BEGIN DESCRIPTION:
DUCK CREEK TRIB 15 1 2
END DESCRIPTION:
XS GIS Cut Line= 3
      3537193.75     10403986.63       3536436.8     10403628.99
      3535981.91     10403444.95
#Sta/Elev= 30
  4363.7  388.36  4430.1  379.57  4719.9  348.49  4873.7  338.53    4902  335.99
  4930.3  330.27  4976.1  328.25  4993.3  328.16  4996.6  328.12  4996.8  327.62
  5000.6  328.12  5029.1  329.26  5051.2  334.67  5073.4  336.66  5194.1  337.75
  5200.7  339.11  5233.4  339.08  5257.5  338.76  5262.9  336.02    5287   338.2
  5289.2  336.65  5292.4   334.4  5311.1  335.56  5316.5  332.04  5335.2  333.63
  5340.6  330.23  5364.7  332.45  5370.1  329.95  5394.3  330.35  5691.6  346.09
#Mann= 7 ,-1 , 0
  4363.7      .1       0  4976.1     .07       0  4993.3     .05       0
  4996.6    .035       0  5000.6     .05       0  5194.1      .1       0
  5289.2     .05       0
Bank Sta=4996.6,5000.6
XS Rating Curve= 0 ,0
Exp/Cntr=0.3,0.1

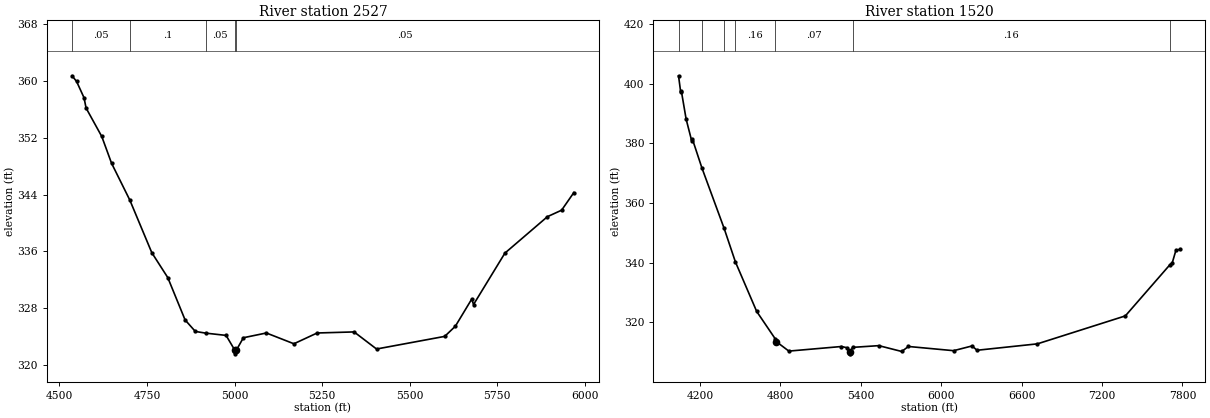
Type RM Length L Ch R = 1 ,2527    ,1007,1007,1007
BEGIN DESCRIPTION:
DUCK CREEK TRIB 15 1 1
END DESCRIPTION:
XS GIS Cut Line= 3
      3537353.49      10403566.5      3536780.55     10403198.43
      3536037.49     10403309.54
#Sta/Elev= 30
  4536.1  360.77    4549  359.97  4570.2  357.68  4576.1  356.22  4620.9  352.21
  4648.8  348.44    4701  343.24  4763.7  335.83  4809.3  332.32  4858.7  326.35
  4887.9  324.73  4917.4  324.49  4975.7  324.17  5000.8  322.07  5001.1  321.57
  5004.8  322.07  5025.1  323.84  5090.7  324.51  5169.3  322.99  5235.7  324.51
  5341.1  324.66  5405.2  322.25  5599.7  324.03  5630.1  325.46  5676.9  329.29
    5682  328.52  5771.6  335.77    5893  340.91  5933.4  341.82  5968.4  344.31
#Mann= 5 ,-1 , 0
  4536.1     .05       0    4701      .1       0  4917.4     .05       0
  5000.8     .03       0  5004.8     .05       0
Bank Sta=5000.8,5004.8
XS Rating Curve= 0 ,0
Exp/Cntr=0.3,0.1

Type RM Length L Ch R = 1 ,1520    ,0,0,0
BEGIN DESCRIPTION:
DUCK CREEK TRIB 15 1 0
END DESCRIPTION:
XS GIS Cut Line= 3
      3537372.66     10403829.77      3537784.13     10402215.14
      3536004.04     10403287.36
#Sta/Elev= 30
  4039.6  402.69  4055.4   397.3  4060.5   397.6  4096.3  388.14  4137.1  380.97
  4142.3  381.54  4213.1  371.89  4379.7   351.5  4464.2  340.21  4622.6  323.63
    4760   314.5  4770.4  313.44  4862.8  310.31  5255.4  311.85  5296.7  311.44
  5315.9  309.39  5319.7  309.89  5337.9  311.56    5534  312.14  5705.1  310.18
  5754.9  311.86    6092  310.45  6229.9  312.04  6266.7  310.59  6717.3  312.74
  7373.6  322.12  7707.6  339.36  7723.2  339.85  7751.1  344.15  7783.9  344.46
#Mann= 7 ,-1 , 0
  4039.6      .1       0  4213.1     .16       0  4379.7     .05       0
  4464.2     .16       0    4760     .07       0  5337.9     .16       0
  7707.6     .05       0
Bank Sta=4770.4,5319.7
XS Rating Curve= 0 ,0
Exp/Cntr=0.3,0.1

Chan Stop Cuts=-1
Use User Specified Reach Order=0
Composite Channel Slope=5