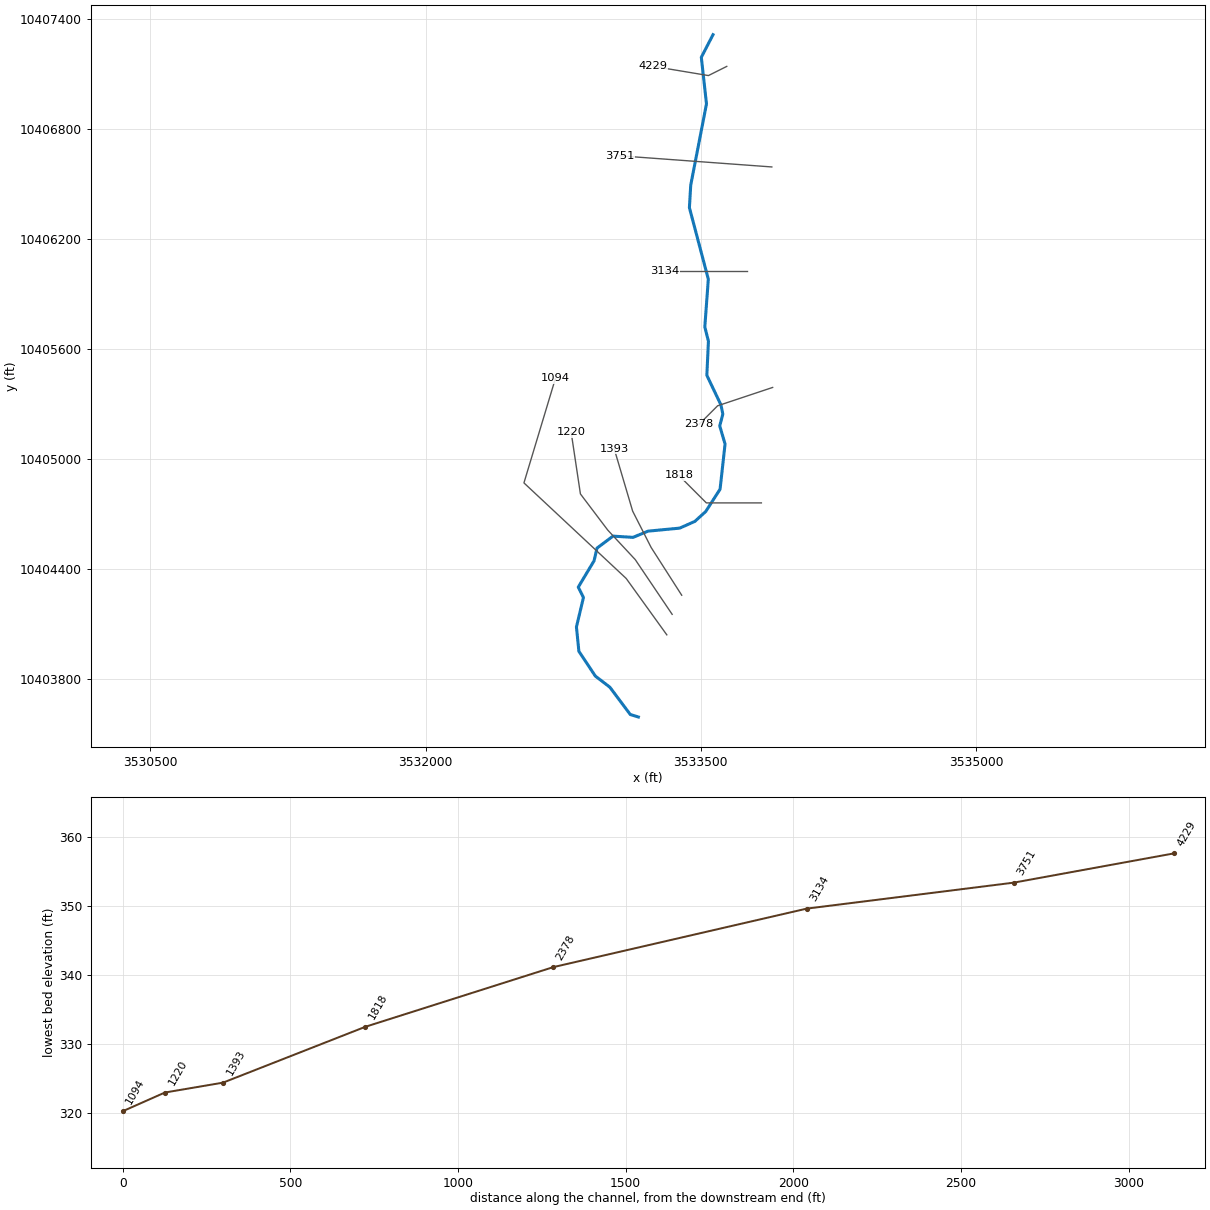
--- DUCK CREEK TRIB 16.prj (project) ---

Proj Title=DUCK CREEK TRIB 16 Base Level Engineering
Current Plan=p01
Default Exp/Contr=0.3,0.1
English Units
Geom File=g01
Flow File=f01
Plan File=p01
BEGIN DESCRIPTION:
DUCK CREEK TRIB 16
END DESCRIPTION:

--- DUCK CREEK TRIB 16.p01 (plan) ---

Plan Title=Multiple Run
Short Identifier=Multiple
Geom File=g01
Flow File=f01
Subcritical Flow
K Sum by GR= 0
Std Step Tol= 0.01
Critical Tol= 0.01
Num of Std Step Trials= 20
Max Error Tol= 0.3
Flow Tol Ratio= 0.001
Split Flow NTrial= 30
Split Flow Tol= 0.02
Split Flow Ratio= 0.02
Log Output Level= 0
Friction Slope Method= 1
Unsteady Friction Slope Method= 2
Unsteady Bridges Friction Slope Method= 1
Parabolic Critical Depth
Global Vel Dist=  1 , 1 , 1
Global Log Level= 0
CheckData=True
Encroach Param= -1, 0, 0, 0
BEGIN DESCRIPTION:
Multiple Run
END DESCRIPTION:

--- DUCK CREEK TRIB 16.f01 (steady flow) ---

Flow Title=Multiple
Number of Profiles=7
Profile Names=10-year,25-year,50-year,1pct_min,100-year,1pct_plu,500-year
River Rch & RM= DUCK CREEK TRIB ,Reach-1,4229
    1000    1393    1723    1557    2105    2847    3134
Boundary for River Rch & Prof#=DUCK CREEK TRIB ,Reach-1,1
Up Type=0
Dn Type=3
Dn Slope=0.005
Boundary for River Rch & Prof#=DUCK CREEK TRIB ,Reach-1,2
Up Type=0
Dn Type=3
Dn Slope=0.005
Boundary for River Rch & Prof#=DUCK CREEK TRIB ,Reach-1,3
Up Type=0
Dn Type=3
Dn Slope=0.005
Boundary for River Rch & Prof#=DUCK CREEK TRIB ,Reach-1,4
Up Type=0
Dn Type=3
Dn Slope=0.005
Boundary for River Rch & Prof#=DUCK CREEK TRIB ,Reach-1,5
Up Type=0
Dn Type=3
Dn Slope=0.005
Boundary for River Rch & Prof#=DUCK CREEK TRIB ,Reach-1,6
Up Type=0
Dn Type=3
Dn Slope=0.005
Boundary for River Rch & Prof#=DUCK CREEK TRIB ,Reach-1,7
Up Type=0
Dn Type=3
Dn Slope=0.005

--- DUCK CREEK TRIB 16.g01 (geometry) ---

Geom Title=Existing Conditions

River Reach=DUCK CREEK TRIB ,Reach-1
Reach XY= 30
      3533567.09     10407314.38      3533503.43     10407191.17
      3533531.50     10406936.99      3533445.69     10406494.71
      3533438.45     10406371.78      3533541.50     10405981.82
      3533522.48     10405721.42      3533542.18     10405643.50
      3533533.51     10405457.74      3533610.33     10405296.50
      3533620.70     10405246.64      3533603.79     10405182.07
      3533632.82     10405083.17      3533605.74     10404837.34
      3533527.27     10404715.12      3533468.24     10404661.65
      3533385.60     10404624.84      3533213.26     10404608.38
      3533131.09     10404574.54      3533021.95     10404581.21
      3532934.73     10404515.90      3532918.68     10404446.46
      3532832.73     10404303.28      3532860.94     10404246.68
      3532822.73     10404086.27      3532836.05     10403953.37
      3532925.71     10403818.31      3533004.41     10403758.30
      3533116.33     10403608.87      3533160.39     10403595.28

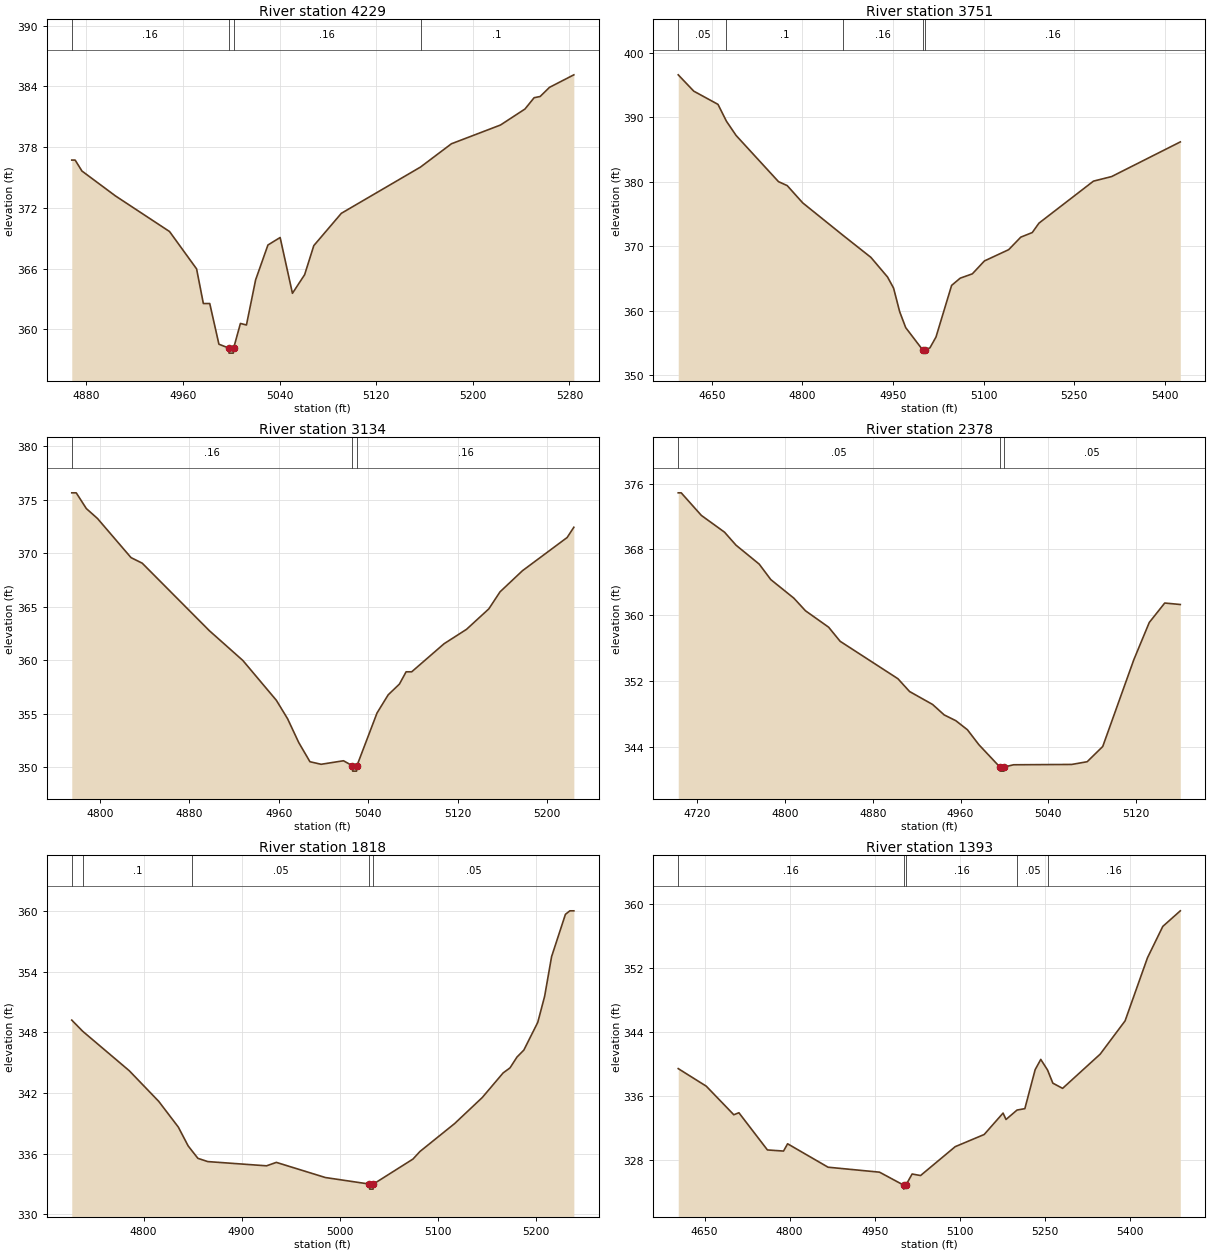
Type RM Length L Ch R = 1,4229,478,478,478
BEGIN DESCRIPTION:
DUCK CREEK TRIB 16 8 0
END DESCRIPTION:
XS GIS Cut Line= 3
      3533642.09     10407141.64      3533542.11     10407091.64
      3533242.13     10407141.64
#Sta/Elev= 30
  4867.8  376.72  4870.6  376.72  4876.2  375.64  4904.1  373.17  4948.8  369.66
  4971.2  365.97  4976.8  362.55  4982.1  362.55  4989.7  358.53  4997.9  358.15
  4998.1  357.65  5001.6  357.65  5001.9  358.15  5007.5  360.58  5012.5  360.43
  5020.1  364.89  5030.3  368.33  5040.4  369.07  5050.6  363.56  5060.7  365.40
  5068.3  368.27  5091.1  371.46  5156.7  376.03  5182.3  378.33  5222.9  380.18
  5243.2  381.76  5250.8  382.88  5255.8  383.00  5263.5  383.90  5283.7  385.14
#Mann=4,-1,0
  4867.8    0.16       0  4997.9    0.07       0  5001.9    0.16       0
  5156.7     0.1       0
Bank Sta=4997.9,5001.9
Exp/Cntr=0.3,0.1

Type RM Length L Ch R = 1,3751,617,617,617
BEGIN DESCRIPTION:
DUCK CREEK TRIB 16 10
END DESCRIPTION:
XS GIS Cut Line= 2
      3533887.70     10406593.50      3533058.72     10406654.27
#Sta/Elev= 30
  4594.6  396.54  4620.3  394.01  4660.4  391.96  4674.4  389.35  4690.4  387.14
  4760.6  379.98  4775.0  379.37  4800.7  376.69  4867.8  371.63  4913.6  368.24
  4941.1  365.20  4951.1  363.48  4961.2  359.82  4971.2  357.35  4999.3  353.90
  4999.5  353.40  5003.3  353.90  5011.3  354.22  5021.3  355.89  5047.2  363.90
  5061.4  365.02  5081.5  365.69  5101.5  367.69  5141.7  369.44  5161.7  371.38
  5180.7  372.09  5191.8  373.55  5282.0  380.06  5312.1  380.77  5425.8  386.14
#Mann=5,-1,0
  4594.6    0.05       0  4674.4     0.1       0  4867.8    0.16       0
  4999.3    0.07       0  5003.3    0.16       0
Bank Sta=4999.3,5003.3
Exp/Cntr=0.3,0.1

Type RM Length L Ch R = 1,3134,756,756,756
BEGIN DESCRIPTION:
DUCK CREEK TRIB 16 7 1
END DESCRIPTION:
XS GIS Cut Line= 3
      3533755.07     10406025.30      3533455.07     10406025.30
      3533306.07     10406025.30
#Sta/Elev= 30
  4775.0  375.66  4779.0  375.66  4788.0  374.19  4798.0  373.26  4828.0  369.60
  4838.0  369.08  4898.0  362.77  4928.0  359.98  4958.0  356.25  4968.0  354.53
  4978.0  352.30  4988.0  350.51  4998.0  350.27  5018.0  350.60  5026.0  350.13
  5026.2  349.63  5029.7  349.63  5030.0  350.13  5048.0  355.07  5058.0  356.77
  5068.0  357.77  5074.0  358.92  5079.0  358.92  5108.0  361.55  5128.0  362.89
  5148.0  364.81  5158.0  366.40  5178.0  368.37  5218.0  371.48  5224.0  372.44
#Mann=3,-1,0
  4775.0    0.16       0  5026.0    0.07       0  5030.0    0.16       0
Bank Sta=5026,5030
Exp/Cntr=0.3,0.1

Type RM Length L Ch R = 1,2378,560,560,560
BEGIN DESCRIPTION:
DUCK CREEK TRIB 16 5 0
END DESCRIPTION:
XS GIS Cut Line= 3
      3533892.14     10405391.65      3533592.11     10405291.64
      3533492.09     10405191.63
#Sta/Elev= 30
  4702.6  374.87  4705.3  374.87  4723.7  372.13  4744.8  370.10  4755.3  368.52
  4776.4  366.23  4787.0  364.35  4808.0  362.10  4818.6  360.57  4839.7  358.58
  4850.2  356.87  4902.9  352.33  4913.5  350.78  4934.5  349.21  4945.1  347.94
  4955.6  347.25  4966.2  346.15  4976.7  344.33  4995.8  341.63  4996.0  341.13
  4999.5  341.13  4999.8  341.63  5008.3  341.90  5061.3  341.94  5075.4  342.27
  5089.6  344.12  5117.9  354.63  5132.0  359.15  5146.1  361.51  5160.3  361.33
#Mann=3,-1,0
  4702.6    0.05       0  4995.8    0.03       0  4999.8    0.05       0
Bank Sta=4995.8,4999.8
Exp/Cntr=0.3,0.1

Type RM Length L Ch R = 1,1818,425,425,425
BEGIN DESCRIPTION:
DUCK CREEK TRIB 16 4 0
END DESCRIPTION:
XS GIS Cut Line= 3
      3533830.79     10404762.34      3533530.74     10404762.34
      3533380.73     10404912.36
#Sta/Elev= 30
  4726.8  349.22  4738.0  348.11  4785.5  344.20  4815.5  341.17  4835.5  338.62
  4845.5  336.76  4849.9  336.21  4855.5  335.52  4865.5  335.20  4925.5  334.78
  4935.5  335.12  4985.5  333.62  5030.5  332.97  5030.7  332.47  5034.2  332.47
  5034.5  332.97  5074.9  335.45  5082.0  336.20  5117.3  338.96  5145.6  341.55
  5166.8  343.98  5173.9  344.49  5181.0  345.56  5188.0  346.25  5202.2  349.00
  5209.2  351.58  5216.3  355.51  5230.4  359.70  5234.9  360.05  5239.0  360.05
#Mann=5,-1,0
  4726.8    0.05       0  4738.0     0.1       0  4849.9    0.05       0
  5030.5    0.03       0  5034.5    0.05       0
Bank Sta=5030.5,5034.5
Exp/Cntr=0.3,0.1

Type RM Length L Ch R = 1,1393,173,173,173
BEGIN DESCRIPTION:
DUCK CREEK TRIB 16 7 0
END DESCRIPTION:
XS GIS Cut Line= 4
      3533396.48     10404259.13      3533229.82     10404519.53
      3533129.13     10404717.45      3533028.60     10405057.16
#Sta/Elev= 30
  4603.6  339.42  4653.1  337.22  4701.6  333.65  4710.6  333.90  4760.9  329.25
  4789.3  329.11  4796.5  330.02  4867.9  327.09  4958.6  326.47  5001.1  324.85
  5001.4  324.35  5005.1  324.85  5016.1  326.24  5031.0  326.05  5092.1  329.66
  5143.2  331.18  5176.5  333.86  5181.7  333.06  5201.2  334.24  5214.9  334.41
  5233.1  339.29  5243.0  340.57  5255.0  339.24  5264.3  337.60  5281.5  336.95
  5347.8  341.23  5391.7  345.39  5431.2  353.28  5458.2  357.20  5489.1  359.15
#Mann=5,-1,0
  4603.6    0.16       0  5001.1    0.07       0  5005.1    0.16       0
  5201.2    0.05       0  5255.0    0.16       0
Bank Sta=5001.1,5005.1
Exp/Cntr=0.3,0.1

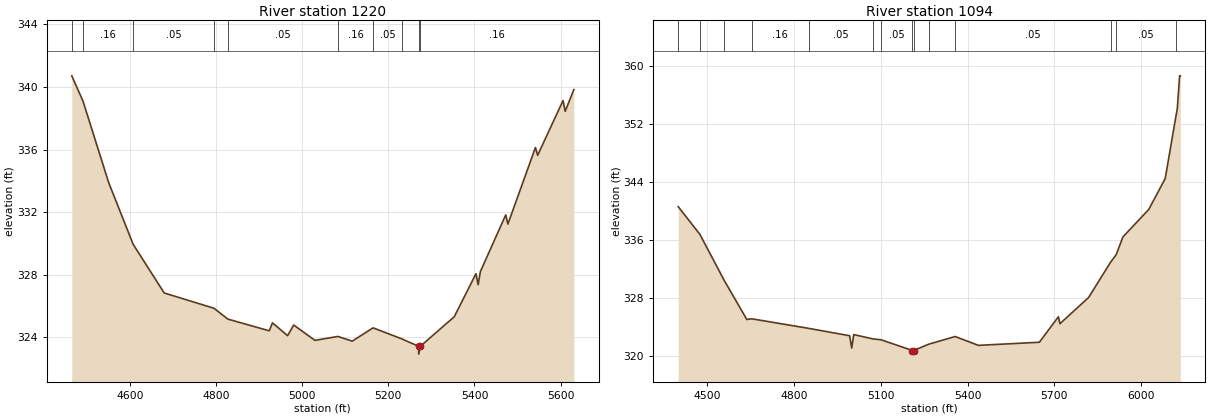
Type RM Length L Ch R = 1,1220,126,126,126
BEGIN DESCRIPTION:
DUCK CREEK TRIB 16 4 1
END DESCRIPTION:
XS GIS Cut Line= 5
      3533344.42     10404154.93      3533143.02     10404453.56
      3532993.45     10404614.08      3532844.41     10404811.20
      3532794.07     10405146.11
#Sta/Elev= 30
  4465.3  340.71  4491.3  339.10  4550.9  333.89  4607.8  329.94  4679.8  326.83
  4795.6  325.85  4827.5  325.16  4923.8  324.41  4931.1  324.92  4966.3  324.10
  4980.5  324.78  5029.8  323.80  5083.2  324.05  5116.3  323.75  5164.7  324.60
  5231.0  323.90  5270.4  323.42  5270.6  322.92  5274.4  323.42  5353.1  325.31
  5403.5  328.06  5408.6  327.36  5413.8  328.20  5472.6  331.82  5477.6  331.23
  5541.6  336.13  5546.7  335.63  5605.6  339.13  5610.6  338.44  5630.7  339.83
#Mann=10,-1,0
  4465.3    0.05       0  4491.3    0.16       0  4607.8    0.05       0
  4795.6    0.16       0  4827.5    0.05       0  5083.2    0.16       0
  5164.7    0.05       0  5231.0    0.16       0  5270.4    0.03       0
  5274.4    0.16       0
Bank Sta=5270.4,5274.4
Exp/Cntr=0.3,0.1

Type RM Length L Ch R = 1,1094,0,0,0
BEGIN DESCRIPTION:
DUCK CREEK TRIB 16 3 0
END DESCRIPTION:
XS GIS Cut Line= 4
      3533315.24     10404043.18      3533093.86     10404350.51
      3532536.56     10404871.35      3532708.44     10405441.66
#Sta/Elev= 30
  4399.1  340.56  4474.0  336.74  4558.1  330.39  4636.5  324.98  4652.9  325.08
  4850.3  323.76  4992.1  322.74  4999.3  321.05  5006.3  322.90  5071.9  322.31
  5101.1  322.18  5209.5  320.70  5209.7  320.20  5213.5  320.70  5266.3  321.58
  5357.4  322.63  5437.7  321.41  5648.6  321.84  5714.5  325.36  5719.8  324.40
  5818.8  328.01  5895.3  332.91  5914.3  333.92  5937.8  336.39  6027.2  340.18
  6084.1  344.45  6121.9  353.22  6125.8  354.07  6134.0  358.63  6136.3  358.63
#Mann=14,-1,0
  4399.1    0.05       0  4474.0    0.16       0  4558.1    0.05       0
  4652.9    0.16       0  4850.3    0.05       0  5071.9    0.12       0
  5101.1    0.05       0  5209.5    0.03       0  5213.5    0.05       0
  5266.3    0.16       0  5357.4    0.05       0  5895.3    0.16       0
  5914.3    0.05       0  6121.9    0.16       0
Bank Sta=5209.5,5213.5
Exp/Cntr=0.3,0.1

Chan Stop Cuts=-1