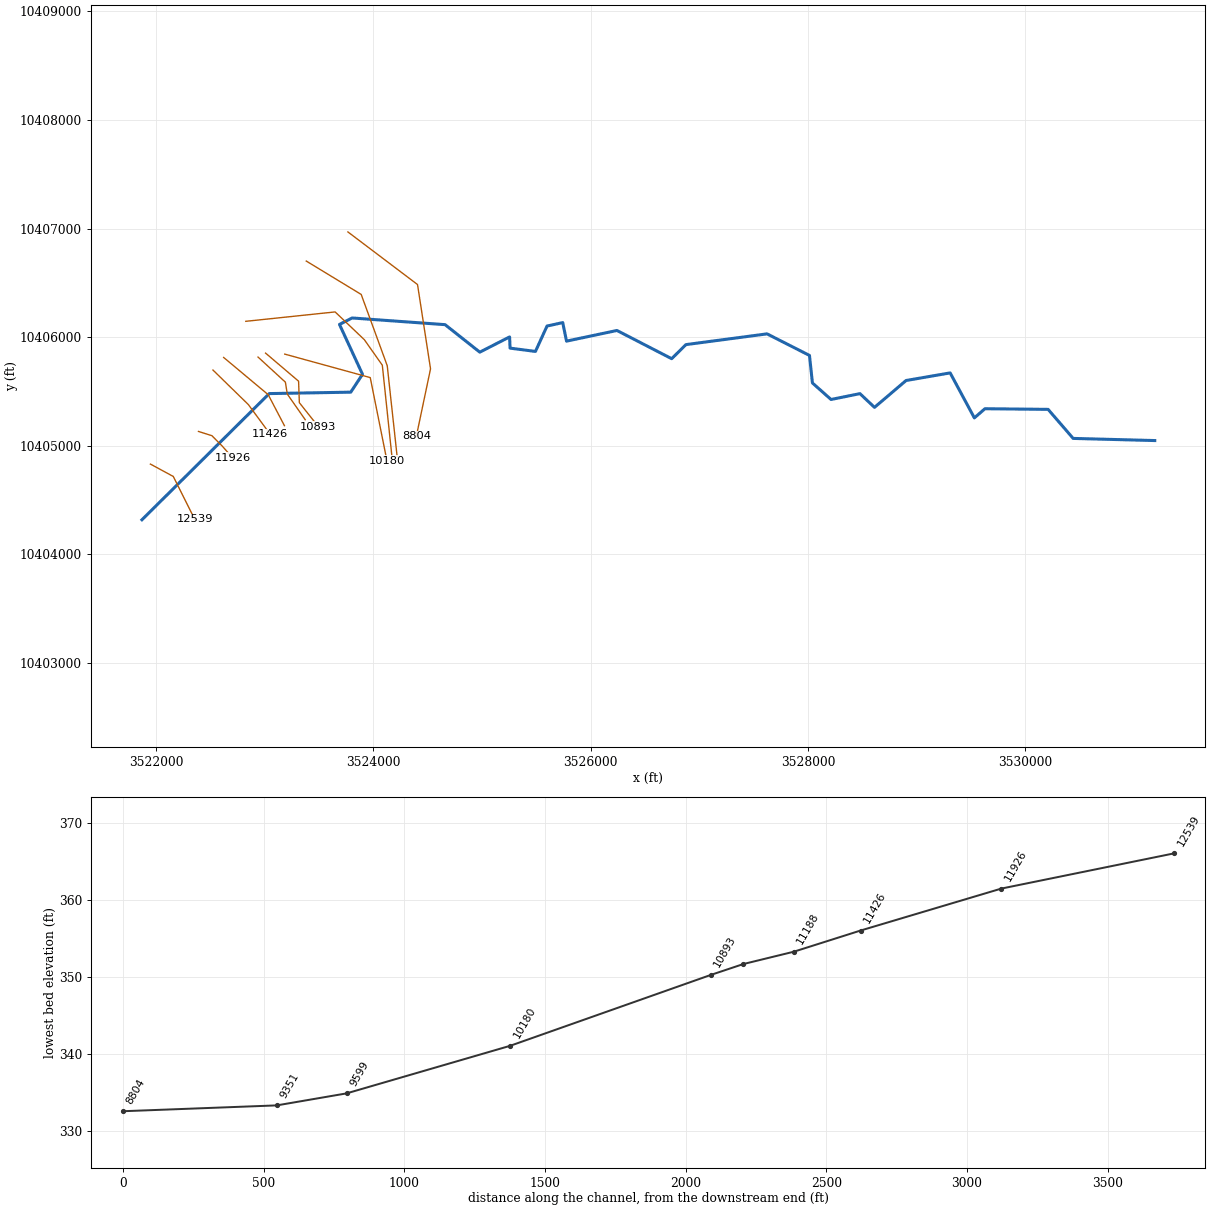
--- DUCK CREEK TRIB 17 3.prj (project) ---

Proj Title=DUCK CREEK TRIB 17 3 Base Level Engineering
Current Plan=p01
Default Exp/Contr=0.3,0.1
English Units
Geom File=g01
Flow File=f01
Plan File=p01
Y Axis Title=Elevation
X Axis Title(PF)=Main Channel Distance
X Axis Title(XS)=Station
BEGIN DESCRIPTION:
DUCK CREEK TRIB 17 3
END DESCRIPTION:
DSS Export Rating Curves= 0
DSS Export Rating Curve Sorted= 0
DSS Export Volume Flow Curves= 0
DXF OffsetX= 0
DXF OffsetY= 0
DXF ScaleX= 1
DXF ScaleY= 10

--- DUCK CREEK TRIB 17 3.p01 (plan) ---

Plan Title=Multiple Run
Short Identifier=Multiple
Geom File=g01
Flow File=f01
Subcritical Flow
K Sum by GR= 0
Std Step Tol= 0.01
Critical Tol= 0.01
Num of Std Step Trials= 20
Max Error Tol= 0.3
Flow Tol Ratio= 0.001
Split Flow NTrial= 30
Split Flow Tol= 0.02
Split Flow Ratio= 0.02
Log Output Level= 0
Friction Slope Method= 1
Unsteady Friction Slope Method= 2
Unsteady Bridges Friction Slope Method= 1
Parabolic Critical Depth
Global Vel Dist=  1 , 1 , 1
Global Log Level= 0
CheckData=True
Encroach Param= -1, 0, 0, 0
BEGIN DESCRIPTION:
Multiple Run
END DESCRIPTION:

--- DUCK CREEK TRIB 17 3.f01 (steady flow) ---

Flow Title=Multiple
Number of Profiles=7
Profile Names=10-year,25-year,50-year,1pct_min,100-year,1pct_plu,500-year
River Rch & RM= DUCK CREEK TRIB ,Reach-1,12539
     574     781     950     848    1147    1551    1664
River Rch & RM= DUCK CREEK TRIB ,Reach-1,11009
    1189    1681    2098    1914    2588    3500    3927
Boundary for River Rch & Prof#=DUCK CREEK TRIB ,Reach-1,1
Up Type=0
Dn Type=3
Dn Slope=0.005
Boundary for River Rch & Prof#=DUCK CREEK TRIB ,Reach-1,2
Up Type=0
Dn Type=3
Dn Slope=0.005
Boundary for River Rch & Prof#=DUCK CREEK TRIB ,Reach-1,3
Up Type=0
Dn Type=3
Dn Slope=0.005
Boundary for River Rch & Prof#=DUCK CREEK TRIB ,Reach-1,4
Up Type=0
Dn Type=3
Dn Slope=0.005
Boundary for River Rch & Prof#=DUCK CREEK TRIB ,Reach-1,5
Up Type=0
Dn Type=3
Dn Slope=0.005
Boundary for River Rch & Prof#=DUCK CREEK TRIB ,Reach-1,6
Up Type=0
Dn Type=3
Dn Slope=0.005
Boundary for River Rch & Prof#=DUCK CREEK TRIB ,Reach-1,7
Up Type=0
Dn Type=3
Dn Slope=0.005

--- DUCK CREEK TRIB 17 3.g01 (geometry) ---

Geom Title=Existing Conditions

River Reach=DUCK CREEK TRIB ,Reach-1
Reach XY= 30
      3521870.40     10404318.91      3523041.75     10405480.80
      3523791.89     10405493.97      3523899.88     10405658.55
      3523688.01     10406117.62      3523804.15     10406176.99
      3524659.50     10406115.55      3524979.03     10405862.25
      3525253.34     10406002.52      3525257.66     10405899.26
      3525491.20     10405868.96      3525597.72     10406102.53
      3525742.16     10406134.41      3525777.16     10405963.73
      3526241.06     10406061.90      3526744.70     10405802.01
      3526875.95     10405931.70      3527622.13     10406030.66
      3528012.57     10405832.07      3528039.70     10405578.42
      3528211.11     10405426.43      3528476.80     10405480.42
      3528610.98     10405353.93      3528901.30     10405601.15
      3529307.01     10405671.34      3529529.56     10405257.09
      3529627.22     10405341.48      3530208.26     10405335.48
      3530438.76     10405068.11      3531189.71     10405048.37

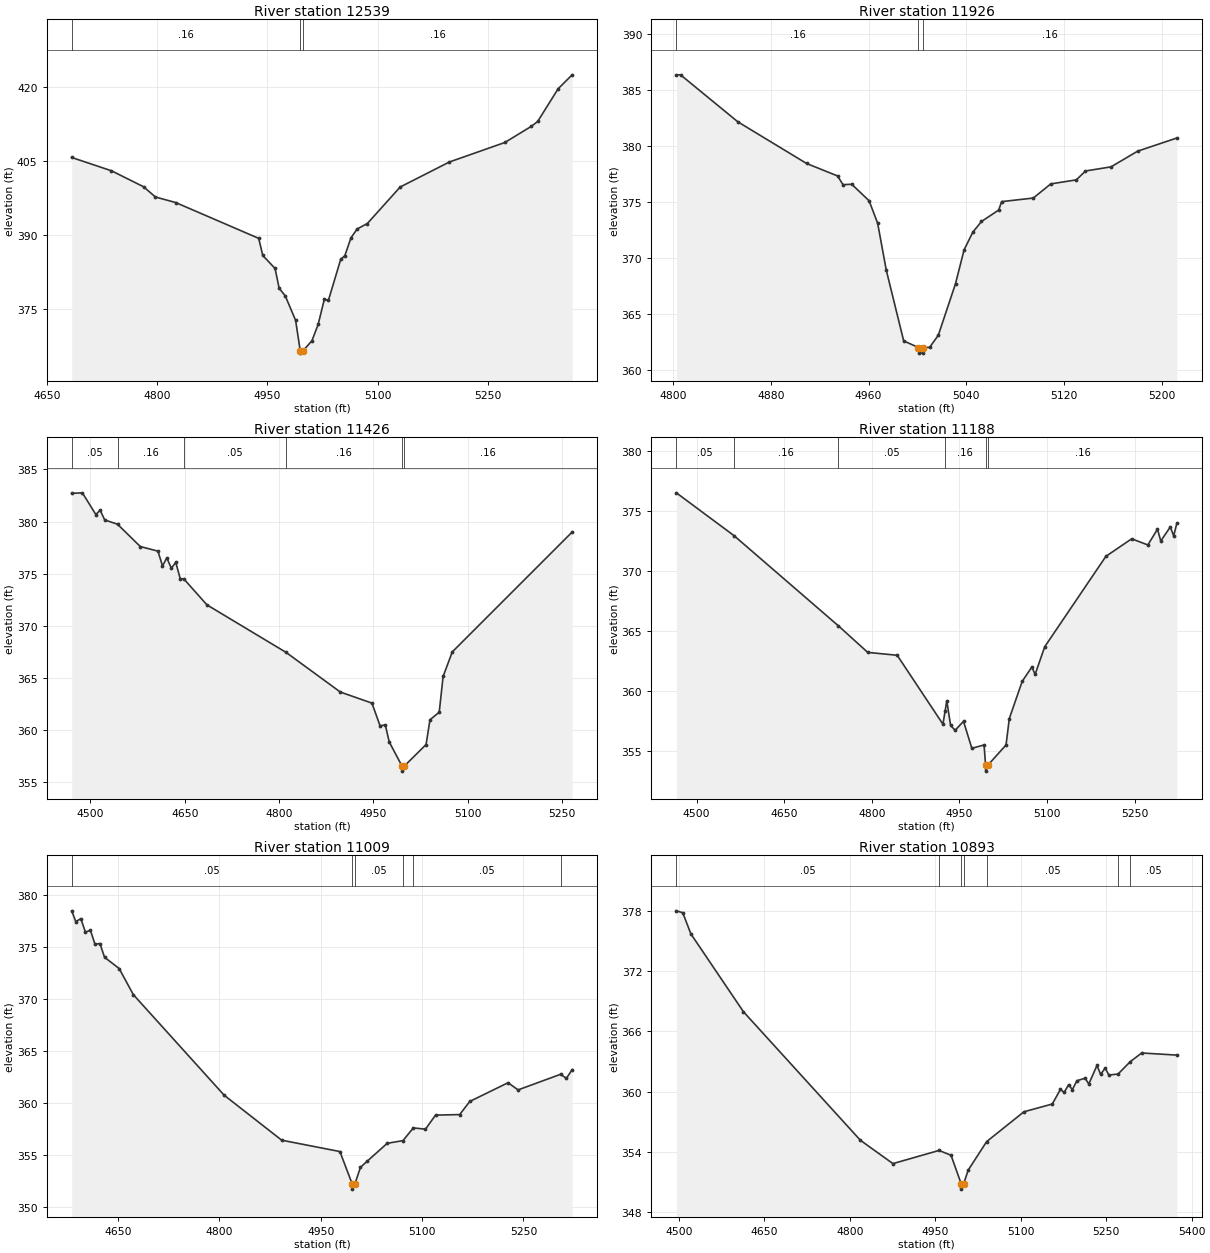
Type RM Length L Ch R = 1,12539,613,613,613
BEGIN DESCRIPTION:
DUCK CREEK TRIB 17 3 11 0
END DESCRIPTION:
XS GIS Cut Line= 3
      3521948.44     10404831.88      3522158.99     10404717.73
      3522356.84     10404322.04
#Sta/Elev= 30
  4683.3  405.79  4737.5  403.09  4781.2  399.85  4797.4  397.77  4824.9  396.65
  4938.1  389.38  4943.7  385.90  4960.4  383.27  4966.0  379.25  4974.3  377.71
  4988.4  372.74  4994.7  366.59  4994.9  366.09  4998.7  366.59  5010.7  368.62
  5019.1  371.90  5027.5  376.99  5033.1  376.80  5049.9  385.13  5055.5  385.87
  5063.8  389.47  5072.2  391.28  5086.1  392.38  5130.9  399.80  5197.9  404.87
  5273.5  408.83  5309.7  412.12  5318.2  413.09  5346.2  419.75  5365.2  422.56
#Mann=3,-1,0
  4683.3    0.16       0  4994.7    0.07       0  4998.7    0.16       0
Bank Sta=4994.7,4998.7
Exp/Cntr=0.3,0.1

Type RM Length L Ch R = 1,11926,500,500,500
BEGIN DESCRIPTION:
DUCK CREEK TRIB 17 3 10
END DESCRIPTION:
XS GIS Cut Line= 4
      3522390.54     10405132.22      3522514.23     10405093.16
      3522610.43     10404996.22      3522705.23     10404889.13
#Sta/Elev= 30
  4802.8  386.32  4806.2  386.32  4853.1  382.13  4909.3  378.42  4934.6  377.31
  4939.1  376.53  4946.2  376.57  4960.4  375.10  4967.4  373.10  4974.5  368.90
  4988.7  362.61  5000.8  362.02  5001.1  361.52  5004.6  361.52  5004.8  362.02
  5009.9  362.03  5017.0  363.11  5031.1  367.71  5038.1  370.72  5045.2  372.29
  5052.3  373.25  5066.4  374.27  5068.8  375.02  5094.7  375.34  5109.0  376.60
  5129.9  376.96  5137.4  377.75  5158.3  378.12  5180.1  379.52  5212.1  380.69
#Mann=3,-1,0
  4802.8    0.16       0  5000.8    0.07       0  5004.8    0.16       0
Bank Sta=5000.8,5004.8
Exp/Cntr=0.3,0.1

Type RM Length L Ch R = 1,11426,238,238,238
BEGIN DESCRIPTION:
DUCK CREEK TRIB 17 3 6 0
END DESCRIPTION:
XS GIS Cut Line= 3
      3522523.91     10405697.58      3522849.44     10405379.86
      3523051.56     10405105.19
#Sta/Elev= 30
  4470.1  382.70  4487.1  382.75  4508.5  380.67  4515.4  381.08  4522.6  380.15
  4543.0  379.74  4579.2  377.60  4607.3  377.16  4614.5  375.74  4621.4  376.51
  4628.6  375.52  4635.6  376.09  4642.7  374.52  4648.4  374.50  4685.2  372.01
  4811.1  367.45  4897.4  363.65  4947.6  362.59  4960.5  360.42  4968.9  360.49
  4975.1  358.87  4995.3  356.57  4995.5  356.07  4999.3  356.57  5033.7  358.62
  5039.9  360.99  5054.6  361.72  5060.8  365.15  5075.4  367.50  5266.0  378.99
#Mann=6,-1,0
  4470.1    0.05       0  4543.0    0.16       0  4648.4    0.05       0
  4811.1    0.16       0  4995.3    0.07       0  4999.3    0.16       0
Bank Sta=4995.3,4999.3
Exp/Cntr=0.3,0.1

Type RM Length L Ch R = 1,11188,179,179,179
BEGIN DESCRIPTION:
DUCK CREEK TRIB 17 3 52
END DESCRIPTION:
XS GIS Cut Line= 3
      3522622.20     10405813.64      3523032.20     10405470.73
      3523181.50     10405185.44
#Sta/Elev= 30
  4465.5  376.49  4564.0  372.93  4742.6  365.42  4793.0  363.20  4843.4  362.96
  4921.7  357.22  4925.3  358.28  4928.3  359.17  4934.8  357.12  4942.6  356.71
  4956.9  357.46  4971.2  355.21  4992.1  355.49  4994.7  353.81  4994.9  353.31
  4998.7  353.81  5029.7  355.49  5035.3  357.69  5057.4  360.79  5073.8  361.98
  5079.5  361.37  5095.9  363.67  5200.6  371.20  5244.7  372.66  5272.4  372.15
  5288.9  373.46  5294.5  372.48  5310.9  373.65  5316.6  372.90  5322.0  373.95
#Mann=6,-1,0
  4465.5    0.05       0  4564.0    0.16       0  4742.6    0.05       0
  4925.3    0.16       0  4994.7    0.07       0  4998.7    0.16       0
Bank Sta=4994.7,4998.7
Exp/Cntr=0.3,0.1

Type RM Length L Ch R = 1,11009,116,116,116
BEGIN DESCRIPTION:
DUCK CREEK TRIB 17 3 4 1
END DESCRIPTION:
XS GIS Cut Line= 4
      3522938.57     10405817.05      3523190.34     10405586.12
      3523207.70     10405476.74      3523372.63     10405240.62
#Sta/Elev= 30
  4581.7  378.44  4587.8  377.40  4595.2  377.69  4602.0  376.40  4609.4  376.57
  4616.2  375.23  4623.5  375.30  4630.3  373.98  4651.9  372.90  4672.9  370.39
  4807.3  360.73  4892.4  356.41  4978.5  355.32  4996.7  352.21  4997.0  351.71
  5000.7  352.21  5008.9  353.80  5019.0  354.40  5048.5  356.11  5071.9  356.37
  5087.1  357.59  5105.1  357.47  5120.0  358.82  5155.7  358.87  5170.6  360.13
  5227.3  361.93  5242.1  361.24  5305.0  362.74  5313.6  362.35  5322.1  363.19
#Mann=6,-1,0
  4581.7    0.05       0  4996.7    0.04       0  5000.7    0.05       0
  5071.9    0.16       0  5087.1    0.05       0  5305.0    0.16       0
Bank Sta=4996.7,5000.7
Exp/Cntr=0.3,0.1

Type RM Length L Ch R = 1,10893,713,713,713
BEGIN DESCRIPTION:
DUCK CREEK TRIB 17 3 4 3
END DESCRIPTION:
XS GIS Cut Line= 4
      3523008.06     10405853.46      3523311.86     10405594.80
      3523318.81     10405396.88      3523494.06     10405176.51
#Sta/Elev= 30
  4495.4  377.99  4506.6  377.80  4520.9  375.69  4613.1  367.95  4818.5  355.15
  4875.6  352.83  4956.5  354.14  4977.6  353.66  4995.6  350.79  4995.9  350.29
  4999.6  350.79  5007.6  352.17  5040.1  355.02  5105.6  357.99  5155.3  358.76
  5169.7  360.22  5176.1  359.91  5184.1  360.69  5190.5  360.19  5198.6  361.08
  5213.0  361.33  5219.4  360.75  5233.8  362.60  5240.2  361.71  5248.2  362.34
  5254.6  361.65  5270.7  361.74  5292.5  362.99  5312.3  363.84  5374.0  363.63
#Mann=7,-1,0
  4495.4    0.05       0  4956.5    0.16       0  4995.6    0.07       0
  4999.6    0.16       0  5040.1    0.05       0  5270.7    0.16       0
  5292.5    0.05       0
Bank Sta=4995.6,4999.6
Exp/Cntr=0.3,0.1

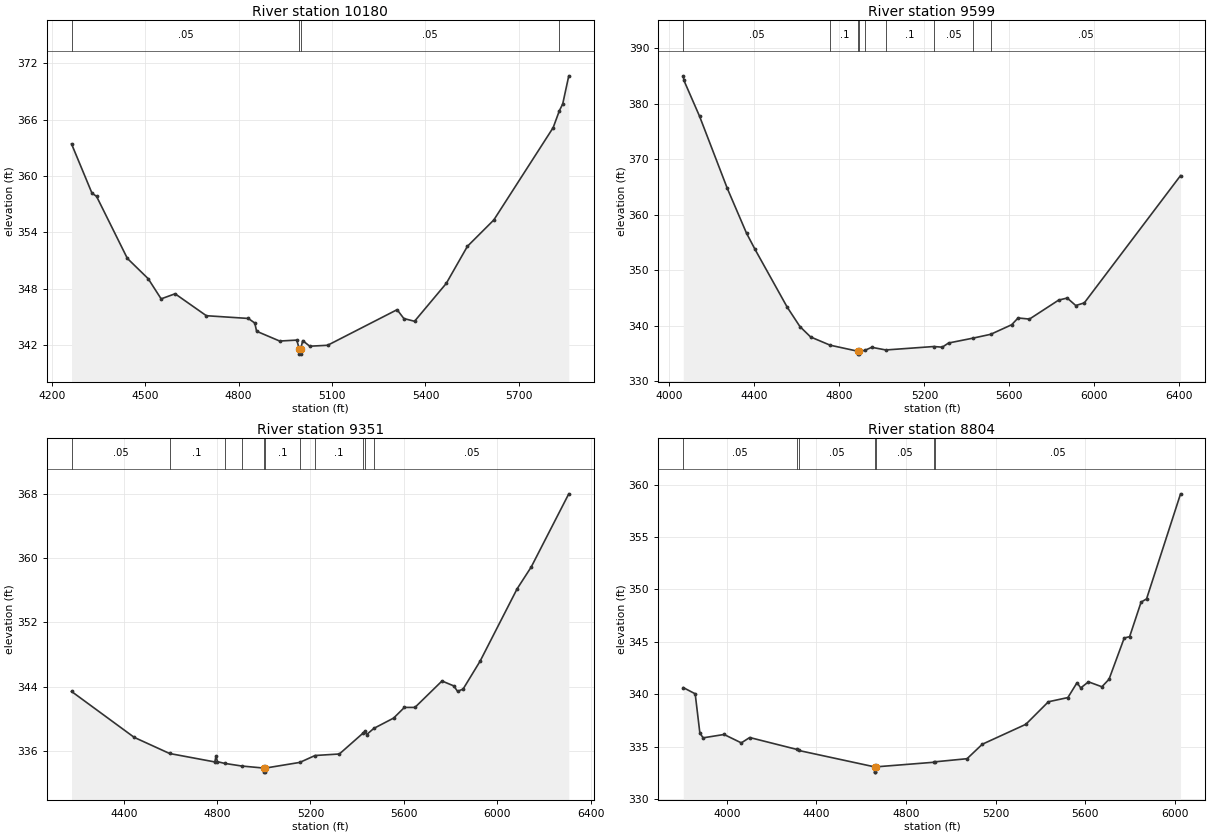
Type RM Length L Ch R = 1,10180,581,581,581
BEGIN DESCRIPTION:
DUCK CREEK TRIB 17 3 12 0
END DESCRIPTION:
XS GIS Cut Line= 3
      3523184.72     10405844.25      3523971.18     10405628.10
      3524124.82     10404862.49
#Sta/Elev= 30
  4263.6  363.41  4329.2  358.18  4343.9  357.84  4442.8  351.25  4509.8  349.09
  4551.3  346.95  4596.1  347.49  4696.5  345.16  4831.3  344.87  4852.0  344.38
  4857.8  343.51  4931.8  342.47  4986.8  342.57  4995.2  341.58  4995.5  341.08
  4999.0  341.08  4999.2  341.58  5005.8  342.52  5028.3  341.92  5085.8  342.02
  5308.9  345.80  5330.6  344.86  5364.9  344.57  5466.7  348.59  5534.6  352.53
  5619.4  355.33  5810.0  365.14  5830.1  366.95  5840.6  367.65  5860.1  370.64
#Mann=4,-1,0
  4263.6    0.05       0  4995.2    0.03       0  4999.2    0.05       0
  5830.1    0.16       0
Bank Sta=4995.2,4999.2
Exp/Cntr=0.3,0.1

Type RM Length L Ch R = 1,9599,248,248,248
BEGIN DESCRIPTION:
DUCK CREEK TRIB 17 3 13 0
END DESCRIPTION:
XS GIS Cut Line= 5
      3522826.10     10406146.20      3523648.10     10406232.68
      3523917.20     10405976.61      3524082.13     10405742.23
      3524171.70     10404891.12
#Sta/Elev= 30
  4065.3  385.01  4067.9  384.21  4141.7  377.74  4272.4  364.74  4362.9  356.67
  4403.2  353.74  4554.0  343.38  4614.3  339.86  4664.6  337.99  4756.4  336.51
  4889.3  335.40  4889.6  334.90  4893.1  334.90  4893.3  335.40  4919.1  335.57
  4952.1  336.13  5018.6  335.65  5244.7  336.27  5284.1  336.15  5313.7  336.90
  5428.8  337.78  5512.1  338.47  5610.8  340.19  5641.0  341.41  5694.6  341.21
  5832.0  344.63  5872.3  345.00  5912.5  343.65  5952.7  344.13  6405.7  367.05
#Mann=9,-1,0
  4065.3    0.05       0  4756.4     0.1       0  4889.3    0.03       0
  4893.3     0.1       0  4919.1    0.05       0  5018.6     0.1       0
  5244.7    0.05       0  5428.8     0.1       0  5512.1    0.05       0
Bank Sta=4889.3,4893.3
Exp/Cntr=0.3,0.1

Type RM Length L Ch R = 1,9351,547,547,547
BEGIN DESCRIPTION:
DUCK CREEK TRIB 17 3 4 0
END DESCRIPTION:
XS GIS Cut Line= 4
      3523382.66     10406701.00      3523887.84     10406393.72
      3524127.43     10405737.47      3524218.57     10404901.54
#Sta/Elev= 30
  4176.1  343.39  4444.7  337.67  4596.3  335.66  4790.0  334.61  4795.3  335.33
  4801.5  334.64  4832.0  334.43  4905.6  334.10  5001.8  333.84  5002.1  333.34
  5005.6  333.34  5005.8  333.84  5154.1  334.55  5219.8  335.41  5323.9  335.60
  5425.8  338.21  5432.4  338.42  5440.8  338.02  5471.7  338.79  5556.3  340.07
  5602.6  341.40  5647.7  341.40  5763.6  344.69  5813.9  344.08  5830.5  343.40
  5854.1  343.69  5926.9  347.16  6085.5  356.17  6145.8  358.88  6306.9  368.00
#Mann=11,-1,0
  4176.1    0.05       0  4596.3     0.1       0  4832.0    0.05       0
  4905.6     0.1       0  5001.8    0.07       0  5005.8     0.1       0
  5154.1    0.05       0  5219.8     0.1       0  5425.8    0.05       0
  5432.4     0.1       0  5471.7    0.05       0
Bank Sta=5001.8,5005.8
Exp/Cntr=0.3,0.1

Type RM Length L Ch R = 1,8804,0,0,0
BEGIN DESCRIPTION:
DUCK CREEK TRIB 17 3 3 2
END DESCRIPTION:
XS GIS Cut Line= 4
      3523765.46     10406969.24      3524406.07     10406484.87
      3524525.87     10405708.83      3524395.65     10405089.01
#Sta/Elev= 30
  3805.0  340.64  3858.1  340.05  3879.0  336.31  3893.5  335.85  3987.1  336.17
  4064.2  335.37  4101.6  335.88  4313.6  334.74  4319.8  334.65  4660.0  333.08
  4660.2  332.58  4663.7  332.58  4664.0  333.08  4923.8  333.52  4928.1  333.56
  5072.8  333.86  5140.9  335.24  5335.4  337.14  5436.2  339.29  5523.3  339.69
  5564.2  341.11  5580.7  340.61  5615.3  341.19  5675.3  340.72  5707.2  341.44
  5775.0  345.37  5799.2  345.50  5850.3  348.79  5874.8  349.10  6026.7  359.12
#Mann=7,-1,0
  3805.0    0.05       0  4313.6     0.1       0  4319.8    0.05       0
  4660.0    0.03       0  4664.0    0.05       0  4923.8     0.1       0
  4928.1    0.05       0
Bank Sta=4660,4664
Exp/Cntr=0.3,0.1

Chan Stop Cuts=-1