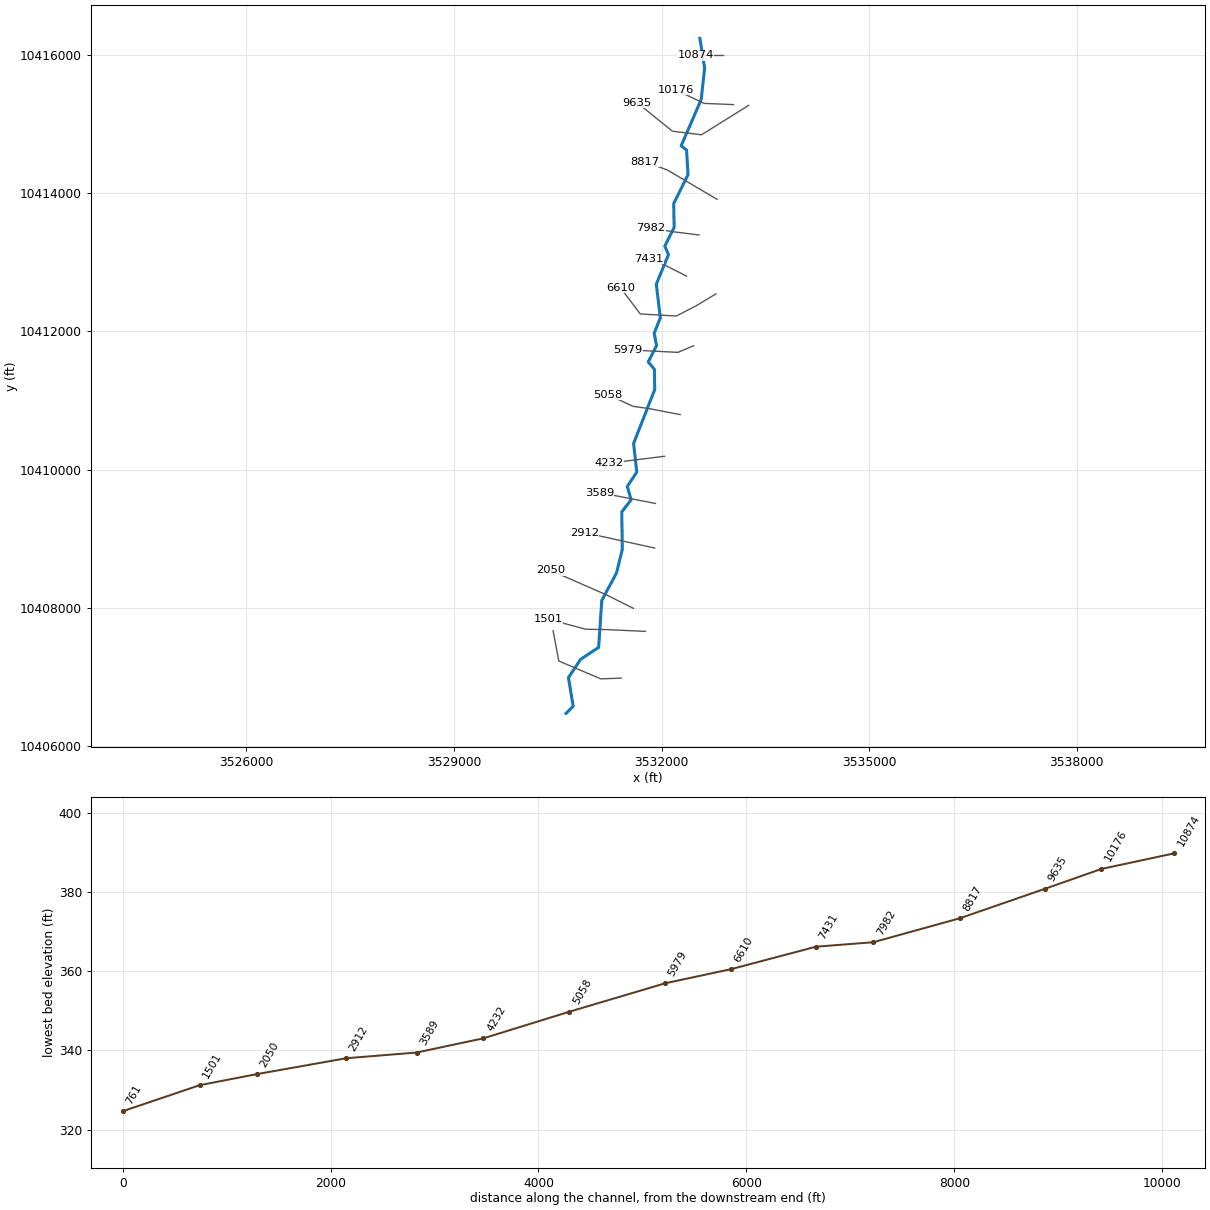
--- DUCK CREEK TRIB 18.prj (project) ---

Proj Title=DUCK CREEK TRIB 18 Base Level Engineering
Current Plan=p01
Default Exp/Contr=0.3,0.1
English Units
Geom File=g01
Flow File=f01
Plan File=p01
Y Axis Title=Elevation
X Axis Title(PF)=Main Channel Distance
X Axis Title(XS)=Station
BEGIN DESCRIPTION:
DUCK CREEK TRIB 18
END DESCRIPTION:
DSS Export Rating Curves= 0
DSS Export Rating Curve Sorted= 0
DSS Export Volume Flow Curves= 0
DXF OffsetX= 0
DXF OffsetY= 0
DXF ScaleX= 1
DXF ScaleY= 10

--- DUCK CREEK TRIB 18.p01 (plan) ---

Plan Title=Multiple Run
Short Identifier=Multiple
Geom File=g01
Flow File=f01
Subcritical Flow
K Sum by GR= 0
Std Step Tol= 0.01
Critical Tol= 0.01
Num of Std Step Trials= 20
Max Error Tol= 0.3
Flow Tol Ratio= 0.001
Split Flow NTrial= 30
Split Flow Tol= 0.02
Split Flow Ratio= 0.02
Log Output Level= 0
Friction Slope Method= 1
Unsteady Friction Slope Method= 2
Unsteady Bridges Friction Slope Method= 1
Parabolic Critical Depth
Global Vel Dist=  1 , 1 , 1
Global Log Level= 0
CheckData=True
Encroach Param= -1, 0, 0, 0
BEGIN DESCRIPTION:
Multiple Run
END DESCRIPTION:

--- DUCK CREEK TRIB 18.f01 (steady flow) ---

Flow Title=Multiple
Program Version=4.10
Number of Profiles= 7
Profile Names=10-year,25-year,50-year,1pct_min,100-year,1pct_plu,500-year
River Rch & RM=DUCK CREEK TRIB,Reach-1         ,10874
    1512    2164    2725    2503    3385    4578    5212
River Rch & RM=DUCK CREEK TRIB,Reach-1         ,8817
    1964    2832    3583    3302    4465    6038    6924
Boundary for River Rch & Prof#=DUCK CREEK TRIB,Reach-1         , 1
Up Type= 0
Dn Type= 3
Dn Slope=0.0054
Boundary for River Rch & Prof#=DUCK CREEK TRIB,Reach-1         , 2
Up Type= 0
Dn Type= 3
Dn Slope=0.0054
Boundary for River Rch & Prof#=DUCK CREEK TRIB,Reach-1         , 3
Up Type= 0
Dn Type= 3
Dn Slope=0.0054
Boundary for River Rch & Prof#=DUCK CREEK TRIB,Reach-1         , 4
Up Type= 0
Dn Type= 3
Dn Slope=0.0054
Boundary for River Rch & Prof#=DUCK CREEK TRIB,Reach-1         , 5
Up Type= 0
Dn Type= 3
Dn Slope=0.0054
Boundary for River Rch & Prof#=DUCK CREEK TRIB,Reach-1         , 6
Up Type= 0
Dn Type= 3
Dn Slope=0.0054
Boundary for River Rch & Prof#=DUCK CREEK TRIB,Reach-1         , 7
Up Type= 0
Dn Type= 3
Dn Slope=0.0054
DSS Import GetInterval= 0
DSS Import GetPeak= 0
DSS Import FillOption= 0

--- DUCK CREEK TRIB 18.g01 (geometry) ---

Geom Title=Existing Conditions
Program Version=4.10

River Reach=DUCK CREEK TRIB ,Reach-1
Reach XY= 30
      3532552.72     10416235.98      3532621.75     10415806.74
      3532571.79     10415351.21      3532281.98     10414680.63
       3532360.5     10414620.78       3532381.6     10414264.03
      3532174.39     10413845.87      3532180.99      10413502.1
      3532046.38     10413230.94      3532099.16     10413107.21
      3531923.34     10412681.34       3531980.9     10412192.12
      3531891.91     10411970.65      3531927.25     10411792.62
      3531806.12     10411556.28      3531895.09     10411450.38
      3531900.45      10411157.1      3531594.65     10410376.45
      3531640.96     10409962.19      3531504.05     10409755.46
      3531558.56     10409563.16       3531424.1     10409386.33
      3531431.65     10408846.05      3531347.78     10408503.06
      3531135.04     10408106.29      3531089.83     10407427.96
      3530827.42     10407253.34       3530653.6      10406990.9
      3530721.56     10406575.27      3530618.09     10406472.92

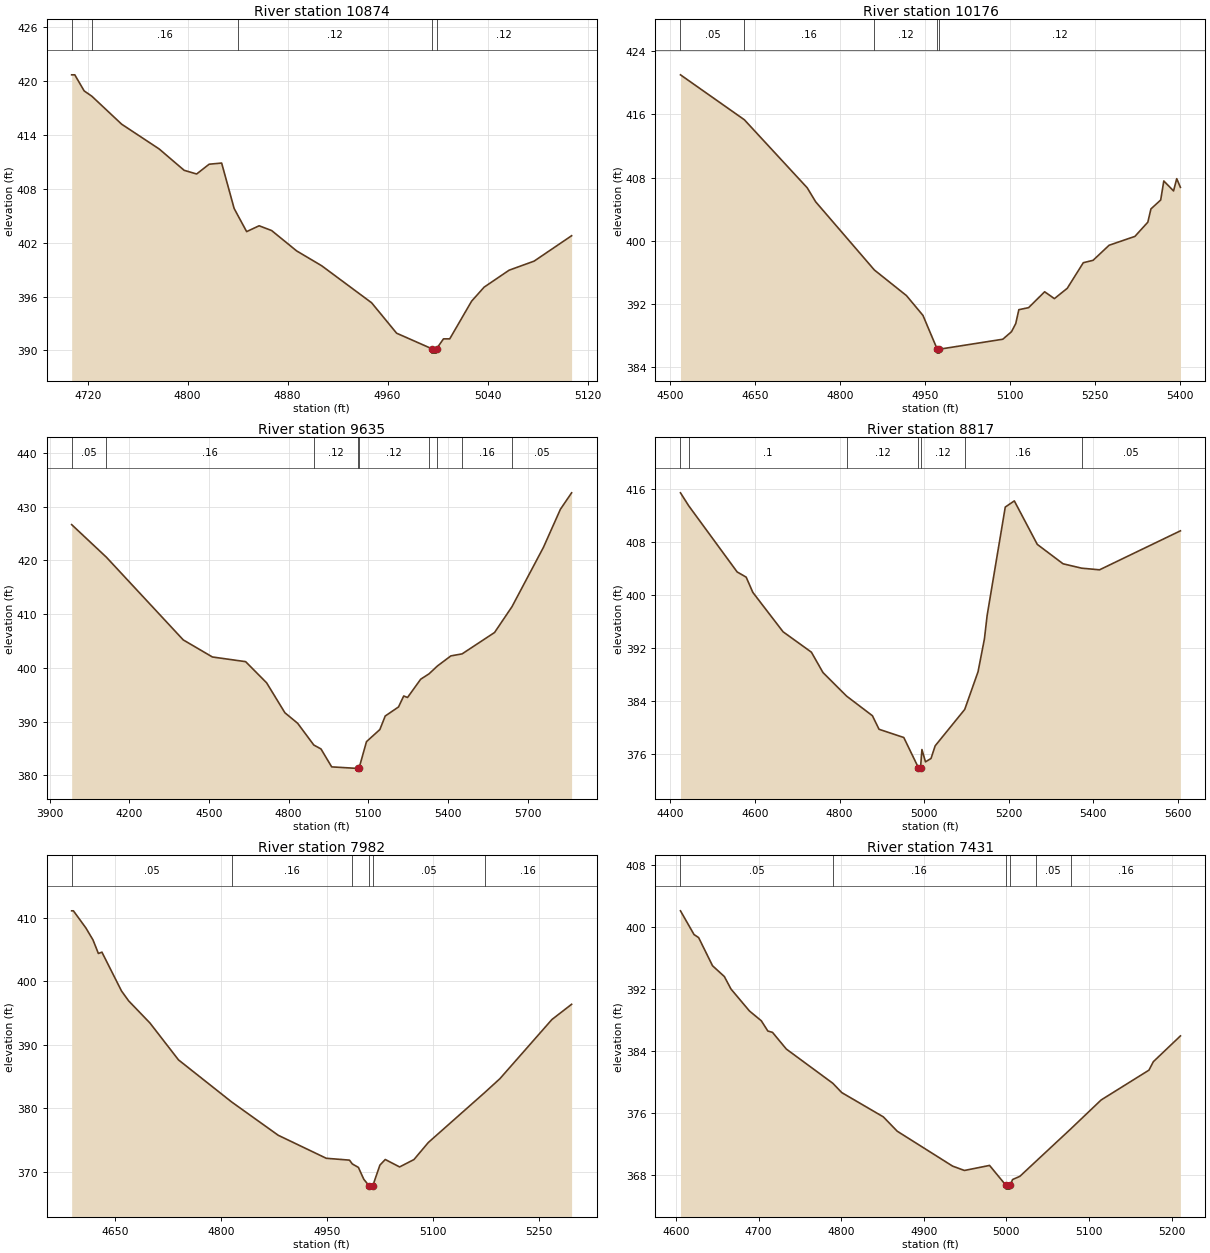
Type RM Length L Ch R = 1 ,10874   ,698,698,698
BEGIN DESCRIPTION:
DUCK CREEK TRIB 18 4 0
END DESCRIPTION:
XS GIS Cut Line= 3
      3532892.07     10415991.64      3532592.11     10415991.64
      3532492.07     10415991.64
#Sta/Elev= 30
  4707.2  420.71  4709.7  420.71  4717.2  418.92  4723.4  418.32  4747.2  415.21
  4777.2  412.45  4797.2  410.07  4807.2  409.66  4817.2  410.75  4827.2  410.88
  4837.2  405.82  4840.4  404.99  4847.2  403.24  4857.2  403.89  4867.2  403.36
  4887.2  401.09  4907.2  399.44  4947.2  395.31  4967.2  391.92  4995.2   390.2
  4995.4   389.7  4998.9   389.7  4999.2   390.2  5004.7  391.29  5009.7  391.29
  5027.2  395.49  5037.2  397.05  5057.2  398.94  5077.2  399.95  5107.2  402.78
#Mann= 5 ,-1 , 0
  4707.2      .1       0  4723.4     .16       0  4840.4     .12       0
  4995.2     .07       0  4999.2     .12       0
Bank Sta=4995.2,4999.2
XS Rating Curve= 0 ,0
Exp/Cntr=0.3,0.1

Type RM Length L Ch R = 1 ,10176   ,541,541,541
BEGIN DESCRIPTION:
DUCK CREEK TRIB 18 3 0
END DESCRIPTION:
XS GIS Cut Line= 3
      3533040.45     10415277.53      3532615.14     10415294.89
      3532202.82      10415490.2
#Sta/Elev= 30
  4518.5  421.01  4631.2  415.32    4742  406.71    4757  404.93  4860.5   396.3
  4917.2  393.05  4946.2  390.55  4971.4  386.27  4971.6  385.77  4975.1  385.77
  4975.4  386.27  5087.1  387.53  5102.4  388.48  5109.9  389.51  5115.4  391.27
  5132.6  391.53  5160.9  393.54  5178.1  392.67  5200.8  393.98  5229.1  397.22
  5246.3  397.52  5274.6  399.43  5320.1  400.55  5342.9  402.35  5348.4  404.03
  5365.6  405.16  5371.1  407.57  5388.3  406.31  5393.9  407.86  5400.4  406.76
#Mann= 5 ,-1 , 0
  4518.5     .05       0  4631.2     .16       0  4860.5     .12       0
  4971.4     .07       0  4975.4     .12       0
Bank Sta=4971.4,4975.4
XS Rating Curve= 0 ,0
Exp/Cntr=0.3,0.1

Type RM Length L Ch R = 1 ,9635    ,818,818,818
BEGIN DESCRIPTION:
DUCK CREEK TRIB 18 23 0
END DESCRIPTION:
XS GIS Cut Line= 4
      3533257.58     10415266.46      3532576.13      10414841.1
      3532155.13     10414893.18      3531647.28     10415305.53
#Sta/Elev= 30
  3983.2  426.67  4113.8  420.61  4403.2  405.21  4512.9  402.03    4638  401.16
    4717  397.22  4785.9  391.64  4833.8  389.69  4894.6  385.64  4921.6  384.91
  4961.9  381.57  5060.6  381.28  5060.9  380.78  5064.6  381.28  5092.9  386.27
  5143.2  388.52  5163.4  391.04  5213.5  392.73    5233  394.77  5247.4  394.49
  5296.9  397.89  5328.5   398.9  5359.8  400.35  5410.4  402.23  5452.9  402.61
    5575  406.59  5640.6   411.4  5758.8  422.43  5822.8  429.53  5864.9  432.59
#Mann= 9 ,-1 , 0
  3983.2     .05       0  4113.8     .16       0  4894.6     .12       0
  5060.6     .07       0  5064.6     .12       0  5328.5     .16       0
  5359.8     .12       0  5452.9     .16       0  5640.6     .05       0
Bank Sta=5060.6,5064.6
XS Rating Curve= 0 ,0
Exp/Cntr=0.3,0.1

Type RM Length L Ch R = 1 ,8817    ,835,835,835
BEGIN DESCRIPTION:
DUCK CREEK TRIB 18 22 0
END DESCRIPTION:
XS GIS Cut Line= 3
      3532801.05     10413907.67      3532080.58     10414333.01
      3531756.06       10414452.
#Sta/Elev= 30
  4423.9  415.39  4443.5  413.42  4557.9  403.44  4579.3  402.65    4595  400.35
  4666.5   394.4  4733.5  391.32  4760.8  388.25  4816.6  384.69  4877.8  381.72
  4893.5  379.67    4952  378.43  4986.7  373.85  4987.1  373.35  4991.6  373.85
  4994.9  376.61  5003.3  374.75  5016.4  375.26  5026.2  377.17  5096.1  382.67
  5127.6  388.36  5142.7  393.32  5149.1  396.86    5192  413.24  5213.4  414.17
  5267.7   407.6  5328.7  404.67  5372.4  404.01  5414.9  403.76  5606.2  409.65
#Mann= 7 ,-1 , 0
  4423.9     .05       0  4443.5      .1       0  4816.6     .12       0
  4986.7     .07       0  4991.6     .12       0  5096.1     .16       0
  5372.4     .05       0
Bank Sta=4986.7,4991.6
XS Rating Curve= 0 ,0
Exp/Cntr=0.3,0.1

Type RM Length L Ch R = 1 ,7982    ,551,551,551
BEGIN DESCRIPTION:
DUCK CREEK TRIB 18 20 0
END DESCRIPTION:
XS GIS Cut Line= 3
      3532542.07     10413391.65      3532142.11     10413441.64
      3531842.12     10413491.64
#Sta/Elev= 30
  4588.7  411.05  4591.2  411.05  4608.8  408.36  4618.9  406.47  4626.5  404.34
  4631.5  404.55  4659.2  398.45  4669.3  396.89  4699.5   393.4  4739.8  387.61
  4814.9     381  4880.9  375.75  4948.9  372.13  4981.7  371.84  4985.7  371.24
  4994.3   370.7  5001.9  368.84  5009.6  367.78    5010  367.28  5014.2  367.28
  5014.6  367.78  5024.7  371.05  5032.3  371.94  5052.6  370.77  5072.9  371.93
  5093.2  374.61    5173  382.47  5194.5  384.65    5268  393.95  5295.9  396.35
#Mann= 6 ,-1 , 0
  4588.7     .05       0  4814.9     .16       0  4985.7     .05       0
  5009.6    .035       0  5014.6     .05       0    5173     .16       0
Bank Sta=5009.6,5014.6
XS Rating Curve= 0 ,0
Exp/Cntr=0.3,0.1

Type RM Length L Ch R = 1 ,7431    ,821,821,821
BEGIN DESCRIPTION:
DUCK CREEK TRIB 18 18 0
END DESCRIPTION:
XS GIS Cut Line= 3
      3532359.64     10412798.24      3531959.64     10412998.24
      3531809.67     10413048.23
#Sta/Elev= 30
  4605.4  402.08  4621.8  399.02  4627.4  398.62  4644.2  394.99  4658.5   393.6
  4666.5  391.99  4688.9  389.15  4703.3  387.88  4711.2  386.56  4716.8  386.39
  4733.6  384.23  4789.8  379.82  4800.7  378.61    4851  375.48  4867.8  373.63
  4934.9  369.12  4949.2  368.56  4979.6  369.21  4999.4  366.65  4999.8  366.15
  5004.1  366.15  5004.5  366.65  5007.5  367.39  5016.3   367.8  5035.7  369.73
  5077.7   373.9  5114.7  377.66  5172.6  381.51  5177.9   382.6  5210.7  385.93
#Mann= 6 ,-1 , 0
  4605.4     .05       0  4789.8     .16       0  4999.4     .07       0
  5004.5     .16       0  5035.7     .05       0  5077.7     .16       0
Bank Sta=4999.4,5004.5
XS Rating Curve= 0 ,0
Exp/Cntr=0.3,0.1

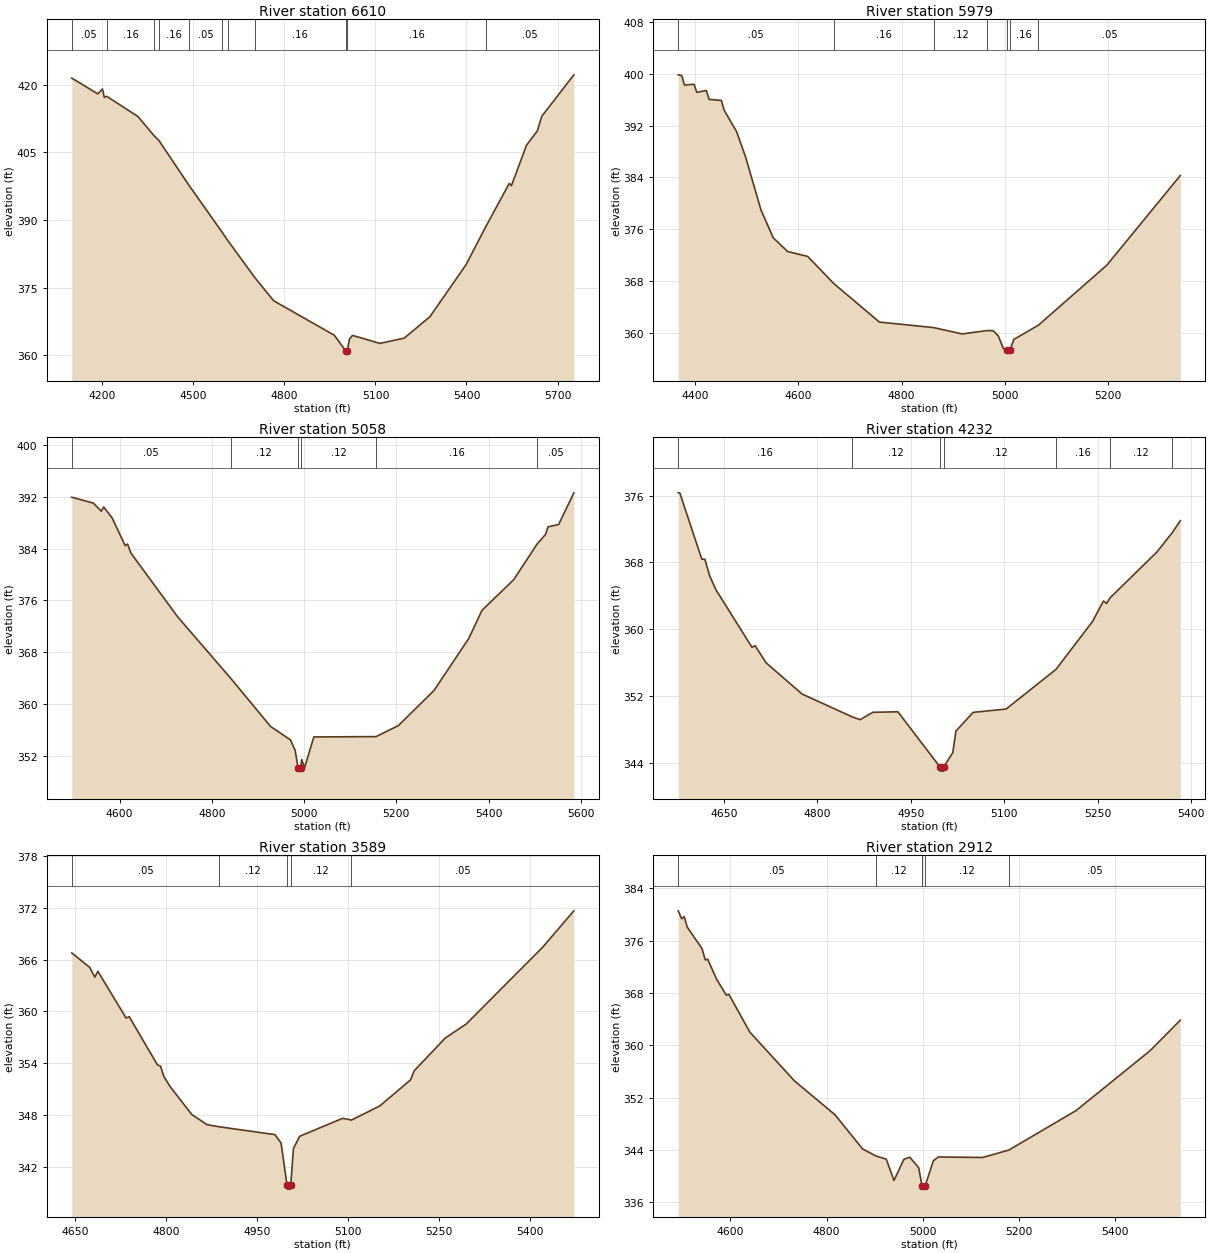
Type RM Length L Ch R = 1 ,6610    ,631,631,631
BEGIN DESCRIPTION:
DUCK CREEK TRIB 18 17 0
END DESCRIPTION:
XS GIS Cut Line= 5
      3532783.46     10412539.18      3532498.01     10412367.14
      3532211.55     10412219.57      3531690.72     10412249.95
      3531404.24     10412631.91
#Sta/Elev= 30
  4099.1  421.51  4184.9     418  4200.4  419.09  4206.2  417.24  4214.2  417.46
  4316.9     413  4370.3  408.73  4386.7  407.61    4485  397.75    4594  387.36
  4612.5  385.52  4702.9  377.19  4764.1   372.1  4964.4  364.43  5001.9  360.96
  5002.3  360.46    5007  360.96  5014.5  363.61  5024.5  364.39  5114.7  362.62
  5194.8  363.79  5279.4  368.54  5398.1  380.04  5465.5  388.77    5541  398.13
  5548.1  397.63  5598.1  406.65  5633.5  409.79  5648.1  413.02  5753.8  422.23
#Mann= 11 ,-1 , 0
  4099.1     .05       0  4214.2     .16       0  4370.3     .05       0
  4386.7     .16       0    4485     .05       0    4594     .16       0
  4612.5     .05       0  4702.9     .16       0  5001.9     .07       0
    5007     .16       0  5465.5     .05       0
Bank Sta=5001.9,5007
XS Rating Curve= 0 ,0
Exp/Cntr=0.3,0.1

Type RM Length L Ch R = 1 ,5979    ,921,921,921
BEGIN DESCRIPTION:
DUCK CREEK TRIB 18 16 0
END DESCRIPTION:
XS GIS Cut Line= 3
      3532462.55     10411789.62      3532234.66     10411694.12
      3531509.79     10411731.01
#Sta/Elev= 30
  4367.3  399.82  4374.1   399.7  4379.5  398.24  4397.9  398.37  4403.3  397.12
  4421.7  397.41  4427.1  396.04  4450.9  395.87  4456.3  394.36  4480.1  391.11
  4497.9  387.14  4527.6  378.99  4551.4  374.69  4579.2  372.58  4618.2  371.82
  4668.8  367.63  4757.1   361.7    4862  360.85  4917.3  359.87  4966.3  360.39
  4977.4  360.38  4987.4  359.58  4997.4  357.61  5004.7  357.41  5005.1  356.91
  5010.3  357.41  5017.5  359.01  5065.4  361.23  5197.7  370.46  5340.2   384.3
#Mann= 7 ,-1 , 0
  4367.3     .05       0  4668.8     .16       0    4862     .12       0
  4966.3     .16       0  5004.7     .07       0  5010.3     .16       0
  5065.4     .05       0
Bank Sta=5004.7,5010.3
XS Rating Curve= 0 ,0
Exp/Cntr=0.3,0.1

Type RM Length L Ch R = 1 ,5058    ,826,826,826
BEGIN DESCRIPTION:
DUCK CREEK TRIB 18 14 0
END DESCRIPTION:
XS GIS Cut Line= 4
      3532267.92     10410794.02      3531820.87     10410880.83
      3531589.08     10410913.15       3531226.7     10411080.28
#Sta/Elev= 30
  4496.4  391.89  4543.1  390.99  4560.5  389.74  4565.6   390.4  4583.8  388.72
  4612.2  384.44  4617.3  384.69  4624.6   383.3  4726.4  373.45  4840.7  364.05
  4927.5  356.61  4970.7  354.54  4980.8   352.9    4987  350.24  4987.5  349.74
  4992.8  350.24  4994.9  351.53    5001  350.24  5021.2     355  5156.1  355.05
  5204.5  356.75  5281.6  362.14  5357.3  370.18  5385.7  374.48  5454.6  379.21
  5505.3   384.7  5523.4  386.15  5528.9  387.33  5551.9  387.69  5584.9  392.57
#Mann= 6 ,-1 , 0
  4496.4     .05       0  4840.7     .12       0    4987     .07       0
  4992.8     .12       0  5156.1     .16       0  5505.3     .05       0
Bank Sta=4987,4992.8
XS Rating Curve= 0 ,0
Exp/Cntr=0.3,0.1

Type RM Length L Ch R = 1 ,4232    ,643,643,643
BEGIN DESCRIPTION:
DUCK CREEK TRIB 18 20
END DESCRIPTION:
XS GIS Cut Line= 3
      3532042.09     10410191.64      3531642.11     10410141.64
      3531242.11     10410091.64
#Sta/Elev= 30
  4576.4  376.33  4578.9  376.33  4614.2   368.4  4619.2  368.38  4626.8  366.41
  4636.8  364.75  4694.8  357.85  4699.8  358.04  4717.5  355.99  4775.4  352.25
  4855.2  349.54  4868.6  349.19  4888.8  350.07  4929.1  350.13  4996.7  343.53
  4997.2  343.03  5002.2  343.03  5002.7  343.53  5017.3  345.25  5022.3  347.82
    5050  350.06  5102.9  350.46  5182.9   355.2  5241.5  360.92  5259.2  363.39
  5264.2  363.09  5269.9  363.77  5344.8  369.23    5369   371.5  5382.6  372.99
#Mann= 7 ,-1 , 0
  4576.4     .16       0  4855.2     .12       0  4996.7     .07       0
  5002.7     .12       0  5182.9     .16       0  5269.9     .12       0
    5369     .16       0
Bank Sta=4996.7,5002.7
XS Rating Curve= 0 ,0
Exp/Cntr=0.3,0.1

Type RM Length L Ch R = 1 ,3589    ,677,677,677
BEGIN DESCRIPTION:
DUCK CREEK TRIB 18 10
END DESCRIPTION:
XS GIS Cut Line= 2
      3531911.29     10409508.79      3531097.68     10409666.75
#Sta/Elev= 30
  4644.1  366.77  4673.8  365.09  4682.1  363.97  4687.2  364.64  4733.8  359.23
  4738.9   359.4  4785.5  353.82  4790.6  353.67  4796.1  352.47  4806.3  351.32
  4842.3  348.07  4867.4   346.9  4887.7  346.65  4979.4  345.75  4989.6  344.78
  4999.4  339.94  4999.9  339.44  5005.1  339.44  5005.6  339.94    5010  344.13
  5020.2  345.55  5091.5  347.64  5105.8  347.43  5152.5  349.06  5203.5  352.09
  5209.3  353.13    5261  356.94  5295.2  358.54  5421.2  367.41  5472.9  371.64
#Mann= 5 ,-1 , 0
  4644.1     .05       0  4887.7     .12       0  4999.4     .07       0
  5005.6     .12       0  5105.8     .05       0
Bank Sta=4999.4,5005.6
XS Rating Curve= 0 ,0
Exp/Cntr=0.3,0.1

Type RM Length L Ch R = 1 ,2912    ,862,862,862
BEGIN DESCRIPTION:
DUCK CREEK TRIB 18 9 0
END DESCRIPTION:
XS GIS Cut Line= 2
      3531900.43     10408864.26      3530880.54     10409087.77
#Sta/Elev= 30
  4491.4  380.56  4498.7  379.34  4503.8  379.67  4510.2  378.06  4540.9  374.78
  4547.6  373.06  4552.7  373.15  4571.6  370.04  4591.4  367.66  4596.6  367.81
  4640.4     362  4733.2  354.55  4817.3  349.38  4874.9  344.14    4903  343.05
  4923.9  342.59  4940.1  339.33  4960.6  342.56  4972.8  342.88  4991.3   341.3
  4998.4   338.5  4998.9     338  5004.8   338.5    5022  342.33  5032.3  342.92
  5124.4  342.84  5178.9  343.97  5318.9  350.02  5472.5  359.16  5535.5  363.84
#Mann= 5 ,-1 , 0
  4491.4     .05       0    4903     .12       0  4998.4     .07       0
  5004.8     .12       0  5178.9     .05       0
Bank Sta=4998.4,5004.8
XS Rating Curve= 0 ,0
Exp/Cntr=0.3,0.1

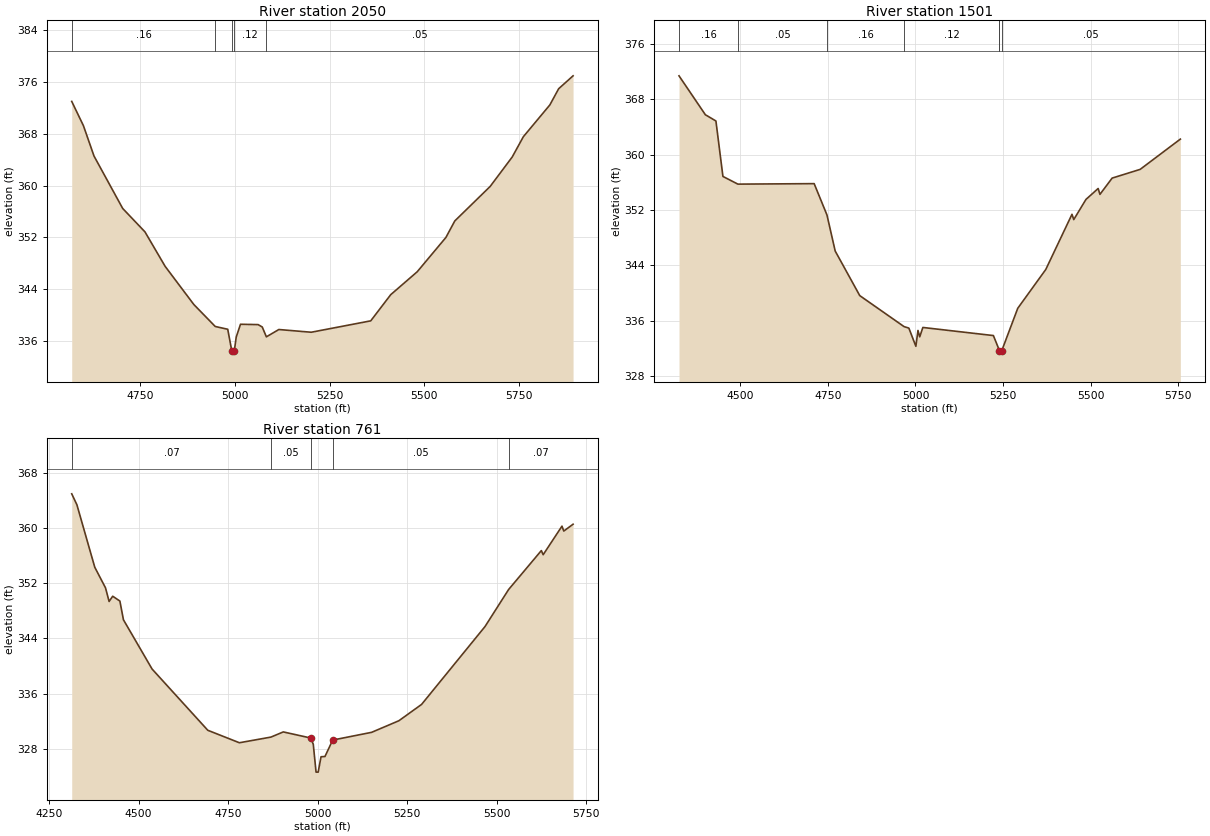
Type RM Length L Ch R = 1 ,2050    ,549,549,549
BEGIN DESCRIPTION:
DUCK CREEK TRIB 18 8 0
END DESCRIPTION:
XS GIS Cut Line= 3
      3531592.14     10407991.63      3531192.11     10408191.64
      3530392.07     10408541.66
#Sta/Elev= 30
    4571  373.01  4601.8  369.26  4629.7  364.57  4705.2  356.48  4763.9  352.86
    4817  347.54  4892.5  341.65    4949  338.25  4981.9  337.82  4992.6  334.48
  4993.1  333.98  4999.2  334.48  5004.3  336.62  5015.5  338.59  5061.9  338.54
  5072.8  338.17  5083.7  336.65  5116.5  337.78  5201.9  337.36  5358.6  339.12
  5411.2  343.16    5481   346.7  5556.6     352    5580  354.55  5673.2  359.88
  5731.2  364.42  5760.5  367.55  5830.3  372.46  5853.6  374.97  5891.5  376.96
#Mann= 5 ,-1 , 0
    4571     .16       0    4949     .12       0  4992.6     .07       0
  4999.2     .12       0  5083.7     .05       0
Bank Sta=4992.6,4999.2
XS Rating Curve= 0 ,0
Exp/Cntr=0.3,0.1

Type RM Length L Ch R = 1 ,1501    ,740,740,740
BEGIN DESCRIPTION:
DUCK CREEK TRIB 18 6 0
END DESCRIPTION:
XS GIS Cut Line= 4
      3531767.27     10407658.72      3531194.37     10407684.76
      3530902.32     10407689.78      3530356.92     10407836.61
#Sta/Elev= 30
  4325.4  371.38  4400.6  365.76  4430.7  364.86  4450.7  356.85  4493.4  355.74
    4711  355.81  4747.5  351.29    4771  346.08  4841.1  339.64  4967.6  335.16
  4981.2  334.95  5001.2  332.32  5007.2  334.61  5012.2  333.69  5021.2  335.04
  5222.4  333.87  5238.8  331.81  5239.6  331.69  5240.1  331.19  5246.3  331.69
  5291.9  337.81  5371.8  343.41  5446.6  351.38  5451.7  350.62  5486.5  353.53
  5521.3  355.11  5526.4  354.26  5561.2  356.61  5641.1  357.87  5755.8  362.24
#Mann= 7 ,-1 , 0
  4325.4     .16       0  4493.4     .05       0  4747.5     .16       0
  4967.6     .12       0  5238.8     .05       0  5239.6     .07       0
  5246.3     .05       0
Bank Sta=5239.6,5246.3
XS Rating Curve= 0 ,0
Exp/Cntr=0.3,0.1

Type RM Length L Ch R = 1 ,761     ,0,0,0
BEGIN DESCRIPTION:
DUCK CREEK TRIB 18 1 0
END DESCRIPTION:
XS GIS Cut Line= 4
      3531416.48     10406982.75      3531121.38      10406971.9
      3530513.74     10407230.14      3530431.46     10407667.53
#Sta/Elev= 30
  4313.3  364.98  4327.7   363.4  4377.7  354.33  4407.7  351.34  4417.7  349.37
  4427.8  350.13  4447.8  349.43  4457.8  346.71  4537.8  339.57  4693.4  330.69
  4781.7  328.88  4869.8   329.7  4904.3  330.45  4980.7  329.57  4988.1  328.67
  4995.9  324.62  5001.8  324.62  5009.8  326.85  5020.7  326.88  5042.4  329.27
  5151.1  330.39  5227.2  332.07  5290.7  334.44  5467.9  345.73  5533.8   351.1
  5625.3  356.75  5630.4  356.15  5682.9  360.29    5688  359.58  5713.9  360.57
#Mann= 5 ,-1 , 0
  4313.3     .07       0  4869.8     .05       0  4980.7     .03       0
  5042.4     .05       0  5533.8     .07       0
Bank Sta=4980.7,5042.4
XS Rating Curve= 0 ,0
Exp/Cntr=0.3,0.1

Chan Stop Cuts=-1
Use User Specified Reach Order=0
Composite Channel Slope=5