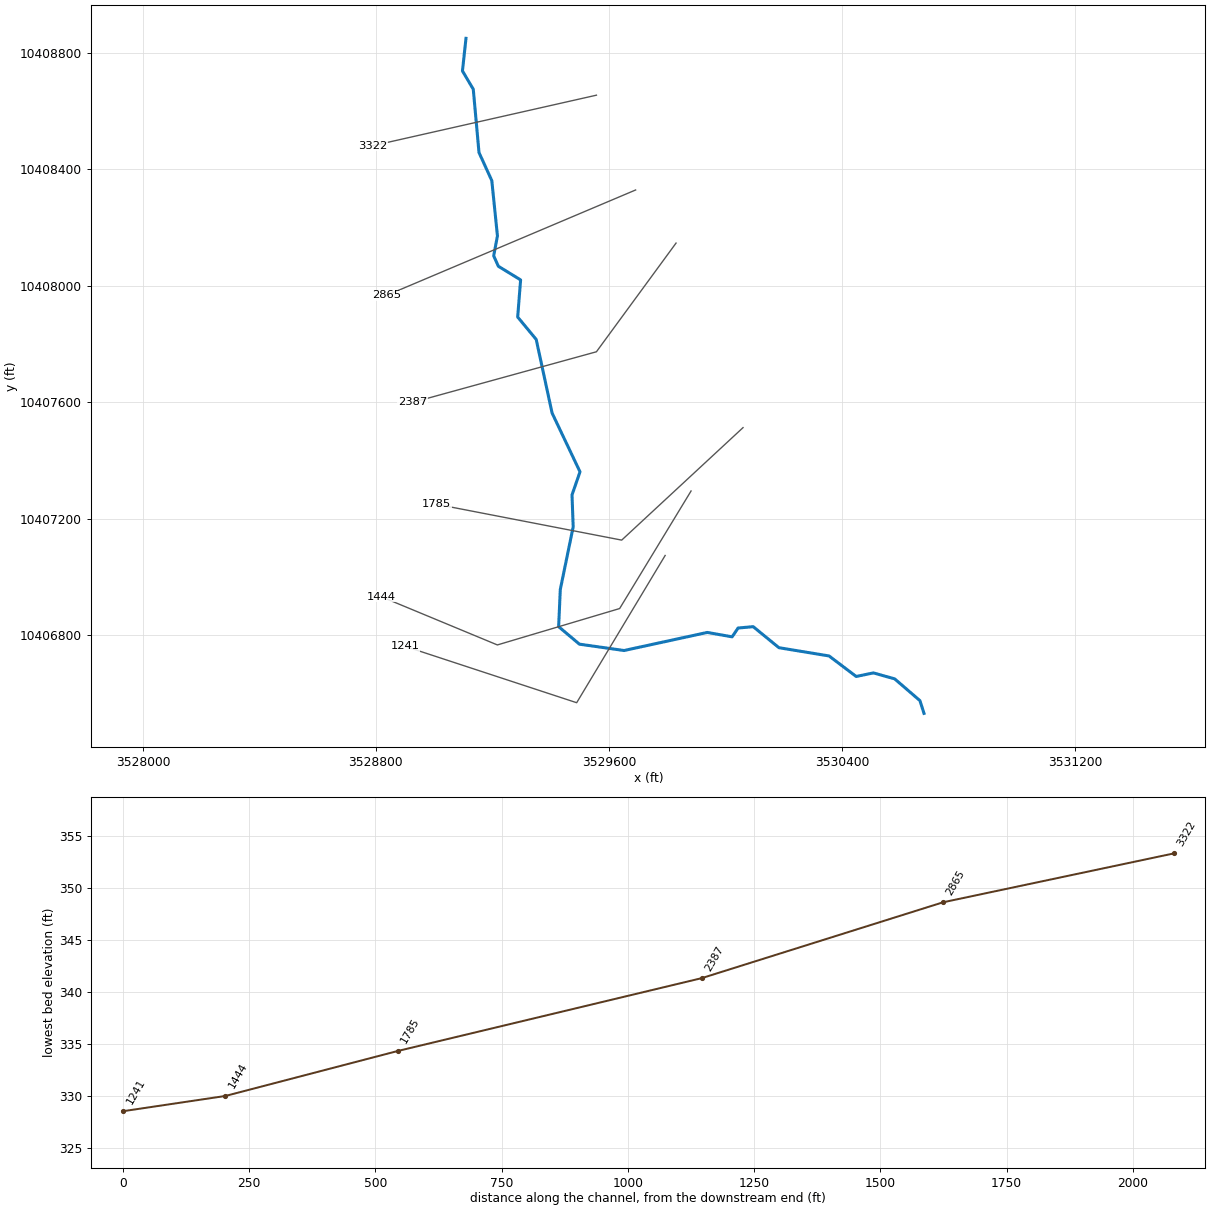
--- DUCK CREEK TRIB 19.prj (project) ---

Proj Title=DUCK CREEK TRIB 19 Base Level Engineering
Current Plan=p01
Default Exp/Contr=0.3,0.1
English Units
Geom File=g01
Flow File=f01
Plan File=p01
BEGIN DESCRIPTION:
DUCK CREEK TRIB 19
END DESCRIPTION:

--- DUCK CREEK TRIB 19.p01 (plan) ---

Plan Title=Multiple Run
Short Identifier=Multiple
Geom File=g01
Flow File=f01
Subcritical Flow
K Sum by GR= 0
Std Step Tol= 0.01
Critical Tol= 0.01
Num of Std Step Trials= 20
Max Error Tol= 0.3
Flow Tol Ratio= 0.001
Split Flow NTrial= 30
Split Flow Tol= 0.02
Split Flow Ratio= 0.02
Log Output Level= 0
Friction Slope Method= 1
Unsteady Friction Slope Method= 2
Unsteady Bridges Friction Slope Method= 1
Parabolic Critical Depth
Global Vel Dist=  1 , 1 , 1
Global Log Level= 0
CheckData=True
Encroach Param= -1, 0, 0, 0
BEGIN DESCRIPTION:
Multiple Run
END DESCRIPTION:

--- DUCK CREEK TRIB 19.f01 (steady flow) ---

Flow Title=Multiple
Number of Profiles=7
Profile Names=10-year,25-year,50-year,1pct_min,100-year,1pct_plu,500-year
River Rch & RM= DUCK CREEK TRIB ,Reach-1,3322
     372     488     579     505     683     924     945
Boundary for River Rch & Prof#=DUCK CREEK TRIB ,Reach-1,1
Up Type=0
Dn Type=3
Dn Slope=0.005
Boundary for River Rch & Prof#=DUCK CREEK TRIB ,Reach-1,2
Up Type=0
Dn Type=3
Dn Slope=0.005
Boundary for River Rch & Prof#=DUCK CREEK TRIB ,Reach-1,3
Up Type=0
Dn Type=3
Dn Slope=0.005
Boundary for River Rch & Prof#=DUCK CREEK TRIB ,Reach-1,4
Up Type=0
Dn Type=3
Dn Slope=0.005
Boundary for River Rch & Prof#=DUCK CREEK TRIB ,Reach-1,5
Up Type=0
Dn Type=3
Dn Slope=0.005
Boundary for River Rch & Prof#=DUCK CREEK TRIB ,Reach-1,6
Up Type=0
Dn Type=3
Dn Slope=0.005
Boundary for River Rch & Prof#=DUCK CREEK TRIB ,Reach-1,7
Up Type=0
Dn Type=3
Dn Slope=0.005

--- DUCK CREEK TRIB 19.g01 (geometry) ---

Geom Title=Existing Conditions

River Reach=DUCK CREEK TRIB ,Reach-1
Reach XY= 30
      3529109.38     10408849.54      3529097.24     10408737.57
      3529134.39     10408674.79      3529154.06     10408457.44
      3529198.00     10408361.03      3529217.40     10408170.97
      3529204.48     10408102.67      3529220.47     10408066.97
      3529296.94     10408020.07      3529286.85     10407892.59
      3529350.46     10407815.62      3529405.02     10407562.92
      3529500.92     10407361.00      3529473.44     10407281.72
      3529477.48     10407172.23      3529433.24     10406957.14
      3529427.51     10406829.40      3529498.78     10406769.30
      3529652.10     10406747.45      3529937.90     10406809.54
      3530023.22     10406794.44      3530043.68     10406824.68
      3530095.59     10406829.37      3530183.90     10406757.15
      3530356.00     10406728.82      3530449.30     10406658.33
      3530508.38     10406670.65      3530581.42     10406650.06
      3530667.99     10406575.54      3530682.11     10406531.64

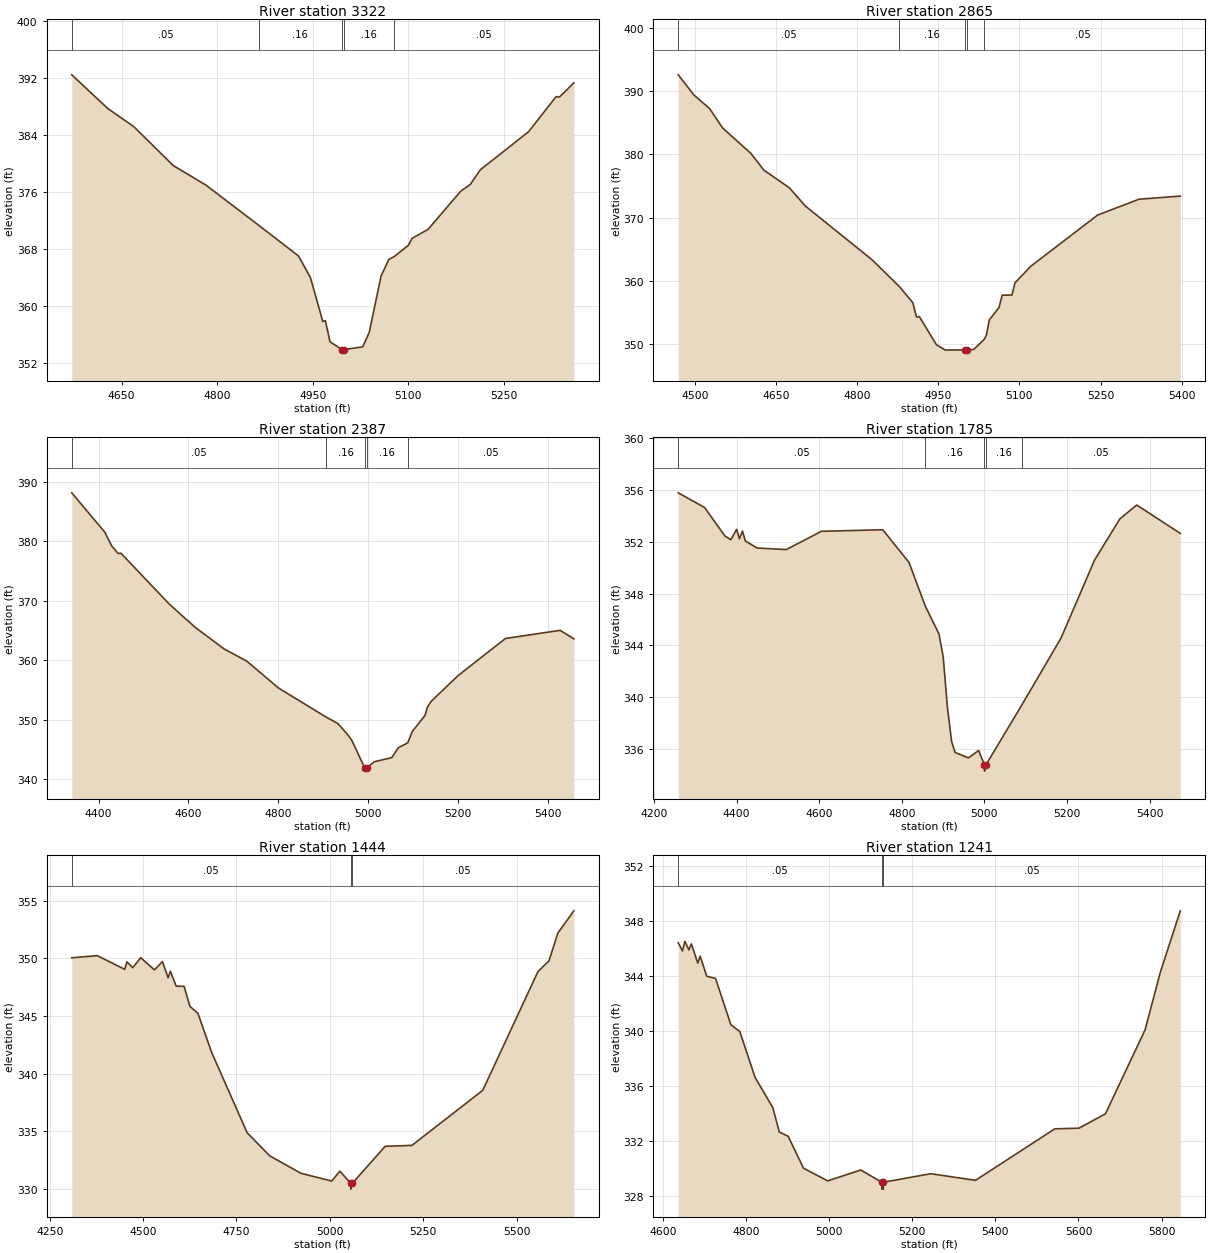
Type RM Length L Ch R = 1,3322,457,457,457
BEGIN DESCRIPTION:
DUCK CREEK TRIB 19 40
END DESCRIPTION:
XS GIS Cut Line= 2
      3529557.27     10408654.35      3528789.04     10408480.74
#Sta/Elev= 30
  4571.9  392.38  4628.5  387.65  4669.5  385.09  4731.0  379.66  4782.2  376.92
  4865.4  371.26  4927.7  366.96  4946.3  363.93  4965.7  357.78  4969.8  357.89
  4977.0  354.94  4995.5  353.84  4995.8  353.34  4999.3  353.34  4999.5  353.84
  5028.3  354.22  5038.5  356.23  5057.2  364.19  5069.3  366.47  5077.7  366.89
  5100.1  368.48  5105.5  369.42  5130.8  370.70  5182.1  376.06  5197.0  377.00
  5212.8  379.06  5288.5  384.40  5331.7  389.32  5336.9  389.26  5359.5  391.25
#Mann=5,-1,0
  4571.9    0.05       0  4865.4    0.16       0  4995.5    0.07       0
  4999.5    0.16       0  5077.7    0.05       0
Bank Sta=4995.5,4999.5
Exp/Cntr=0.3,0.1

Type RM Length L Ch R = 1,2865,478,478,478
BEGIN DESCRIPTION:
DUCK CREEK TRIB 19 30
END DESCRIPTION:
XS GIS Cut Line= 2
      3529691.83     10408328.84      3528836.55     10407966.91
#Sta/Elev= 30
  4468.9  392.55  4498.0  389.36  4527.1  387.20  4550.8  384.18  4603.6  380.12
  4627.3  377.51  4674.6  374.71  4703.8  371.86  4826.9  363.40  4878.1  359.13
  4902.9  356.58  4909.6  354.33  4915.0  354.38  4946.4  349.96  4962.4  349.13
  4998.7  349.13  4998.9  348.63  5002.7  349.13  5015.2  349.20  5035.1  350.82
  5038.9  351.47  5044.3  353.88  5062.5  355.86  5068.0  357.77  5086.2  357.80
  5091.7  359.71  5120.8  362.33  5244.7  370.42  5321.2  372.92  5397.6  373.41
#Mann=5,-1,0
  4468.9    0.05       0  4878.1    0.16       0  4998.7    0.07       0
  5002.7    0.16       0  5035.1    0.05       0
Bank Sta=4998.7,5002.7
Exp/Cntr=0.3,0.1

Type RM Length L Ch R = 1,2387,602,602,602
BEGIN DESCRIPTION:
DUCK CREEK TRIB 19 5 0
END DESCRIPTION:
XS GIS Cut Line= 3
      3529830.65     10408146.50      3529557.24     10407773.27
      3528925.24     10407599.17
#Sta/Elev= 30
  4340.1  388.19  4414.0  381.53  4428.7  379.29  4443.4  377.97  4449.6  378.02
  4556.9  369.48  4614.7  365.55  4679.6  361.89  4729.8  359.85  4800.7  355.31
  4906.5  350.43  4932.6  349.34  4953.3  347.59  4963.7  346.52  4992.8  341.82
  4993.0  341.32  4996.5  341.32  4996.8  341.82  5013.2  342.89  5052.7  343.59
  5067.4  345.26  5088.3  346.08  5098.5  348.00  5126.7  350.69  5131.9  352.04
  5140.0  353.03  5200.7  357.42  5306.0  363.66  5427.7  365.03  5458.3  363.60
#Mann=5,-1,0
  4340.1    0.05       0  4906.5    0.16       0  4992.8    0.07       0
  4996.8    0.16       0  5088.3    0.05       0
Bank Sta=4992.8,4996.8
Exp/Cntr=0.3,0.1

Type RM Length L Ch R = 1,1785,341,341,341
BEGIN DESCRIPTION:
DUCK CREEK TRIB 19 2 2
END DESCRIPTION:
XS GIS Cut Line= 3
      3530060.69     10407512.83      3529644.04     10407126.56
      3529008.50     10407249.64
#Sta/Elev= 30
  4258.9  355.78  4322.6  354.65  4371.9  352.45  4386.1  352.16  4400.3  352.96
  4407.1  352.23  4414.4  352.83  4421.3  352.07  4449.6  351.52  4520.5  351.40
  4605.5  352.81  4754.0  352.93  4817.6  350.41  4857.1  347.03  4890.1  344.89
  4900.3  343.13  4910.5  339.25  4920.7  336.59  4929.2  335.74  4961.4  335.32
  4986.1  335.89  5000.2  334.80  5000.4  334.30  5004.2  334.80  5090.8  339.41
  5185.5  344.56  5267.0  350.60  5328.1  353.77  5368.9  354.84  5474.4  352.65
#Mann=5,-1,0
  4258.9    0.05       0  4857.1    0.16       0  5000.2    0.07       0
  5004.2    0.16       0  5090.8    0.05       0
Bank Sta=5000.2,5004.2
Exp/Cntr=0.3,0.1

Type RM Length L Ch R = 1,1444,203,203,203
BEGIN DESCRIPTION:
DUCK CREEK TRIB 19 4 0
END DESCRIPTION:
XS GIS Cut Line= 4
      3529882.24     10407295.26      3529637.00     10406891.60
      3529217.11     10406766.64      3528816.91     10406932.74
#Sta/Elev= 30
  4309.2  350.06  4377.3  350.25  4450.9  349.06  4456.8  349.71  4472.3  349.20
  4493.6  350.07  4530.4  349.01  4551.7  349.73  4567.2  348.33  4573.1  348.90
  4588.6  347.60  4609.9  347.58  4625.4  345.84  4646.7  345.25  4683.5  341.85
  4778.5  334.87  4839.0  332.86  4922.3  331.35  5004.9  330.67  5026.6  331.53
  5055.9  330.47  5056.1  329.97  5059.9  330.47  5148.0  333.69  5219.6  333.77
  5409.1  338.55  5557.0  348.87  5586.3  349.79  5610.1  352.21  5652.9  354.14
#Mann=3,-1,0
  4309.2    0.05       0  5055.9    0.03       0  5059.9    0.05       0
Bank Sta=5055.9,5059.9
Exp/Cntr=0.3,0.1

Type RM Length L Ch R = 1,1241,0,0,0
BEGIN DESCRIPTION:
DUCK CREEK TRIB 19 3 0
END DESCRIPTION:
XS GIS Cut Line= 3
      3529793.24     10407073.87      3529489.44     10406568.25
      3528901.31     10406761.40
#Sta/Elev= 30
  4636.3  346.40  4646.5  345.81  4652.3  346.50  4662.0  345.88  4667.9  346.32
  4683.4  344.92  4689.2  345.43  4704.8  343.97  4726.1  343.81  4763.1  340.44
  4784.4  339.96  4821.3  336.62  4864.1  334.42  4879.6  332.65  4901.0  332.34
  4937.9  330.02  4996.2  329.10  5075.9  329.89  5126.3  329.00  5126.6  328.50
  5130.1  328.50  5130.3  329.00  5244.4  329.62  5352.1  329.14  5543.0  332.88
  5601.3  332.93  5664.9  333.97  5760.2  340.06  5797.5  344.30  5845.2  348.72
#Mann=3,-1,0
  4636.3    0.05       0  5126.3    0.03       0  5130.3    0.05       0
Bank Sta=5126.3,5130.3
Exp/Cntr=0.3,0.1

Chan Stop Cuts=-1