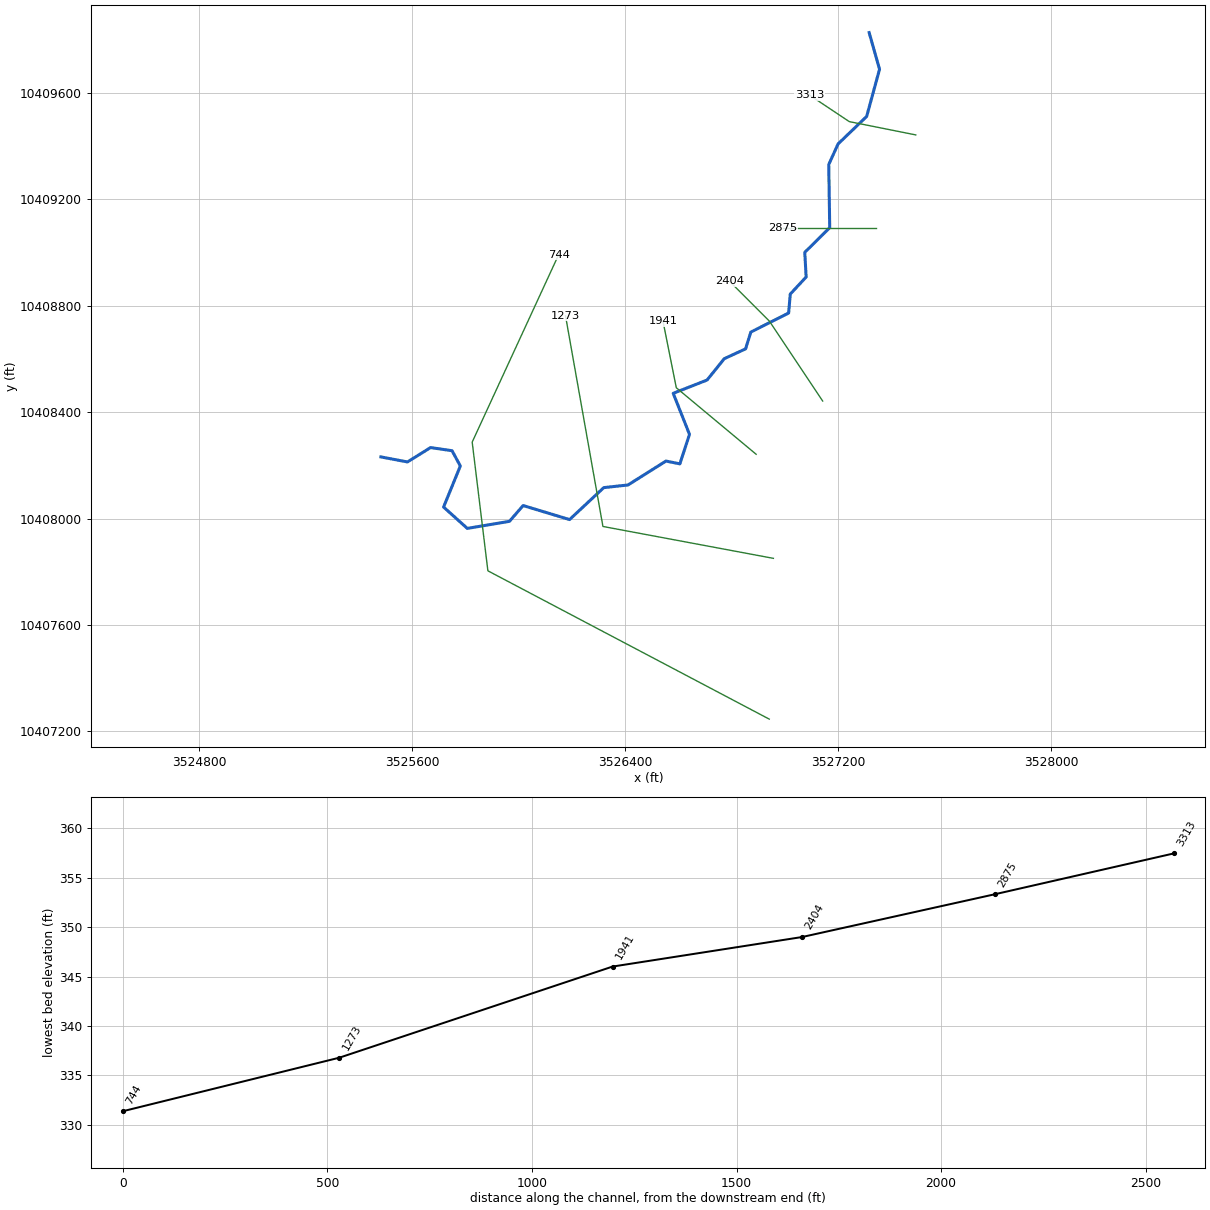
--- DUCK CREEK TRIB 20.prj (project) ---

Proj Title=DUCK CREEK TRIB 20 Base Level Engineering
Current Plan=p01
Default Exp/Contr=0.3,0.1
English Units
Geom File=g01
Flow File=f01
Plan File=p01
BEGIN DESCRIPTION:
DUCK CREEK TRIB 20
END DESCRIPTION:

--- DUCK CREEK TRIB 20.p01 (plan) ---

Plan Title=Multiple Run
Short Identifier=Multiple
Geom File=g01
Flow File=f01
Subcritical Flow
K Sum by GR= 0
Std Step Tol= 0.01
Critical Tol= 0.01
Num of Std Step Trials= 20
Max Error Tol= 0.3
Flow Tol Ratio= 0.001
Split Flow NTrial= 30
Split Flow Tol= 0.02
Split Flow Ratio= 0.02
Log Output Level= 0
Friction Slope Method= 1
Unsteady Friction Slope Method= 2
Unsteady Bridges Friction Slope Method= 1
Parabolic Critical Depth
Global Vel Dist=  1 , 1 , 1
Global Log Level= 0
CheckData=True
Encroach Param= -1, 0, 0, 0
BEGIN DESCRIPTION:
Multiple Run
END DESCRIPTION:

--- DUCK CREEK TRIB 20.f01 (steady flow) ---

Flow Title=Multiple
Number of Profiles=7
Profile Names=10-year,25-year,50-year,1pct_min,100-year,1pct_plu,500-year
River Rch & RM= DUCK CREEK TRIB ,Reach-1,3313
     478     639     768     678     918    1241    1301
Boundary for River Rch & Prof#=DUCK CREEK TRIB ,Reach-1,1
Up Type=0
Dn Type=3
Dn Slope=0.005
Boundary for River Rch & Prof#=DUCK CREEK TRIB ,Reach-1,2
Up Type=0
Dn Type=3
Dn Slope=0.005
Boundary for River Rch & Prof#=DUCK CREEK TRIB ,Reach-1,3
Up Type=0
Dn Type=3
Dn Slope=0.005
Boundary for River Rch & Prof#=DUCK CREEK TRIB ,Reach-1,4
Up Type=0
Dn Type=3
Dn Slope=0.005
Boundary for River Rch & Prof#=DUCK CREEK TRIB ,Reach-1,5
Up Type=0
Dn Type=3
Dn Slope=0.005
Boundary for River Rch & Prof#=DUCK CREEK TRIB ,Reach-1,6
Up Type=0
Dn Type=3
Dn Slope=0.005
Boundary for River Rch & Prof#=DUCK CREEK TRIB ,Reach-1,7
Up Type=0
Dn Type=3
Dn Slope=0.005

--- DUCK CREEK TRIB 20.g01 (geometry) ---

Geom Title=Existing Conditions

River Reach=DUCK CREEK TRIB ,Reach-1
Reach XY= 30
      3527316.80     10409826.15      3527355.86     10409688.34
      3527307.44     10409510.97      3527200.08     10409407.76
      3527164.97     10409330.35      3527168.66     10409093.01
      3527074.96     10409000.38      3527079.99     10408907.58
      3527020.44     10408843.54      3527014.22     10408772.39
      3526872.18     10408700.75      3526852.49     10408637.64
      3526772.40     10408600.81      3526707.80     10408520.55
      3526580.52     10408470.62      3526641.74     10408316.32
      3526605.62     10408205.56      3526553.26     10408216.04
      3526410.51     10408126.16      3526319.62     10408116.29
      3526191.11     10407996.21      3526016.47     10408048.91
      3525965.21     10407989.64      3525806.87     10407962.99
      3525717.65     10408043.23      3525780.62     10408197.55
      3525749.42     10408254.99      3525668.70     10408266.75
      3525581.95     10408212.75      3525482.11     10408231.64

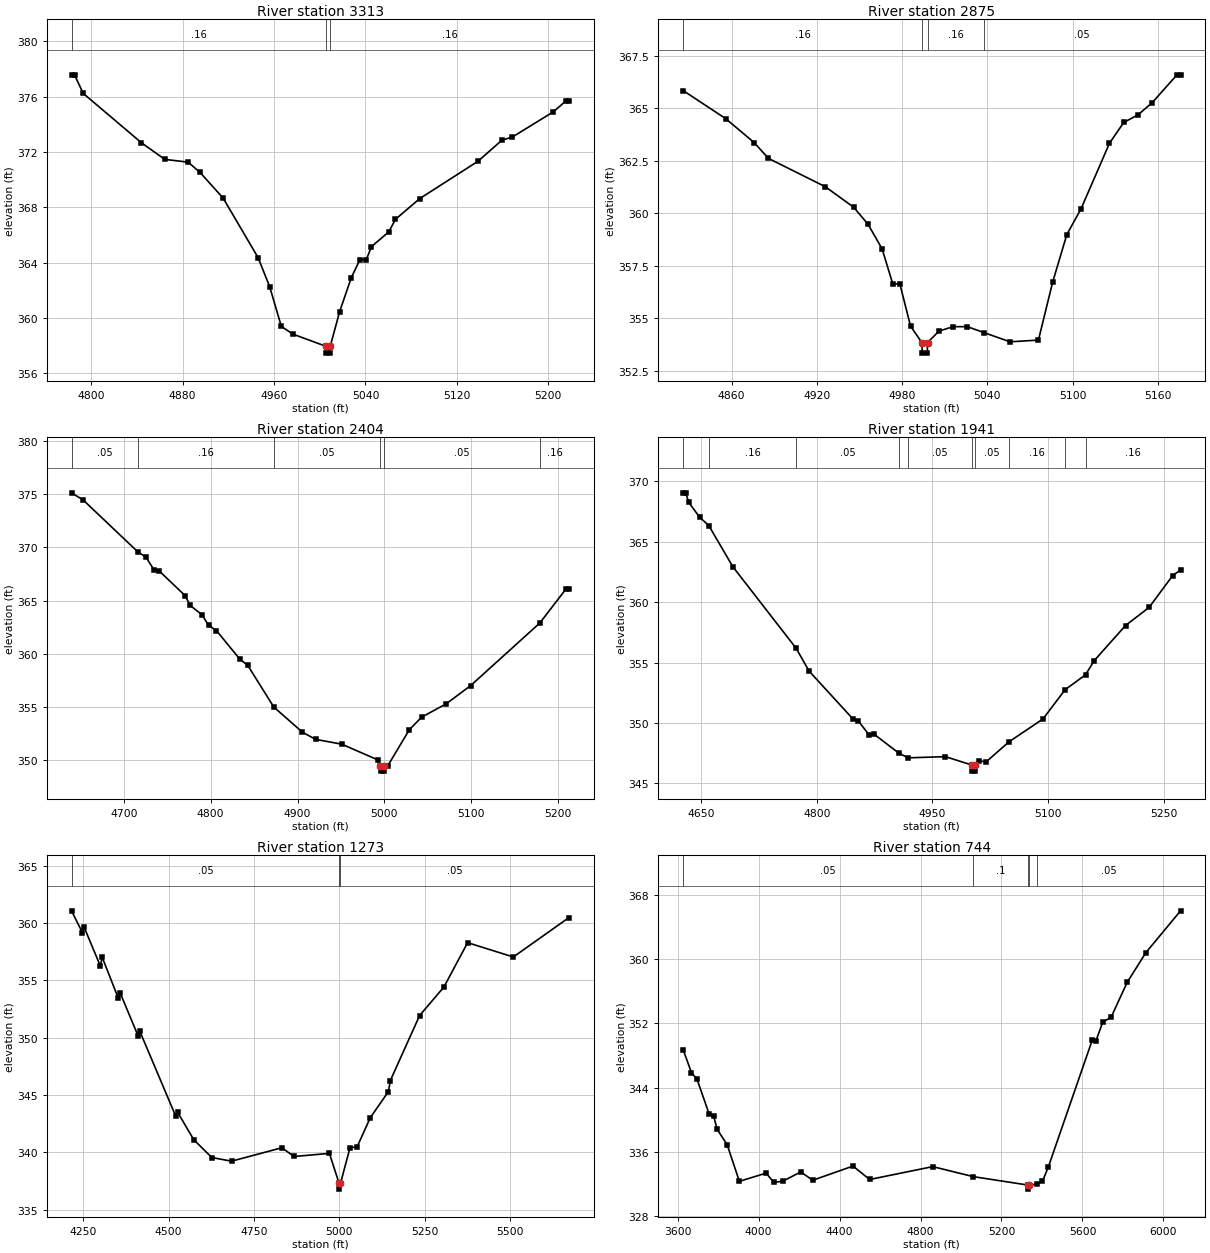
Type RM Length L Ch R = 1,3313,438,438,438
BEGIN DESCRIPTION:
DUCK CREEK TRIB 20 18
END DESCRIPTION:
XS GIS Cut Line= 3
      3527492.14     10409441.63      3527242.11     10409491.64
      3527092.08     10409591.66
#Sta/Elev= 30
  4782.8  377.58  4785.4  377.58  4793.0  376.24  4844.0  372.67  4864.4  371.47
  4884.8  371.27  4895.0  370.55  4915.4  368.68  4946.0  364.38  4956.2  362.27
  4966.4  359.40  4976.6  358.84  5005.2  357.97  5005.4  357.47  5008.9  357.47
  5009.2  357.97  5017.4  360.46  5027.6  362.92  5035.2  364.23  5040.8  364.23
  5045.3  365.17  5060.3  366.22  5066.3  367.14  5087.4  368.63  5138.4  371.33
  5159.5  372.86  5168.5  373.08  5204.5  374.91  5215.1  375.67  5218.1  375.67
#Mann=3,-1,0
  4782.8    0.16       0  5005.2    0.07       0  5009.2    0.16       0
Bank Sta=5005.2,5009.2
Exp/Cntr=0.3,0.1

Type RM Length L Ch R = 1,2875,471,471,471
BEGIN DESCRIPTION:
DUCK CREEK TRIB 20 7 0
END DESCRIPTION:
XS GIS Cut Line= 3
      3527342.14     10409091.64      3527192.11     10409091.64
      3526992.14     10409091.64
#Sta/Elev= 30
  4825.9  365.84  4855.9  364.50  4875.9  363.36  4885.9  362.61  4925.9  361.26
  4945.9  360.28  4955.9  359.48  4965.9  358.30  4973.4  356.63  4978.4  356.63
  4985.9  354.62  4993.9  353.83  4994.2  353.33  4997.7  353.33  4997.9  353.83
  5005.9  354.38  5015.9  354.59  5025.9  354.59  5037.5  354.31  5055.9  353.87
  5075.9  353.95  5085.9  356.71  5095.9  358.98  5105.9  360.21  5125.9  363.33
  5135.9  364.32  5145.9  364.68  5155.9  365.26  5173.4  366.59  5175.9  366.59
#Mann=4,-1,0
  4825.9    0.16       0  4993.9    0.07       0  4997.9    0.16       0
  5037.5    0.05       0
Bank Sta=4993.9,4997.9
Exp/Cntr=0.3,0.1

Type RM Length L Ch R = 1,2404,463,463,463
BEGIN DESCRIPTION:
DUCK CREEK TRIB 20 6 0
END DESCRIPTION:
XS GIS Cut Line= 3
      3527142.12     10408441.63      3526942.11     10408741.64
      3526792.11     10408891.64
#Sta/Elev= 30
  4639.8  375.11  4653.3  374.43  4716.4  369.55  4725.5  369.08  4734.5  367.91
  4740.5  367.80  4770.5  365.47  4776.5  364.54  4790.1  363.66  4797.6  362.67
  4806.6  362.19  4833.6  359.50  4842.6  358.93  4872.7  355.01  4905.7  352.65
  4920.8  351.98  4950.8  351.53  4992.9  350.04  4995.4  349.50  4995.6  349.00
  4999.1  349.00  4999.4  349.50  5003.9  349.50  5028.7  352.88  5042.8  354.06
  5071.1  355.31  5099.4  357.03  5179.0  362.90  5209.0  366.08  5212.5  366.08
#Mann=6,-1,0
  4639.8    0.05       0  4716.4    0.16       0  4872.7    0.05       0
  4995.4    0.03       0  4999.4    0.05       0  5179.0    0.16       0
Bank Sta=4995.4,4999.4
Exp/Cntr=0.3,0.1

Type RM Length L Ch R = 1,1941,668,668,668
BEGIN DESCRIPTION:
DUCK CREEK TRIB 20 5 0
END DESCRIPTION:
XS GIS Cut Line= 3
      3526892.12     10408241.63      3526592.11     10408491.64
      3526542.10     10408741.66
#Sta/Elev= 30
  4626.4  369.06  4629.7  369.06  4633.6  368.28  4647.9  367.03  4659.7  366.35
  4690.9  362.94  4773.1  356.18  4789.8  354.30  4847.1  350.31  4853.6  350.18
  4867.9  348.99  4874.4  349.06  4906.1  347.51  4918.3  347.11  4966.8  347.21
  5001.3  346.51  5001.5  346.01  5005.0  346.01  5005.3  346.51  5009.8  346.88
  5019.5  346.77  5049.3  348.44  5093.4  350.33  5122.0  352.75  5148.6  353.99
  5159.7  355.15  5200.5  358.07  5231.1  359.57  5261.7  362.21  5271.9  362.67
#Mann=10,-1,0
  4626.4    0.05       0  4659.7    0.16       0  4773.1    0.05       0
  4906.1    0.16       0  4918.3    0.05       0  5001.3    0.03       0
  5005.3    0.05       0  5049.3    0.16       0  5122.0    0.05       0
  5148.6    0.16       0
Bank Sta=5001.3,5005.3
Exp/Cntr=0.3,0.1

Type RM Length L Ch R = 1,1273,529,529,529
BEGIN DESCRIPTION:
DUCK CREEK TRIB 20 4 0
END DESCRIPTION:
XS GIS Cut Line= 3
      3526957.02     10407850.52      3526316.43     10407970.31
      3526175.82     10408761.93
#Sta/Elev= 30
  4216.1  361.08  4248.0  359.17  4253.0  359.65  4300.6  356.25  4305.7  357.04
  4353.2  353.43  4358.3  353.92  4411.0  350.15  4416.0  350.56  4521.3  343.13
  4526.4  343.50  4573.9  341.09  4626.6  339.54  4684.3  339.22  4831.5  340.39
  4867.4  339.63  4970.7  339.90  4999.2  337.28  4999.4  336.78  5003.2  337.28
  5031.0  340.39  5052.0  340.48  5090.1  343.00  5143.4  345.30  5149.1  346.26
  5234.8  351.94  5305.9  354.43  5375.2  358.30  5509.0  357.05  5671.8  360.49
#Mann=3,-1,0
  4216.1    0.05       0  4999.2    0.03       0  5003.2    0.05       0
Bank Sta=4999.2,5003.2
Exp/Cntr=0.3,0.1

Type RM Length L Ch R = 1,744,0,0,0
BEGIN DESCRIPTION:
DUCK CREEK TRIB 20 1 0
END DESCRIPTION:
XS GIS Cut Line= 4
      3526941.41     10407246.36      3525884.14     10407803.64
      3525825.15     10408287.30      3526149.78     10408991.16
#Sta/Elev= 30
  3627.1  348.73  3668.2  345.86  3695.9  345.03  3756.3  340.66  3778.4  340.43
  3794.7  338.82  3844.5  336.90  3904.9  332.33  4037.0  333.35  4075.4  332.20
  4119.5  332.35  4207.6  333.49  4268.0  332.47  4466.3  334.23  4548.7  332.56
  4860.5  334.16  5061.5  332.91  5332.4  331.86  5332.7  331.36  5336.4  331.86
  5375.2  331.99  5402.4  332.34  5431.7  334.14  5649.3  349.98  5666.7  349.82
  5700.7  352.17  5741.1  352.73  5821.0  357.10  5912.8  360.78  6084.6  366.00
#Mann=5,-1,0
  3627.1    0.05       0  5061.5     0.1       0  5332.4    0.03       0
  5336.4     0.1       0  5375.2    0.05       0
Bank Sta=5332.4,5336.4
Exp/Cntr=0.3,0.1

Chan Stop Cuts=-1