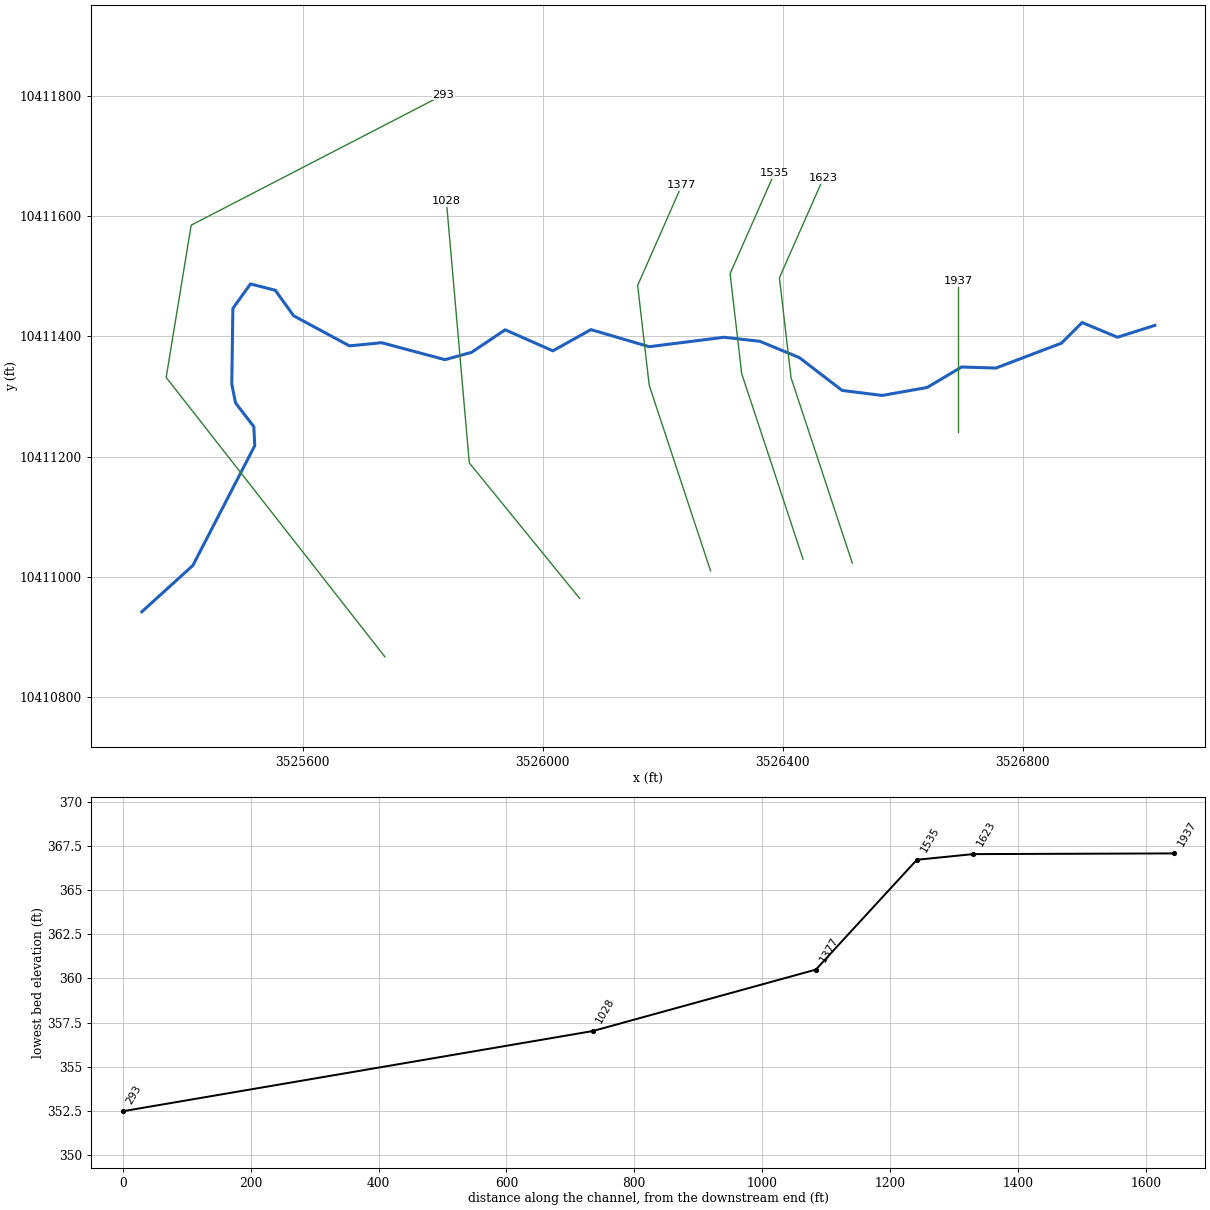
--- DUCK CREEK TRIB 21 1.prj (project) ---

Proj Title=DUCK CREEK TRIB 21 1 Base Level Engineering
Current Plan=p01
Default Exp/Contr=0.3,0.1
English Units
Geom File=g01
Flow File=f01
Plan File=p01
Y Axis Title=Elevation
X Axis Title(PF)=Main Channel Distance
X Axis Title(XS)=Station
BEGIN DESCRIPTION:
DUCK CREEK TRIB 21 1
END DESCRIPTION:
DSS Export Rating Curves= 0
DSS Export Rating Curve Sorted= 0
DSS Export Volume Flow Curves= 0
DXF OffsetX= 0
DXF OffsetY= 0
DXF ScaleX= 1
DXF ScaleY= 10

--- DUCK CREEK TRIB 21 1.p01 (plan) ---

Plan Title=Multiple Run
Short Identifier=Multiple
Geom File=g01
Flow File=f01
Subcritical Flow
K Sum by GR= 0
Std Step Tol= 0.01
Critical Tol= 0.01
Num of Std Step Trials= 20
Max Error Tol= 0.3
Flow Tol Ratio= 0.001
Split Flow NTrial= 30
Split Flow Tol= 0.02
Split Flow Ratio= 0.02
Log Output Level= 0
Friction Slope Method= 1
Unsteady Friction Slope Method= 2
Unsteady Bridges Friction Slope Method= 1
Parabolic Critical Depth
Global Vel Dist=  1 , 1 , 1
Global Log Level= 0
CheckData=True
Encroach Param= -1, 0, 0, 0
BEGIN DESCRIPTION:
Multiple Run
END DESCRIPTION:

--- DUCK CREEK TRIB 21 1.f01 (steady flow) ---

Flow Title=Multiple
Number of Profiles=7
Profile Names=10-year,25-year,50-year,1pct_min,100-year,1pct_plu,500-year
River Rch & RM= DUCK CREEK TRIB ,Reach-1,1937
     463     618     743     655     886    1198    1253
Boundary for River Rch & Prof#=DUCK CREEK TRIB ,Reach-1,1
Up Type=0
Dn Type=3
Dn Slope=0.005
Boundary for River Rch & Prof#=DUCK CREEK TRIB ,Reach-1,2
Up Type=0
Dn Type=3
Dn Slope=0.005
Boundary for River Rch & Prof#=DUCK CREEK TRIB ,Reach-1,3
Up Type=0
Dn Type=3
Dn Slope=0.005
Boundary for River Rch & Prof#=DUCK CREEK TRIB ,Reach-1,4
Up Type=0
Dn Type=3
Dn Slope=0.005
Boundary for River Rch & Prof#=DUCK CREEK TRIB ,Reach-1,5
Up Type=0
Dn Type=3
Dn Slope=0.005
Boundary for River Rch & Prof#=DUCK CREEK TRIB ,Reach-1,6
Up Type=0
Dn Type=3
Dn Slope=0.005
Boundary for River Rch & Prof#=DUCK CREEK TRIB ,Reach-1,7
Up Type=0
Dn Type=3
Dn Slope=0.005

--- DUCK CREEK TRIB 21 1.g01 (geometry) ---

Geom Title=Existing Conditions
Program Version=4.10

River Reach=DUCK CREEK TRIB ,Reach-1
Reach XY= 30
      3527020.11     10411418.31      3526957.96     10411398.65
      3526898.99     10411423.13      3526864.58     10411388.75
      3526755.19     10411347.29       3526698.2     10411349.08
      3526640.74     10411314.95      3526565.74     10411301.72
      3526499.07     10411310.05      3526427.71     10411364.74
      3526362.09     10411391.82      3526302.19     10411398.59
      3526177.53     10411382.88      3526080.39     10411411.33
      3526016.89     10411375.97      3525937.52     10411411.03
       3525881.4     10411373.43      3525837.09     10411361.28
       3525731.6     10411389.52        3525678.     10411384.25
      3525584.94     10411434.37      3525554.42     10411476.76
      3525513.03     10411487.39      3525483.69     10411446.66
      3525481.84     10411320.61      3525488.08     10411289.31
      3525518.58     10411249.76      3525520.12     10411218.06
      3525417.05     10411018.71      3525332.11     10410941.64

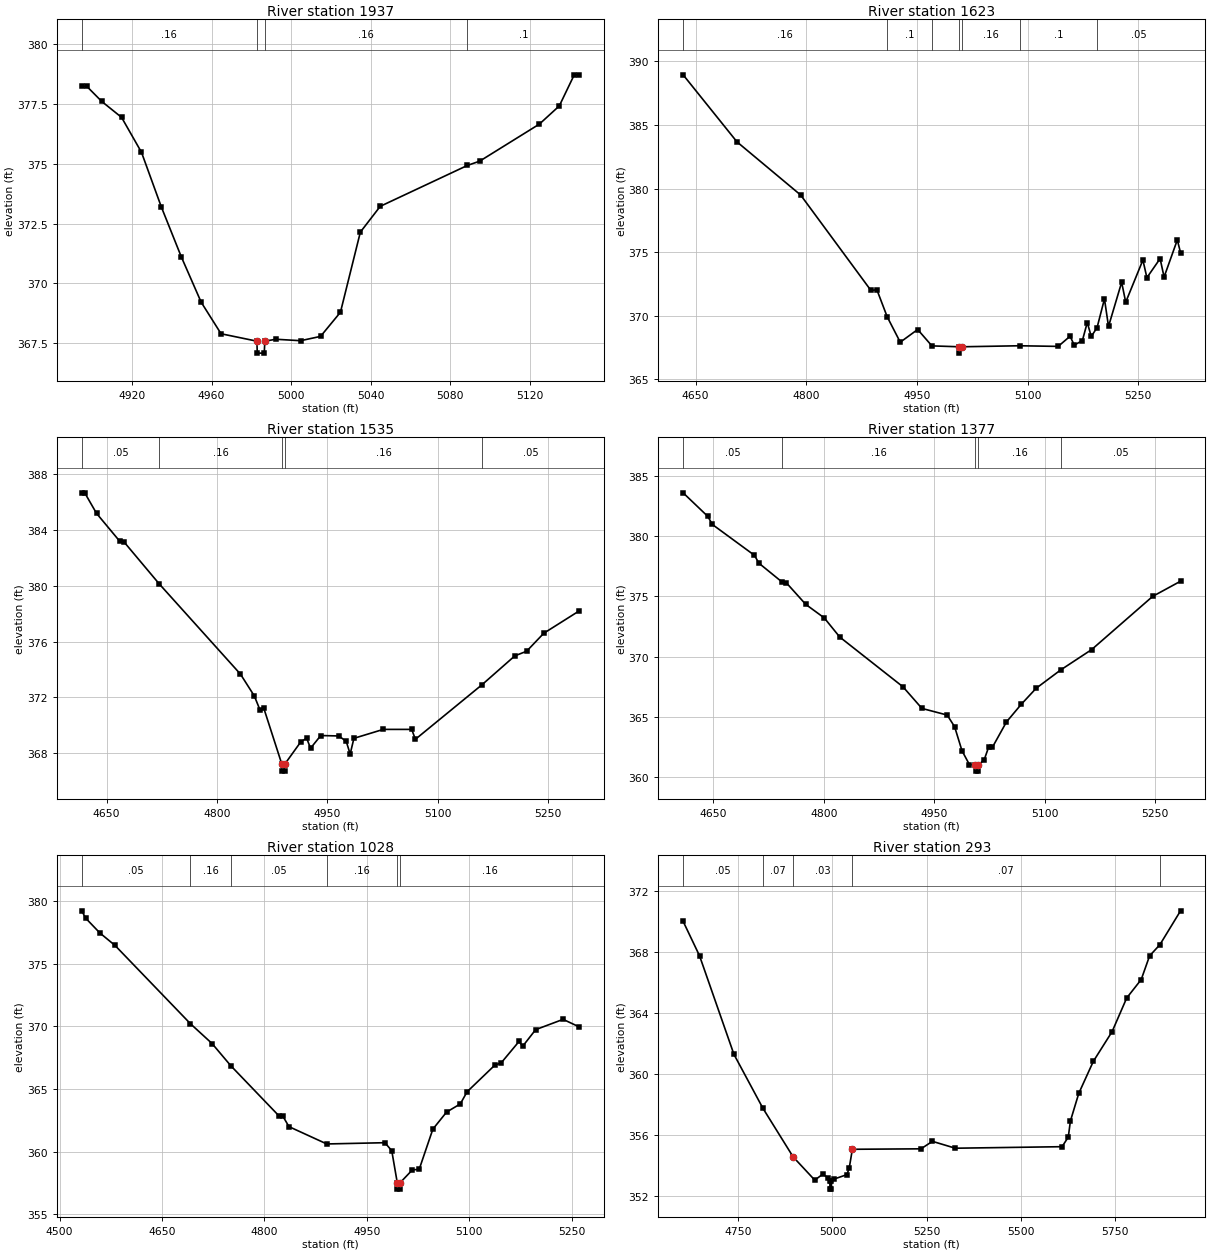
Type RM Length L Ch R = 1 ,1937    ,314,314,314
BEGIN DESCRIPTION:
DUCK CREEK TRIB 21 1 12 0
END DESCRIPTION:
XS GIS Cut Line= 3
      3526692.11     10411241.65      3526692.11     10411341.64
      3526692.11     10411491.65
#Sta/Elev= 25
  4894.8  378.24  4897.3  378.24  4904.8  377.61  4914.8  376.94  4924.8  375.48
  4934.8  373.19  4944.8  371.11  4954.8  369.21  4964.8  367.89  4982.8  367.58
    4983  367.08  4986.5  367.08  4986.8  367.58  4992.3  367.66  5004.8   367.6
  5014.8  367.78  5024.8  368.79  5034.8  372.14  5044.8  373.22  5088.6  374.93
  5094.8  375.11  5124.8  376.66  5134.8  377.42  5142.3  378.72  5144.8  378.72
#Mann= 4 ,-1 , 0
  4894.8     .16       0  4982.8     .07       0  4986.8     .16       0
  5088.6      .1       0
Bank Sta=4982.8,4986.8
XS Rating Curve= 0 ,0
Exp/Cntr=0.3,0.1

Type RM Length L Ch R = 1 ,1623    ,88,88,88
BEGIN DESCRIPTION:
DUCK CREEK TRIB 21 1 10 0
END DESCRIPTION:
XS GIS Cut Line= 4
       3526516.1     10411022.36       3526413.9     10411331.22
      3526394.56     10411497.66      3526467.71     10411663.34
#Sta/Elev= 30
  4633.2  388.95  4706.2  383.67  4792.4  379.49  4887.6  371.98  4895.8  372.02
  4909.7   369.9  4927.4   367.9    4951   368.9  4970.3  367.61  5007.3  367.54
  5007.5  367.04  5011.3  367.54    5089  367.62  5141.4  367.57  5157.5  368.37
  5163.2  367.67  5174.2  368.03  5180.8  369.45  5186.2  368.35  5194.1  369.05
  5204.1  371.31  5209.6  369.14  5227.4  372.62  5232.9  371.05  5256.2  374.37
  5261.6  372.98  5279.5  374.48  5284.9  373.03  5302.8  375.95  5307.2  374.95
#Mann= 7 ,-1 , 0
  4633.2     .16       0  4909.7      .1       0  4970.3     .16       0
  5007.3     .07       0  5011.3     .16       0    5089      .1       0
  5194.1     .05       0
Bank Sta=5007.3,5011.3
XS Rating Curve= 0 ,0
Exp/Cntr=0.3,0.1

Type RM Length L Ch R = 1 ,1535    ,158,158,158
BEGIN DESCRIPTION:
DUCK CREEK TRIB 21 1 3 2
END DESCRIPTION:
XS GIS Cut Line= 4
      3526433.87     10411029.18      3526331.67     10411338.04
      3526312.33     10411504.48      3526386.13     10411671.62
#Sta/Elev= 30
  4616.3  386.66  4620.3  386.66  4636.3  385.19    4668  383.18  4673.2  383.17
  4721.4  380.14  4831.8  373.67  4850.6  372.11  4858.3  371.11  4863.5  371.23
    4888  367.22  4888.2  366.72  4891.7  366.72    4892  367.22  4913.8  368.82
  4921.7  369.08    4927  368.36  4940.9  369.27  4965.4  369.24  4975.5  368.85
  4980.8  367.94  4985.9  369.07  5025.8  369.71  5064.4  369.71  5069.4     369
  5159.9  372.91  5204.5  374.98  5220.5  375.31  5243.8   376.6  5291.9   378.2
#Mann= 5 ,-1 , 0
  4616.3     .05       0  4721.4     .16       0    4888     .07       0
    4892     .16       0  5159.9     .05       0
Bank Sta=4888,4892
XS Rating Curve= 0 ,0
Exp/Cntr=0.3,0.1

Type RM Length L Ch R = 1 ,1377    ,349,349,349
BEGIN DESCRIPTION:
DUCK CREEK TRIB 21 1 4 0
END DESCRIPTION:
XS GIS Cut Line= 4
      3526279.76     10411009.73      3526177.59     10411318.51
      3526158.25     10411484.95      3526232.05     10411652.08
#Sta/Elev= 30
    4609  383.58  4642.6  381.62  4648.6  380.96  4705.8   378.4    4712  377.74
    4743   376.2    4749  376.13  4775.5  374.33  4800.6  373.21  4821.7  371.62
  4907.6  367.49  4933.3   365.7  4967.6  365.15  4977.7  364.18  4987.7  362.19
  4997.8  361.04  5005.9     361  5006.1   360.5  5009.6   360.5  5009.9     361
  5017.9  361.45    5024  362.51  5029.1  362.49  5048.1  364.58  5068.3  366.05
  5088.4  367.37  5121.7  368.89  5163.8  370.58  5246.6  374.99  5284.5  376.25
#Mann= 5 ,-1 , 0
    4609     .05       0    4743     .16       0  5005.9     .07       0
  5009.9     .16       0  5121.7     .05       0
Bank Sta=5005.9,5009.9
XS Rating Curve= 0 ,0
Exp/Cntr=0.3,0.1

Type RM Length L Ch R = 1 ,1028    ,735,735,735
BEGIN DESCRIPTION:
DUCK CREEK TRIB 21 1 3 1
END DESCRIPTION:
XS GIS Cut Line= 3
      3526061.74     10410963.67       3525877.7     10411189.38
      3525839.51     10411625.18
#Sta/Elev= 30
  4532.5   379.2  4538.1  378.62  4558.9  377.44  4581.2  376.44  4691.7   370.2
  4723.4  368.62  4750.7  366.86    4822  362.82  4827.2  362.82    4836     362
  4891.4  360.62  4976.6  360.72  4986.6  360.08  4994.7  357.52  4994.9  357.02
  4998.4  357.02  4998.7  357.52  5016.7  358.55  5026.8   358.6  5046.8   361.8
  5066.9  363.16    5087  363.81    5097  364.78  5137.2  366.88  5147.2   367.1
  5173.2   368.8  5178.3   368.4  5197.4  369.73  5237.6  370.55  5261.2  369.95
#Mann= 6 ,-1 , 0
  4532.5     .05       0  4691.7     .16       0  4750.7     .05       0
  4891.4     .16       0  4994.7     .07       0  4998.7     .16       0
Bank Sta=4994.7,4998.7
XS Rating Curve= 0 ,0
Exp/Cntr=0.3,0.1

Type RM Length L Ch R = 1 ,293     ,0,0,0
BEGIN DESCRIPTION:
DUCK CREEK TRIB 21 1 1 0
END DESCRIPTION:
XS GIS Cut Line= 4
       3525737.1     10410866.43      3525372.49     10411331.74
      3525414.16     10411585.22       3525834.3     10411802.23
#Sta/Elev= 30
  4603.4  370.02  4646.9  367.77  4738.3  361.31  4815.2  357.78  4895.6  354.59
    4953  353.07  4974.2  353.46  4988.7  353.22    4993  352.98  4993.3  352.48
  4996.8  352.48    4997  352.98  5003.1  353.13  5038.4  353.43  5044.7  353.89
  5052.8  355.09    5235  355.12  5265.4  355.61  5326.2  355.16  5609.7  355.26
  5626.2  355.89  5631.8  356.94    5654  358.75  5692.7  360.85  5742.6   362.8
  5781.3     365  5819.9  366.21  5842.1  367.76  5869.4  368.49  5924.3  370.71
#Mann= 5 ,-1 , 0
  4603.4     .05       0  4815.2     .07       0  4895.6     .03       0
  5052.8     .07       0  5869.4     .05       0
Bank Sta=4895.6,5052.8
XS Rating Curve= 0 ,0
Exp/Cntr=0.3,0.1

Chan Stop Cuts=-1
Use User Specified Reach Order=0
Composite Channel Slope=5