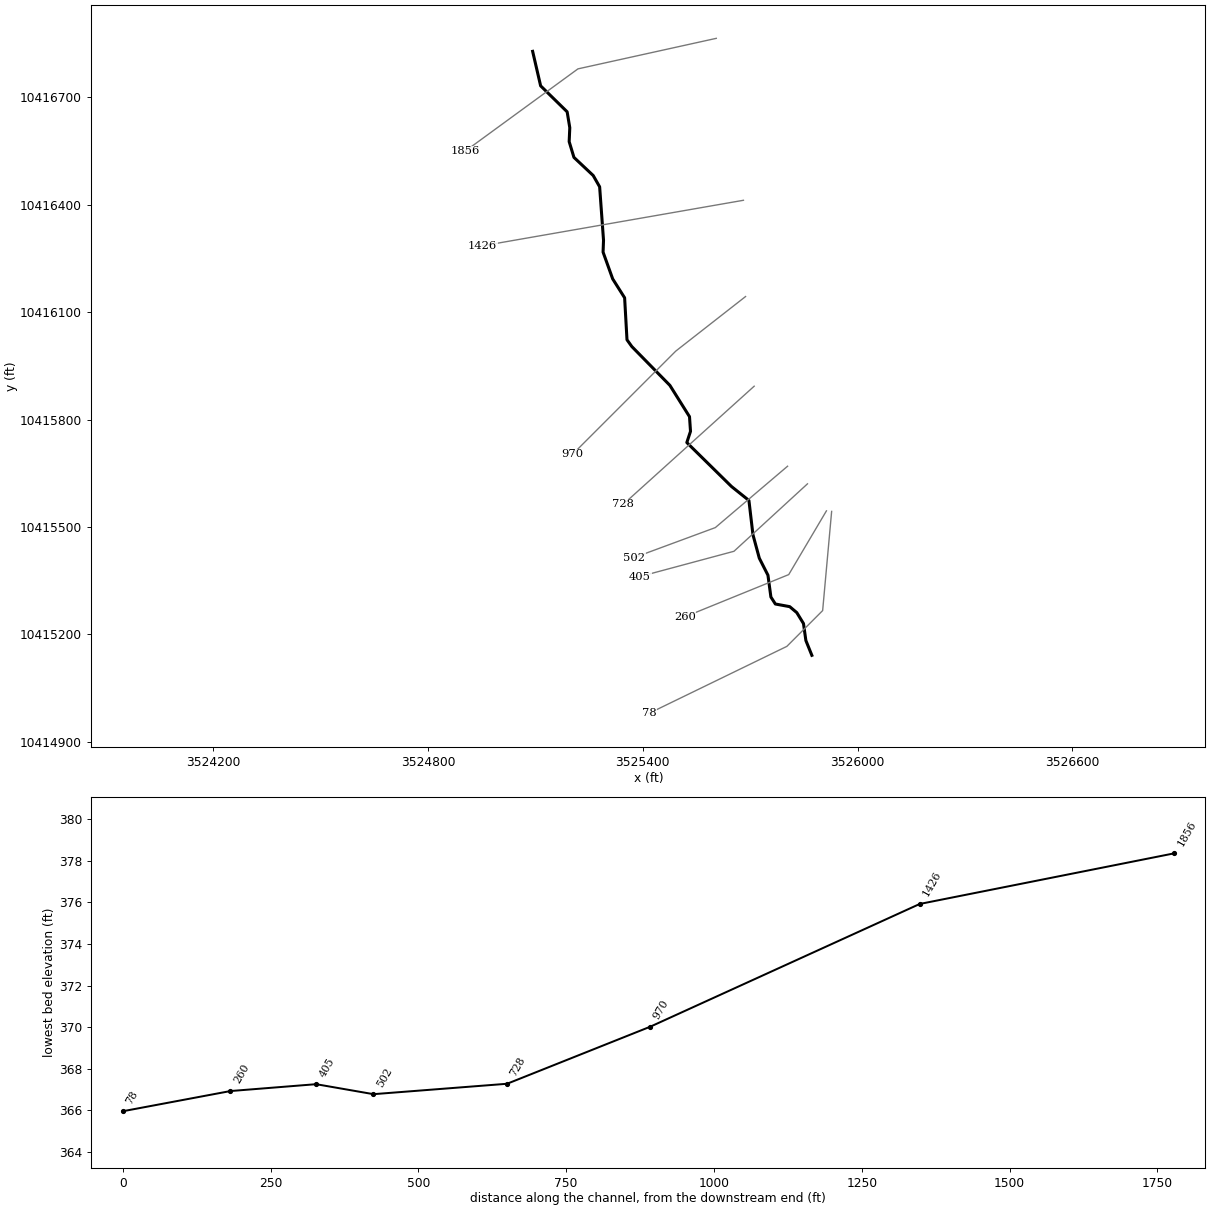
--- DUCK CREEK TRIB 21 2.prj (project) ---

Proj Title=DUCK CREEK TRIB 21 2 Base Level Engineering
Current Plan=p01
Default Exp/Contr=0.3,0.1
English Units
Geom File=g01
Flow File=f01
Plan File=p01
Y Axis Title=Elevation
X Axis Title(PF)=Main Channel Distance
X Axis Title(XS)=Station
BEGIN DESCRIPTION:
DUCK CREEK TRIB 21 2
END DESCRIPTION:
DSS Export Rating Curves= 0
DSS Export Rating Curve Sorted= 0
DSS Export Volume Flow Curves= 0
DXF OffsetX= 0
DXF OffsetY= 0
DXF ScaleX= 1
DXF ScaleY= 10

--- DUCK CREEK TRIB 21 2.p01 (plan) ---

Plan Title=Multiple Run
Short Identifier=Multiple
Geom File=g01
Flow File=f01
Subcritical Flow
K Sum by GR= 0
Std Step Tol= 0.01
Critical Tol= 0.01
Num of Std Step Trials= 20
Max Error Tol= 0.3
Flow Tol Ratio= 0.001
Split Flow NTrial= 30
Split Flow Tol= 0.02
Split Flow Ratio= 0.02
Log Output Level= 0
Friction Slope Method= 1
Unsteady Friction Slope Method= 2
Unsteady Bridges Friction Slope Method= 1
Parabolic Critical Depth
Global Vel Dist=  1 , 1 , 1
Global Log Level= 0
CheckData=True
Encroach Param= -1, 0, 0, 0
BEGIN DESCRIPTION:
Multiple Run
END DESCRIPTION:

--- DUCK CREEK TRIB 21 2.f01 (steady flow) ---

Flow Title=Multiple
Number of Profiles=7
Profile Names=10-year,25-year,50-year,1pct_min,100-year,1pct_plu,500-year
River Rch & RM= DUCK CREEK TRIB ,Reach-1,1856
     366     479     568     494     668     904     920
River Rch & RM= DUCK CREEK TRIB ,Reach-1,78
    1726    2482    3133    2884    3901    5275    6034
Boundary for River Rch & Prof#=DUCK CREEK TRIB ,Reach-1,1
Up Type=0
Dn Type=3
Dn Slope=0.005
Boundary for River Rch & Prof#=DUCK CREEK TRIB ,Reach-1,2
Up Type=0
Dn Type=3
Dn Slope=0.005
Boundary for River Rch & Prof#=DUCK CREEK TRIB ,Reach-1,3
Up Type=0
Dn Type=3
Dn Slope=0.005
Boundary for River Rch & Prof#=DUCK CREEK TRIB ,Reach-1,4
Up Type=0
Dn Type=3
Dn Slope=0.005
Boundary for River Rch & Prof#=DUCK CREEK TRIB ,Reach-1,5
Up Type=0
Dn Type=3
Dn Slope=0.005
Boundary for River Rch & Prof#=DUCK CREEK TRIB ,Reach-1,6
Up Type=0
Dn Type=3
Dn Slope=0.005
Boundary for River Rch & Prof#=DUCK CREEK TRIB ,Reach-1,7
Up Type=0
Dn Type=3
Dn Slope=0.005

--- DUCK CREEK TRIB 21 2.g01 (geometry) ---

Geom Title=Existing Conditions
Program Version=4.10

River Reach=DUCK CREEK TRIB ,Reach-1
Reach XY= 30
      3525092.11     10416828.88      3525114.43     10416732.52
      3525188.51     10416659.96      3525195.88     10416615.56
      3525194.16     10416576.64      3525207.52     10416532.59
       3525261.3     10416482.02      3525279.27     10416450.47
      3525290.13     10416301.19      3525288.87       10416268.
      3525315.73     10416193.18      3525349.07     10416140.39
      3525355.68     10416023.12      3525369.18     10416004.24
      3525475.47     10415895.82      3525530.33     10415808.32
      3525533.11     10415767.35      3525522.83     10415736.06
      3525647.69     10415613.19      3525696.31      10415574.3
      3525707.58     10415478.52      3525725.32     10415413.01
      3525749.46     10415365.46      3525757.71     10415304.48
      3525770.18     10415285.01      3525810.28      10415277.6
      3525830.01     10415260.98      3525848.72     10415230.48
      3525855.41       10415183.      3525872.11     10415141.64

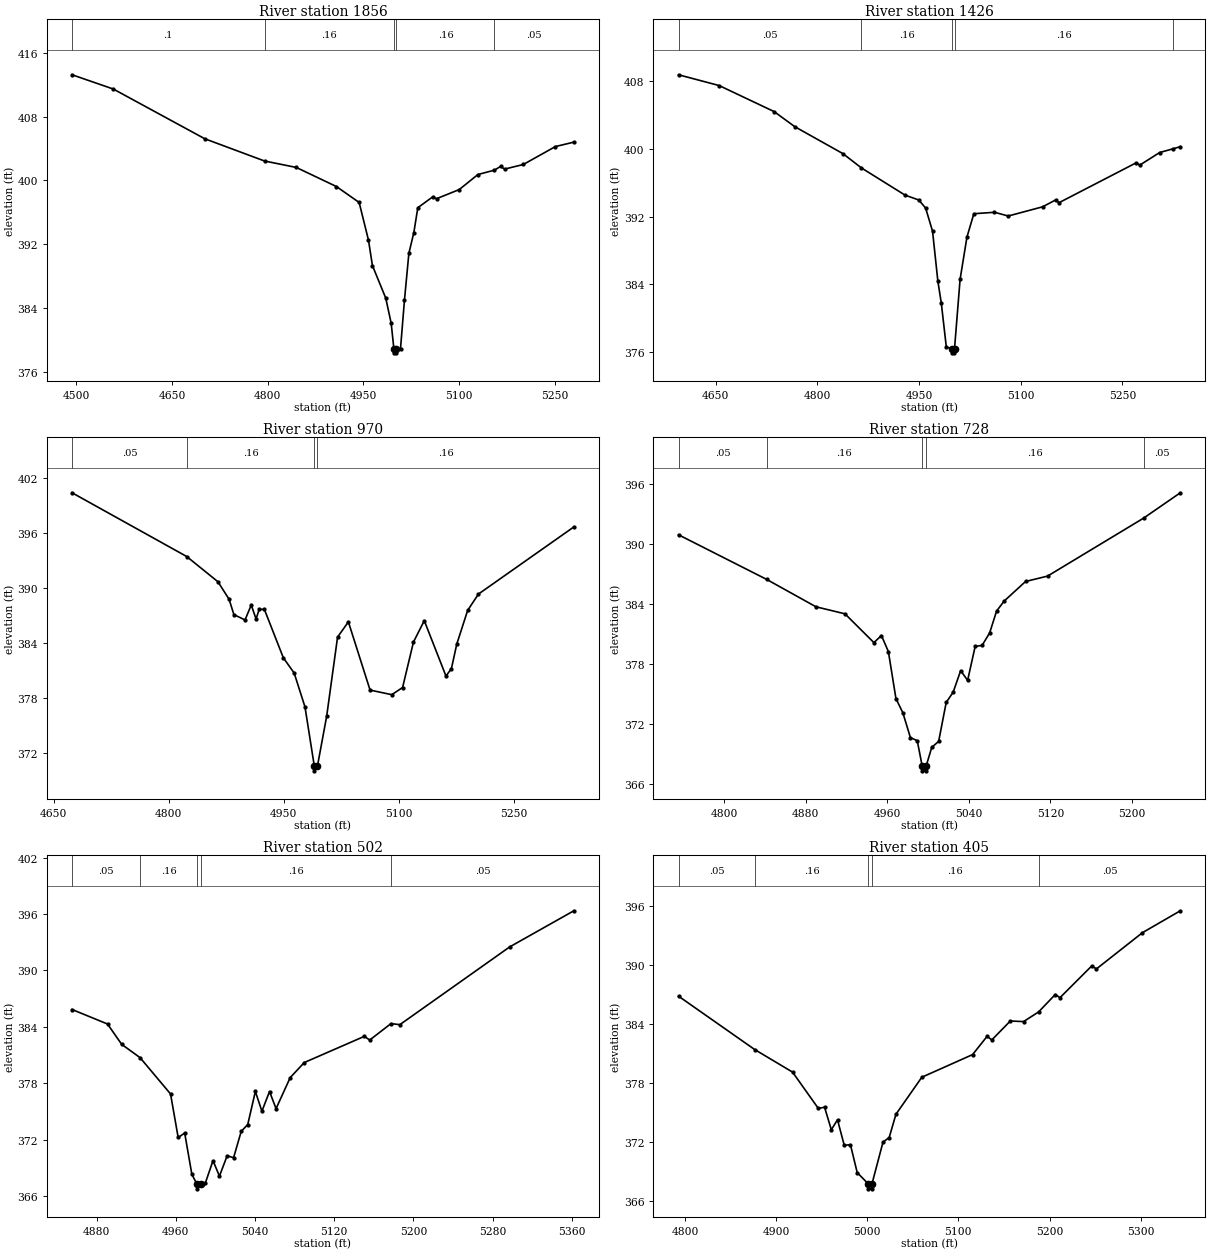
Type RM Length L Ch R = 1 ,1856    ,430,430,430
BEGIN DESCRIPTION:
DUCK CREEK TRIB 21 2 50 1
END DESCRIPTION:
XS GIS Cut Line= 3
      3525605.18     10416865.23      3525218.66     10416779.92
      3524903.34     10416549.77
#Sta/Elev= 30
  4493.4  413.28    4558  411.49  4701.4  405.24  4794.9  402.45  4844.7  401.64
  4907.6  399.24  4943.2  397.24  4957.8  392.51    4964  389.31  4984.9  385.22
  4993.4  382.06  4997.6  378.85  4997.8  378.35  5001.3  378.35  5001.6  378.85
    5008  378.88  5014.2  384.98  5021.1  390.85  5028.9  393.46  5035.1  396.58
  5058.2  397.93  5064.4  397.71    5100  398.86  5129.3  400.75  5155.2   401.3
  5164.8  401.77    5171  401.43  5200.4  402.01  5250.6  404.26  5279.6  404.82
#Mann= 5 ,-1 , 0
  4493.4      .1       0  4794.9     .16       0  4997.6     .07       0
  5001.6     .16       0  5155.2     .05       0
Bank Sta=4997.6,5001.6
XS Rating Curve= 0 ,0
Exp/Cntr=0.3,0.1

Type RM Length L Ch R = 1 ,1426    ,456,456,456
BEGIN DESCRIPTION:
DUCK CREEK TRIB 21 2 40 0
END DESCRIPTION:
XS GIS Cut Line= 2
      3525680.99     10416412.83      3524952.21     10416285.66
#Sta/Elev= 30
  4595.5  408.76  4655.3  407.49  4736.5  404.41  4766.9  402.63    4838  399.44
  4865.1  397.76  4929.4  394.55  4949.7  393.97  4959.8  393.02    4970  390.28
  4977.8  384.41  4982.9  381.79  4990.3   376.6  4998.4  376.42  4998.7  375.92
  5002.2  375.92  5002.4  376.42  5010.6   384.6  5020.7  389.59  5030.9  392.35
  5061.3  392.52  5081.6  392.08  5132.4  393.17  5151.3  393.97  5156.4  393.65
  5270.4  398.37  5275.5  398.09  5304.9  399.58  5325.1  400.03  5335.3  400.27
#Mann= 5 ,-1 , 0
  4595.5     .05       0  4865.1     .16       0  4998.4     .07       0
  5002.4     .16       0  5325.1     .05       0
Bank Sta=4998.4,5002.4
XS Rating Curve= 0 ,0
Exp/Cntr=0.3,0.1

Type RM Length L Ch R = 1 ,970     ,242,242,242
BEGIN DESCRIPTION:
DUCK CREEK TRIB 21 2 2 2
END DESCRIPTION:
XS GIS Cut Line= 3
      3525686.92     10416143.93      3525492.11     10415991.64
      3525204.15      10415703.7
#Sta/Elev= 30
  4673.8  400.39  4823.3  393.43  4864.1  390.67  4878.6  388.76  4884.9  387.08
  4899.4   386.5  4907.5  388.13  4913.8  386.61  4917.9  387.66  4924.6  387.66
  4949.4  382.36  4963.5   380.7  4977.6     377  4989.8  370.52    4990  370.02
  4993.8  370.52  5005.9  375.99  5020.1  384.63  5034.2  386.29  5062.5  378.84
  5090.8  378.34  5104.9  379.12  5119.1  384.09  5133.2  386.42  5161.5  380.37
  5168.6  381.19  5175.6  383.87  5189.8  387.55  5203.9  389.33  5328.3  396.66
#Mann= 4 ,-1 , 0
  4673.8     .05       0  4823.3     .16       0  4989.8     .07       0
  4993.8     .16       0
Bank Sta=4989.8,4993.8
XS Rating Curve= 0 ,0
Exp/Cntr=0.3,0.1

Type RM Length L Ch R = 1 ,728     ,226,226,226
BEGIN DESCRIPTION:
DUCK CREEK TRIB 21 2 4 0
END DESCRIPTION:
XS GIS Cut Line= 2
      3525710.99     10415893.47      3525345.64     10415563.79
#Sta/Elev= 30
  4755.4  390.88  4841.8  386.42  4890.2  383.68  4918.6  382.98    4947   380.1
  4954.4  380.81  4961.2   379.2  4968.6  374.51  4975.4  373.08  4982.8   370.6
  4989.5   370.3  4994.3  367.78  4994.6  367.28  4998.1  367.28  4998.3  367.78
  5003.7  369.62  5010.5  370.23  5017.9  374.12  5024.7  375.14  5032.1   377.3
  5038.9  376.32  5046.3  379.72  5053.1  379.82  5060.5  381.07  5067.3  383.25
  5074.7  384.25  5095.7  386.21  5117.3  386.75  5211.4  392.54  5247.5  395.08
#Mann= 5 ,-1 , 0
  4755.4     .05       0  4841.8     .16       0  4994.3     .07       0
  4998.3     .16       0  5211.4     .05       0
Bank Sta=4994.3,4998.3
XS Rating Curve= 0 ,0
Exp/Cntr=0.3,0.1

Type RM Length L Ch R = 1 ,502     ,97,97,97
BEGIN DESCRIPTION:
DUCK CREEK TRIB 21 2 2 1
END DESCRIPTION:
XS GIS Cut Line= 3
      3525804.29     10415669.94      3525602.46     10415498.48
      3525375.31     10415414.51
#Sta/Elev= 30
  4855.2  385.85    4891  384.31  4905.3  382.15  4923.9  380.73  4954.7  376.87
  4962.4  372.24    4969  372.71  4976.2  368.34  4981.3  367.28  4981.5  366.78
  4985.3  367.28  4989.9  367.41  4997.6  369.78  5004.1  368.13  5011.9   370.3
  5018.4  370.09  5026.1  372.89  5032.7  373.62  5040.4  377.14    5047  375.03
  5054.7  377.13  5061.3  375.31  5075.6  378.61  5089.8  380.21  5150.6     383
  5155.9   382.6  5177.4  384.35  5186.4  384.24  5297.4  392.51  5362.2  396.35
#Mann= 5 ,-1 , 0
  4855.2     .05       0  4923.9     .16       0  4981.3     .07       0
  4985.3     .16       0  5177.4     .05       0
Bank Sta=4981.3,4985.3
XS Rating Curve= 0 ,0
Exp/Cntr=0.3,0.1

Type RM Length L Ch R = 1 ,405     ,145,145,145
BEGIN DESCRIPTION:
DUCK CREEK TRIB 21 2 3 0
END DESCRIPTION:
XS GIS Cut Line= 3
      3525859.84     10415620.69      3525654.54     10415432.29
      3525391.98     10415361.77
#Sta/Elev= 30
    4793  386.82  4876.6   381.4  4918.1  379.11  4946.4  375.42  4953.2  375.55
  4960.6  373.26  4967.4  374.27  4974.8  371.68  4981.6  371.74    4989  368.91
  5001.2  367.76  5001.4  367.26  5004.9  367.26  5005.2  367.76  5017.3     372
  5024.1  372.47  5031.5  374.83  5059.9  378.59  5115.6  380.89  5131.5  382.74
  5136.7  382.38    5157   384.3  5171.5  384.24    5188  385.22  5206.3  386.99
  5211.5  386.67  5246.3  389.89  5251.5  389.59    5302  393.27  5343.5  395.49
#Mann= 5 ,-1 , 0
    4793     .05       0  4876.6     .16       0  5001.2     .07       0
  5005.2     .16       0    5188     .05       0
Bank Sta=5001.2,5005.2
XS Rating Curve= 0 ,0
Exp/Cntr=0.3,0.1

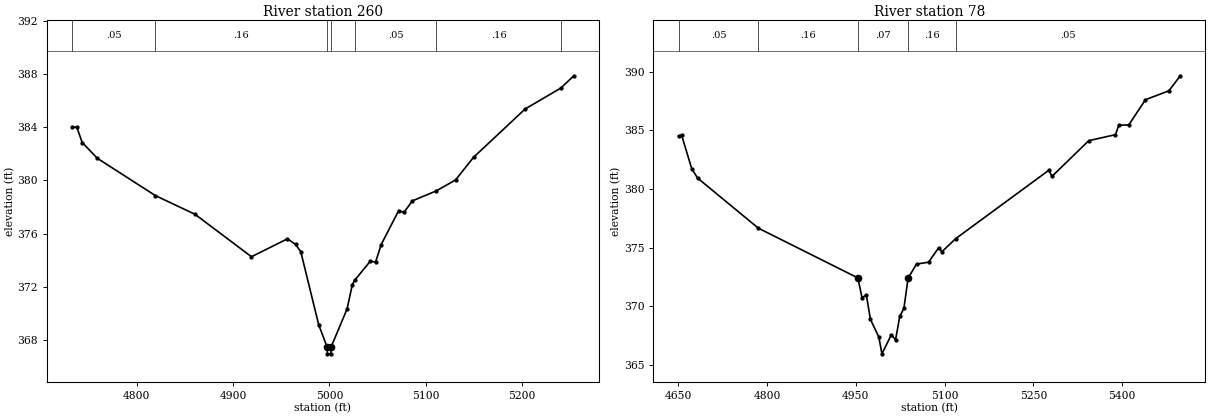
Type RM Length L Ch R = 1 ,260     ,182,182,182
BEGIN DESCRIPTION:
DUCK CREEK TRIB 21 2 2 0
END DESCRIPTION:
XS GIS Cut Line= 3
      3525912.79     10415545.15      3525807.53     10415367.19
      3525516.91     10415248.99
#Sta/Elev= 30
  4733.1  384.02    4738  384.02  4743.6  382.86  4759.3  381.67  4819.5  378.86
  4860.6  377.45  4919.2  374.25  4956.5   375.6  4964.9  375.18  4970.3  374.64
  4988.9  369.13  4997.7  367.43    4998  366.93  5001.5  366.93  5001.7  367.43
  5018.4  370.32  5023.8  372.15  5026.4  372.49  5042.5  373.92  5047.9  373.84
  5053.7  375.16  5071.9  377.73  5077.3  377.59  5086.1  378.46  5111.1  379.22
  5130.9  380.04  5149.5  381.74  5203.1  385.39    5240  386.96  5253.6  387.89
#Mann= 7 ,-1 , 0
  4733.1     .05       0  4819.5     .16       0  4997.7     .07       0
  5001.7     .16       0  5026.4     .05       0  5111.1     .16       0
    5240     .05       0
Bank Sta=4997.7,5001.7
XS Rating Curve= 0 ,0
Exp/Cntr=0.3,0.1

Type RM Length L Ch R = 1 ,78      ,0,0,0
BEGIN DESCRIPTION:
DUCK CREEK TRIB 21 2 1 0
END DESCRIPTION:
XS GIS Cut Line= 4
      3525927.39      10415543.7      3525902.26     10415266.64
      3525802.26     10415166.64      3525417.04     10414979.48
#Sta/Elev= 30
  4650.5  384.52  4655.6  384.62  4672.7  381.75  4682.7  380.94  4785.4  376.67
  4953.6  372.43  4960.6  370.72  4967.7  371.01  4974.8  368.89  4988.9   367.4
  4994.2  365.96  5010.1  367.59  5017.2  367.15  5024.3  369.15  5031.3  369.83
  5038.4  372.41  5052.6  373.61    5073  373.77    5090     375  5095.5  374.66
  5118.6  375.77    5276   381.6  5281.6  381.09  5343.7  384.13  5388.8  384.64
  5394.4  385.44  5411.4  385.48  5439.5  387.62  5479.1  388.38  5498.4  389.66
#Mann= 5 ,-1 , 0
  4650.5     .05       0  4785.4     .16       0  4953.6     .07       0
  5038.4     .16       0  5118.6     .05       0
Bank Sta=4953.6,5038.4
XS Rating Curve= 0 ,0
Exp/Cntr=0.3,0.1

Chan Stop Cuts=-1
Use User Specified Reach Order=0
Composite Channel Slope=5