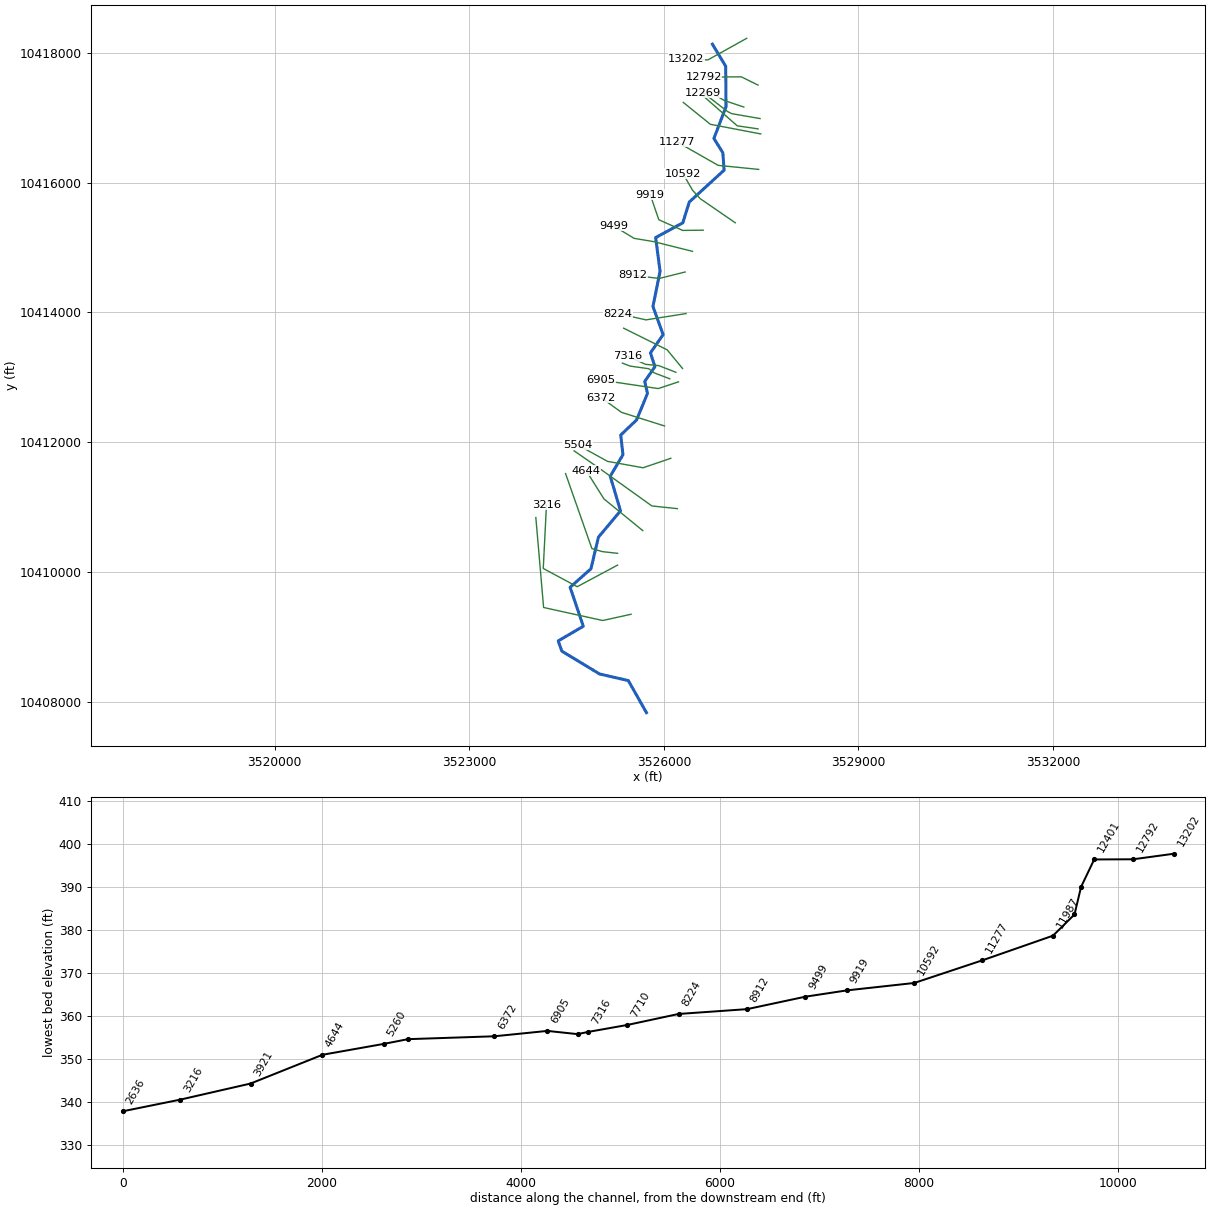
--- DUCK CREEK TRIB 21.prj (project) ---

Proj Title=DUCK CREEK TRIB 21 Base Level Engineering
Current Plan=p01
Default Exp/Contr=0.3,0.1
English Units
Geom File=g01
Flow File=f01
Plan File=p01
Y Axis Title=Elevation
X Axis Title(PF)=Main Channel Distance
X Axis Title(XS)=Station
BEGIN DESCRIPTION:
DUCK CREEK TRIB 21
END DESCRIPTION:
DSS Export Rating Curves= 0
DSS Export Rating Curve Sorted= 0
DSS Export Volume Flow Curves= 0
DXF OffsetX= 0
DXF OffsetY= 0
DXF ScaleX= 1
DXF ScaleY= 10

--- DUCK CREEK TRIB 21.p01 (plan) ---

Plan Title=Multiple Run
Short Identifier=Multiple
Geom File=g01
Flow File=f01
Subcritical Flow
K Sum by GR= 0
Std Step Tol= 0.01
Critical Tol= 0.01
Num of Std Step Trials= 20
Max Error Tol= 0.3
Flow Tol Ratio= 0.001
Split Flow NTrial= 30
Split Flow Tol= 0.02
Split Flow Ratio= 0.02
Log Output Level= 0
Friction Slope Method= 1
Unsteady Friction Slope Method= 2
Unsteady Bridges Friction Slope Method= 1
Parabolic Critical Depth
Global Vel Dist=  1 , 1 , 1
Global Log Level= 0
CheckData=True
Encroach Param= -1, 0, 0, 0
BEGIN DESCRIPTION:
Multiple Run
END DESCRIPTION:

--- DUCK CREEK TRIB 21.f01 (steady flow) ---

Flow Title=Multiple
Program Version=4.10
Number of Profiles= 7
Profile Names=10-year,25-year,50-year,1pct_min,100-year,1pct_plu,500-year
River Rch & RM=DUCK CREEK TRIB,Reach-1         ,13202
    1405    2008    2526    2320    3137    4243    4828
River Rch & RM=DUCK CREEK TRIB,Reach-1         ,9499
    1726    2482    3133    2884    3901    5275    6034
River Rch & RM=DUCK CREEK TRIB,Reach-1         ,5260
    1925    2776    3512    3237    4378    5920    6790
River Rch & RM=DUCK CREEK TRIB,Reach-1         ,4644
    1925    2776    3512    3237    4378    5920    6790
Boundary for River Rch & Prof#=DUCK CREEK TRIB,Reach-1         , 1
Up Type= 0
Dn Type= 3
Dn Slope=0.0086
Boundary for River Rch & Prof#=DUCK CREEK TRIB,Reach-1         , 2
Up Type= 0
Dn Type= 3
Dn Slope=0.0086
Boundary for River Rch & Prof#=DUCK CREEK TRIB,Reach-1         , 3
Up Type= 0
Dn Type= 3
Dn Slope=0.0086
Boundary for River Rch & Prof#=DUCK CREEK TRIB,Reach-1         , 4
Up Type= 0
Dn Type= 3
Dn Slope=0.0086
Boundary for River Rch & Prof#=DUCK CREEK TRIB,Reach-1         , 5
Up Type= 0
Dn Type= 3
Dn Slope=0.0086
Boundary for River Rch & Prof#=DUCK CREEK TRIB,Reach-1         , 6
Up Type= 0
Dn Type= 3
Dn Slope=0.0086
Boundary for River Rch & Prof#=DUCK CREEK TRIB,Reach-1         , 7
Up Type= 0
Dn Type= 3
Dn Slope=0.0086
DSS Import GetInterval= 0
DSS Import GetPeak= 0
DSS Import FillOption= 0

--- DUCK CREEK TRIB 21.g01 (geometry) ---

Geom Title=Existing Conditions
Program Version=4.10

River Reach=DUCK CREEK TRIB ,Reach-1
Reach XY= 30
      3526749.58     10418134.17      3526954.48     10417793.25
      3526958.46      10417170.3       3526772.4     10416681.55
      3526909.93     10416460.79      3526929.39     10416192.84
      3526392.77     10415701.53       3526292.6     10415381.22
        3525874.     10415153.58      3525942.32     10414634.86
      3525832.31     10414091.73      3525989.26     10413657.56
       3525793.8     10413376.68      3525862.55     10413164.18
      3525705.78     10412936.05      3525748.74     10412753.09
       3525579.9     10412342.51      3525335.74     10412110.14
      3525370.09     10411807.37      3525174.29     10411475.73
      3525332.11     10410941.64      3524992.09     10410536.49
      3524876.63     10410049.14      3524555.51     10409763.42
      3524758.67      10409162.9       3524372.4     10408937.15
      3524427.28     10408779.55      3525009.85     10408427.57
      3525453.22     10408325.45      3525732.11     10407831.64

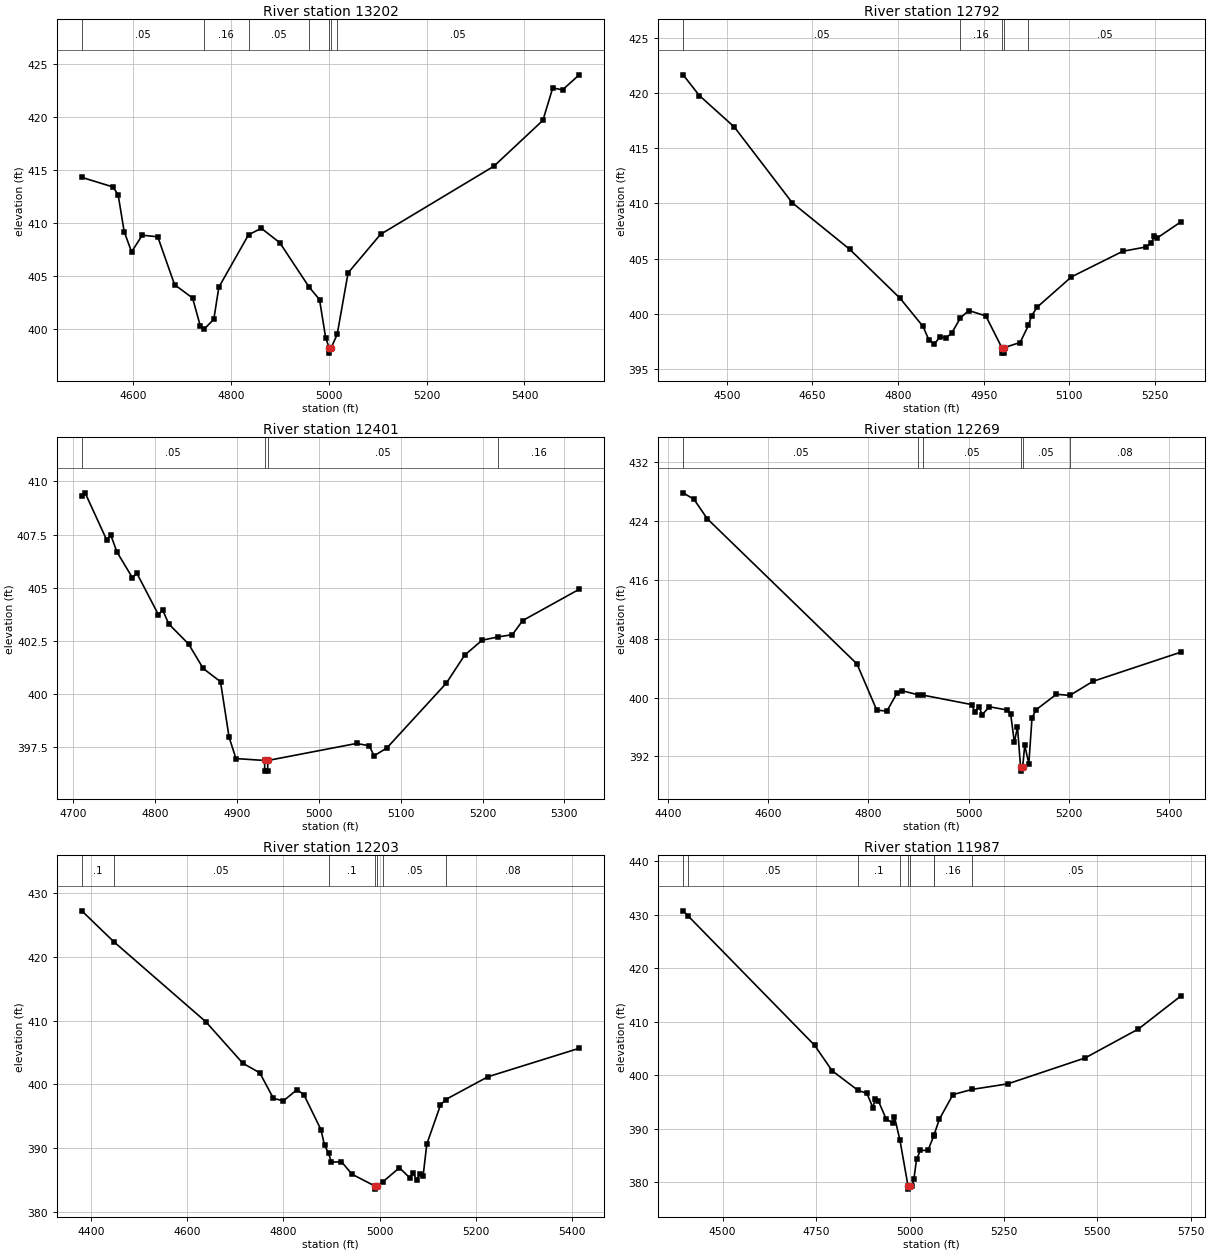
Type RM Length L Ch R = 1 ,13202   ,410,410,410
BEGIN DESCRIPTION:
DUCK CREEK TRIB 21 3 1
END DESCRIPTION:
XS GIS Cut Line= 3
      3527277.82      10418225.2      3526678.85     10417891.86
      3526348.09     10417912.69
#Sta/Elev= 30
    4495  414.28  4559.1  413.37  4569.4  412.61  4581.7  409.16  4596.8  407.26
  4618.6  408.83  4650.3  408.68  4684.7  404.17  4721.5  402.91  4737.5  400.24
  4744.7  399.96  4764.9  400.91  4775.2  403.93  4835.9  408.87  4862.1  409.48
  4899.8  408.12  4959.8  403.94    4981  402.77  4993.6  399.16  5000.8  398.22
    5001  397.72  5004.8  398.22  5017.1  399.48  5039.4  405.28  5105.7  408.91
  5337.5  415.33  5437.7  419.65  5457.8  422.71  5477.8  422.52  5511.9  423.94
#Mann= 7 ,-1 , 0
    4495     .05       0  4744.7     .16       0  4835.9     .05       0
  4959.8     .16       0  5000.8     .07       0  5004.8     .16       0
  5017.1     .05       0
Bank Sta=5000.8,5004.8
XS Rating Curve= 0 ,0
Exp/Cntr=0.3,0.1

Type RM Length L Ch R = 1 ,12792   ,391,391,391
BEGIN DESCRIPTION:
DUCK CREEK TRIB 21 3 0
END DESCRIPTION:
XS GIS Cut Line= 3
      3527452.32     10417503.82      3527194.47     10417631.44
       3526611.1     10417626.23
#Sta/Elev= 30
  4423.5  421.64    4452  419.76    4513  416.92  4614.6  410.05  4714.9  405.85
  4803.6  401.39  4843.6  398.85  4853.6  397.66  4863.6  397.27  4873.6  397.92
  4883.6  397.81  4893.6  398.22    4909  399.61  4923.6  400.29  4953.6   399.8
  4981.6  396.93  4981.8  396.43  4985.3  396.43  4985.6  396.93  5013.6  397.39
  5028.3  398.95  5033.6   399.8  5043.6   400.6  5103.6  403.34  5193.6  405.66
  5233.6  406.04  5243.6  406.42  5248.6  407.03  5253.6  406.86  5294.6   408.3
#Mann= 5 ,-1 , 0
  4423.5     .05       0    4909     .16       0  4981.6     .07       0
  4985.6     .16       0  5028.3     .05       0
Bank Sta=4981.6,4985.6
XS Rating Curve= 0 ,0
Exp/Cntr=0.3,0.1

Type RM Length L Ch R = 1 ,12401   ,132,132,132
BEGIN DESCRIPTION:
DUCK CREEK TRIB 21 21 0
END DESCRIPTION:
XS GIS Cut Line= 3
      3527232.91     10417166.07      3526932.93     10417266.06
      3526682.89     10417416.08
#Sta/Elev= 30
  4710.3  409.31  4714.3  409.46  4740.6  407.26  4745.9  407.46  4753.3  406.68
  4772.2  405.47  4777.5  405.69  4803.9  403.74  4809.1  403.96  4816.6   403.3
  4840.8  402.36  4858.7  401.21  4879.8  400.59  4890.3  397.98  4898.7  396.98
  4933.6  396.89  4933.9  396.39  4937.4  396.39  4937.6  396.89    5046  397.69
  5061.6  397.58  5067.4  397.11  5082.9  397.47  5155.7  400.52  5178.2  401.84
  5199.6  402.54  5218.8  402.69  5236.5   402.8    5249  403.46  5318.1  404.93
#Mann= 4 ,-1 , 0
  4710.3     .05       0  4933.6    .033       0  4937.6     .05       0
  5218.8     .16       0
Bank Sta=4933.6,4937.6
XS Rating Curve= 0 ,0
Exp/Cntr=0.3,0.1

Type RM Length L Ch R = 1 ,12269   ,66,66,66
BEGIN DESCRIPTION:
DUCK CREEK TRIB 21 22
END DESCRIPTION:
XS GIS Cut Line= 5
      3527483.56     10416988.21      3527046.03     10417063.73
      3526980.93     10417097.59      3526798.64     10417238.21
      3526603.33     10417389.25
#Sta/Elev= 30
  4429.4  427.81  4451.2  426.92  4477.8  424.28    4777  404.56  4816.5  398.29
  4836.8  398.15  4857.1  400.61  4867.2  400.92  4898.8  400.38  4909.2  400.32
  5006.4  399.04  5012.7  398.04  5020.9  398.77  5027.2  397.66  5041.7  398.75
  5077.1   398.3  5084.2  397.78  5091.6  393.94  5097.9  395.99  5104.1   390.5
  5104.3     390  5108.1   390.5  5112.4  393.49  5120.6  391.03  5126.9  397.21
  5134.7  398.32  5175.7  400.44  5202.6  400.29  5248.5  402.19  5423.9  406.15
#Mann= 6 ,-1 , 0
  4429.4     .05       0  4898.8      .1       0  4909.2     .05       0
  5104.1    .033       0  5108.1     .05       0  5202.6     .08       0
Bank Sta=5104.1,5108.1
XS Rating Curve= 0 ,0
Exp/Cntr=0.3,0.1

Type RM Length L Ch R = 1 ,12203   ,216,216,216
BEGIN DESCRIPTION:
Mapping XS 0f5fe55b
END DESCRIPTION:
XS GIS Cut Line= 3
      3527452.31     10416829.35      3527131.97     10416876.23
      3526598.11     10417344.98
#Sta/Elev= 30
  4380.8  427.21  4447.2  422.38  4638.5  409.84  4715.7  403.32  4750.8  401.83
  4779.3  397.81  4800.1  397.44  4828.6   399.2  4842.8  398.36    4878  392.93
  4885.5  390.47  4893.8  389.24  4899.8  387.82  4920.7   387.9  4942.5  385.94
  4989.8   384.1  4990.1   383.6  4993.8   384.1  5007.2  384.77  5041.2  386.95
    5063  385.35  5069.6   386.2    5077  384.99  5083.9  386.03  5090.5  385.67
  5098.1  390.65  5126.6  396.78  5137.2  397.63  5225.3  401.21    5415  405.67
#Mann= 7 ,-1 , 0
  4380.8      .1       0  4447.2     .05       0  4893.8      .1       0
  4989.8     .07       0  4993.8      .1       0  5007.2     .05       0
  5137.2     .08       0
Bank Sta=4989.8,4993.8
XS Rating Curve= 0 ,0
Exp/Cntr=0.3,0.1

Type RM Length L Ch R = 1 ,11987   ,710,710,710
BEGIN DESCRIPTION:
DUCK CREEK TRIB 21 23
END DESCRIPTION:
XS GIS Cut Line= 3
        3527494.     10416751.22      3526717.91     10416899.67
      3526299.61     10417237.43
#Sta/Elev= 30
  4394.6   430.7  4407.5  429.77  4745.3  405.58  4792.3   400.8  4861.4  397.14
  4885.2  396.57  4901.5  393.85  4906.6   395.6  4915.8  395.14  4936.1  391.87
  4953.6  390.98  4958.7  392.22  4973.3  387.84  4995.2  379.17  4995.5  378.67
  4999.2  379.17  5005.6  379.32  5010.7  380.59  5017.6  384.22  5027.8   385.9
  5048.1  385.93  5063.7  388.61  5064.2  388.78  5078.7  391.76  5114.9  396.34
  5165.6  397.31  5261.2  398.35  5467.5  403.19  5609.8   408.6  5722.4  414.73
#Mann= 9 ,-1 , 0
  4394.6      .1       0  4407.5     .05       0  4861.4      .1       0
  4973.3     .16       0  4995.2     .07       0  4999.2     .16       0
  5063.7      .1       0  5064.2     .16       0  5165.6     .05       0
Bank Sta=4995.2,4999.2
XS Rating Curve= 0 ,0
Exp/Cntr=0.3,0.1

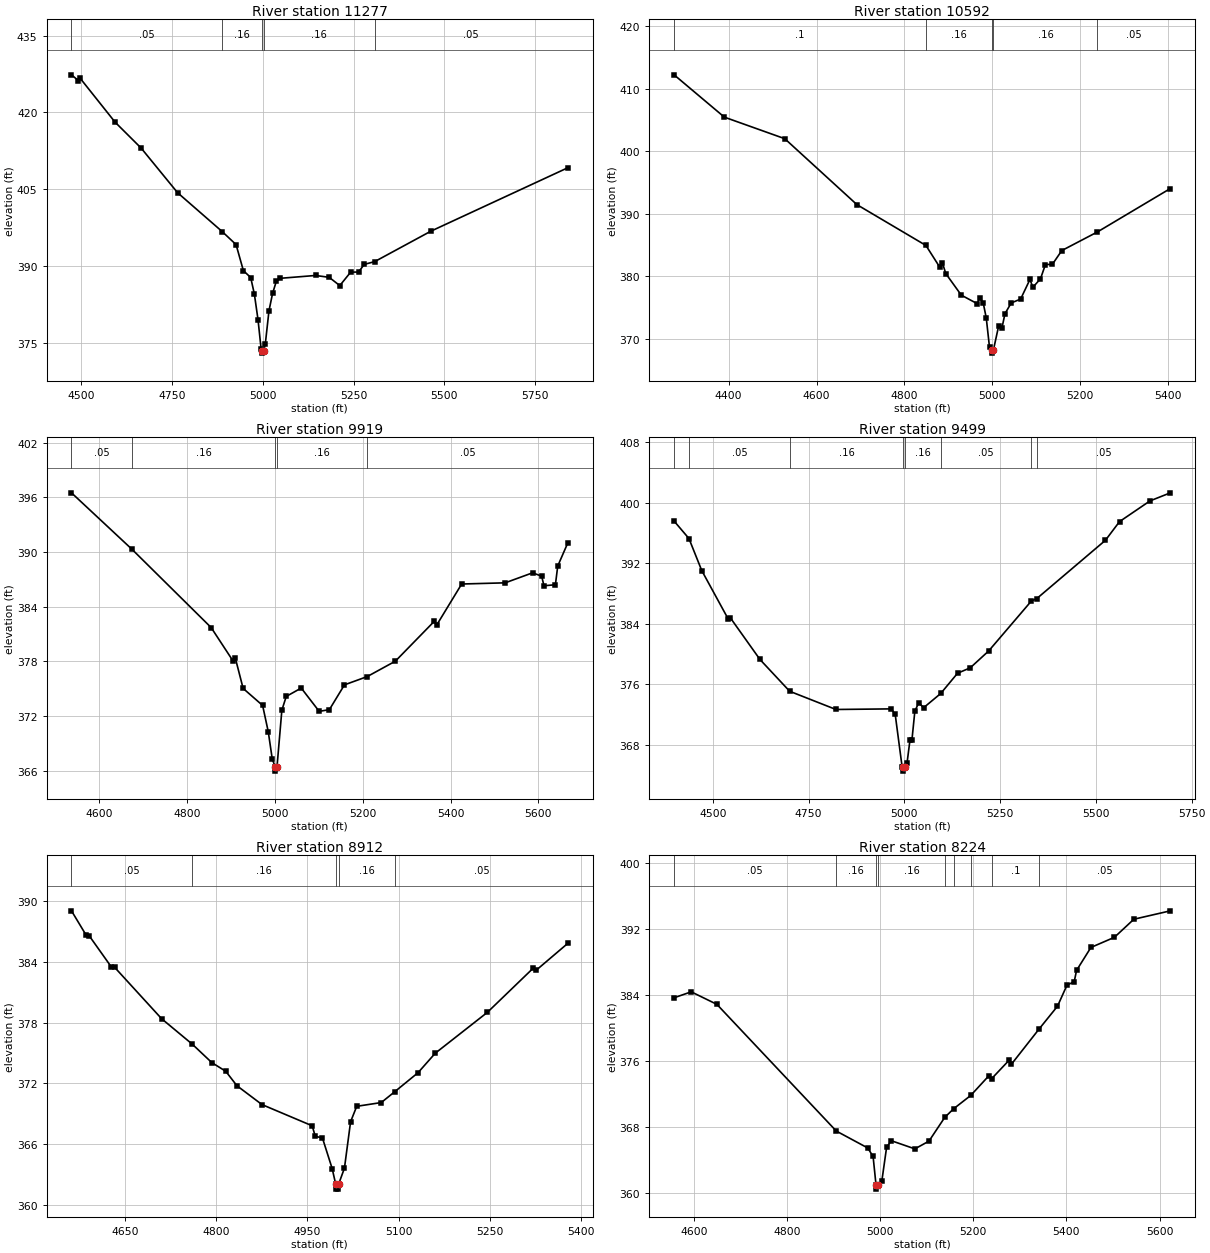
Type RM Length L Ch R = 1 ,11277   ,685,685,685
BEGIN DESCRIPTION:
DUCK CREEK TRIB 21 18 1
END DESCRIPTION:
XS GIS Cut Line= 3
      3527462.66     10416204.36       3526837.7     10416266.86
      3526197.06     10416631.45
#Sta/Elev= 30
  4474.1  427.34  4493.4  426.19  4498.4  426.63  4593.9   418.1  4665.6  413.03
  4766.1  404.29  4888.7   396.7  4926.9  394.15    4947  389.06  4967.1  387.72
  4977.2  384.49  4987.2  379.51  4995.9  373.71  4998.8  373.44  4999.1  372.94
  5002.9  373.44  5007.3  374.73  5017.4  381.22  5027.4  384.64  5037.5  386.95
  5047.5  387.56  5145.5  388.12    5183  387.76  5212.2  386.14  5242.1  388.77
  5263.7  388.79  5279.6  390.29    5308  390.82  5462.6  396.77  5839.3  409.17
#Mann= 5 ,-1 , 0
  4474.1     .05       0  4888.7     .16       0  4998.8     .07       0
  5002.9     .16       0    5308     .05       0
Bank Sta=4998.8,5002.9
XS Rating Curve= 0 ,0
Exp/Cntr=0.3,0.1

Type RM Length L Ch R = 1 ,10592   ,673,673,673
BEGIN DESCRIPTION:
DUCK CREEK TRIB 21 18 0
END DESCRIPTION:
XS GIS Cut Line= 4
      3527101.44     10415381.81      3526558.93     10415755.05
      3526441.75     10415885.26      3526294.19     10416141.31
#Sta/Elev= 30
  4275.8  412.25  4390.2  405.47  4527.6  402.02  4691.9  391.45  4848.8  384.92
    4880  381.47  4886.1  382.18    4894  380.41  4929.3  376.96  4965.1  375.61
  4971.9  376.55  4979.3  375.68  4986.1   373.3  4993.5   368.6  4998.1  368.17
  4998.4  367.67  5002.4  368.17  5014.5  372.09  5021.9  371.74  5028.7  373.99
  5042.9  375.71  5064.3  376.33  5085.5  379.47  5092.2  378.22  5109.5  379.58
  5120.7  381.86  5136.5  381.89    5158   384.1    5239  387.08    5405  394.04
#Mann= 5 ,-1 , 0
  4275.8      .1       0  4848.8     .16       0  4998.1     .07       0
  5002.4     .16       0    5239     .05       0
Bank Sta=4998.1,5002.4
XS Rating Curve= 0 ,0
Exp/Cntr=0.3,0.1

Type RM Length L Ch R = 1 ,9919    ,420,420,420
BEGIN DESCRIPTION:
DUCK CREEK TRIB 21 17 0
END DESCRIPTION:
XS GIS Cut Line= 4
      3526606.83     10415267.51       3526290.9     10415264.04
      3525922.84     10415428.97      3525789.35     10415817.29
#Sta/Elev= 30
  4536.9  396.51  4675.1  390.29  4854.9  381.72  4904.5  378.07    4910  378.36
  4927.7  375.04  4972.1  373.17    4985  370.27    4994   367.3  5000.5  366.46
  5000.8  365.96  5004.9  366.46  5015.9  372.65  5025.9  374.16    5060  375.08
  5100.9  372.52  5124.1  372.71  5158.4  375.43  5210.3  376.34  5274.3  378.03
  5362.8   382.4  5368.1  381.97  5425.3   386.5  5524.3  386.63  5586.8  387.73
  5607.4  387.36  5612.7  386.31  5638.7  386.42    5644  388.47  5666.8     391
#Mann= 5 ,-1 , 0
  4536.9     .05       0  4675.1     .16       0  5000.5     .07       0
  5004.9     .16       0  5210.3     .05       0
Bank Sta=5000.5,5004.9
XS Rating Curve= 0 ,0
Exp/Cntr=0.3,0.1

Type RM Length L Ch R = 1 ,9499    ,587,587,587
BEGIN DESCRIPTION:
DUCK CREEK TRIB 21 16 0
END DESCRIPTION:
XS GIS Cut Line= 4
      3526442.12     10414941.64      3525842.11     10415091.64
      3525542.11     10415141.64      3525223.18     10415335.22
#Sta/Elev= 30
  4398.7  397.59  4437.5  395.28  4470.9  391.04  4540.5  384.58  4545.6  384.78
  4622.9  379.27  4700.5  375.06  4821.3  372.65  4965.6  372.73    4976     372
    4994  365.07  4996.7  364.99  4997.1  364.49  5001.6  364.99  5006.9  365.56
  5014.6  368.62  5019.7  368.62  5027.3  372.43  5037.5  373.55  5050.1  372.88
  5094.9  374.77  5138.8  377.45  5171.8  378.16  5219.9  380.39  5331.7  387.02
  5345.9  387.34  5524.9  395.05  5561.7  397.52  5641.2  400.26  5694.4  401.33
#Mann= 8 ,-1 , 0
  4398.7     .16       0  4437.5     .05       0  4700.5     .16       0
  4996.7     .07       0  5001.6     .16       0  5094.9     .05       0
  5331.7     .16       0  5345.9     .05       0
Bank Sta=4996.7,5001.6
XS Rating Curve= 0 ,0
Exp/Cntr=0.3,0.1

Type RM Length L Ch R = 1 ,8912    ,688,688,688
BEGIN DESCRIPTION:
DUCK CREEK TRIB 21 14 0
END DESCRIPTION:
XS GIS Cut Line= 3
      3526328.02     10414623.25      3525928.04     10414523.25
      3525528.04     10414573.25
#Sta/Elev= 30
  4562.3  389.01  4586.7  386.58  4591.8  386.52  4627.9  383.47  4633.1  383.45
  4710.4  378.38  4760.8  375.87  4792.8  374.06  4815.8   373.2  4834.1  371.78
  4875.3  369.92  4957.8  367.83  4962.9  366.79  4974.6  366.64  4990.6  363.62
  4996.4  362.09  4996.7  361.59  5000.9  361.59  5001.3  362.09  5010.8  363.66
  5020.9  368.23    5031  369.75  5071.3  370.12  5093.7   371.2  5131.7  373.06
    5160  374.98  5245.7  379.01  5321.3  383.38  5326.3  383.18  5377.7   385.8
#Mann= 5 ,-1 , 0
  4562.3     .05       0  4760.8     .16       0  4996.4     .07       0
  5001.3     .16       0  5093.7     .05       0
Bank Sta=4996.4,5001.3
XS Rating Curve= 0 ,0
Exp/Cntr=0.3,0.1

Type RM Length L Ch R = 1 ,8224    ,514,514,514
BEGIN DESCRIPTION:
DUCK CREEK TRIB 21 13 0
END DESCRIPTION:
XS GIS Cut Line= 3
      3526342.87     10413982.46      3525724.82     10413885.23
      3525295.68     10413982.14
#Sta/Elev= 30
  4557.6  383.67  4594.4  384.39  4649.5  382.87  4905.9  367.51  4973.4  365.46
  4984.9  364.43  4991.2  360.97  4991.6  360.47  4996.2  360.97  5003.8   361.5
  5013.9  365.54    5024  366.34  5074.6  365.35  5104.9  366.29  5138.8  369.17
    5158  370.22  5194.6  371.83  5233.6  374.22  5239.8  373.88  5276.8  376.09
  5281.9  375.61    5342  379.93  5380.8  382.64  5401.3  385.21  5416.7  385.61
  5421.8  386.99  5452.6  389.77  5503.1     391  5544.8  393.19  5623.2  394.21
#Mann= 9 ,-1 , 0
  4557.6     .05       0  4905.9     .16       0  4991.2     .07       0
  4996.2     .16       0  5138.8     .05       0    5158     .16       0
  5194.6     .05       0  5239.8      .1       0    5342     .05       0
Bank Sta=4991.2,4996.2
XS Rating Curve= 0 ,0
Exp/Cntr=0.3,0.1

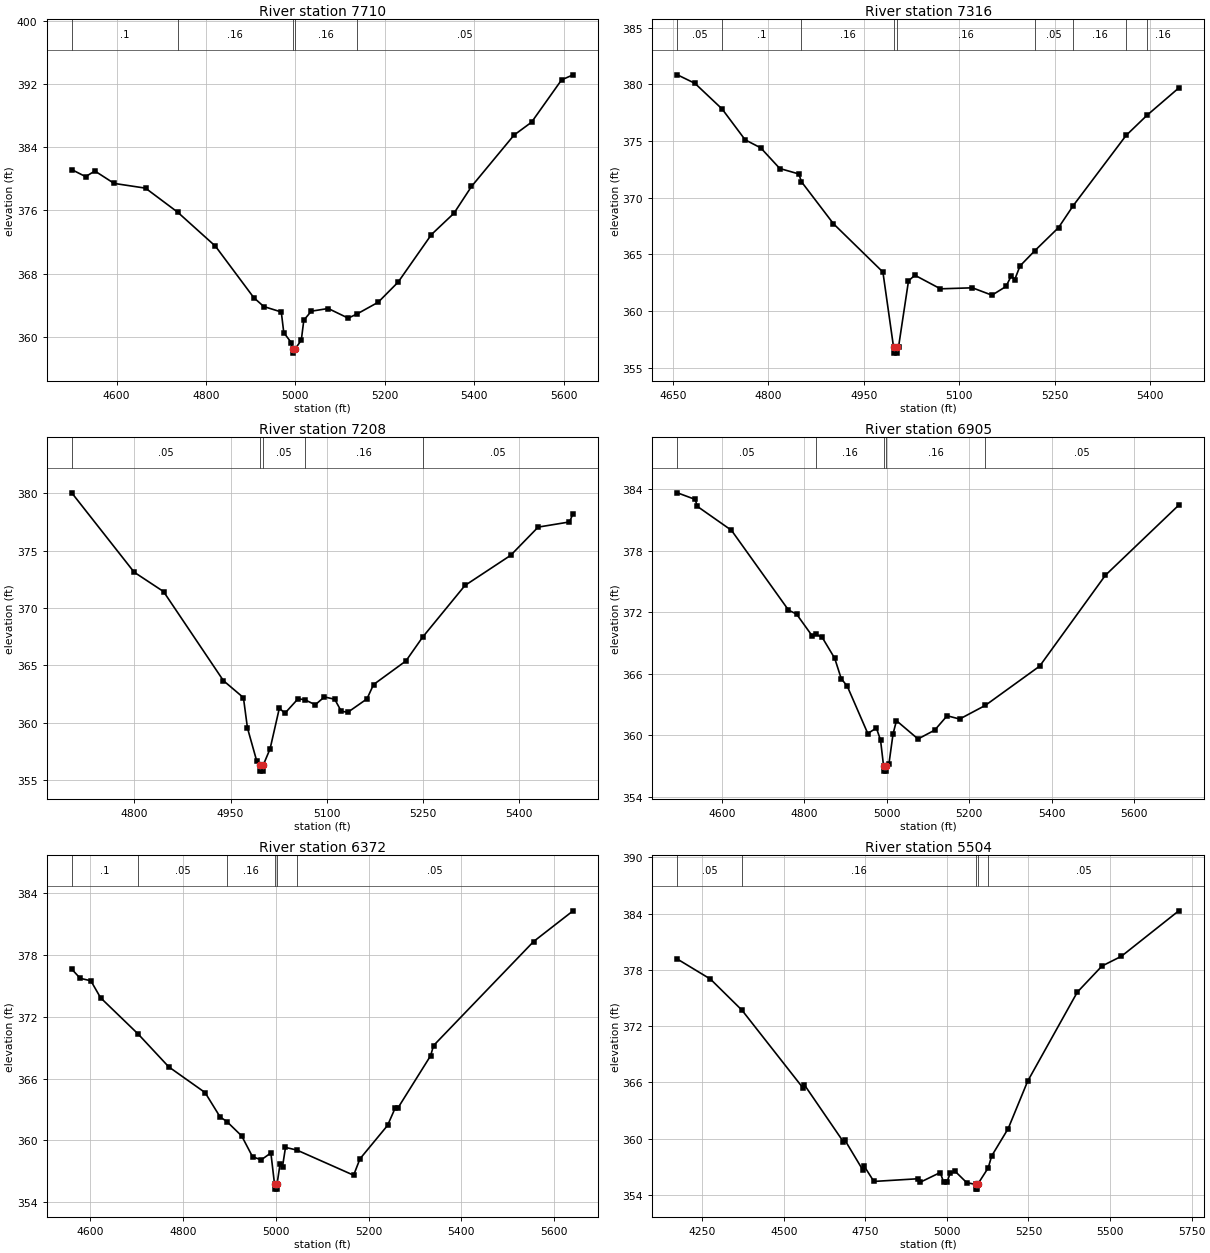
Type RM Length L Ch R = 1 ,7710    ,394,394,394
BEGIN DESCRIPTION:
DUCK CREEK TRIB 21 10
END DESCRIPTION:
XS GIS Cut Line= 3
      3526289.15     10413135.58      3526051.31     10413423.76
      3525381.63     10413756.86
#Sta/Elev= 30
  4499.7  381.16  4530.7  380.27  4551.5  380.98  4594.5  379.41  4664.8  378.81
  4736.4  375.78  4821.2  371.46  4906.9  364.95  4929.3  363.82  4968.5  363.13
  4974.1  360.51  4990.9  359.25  4993.8  358.42  4994.2  357.92  4999.2  358.42
  5013.3  359.57  5018.9  362.09  5035.7  363.23  5073.5  363.57  5118.2  362.35
  5138.3  362.89  5185.2  364.36  5229.9  366.91  5304.5  372.94  5354.8  375.63
    5394  379.02  5489.2  385.53  5528.4  387.16  5595.6  392.52  5621.3  393.16
#Mann= 5 ,-1 , 0
  4499.7      .1       0  4736.4     .16       0  4993.8     .07       0
  4999.2     .16       0  5138.3     .05       0
Bank Sta=4993.8,4999.2
XS Rating Curve= 0 ,0
Exp/Cntr=0.3,0.1

Type RM Length L Ch R = 1 ,7316    ,108,108,108
BEGIN DESCRIPTION:
DUCK CREEK TRIB 21 17
END DESCRIPTION:
XS GIS Cut Line= 4
      3526185.41     10413077.74      3525921.07     10413180.61
      3525717.94     10413200.14      3525445.79     10413325.85
#Sta/Elev= 30
  4657.2  380.84  4684.7  380.09  4727.4  377.83  4763.6  375.11  4788.1   374.4
    4818  372.58  4847.9   372.1  4852.1  371.41  4902.3  367.71    4980  363.45
  4996.8   356.8  4997.2   356.3  5001.7   356.3  5002.2   356.8  5004.5  356.82
  5020.2  362.67  5030.2  363.17  5070.4  361.97  5120.6  362.06  5151.3  361.41
  5173.4  362.18  5181.6  363.11  5187.1  362.79  5195.4  363.99  5218.6  365.33
  5255.9  367.37    5279  369.31  5361.9  375.49  5394.6  377.26  5444.7  379.68
#Mann= 9 ,-1 , 0
  4657.2     .05       0  4727.4      .1       0  4852.1     .16       0
  4996.8     .07       0  5002.2     .16       0  5218.6     .05       0
    5279     .16       0  5361.9     .05       0  5394.6     .16       0
Bank Sta=4996.8,5002.2
XS Rating Curve= 0 ,0
Exp/Cntr=0.3,0.1

Type RM Length L Ch R = 1 ,7208    ,303,303,303
BEGIN DESCRIPTION:
DUCK CREEK TRIB 21 8 1
END DESCRIPTION:
XS GIS Cut Line= 5
       3526092.9      10412976.2      3525852.06     10413068.63
      3525768.72     10413132.43      3525480.96      10413172.8
      3525361.14     10413218.38
#Sta/Elev= 30
  4702.4  380.05  4799.7  373.13  4845.5  371.44  4938.9  363.67  4970.1  362.19
  4976.4  359.54  4990.9  356.65  4995.4  356.28  4995.8  355.78  5000.3  355.78
  5000.8  356.28  5011.7  357.73  5026.2  361.29  5034.5  360.81  5055.3  362.09
  5065.6  362.01  5082.1  361.57  5096.4  362.25  5112.4  362.05  5122.5  361.02
  5132.6   360.9  5162.7  362.08    5173  363.33  5223.5  365.39  5249.6  367.47
  5315.5  371.97  5386.8   374.6  5429.6  377.06  5478.5  377.51  5484.1  378.24
#Mann= 5 ,-1 , 0
  4702.4     .05       0  4995.4     .03       0  5000.8     .05       0
  5065.6     .16       0  5249.6     .05       0
Bank Sta=4995.4,5000.8
XS Rating Curve= 0 ,0
Exp/Cntr=0.3,0.1

Type RM Length L Ch R = 1 ,6905    ,533,533,533
BEGIN DESCRIPTION:
DUCK CREEK TRIB 21 8 0
END DESCRIPTION:
XS GIS Cut Line= 3
      3526226.68     10412930.71      3525914.16     10412826.54
      3525035.84     10412956.47
#Sta/Elev= 30
  4491.6  383.62  4534.7  382.98    4540   382.3  4622.9  379.97  4761.3  372.21
    4781  371.81  4819.3  369.67    4828  369.86  4843.3  369.54  4873.6  367.51
  4889.4  365.53    4904   364.8  4953.9  360.19  4974.7  360.73  4984.8  359.56
  4992.2  357.03  4992.7  356.53  4997.2  356.53  4997.6  357.03  5005.1   357.2
  5015.2  360.15  5023.5  361.44  5075.8  359.66  5116.3  360.52  5146.6  361.92
  5176.9   361.6  5239.3  362.93  5371.2  366.75  5530.7  375.59  5708.9  382.42
#Mann= 5 ,-1 , 0
  4491.6     .05       0    4828     .16       0  4992.2     .07       0
  4997.6     .16       0  5239.3     .05       0
Bank Sta=4992.2,4997.6
XS Rating Curve= 0 ,0
Exp/Cntr=0.3,0.1

Type RM Length L Ch R = 1 ,6372    ,868,868,868
BEGIN DESCRIPTION:
DUCK CREEK TRIB 21 7 1
END DESCRIPTION:
XS GIS Cut Line= 3
       3526011.4     10412250.14      3525346.45     10412460.22
      3525036.43     10412685.37
#Sta/Elev= 30
  4560.4  376.63  4578.7  375.74  4601.6   375.5  4622.6  373.85  4703.6  370.33
  4769.4  367.15  4847.8  364.65  4880.1  362.29  4894.7  361.84  4926.7  360.44
    4950  358.43  4968.7  358.12  4989.6  358.79  4997.4  355.78  4997.8  355.28
  5002.5  355.28  5002.9  355.78  5009.4  357.72  5014.7  357.47  5021.1  359.33
  5045.7  359.07  5167.9  356.63  5181.6  358.22    5241  361.46  5257.4  363.14
  5263.2  363.14  5333.9  368.23  5340.1  369.21  5555.8  379.31  5640.9  382.29
#Mann= 6 ,-1 , 0
  4560.4      .1       0  4703.6     .05       0  4894.7     .16       0
  4997.4     .07       0  5002.9     .16       0  5045.7     .05       0
Bank Sta=4997.4,5002.9
XS Rating Curve= 0 ,0
Exp/Cntr=0.3,0.1

Type RM Length L Ch R = 1 ,5504    ,244,244,244
BEGIN DESCRIPTION:
Mapping XS 67daf5fe
END DESCRIPTION:
XS GIS Cut Line= 4
      3526107.74     10411751.71      3525680.65     10411605.88
      3525131.17     10411704.83      3524670.23     10411960.05
#Sta/Elev= 30
    4174  379.15  4275.1  377.02  4371.9   373.7  4558.1  365.44  4563.3  365.73
  4682.9  359.65    4688   359.8  4741.6  356.69  4746.6  357.05  4776.2  355.43
  4912.6  355.72  4918.5  355.35  4979.5  356.38  4989.6  355.39  4999.8  355.35
  5009.9  356.28  5024.9  356.52  5060.7   355.3  5088.4  355.11  5088.9  354.61
  5093.6  354.61    5094  355.11  5126.6  356.88  5137.2  358.15  5187.8  361.07
  5247.4  366.12  5399.7  375.63  5475.2  378.41  5534.7  379.45  5710.5   384.3
#Mann= 5 ,-1 , 0
    4174     .05       0  4371.9     .16       0  5088.4     .07       0
    5094     .16       0  5126.6     .05       0
Bank Sta=5088.4,5094
XS Rating Curve= 0 ,0
Exp/Cntr=0.3,0.1

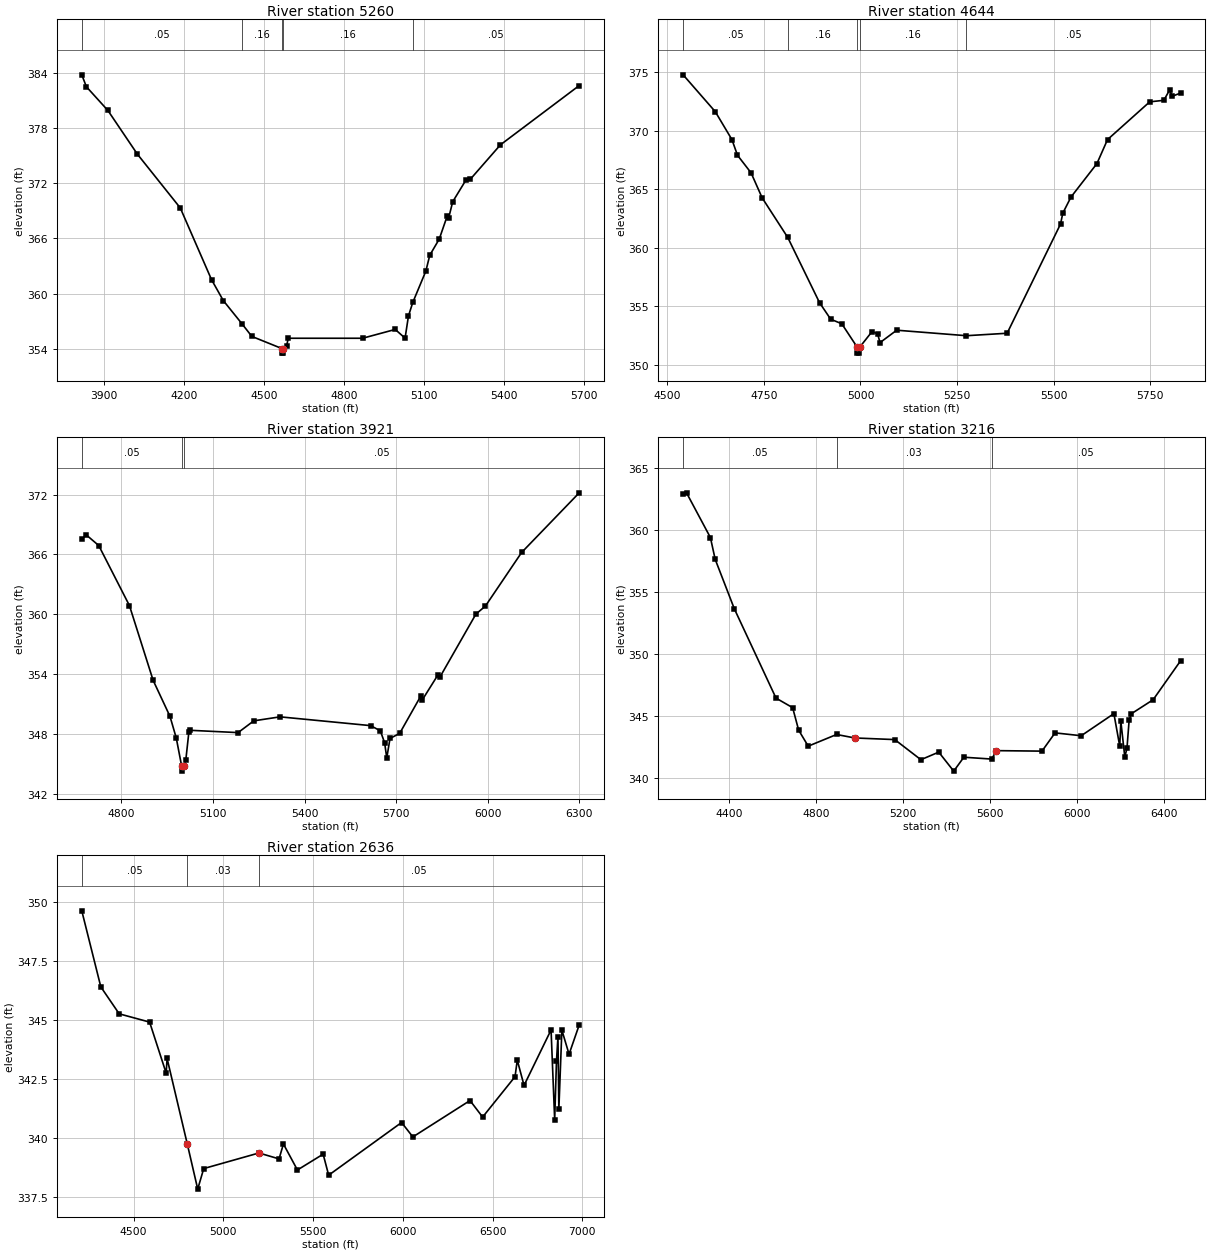
Type RM Length L Ch R = 1 ,5260    ,616,616,616
BEGIN DESCRIPTION:
DUCK CREEK TRIB 21 7 0
END DESCRIPTION:
XS GIS Cut Line= 4
      3526209.35     10410975.66      3525816.07     10411017.33
      3525000.97     10411600.67      3524617.12     10411866.63
#Sta/Elev= 30
  3815.6  383.82  3832.9  382.52  3913.4  379.94    4024  375.18  4184.9  369.32
    4302  361.51  4346.2  359.23    4416  356.71  4453.1  355.33  4565.7  354.01
  4566.2  353.51  4570.9  353.51  4571.4  354.01  4583.3  354.26  4589.5  355.13
  4868.3  355.13  4990.7  356.09  5027.6  355.14  5040.3  357.56  5056.5  359.03
  5105.4  362.44  5120.2  364.17  5155.8  365.94  5185.3  368.42  5191.4  368.28
  5206.2     370  5256.8  372.41  5271.7  372.43  5385.2   376.2  5680.4  382.65
#Mann= 5 ,-1 , 0
  3815.6     .05       0    4416     .16       0  4565.7     .07       0
  4571.4     .16       0  5056.5     .05       0
Bank Sta=4565.7,4571.4
XS Rating Curve= 0 ,0
Exp/Cntr=0.3,0.1

Type RM Length L Ch R = 1 ,4644    ,723,723,723
BEGIN DESCRIPTION:
DUCK CREEK TRIB 21 4 0
END DESCRIPTION:
XS GIS Cut Line= 3
      3525675.42     10410637.14      3525076.49     10411126.71
      3524803.04     10411561.63
#Sta/Elev= 30
  4541.1  374.78  4624.3  371.63  4667.4  369.24  4681.8   367.9  4716.9   366.4
  4745.6  364.26  4811.9  360.87  4894.2  355.29    4923  353.88  4951.7  353.49
  4991.7  351.48  4992.2  350.98  4997.4  350.98  4997.9  351.48  5029.9  352.82
  5044.3  352.64  5050.7  351.88  5093.8  352.94  5274.2  352.47  5379.6  352.68
  5517.8  362.02  5523.7  362.95  5544.9  364.33    5612  367.19  5639.4  369.24
  5748.6  372.47  5785.1   372.6  5800.4   373.5  5806.3  372.94  5828.4  373.22
#Mann= 5 ,-1 , 0
  4541.1     .05       0  4811.9     .16       0  4991.7     .07       0
  4997.9     .16       0  5274.2     .05       0
Bank Sta=4991.7,4997.9
XS Rating Curve= 0 ,0
Exp/Cntr=0.3,0.1

Type RM Length L Ch R = 1 ,3921    ,705,705,705
BEGIN DESCRIPTION:
DUCK CREEK TRIB 21 5 0
END DESCRIPTION:
XS GIS Cut Line= 4
      3525287.23     10410287.17      3525052.86     10410313.21
       3524891.4     10410360.09      3524485.14     10411516.35
#Sta/Elev= 30
  4670.1  367.54  4685.3  367.95  4725.6   366.9  4826.2  360.88  4903.8  353.39
    4959  349.78  4979.6  347.61  4997.3  344.79  4997.8  344.29  5003.6  344.79
  5010.8  345.38  5020.9  348.21  5026.1  348.38  5182.2  348.15  5233.6  349.33
  5319.5  349.73  5616.3  348.85  5648.1  348.33  5662.1  347.14  5669.2  345.61
  5679.8  347.56  5711.6  348.08  5780.7  351.82    5786  351.45  5837.4  353.96
  5842.7  353.68  5961.3  360.03  5992.3  360.83  6110.9   366.2  6299.6  372.18
#Mann= 3 ,-1 , 0
  4670.1     .05       0  4997.3     .03       0  5003.6     .05       0
Bank Sta=4997.3,5003.6
XS Rating Curve= 0 ,0
Exp/Cntr=0.3,0.1

Type RM Length L Ch R = 1 ,3216    ,580,580,580
BEGIN DESCRIPTION:
DUCK CREEK TRIB 21 9 0
END DESCRIPTION:
XS GIS Cut Line= 4
      3525287.42     10410105.87      3524665.03     10409772.54
      3524141.59     10410053.79      3524191.03     10411037.41
#Sta/Elev= 30
  4190.1  362.85  4205.7  362.97  4315.4  359.37  4337.3  357.62  4425.1  353.64
  4616.8  346.44  4693.2  345.67  4720.8  343.86  4764.7  342.57    4895  343.51
  4978.9  343.23  5162.3   343.1  5282.4  341.48  5364.4  342.09  5433.2  340.56
  5479.7  341.68  5608.3  341.53  5628.4  342.21  5838.6  342.17  5898.7  343.64
  6018.9  343.41    6169  345.19  6195.9  342.57  6200.9  344.58  6219.1   341.7
  6229.1   342.4  6239.1  344.68  6249.1  345.18  6349.3  346.31  6475.2  349.44
#Mann= 3 ,-1 , 0
  4190.1     .05       0    4895     .03       0  5608.3     .05       0
Bank Sta=4978.9,5628.4
XS Rating Curve= 0 ,0
Exp/Cntr=0.3,0.1

Type RM Length L Ch R = 1 ,2636    ,0,0,0
BEGIN DESCRIPTION:
DUCK CREEK TRIB 21 4 1
END DESCRIPTION:
XS GIS Cut Line= 4
      3525495.71     10409348.05      3525058.26     10409251.71
       3524146.8     10409452.23      3524027.21     10410837.89
#Sta/Elev= 30
    4211  349.62  4317.1   346.4  4419.5  345.26    4589  344.91  4681.2  342.75
  4686.4  343.37  4798.3  339.77  4857.1  337.84  4890.5  338.71  5198.3  339.37
  5310.3  339.12  5334.7  339.75  5412.7  338.65    5556  339.32  5586.8  338.43
  5993.1  340.66  6056.1  340.05  6374.5  341.59  6444.8  340.89  6625.4   342.6
  6637.9   343.3  6675.6  342.23  6826.2  344.58  6846.3  340.78  6856.3  343.25
  6864.6  344.29  6869.6  341.22  6886.4  344.57  6926.5  343.55    6983  344.79
#Mann= 3 , 0 , 0
    4211     .05       0  4798.3     .03       0  5198.3     .05       0
Bank Sta=4798.3,5198.3
XS Rating Curve= 0 ,0
Exp/Cntr=0.3,0.1

Chan Stop Cuts=-1
Use User Specified Reach Order=0
Composite Channel Slope=5