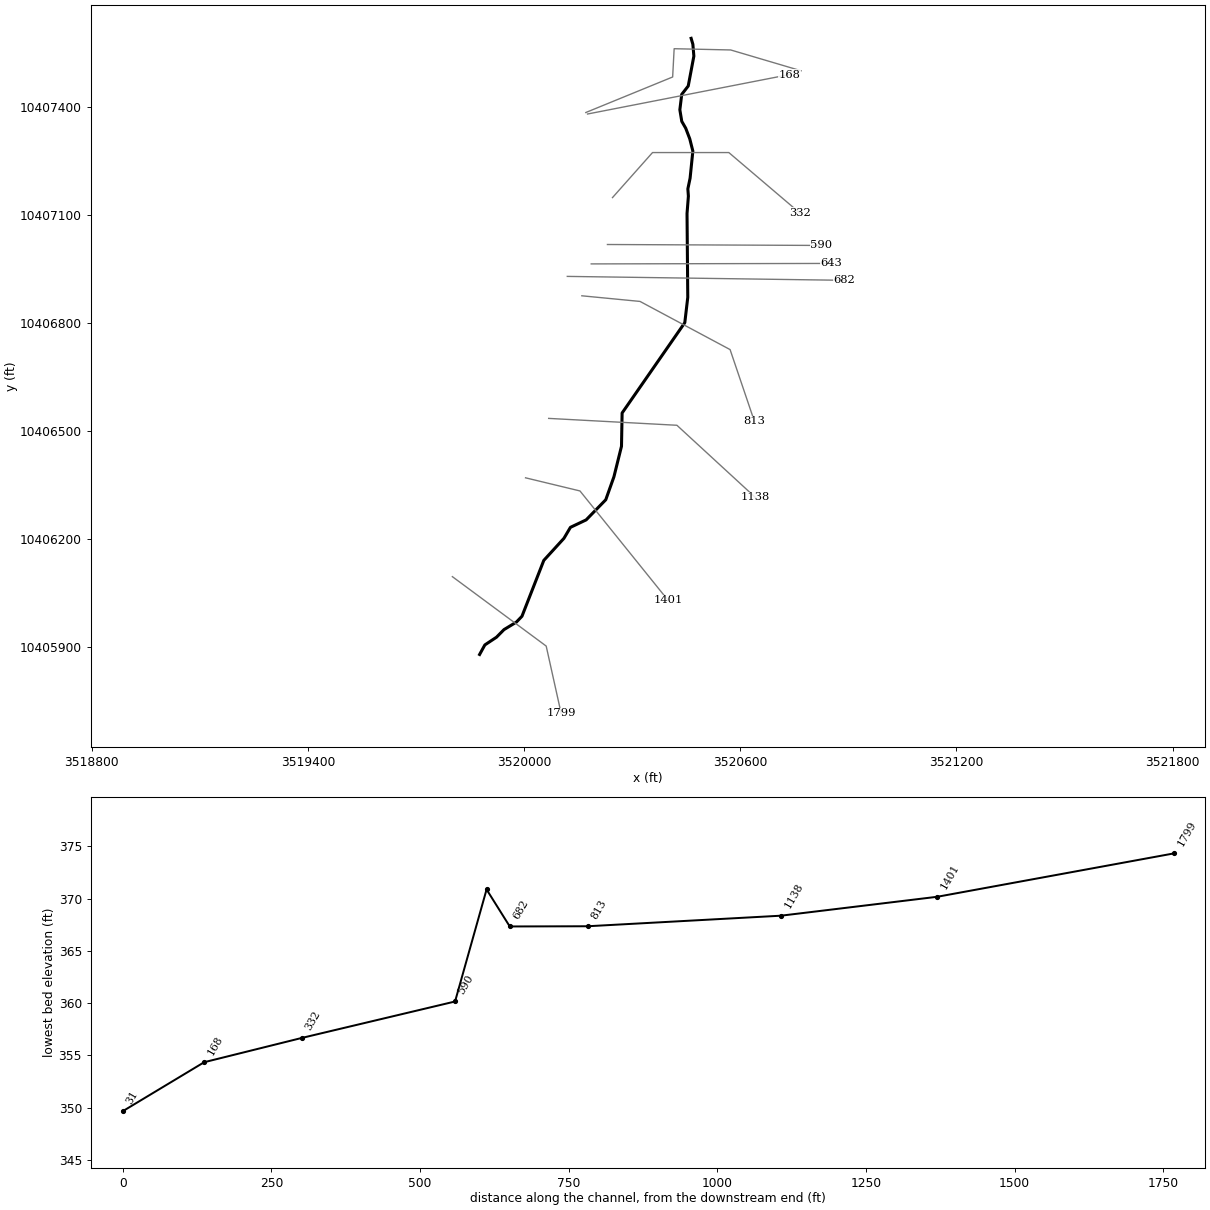
--- DUCK CREEK TRIB 22 1.prj (project) ---

Proj Title=DUCK CREEK TRIB 22 1 Base Level Engineering
Current Plan=p01
Default Exp/Contr=0.3,0.1
English Units
Geom File=g01
Flow File=f01
Plan File=p01
Y Axis Title=Elevation
X Axis Title(PF)=Main Channel Distance
X Axis Title(XS)=Station
BEGIN DESCRIPTION:
DUCK CREEK TRIB 22 1
END DESCRIPTION:
DSS Export Rating Curves= 0
DSS Export Rating Curve Sorted= 0
DSS Export Volume Flow Curves= 0
DXF OffsetX= 0
DXF OffsetY= 0
DXF ScaleX= 1
DXF ScaleY= 10

--- DUCK CREEK TRIB 22 1.p01 (plan) ---

Plan Title=Multiple Run
Short Identifier=Multiple
Geom File=g01
Flow File=f01
Subcritical Flow
K Sum by GR= 0
Std Step Tol= 0.01
Critical Tol= 0.01
Num of Std Step Trials= 20
Max Error Tol= 0.3
Flow Tol Ratio= 0.001
Split Flow NTrial= 30
Split Flow Tol= 0.02
Split Flow Ratio= 0.02
Log Output Level= 0
Friction Slope Method= 1
Unsteady Friction Slope Method= 2
Unsteady Bridges Friction Slope Method= 1
Parabolic Critical Depth
Global Vel Dist=  1 , 1 , 1
Global Log Level= 0
CheckData=True
Encroach Param= -1, 0, 0, 0
BEGIN DESCRIPTION:
Multiple Run
END DESCRIPTION:

--- DUCK CREEK TRIB 22 1.f01 (steady flow) ---

Flow Title=Multiple
Program Version=4.10
Number of Profiles= 7
Profile Names=10-year,25-year,50-year,1pct_min,100-year,1pct_plu,500-year
River Rch & RM=DUCK CREEK TRIB,Reach-1         ,1799
     464     621     747     660     893    1208    1268
Boundary for River Rch & Prof#=DUCK CREEK TRIB,Reach-1         , 1
Up Type= 0
Dn Type= 3
Dn Slope=0.013
Boundary for River Rch & Prof#=DUCK CREEK TRIB,Reach-1         , 2
Up Type= 0
Dn Type= 3
Dn Slope=0.013
Boundary for River Rch & Prof#=DUCK CREEK TRIB,Reach-1         , 3
Up Type= 0
Dn Type= 3
Dn Slope=0.013
Boundary for River Rch & Prof#=DUCK CREEK TRIB,Reach-1         , 4
Up Type= 0
Dn Type= 3
Dn Slope=0.013
Boundary for River Rch & Prof#=DUCK CREEK TRIB,Reach-1         , 5
Up Type= 0
Dn Type= 3
Dn Slope=0.013
Boundary for River Rch & Prof#=DUCK CREEK TRIB,Reach-1         , 6
Up Type= 0
Dn Type= 3
Dn Slope=0.013
Boundary for River Rch & Prof#=DUCK CREEK TRIB,Reach-1         , 7
Up Type= 0
Dn Type= 3
Dn Slope=0.013
DSS Import GetInterval= 0
DSS Import GetPeak= 0
DSS Import FillOption= 0

--- DUCK CREEK TRIB 22 1.g01 (geometry) ---

Geom Title=Existing Conditions
Program Version=4.10

River Reach=DUCK CREEK TRIB ,Reach-1
Reach XY= 30
       3519876.4     10405879.43        3519891.     10405905.96
      3519923.33     10405927.42       3519944.1     10405948.46
      3519978.48     10405969.32      3519993.99     10405985.48
      3520054.62     10406140.61      3520110.52     10406201.81
      3520128.53     10406232.33      3520172.18     10406253.04
       3520226.6     10406308.91      3520249.31      10406372.8
      3520270.26     10406457.41        3520272.     10406549.75
      3520445.97     10406800.45      3520454.22      10406870.8
      3520452.16     10407103.22      3520455.95     10407151.66
      3520454.46     10407171.77      3520460.68     10407201.54
      3520468.32     10407276.71      3520459.78     10407310.57
      3520448.53     10407340.12      3520437.56     10407359.22
      3520432.25     10407391.34      3520437.46     10407434.05
      3520455.51     10407457.31      3520471.14      10407540.3
      3520468.36     10407573.28      3520463.55     10407589.62

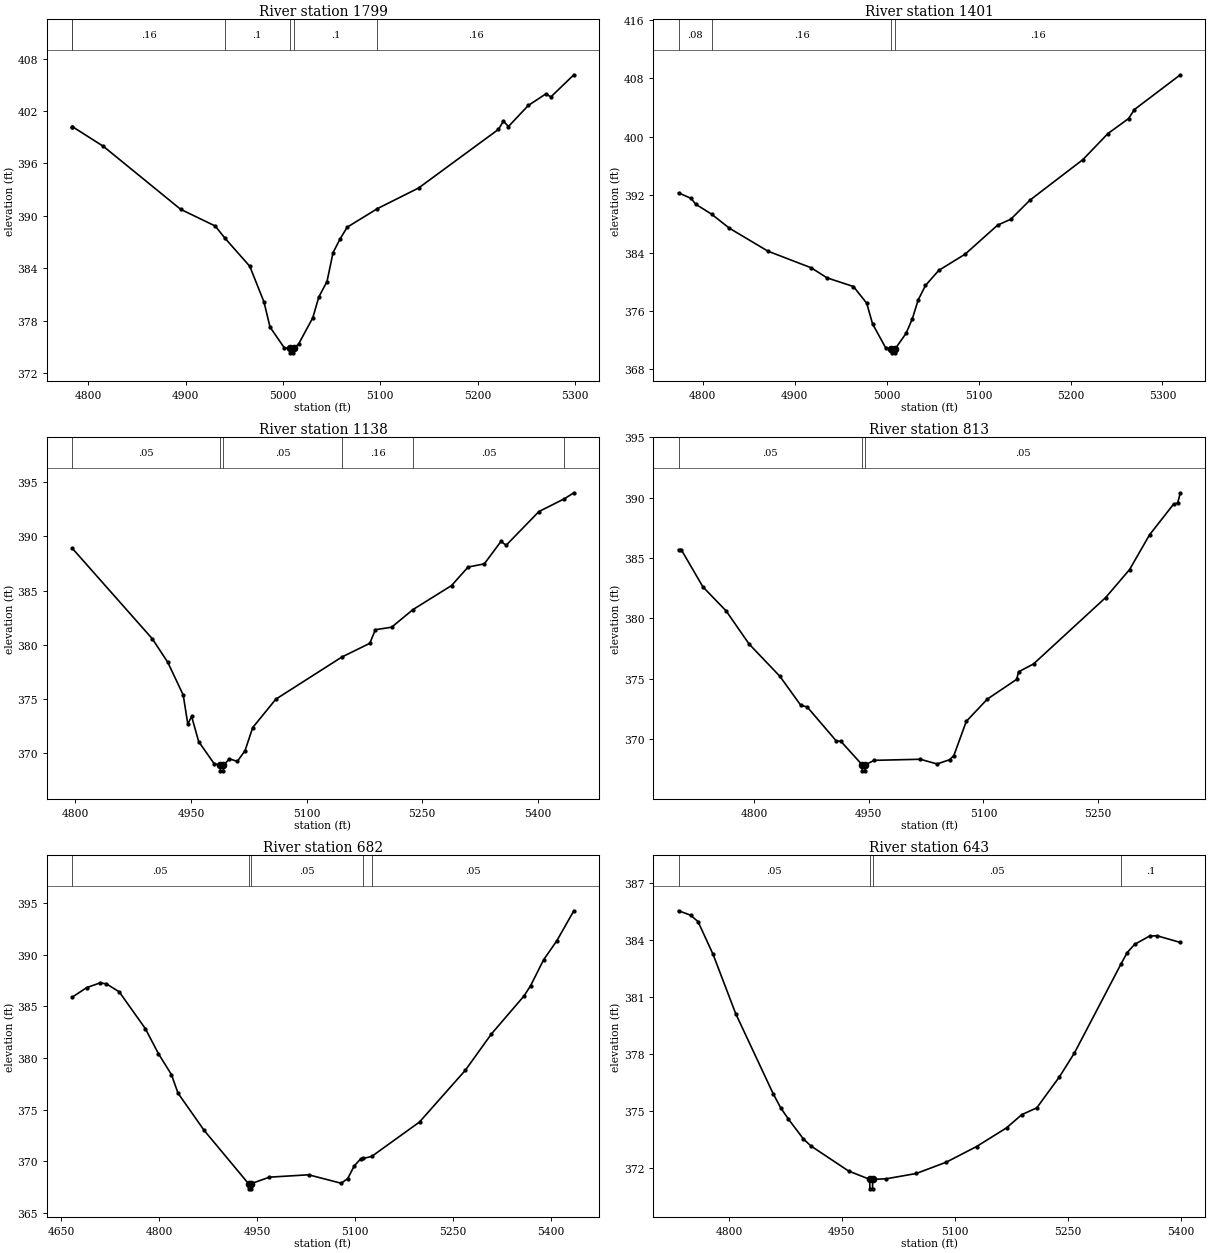
Type RM Length L Ch R = 1 ,1799    ,398,398,398
BEGIN DESCRIPTION:
DUCK CREEK TRIB 22 1 11 0
END DESCRIPTION:
XS GIS Cut Line= 3
      3519800.86     10406095.48      3520061.26     10405902.79
      3520102.77     10405715.99
#Sta/Elev= 30
  4783.4  400.21  4783.7  400.21  4815.6  397.95  4894.9  390.75  4930.4  388.84
  4940.3  387.46  4965.9  384.23  4980.5  380.14  4986.7  377.27  5001.3  374.91
  5006.9  374.83  5007.1  374.33  5010.6  374.33  5010.9  374.83    5016  375.33
  5030.6  378.34  5036.8  380.72  5045.2  382.49  5051.4  385.79  5058.6  387.36
    5066  388.71    5097  390.83  5139.3  393.19  5221.2  399.89  5226.4  400.84
  5231.5  400.22  5251.9  402.63  5269.9  403.95  5275.1  403.61  5298.7  406.14
#Mann= 6 ,-1 , 0
  4783.4     .05       0  4783.7     .16       0  4940.3      .1       0
  5006.9     .07       0  5010.9      .1       0    5097     .16       0
Bank Sta=5006.9,5010.9
XS Rating Curve= 0 ,0
Exp/Cntr=0.3,0.1

Type RM Length L Ch R = 1 ,1401    ,263,263,263
BEGIN DESCRIPTION:
DUCK CREEK TRIB 22 1 3 1
END DESCRIPTION:
XS GIS Cut Line= 3
      3520003.93     10406369.81      3520155.01     10406333.35
      3520399.81     10406029.51
#Sta/Elev= 30
  4773.8  392.23  4787.3  391.48  4792.5  390.67  4809.9  389.28  4829.2  387.35
  4871.1  384.19  4918.1   381.9  4935.2  380.52    4964  379.32  4978.4  377.02
  4984.8  374.16  4999.2  370.83  5005.1  370.68  5005.4  370.18  5008.9  370.18
  5009.1  370.68  5021.3  372.89    5028  374.87  5034.4  377.48  5042.3  379.47
  5056.7  381.54  5085.5  383.79  5120.7  387.78  5135.1   388.6  5155.9  391.23
  5213.5  396.82  5240.7  400.41  5263.1  402.47  5269.5  403.72  5319.4  408.51
#Mann= 4 ,-1 , 0
  4773.8     .08       0  4809.9     .16       0  5005.1     .07       0
  5009.1     .16       0
Bank Sta=5005.1,5009.1
XS Rating Curve= 0 ,0
Exp/Cntr=0.3,0.1

Type RM Length L Ch R = 1 ,1138    ,325,325,325
BEGIN DESCRIPTION:
DUCK CREEK TRIB 22 1 3 0
END DESCRIPTION:
XS GIS Cut Line= 3
      3520068.16     10406534.74       3520424.1     10406515.64
       3520640.8     10406316.28
#Sta/Elev= 30
  4795.7  388.92  4899.8  380.55  4919.8  378.39  4939.9  375.36  4945.8  372.69
  4950.8  373.39  4959.9  371.07  4979.9  369.04  4987.9  368.87  4988.2  368.37
  4991.7  368.37  4991.9  368.87  4999.9  369.48    5010  369.24    5020  370.22
    5030  372.36    5060  374.98  5145.7  378.87  5181.8  380.13  5189.2  381.39
  5210.2  381.62    5238  383.25  5287.9  385.46  5309.4  387.17  5330.4  387.46
    5352  389.53  5358.8  389.18  5401.3  392.29  5434.4  393.47  5446.6  394.02
#Mann= 6 ,-1 , 0
  4795.7     .05       0  4987.9     .03       0  4991.9     .05       0
  5145.7     .16       0    5238     .05       0  5434.4     .16       0
Bank Sta=4987.9,4991.9
XS Rating Curve= 0 ,0
Exp/Cntr=0.3,0.1

Type RM Length L Ch R = 1 ,813     ,131,131,131
BEGIN DESCRIPTION:
DUCK CREEK TRIB 22 1 10 0
END DESCRIPTION:
XS GIS Cut Line= 4
      3520160.21     10406875.01      3520321.67     10406859.39
      3520571.67     10406725.71      3520639.27     10406526.37
#Sta/Elev= 30
  4701.2   385.7  4704.7   385.7  4733.2   382.6  4763.4  380.62  4793.5  377.87
  4833.7   375.2  4861.1  372.79  4869.4  372.66  4907.6  369.83  4913.3  369.82
  4941.3  367.86  4941.5  367.36    4945  367.36  4945.3  367.86  4957.2  368.23
  5017.3  368.32  5039.3  367.93  5055.6  368.28  5061.2  368.62  5077.5  371.46
  5105.1  373.31  5143.3  374.94  5145.9  375.57  5165.4  376.22  5259.7  381.72
  5291.1  384.05  5317.2  386.93  5348.6  389.47  5353.9  389.56  5357.4  390.41
#Mann= 3 ,-1 , 0
  4701.2     .05       0  4941.3     .03       0  4945.3     .05       0
Bank Sta=4941.3,4945.3
XS Rating Curve= 0 ,0
Exp/Cntr=0.3,0.1

Type RM Length L Ch R = 1 ,682     ,39,39,39
BEGIN DESCRIPTION:
DUCK CREEK TRIB 22 1 4 0
END DESCRIPTION:
XS GIS Cut Line= 2
      3520119.81     10406928.86      3520888.43     10406917.99
#Sta/Elev= 30
  4666.2  385.88  4688.5  386.81  4708.5  387.26  4718.5  387.19  4738.5   386.4
  4778.5  382.84  4798.5  380.42  4818.4   378.4  4828.5   376.6  4868.5     373
  4936.5  367.84  4936.8  367.34  4940.3  367.34  4940.5  367.84  4968.5  368.47
  5028.5   368.7  5078.5  367.88  5088.5  368.34  5098.5  369.56  5108.5  370.26
  5112.4  370.28  5125.3  370.48  5198.5  373.81  5268.6  378.81  5308.6  382.33
  5358.6  386.01  5368.6     387  5388.6  389.51  5408.6  391.33  5434.9  394.25
#Mann= 5 ,-1 , 0
  4666.2     .05       0  4936.5     .03       0  4940.5     .05       0
  5112.4     .16       0  5125.3     .05       0
Bank Sta=4936.5,4940.5
XS Rating Curve= 0 ,0
Exp/Cntr=0.3,0.1

Type RM Length L Ch R = 1 ,643     ,53,53,53
BEGIN DESCRIPTION:
DUCK CREEK TRIB 22 1 3 2
END DESCRIPTION:
XS GIS Cut Line= 2
      3520186.19     10406963.55      3520852.79     10406964.85
#Sta/Elev= 30
  4733.1  385.54    4749  385.31    4759  384.97    4779  383.24    4809  380.12
    4859  375.88    4869  375.14    4879  374.56    4899  373.51    4909  373.14
    4959  371.82    4987  371.38  4987.3  370.88  4990.8  370.88    4991  371.38
    5009  371.41    5049  371.69    5089  372.29    5129  373.11    5169   374.1
    5189  374.79    5209  375.15    5239  376.78    5259  378.04  5320.7  382.72
    5329  383.33    5339  383.77    5359  384.21    5369  384.22  5399.7  383.87
#Mann= 4 ,-1 , 0
  4733.1     .05       0    4987     .03       0    4991     .05       0
  5320.7      .1       0
Bank Sta=4987,4991
XS Rating Curve= 0 ,0
Exp/Cntr=0.3,0.1

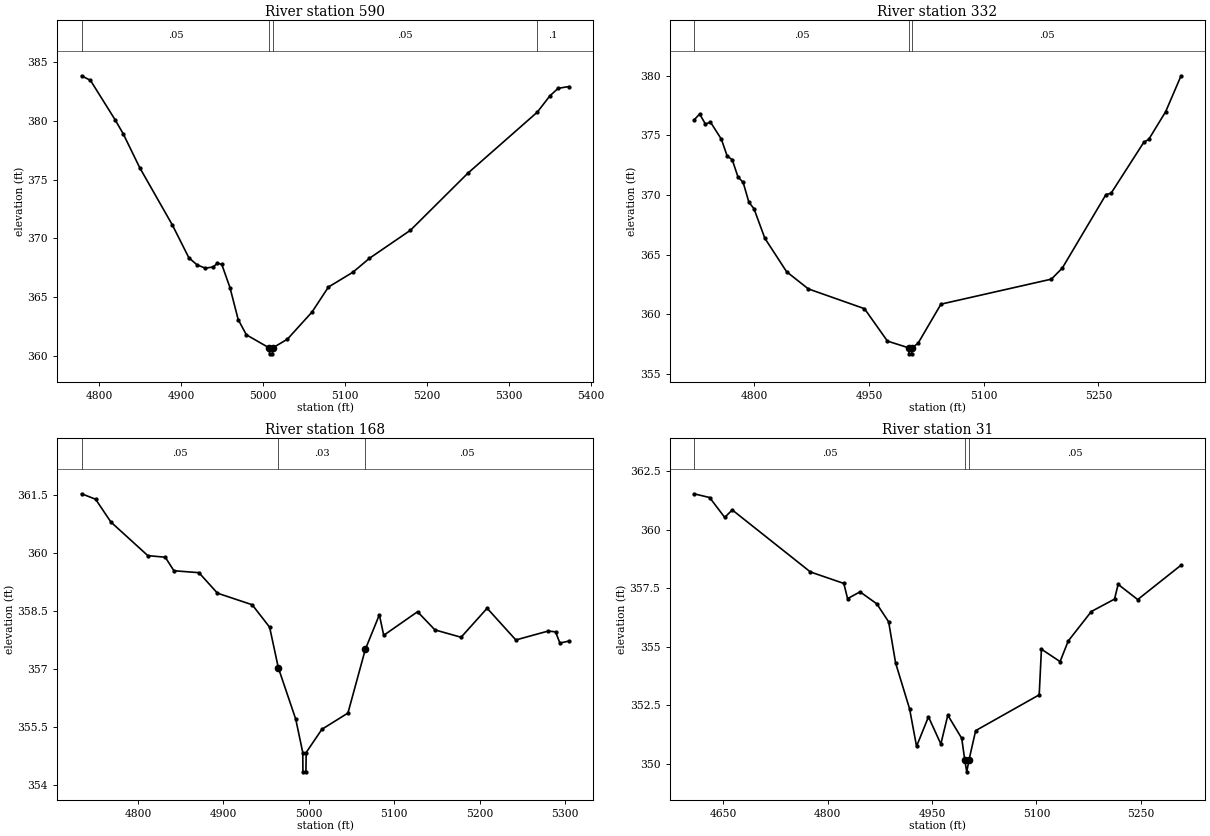
Type RM Length L Ch R = 1 ,590     ,258,258,258
BEGIN DESCRIPTION:
DUCK CREEK TRIB 22 1 2 2
END DESCRIPTION:
XS GIS Cut Line= 2
      3520231.26     10407017.37      3520825.05     10407014.76
#Sta/Elev= 30
  4778.8  383.85  4789.6  383.46  4819.6  380.11  4829.6   378.9  4849.6  376.03
  4889.6  371.12  4909.6  368.34  4919.6  367.74  4929.6  367.46  4939.3  367.56
  4944.3  367.88  4949.7  367.78  4959.7   365.8  4969.7  363.08  4979.7  361.78
  5007.7  360.66  5007.9  360.16  5011.4  360.16  5011.7  360.66  5029.7  361.41
  5059.7  363.72  5079.7  365.85  5109.7  367.12  5129.7   368.3  5179.7  370.69
  5249.7  375.55  5334.3  380.75  5349.7  382.14  5359.7  382.78  5372.6  382.93
#Mann= 4 ,-1 , 0
  4778.8     .05       0  5007.7     .03       0  5011.7     .05       0
  5334.3      .1       0
Bank Sta=5007.7,5011.7
XS Rating Curve= 0 ,0
Exp/Cntr=0.3,0.1

Type RM Length L Ch R = 1 ,332     ,164,164,164
BEGIN DESCRIPTION:
Mapping XS 95ea554d
END DESCRIPTION:
XS GIS Cut Line= 4
      3520245.29     10407147.58      3520356.39     10407272.58
       3520568.2     10407272.58      3520764.66     10407105.42
#Sta/Elev= 30
  4721.1  376.29  4728.5   376.8  4736.1  375.96  4742.7  376.12    4757  374.68
  4764.5  373.28  4771.2  372.96  4778.7  371.51  4785.4  371.07  4792.9   369.4
  4799.6  368.85  4813.8  366.37  4842.3  363.56  4870.7  362.12  4944.1  360.46
  4974.1  357.74  5002.1  357.17  5002.3  356.67  5005.8  356.67  5006.1  357.17
  5014.1  357.55  5044.1  360.84  5188.5  362.94  5202.8  363.87  5259.9  370.04
  5266.5  370.14  5309.4  374.43  5315.9  374.68  5337.9  376.99  5358.1  380.01
#Mann= 3 ,-1 , 0
  4721.1     .05       0  5002.1     .03       0  5006.1     .05       0
Bank Sta=5002.1,5006.1
XS Rating Curve= 0 ,0
Exp/Cntr=0.3,0.1

Type RM Length L Ch R = 1 ,168     ,137,137,137
BEGIN DESCRIPTION:
DUCK CREEK TRIB 22 1 1 0
END DESCRIPTION:
XS GIS Cut Line= 2
      3520175.97     10407379.56      3520735.79     10407488.92
#Sta/Elev= 30
    4734  361.54  4750.4   361.4  4768.3  360.81  4811.6  359.94    4832   359.9
  4842.1  359.55  4871.4   359.5  4893.1  358.97  4933.8  358.67  4954.2  358.09
  4964.4  357.04  4984.8  355.71    4993  354.85  4993.2  354.35  4996.7  354.35
    4997  354.85  5015.4  355.45  5045.9  355.87  5066.3  357.52  5082.7  358.41
  5087.8  357.88  5127.4  358.49  5147.8  358.02  5178.4  357.83  5208.9  358.58
  5242.5  357.76  5280.3  357.99    5289  357.97  5294.1  357.68  5304.4  357.73
#Mann= 3 , 0 , 0
    4734     .05       0  4964.4     .03       0  5066.3     .05       0
Bank Sta=4964.4,5066.3
XS Rating Curve= 0 ,0
Exp/Cntr=0.3,0.1

Type RM Length L Ch R = 1 ,31      ,0,0,0
BEGIN DESCRIPTION:
DUCK CREEK TRIB 22 1 1 0
END DESCRIPTION:
XS GIS Cut Line= 5
      3520171.24     10407383.73      3520412.26     10407482.36
      3520416.42     10407560.83      3520573.37     10407557.36
      3520768.81     10407499.55
#Sta/Elev= 30
  4607.9  361.54  4630.4  361.38  4652.1  360.53  4662.9  360.85  4775.2   358.2
  4823.2  357.71  4828.6  357.06  4846.5  357.35  4870.5  356.84  4887.6  356.07
  4897.6  354.31  4917.7  352.35  4927.7  350.75  4944.8  352.01  4962.6  350.85
  4972.6  352.08  4992.6  351.09    4997  350.16  4999.8  349.66    5003  350.16
  5012.6  351.42  5103.9  352.95  5107.1   354.9  5133.9  354.37  5145.6  355.25
  5178.8  356.51  5212.1  357.04  5217.3  357.67  5245.4  357.02  5307.7  358.49
#Mann= 3 ,-1 , 0
  4607.9     .05       0    4997     .03       0    5003     .05       0
Bank Sta=4997,5003
XS Rating Curve= 0 ,0
Exp/Cntr=0.3,0.1

Chan Stop Cuts=-1
Use User Specified Reach Order=0
Composite Channel Slope=5