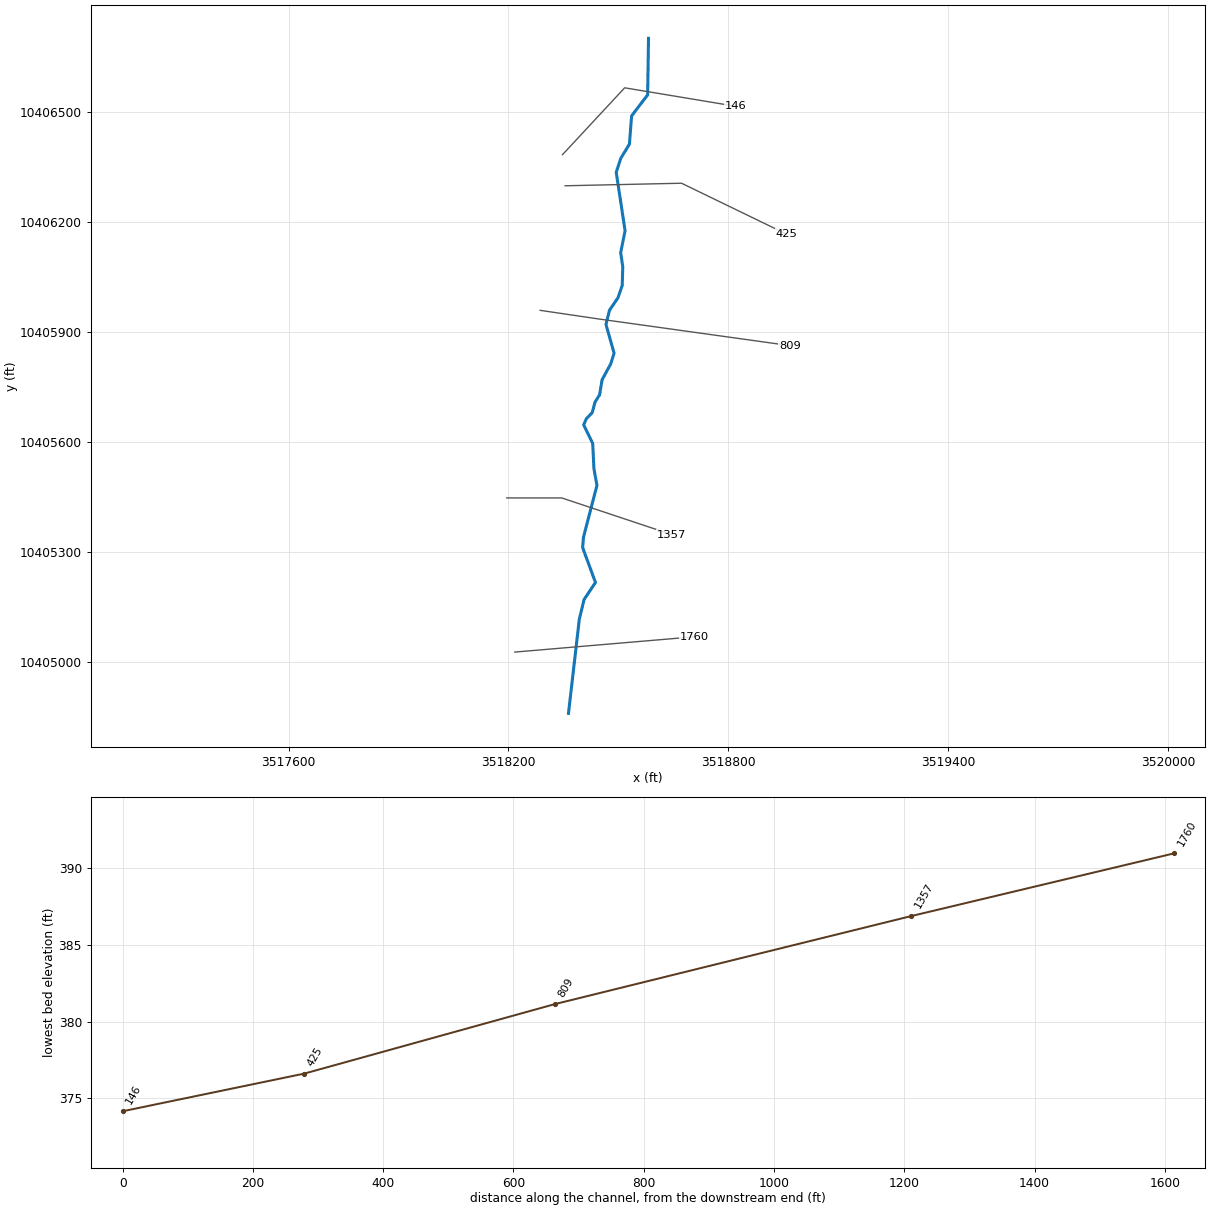
--- DUCK CREEK TRIB 22 3.prj (project) ---

Proj Title=DUCK CREEK TRIB 22 3 Base Level Engineering
Current Plan=p01
Default Exp/Contr=0.3,0.1
English Units
Geom File=g01
Flow File=f01
Plan File=p01
BEGIN DESCRIPTION:
DUCK CREEK TRIB 22 3
END DESCRIPTION:

--- DUCK CREEK TRIB 22 3.p01 (plan) ---

Plan Title=Multiple Run
Short Identifier=Multiple
Geom File=g01
Flow File=f01
Subcritical Flow
K Sum by GR= 0
Std Step Tol= 0.01
Critical Tol= 0.01
Num of Std Step Trials= 20
Max Error Tol= 0.3
Flow Tol Ratio= 0.001
Split Flow NTrial= 30
Split Flow Tol= 0.02
Split Flow Ratio= 0.02
Log Output Level= 0
Friction Slope Method= 1
Unsteady Friction Slope Method= 2
Unsteady Bridges Friction Slope Method= 1
Parabolic Critical Depth
Global Vel Dist=  1 , 1 , 1
Global Log Level= 0
CheckData=True
Encroach Param= -1, 0, 0, 0
BEGIN DESCRIPTION:
Multiple Run
END DESCRIPTION:

--- DUCK CREEK TRIB 22 3.f01 (steady flow) ---

Flow Title=Multiple
Number of Profiles=7
Profile Names=10-year,25-year,50-year,1pct_min,100-year,1pct_plu,500-year
River Rch & RM= DUCK CREEK TRIB ,Reach-1,1760
     564     763     925     823    1112    1505    1600
Boundary for River Rch & Prof#=DUCK CREEK TRIB ,Reach-1,1
Up Type=0
Dn Type=3
Dn Slope=0.005
Boundary for River Rch & Prof#=DUCK CREEK TRIB ,Reach-1,2
Up Type=0
Dn Type=3
Dn Slope=0.005
Boundary for River Rch & Prof#=DUCK CREEK TRIB ,Reach-1,3
Up Type=0
Dn Type=3
Dn Slope=0.005
Boundary for River Rch & Prof#=DUCK CREEK TRIB ,Reach-1,4
Up Type=0
Dn Type=3
Dn Slope=0.005
Boundary for River Rch & Prof#=DUCK CREEK TRIB ,Reach-1,5
Up Type=0
Dn Type=3
Dn Slope=0.005
Boundary for River Rch & Prof#=DUCK CREEK TRIB ,Reach-1,6
Up Type=0
Dn Type=3
Dn Slope=0.005
Boundary for River Rch & Prof#=DUCK CREEK TRIB ,Reach-1,7
Up Type=0
Dn Type=3
Dn Slope=0.005

--- DUCK CREEK TRIB 22 3.g01 (geometry) ---

Geom Title=Existing Conditions

River Reach=DUCK CREEK TRIB ,Reach-1
Reach XY= 30
      3518363.74     10404859.39      3518393.32     10405116.43
      3518406.29     10405169.97      3518437.41     10405216.65
      3518402.37     10405311.77      3518404.69     10405340.33
      3518441.42     10405481.58      3518433.18     10405526.99
      3518429.88     10405595.96      3518405.12     10405646.79
      3518412.88     10405664.12      3518428.39     10405679.96
      3518436.32     10405709.09      3518448.72     10405728.90
      3518455.58     10405770.14      3518478.98     10405813.11
      3518488.18     10405842.37      3518466.03     10405920.99
      3518475.74     10405959.94      3518498.57     10405993.07
      3518510.41     10406027.12      3518511.91     10406077.99
      3518506.21     10406116.72      3518518.21     10406176.60
      3518494.01     10406336.04      3518506.56     10406374.41
      3518530.04     10406412.91      3518535.99     10406490.00
      3518579.84     10406547.43      3518582.11     10406701.64

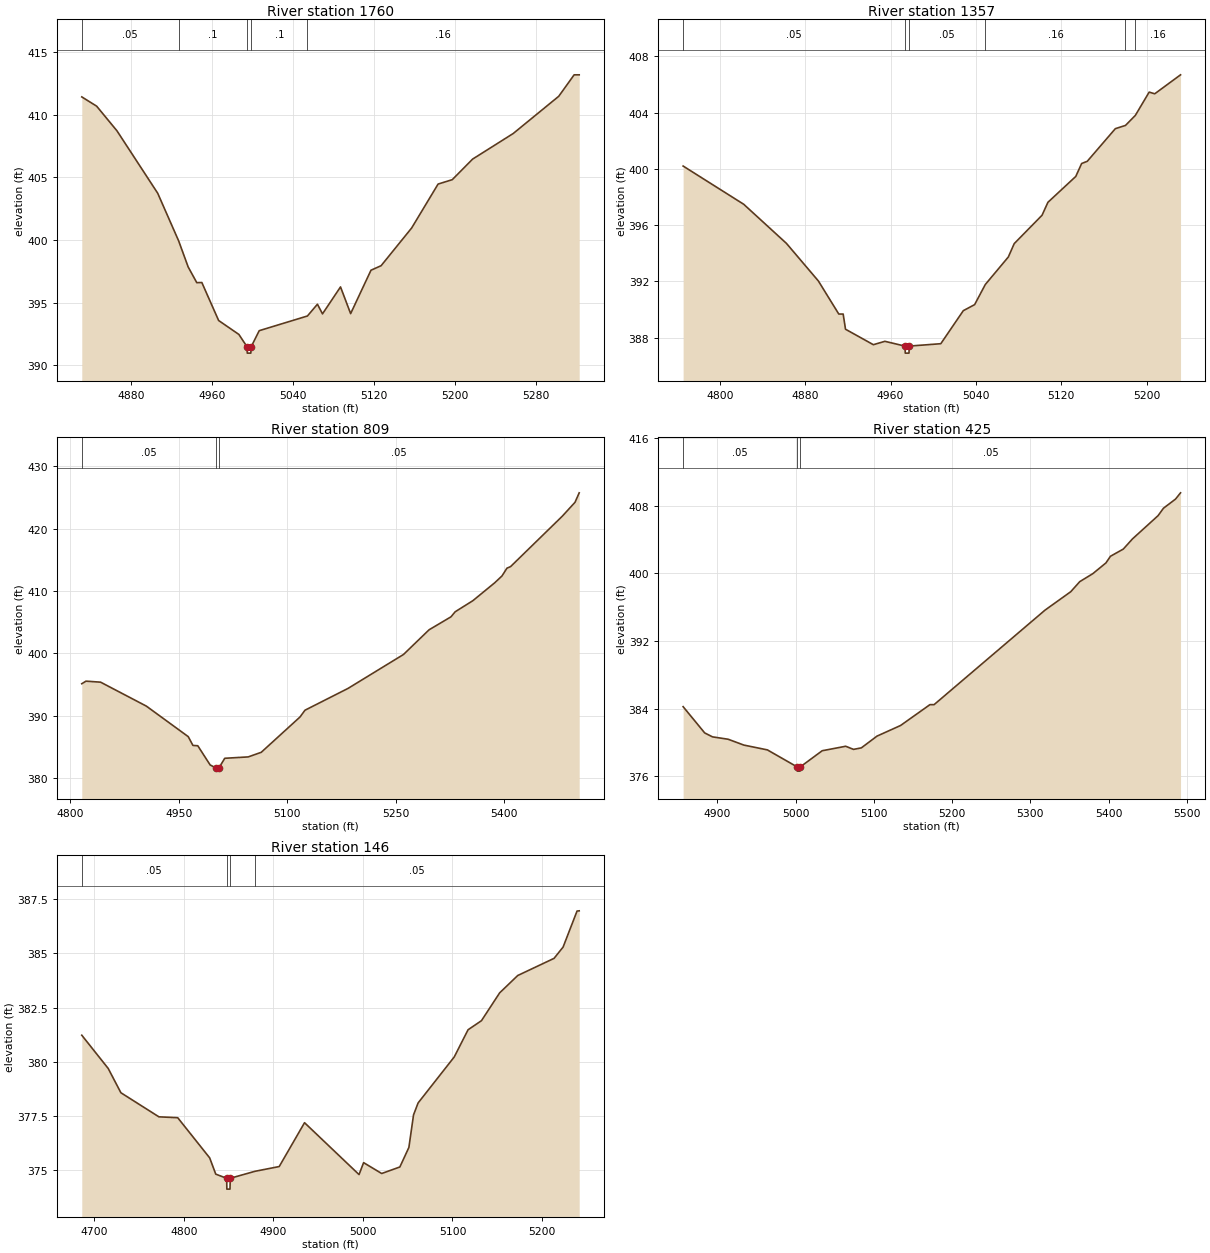
Type RM Length L Ch R = 1,1760,403,403,403
BEGIN DESCRIPTION:
DUCK CREEK TRIB 22 3 11
END DESCRIPTION:
XS GIS Cut Line= 2
      3518217.42     10405026.70      3518707.05     10405068.38
#Sta/Elev= 30
  4831.5  411.41  4846.2  410.67  4866.3  408.70  4906.5  403.73  4927.3  399.91
  4936.6  397.85  4945.1  396.60  4950.1  396.61  4966.7  393.58  4986.7  392.47
  4994.8  391.48  4995.0  390.98  4998.5  390.98  4998.8  391.48  5006.8  392.77
  5054.4  393.94  5064.3  394.88  5069.3  394.11  5087.1  396.26  5097.1  394.13
  5117.2  397.59  5127.2  397.95  5157.4  400.96  5183.5  404.46  5197.5  404.81
  5217.6  406.45  5257.7  408.49  5302.7  411.46  5317.9  413.17  5322.9  413.17
#Mann=5,-1,0
  4831.5    0.05       0  4927.3     0.1       0  4994.8    0.07       0
  4998.8     0.1       0  5054.4    0.16       0
Bank Sta=4994.8,4998.8
Exp/Cntr=0.3,0.1

Type RM Length L Ch R = 1,1357,548,548,548
BEGIN DESCRIPTION:
DUCK CREEK TRIB 22 3 10
END DESCRIPTION:
XS GIS Cut Line= 3
      3518195.26     10405447.39      3518345.27     10405447.39
      3518645.23     10405347.40
#Sta/Elev= 30
  4765.6  400.20  4822.4  397.48  4862.4  394.70  4892.4  392.02  4911.5  389.67
  4915.6  389.67  4917.8  388.59  4943.9  387.49  4954.7  387.73  4973.5  387.39
  4973.8  386.89  4977.3  386.89  4977.5  387.39  5007.1  387.56  5028.2  389.91
  5038.8  390.34  5048.8  391.77  5070.4  393.73  5075.9  394.68  5102.0  396.70
  5107.5  397.62  5133.6  399.46  5139.1  400.38  5144.4  400.54  5170.7  402.86
  5180.2  403.09  5189.4  403.80  5202.4  405.46  5207.6  405.34  5231.8  406.69
#Mann=6,-1,0
  4765.6    0.05       0  4973.5    0.03       0  4977.5    0.05       0
  5048.8    0.16       0  5180.2     0.1       0  5189.4    0.16       0
Bank Sta=4973.5,4977.5
Exp/Cntr=0.3,0.1

Type RM Length L Ch R = 1,809,384,384,384
BEGIN DESCRIPTION:
DUCK CREEK TRIB 22 3 4 1
END DESCRIPTION:
XS GIS Cut Line= 3
      3518286.41     10405959.32      3518445.22     10405935.89
      3518967.84     10405863.08
#Sta/Elev= 30
  4815.7  395.15  4821.5  395.56  4841.7  395.40  4905.0  391.56  4963.0  386.66
  4969.5  385.25  4976.2  385.20  4993.3  382.12  5001.4  381.63  5001.6  381.13
  5005.1  381.13  5005.4  381.63  5013.5  383.19  5046.0  383.41  5064.0  384.15
  5117.6  389.81  5124.5  390.90  5184.1  394.40  5260.8  399.84  5296.2  403.80
  5326.5  405.88  5332.3  406.69  5356.8  408.47  5387.0  411.34  5397.1  412.44
  5403.9  413.68  5409.0  413.94  5480.5  422.02  5498.1  424.25  5503.9  425.77
#Mann=3,-1,0
  4815.7    0.05       0  5001.4    0.03       0  5005.4    0.05       0
Bank Sta=5001.4,5005.4
Exp/Cntr=0.3,0.1

Type RM Length L Ch R = 1,425,279,279,279
BEGIN DESCRIPTION:
Mapping XS ea13a279
END DESCRIPTION:
XS GIS Cut Line= 3
      3518354.58     10406299.28      3518672.29     10406306.22
      3518957.90     10406167.74
#Sta/Elev= 30
  4856.5  384.22  4884.0  381.12  4894.0  380.65  4914.0  380.37  4934.0  379.68
  4964.1  379.11  5002.1  377.10  5002.3  376.60  5005.8  376.60  5006.1  377.10
  5034.1  379.01  5064.1  379.54  5074.1  379.17  5084.1  379.35  5104.1  380.74
  5134.1  381.99  5171.7  384.46  5177.0  384.46  5318.6  395.63  5351.5  397.81
  5363.0  399.00  5379.6  399.94  5396.4  401.21  5402.2  402.00  5418.6  402.85
  5430.4  404.06  5463.0  406.80  5469.9  407.68  5485.3  408.76  5491.7  409.50
#Mann=3,-1,0
  4856.5    0.05       0  5002.1    0.03       0  5006.1    0.05       0
Bank Sta=5002.1,5006.1
Exp/Cntr=0.3,0.1

Type RM Length L Ch R = 1,146,0,0,0
BEGIN DESCRIPTION:
DUCK CREEK TRIB 22 3 4 0
END DESCRIPTION:
XS GIS Cut Line= 3
      3518347.63     10406384.33      3518517.11     10406566.64
      3518819.83     10406516.29
#Sta/Elev= 30
  4685.8  381.23  4715.3  379.70  4729.5  378.58  4772.0  377.47  4793.0  377.43
  4828.7  375.58  4835.5  374.83  4847.7  374.64  4847.9  374.14  4851.4  374.14
  4851.7  374.64  4879.2  374.96  4906.4  375.18  4934.7  377.20  4995.6  374.81
  5000.7  375.36  5020.9  374.86  5041.2  375.16  5051.3  376.06  5056.5  377.56
  5061.6  378.11  5102.0  380.23  5117.4  381.48  5132.4  381.90  5152.7  383.18
  5172.9  383.98  5213.5  384.77  5223.6  385.29  5239.2  386.95  5241.6  386.96
#Mann=4,-1,0
  4685.8    0.05       0  4847.7    0.03       0  4851.7    0.05       0
  4879.2    0.05       0
Bank Sta=4847.7,4851.7
Exp/Cntr=0.3,0.1

Chan Stop Cuts=-1