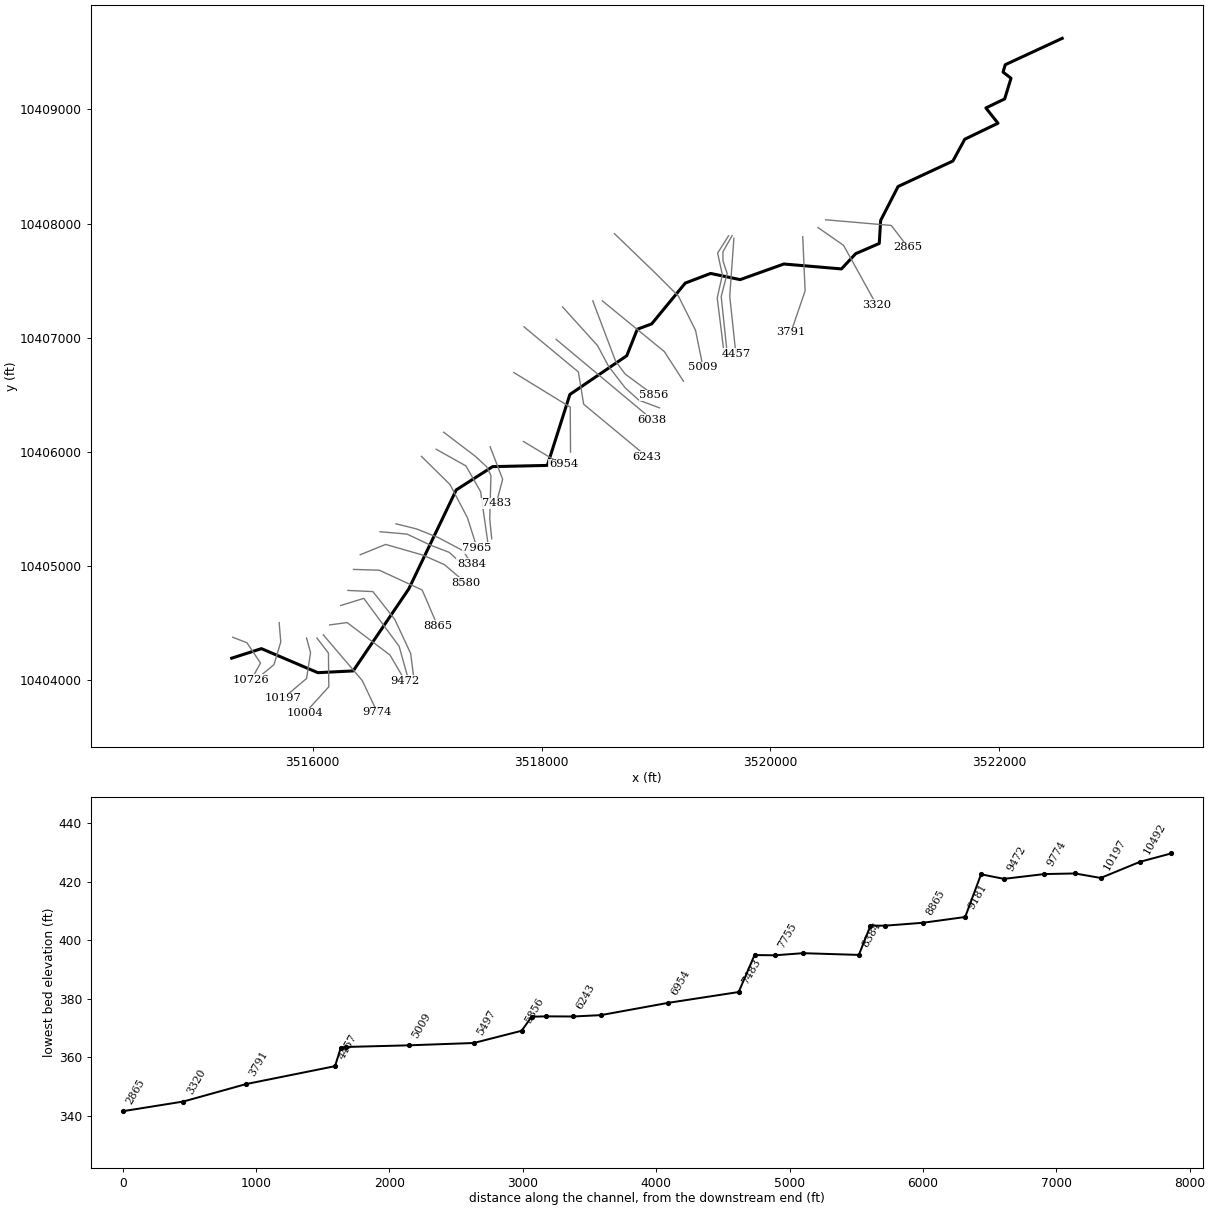
--- DUCK CREEK TRIB 22.prj (project) ---

Proj Title=DUCK CREEK TRIB 22 Base Level Engineering
Current Plan=p01
Default Exp/Contr=0.3,0.1
English Units
Geom File=g01
Flow File=f01
Plan File=p01
Y Axis Title=Elevation
X Axis Title(PF)=Main Channel Distance
X Axis Title(XS)=Station
BEGIN DESCRIPTION:
DUCK CREEK TRIB 22
END DESCRIPTION:
DSS Export Rating Curves= 0
DSS Export Rating Curve Sorted= 0
DSS Export Volume Flow Curves= 0
DXF OffsetX= 0
DXF OffsetY= 0
DXF ScaleX= 1
DXF ScaleY= 10

--- DUCK CREEK TRIB 22.p01 (plan) ---

Plan Title=Multiple Run
Short Identifier=Multiple
Geom File=g01
Flow File=f01
Subcritical Flow
K Sum by GR= 0
Std Step Tol= 0.01
Critical Tol= 0.01
Num of Std Step Trials= 20
Max Error Tol= 0.3
Flow Tol Ratio= 0.001
Split Flow NTrial= 30
Split Flow Tol= 0.02
Split Flow Ratio= 0.02
Log Output Level= 0
Friction Slope Method= 1
Unsteady Friction Slope Method= 2
Unsteady Bridges Friction Slope Method= 1
Parabolic Critical Depth
Global Vel Dist=  1 , 1 , 1
Global Log Level= 0
CheckData=True
Encroach Param= -1, 0, 0, 0
BEGIN DESCRIPTION:
Multiple Run
END DESCRIPTION:

--- DUCK CREEK TRIB 22.f01 (steady flow) ---

Flow Title=Multiple
Program Version=4.10
Number of Profiles= 7
Profile Names=10-year,25-year,50-year,1pct_min,100-year,1pct_plu,500-year
River Rch & RM=DUCK CREEK TRIB,Reach-1         ,10726
     843    1172    1447    1309    1770    2393    2635
River Rch & RM=DUCK CREEK TRIB,Reach-1         ,7483
     843    1172    1447    1309    1770    2393    2635
River Rch & RM=DUCK CREEK TRIB,Reach-1         ,6243
    1374    1965    2473    2273    3074    4158    4740
River Rch & RM=DUCK CREEK TRIB,Reach-1         ,5497
    1374    1965    2473    2273    3074    4158    4740
River Rch & RM=DUCK CREEK TRIB,Reach-1         ,3320
    1617    2327    2939    2709    3664    4955    5682
Boundary for River Rch & Prof#=DUCK CREEK TRIB,Reach-1         , 1
Up Type= 0
Dn Type= 3
Dn Slope=0.005
Boundary for River Rch & Prof#=DUCK CREEK TRIB,Reach-1         , 2
Up Type= 0
Dn Type= 3
Dn Slope=0.005
Boundary for River Rch & Prof#=DUCK CREEK TRIB,Reach-1         , 3
Up Type= 0
Dn Type= 3
Dn Slope=0.005
Boundary for River Rch & Prof#=DUCK CREEK TRIB,Reach-1         , 4
Up Type= 0
Dn Type= 3
Dn Slope=0.005
Boundary for River Rch & Prof#=DUCK CREEK TRIB,Reach-1         , 5
Up Type= 0
Dn Type= 3
Dn Slope=0.005
Boundary for River Rch & Prof#=DUCK CREEK TRIB,Reach-1         , 6
Up Type= 0
Dn Type= 3
Dn Slope=0.005
Boundary for River Rch & Prof#=DUCK CREEK TRIB,Reach-1         , 7
Up Type= 0
Dn Type= 3
Dn Slope=0.005
DSS Import GetInterval= 0
DSS Import GetPeak= 0
DSS Import FillOption= 0

--- DUCK CREEK TRIB 22.g01 (geometry) ---

Geom Title=Existing Conditions
Program Version=4.10

River Reach=DUCK CREEK TRIB ,Reach-1
Reach XY= 30
      3515292.23     10404194.81      3515552.23     10404278.38
      3516044.95     10404067.94      3516353.91     10404083.38
      3516839.87     10404801.49      3517254.64     10405668.17
      3517572.16     10405871.75      3518050.65     10405882.48
      3518247.56     10406503.45      3518744.86     10406842.81
      3518836.81     10407074.48      3518962.31     10407121.34
        3519256.     10407478.55      3519477.36     10407563.19
       3519735.6     10407508.93      3520117.55     10407645.65
      3520620.66      10407602.7      3520744.97     10407736.04
      3520951.22     10407825.62      3520963.54     10408027.53
      3521115.85     10408324.18      3521594.71     10408547.27
      3521698.57     10408738.26      3521988.86     10408878.26
      3521883.02     10409011.69      3522046.88      10409090.9
      3522102.84     10409271.92      3522033.21     10409325.74
       3522052.3     10409390.41      3522550.14     10409621.36

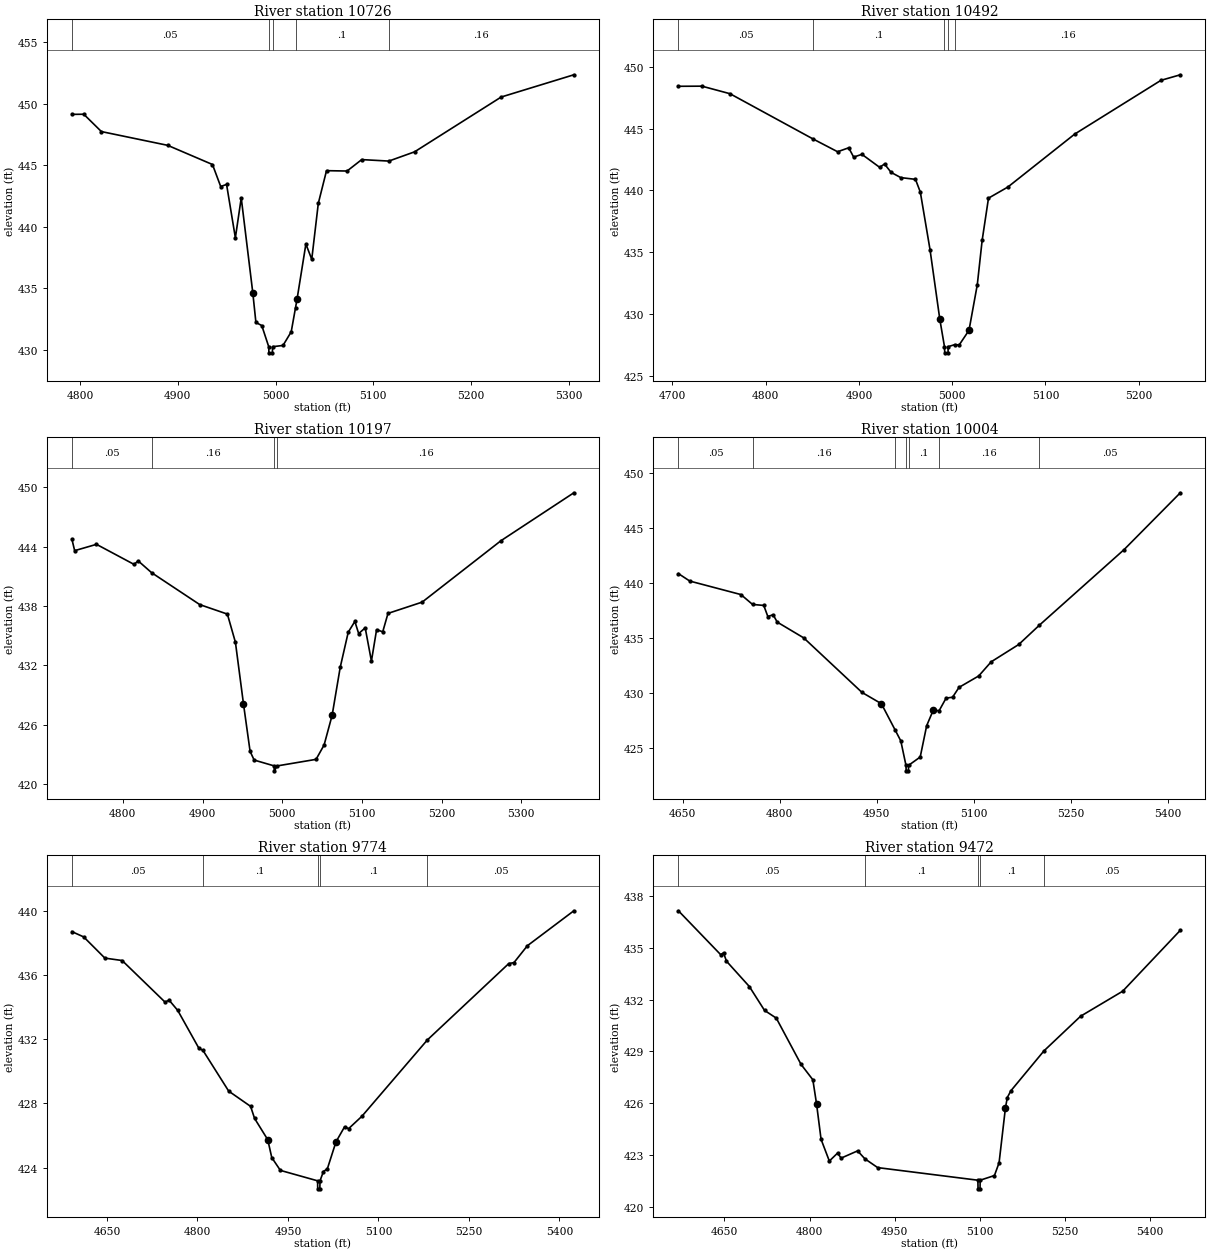
Type RM Length L Ch R = 1 ,10726   ,234,234,234
BEGIN DESCRIPTION:
DUCK CREEK TRIB 22 31 0
END DESCRIPTION:
XS GIS Cut Line= 4
      3515300.85     10404378.26       3515425.8     10404329.66
      3515543.86     10404152.58      3515463.98     10404006.72
#Sta/Elev= 30
  4791.8  449.15  4803.9  449.16  4821.9  447.75  4889.7  446.63  4935.5  445.07
  4943.9  443.28  4949.9  443.45  4958.9  439.11  4964.9  442.35 4976.74  434.62
  4979.9  432.22  4985.9  431.97    4993  430.25  4993.2  429.75  4996.7  429.75
    4997  430.25  5007.6  430.35    5016  431.46  5020.4  433.42    5022  434.13
    5031   438.6    5037  437.36  5043.7  441.91  5052.1  444.57  5073.1  444.54
  5088.1  445.47  5115.8  445.35  5142.1   446.1  5230.7  450.56    5305  452.37
#Mann= 5 ,-1 , 0
  4791.8     .05       0    4993     .03       0    4997     .05       0
  5020.4      .1       0  5115.8     .16       0
Bank Sta=4976.74,5022
XS Rating Curve= 0 ,0
Exp/Cntr=0.3,0.1

Type RM Length L Ch R = 1 ,10492   ,295,295,295
BEGIN DESCRIPTION:
Mapping XS 25f276ef
END DESCRIPTION:
XS GIS Cut Line= 4
      3515707.05     10404506.78      3515720.94     10404336.61
      3515661.91     10404138.69      3515538.28     10404035.67
#Sta/Elev= 30
  4706.4  448.42  4731.6  448.43  4761.7  447.82  4850.6  444.17  4877.1  443.13
    4889  443.45  4894.3   442.7  4903.2  442.92  4922.2  441.87  4927.4  442.14
  4934.5  441.46  4944.9  441.04  4960.6   440.9  4965.8  439.87  4976.2  435.22
  4986.7  429.59  4991.7  427.38    4992  426.88  4995.5  426.88  4995.7  427.38
  5002.6  427.54  5007.5  427.52    5018   428.7  5026.9  432.39  5032.1  435.97
  5038.9  439.38  5059.7  440.28  5131.4  444.56  5223.8   448.9  5244.6  449.35
#Mann= 5 ,-1 , 0
  4706.4     .05       0  4850.6      .1       0  4991.7     .07       0
  4995.7      .1       0  5002.6     .16       0
Bank Sta=4986.7,5018
XS Rating Curve= 0 ,0
Exp/Cntr=0.3,0.1

Type RM Length L Ch R = 1 ,10197   ,193,193,193
BEGIN DESCRIPTION:
Mapping XS 791fefcd
END DESCRIPTION:
XS GIS Cut Line= 4
      3515946.62     10404371.37      3515981.36     10404242.86
      3515946.63     10404017.16      3515741.78     10403843.55
#Sta/Elev= 30
  4736.1  444.74  4739.5   443.6  4766.9  444.24  4814.1  442.21  4819.2  442.57
    4836  441.38  4896.5  438.15  4931.2  437.19  4941.3  434.34  4951.4  428.12
  4959.7  423.32  4964.8  422.44  4989.9  421.85  4990.1  421.35  4993.9  421.85
  5042.5  422.51  5052.6  423.96  5062.7  426.97  5072.8   431.8  5082.9  435.36
  5091.2  436.45    5096  435.22  5104.2   435.8    5112  432.44  5118.5  435.62
  5126.2   435.4  5132.8  437.26  5175.7   438.4  5274.5   444.6  5366.1  449.45
#Mann= 4 ,-1 , 0
  4736.1     .05       0    4836     .16       0  4989.9     .07       0
  4993.9     .16       0
Bank Sta=4951.4,5062.7
XS Rating Curve= 0 ,0
Exp/Cntr=0.3,0.1

Type RM Length L Ch R = 1 ,10004   ,230,230,230
BEGIN DESCRIPTION:
Mapping XS eea90685
END DESCRIPTION:
XS GIS Cut Line= 4
      3516036.93     10404371.31      3516137.61     10404239.38
      3516141.08     10403944.25      3515929.29     10403711.63
#Sta/Elev= 30
  4643.5  440.87  4661.1  440.19  4740.1  438.96  4758.1  438.06  4775.4  437.97
  4781.7  436.96  4789.9  437.12  4796.2  436.45  4837.2  435.01  4927.2  430.04
  4957.2  429.01  4978.2  426.64  4987.2  425.62  4995.2  423.39  4995.5  422.89
    4999  422.89  4999.2  423.39  5017.2  424.15  5027.2  427.01  5037.2   428.4
  5046.5  428.38  5057.2  429.52  5067.2   429.6  5077.2   430.5  5107.6  431.54
  5126.9  432.83  5169.5  434.41  5201.4  436.17  5332.3  443.06  5419.2  448.24
#Mann= 7 ,-1 , 0
  4643.5     .05       0  4758.1     .16       0  4978.2      .1       0
  4995.2     .07       0  4999.2      .1       0  5046.5     .16       0
  5201.4     .05       0
Bank Sta=4957.2,5037.2
XS Rating Curve= 0 ,0
Exp/Cntr=0.3,0.1

Type RM Length L Ch R = 1 ,9774    ,302,302,302
BEGIN DESCRIPTION:
Mapping XS 64d8851b
END DESCRIPTION:
XS GIS Cut Line= 3
      3516092.47     10404399.11      3516432.75      10403999.8
      3516564.71     10403721.98
#Sta/Elev= 30
  4591.9  438.71  4611.4  438.38  4646.5  437.06  4675.1  436.91  4746.2  434.32
    4753  434.44  4767.3   433.8  4802.4  431.44  4809.1  431.31  4851.8  428.77
  4888.1  427.82  4894.7  427.07  4916.6  425.74  4923.2  424.63  4937.5  423.83
  4999.2  423.18  4999.4  422.68  5002.9  422.68  5003.2  423.18  5008.9  423.76
  5015.4  423.93  5029.7  425.61    5044  426.55  5050.6  426.43  5072.6   427.2
  5181.2  431.96  5316.2  436.72  5324.8  436.78    5347  437.83  5424.1  440.01
#Mann= 5 ,-1 , 0
  4591.9     .05       0  4809.1      .1       0  4999.2     .07       0
  5003.2      .1       0  5181.2     .05       0
Bank Sta=4916.6,5029.7
XS Rating Curve= 0 ,0
Exp/Cntr=0.3,0.1

Type RM Length L Ch R = 1 ,9472    ,172,172,172
BEGIN DESCRIPTION:
Mapping XS 183e07d4
END DESCRIPTION:
XS GIS Cut Line= 4
      3516148.07     10404485.92       3516300.8     10404506.75
       3516675.8     10404222.02      3516807.33     10403997.04
#Sta/Elev= 30
  4568.7  437.15  4643.2  434.61  4648.3  434.71  4653.5  434.23  4693.9  432.76
  4720.6  431.38  4741.4  430.93  4785.1  428.25  4805.9  427.36  4812.4  425.97
  4820.4  423.91    4835  422.65  4849.5  423.11  4855.8  422.82  4884.9  423.24
  4897.7  422.78  4920.3  422.27  5097.1  421.54  5097.4  421.04  5100.9  421.04
  5101.1  421.54  5126.3  421.81  5134.5  422.55 5145.64  425.71    5149  426.33
  5155.3  426.72  5213.6  429.03  5278.3  431.04  5352.6  432.49  5454.3  436.02
#Mann= 5 ,-1 , 0
  4568.7     .05       0  4897.7      .1       0  5097.1     .07       0
  5101.1      .1       0  5213.6     .05       0
Bank Sta=4812.4,5145.64
XS Rating Curve= 0 ,0
Exp/Cntr=0.3,0.1

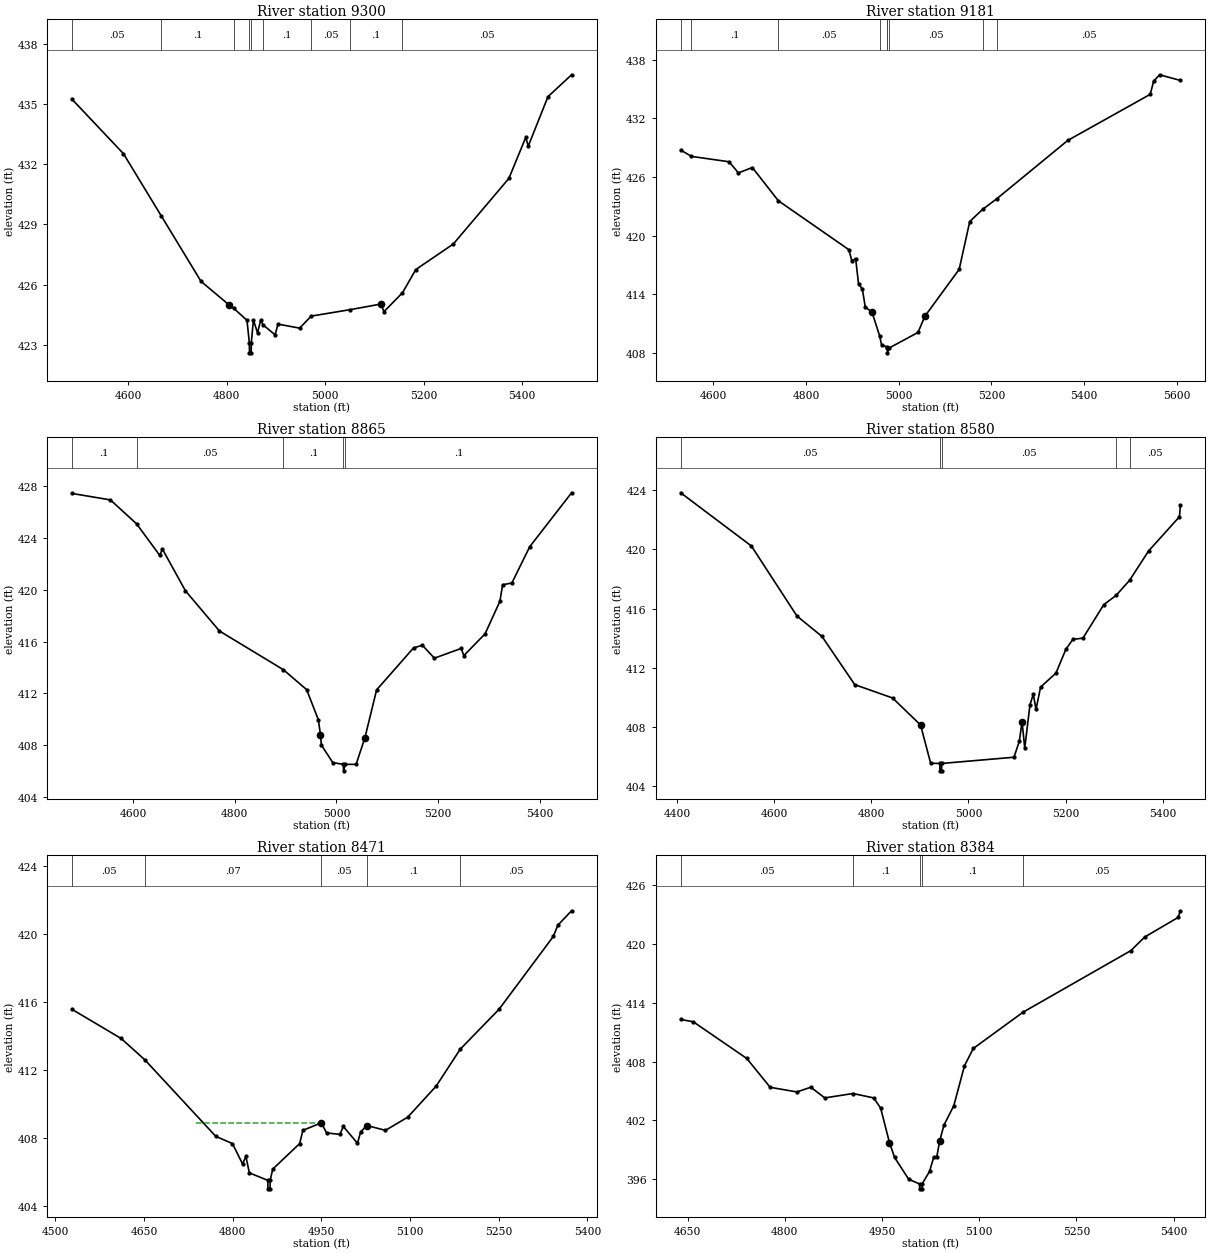
Type RM Length L Ch R = 1 ,9300    ,119,119,119
BEGIN DESCRIPTION:
Mapping XS 17f3aeb1
END DESCRIPTION:
XS GIS Cut Line= 4
      3516245.28     10404656.06      3516446.63     10404718.55
      3516755.66     10404298.41       3516831.7     10404025.38
#Sta/Elev= 30
  4485.2  435.24  4590.1  432.52  4666.5  429.44  4747.8  426.16  4804.1     425
  4814.6  424.81  4841.2  424.22    4846   423.1  4846.3   422.6  4849.8   422.6
    4850   423.1  4854.3  424.24  4862.7  423.59  4868.9  424.22  4874.5  423.98
  4898.2   423.5  4904.4  424.03  4948.3  423.83  4971.7  424.43  5050.8  424.75
  5113.4  425.03  5119.6  424.65  5157.2  425.59  5184.4  426.75  5260.6  428.02
  5373.6  431.29  5407.8  433.33    5413   432.9    5453  435.36    5501  436.45
#Mann= 9 ,-1 , 0
  4485.2     .05       0  4666.5      .1       0  4814.6     .05       0
    4846     .03       0    4850     .05       0  4874.5      .1       0
  4971.7     .05       0  5050.8      .1       0  5157.2     .05       0
Bank Sta=4804.1,5113.4
XS Rating Curve= 0 ,0
Exp/Cntr=0.3,0.1

Type RM Length L Ch R = 1 ,9181    ,316,316,316
BEGIN DESCRIPTION:
Mapping XS 1e474efe
END DESCRIPTION:
XS GIS Cut Line= 5
      3516307.71       10404788.       3516526.5     10404777.58
      3516717.47     10404534.52      3516856.36     10404235.91
      3516884.14     10404017.14
#Sta/Elev= 30
  4529.8  428.76  4553.1  428.11  4634.3  427.56  4654.3  426.42  4684.4  426.97
  4740.4  423.57  4892.7  418.55  4899.1  417.38  4907.2  417.65  4913.5  415.03
  4921.6  414.55    4928  412.67  4942.4  412.17  4958.8  409.75  4963.2   408.8
  4973.9  408.61  4975.7  408.49  4975.9  407.99  4979.7  408.49  5041.8  410.08
  5056.3  411.72  5130.5  416.54  5153.4  421.44    5181  422.68  5211.6  423.77
  5364.9  429.75  5542.8  434.47  5549.9  435.81  5562.9  436.47  5607.8  435.89
#Mann= 9 ,-1 , 0
  4529.8     .05       0  4553.1      .1       0  4740.4     .05       0
  4958.8      .1       0  4973.9     .05       0  4975.7     .03       0
  4979.7     .05       0    5181      .1       0  5211.6     .05       0
Bank Sta=4942.4,5056.3
XS Rating Curve= 0 ,0
Exp/Cntr=0.3,0.1

Type RM Length L Ch R = 1 ,8865    ,285,285,285
BEGIN DESCRIPTION:
Mapping XS 268a67a9
END DESCRIPTION:
XS GIS Cut Line= 4
      3516356.34     10404972.02      3516582.05     10404965.08
      3516957.05     10404791.47      3517092.22     10404476.07
#Sta/Elev= 30
  4479.9  427.44  4555.7  426.94  4607.2  425.09  4652.8  422.65  4657.8  423.15
  4703.2  419.92  4769.9  416.82  4895.6  413.83  4941.4  412.29  4964.3  409.97
  4968.6  408.82  4970.3  408.01  4992.7  406.66  5013.6  406.52  5013.9  406.02
  5017.6  406.52  5038.6  406.52    5056  408.59  5078.9  412.27  5151.4  415.51
  5168.8  415.72  5192.4  414.72    5245  415.47  5250.4  414.92  5292.1   416.6
  5321.1   419.1  5326.6  420.39  5344.7  420.52  5379.9  423.33  5462.1  427.49
#Mann= 5 ,-1 , 0
  4479.9      .1       0  4607.2     .05       0  4895.6      .1       0
  5013.6     .07       0  5017.6      .1       0
Bank Sta=4968.6,5056
XS Rating Curve= 0 ,0
Exp/Cntr=0.3,0.1

Type RM Length L Ch R = 1 ,8580    ,109,109,109
BEGIN DESCRIPTION:
Mapping XS 190a4be2
END DESCRIPTION:
XS GIS Cut Line= 5
      3516415.36     10405100.48      3516637.61     10405190.77
        3516964.     10405097.02       3517151.5     10405013.69
      3517338.03     10404854.79
#Sta/Elev= 30
  4407.1  423.83  4552.8  420.23  4646.7  415.49  4698.3  414.11  4765.8  410.85
  4843.6  409.95  4901.4  408.12  4922.2  405.53    4941  405.52  4941.2  405.02
  4944.7  405.02    4945  405.52  5093.9  405.94  5104.9  407.03  5110.5  408.34
    5116  406.56  5126.8  409.49  5133.7  410.21  5139.2  409.17  5148.7  410.69
  5180.3  411.63  5200.9  413.25  5215.2  413.91    5236     414  5278.8  416.26
  5304.3  416.89  5332.1  417.91  5371.1  419.89  5434.8  422.21  5436.8     423
#Mann= 5 ,-1 , 0
  4407.1     .05       0    4941    .033       0    4945     .05       0
  5304.3      .1       0  5332.1     .05       0
Bank Sta=4901.4,5110.5
XS Rating Curve= 0 ,0
Exp/Cntr=0.3,0.1

Type RM Length L Ch R = 1 ,8471    ,87,87,87
BEGIN DESCRIPTION:
Mapping XS a938ba34
END DESCRIPTION:
XS GIS Cut Line= 5
      3516588.99     10405301.89      3516825.11     10405281.05
      3517029.97     10405183.83      3517193.16     10405121.33
      3517345.92     10404982.46
#Sta/Elev= 30
  4528.1  415.59  4611.5  413.87  4651.7  412.61  4771.4  408.12  4799.7  407.69
  4816.8  406.49  4822.4  406.94  4828.2  405.97  4859.4  405.53  4859.7  405.03
  4863.2  405.03  4863.4  405.53  4867.8  406.19  4913.3  407.69  4918.8  408.47
    4950  408.91  4958.8  408.32  4981.5  408.23    4987   408.7  5011.1  407.71
  5016.5  408.39 5027.18  408.75  5058.4  408.47  5095.9  409.24  5144.1  411.07
  5184.8  413.24  5250.5  415.59  5342.4  419.88  5349.8  420.53  5373.1  421.38
#Mann= 5 ,-1 , 0
  4528.1     .05       0  4651.7     .07       0    4950     .05       0
 5027.18      .1       0  5184.8     .05       0
#XS Ineff= 1 ,-1
 4737.21 4944.33  408.88
Permanent Ineff=
       T
Bank Sta=4950,5027.18
XS Rating Curve= 0 ,0
Exp/Cntr=0.3,0.1

Type RM Length L Ch R = 1 ,8384    ,419,419,419
BEGIN DESCRIPTION:
Mapping XS 2fb2a9bf
END DESCRIPTION:
XS GIS Cut Line= 5
      3516727.92     10405371.32      3516908.44     10405326.19
      3517099.41      10405249.8      3517314.69     10405135.22
      3517387.37     10405021.01
#Sta/Elev= 30
  4639.4  412.29  4658.9  412.05  4741.4  408.31  4777.5  405.37  4818.7   404.9
  4840.2  405.38  4861.7  404.29  4905.2  404.74  4937.2  404.29  4947.9  403.25
  4961.5  399.74  4969.4  398.22  4991.1     396  5007.9  395.52  5008.2  395.02
  5011.7  395.02  5011.9  395.52  5023.3  396.79  5029.9  398.27  5034.5  398.27
  5038.9  399.88  5045.5  401.51  5060.8   403.5  5077.2  407.56  5090.8  409.33
  5167.6  413.03    5334  419.31  5355.2  420.69  5406.8  422.69  5410.4  423.37
#Mann= 5 ,-1 , 0
  4639.4     .05       0  4905.2      .1       0  5007.9     .07       0
  5011.9      .1       0  5167.6     .05       0
Bank Sta=4961.5,5038.9
XS Rating Curve= 0 ,0
Exp/Cntr=0.3,0.1

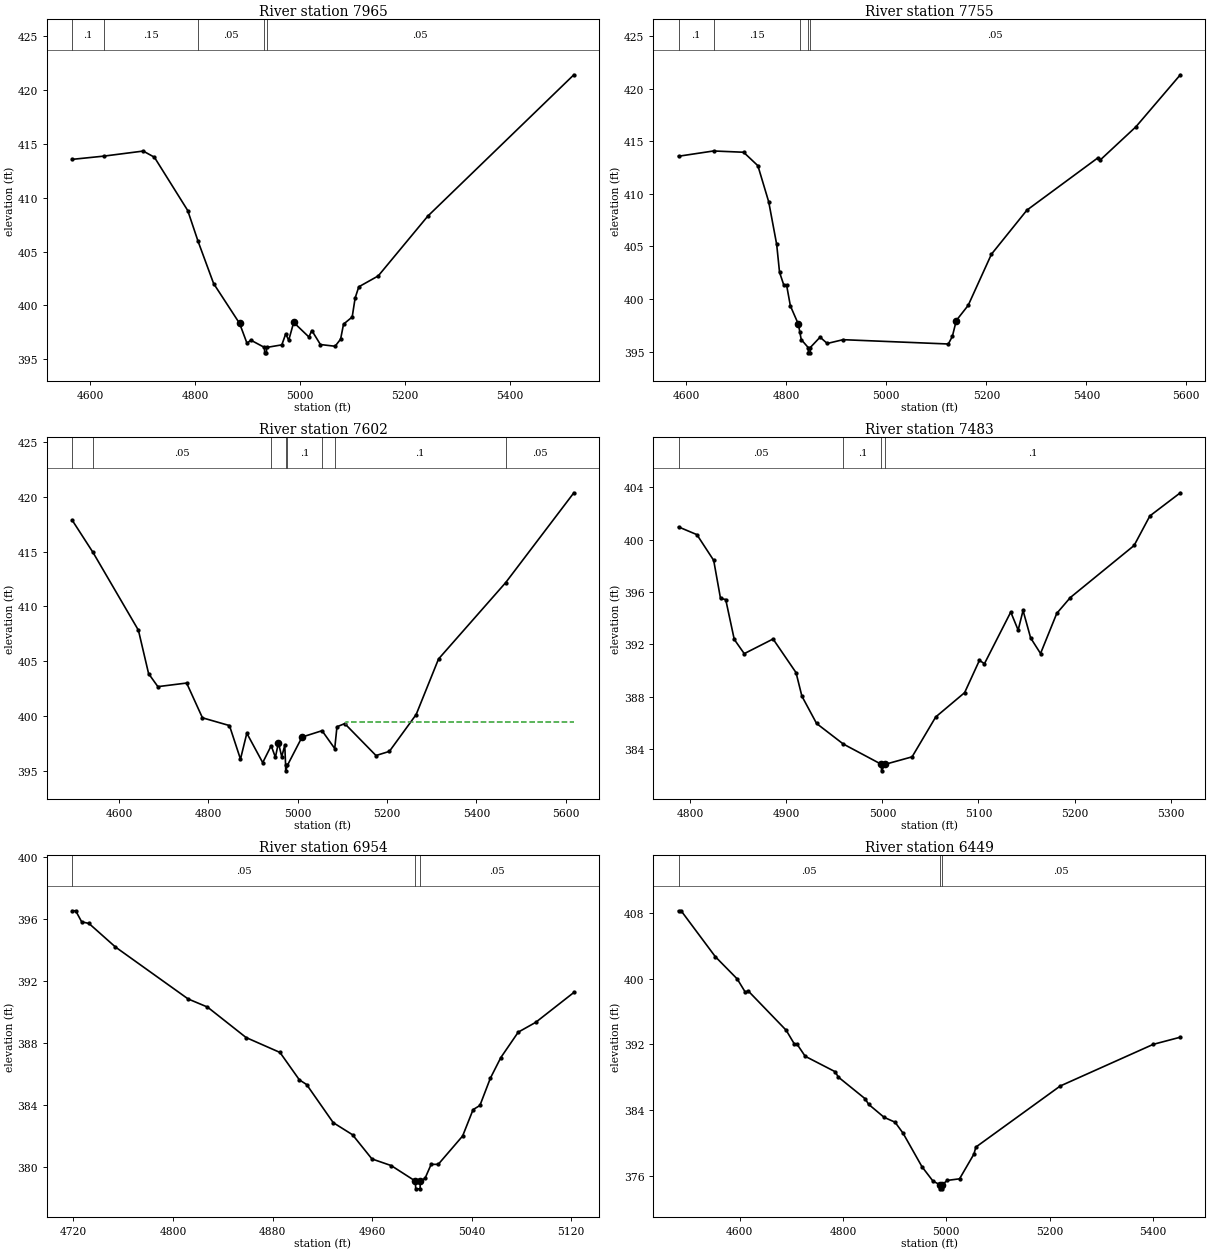
Type RM Length L Ch R = 1 ,7965    ,210,210,210
BEGIN DESCRIPTION:
Mapping XS 7157ee9d
END DESCRIPTION:
XS GIS Cut Line= 4
      3516950.12      10405961.6      3517200.11     10405715.08
      3517352.88     10405423.41      3517436.22     10405159.51
#Sta/Elev= 30
  4565.4  413.54  4625.8  413.84  4701.1  414.31  4722.4  413.74    4786   408.8
  4805.7  405.95  4835.4  402.03    4885  398.33  4899.1  396.49  4906.2  396.79
  4932.4  396.11  4932.7  395.61  4936.2  395.61  4936.4  396.11  4965.5  396.35
  4972.9  397.37  4978.6  396.77  4988.1  398.43  5017.1  397.08  5022.7  397.68
  5039.1  396.38  5067.1  396.22  5077.6  396.88  5083.2  398.27  5099.7  398.93
  5105.3  400.69  5112.3  401.73  5149.4  402.74  5243.9  408.28  5522.5  421.38
#Mann= 5 ,-1 , 0
  4565.4      .1       0  4625.8     .15       0  4805.7     .05       0
  4932.4    .033       0  4936.4     .05       0
Bank Sta=4885,4988.1
XS Rating Curve= 0 ,0
Exp/Cntr=0.3,0.1

Type RM Length L Ch R = 1 ,7755    ,153,153,153
BEGIN DESCRIPTION:
Mapping XS 32b6acd9
END DESCRIPTION:
XS GIS Cut Line= 4
      3517078.57     10406024.11        3517339.     10405878.27
      3517467.47     10405652.58      3517529.97     10405211.56
#Sta/Elev= 30
  4584.4  413.57  4654.4  414.07  4714.5  413.95  4743.1  412.67  4764.8  409.23
  4780.7  405.19  4786.4  402.55  4794.7  401.36  4800.5  401.33  4808.1  399.35
  4824.1  397.61  4826.9  396.89  4829.8  396.15  4843.8  395.39  4844.1  394.89
  4847.6  394.89  4847.8  395.39  4867.5  396.38  4881.8  395.78  4913.5  396.14
    5124  395.73  5132.1  396.46  5139.9  397.96  5163.7   399.4  5210.2  404.26
  5281.2  408.45  5423.2  413.42  5428.2  413.23  5499.2  416.37    5588  421.31
#Mann= 5 ,-1 , 0
  4584.4      .1       0  4654.4     .15       0  4826.9     .05       0
  4843.8    .033       0  4847.8     .05       0
Bank Sta=4824.1,5139.9
XS Rating Curve= 0 ,0
Exp/Cntr=0.3,0.1

Type RM Length L Ch R = 1 ,7602    ,119,119,119
BEGIN DESCRIPTION:
Mapping XS 97aed561
END DESCRIPTION:
XS GIS Cut Line= 6
      3517144.58     10406173.39      3517422.33     10405961.61
      3517519.55     10405871.33      3517557.75     10405794.94
      3517547.33       10405413.      3517564.69     10405239.41
#Sta/Elev= 30
  4494.5  417.91  4541.3  414.95  4643.1  407.83  4665.9  403.86  4686.7  402.67
  4751.1     403  4786.5  399.82    4847  399.11  4871.7  396.04  4885.9  398.41
  4921.5  395.72  4940.5  397.27  4949.9  396.21  4956.7  397.54  4964.1  396.26
  4970.9   397.3  4972.8  395.47    4973  394.97  4976.8  395.47  5009.6  398.06
  5054.4  398.64  5082.8  397.01  5087.8     399  5105.2  399.29  5175.2  396.37
  5205.2  396.75  5265.2  400.12  5315.3   405.2  5465.6  412.18  5618.4   420.4
#Mann= 8 ,-1 , 0
  4494.5      .1       0  4541.3     .05       0  4940.5      .1       0
  4972.8     .07       0  4976.8      .1       0  5054.4     .05       0
  5082.8      .1       0  5465.6     .05       0
#XS Ineff= 2 , 0
                         5108.14          399.43
Permanent Ineff=
       T       T
Bank Sta=4956.7,5009.6
XS Rating Curve= 0 ,0
Exp/Cntr=0.3,0.1

Type RM Length L Ch R = 1 ,7483    ,529,529,529
BEGIN DESCRIPTION:
DUCK CREEK TRIB 22 31 0
END DESCRIPTION:
XS GIS Cut Line= 3
      3517550.78     10406045.77      3517660.14     10405761.08
      3517604.58     10405550.98
#Sta/Elev= 30
  4787.8  400.97  4806.9  400.38  4824.4  398.41  4831.5   395.5  4836.9  395.42
  4845.8  392.37  4856.2  391.28  4886.2   392.4  4910.1  389.83  4916.2  388.03
  4931.5  385.94  4959.3  384.37  4998.9  382.82  4999.1  382.32  5002.9  382.82
  5030.9  383.39  5055.5  386.44  5085.6   388.3    5101  390.77  5106.2  390.51
  5133.6  394.46  5141.3  393.08  5146.4  394.58  5154.3  392.48  5164.6  391.29
  5181.5  394.36  5195.6  395.57    5262  399.55  5278.4  401.81  5310.1  403.58
#Mann= 4 ,-1 , 0
  4787.8     .05       0  4959.3      .1       0  4998.9     .07       0
  5002.9      .1       0
Bank Sta=4998.9,5002.9
XS Rating Curve= 0 ,0
Exp/Cntr=0.3,0.1

Type RM Length L Ch R = 1 ,6954    ,505,505,505
BEGIN DESCRIPTION:
DUCK CREEK TRIB 22 16 0
END DESCRIPTION:
XS GIS Cut Line= 3
      3517842.14     10406091.62      3518092.11     10405941.64
       3518192.1     10405891.65
#Sta/Elev= 30
  4718.9  396.55  4721.8  396.55  4726.6  395.84  4732.5  395.73  4753.8  394.21
  4812.2  390.86  4827.7  390.34  4858.8  388.37    4886  387.41  4901.6  385.64
  4907.4  385.34  4928.8  382.88  4944.3   382.1  4959.9  380.54  4975.4  380.11
  4994.8  379.11  4995.1  378.61  4998.6  378.61  4998.8  379.11  5002.6  379.29
  5007.5  380.19  5013.2  380.19  5032.8  382.02  5041.2  383.72  5046.7  383.99
  5055.1  385.75  5063.5  387.08  5077.5  388.72  5091.5  389.35  5122.2  391.28
#Mann= 3 ,-1 , 0
  4718.9     .05       0  4994.8     .03       0  4998.8     .05       0
Bank Sta=4994.8,4998.8
XS Rating Curve= 0 ,0
Exp/Cntr=0.3,0.1

Type RM Length L Ch R = 1 ,6449    ,206,206,206
BEGIN DESCRIPTION:
DUCK CREEK TRIB 22 2 0
END DESCRIPTION:
XS GIS Cut Line= 3
      3517758.63     10406695.12      3518250.84     10406392.82
      3518253.27     10405999.25
#Sta/Elev= 30
  4481.9  408.26  4486.9  408.26    4553  402.68  4595.5  399.96    4611  398.36
  4616.8   398.5  4690.3  393.71  4705.7  392.08  4711.5     392    4727  390.55
    4785  388.67  4791.1  388.02    4843  385.38  4849.8   384.7  4879.7  383.12
    4901  382.52  4916.4  381.19  4953.1   377.1  4974.4  375.35  4987.8  374.91
  4988.1  374.41  4991.6  374.41  4991.8  374.91  5002.3  375.44  5025.8  375.63
  5053.7  378.65  5057.3  379.49  5220.7  386.93  5400.7     392  5453.1  392.87
#Mann= 3 ,-1 , 0
  4481.9     .05       0  4987.8     .03       0  4991.8     .05       0
Bank Sta=4987.8,4991.8
XS Rating Curve= 0 ,0
Exp/Cntr=0.3,0.1

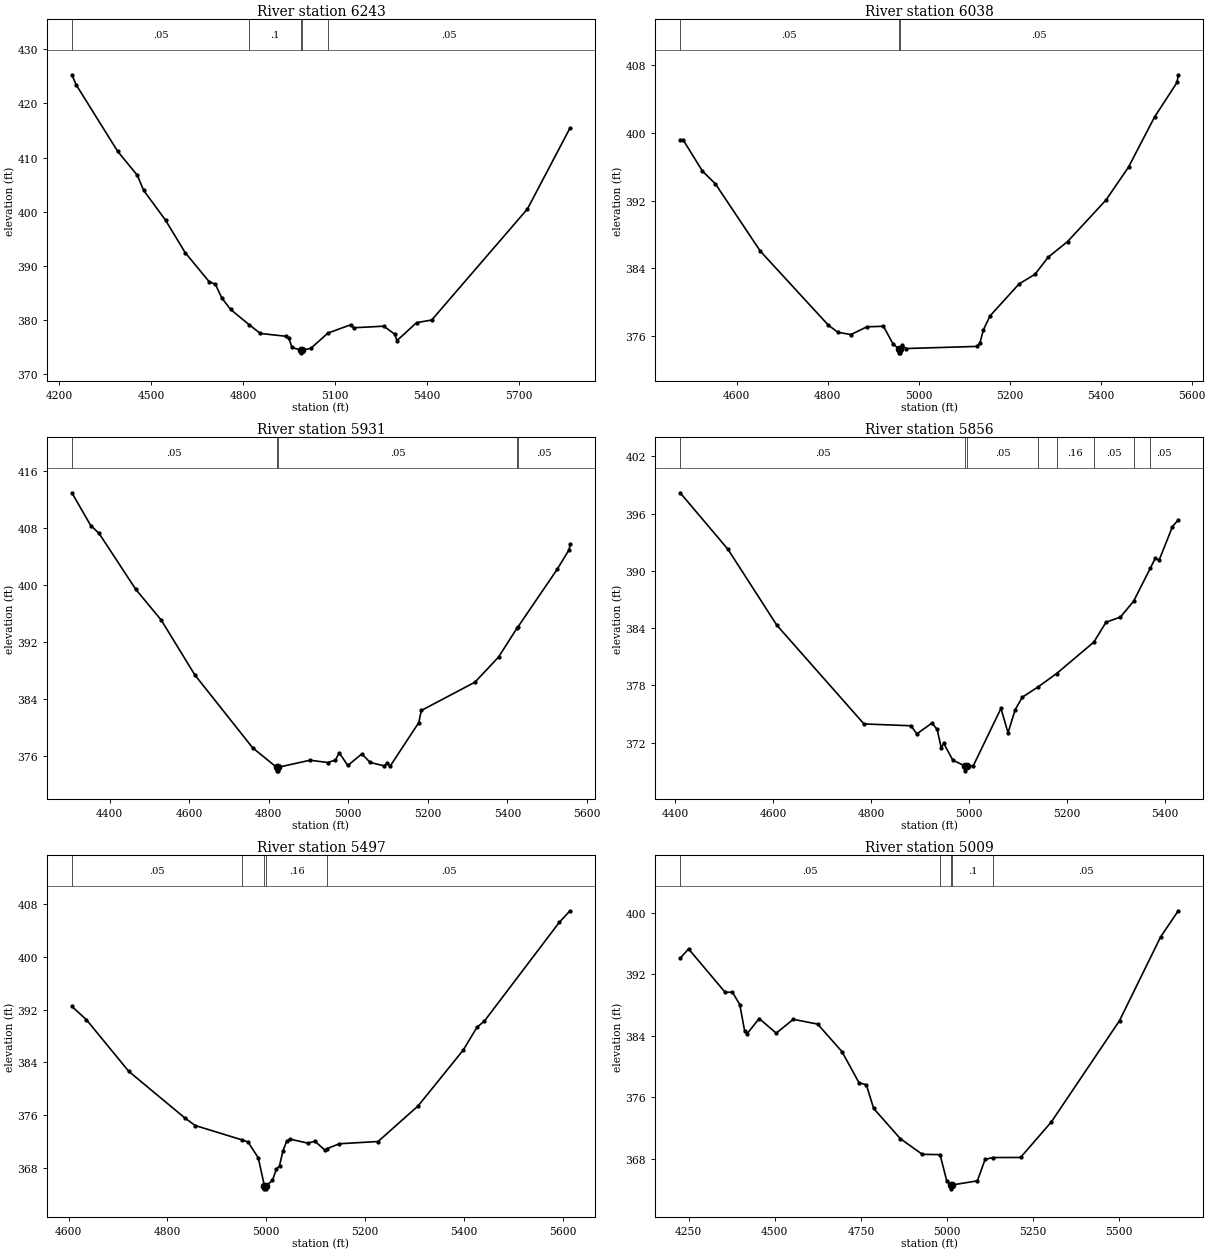
Type RM Length L Ch R = 1 ,6243    ,205,205,205
BEGIN DESCRIPTION:
DUCK CREEK TRIB 22 14 1
END DESCRIPTION:
XS GIS Cut Line= 4
      3517846.46     10407095.76      3518321.71      10406700.8
      3518368.12     10406418.31      3518923.08     10405957.12
#Sta/Elev= 30
  4240.7  425.28  4254.8  423.42  4390.2  411.14    4454  406.75  4474.8  403.96
  4546.4  398.43  4610.2  392.47  4688.3  387.11  4709.2  386.59    4730  384.08
  4758.6  381.97  4819.5  379.13  4855.7  377.53  4938.9  377.01  4948.8  376.63
  4959.1  374.96  4987.5  374.45  4987.8  373.95  4991.5  374.45  5020.1  374.76
  5076.1  377.59  5152.1  379.16  5159.9  378.58  5258.8  378.87    5294   377.4
  5301.8  376.21  5365.6  379.52  5415.1  380.01  5727.6  400.52  5866.5  415.46
#Mann= 5 ,-1 , 0
  4240.7     .05       0  4819.5      .1       0  4987.5     .07       0
  4991.5      .1       0  5076.1     .05       0
Bank Sta=4987.5,4991.5
XS Rating Curve= 0 ,0
Exp/Cntr=0.3,0.1

Type RM Length L Ch R = 1 ,6038    ,107,107,107
BEGIN DESCRIPTION:
DUCK CREEK TRIB 22 12 3
END DESCRIPTION:
XS GIS Cut Line= 2
      3518127.22     10406986.13      3518967.31     10406283.16
#Sta/Elev= 30
  4475.3  399.19  4481.7  399.19  4524.3  395.48  4552.9  393.97  4651.8     386
  4801.4  377.25  4822.3  376.42  4850.9  376.15    4886  377.07  4922.4  377.13
  4943.3  375.05  4955.6  374.49  4955.8  373.99  4959.3  373.99  4959.6  374.49
  4964.1  374.87  4971.9   374.5    5128  374.75  5134.6  375.18  5142.3  376.73
  5156.7  378.36  5220.4  382.13  5255.6  383.28  5284.2  385.28  5327.1  387.14
  5411.7  392.06  5461.2  395.95  5518.4  401.87  5567.9  405.96  5570.7  406.87
#Mann= 3 ,-1 , 0
  4475.3     .05       0  4955.6     .03       0  4959.6     .05       0
Bank Sta=4955.6,4959.6
XS Rating Curve= 0 ,0
Exp/Cntr=0.3,0.1

Type RM Length L Ch R = 1 ,5931    ,75,75,75
BEGIN DESCRIPTION:
DUCK CREEK TRIB 22 15 0
END DESCRIPTION:
XS GIS Cut Line= 6
      3518183.67       10407270.      3518489.23     10406931.46
      3518586.45     10406749.16      3518732.28     10406559.93
      3518850.34     10406454.02      3519030.44     10406386.48
#Sta/Elev= 30
  4304.9   412.9  4352.3   408.3  4373.3   407.2  4465.2  399.37  4529.4  395.05
  4613.9  387.35  4759.4  377.11  4819.6  374.38  4819.9  373.88  4823.4  373.88
  4823.6  374.38  4903.8  375.37  4947.7  375.05  4967.5  375.38    4977  376.42
  4998.7  374.63    5034  376.26  5054.8  375.06  5090.7  374.57  5098.3     375
  5104.6  374.49  5177.2  380.66  5183.5  382.35  5318.3  386.32  5377.6  389.84
  5423.9  393.89  5425.9  394.03  5525.1  402.16  5555.4  404.94  5557.4  405.66
#Mann= 5 ,-1 , 0
  4304.9     .05       0  4819.6     .03       0  4823.6     .05       0
  5423.9     .16       0  5425.9     .05       0
Bank Sta=4819.6,4823.6
XS Rating Curve= 0 ,0
Exp/Cntr=0.3,0.1

Type RM Length L Ch R = 1 ,5856    ,359,359,359
BEGIN DESCRIPTION:
DUCK CREEK TRIB 22 14 0
END DESCRIPTION:
XS GIS Cut Line= 4
      3518447.99     10407323.06      3518647.63     10406793.57
      3518730.11     10406682.57      3518982.72     10406496.68
#Sta/Elev= 30
  4409.7  398.17  4507.4  392.25  4607.3   384.3  4785.3  373.97  4881.4  373.78
  4893.3  372.93  4924.2  374.06  4934.9  373.39    4943  371.48  4948.3  371.93
  4966.9  370.17  4992.1  369.56  4992.3  369.06  4996.1  369.56  5008.7   369.6
  5065.2   375.6  5079.6  373.04  5094.2  375.46  5108.8  376.77  5140.6  377.83
    5179  379.25    5255  382.54  5279.8  384.62  5309.1  385.15  5336.2  386.82
  5370.6   390.3  5380.1  391.29  5388.5  391.14  5415.6  394.63  5427.5  395.34
#Mann= 8 ,-1 , 0
  4409.7     .05       0  4992.1     .07       0  4996.1     .05       0
  5140.6     .05       0    5179     .16       0    5255     .05       0
  5336.2     .16       0  5370.6     .05       0
Bank Sta=4992.1,4996.1
XS Rating Curve= 0 ,0
Exp/Cntr=0.3,0.1

Type RM Length L Ch R = 1 ,5497    ,488,488,488
BEGIN DESCRIPTION:
DUCK CREEK TRIB 22 12 2
END DESCRIPTION:
XS GIS Cut Line= 3
      3518531.74     10407322.93      3519073.41     10406878.49
      3519240.08      10406619.8
#Sta/Elev= 30
  4606.5  392.47  4635.7  390.48  4721.8  382.64  4835.2   375.6  4856.1  374.46
  4950.7  372.29    4963  371.97  4983.8  369.57  4996.1  365.38  4996.4  364.88
  4999.9  364.88  5000.1  365.38  5012.5  366.16  5020.4  367.85  5026.8  368.38
  5033.8  370.61  5041.2  372.08  5047.7  372.41  5084.2  371.79  5098.5  372.08
  5119.4  370.68  5123.4  370.97  5148.1   371.7  5226.3  372.04  5307.2  377.41
  5398.6  385.86  5426.5  389.32  5441.7  390.27  5592.9  405.17  5614.9  406.94
#Mann= 5 ,-1 , 0
  4606.5     .05       0  4950.7     .16       0  4996.1     .07       0
  5000.1     .16       0  5123.4     .05       0
Bank Sta=4996.1,5000.1
XS Rating Curve= 0 ,0
Exp/Cntr=0.3,0.1

Type RM Length L Ch R = 1 ,5009    ,472,472,472
BEGIN DESCRIPTION:
DUCK CREEK TRIB 22 12 1
END DESCRIPTION:
XS GIS Cut Line= 5
      3518637.11     10407911.42      3518995.72     10407564.97
      3519195.72     10407364.97      3519345.72     10407064.97
      3519411.42     10406741.25
#Sta/Elev= 30
  4224.9  394.07  4249.4  395.29  4355.7  389.64  4376.8  389.67  4398.1  388.05
  4412.3  384.61  4419.2  384.25  4454.5  386.23  4504.1  384.33  4553.5  386.13
  4624.3  385.51    4695  381.93  4744.5  377.88  4765.8  377.62    4787  374.54
  4864.7   370.6  4928.4  368.57    4980  368.53  4999.1  365.16  5010.6  364.58
  5010.8  364.08  5014.6  364.58  5088.4  365.12  5110.7   367.9  5133.2  368.15
  5213.8  368.16  5303.3  372.78  5501.5  385.97  5620.7  396.85  5672.1  400.25
#Mann= 5 ,-1 , 0
  4224.9     .05       0    4980      .1       0  5010.6     .07       0
  5014.6      .1       0  5133.2     .05       0
Bank Sta=5010.6,5014.6
XS Rating Curve= 0 ,0
Exp/Cntr=0.3,0.1

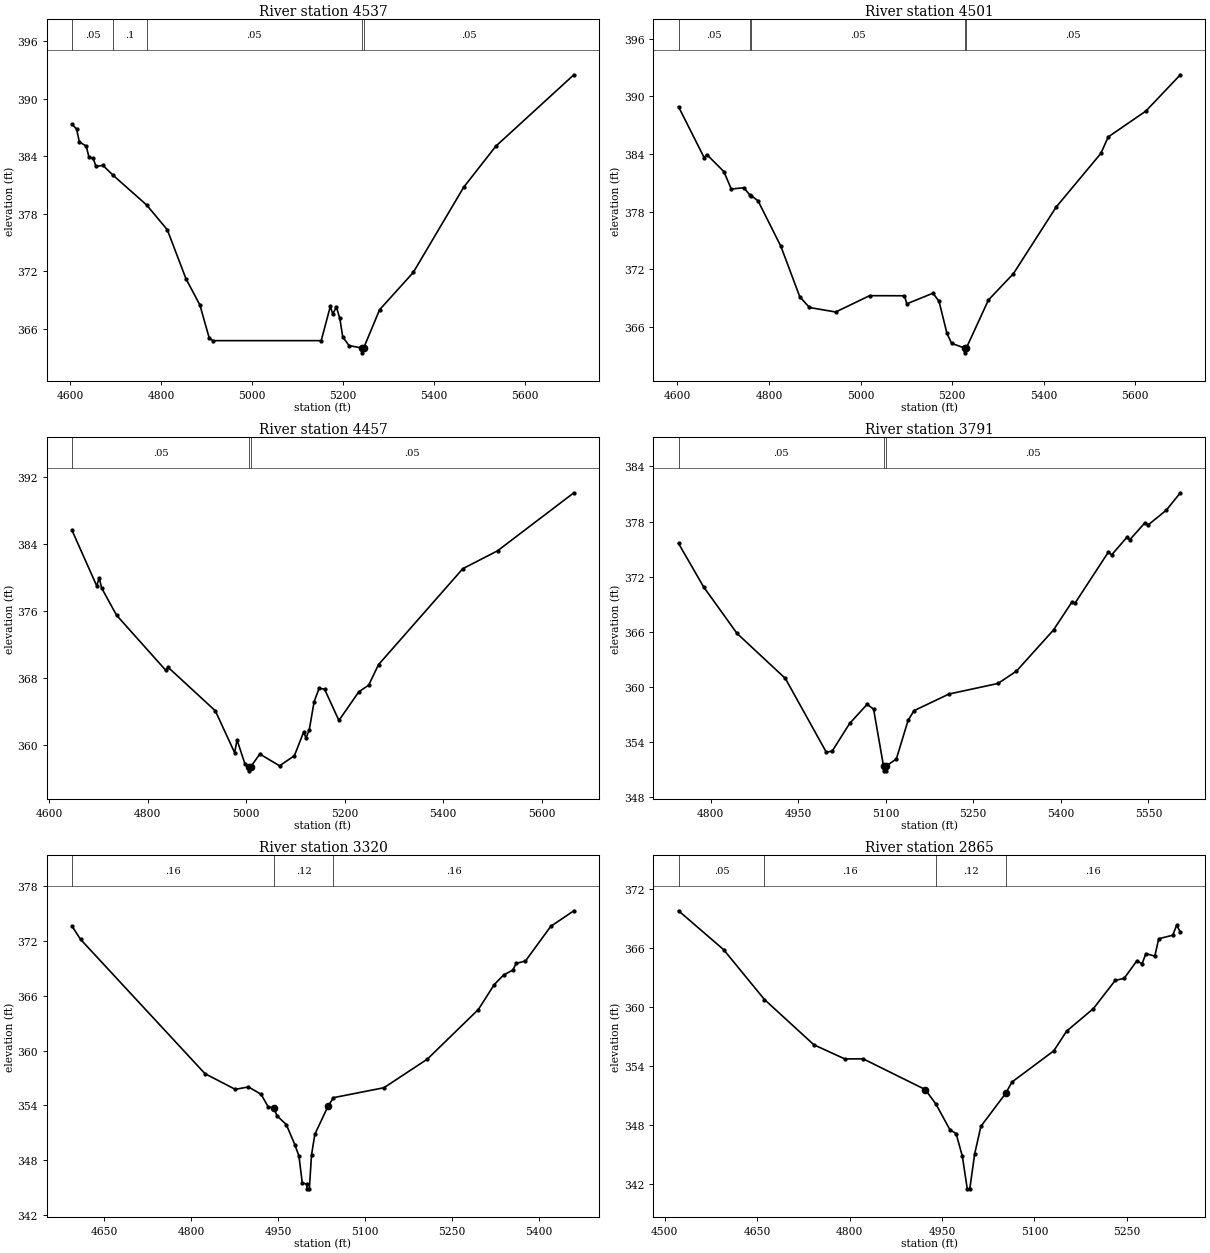
Type RM Length L Ch R = 1 ,4537    ,36,36,36
BEGIN DESCRIPTION:
DUCK CREEK TRIB 22 12 0
END DESCRIPTION:
XS GIS Cut Line= 5
      3519634.17     10407892.37      3519538.69     10407741.33
      3519580.35     10407550.36      3519535.21     10407348.97
      3519599.45     10406831.58
#Sta/Elev= 30
  4604.6  387.33  4614.6  386.82  4620.5   385.5  4635.8  385.04  4641.7  383.89
  4651.1  383.79    4657  382.93  4672.2  383.05  4694.6  382.02  4768.3  378.92
  4813.7  376.34  4854.6  371.25  4885.3   368.5  4905.8  365.06  4913.8  364.79
  5151.7  364.79  5171.8  368.37  5176.9  367.57  5185.1  368.28  5192.5  367.12
    5199  365.18  5212.7  364.28  5240.9  364.02  5241.2  363.52  5244.9  364.02
  5279.9  368.01  5353.8  371.89  5464.6  380.77  5535.1  385.04  5706.5  392.48
#Mann= 5 ,-1 , 0
  4604.6     .05       0  4694.6      .1       0  4768.3     .05       0
  5240.9     .03       0  5244.9     .05       0
Bank Sta=5240.9,5244.9
XS Rating Curve= 0 ,0
Exp/Cntr=0.3,0.1

Type RM Length L Ch R = 1 ,4501    ,44,44,44
BEGIN DESCRIPTION:
DUCK CREEK TRIB 22 17 0
END DESCRIPTION:
XS GIS Cut Line= 6
      3519665.43     10407894.13      3519585.56     10407753.49
      3519585.56     10407673.62      3519622.02     10407562.51
      3519569.94     10407361.12      3519625.32     10406834.99
#Sta/Elev= 30
  4602.6  388.93  4658.6  383.63  4664.3  383.96  4701.8  382.17  4717.7  380.37
  4745.1   380.5  4758.7  379.73  4761.9  379.66  4776.2  379.14  4826.2  374.39
  4867.3  369.16  4888.4  368.04  4945.8  367.57  5019.8  369.27  5095.9  369.26
    5101  368.42  5158.3  369.53  5171.4  368.67  5188.7  365.34  5198.8  364.31
    5227  363.82  5227.2  363.32    5231  363.82  5279.2  368.82  5333.9  371.57
  5426.9  378.48  5524.9  384.09  5540.7  385.79  5622.9  388.48  5698.2  392.26
#Mann= 5 ,-1 , 0
  4602.6     .05       0  4758.7      .1       0  4761.9     .05       0
    5227     .03       0    5231     .05       0
Bank Sta=5227,5231
XS Rating Curve= 0 ,0
Exp/Cntr=0.3,0.1

Type RM Length L Ch R = 1 ,4457    ,666,666,666
BEGIN DESCRIPTION:
DUCK CREEK TRIB 22 11 0
END DESCRIPTION:
XS GIS Cut Line= 3
      3519681.05     10407871.56      3519644.59      10407364.6
      3519698.41     10406857.62
#Sta/Elev= 30
  4646.8  385.64  4696.8  379.03  4701.8  379.98  4706.9  378.76    4737  375.53
  4836.7  368.96  4841.7  369.31  4937.5  364.11  4976.6  359.12  4981.6  360.63
  4997.6  357.76  5005.6  357.45  5005.9  356.95  5009.6  357.45  5027.7  358.96
  5067.8  357.55  5097.9  358.76  5116.5  361.56  5121.5  360.88    5128  361.83
    5138  365.22    5148   366.8  5159.1   366.7  5188.2  362.96  5228.4  366.37
  5248.6  367.18  5268.6  369.63  5439.6  381.08    5510  383.21  5664.9  390.14
#Mann= 3 ,-1 , 0
  4646.8     .05       0  5005.6     .03       0  5009.6     .05       0
Bank Sta=5005.6,5009.6
XS Rating Curve= 0 ,0
Exp/Cntr=0.3,0.1

Type RM Length L Ch R = 1 ,3791    ,471,471,471
BEGIN DESCRIPTION:
DUCK CREEK TRIB 22 13 0
END DESCRIPTION:
XS GIS Cut Line= 3
      3520282.61     10407884.35      3520303.44     10407410.43
      3520178.57     10407046.22
#Sta/Elev= 30
  4745.2  375.61    4788  370.89  4845.3  365.81  4928.1   360.9  4998.2  352.87
  5008.2  352.96  5038.2  355.99  5068.2  358.08  5079.3  357.55  5096.3  351.33
  5096.5  350.83    5100  350.83  5100.3  351.33  5118.3  352.13  5138.3  356.32
  5148.3  357.38  5208.4   359.2  5292.3  360.35    5324   361.7  5387.4  366.18
    5419  369.23  5424.3  369.11  5481.5  374.68  5486.8  374.35  5512.8  376.26
  5518.1  376.01  5544.1  377.87  5549.4  377.62  5580.7  379.24  5604.6  381.13
#Mann= 3 ,-1 , 0
  4745.2     .05       0  5096.3     .03       0  5100.3     .05       0
Bank Sta=5096.3,5100.3
XS Rating Curve= 0 ,0
Exp/Cntr=0.3,0.1

Type RM Length L Ch R = 1 ,3320    ,455,455,455
BEGIN DESCRIPTION:
DUCK CREEK TRIB 22 9 0
END DESCRIPTION:
XS GIS Cut Line= 3
       3520415.4     10407965.13      3520639.38     10407808.87
      3520925.82     10407290.67
#Sta/Elev= 30
  4594.7  373.62  4609.3  372.19  4823.9  357.47  4876.1  355.75  4898.8  356.02
  4920.6  355.21  4933.2   353.8  4942.3  353.75  4948.1  352.85  4964.1  351.89
  4978.9  349.68  4985.9  348.43  4991.6  345.51  4999.4  345.35  4999.8  344.85
  5003.8  344.85  5007.6  348.57  5013.3  350.83    5036   353.9  5045.4  354.84
  5132.5  355.93  5207.4  359.07  5295.2   364.5  5322.6  367.23  5338.7  368.28
  5354.7  368.83  5360.4  369.55  5376.5  369.82    5420  373.61  5459.9  375.32
#Mann= 3 ,-1 , 0
  4594.7     .16       0  4942.3     .12       0  5045.4     .16       0
Bank Sta=4942.3,5036
XS Rating Curve= 0 ,0
Exp/Cntr=0.3,0.1

Type RM Length L Ch R = 1 ,2865    ,187,187,187
BEGIN DESCRIPTION:
DUCK CREEK TRIB 22 8 0
END DESCRIPTION:
XS GIS Cut Line= 3
      3520483.13     10408032.83      3521056.05     10407983.35
      3521201.85     10407793.28
#Sta/Elev= 30
  4522.2  369.76  4595.3  365.82  4661.7  360.75    4742  356.15  4792.2  354.72
  4821.9  354.73  4922.7  351.61  4940.2  350.12  4962.8  347.53  4972.8  347.14
  4982.9  344.85  4990.9  341.53    4995  341.53    5003  345.09    5013  347.87
  5053.1  351.21  5063.6  352.38  5131.4  355.54  5152.2  357.54  5195.7  359.83
  5231.1  362.69  5245.6   362.9  5266.4  364.69  5274.6  364.37  5280.9  365.41
  5295.4  365.16  5301.7  366.92  5324.5  367.28  5330.8  368.29  5336.8  367.61
#Mann= 4 ,-1 , 0
  4522.2     .05       0  4661.7     .16       0  4940.2     .12       0
  5053.1     .16       0
Bank Sta=4922.7,5053.1
XS Rating Curve= 0 ,0
Exp/Cntr=0.3,0.1