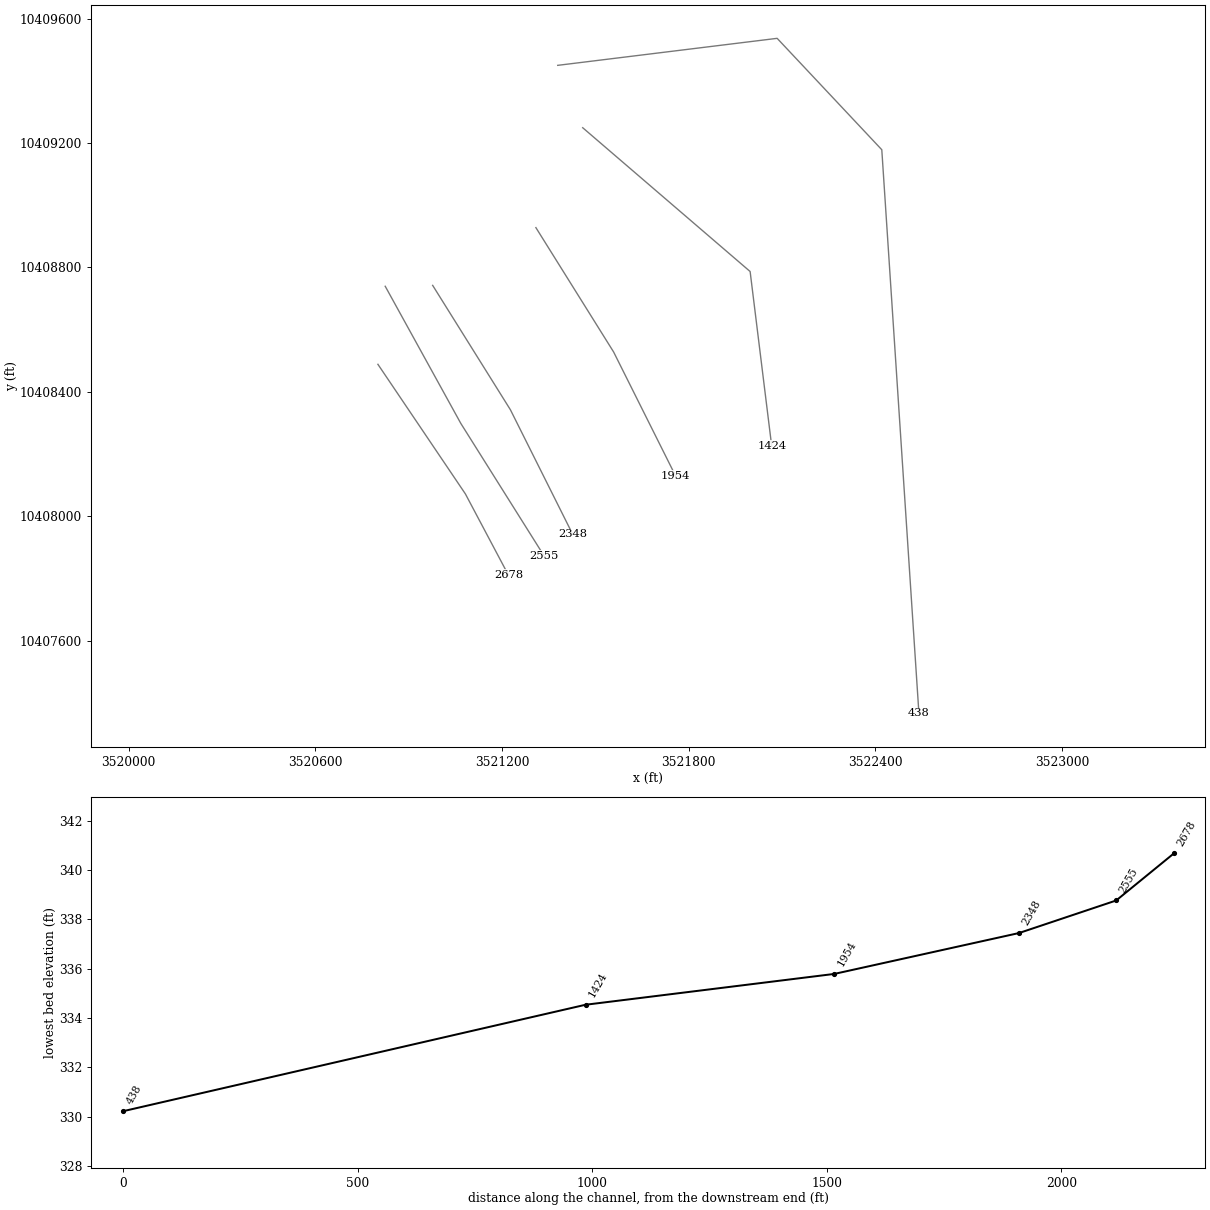
HEC-RAS study DUCK CREEK TRIB 22.prj: DUCK CREEK TRIB 22 Base Level Engineering

--- DUCK CREEK TRIB 22.g01 (geometry) --- (continued)

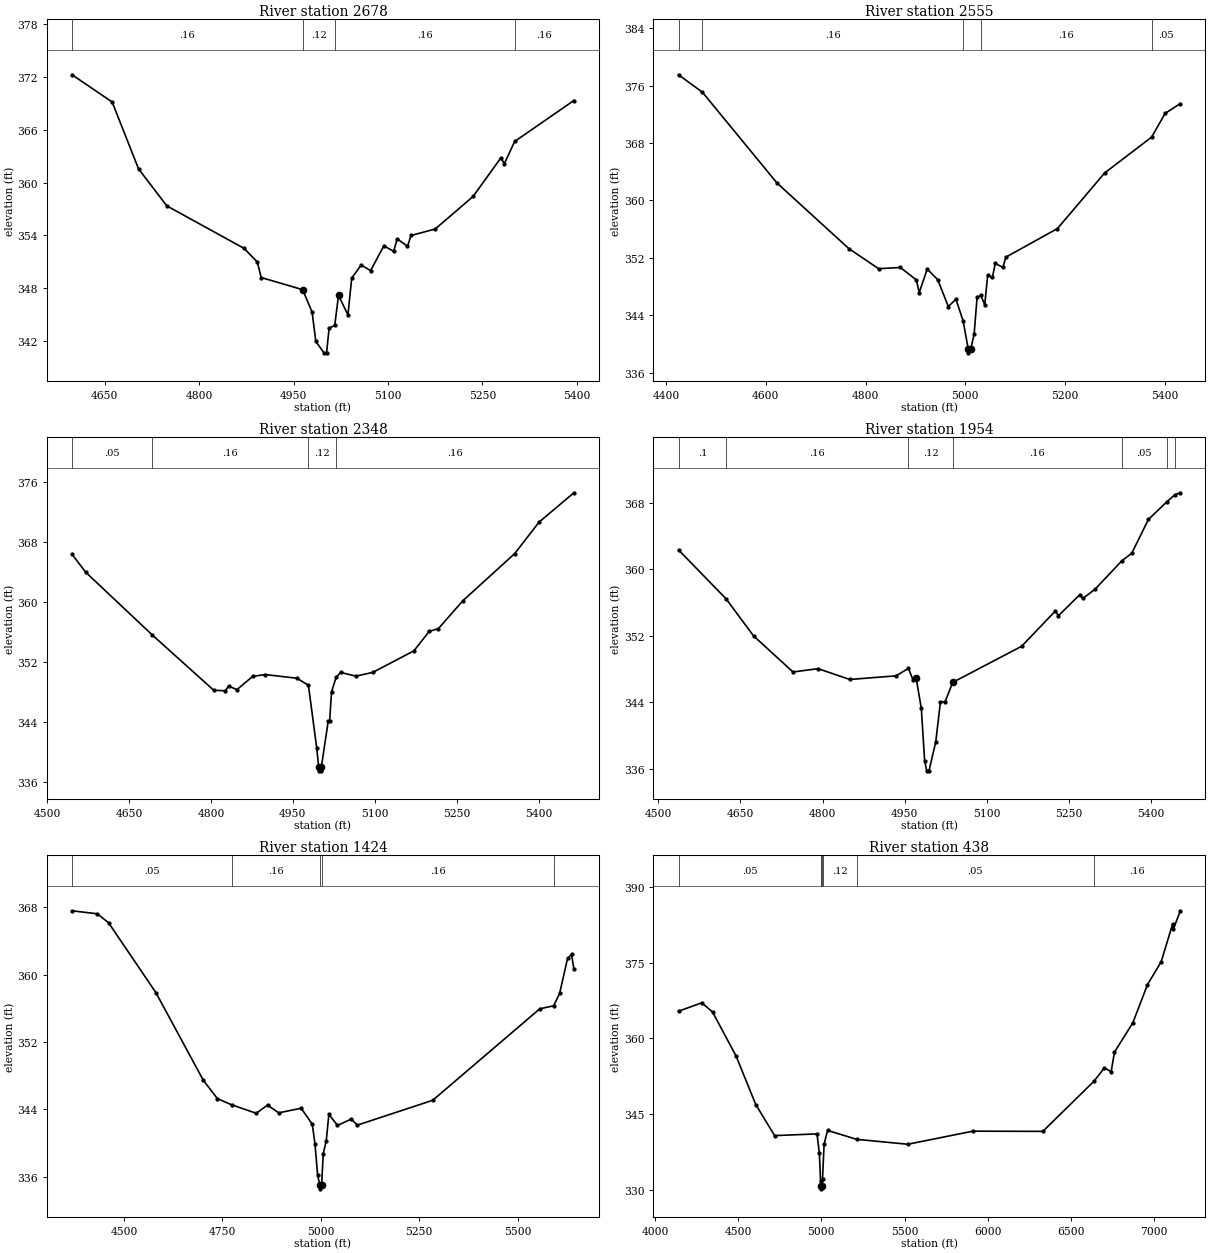
Type RM Length L Ch R = 1 ,2678    ,123,123,123
BEGIN DESCRIPTION:
DUCK CREEK TRIB 22 61
END DESCRIPTION:
XS GIS Cut Line= 3
      3520800.86     10408488.53      3521082.09     10408071.89
      3521220.11     10407811.48
#Sta/Elev= 30
    4598  372.24  4661.7  369.15  4703.7  361.55  4748.6  357.36  4871.5  352.53
  4892.5  350.98  4898.5  349.23  4964.4  347.85  4979.4  345.31  4985.4  341.97
  4998.3  340.68  5002.5  340.68  5006.4  343.47  5015.4   343.8  5021.4  347.19
  5036.4     345  5042.4  349.16  5057.4  350.65  5072.4  350.01  5093.4  352.82
    5109  352.21  5114.7  353.62    5131  352.77  5136.7     354    5175  354.73
  5235.3  358.43  5279.3   362.8    5285  362.16  5301.3  364.67  5395.4  369.32
#Mann= 4 ,-1 , 0
    4598     .16       0  4964.4     .12       0  5015.4     .16       0
  5301.3     .16       0
Bank Sta=4964.4,5021.4
XS Rating Curve= 0 ,0
Exp/Cntr=0.3,0.1

Type RM Length L Ch R = 1 ,2555    ,207,207,207
BEGIN DESCRIPTION:
DUCK CREEK TRIB 22 60
END DESCRIPTION:
XS GIS Cut Line= 3
      3520824.35      10408739.4       3521067.4     10408298.44
      3521334.76      10407873.1
#Sta/Elev= 30
  4425.1   377.5  4473.1  375.06  4622.4  362.43  4766.5  353.29  4826.2  350.49
  4869.7  350.66  4901.8  348.93  4907.6  347.16  4923.6  350.44  4944.7  348.96
  4965.9  345.22  4981.2  346.24  4995.7  343.19  5005.9  339.27  5006.2  338.77
  5010.8  339.27  5017.7   341.4  5023.6  346.52  5031.1  346.78  5038.9  345.46
  5044.8  349.58  5054.2  349.27  5060.1  351.22  5075.4  350.67  5081.3   352.1
  5184.7  356.08  5279.2  363.82  5373.5  368.82  5400.5  372.12    5431  373.49
#Mann= 5 ,-1 , 0
  4425.1     .05       0  4473.1     .16       0  4995.7     .12       0
  5031.1     .16       0  5373.5     .05       0
Bank Sta=5005.9,5010.8
XS Rating Curve= 0 ,0
Exp/Cntr=0.3,0.1

Type RM Length L Ch R = 1 ,2348    ,394,394,394
BEGIN DESCRIPTION:
DUCK CREEK TRIB 22 7 0
END DESCRIPTION:
XS GIS Cut Line= 3
      3520976.85     10408742.28      3521226.84      10408342.3
      3521426.84     10407942.29
#Sta/Elev= 30
  4545.8  366.35  4570.6  363.97  4692.3  355.61  4805.3   348.2  4826.5  348.14
  4832.4  348.76  4847.7  348.29  4876.7  350.06  4899.6   350.3  4957.4  349.81
  4978.6  348.87  4993.9  340.45  4997.4  337.95  4997.7  337.45  5001.9  337.45
  5002.3  337.95  5014.9  344.09  5017.5  344.09  5020.9  347.99  5029.4  349.94
  5037.7  350.58  5065.7  350.09  5096.5  350.59  5171.9  353.47  5199.8  356.06
  5216.6  356.43  5261.3  360.14  5356.3  366.44  5401.1  370.65  5464.7  374.56
#Mann= 4 ,-1 , 0
  4545.8     .05       0  4692.3     .16       0  4978.6     .12       0
  5029.4     .16       0
Bank Sta=4997.4,5002.3
XS Rating Curve= 0 ,0
Exp/Cntr=0.3,0.1

Type RM Length L Ch R = 1 ,1954    ,530,530,530
BEGIN DESCRIPTION:
DUCK CREEK TRIB 22 42
END DESCRIPTION:
XS GIS Cut Line= 3
      3521308.67     10408927.94      3521558.68     10408527.92
       3521757.9     10408129.48
#Sta/Elev= 30
  4536.8  362.32  4623.9  356.43  4673.9     352    4746  347.66  4791.9  348.06
  4849.8  346.76  4934.7   347.2    4957   348.1  4965.3  346.71  4971.2  346.91
  4980.6  343.28  4986.6  337.02  4990.4  335.79  4994.6  335.79    5007  339.28
  5015.5  344.07  5024.2   344.1  5037.9  346.41    5164  350.75  5225.5  354.98
  5231.1  354.41  5270.2  356.94  5275.8  356.49  5298.2   357.6  5347.1  361.01
  5365.2  361.92  5395.7  365.98  5429.2  368.09  5444.2  368.95    5454  369.18
#Mann= 7 ,-1 , 0
  4536.8      .1       0  4623.9     .16       0    4957     .12       0
  5037.9     .16       0  5347.1     .05       0  5429.2     .16       0
  5444.2     .05       0
Bank Sta=4971.2,5037.9
XS Rating Curve= 0 ,0
Exp/Cntr=0.3,0.1

Type RM Length L Ch R = 1 ,1424    ,986,986,986
BEGIN DESCRIPTION:
DUCK CREEK TRIB 22 32 0
END DESCRIPTION:
XS GIS Cut Line= 3
      3521459.15     10409249.08      3521997.32     10408786.86
      3522066.65     10408225.74
#Sta/Elev= 30
  4368.3  367.58  4432.5  367.22    4461  366.16  4581.7  357.82  4701.7  347.44
  4737.5  345.26  4773.9  344.52  4836.3  343.52  4864.8  344.49  4893.4  343.57
  4950.4  344.12  4978.6  342.21  4985.6  339.82  4992.1  336.18  4997.3  335.04
  4997.7  334.54  5002.3  335.04  5006.4  338.71  5014.1  340.27  5020.7   343.4
  5042.6  342.07  5077.6  342.83    5093  342.11  5284.5  345.06  5556.5  355.93
  5591.8  356.29  5606.9  357.76  5627.1  361.91  5637.2  362.39  5643.1  360.66
#Mann= 5 ,-1 , 0
  4368.3     .05       0  4773.9     .16       0  4997.3     .07       0
  5002.3     .16       0  5591.8     .05       0
Bank Sta=4997.3,5002.3
XS Rating Curve= 0 ,0
Exp/Cntr=0.3,0.1

Type RM Length L Ch R = 1 ,438     ,0,0,0
BEGIN DESCRIPTION:
DUCK CREEK TRIB 22 1 0
END DESCRIPTION:
XS GIS Cut Line= 4
      3521378.85     10409449.57       3522084.2     10409536.39
      3522420.57     10409178.31      3522539.91     10407366.49
#Sta/Elev= 30
    4141  365.39  4280.5  367.06  4345.8  365.23  4486.8  356.54  4605.4  346.92
  4718.6  340.76  4973.8   341.1  4987.9  337.23  4995.2  331.78  4998.9  330.89
  4999.6  330.72    5000  330.22  5004.6  330.72    5007   332.2  5016.3  339.05
  5037.3  341.79  5212.3  340.02    5520  339.05  5910.9  341.64  6331.8   341.6
  6639.1  351.52  6702.6  354.19  6742.7   353.4  6762.7   357.3  6872.9  363.08
    6961  370.64  7043.3  375.17  7112.2  382.63  7117.2  381.65  7158.7  385.28
#Mann= 7 ,-1 , 0
    4141     .05       0  4998.9     .16       0  4999.6     .07       0
  5004.6     .16       0    5007     .12       0  5212.3     .05       0
  6639.1     .16       0
Bank Sta=4999.6,5004.6
XS Rating Curve= 0 ,0
Exp/Cntr=0.3,0.1

Chan Stop Cuts=-1
Use User Specified Reach Order=0
Composite Channel Slope=5