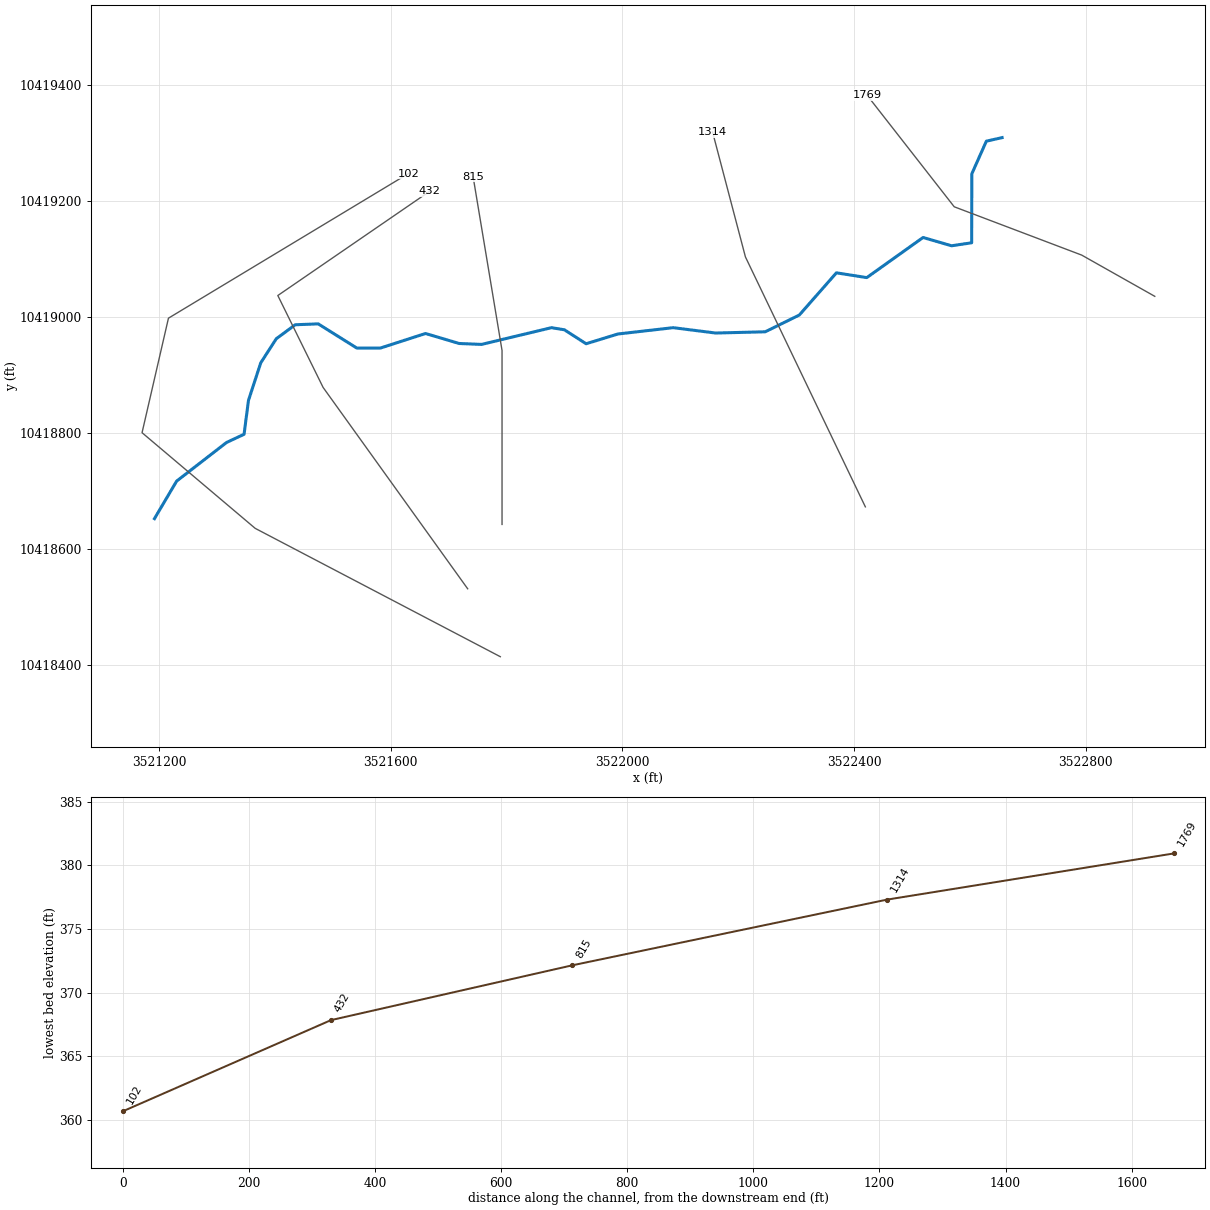
--- DUCK CREEK TRIB 23 1.prj (project) ---

Proj Title=DUCK CREEK TRIB 23 1 Base Level Engineering
Current Plan=p01
Default Exp/Contr=0.3,0.1
English Units
Geom File=g01
Flow File=f01
Plan File=p01
BEGIN DESCRIPTION:
DUCK CREEK TRIB 23 1
END DESCRIPTION:

--- DUCK CREEK TRIB 23 1.p01 (plan) ---

Plan Title=Multiple Run
Short Identifier=Multiple
Geom File=g01
Flow File=f01
Subcritical Flow
K Sum by GR= 0
Std Step Tol= 0.01
Critical Tol= 0.01
Num of Std Step Trials= 20
Max Error Tol= 0.3
Flow Tol Ratio= 0.001
Split Flow NTrial= 30
Split Flow Tol= 0.02
Split Flow Ratio= 0.02
Log Output Level= 0
Friction Slope Method= 1
Unsteady Friction Slope Method= 2
Unsteady Bridges Friction Slope Method= 1
Parabolic Critical Depth
Global Vel Dist=  1 , 1 , 1
Global Log Level= 0
CheckData=True
Encroach Param= -1, 0, 0, 0
BEGIN DESCRIPTION:
Multiple Run
END DESCRIPTION:

--- DUCK CREEK TRIB 23 1.f01 (steady flow) ---

Flow Title=Multiple
Number of Profiles=7
Profile Names=10-year,25-year,50-year,1pct_min,100-year,1pct_plu,500-year
River Rch & RM= DUCK CREEK TRIB ,Reach-1,1769
     735    1012    1242    1116    1509    2041    2220
Boundary for River Rch & Prof#=DUCK CREEK TRIB ,Reach-1,1
Up Type=0
Dn Type=3
Dn Slope=0.005
Boundary for River Rch & Prof#=DUCK CREEK TRIB ,Reach-1,2
Up Type=0
Dn Type=3
Dn Slope=0.005
Boundary for River Rch & Prof#=DUCK CREEK TRIB ,Reach-1,3
Up Type=0
Dn Type=3
Dn Slope=0.005
Boundary for River Rch & Prof#=DUCK CREEK TRIB ,Reach-1,4
Up Type=0
Dn Type=3
Dn Slope=0.005
Boundary for River Rch & Prof#=DUCK CREEK TRIB ,Reach-1,5
Up Type=0
Dn Type=3
Dn Slope=0.005
Boundary for River Rch & Prof#=DUCK CREEK TRIB ,Reach-1,6
Up Type=0
Dn Type=3
Dn Slope=0.005
Boundary for River Rch & Prof#=DUCK CREEK TRIB ,Reach-1,7
Up Type=0
Dn Type=3
Dn Slope=0.005

--- DUCK CREEK TRIB 23 1.g01 (geometry) ---

Geom Title=Existing Conditions

River Reach=DUCK CREEK TRIB ,Reach-1
Reach XY= 30
      3522655.39     10419308.68      3522628.14     10419302.52
      3522603.08     10419246.34      3522602.77     10419127.32
      3522568.08     10419122.16      3522518.92     10419136.44
      3522421.70     10419067.26      3522369.31     10419075.52
      3522305.23     10419002.68      3522246.45     10418973.84
      3522160.96     10418971.68      3522087.44     10418980.92
      3521992.02     10418970.02      3521937.21     10418953.22
      3521899.70     10418977.30      3521877.45     10418980.92
      3521756.74     10418952.07      3521718.01     10418953.67
      3521659.98     10418970.89      3521582.34     10418945.84
      3521541.43     10418945.78      3521474.79     10418987.49
      3521435.19     10418985.98      3521402.45     10418961.90
      3521375.59     10418920.30      3521354.40     10418855.53
      3521346.79     10418797.09      3521316.63     10418783.02
      3521230.38     10418716.33      3521192.11     10418651.64

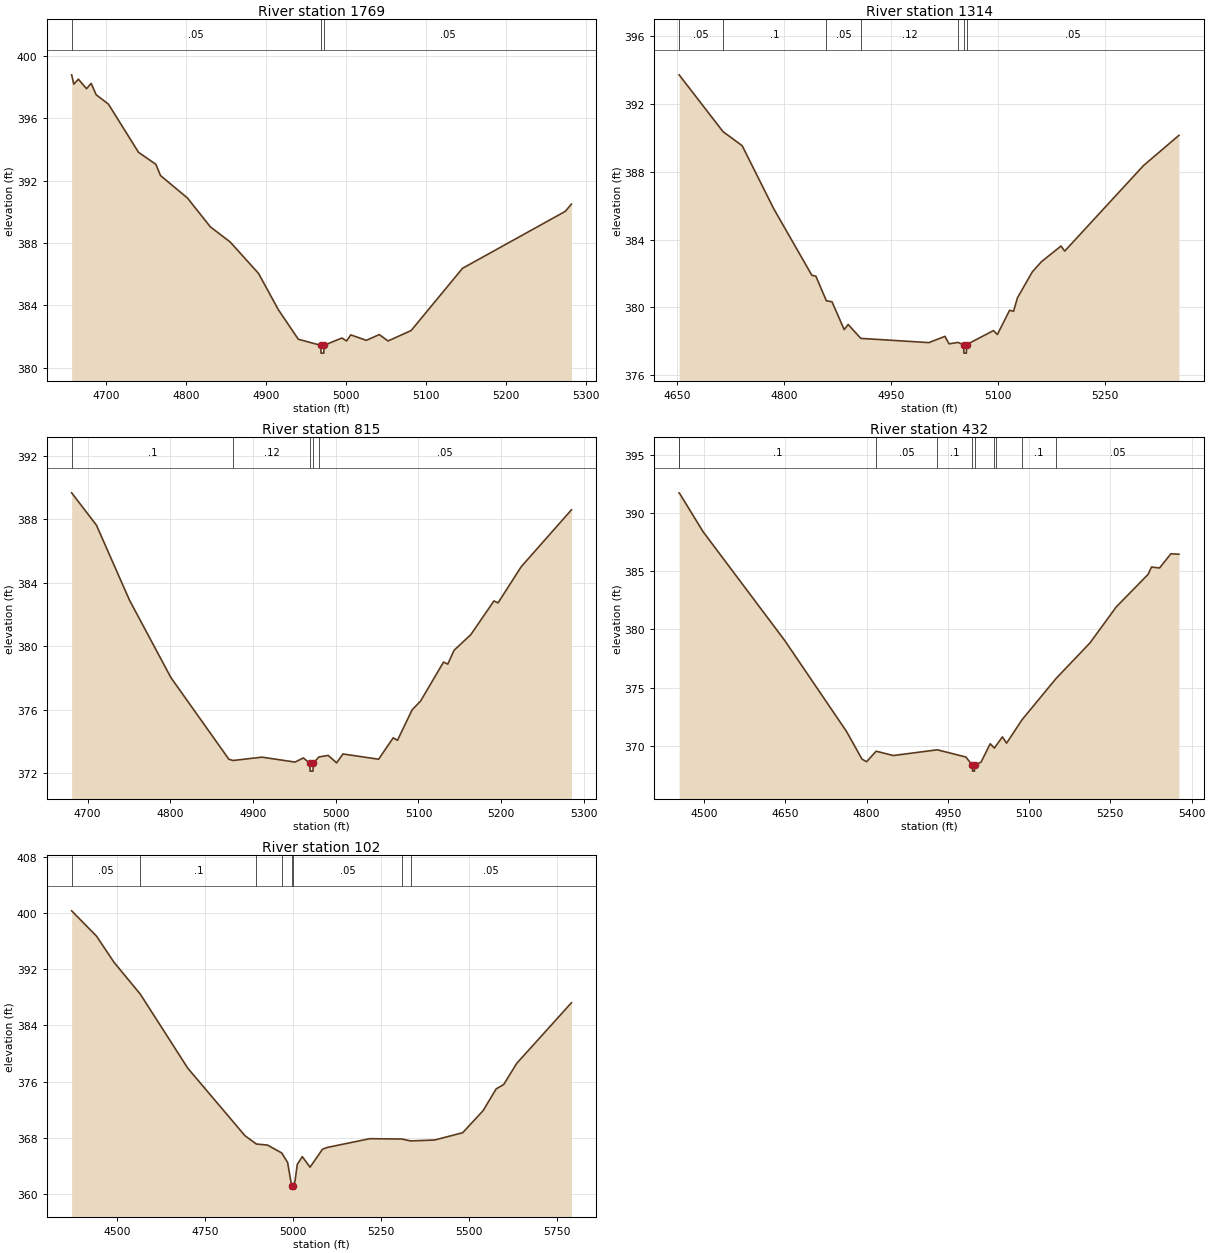
Type RM Length L Ch R = 1,1769,455,455,455
BEGIN DESCRIPTION:
DUCK CREEK TRIB 23 1 30 0
END DESCRIPTION:
XS GIS Cut Line= 4
      3522918.87     10419034.98      3522792.75     10419106.07
      3522572.66     10419189.40      3522421.87     10419382.23
#Sta/Elev= 30
  4656.7  398.78  4659.4  398.18  4665.1  398.50  4675.3  397.89  4681.1  398.23
  4687.4  397.50  4702.7  396.90  4740.3  393.81  4762.0  393.04  4767.8  392.32
  4801.5  390.88  4830.1  389.03  4854.9  388.06  4890.4  386.04  4915.2  383.71
  4940.1  381.82  4968.2  381.43  4968.5  380.93  4972.0  380.93  4972.2  381.43
  4994.6  381.90  5000.4  381.71  5005.7  382.10  5025.2  381.75  5041.3  382.12
  5052.3  381.71  5081.2  382.38  5145.4  386.37  5273.8  390.02  5281.6  390.49
#Mann=3,-1,0
  4656.7    0.05       0  4968.2    0.03       0  4972.2    0.05       0
Bank Sta=4968.2,4972.2
Exp/Cntr=0.3,0.1

Type RM Length L Ch R = 1,1314,499,499,499
BEGIN DESCRIPTION:
DUCK CREEK TRIB 23 1 20 0
END DESCRIPTION:
XS GIS Cut Line= 3
      3522419.27     10418671.94      3522212.26     10419102.88
      3522155.47     10419318.44
#Sta/Elev= 30
  4652.7  393.72  4714.2  390.37  4741.1  389.54  4785.5  385.81  4838.9  381.89
  4844.5  381.84  4859.2  380.39  4867.1  380.33  4884.2  378.69  4889.8  378.99
  4907.5  378.17  5003.0  377.92  5025.6  378.29  5031.2  377.85  5043.8  377.93
  5051.8  377.80  5052.1  377.30  5055.6  377.30  5055.8  377.80  5093.5  378.63
  5099.1  378.40  5116.2  379.83  5121.7  379.77  5127.3  380.57  5148.0  382.09
  5160.5  382.68  5188.3  383.62  5193.5  383.32  5304.1  388.37  5353.7  390.15
#Mann=7,-1,0
  4652.7    0.05       0  4714.2     0.1       0  4859.2    0.05       0
  4907.5    0.12       0  5043.8    0.05       0  5051.8    0.07       0
  5055.8    0.05       0
Bank Sta=5051.8,5055.8
Exp/Cntr=0.3,0.1

Type RM Length L Ch R = 1,815,383,383,383
BEGIN DESCRIPTION:
DUCK CREEK TRIB 23 1 4 0
END DESCRIPTION:
XS GIS Cut Line= 3
      3521792.11     10418641.64      3521792.11     10418941.64
      3521742.11     10419241.61
#Sta/Elev= 30
  4680.8  389.67  4710.8  387.63  4750.8  382.90  4800.8  378.03  4870.8  372.89
  4875.9  372.81  4910.8  373.02  4950.8  372.71  4960.8  372.97  4968.8  372.64
  4969.0  372.14  4972.5  372.14  4972.8  372.64  4979.6  373.03  4990.9  373.13
  5001.1  372.66  5008.7  373.22  5051.8  372.89  5069.5  374.24  5074.6  374.08
  5092.3  376.00  5102.5  376.55  5130.3  379.01  5135.4  378.88  5143.0  379.75
  5163.3  380.74  5191.2  382.86  5196.2  382.74  5224.1  385.01  5284.9  388.60
#Mann=5,-1,0
  4680.8     0.1       0  4875.9    0.12       0  4968.8    0.03       0
  4972.8    0.12       0  4979.6    0.05       0
Bank Sta=4968.8,4972.8
Exp/Cntr=0.3,0.1

Type RM Length L Ch R = 1,432,330,330,330
BEGIN DESCRIPTION:
DUCK CREEK TRIB 23 1 4 11
END DESCRIPTION:
XS GIS Cut Line= 4
      3521732.78     10418530.70      3521483.20     10418877.95
      3521405.07     10419036.37      3521667.41     10419216.32
#Sta/Elev= 30
  4454.2  391.72  4454.4  391.72  4498.3  388.39  4649.3  379.03  4763.2  371.23
  4791.7  368.86  4800.2  368.64  4817.9  369.54  4849.4  369.17  4930.8  369.66
  4983.4  369.04  4995.5  368.33  4995.7  367.83  4999.2  367.83  4999.5  368.33
  5011.4  368.60  5028.3  370.18  5036.1  369.81  5038.1  369.95  5050.8  370.77
  5058.5  370.23  5087.2  372.25  5150.0  375.79  5212.3  378.83  5261.0  381.93
  5319.9  384.73  5325.9  385.35  5340.8  385.27  5361.8  386.49  5376.6  386.45
#Mann=10,-1,0
  4454.2    0.05       0  4454.4     0.1       0  4817.9    0.05       0
  4930.8     0.1       0  4995.5    0.07       0  4999.5     0.1       0
  5036.1    0.16       0  5038.1    0.05       0  5087.2     0.1       0
  5150.0    0.05       0
Bank Sta=4995.5,4999.5
Exp/Cntr=0.3,0.1

Type RM Length L Ch R = 1,102,0,0,0
BEGIN DESCRIPTION:
DUCK CREEK TRIB 23 1 1 0
END DESCRIPTION:
XS GIS Cut Line= 5
      3521789.15     10418413.56      3521366.01     10418634.89
      3521170.70     10418799.82      3521216.27     10418997.31
      3521630.54     10419246.74
#Sta/Elev= 30
  4372.1  400.34  4442.8  396.73  4492.9  392.97  4567.0  388.47  4702.0  377.90
  4864.6  368.27  4896.7  367.10  4928.3  366.95  4968.9  365.82  4985.5  364.46
  4996.7  361.17  4997.0  360.67  5000.5  360.67  5000.7  361.17  5006.3  361.76
  5012.8  364.19  5027.1  365.30  5049.2  363.80  5084.3  366.35  5098.6  366.62
  5218.8  367.86  5310.0  367.81  5334.9  367.54  5402.9  367.67  5482.6  368.71
  5540.8  371.87  5577.7  374.96  5599.1  375.58  5636.0  378.59  5791.5  387.24
#Mann=8,-1,0
  4372.1    0.05       0  4567.0     0.1       0  4896.7    0.12       0
  4968.9    0.05       0  4996.7    0.03       0  5000.7    0.05       0
  5310.0    0.16       0  5334.9    0.05       0
Bank Sta=4996.7,5000.7
Exp/Cntr=0.3,0.1

Chan Stop Cuts=-1