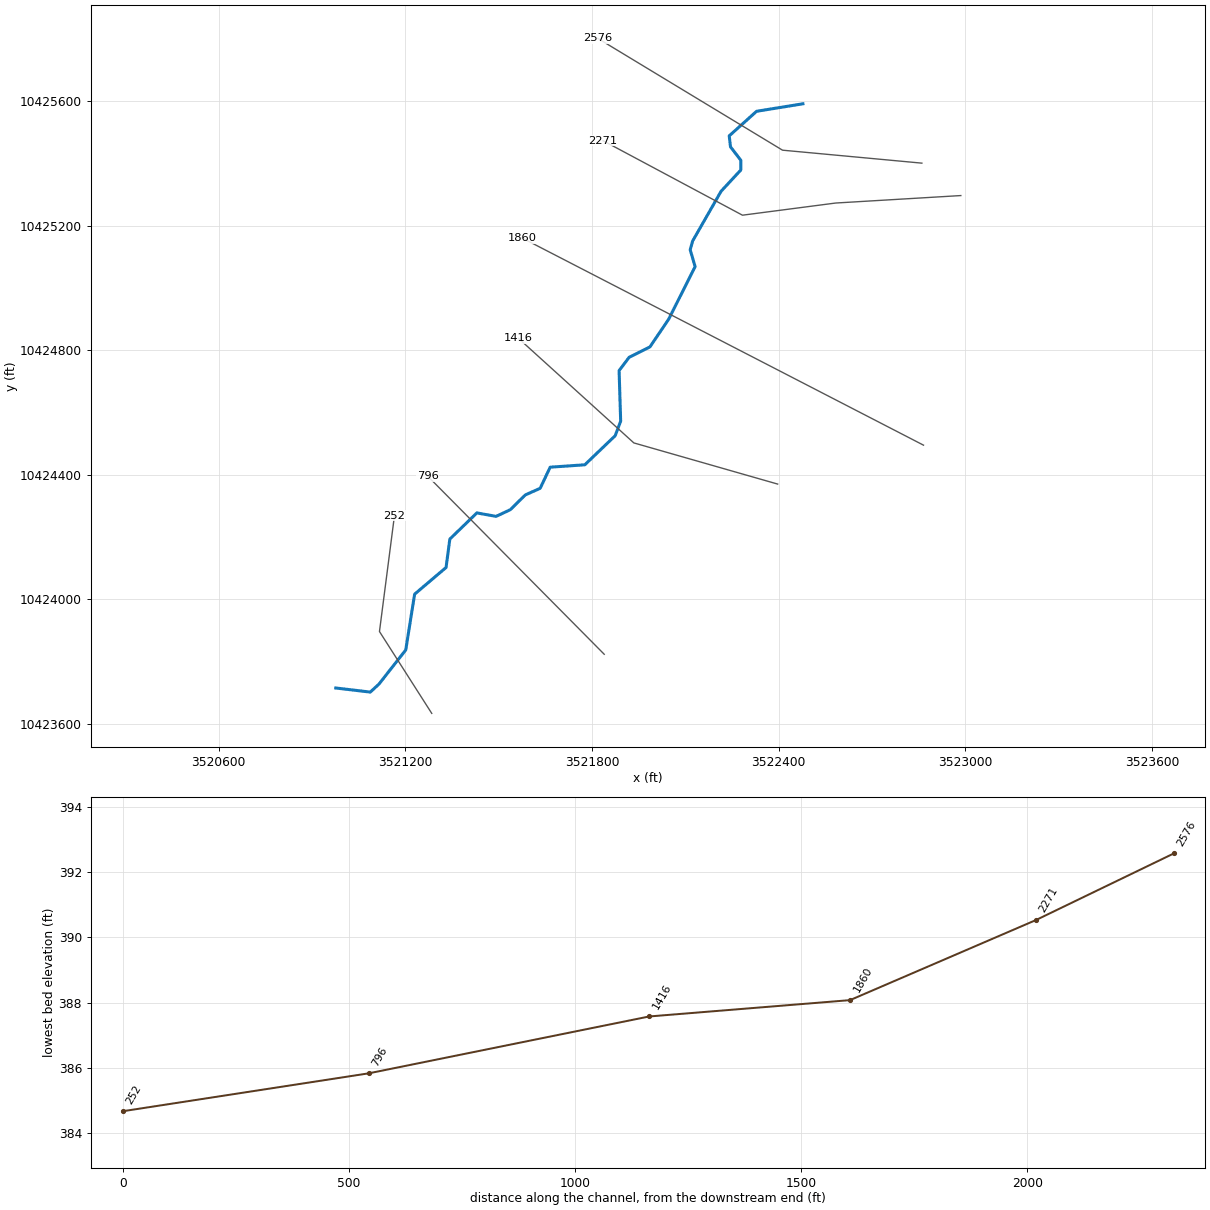
--- DUCK CREEK TRIB 23 3.prj (project) ---

Proj Title=DUCK CREEK TRIB 23 3 Base Level Engineering
Current Plan=p01
Default Exp/Contr=0.3,0.1
English Units
Geom File=g01
Flow File=f01
Plan File=p01
Y Axis Title=Elevation
X Axis Title(PF)=Main Channel Distance
X Axis Title(XS)=Station
BEGIN DESCRIPTION:
DUCK CREEK TRIB 23 3
END DESCRIPTION:
DSS Export Rating Curves= 0
DSS Export Rating Curve Sorted= 0
DSS Export Volume Flow Curves= 0
DXF OffsetX= 0
DXF OffsetY= 0
DXF ScaleX= 1
DXF ScaleY= 10

--- DUCK CREEK TRIB 23 3.p01 (plan) ---

Plan Title=Multiple Run
Short Identifier=Multiple
Geom File=g01
Flow File=f01
Subcritical Flow
K Sum by GR= 0
Std Step Tol= 0.01
Critical Tol= 0.01
Num of Std Step Trials= 20
Max Error Tol= 0.3
Flow Tol Ratio= 0.001
Split Flow NTrial= 30
Split Flow Tol= 0.02
Split Flow Ratio= 0.02
Log Output Level= 0
Friction Slope Method= 1
Unsteady Friction Slope Method= 2
Unsteady Bridges Friction Slope Method= 1
Parabolic Critical Depth
Global Vel Dist=  1 , 1 , 1
Global Log Level= 0
CheckData=True
Encroach Param= -1, 0, 0, 0
BEGIN DESCRIPTION:
Multiple Run
END DESCRIPTION:

--- DUCK CREEK TRIB 23 3.f01 (steady flow) ---

Flow Title=Multiple
Number of Profiles=7
Profile Names=10-year,25-year,50-year,1pct_min,100-year,1pct_plu,500-year
River Rch & RM= DUCK CREEK TRIB ,Reach-1,2576
     959    1345    1671    1519    2054    2778    3093
Boundary for River Rch & Prof#=DUCK CREEK TRIB ,Reach-1,1
Up Type=0
Dn Type=3
Dn Slope=0.005
Boundary for River Rch & Prof#=DUCK CREEK TRIB ,Reach-1,2
Up Type=0
Dn Type=3
Dn Slope=0.005
Boundary for River Rch & Prof#=DUCK CREEK TRIB ,Reach-1,3
Up Type=0
Dn Type=3
Dn Slope=0.005
Boundary for River Rch & Prof#=DUCK CREEK TRIB ,Reach-1,4
Up Type=0
Dn Type=3
Dn Slope=0.005
Boundary for River Rch & Prof#=DUCK CREEK TRIB ,Reach-1,5
Up Type=0
Dn Type=3
Dn Slope=0.005
Boundary for River Rch & Prof#=DUCK CREEK TRIB ,Reach-1,6
Up Type=0
Dn Type=3
Dn Slope=0.005
Boundary for River Rch & Prof#=DUCK CREEK TRIB ,Reach-1,7
Up Type=0
Dn Type=3
Dn Slope=0.005

--- DUCK CREEK TRIB 23 3.g01 (geometry) ---

Geom Title=Existing Conditions
Program Version=4.10

River Reach=DUCK CREEK TRIB ,Reach-1
Reach XY= 30
      3522477.93     10425591.64      3522329.06     10425567.54
      3522241.06     10425488.57      3522245.19     10425453.24
      3522278.46     10425409.91       3522278.2     10425378.74
      3522214.89     10425310.49       3522123.6     10425150.86
      3522115.66      10425122.5      3522131.48      10425068.3
      3522046.42     10424899.26      3521986.41     10424810.58
      3521919.36     10424776.86      3521887.22     10424734.32
      3521892.27     10424571.68       3521874.6       10424525.
      3521777.04      10424431.6      3521665.75     10424423.91
      3521633.65     10424356.14      3521585.71     10424334.61
       3521537.8     10424287.39      3521491.96     10424265.86
      3521430.16     10424276.97      3521343.35     10424192.94
      3521331.18     10424101.54      3521230.16     10424015.86
      3521201.69     10423836.69      3521115.58     10423726.97
       3521087.8     10423701.27      3520976.75     10423714.38

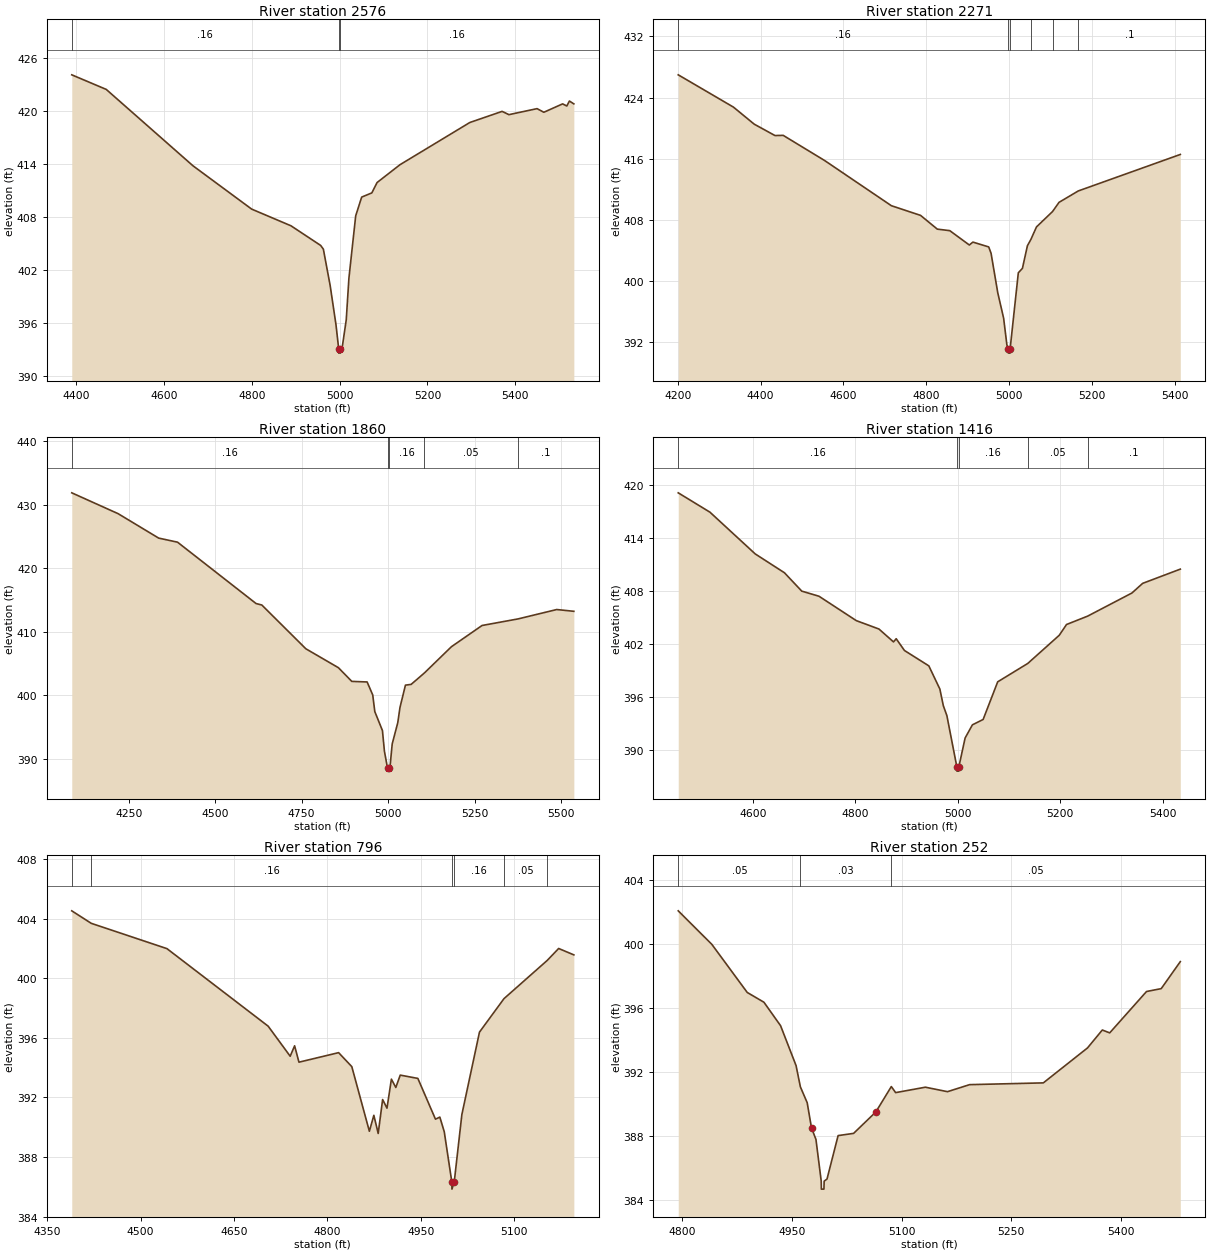
Type RM Length L Ch R = 1 ,2576    ,305,305,305
BEGIN DESCRIPTION:
DUCK CREEK TRIB 23 3 23 0
END DESCRIPTION:
XS GIS Cut Line= 3
      3522860.22      10425400.9      3522412.33     10425442.56
      3521818.55     10425801.95
#Sta/Elev= 30
  4389.8  424.09  4468.3  422.44  4665.9  413.79  4799.7  408.88  4889.3  406.99
  4956.8  404.77    4963  404.35  4978.5  400.23  4991.8  395.78  4997.9  393.07
  4998.1  392.57  5001.6  392.57  5001.9  393.07  5005.7  393.13  5015.2  396.36
  5021.2  401.04  5036.7  408.12  5050.3  410.24  5073.5  410.72  5085.4  411.89
  5137.6  413.91  5296.7  418.69  5370.3  419.95  5385.8  419.58  5449.9  420.26
  5465.4  419.85  5508.1   420.8  5517.7  420.56  5523.6  421.12  5533.7   420.8
#Mann= 3 ,-1 , 0
  4389.8     .16       0  4997.9     .07       0  5001.9     .16       0
Bank Sta=4997.9,5001.9
XS Rating Curve= 0 ,0
Exp/Cntr=0.3,0.1

Type RM Length L Ch R = 1 ,2271    ,411,411,411
BEGIN DESCRIPTION:
DUCK CREEK TRIB 23 3 6 0
END DESCRIPTION:
XS GIS Cut Line= 4
      3522985.29     10425296.73      3522583.08     10425272.74
       3522283.6     10425233.67      3521835.68     10425473.02
#Sta/Elev= 30
  4201.2  426.98  4334.6  422.75  4384.7  420.52  4434.8  419.03  4454.8  419.05
    4555  415.75    4716  409.84  4786.6  408.57    4827  406.77  4857.2  406.57
  4904.4  404.69    4913  405.07  4951.2  404.44  4956.9   403.6  4973.1  398.42
  4987.2  395.11  4995.1  391.61  4998.8  391.03    4999  390.53  5002.5  390.53
  5002.8  391.03  5022.7  401.05  5032.6  401.63  5044.7   404.6    5053  405.41
  5066.6  407.06  5105.3  409.07  5121.1  410.28  5167.5  411.77    5414  416.55
#Mann= 6 ,-1 , 0
  4201.2     .16       0  4998.8     .07       0  5002.8     .16       0
    5053      .1       0  5105.3     .05       0  5167.5      .1       0
Bank Sta=4998.8,5002.8
XS Rating Curve= 0 ,0
Exp/Cntr=0.3,0.1

Type RM Length L Ch R = 1 ,1860    ,444,444,444
BEGIN DESCRIPTION:
DUCK CREEK TRIB 23 3 5 0
END DESCRIPTION:
XS GIS Cut Line= 2
      3522865.42     10424494.66      3521575.41     10425160.47
#Sta/Elev= 30
  4085.4  431.84  4219.5  428.56  4336.7  424.72  4391.2  424.08  4618.3  414.43
  4634.9   414.2  4762.2  407.32  4856.4  404.34  4895.1  402.19  4939.4   402.1
  4955.6  400.06  4961.6  397.44  4983.7  394.46  4989.4  391.22  4998.3  388.58
  4998.5  388.08    5002  388.08  5002.3  388.58  5005.9  388.95  5011.9  392.36
    5028   395.7  5034.4   398.1  5050.2   401.6  5066.7  401.72  5105.1  403.52
  5183.1  407.64  5271.7  410.98  5375.5  412.01  5487.7  413.49  5537.1  413.21
#Mann= 5 ,-1 , 0
  4085.4     .16       0  4998.3     .07       0  5002.3     .16       0
  5105.1     .05       0  5375.5      .1       0
Bank Sta=4998.3,5002.3
XS Rating Curve= 0 ,0
Exp/Cntr=0.3,0.1

Type RM Length L Ch R = 1 ,1416    ,620,620,620
BEGIN DESCRIPTION:
DUCK CREEK TRIB 23 3 4 0
END DESCRIPTION:
XS GIS Cut Line= 3
      3522396.73     10424369.64      3521934.64      10424501.9
      3521564.34     10424837.51
#Sta/Elev= 30
  4454.3  419.09  4516.2   416.9  4604.7  412.17  4661.7  410.04  4695.5  407.96
  4729.2  407.38    4802  404.62  4846.2  403.67  4874.7  402.21  4879.9  402.57
    4896  401.24  4943.6   399.5  4965.2  396.87  4971.9     395  4978.9  393.86
  4998.3  388.08  4998.6  387.58  5002.1  387.58  5002.3  388.08  5014.5  391.33
  5028.7  392.82  5049.7  393.43  5078.1  397.69  5136.8  399.77  5198.3  402.96
  5212.5  404.18  5253.8  405.13  5340.3  407.75  5361.2  408.84  5434.7  410.45
#Mann= 5 ,-1 , 0
  4454.3     .16       0  4998.3     .07       0  5002.3     .16       0
  5136.8     .05       0  5253.8      .1       0
Bank Sta=4998.3,5002.3
XS Rating Curve= 0 ,0
Exp/Cntr=0.3,0.1

Type RM Length L Ch R = 1 ,796     ,544,544,544
BEGIN DESCRIPTION:
DUCK CREEK TRIB 23 3 3 0
END DESCRIPTION:
XS GIS Cut Line= 2
      3521839.44     10423822.74       3521271.7     10424395.69
#Sta/Elev= 30
  4389.4  404.54  4420.7   403.7  4542.3     402  4704.9  396.79  4740.3  394.77
  4747.4  395.47  4754.4  394.37  4818.1  395.01  4839.3  394.07  4867.5  389.73
  4874.7   390.8  4881.7  389.58  4888.8  391.86  4895.8  391.28  4902.9  393.23
    4910  392.67  4917.1   393.5  4945.4  393.28  4973.7  390.54  4980.7  390.68
  4987.8   389.7  4999.9  386.34  5000.2  385.84  5003.9  386.34  5016.1  390.85
  5044.4  396.39  5083.8  398.64  5153.3  401.21  5171.6  402.01    5196  401.58
#Mann= 6 ,-1 , 0
  4389.4     .05       0  4420.7     .16       0  4999.9     .07       0
  5003.9     .16       0  5083.8     .05       0  5153.3     .16       0
Bank Sta=4999.9,5003.9
XS Rating Curve= 0 ,0
Exp/Cntr=0.3,0.1

Type RM Length L Ch R = 1 ,252     ,0,0,0
BEGIN DESCRIPTION:
DUCK CREEK TRIB 23 3 1 0
END DESCRIPTION:
XS GIS Cut Line= 3
      3521285.17     10423632.84      3521117.21     10423895.85
      3521165.29     10424267.49
#Sta/Elev= 30
  4794.4   402.1  4840.4     400  4888.8  396.99  4911.6  396.38  4934.4  394.91
  4955.6  392.41  4961.5  391.08  4970.8  390.09  4976.7  388.51  4982.8  387.79
    4990  385.18  4990.2  384.68  4993.7  384.68    4994  385.18  4997.9  385.31
  5013.1  388.03  5034.3  388.17  5064.7  389.51  5085.9   391.1  5091.8  390.72
  5132.5  391.06  5162.7  390.78    5193  391.22  5293.8  391.33  5354.3  393.52
  5374.5  394.64  5384.6  394.46    5435  397.05  5455.1  397.23  5481.2  398.92
#Mann= 3 ,-1 , 0
  4794.4     .05       0  4961.5     .03       0  5085.9     .05       0
Bank Sta=4976.7,5064.7
XS Rating Curve= 0 ,0
Exp/Cntr=0.3,0.1

Chan Stop Cuts=-1
Use User Specified Reach Order=0
Composite Channel Slope=5