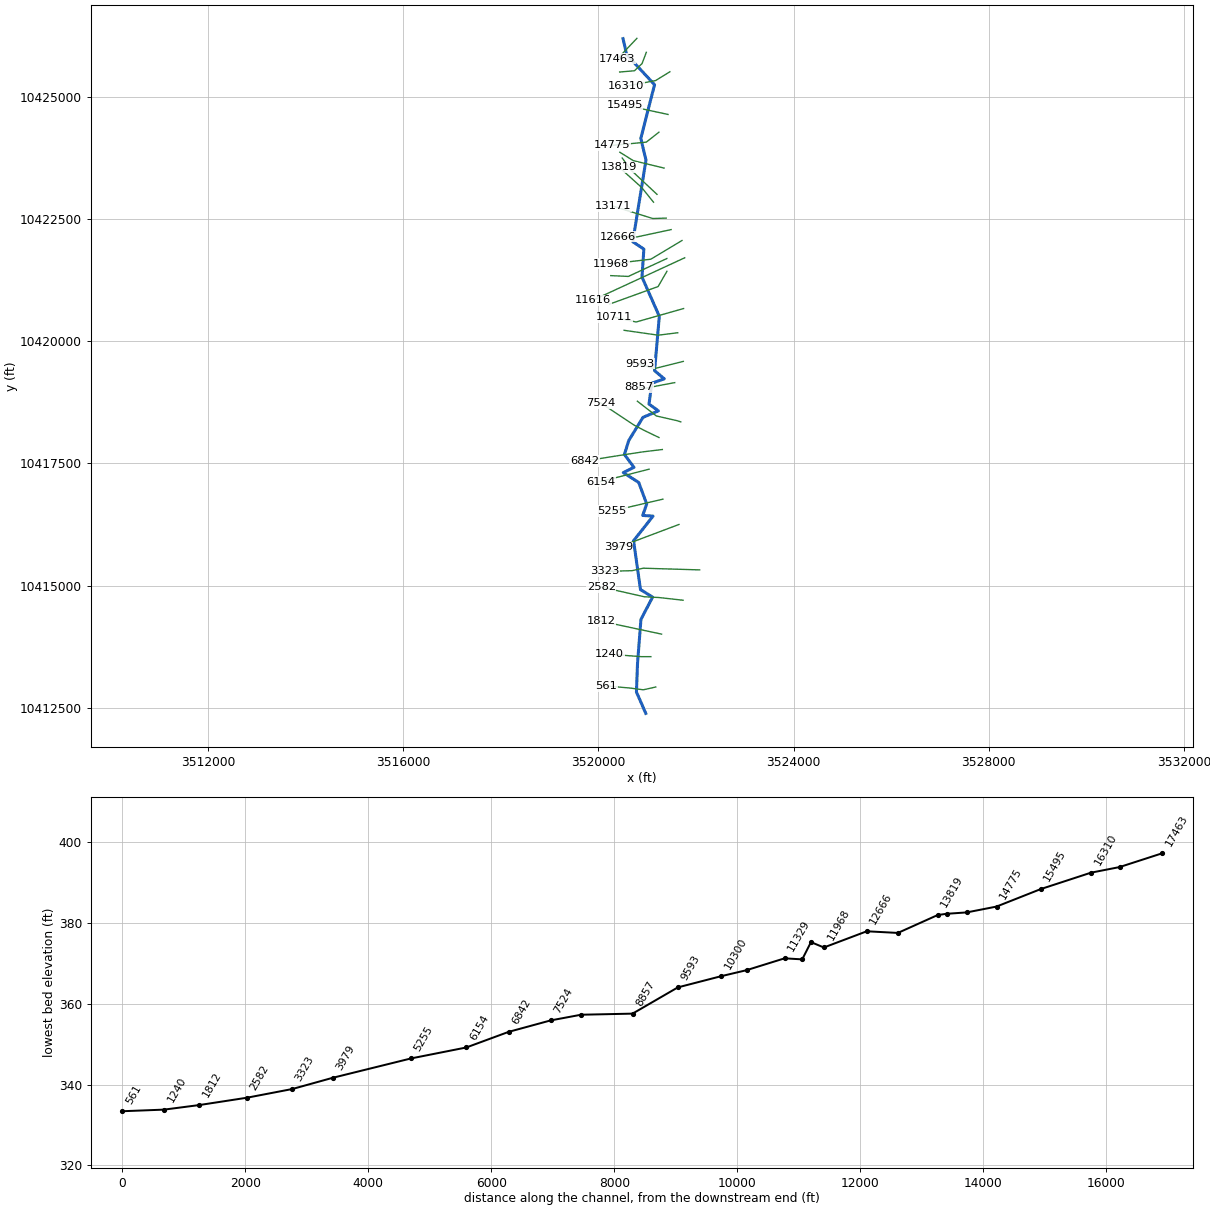
--- DUCK CREEK TRIB 23.prj (project) ---

Proj Title=DUCK CREEK TRIB 23 Base Level Engineering
Current Plan=p01
Default Exp/Contr=0.3,0.1
English Units
Geom File=g01
Flow File=f01
Plan File=p01
Y Axis Title=Elevation
X Axis Title(PF)=Main Channel Distance
X Axis Title(XS)=Station
BEGIN DESCRIPTION:
DUCK CREEK TRIB 23
END DESCRIPTION:
DSS Export Rating Curves= 0
DSS Export Rating Curve Sorted= 0
DSS Export Volume Flow Curves= 0
DXF OffsetX= 0
DXF OffsetY= 0
DXF ScaleX= 1
DXF ScaleY= 10

--- DUCK CREEK TRIB 23.p01 (plan) ---

Plan Title=Multiple Run
Short Identifier=Multiple
Geom File=g01
Flow File=f01
Subcritical Flow
K Sum by GR= 0
Std Step Tol= 0.01
Critical Tol= 0.01
Num of Std Step Trials= 20
Max Error Tol= 0.3
Flow Tol Ratio= 0.001
Split Flow NTrial= 30
Split Flow Tol= 0.02
Split Flow Ratio= 0.02
Log Output Level= 0
Friction Slope Method= 1
Unsteady Friction Slope Method= 2
Unsteady Bridges Friction Slope Method= 1
Parabolic Critical Depth
Global Vel Dist=  1 , 1 , 1
Global Log Level= 0
CheckData=True
Encroach Param= -1, 0, 0, 0
BEGIN DESCRIPTION:
Multiple Run
END DESCRIPTION:

--- DUCK CREEK TRIB 23.f01 (steady flow) ---

Flow Title=Multiple
Number of Profiles=7
Profile Names=10-year,25-year,50-year,1pct_min,100-year,1pct_plu,500-year
River Rch & RM= DUCK CREEK TRIB ,Reach-1,17463
     683     925    1121     994    1344    1818    1926
River Rch & RM= DUCK CREEK TRIB ,Reach-1,14292
    1595    2260    2824    2572    3478    4704    5264
River Rch & RM= DUCK CREEK TRIB ,Reach-1,8020
    1905    2708    3389    3087    4175    5646    6324
Boundary for River Rch & Prof#=DUCK CREEK TRIB ,Reach-1,1
Up Type=0
Dn Type=3
Dn Slope=0.005
Boundary for River Rch & Prof#=DUCK CREEK TRIB ,Reach-1,2
Up Type=0
Dn Type=3
Dn Slope=0.005
Boundary for River Rch & Prof#=DUCK CREEK TRIB ,Reach-1,3
Up Type=0
Dn Type=3
Dn Slope=0.005
Boundary for River Rch & Prof#=DUCK CREEK TRIB ,Reach-1,4
Up Type=0
Dn Type=3
Dn Slope=0.005
Boundary for River Rch & Prof#=DUCK CREEK TRIB ,Reach-1,5
Up Type=0
Dn Type=3
Dn Slope=0.005
Boundary for River Rch & Prof#=DUCK CREEK TRIB ,Reach-1,6
Up Type=0
Dn Type=3
Dn Slope=0.005
Boundary for River Rch & Prof#=DUCK CREEK TRIB ,Reach-1,7
Up Type=0
Dn Type=3
Dn Slope=0.005

--- DUCK CREEK TRIB 23.g01 (geometry) ---

Geom Title=Existing Conditions
Program Version=4.10

River Reach=DUCK CREEK TRIB ,Reach-1
Reach XY= 30
      3520506.48     10426204.76      3520581.76     10425874.79
      3521152.14     10425261.03      3520870.94     10424160.22
      3520976.75     10423714.38      3520705.92     10422043.37
      3520933.35     10421892.33      3520895.16     10421318.54
      3521250.04     10420515.76      3521153.17     10419401.88
       3521351.5     10419234.55      3521097.23     10419144.33
      3521038.39     10418717.49      3521230.66     10418577.42
      3520915.43     10418445.07      3520624.34     10417970.81
      3520534.73     10417684.33      3520730.81     10417420.62
      3520511.95     10417312.24      3520828.73     10417110.17
      3520991.49     10416670.79       3520909.7     10416435.46
      3521121.57     10416421.68      3520722.69     10415916.66
      3520864.06     10414917.09      3521112.42      10414761.7
      3520873.72     10414306.19      3520803.56     10413404.13
      3520781.34     10412818.02      3520972.72     10412380.22

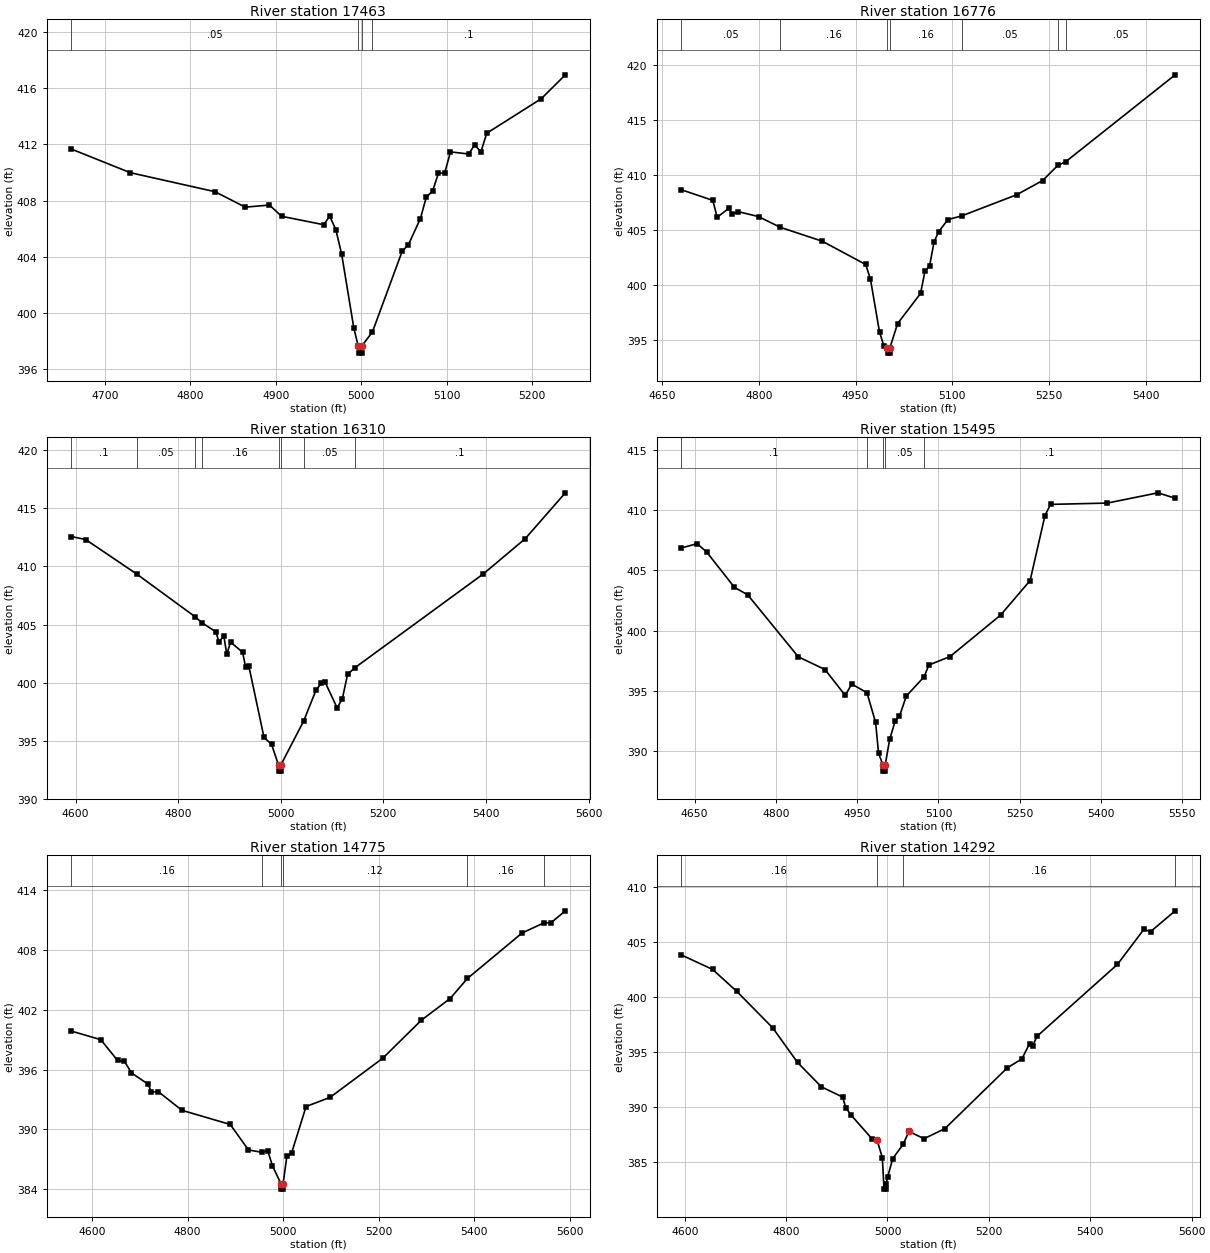
Type RM Length L Ch R = 1 ,17463   ,687,687,687
BEGIN DESCRIPTION:
DUCK CREEK TRIB 23 5 0
END DESCRIPTION:
XS GIS Cut Line= 2
       3520791.4     10426210.22       3520392.1     10425791.63
#Sta/Elev= 30
  4660.6  411.67  4729.7  409.99  4828.8  408.64  4864.3  407.54  4892.6  407.69
  4906.8  406.89  4956.2  406.29  4963.1   406.9  4970.3  405.95  4977.2  404.18
  4991.4  398.94  4996.6  397.66  4996.9  397.16  5000.4  397.16  5000.6  397.66
  5013.2  398.67    5048   404.4  5055.3  404.87  5069.4  406.73  5076.3  408.26
  5083.6  408.67  5090.5  409.96  5097.7  409.95  5104.6  411.47    5126  411.32
  5132.9  411.98  5140.2  411.47  5147.1   412.8  5210.9  415.25  5239.1  416.95
#Mann= 4 ,-1 , 0
  4660.6     .05       0  4996.6    .035       0  5000.6     .05       0
  5013.2      .1       0
Bank Sta=4996.6,5000.6
XS Rating Curve= 0 ,0
Exp/Cntr=0.3,0.1

Type RM Length L Ch R = 1 ,16776   ,466,466,466
BEGIN DESCRIPTION:
DUCK CREEK TRIB 23 4 0
END DESCRIPTION:
XS GIS Cut Line= 4
      3520984.11     10425923.73      3520895.58     10425692.01
      3520741.07     10425545.53       3520437.2     10425520.13
#Sta/Elev= 30
  4679.6  408.66  4728.6  407.69  4735.4  406.15  4753.3  406.96  4758.7  406.41
  4767.5  406.67  4799.6  406.21    4833  405.24  4898.3  403.97  4965.7  401.85
    4973  400.52  4987.1  395.69    4994  394.41  4999.3  394.28  4999.5  393.78
    5003  393.78  5003.3  394.28  5015.1  396.47  5050.7  399.21  5057.5  401.23
  5064.8  401.75  5071.7  403.92    5079  404.85  5093.1  405.94  5114.3  406.27
  5199.7   408.2  5239.9  409.49  5263.5  410.87  5275.8  411.21  5445.5  419.12
#Mann= 7 ,-1 , 0
  4679.6     .05       0    4833     .16       0  4999.3     .07       0
  5003.3     .16       0  5114.3     .05       0  5263.5      .1       0
  5275.8     .05       0
Bank Sta=4999.3,5003.3
XS Rating Curve= 0 ,0
Exp/Cntr=0.3,0.1

Type RM Length L Ch R = 1 ,16310   ,815,815,815
BEGIN DESCRIPTION:
DUCK CREEK TRIB 23 34 0
END DESCRIPTION:
XS GIS Cut Line= 3
      3521465.91     10425525.35      3521175.45     10425345.64
      3520565.19     10425229.37
#Sta/Elev= 30
  4591.9  412.57  4619.9  412.31  4719.7  409.33  4833.1  405.67  4845.9  405.17
  4873.6  404.37  4879.5  403.51    4889  404.02  4894.9  402.44  4902.1  403.49
  4925.6  402.62  4931.5  401.35  4937.7  401.45  4967.4  395.29  4982.1  394.69
  4995.9  392.89  4996.2  392.39  4999.7  392.39  4999.9  392.89  5044.8  396.71
  5069.2  399.41  5079.4  399.94  5086.4  400.05  5109.9  397.83  5120.1  398.62
  5130.3  400.72  5144.7  401.29    5395  409.36  5476.4  412.38  5554.7  416.33
#Mann= 8 ,-1 , 0
  4591.9      .1       0  4719.7     .05       0  4833.1      .1       0
  4845.9     .16       0  4995.9     .07       0  4999.9     .16       0
  5044.8     .05       0  5144.7      .1       0
Bank Sta=4995.9,4999.9
XS Rating Curve= 0 ,0
Exp/Cntr=0.3,0.1

Type RM Length L Ch R = 1 ,15495   ,720,720,720
BEGIN DESCRIPTION:
DUCK CREEK TRIB 23 33 0
END DESCRIPTION:
XS GIS Cut Line= 2
      3521427.97     10424650.89      3520537.28     10424843.61
#Sta/Elev= 30
  4625.4  406.86  4654.8  407.22  4672.3  406.53  4723.5   403.6  4748.1  402.97
  4841.4  397.83  4890.7  396.77  4928.1  394.62  4939.9  395.57  4968.1  394.85
    4984  392.39  4989.5  389.82  4997.7  388.84    4998  388.34  5001.5  388.34
  5001.7  388.84    5010  390.98  5020.2   392.5  5028.1   392.9  5040.7  394.57
  5073.3  396.16  5082.4  397.15  5121.4  397.85  5214.6  401.29  5269.1  404.16
  5296.4  409.54  5306.7  410.48  5411.6  410.59    5505  411.44  5536.7  410.99
#Mann= 5 ,-1 , 0
  4625.4      .1       0  4968.1     .05       0  4997.7    .035       0
  5001.7     .05       0  5073.3      .1       0
Bank Sta=4997.7,5001.7
XS Rating Curve= 0 ,0
Exp/Cntr=0.3,0.1

Type RM Length L Ch R = 1 ,14775   ,483,483,483
BEGIN DESCRIPTION:
DUCK CREEK TRIB 23 31 0
END DESCRIPTION:
XS GIS Cut Line= 3
      3521242.35     10424287.05      3520983.07      10424083.7
       3520282.1     10424015.48
#Sta/Elev= 30
  4556.9  399.87  4618.4  399.01  4653.7  396.92  4668.1  396.83  4682.6  395.68
  4717.8  394.53  4724.2  393.75  4738.6   393.8  4788.4  391.92  4889.4   390.5
  4927.6  387.94  4955.6  387.71  4967.8  387.87  4977.8  386.35  4995.9  384.51
  4996.2  384.01  4999.7  384.01  4999.9  384.51    5008  387.34    5018  387.66
  5048.1   392.3  5098.4  393.22  5208.9  397.16  5289.3  400.96  5349.6  403.14
  5385.8  405.15  5500.3  409.72  5545.4  410.72  5560.6  410.74  5590.7  411.94
#Mann= 6 ,-1 , 0
  4556.9     .16       0  4955.6     .12       0  4995.9     .07       0
  4999.9     .12       0  5385.8     .16       0  5545.4     .05       0
Bank Sta=4995.9,4999.9
XS Rating Curve= 0 ,0
Exp/Cntr=0.3,0.1

Type RM Length L Ch R = 1 ,14292   ,330,330,330
BEGIN DESCRIPTION:
DUCK CREEK TRIB 23 3 0
END DESCRIPTION:
XS GIS Cut Line= 3
      3521347.69      10423552.1      3520717.47     10423704.45
      3520440.93     10423877.12
#Sta/Elev= 30
  4593.1  403.84    4655  402.52  4702.2  400.55  4773.7  397.21  4822.6  394.07
  4869.6  391.86  4911.5  390.93  4917.8  389.96  4928.1   389.3  4969.2  387.15
  4979.5  387.02  4989.8  385.44  4993.2  382.57  4997.1  382.57  4997.5  383.07
  5000.3  383.67  5010.4  385.35  5030.9  386.63  5042.2  387.81  5072.1  387.15
  5113.2  388.06  5236.5  393.59    5265  394.39  5280.3  395.78  5286.2  395.56
    5295  396.45  5453.7  402.98  5505.6  406.15    5519  405.95  5567.5  407.84
#Mann= 4 ,-1 , 0
  4593.1     .16       0  4979.5     .12       0  5030.9     .16       0
  5567.5     .05       0
Bank Sta=4979.5,5042.2
XS Rating Curve= 0 ,0
Exp/Cntr=0.3,0.1

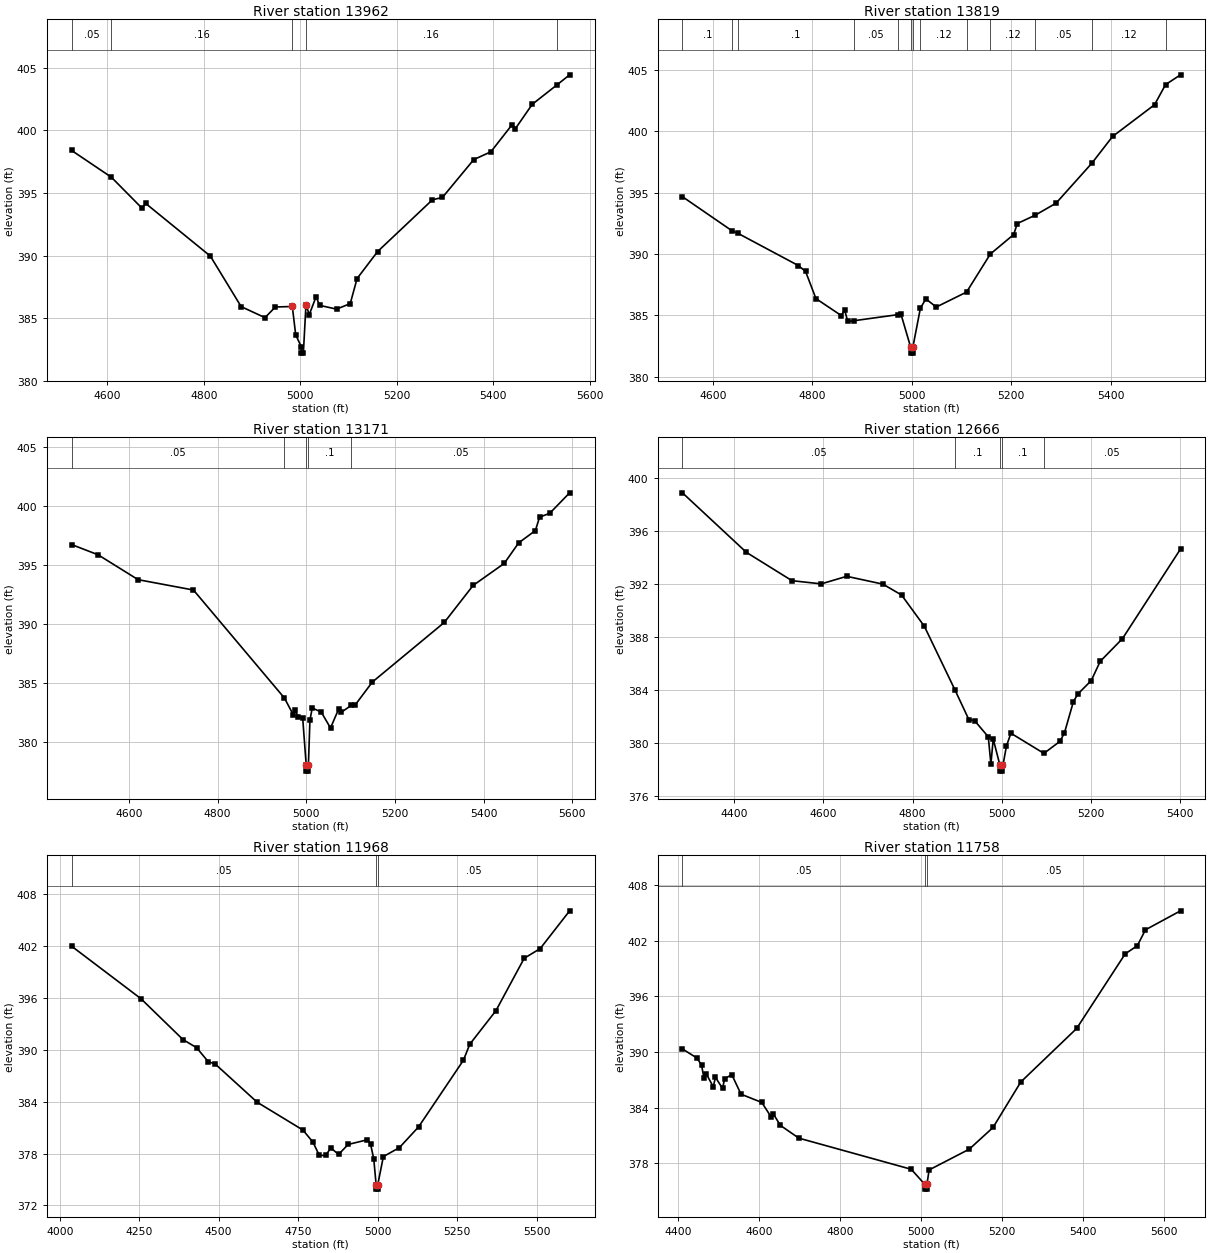
Type RM Length L Ch R = 1 ,13962   ,143,143,143
BEGIN DESCRIPTION:
DUCK CREEK TRIB 23 29 0
END DESCRIPTION:
XS GIS Cut Line= 3
      3521201.82     10423014.36      3520669.29     10423511.74
      3520490.51     10423757.89
#Sta/Elev= 30
  4525.7  398.39  4608.3  396.25  4672.3  393.76  4679.1  394.17  4813.5  389.96
  4877.4  385.93  4926.8  385.05  4948.3   385.9  4983.5  385.94  4990.5  383.68
  5002.2  382.72  5002.5  382.22  5006.4  382.22  5011.8  386.08  5018.6  385.29
  5032.8  386.72  5040.1  386.03  5075.3  385.73  5103.6  386.17  5117.8  388.17
  5160.3  390.32    5274  394.45  5294.8  394.64  5359.8  397.66  5395.3  398.28
  5439.4  400.45  5445.6   400.1  5481.1  402.07  5531.4  403.59  5558.6  404.42
#Mann= 5 ,-1 , 0
  4525.7     .05       0  4608.3     .16       0  4983.5     .12       0
  5011.8     .16       0  5531.4     .05       0
Bank Sta=4983.5,5011.8
XS Rating Curve= 0 ,0
Exp/Cntr=0.3,0.1

Type RM Length L Ch R = 1 ,13819   ,648,648,648
BEGIN DESCRIPTION:
DUCK CREEK TRIB 23 28 0
END DESCRIPTION:
XS GIS Cut Line= 3
      3521131.52      10422852.9      3520889.35     10423153.67
      3520432.32     10423565.12
#Sta/Elev= 30
  4538.9  394.68  4638.8  391.89  4650.1   391.7    4772  389.06  4786.4  388.58
  4807.2  386.37  4858.3  384.98  4864.8  385.45  4871.2   384.5    4883  384.56
  4972.1  385.06  4978.1   385.1  4997.5  382.42  4997.8  381.92  5001.8  381.92
  5002.1  382.42  5017.2  385.59  5028.2  386.34  5049.1  385.68    5110   386.9
  5157.7     390  5204.6  391.59    5212  392.49  5247.9  393.17  5289.8  394.15
    5362  397.42  5403.4  399.59  5487.8  402.18  5509.9  403.82    5540  404.62
#Mann= 13 ,-1 , 0
  4538.9      .1       0  4638.8     .05       0  4650.1      .1       0
    4883     .05       0  4972.1      .1       0  4997.5     .07       0
  5002.1      .1       0  5017.2     .12       0    5110     .05       0
  5157.7     .12       0  5247.9     .05       0    5362     .12       0
  5509.9     .05       0
Bank Sta=4997.5,5002.1
XS Rating Curve= 0 ,0
Exp/Cntr=0.3,0.1

Type RM Length L Ch R = 1 ,13171   ,505,505,505
BEGIN DESCRIPTION:
DUCK CREEK TRIB 23 28 1
END DESCRIPTION:
XS GIS Cut Line= 3
      3521391.98     10422527.36      3521117.21     10422518.25
      3520307.31     10422770.86
#Sta/Elev= 30
  4470.5  396.72  4530.4  395.85  4620.5  393.74  4745.4  392.86  4950.6  383.69
  4970.3  382.29  4975.5  382.66  4981.2   382.1  4991.7  382.02  4999.7  377.99
  5000.1  377.49  5004.2  377.49  5004.6  377.99  5008.1  381.82  5013.3  382.85
  5033.6   382.5  5054.5  381.15  5073.1  382.78  5078.3  382.47  5100.9  383.06
  5110.8  383.14  5148.8  385.05  5311.1  390.11  5376.1  393.25  5446.3  395.12
  5478.8  396.86  5516.6  397.91  5525.9  399.04  5549.1  399.38  5593.8  401.11
#Mann= 5 ,-1 , 0
  4470.5     .05       0  4950.6      .1       0  4999.7     .07       0
  5004.6      .1       0  5100.9     .05       0
Bank Sta=4999.7,5004.6
XS Rating Curve= 0 ,0
Exp/Cntr=0.3,0.1

Type RM Length L Ch R = 1 ,12666   ,698,698,698
BEGIN DESCRIPTION:
DUCK CREEK TRIB 23 27 1
END DESCRIPTION:
XS GIS Cut Line= 3
      3521492.08     10422291.64      3520792.11     10422141.64
      3520392.07     10422141.64
#Sta/Elev= 30
  4284.3   398.9  4427.5  394.41  4529.7  392.27  4595.3  392.03  4652.4   392.6
  4733.4  392.01  4775.2  391.19  4826.3  388.83  4895.1  384.01    4926  381.79
  4938.8  381.71  4969.5  380.49  4975.4  378.44  4980.6  380.32  4995.2   378.4
  4995.5   377.9  4999.7   377.9  5000.1   378.4  5002.7   378.4  5010.2  379.79
  5020.2  380.76  5094.2  379.24  5130.2  380.15  5140.2  380.79  5160.2  383.14
  5170.2  383.72  5200.2  384.73  5220.2  386.18  5270.2   387.9  5400.2  394.66
#Mann= 5 ,-1 , 0
  4284.3     .05       0  4895.1      .1       0  4995.2     .07       0
  5000.1      .1       0  5094.2     .05       0
Bank Sta=4995.2,5000.1
XS Rating Curve= 0 ,0
Exp/Cntr=0.3,0.1

Type RM Length L Ch R = 1 ,11968   ,210,210,210
BEGIN DESCRIPTION:
DUCK CREEK TRIB 23 27 0
END DESCRIPTION:
XS GIS Cut Line= 3
      3521715.04     10422068.39       3521075.1     10421684.82
      3520260.18     10421589.22
#Sta/Elev= 30
  4037.3  402.01  4255.5  395.93  4387.7   391.2  4430.5  390.26  4467.4  388.63
  4488.8  388.38    4621  383.95  4764.9  380.73  4796.5  379.33  4816.6  377.79
  4836.7  377.79  4852.7  378.67    4877   377.9  4907.2  379.06  4967.6   379.6
  4977.7  379.11  4987.8  377.38  4995.3  374.39  4995.7  373.89  4999.9  373.89
  5000.3  374.39    5018  377.66  5068.3  378.69  5128.7  381.09  5269.7   388.8
  5289.8  390.66    5372  394.54    5461  400.61  5511.3  401.73  5603.9   406.1
#Mann= 3 ,-1 , 0
  4037.3     .05       0  4995.3     .03       0  5000.3     .05       0
Bank Sta=4995.3,5000.3
XS Rating Curve= 0 ,0
Exp/Cntr=0.3,0.1

Type RM Length L Ch R = 1 ,11758   ,142,142,142
BEGIN DESCRIPTION:
DUCK CREEK TRIB 23 25 0
END DESCRIPTION:
XS GIS Cut Line= 3
      3521404.99     10421699.25      3520614.61     10421332.05
      3520255.52      10421348.9
#Sta/Elev= 30
  4409.8  390.34  4446.1  389.35  4457.1  388.58    4463  387.18  4468.5  387.67
  4485.9  386.26  4491.4  387.28  4508.8  386.09  4514.3  387.13  4531.7  387.57
  4554.6  385.46  4605.9  384.57  4628.8  383.02  4634.3  383.35  4651.7   382.1
  4697.5  380.72  4975.3  377.36  5009.1  375.72  5009.5  375.22  5013.8  375.22
  5014.1  375.72  5019.4  377.29  5118.7  379.53  5177.4  381.87  5246.1  386.78
  5384.1  392.55  5504.1   400.6  5534.1  401.48  5554.1  403.19  5640.8  405.24
#Mann= 3 ,-1 , 0
  4409.8     .05       0  5009.1     .03       0  5014.1     .05       0
Bank Sta=5009.1,5014.1
XS Rating Curve= 0 ,0
Exp/Cntr=0.3,0.1

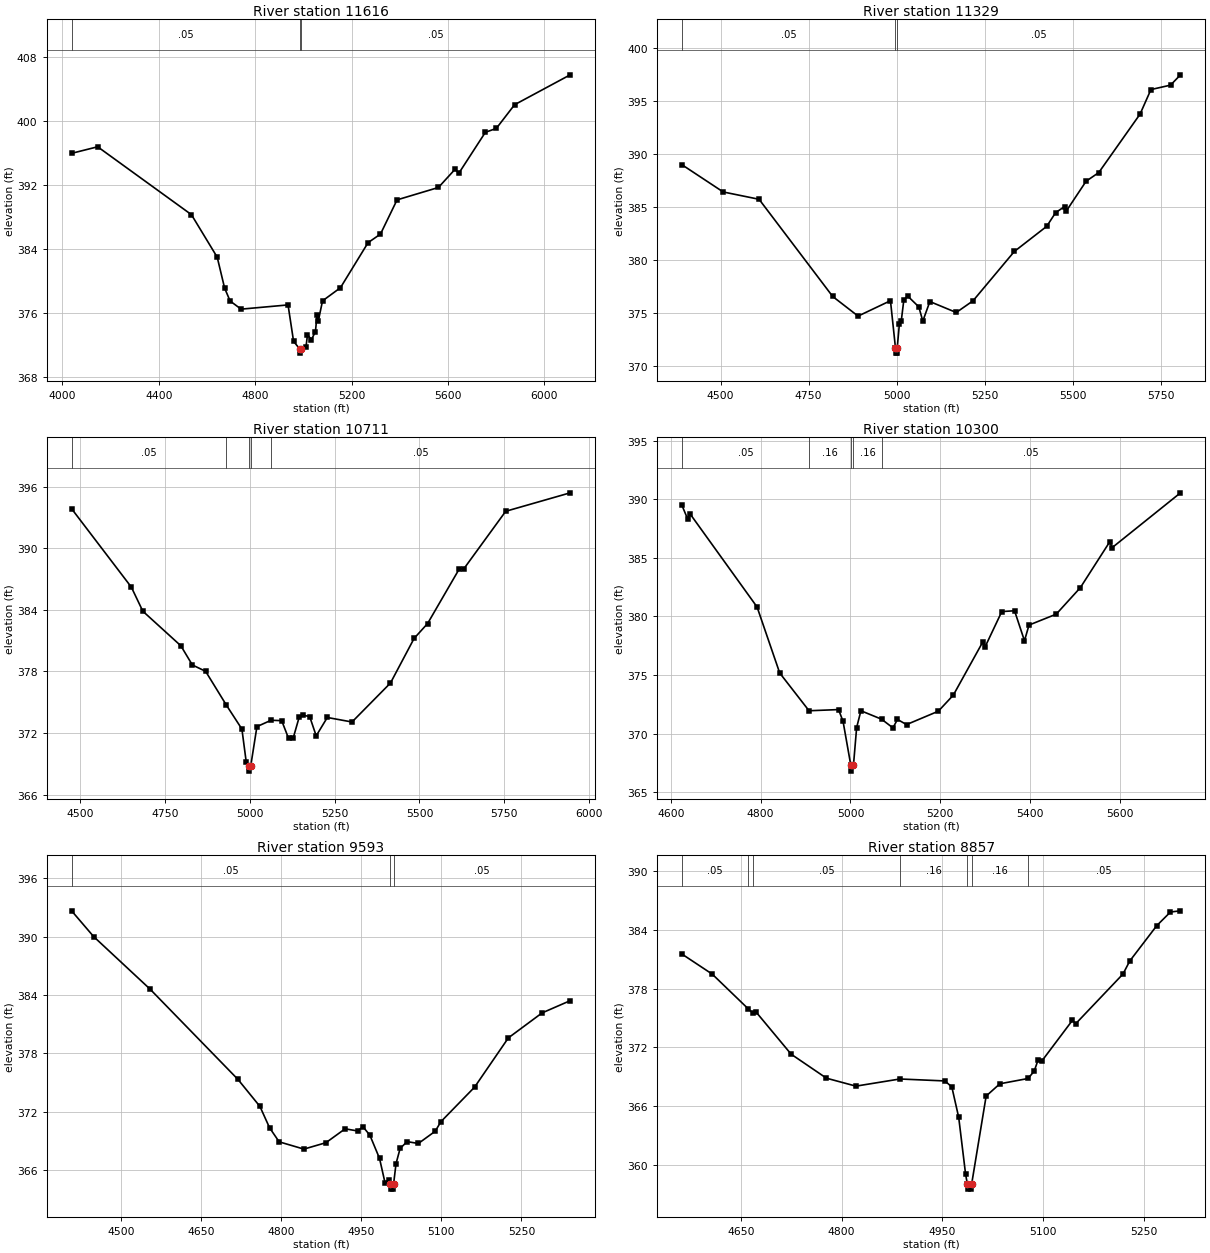
Type RM Length L Ch R = 1 ,11616   ,287,287,287
BEGIN DESCRIPTION:
DUCK CREEK TRIB 23 23 0
END DESCRIPTION:
XS GIS Cut Line= 2
      3521770.57     10421714.21      3519892.68     10420846.42
#Sta/Elev= 30
  4038.4  395.94  4146.6  396.76  4535.6  388.27  4642.6  382.95  4673.2  379.09
  4696.1  377.47  4741.7  376.45  4936.5  376.98  4959.4  372.43  4985.4  371.45
  4985.7  370.95  4990.4  371.45  5010.8  371.69  5017.1  373.24  5033.7  372.64
  5050.2  373.65  5056.7  375.75  5062.2     375  5079.6  377.49  5153.9  379.13
  5268.6  384.77    5320  385.84  5388.8  390.12  5560.4  391.67  5629.2  393.94
  5645.1  393.45  5755.2  398.57  5800.7  399.06  5876.4  402.02  6107.1  405.76
#Mann= 3 ,-1 , 0
  4038.4     .05       0  4985.4    .035       0  4990.4     .05       0
Bank Sta=4985.4,4990.4
XS Rating Curve= 0 ,0
Exp/Cntr=0.3,0.1

Type RM Length L Ch R = 1 ,11329   ,618,618,618
BEGIN DESCRIPTION:
DUCK CREEK TRIB 23 23 1
END DESCRIPTION:
XS GIS Cut Line= 3
      3521406.29     10421437.55      3521225.28     10421125.02
      3520233.16     10420766.14
#Sta/Elev= 30
  4390.3  388.97  4507.6   386.4  4609.5  385.71  4818.6  376.55  4890.7   374.7
  4982.7  376.15  4996.9  371.71  4997.3  371.21  5001.6  371.21  5001.9  371.71
    5008  373.94  5013.3  374.22  5020.7  376.23  5031.3   376.6  5063.2  375.57
  5074.6  374.23  5094.6  376.07  5169.6  375.04  5217.2  376.14  5334.5  380.79
  5426.5  383.16  5451.8  384.45  5477.1  385.02  5482.5  384.62  5538.4  387.41
  5574.4  388.23  5691.7  393.74  5722.5  396.05  5778.3  396.47  5806.5  397.44
#Mann= 3 ,-1 , 0
  4390.3     .05       0  4996.9     .03       0  5001.9     .05       0
Bank Sta=4996.9,5001.9
XS Rating Curve= 0 ,0
Exp/Cntr=0.3,0.1

Type RM Length L Ch R = 1 ,10711   ,411,411,411
BEGIN DESCRIPTION:
DUCK CREEK TRIB 23 21 2
END DESCRIPTION:
XS GIS Cut Line= 3
      3521747.37     10420674.49      3520774.76     10420398.46
      3520326.36     10420495.94
#Sta/Elev= 30
  4474.5  393.86  4650.6  386.22  4684.5  383.87  4796.6   380.5  4830.5  378.63
  4869.6  378.01  4930.9  374.71  4976.6  372.38  4989.3  369.18  4996.8  368.78
  4997.3  368.28  5002.6  368.78  5020.9  372.62  5062.7  373.24  5093.9   373.2
  5114.1  371.48  5127.8   371.5  5145.3  373.52  5155.6  373.74  5176.4   373.6
  5195.6  371.72  5228.4  373.51  5301.2  373.07  5414.6  376.87  5484.3  381.22
  5524.1  382.67  5617.2  387.98  5631.5  388.03  5754.3  393.61  5944.4  395.41
#Mann= 5 ,-1 , 0
  4474.5     .05       0  4930.9     .16       0  4996.8     .07       0
  5002.6     .16       0  5062.7     .05       0
Bank Sta=4996.8,5002.6
XS Rating Curve= 0 ,0
Exp/Cntr=0.3,0.1

Type RM Length L Ch R = 1 ,10300   ,707,707,707
BEGIN DESCRIPTION:
DUCK CREEK TRIB 23 21 1
END DESCRIPTION:
XS GIS Cut Line= 3
      3521628.18     10420178.44      3521228.22     10420128.45
       3520528.2     10420228.45
#Sta/Elev= 30
  4624.6  389.48  4637.4  388.31  4642.5  388.76    4792   380.8  4842.4  375.17
  4907.7  371.95  4973.4  372.05  4983.4  371.05  5000.7   367.3  5001.2   366.8
  5006.6   367.3  5013.7  370.52  5023.2  371.95  5069.2  371.23  5094.5  370.49
  5104.6  371.21  5124.8  370.77  5195.5  371.91  5228.9  373.28  5294.6  377.82
  5299.6  377.39  5336.9  380.41  5365.3  380.48  5387.4  377.92  5397.5  379.26
  5458.1  380.19  5511.8  382.45  5577.4  386.37  5582.5  385.86  5734.8  390.54
#Mann= 5 ,-1 , 0
  4624.6     .05       0  4907.7     .16       0  5000.7     .07       0
  5006.6     .16       0  5069.2     .05       0
Bank Sta=5000.7,5006.6
XS Rating Curve= 0 ,0
Exp/Cntr=0.3,0.1

Type RM Length L Ch R = 1 ,9593    ,736,736,736
BEGIN DESCRIPTION:
DUCK CREEK TRIB 23 21 0
END DESCRIPTION:
XS GIS Cut Line= 3
      3521742.13     10419591.65      3521142.11     10419441.64
      3520842.13     10419541.64
#Sta/Elev= 30
  4406.7  392.67    4448  390.02  4553.6  384.62  4718.5  375.32  4759.8  372.53
  4777.8  370.34  4795.8  368.89  4842.2  368.14  4883.5   368.8  4919.5  370.23
  4942.7  370.01    4953  370.44  4965.9  369.57    4984  367.18  4994.3  364.67
    5002     365  5004.1  364.52  5004.6  364.02  5009.8  364.02  5010.3  364.52
  5014.9  366.64  5022.6  368.21  5035.7  368.91  5056.8  368.72  5088.4  369.98
    5099  370.96  5162.2  374.52  5225.5  379.59  5288.7  382.16  5341.4  383.42
#Mann= 3 ,-1 , 0
  4406.7     .05       0  5004.1     .03       0  5010.3     .05       0
Bank Sta=5004.1,5010.3
XS Rating Curve= 0 ,0
Exp/Cntr=0.3,0.1

Type RM Length L Ch R = 1 ,8857    ,837,837,837
BEGIN DESCRIPTION:
DUCK CREEK TRIB 23 20 0
END DESCRIPTION:
XS GIS Cut Line= 4
      3521566.41     10419156.61      3521233.07     10419094.11
      3520972.65     10419042.03      3520837.28     10419059.38
#Sta/Elev= 30
  4562.6  381.52  4607.7  379.47  4661.5  375.91    4668   375.5  4672.4  375.64
    4725   371.3  4777.5  368.85  4821.3  368.04  4886.7  368.77  4953.7  368.57
  4963.9  367.95  4974.1  364.85  4984.3  359.07    4987  358.03  4987.5  357.53
  4992.8  357.53  4993.3  358.03  5014.9  367.03  5035.3  368.28  5077.2  368.82
  5086.3  369.57  5092.1  370.71  5097.2  370.56  5143.1  374.75  5148.2  374.42
  5218.3  379.48  5228.4  380.81  5268.7  384.43  5288.9  385.81  5303.8  385.93
#Mann= 7 ,-1 , 0
  4562.6     .05       0  4661.5      .1       0    4668     .05       0
  4886.7     .16       0    4987     .07       0  4993.3     .16       0
  5077.2     .05       0
Bank Sta=4987,4993.3
XS Rating Curve= 0 ,0
Exp/Cntr=0.3,0.1

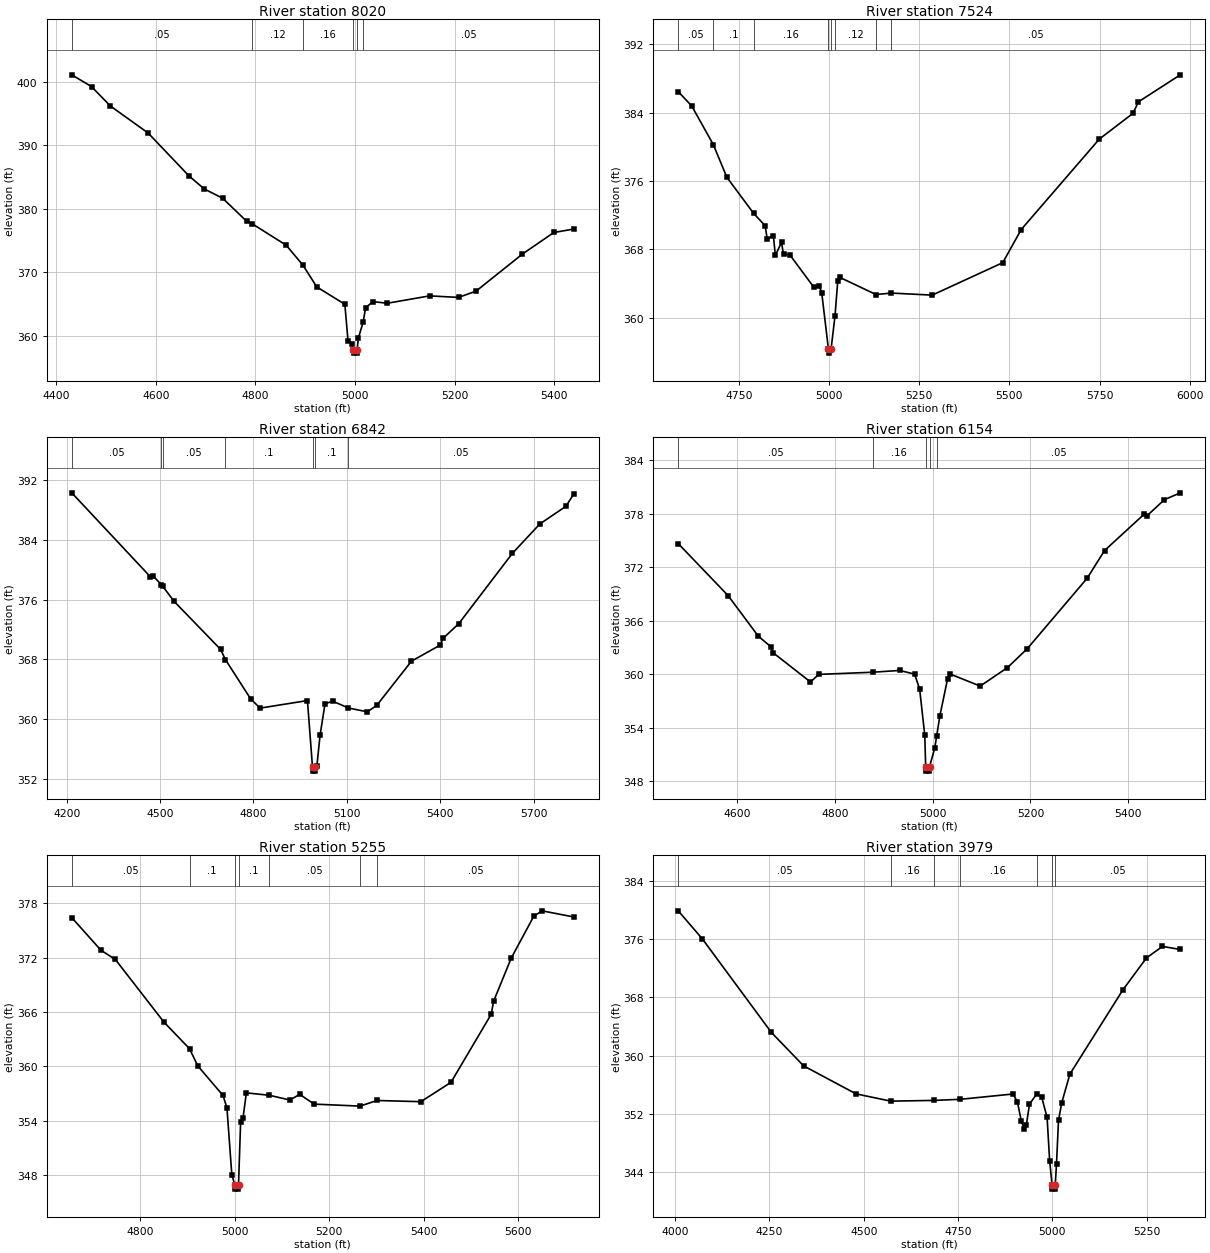
Type RM Length L Ch R = 1 ,8020    ,496,496,496
BEGIN DESCRIPTION:
DUCK CREEK TRIB 23 18 0
END DESCRIPTION:
XS GIS Cut Line= 4
       3521689.9     10418352.65      3521614.33      10418376.9
      3521189.85     10418473.26      3520800.43     10418775.68
#Sta/Elev= 30
  4431.4  401.11  4471.1  399.25  4508.9   396.2  4584.8  391.93  4666.9  385.16
  4697.6  383.12  4734.5  381.65  4782.7  378.01  4793.1  377.66  4861.7  374.27
  4895.3  371.13  4923.2  367.69  4979.5  364.95  4985.8  359.23  4993.8  358.71
  4996.6  357.76  4997.1  357.26  5003.6  357.26  5004.1  357.76  5006.6  359.63
  5016.2  362.15  5021.1  364.39  5035.6  365.38  5064.6  365.12  5149.7  366.28
  5207.6  366.04  5242.9  367.03  5335.7  372.86    5399  376.27  5439.1  376.81
#Mann= 6 ,-1 , 0
  4431.4     .05       0  4793.1     .12       0  4895.3     .16       0
  4996.6     .07       0  5004.1     .16       0  5016.2     .05       0
Bank Sta=4996.6,5004.1
XS Rating Curve= 0 ,0
Exp/Cntr=0.3,0.1

Type RM Length L Ch R = 1 ,7524    ,682,682,682
BEGIN DESCRIPTION:
DUCK CREEK TRIB 23 17 0
END DESCRIPTION:
XS GIS Cut Line= 4
      3521243.45     10418031.63      3520948.35     10418173.97
      3520740.01     10418281.61      3520049.04     10418739.94
#Sta/Elev= 30
  4582.4  386.46  4619.9  384.78  4679.7  380.25  4717.1  376.44  4791.5   372.2
  4823.4  370.76  4828.9  369.19    4846  369.62  4851.5   367.3  4868.6  368.81
  4874.1  367.41  4891.2  367.38  4957.9  363.58  4973.3  363.72  4980.1  362.89
  4998.5  356.35    4999  355.85    5006  356.35  5016.8   360.2  5024.4  364.27
    5030  364.72  5130.4  362.71  5173.1  362.88  5286.2  362.64  5481.7  366.44
  5532.8  370.32  5749.3  380.91  5842.6  383.92  5857.6  385.27  5973.7  388.43
#Mann= 8 ,-1 , 0
  4582.4     .05       0  4679.7      .1       0  4791.5     .16       0
  4998.5     .07       0    5006     .16       0  5016.8     .12       0
  5130.4      .1       0  5173.1     .05       0
Bank Sta=4998.5,5006
XS Rating Curve= 0 ,0
Exp/Cntr=0.3,0.1

Type RM Length L Ch R = 1 ,6842    ,688,688,688
BEGIN DESCRIPTION:
DUCK CREEK TRIB 23 16 0
END DESCRIPTION:
XS GIS Cut Line= 4
      3521312.18     10417786.22      3520917.97     10417738.62
      3520505.58     10417675.99      3519717.12     10417549.68
#Sta/Elev= 30
  4216.3  390.29  4468.2  379.07  4478.3  379.14  4503.5     378  4508.5  377.77
  4545.1  375.75  4694.2  369.33  4709.8  367.96  4791.3  362.67  4821.4  361.46
  4973.3  362.47  4989.6  353.52  4990.1  353.02  4996.9  353.02  4997.4  353.52
  5003.7  353.74  5013.8  357.82  5029.7  362.03  5054.3  362.39  5104.7  361.48
  5165.7  360.96    5196  361.83  5307.5  367.75  5398.6  369.87  5409.7  370.83
  5459.4  372.77  5631.5  382.18  5719.7  386.12  5803.7  388.49    5829  390.15
#Mann= 7 ,-1 , 0
  4216.3     .05       0  4503.5      .1       0  4508.5     .05       0
  4709.8      .1       0  4989.6     .07       0  4997.4      .1       0
  5104.7     .05       0
Bank Sta=4989.6,4997.4
XS Rating Curve= 0 ,0
Exp/Cntr=0.3,0.1

Type RM Length L Ch R = 1 ,6154    ,899,899,899
BEGIN DESCRIPTION:
DUCK CREEK TRIB 23 35 0
END DESCRIPTION:
XS GIS Cut Line= 2
      3521040.92     10417383.36       3520045.3      10417128.6
#Sta/Elev= 30
  4479.1  374.65  4581.1  368.83    4643  364.28  4668.2  363.12    4674  362.39
  4749.8  359.15  4766.9     360  4877.2  360.24  4932.1  360.44    4963  360.03
  4973.3  358.33  4983.7  353.19  4985.6  349.66  4986.1  349.16    4993  349.16
  4993.5  349.66  5004.3  351.78    5008  353.06  5014.6  355.35  5030.4  359.49
  5035.5  360.04  5097.2  358.69  5152.8  360.75  5193.6  362.88  5316.1  370.77
  5351.7  373.87  5433.4  377.98  5438.5  377.76  5474.2  379.57  5506.8  380.34
#Mann= 5 ,-1 , 0
  4479.1     .05       0  4877.2     .16       0  4985.6     .07       0
  4993.5     .16       0    5008     .05       0
Bank Sta=4985.6,4993.5
XS Rating Curve= 0 ,0
Exp/Cntr=0.3,0.1

Type RM Length L Ch R = 1 ,5255    ,1276,1276,1276
BEGIN DESCRIPTION:
DUCK CREEK TRIB 23 11 0
END DESCRIPTION:
XS GIS Cut Line= 2
      3521322.17     10416768.77      3520286.57     10416526.79
#Sta/Elev= 30
  4654.8  376.44  4716.5  372.84  4747.1  371.82    4850   364.9  4904.2  361.96
  4921.9  360.05  4975.1   356.8  4983.5  355.42  4993.8  348.05    5000  346.95
  5000.5  346.45  5007.5  346.45    5008  346.95  5012.5  353.89  5017.6  354.34
  5024.6  357.08  5073.1  356.82    5117  356.29  5137.5  356.92  5168.3  355.84
  5265.4  355.62  5301.3  356.24  5394.3  356.11  5458.1  358.25  5543.2  365.76
  5548.3   367.2  5585.7  371.97  5633.3  376.58    5651  377.19  5718.3  376.51
#Mann= 7 ,-1 , 0
  4654.8     .05       0  4904.2      .1       0    5000     .07       0
    5008      .1       0  5073.1     .05       0  5265.4     .16       0
  5301.3     .05       0
Bank Sta=5000,5008
XS Rating Curve= 0 ,0
Exp/Cntr=0.3,0.1

Type RM Length L Ch R = 1 ,3979    ,656,656,656
BEGIN DESCRIPTION:
DUCK CREEK TRIB 23 15 0
END DESCRIPTION:
XS GIS Cut Line= 2
       3521652.9     10416250.55      3520408.13      10415781.8
#Sta/Elev= 30
  4008.7  379.89  4072.4  376.05  4255.3  363.19  4340.8  358.59  4479.7  354.74
  4571.7  353.74  4685.7  353.84  4755.5  353.99  4895.3  354.72  4907.1  353.67
  4917.8  350.96  4925.5  349.92  4930.8  350.43  4939.2  353.31  4958.1  354.72
  4971.2  354.35  4985.9   351.5  4992.6  345.56  4999.2  342.15  4999.7  341.65
  5006.9  341.65  5007.4  342.15  5010.8  345.11  5016.1   351.1  5024.7  353.52
  5046.3  357.46  5186.7  369.03  5249.1  373.42  5291.6     375  5338.8  374.58
#Mann= 7 ,-1 , 0
  4008.7     .05       0  4571.7     .16       0  4685.7     .05       0
  4755.5     .16       0  4958.1     .05       0  4999.2     .03       0
  5007.4     .05       0
Bank Sta=4999.2,5007.4
XS Rating Curve= 0 ,0
Exp/Cntr=0.3,0.1

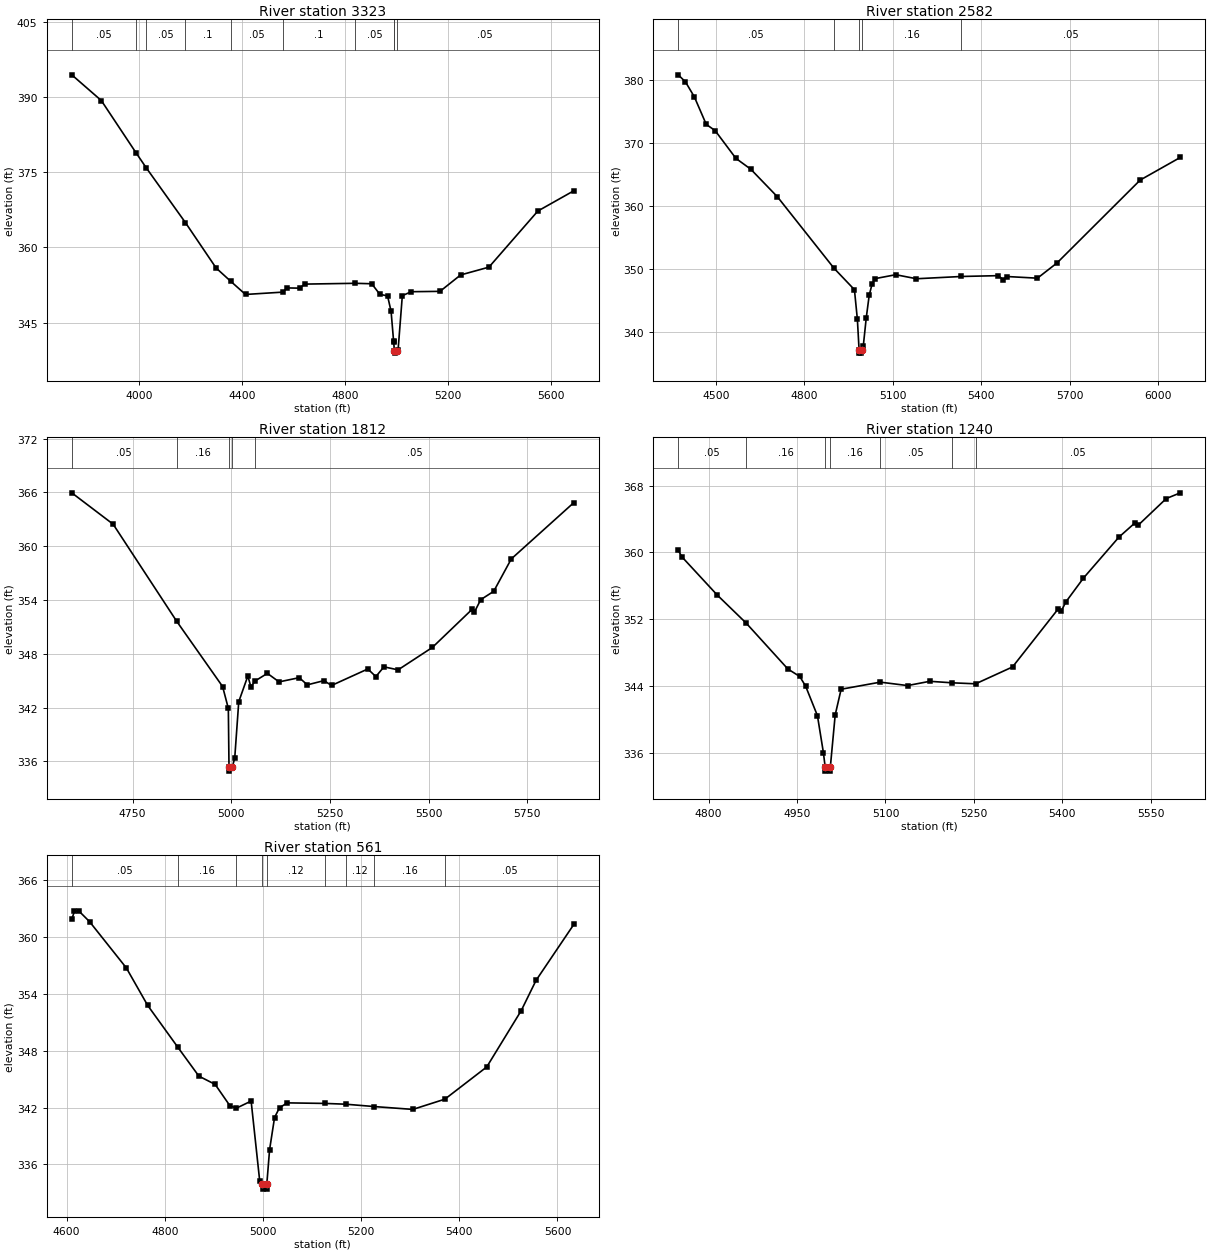
Type RM Length L Ch R = 1 ,3323    ,741,741,741
BEGIN DESCRIPTION:
DUCK CREEK TRIB 23 9 0
END DESCRIPTION:
XS GIS Cut Line= 4
      3522076.81     10415319.81      3520921.05     10415354.47
      3520692.36     10415303.98      3520132.35     10415288.56
#Sta/Elev= 30
  3739.5  394.52  3854.3  389.38  3988.4  378.99  4029.1  375.91  4181.3  364.96
  4300.3   355.9  4357.1  353.24  4414.5  350.61  4560.6  351.08  4574.6  351.92
  4624.6  351.87  4644.6  352.68  4840.9  352.84  4904.9  352.75  4936.4  350.64
  4966.4  350.32  4980.1  347.25  4989.9  341.27  4990.2  341.09    4993  339.38
  4993.5  338.88  5001.2  339.38  5007.4  339.56  5023.8  350.37  5058.6  351.16
  5170.2  351.23  5250.3  354.51  5360.3  356.07  5550.4  367.29  5690.2  371.34
#Mann= 11 ,-1 , 0
  3739.5     .05       0  3988.4      .1       0  4029.1     .05       0
  4181.3      .1       0  4357.1     .05       0  4560.6      .1       0
  4840.9     .05       0  4989.9     .16       0  4990.2     .05       0
    4993     .03       0  5001.2     .05       0
Bank Sta=4993,5001.2
XS Rating Curve= 0 ,0
Exp/Cntr=0.3,0.1

Type RM Length L Ch R = 1 ,2582    ,770,770,770
BEGIN DESCRIPTION:
DUCK CREEK TRIB 23 8 0
END DESCRIPTION:
XS GIS Cut Line= 4
      3521736.51     10414698.28      3521240.01     10414753.83
      3520940.42     10414769.47      3520059.45     10414969.11
#Sta/Elev= 30
  4372.7  380.76  4397.3  379.64  4427.4  377.27  4467.7  372.92  4497.9  371.93
  4568.3  367.54  4618.6  365.83  4709.2  361.45  4900.9  350.16  4970.3  346.76
  4980.3  342.06  4986.1  337.22  4986.6  336.72  4994.1  336.72  4994.6  337.22
  5000.4  337.87  5010.4  342.31  5020.4  345.87  5030.4   347.7  5040.4  348.51
  5110.5  349.13  5180.8  348.49  5333.3  348.85  5457.7  348.98  5474.6  348.36
  5488.4  348.84    5591  348.58  5657.4  350.99  5939.6  364.11  6075.6  367.69
#Mann= 5 ,-1 , 0
  4372.7     .05       0  4900.9     .16       0  4986.1     .07       0
  4994.6     .16       0  5333.3     .05       0
Bank Sta=4986.1,4994.6
XS Rating Curve= 0 ,0
Exp/Cntr=0.3,0.1

Type RM Length L Ch R = 1 ,1812    ,572,572,572
BEGIN DESCRIPTION:
DUCK CREEK TRIB 23 6 0
END DESCRIPTION:
XS GIS Cut Line= 2
      3521296.07     10414003.99       3520051.3     10414269.61
#Sta/Elev= 30
  4595.6  365.95  4700.5  362.45  4861.7  351.62    4978  344.35  4992.5  341.91
  4994.2  335.42  4994.7  334.92  5002.7  335.42  5008.7  336.36  5018.9  342.66
    5042  345.53  5049.6  344.33  5061.3     345  5091.5  345.82  5121.1  344.87
  5172.3  345.34  5192.7  344.54    5235  345.01  5254.1  344.47  5346.1  346.31
  5366.5  345.46    5387  346.55  5422.8  346.21  5509.7  348.71  5610.7  352.97
  5615.8  352.61  5632.4  354.04  5665.3  354.97  5709.8  358.58  5868.4  364.86
#Mann= 5 ,-1 , 0
  4595.6     .05       0  4861.7     .16       0  4994.2     .07       0
  5002.7     .16       0  5061.3     .05       0
Bank Sta=4994.2,5002.7
XS Rating Curve= 0 ,0
Exp/Cntr=0.3,0.1

Type RM Length L Ch R = 1 ,1240    ,679,679,679
BEGIN DESCRIPTION:
DUCK CREEK TRIB 23 30 0
END DESCRIPTION:
XS GIS Cut Line= 3
      3521078.24     10413542.34      3520878.22     10413542.34
      3520228.26     10413592.33
#Sta/Elev= 30
  4748.4  360.25  4754.5  359.47  4814.5  354.89  4863.6  351.53  4934.5  346.02
  4954.6  345.13  4964.6  343.96  4984.6  340.43  4994.7  336.01  4997.7  334.29
  4998.2  333.79    5006  333.79  5006.5  334.29  5014.7  340.52  5024.8   343.6
  5091.2  344.45  5137.5  344.04  5175.2  344.55  5213.2  344.37    5253  344.25
  5315.6  346.27  5393.3  353.24  5398.3  352.96  5405.9  354.04    5436  356.92
  5496.1  361.82  5523.7  363.55  5528.7  363.24  5576.4  366.44  5600.3  367.13
#Mann= 7 ,-1 , 0
  4748.4     .05       0  4863.6     .16       0  4997.7     .07       0
  5006.5     .16       0  5091.2     .05       0  5213.2     .16       0
    5253     .05       0
Bank Sta=4997.7,5006.5
XS Rating Curve= 0 ,0
Exp/Cntr=0.3,0.1

Type RM Length L Ch R = 1 ,561     ,0,0,0
BEGIN DESCRIPTION:
DUCK CREEK TRIB 23 1 0
END DESCRIPTION:
XS GIS Cut Line= 4
      3521177.48     10412920.49      3520922.56     10412863.39
      3520646.26     10412899.67      3520165.36     10412941.18
#Sta/Elev= 30
  4610.7  361.86  4616.2  362.71  4624.8  362.75  4646.9  361.61  4721.8  356.73
  4765.2  352.78  4826.7  348.36  4869.6  345.31  4902.7  344.44  4932.9  342.18
    4946  341.93    4976  342.68  4993.4  334.29  4999.1  333.89  4999.6  333.39
  5007.4  333.39  5007.9  333.89  5013.6  337.55  5023.7  340.94  5033.8  341.98
  5049.7  342.49  5127.3  342.43  5168.5  342.35    5227   342.1  5305.3   341.8
  5370.6  342.88  5455.9  346.28  5526.2  352.23  5556.3  355.41  5633.3  361.32
#Mann= 9 ,-1 , 0
  4610.7     .05       0  4826.7     .16       0    4946     .12       0
  4999.1     .07       0  5007.9     .12       0  5127.3     .16       0
  5168.5     .12       0    5227     .16       0  5370.6     .05       0
Bank Sta=4999.1,5007.9
XS Rating Curve= 0 ,0
Exp/Cntr=0.3,0.1

Chan Stop Cuts=-1
Use User Specified Reach Order=0
Composite Channel Slope=5