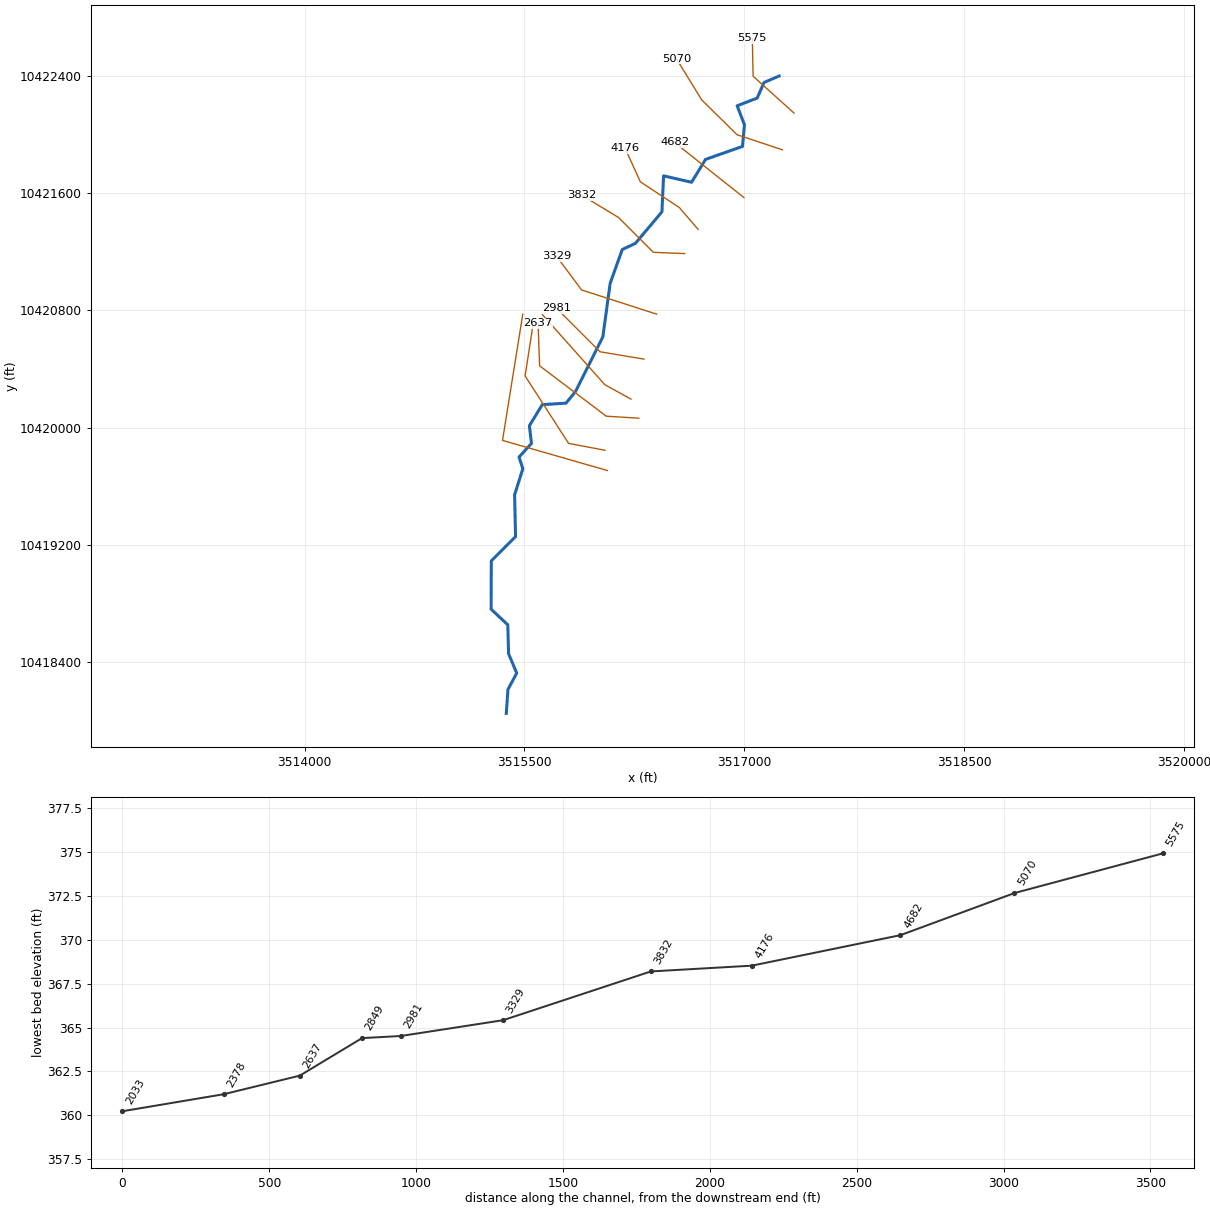
--- DUCK CREEK TRIB 24 2.prj (project) ---

Proj Title=DUCK CREEK TRIB 24 2 Base Level Engineering
Current Plan=p01
Default Exp/Contr=0.3,0.1
English Units
Geom File=g01
Flow File=f01
Plan File=p01
Y Axis Title=Elevation
X Axis Title(PF)=Main Channel Distance
X Axis Title(XS)=Station
BEGIN DESCRIPTION:
DUCK CREEK TRIB 24 2
END DESCRIPTION:
DSS Export Rating Curves= 0
DSS Export Rating Curve Sorted= 0
DSS Export Volume Flow Curves= 0
DXF OffsetX= 0
DXF OffsetY= 0
DXF ScaleX= 1
DXF ScaleY= 10

--- DUCK CREEK TRIB 24 2.p01 (plan) ---

Plan Title=Multiple Run
Short Identifier=Multiple
Geom File=g01
Flow File=f01
Subcritical Flow
K Sum by GR= 0
Std Step Tol= 0.01
Critical Tol= 0.01
Num of Std Step Trials= 20
Max Error Tol= 0.3
Flow Tol Ratio= 0.001
Split Flow NTrial= 30
Split Flow Tol= 0.02
Split Flow Ratio= 0.02
Log Output Level= 0
Friction Slope Method= 1
Unsteady Friction Slope Method= 2
Unsteady Bridges Friction Slope Method= 1
Parabolic Critical Depth
Global Vel Dist=  1 , 1 , 1
Global Log Level= 0
CheckData=True
Encroach Param= -1, 0, 0, 0
BEGIN DESCRIPTION:
Multiple Run
END DESCRIPTION:

--- DUCK CREEK TRIB 24 2.f01 (steady flow) ---

Flow Title=Multiple
Program Version=4.10
Number of Profiles= 7
Profile Names=10-year,25-year,50-year,1pct_min,100-year,1pct_plu,500-year
River Rch & RM=DUCK CREEK TRIB,Reach-1         ,5575
     703     950    1149    1016    1374    1858    1958
Boundary for River Rch & Prof#=DUCK CREEK TRIB,Reach-1         , 1
Up Type= 0
Dn Type= 3
Dn Slope=0.006
Boundary for River Rch & Prof#=DUCK CREEK TRIB,Reach-1         , 2
Up Type= 0
Dn Type= 3
Dn Slope=0.006
Boundary for River Rch & Prof#=DUCK CREEK TRIB,Reach-1         , 3
Up Type= 0
Dn Type= 3
Dn Slope=0.006
Boundary for River Rch & Prof#=DUCK CREEK TRIB,Reach-1         , 4
Up Type= 0
Dn Type= 3
Dn Slope=0.006
Boundary for River Rch & Prof#=DUCK CREEK TRIB,Reach-1         , 5
Up Type= 0
Dn Type= 3
Dn Slope=0.006
Boundary for River Rch & Prof#=DUCK CREEK TRIB,Reach-1         , 6
Up Type= 0
Dn Type= 3
Dn Slope=0.006
Boundary for River Rch & Prof#=DUCK CREEK TRIB,Reach-1         , 7
Up Type= 0
Dn Type= 3
Dn Slope=0.006
DSS Import GetInterval= 0
DSS Import GetPeak= 0
DSS Import FillOption= 0

--- DUCK CREEK TRIB 24 2.g01 (geometry) ---

Geom Title=Existing Conditions
Program Version=4.10

River Reach=DUCK CREEK TRIB ,Reach-1
Reach XY= 30
      3517238.25     10422399.76      3517134.84      10422355.4
      3517088.68     10422249.36      3516951.75      10422196.7
      3517001.61     10422066.95      3516988.25      10421919.5
      3516736.23     10421830.89      3516640.65     10421674.84
      3516449.82     10421718.65      3516438.55     10421473.11
      3516257.22     10421257.55      3516167.81     10421215.88
      3516085.34     10420985.41      3516035.43     10420619.96
      3515849.23     10420247.57      3515784.13     10420167.71
      3515622.24     10420157.72      3515534.13     10420013.63
      3515548.63     10419893.11      3515463.84     10419800.26
      3515489.55     10419719.77      3515433.31       10419542.
       3515439.9      10419257.4       3515274.4     10419091.97
      3515273.13     10418762.03      3515386.97     10418655.22
      3515392.22     10418458.02      3515447.77     10418326.07
      3515387.88      10418214.1      3515376.66     10418051.23

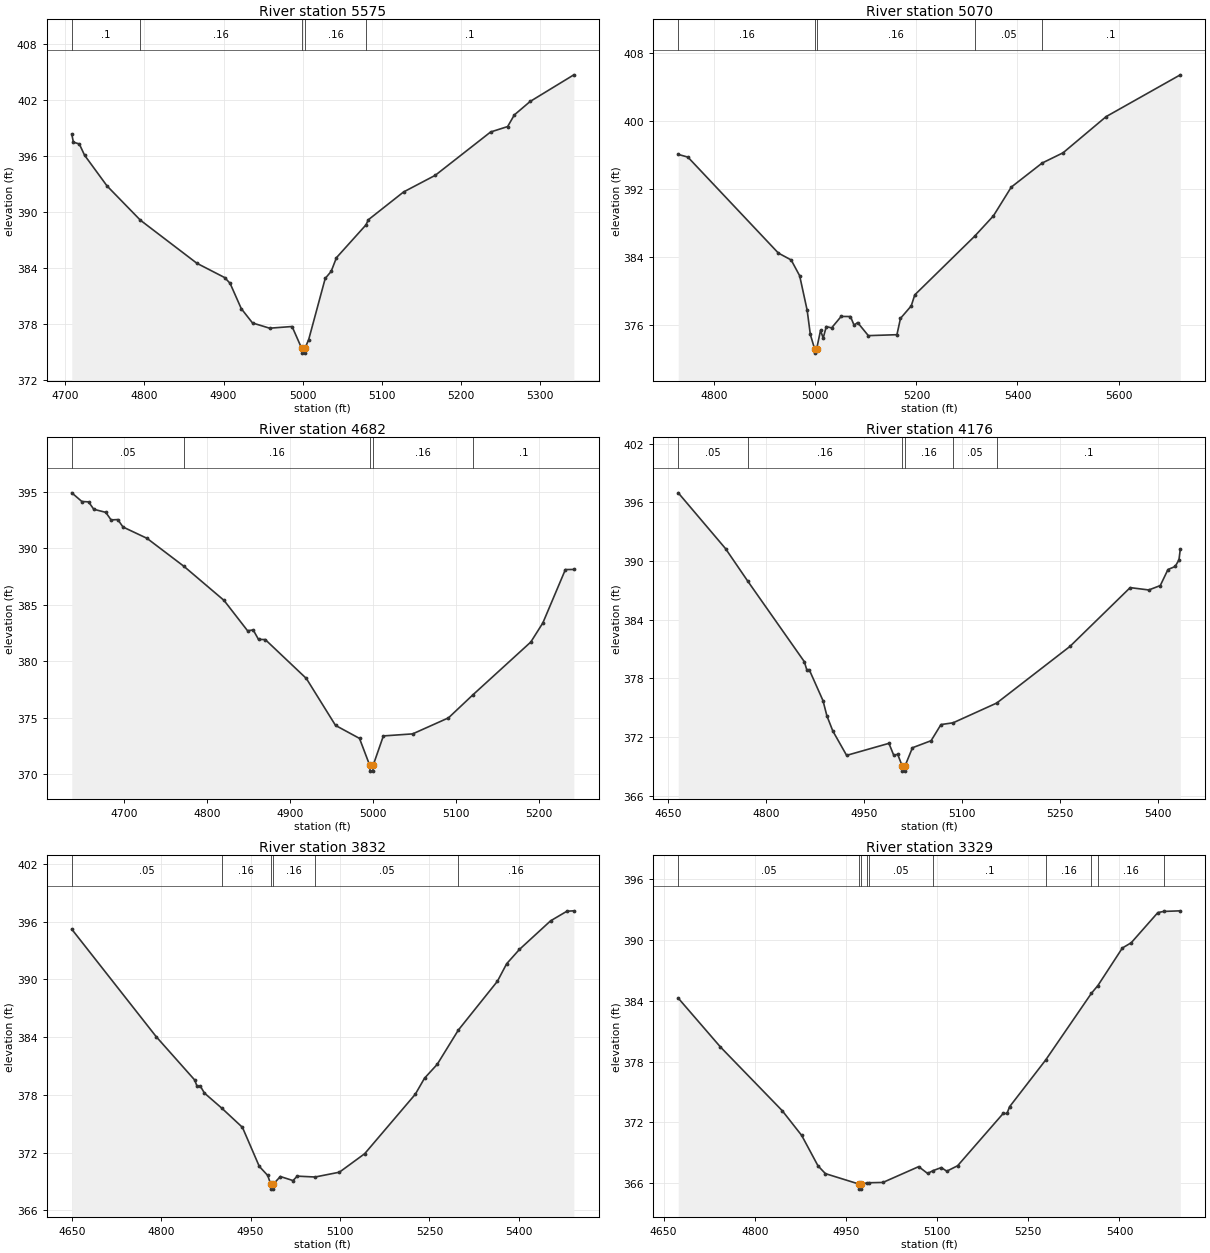
Type RM Length L Ch R = 1 ,5575    ,505,505,505
BEGIN DESCRIPTION:
DUCK CREEK TRIB 24 2 31 0
END DESCRIPTION:
XS GIS Cut Line= 3
      3517340.08     10422146.62      3517060.55     10422398.36
      3517055.35     10422656.84
#Sta/Elev= 30
  4708.1  398.39  4710.1  397.52  4717.6  397.33  4724.3  396.12  4752.7  392.83
  4794.9  389.16  4866.3  384.55  4901.4  383.02  4908.2  382.41  4922.4  379.69
  4936.6  378.16  4958.2   377.6  4986.6  377.78  4998.8  375.43  4999.1  374.93
  5002.6  374.93  5002.8  375.43  5007.6  376.38  5028.5  382.93    5036  383.68
  5042.7  385.15    5080  388.66    5083  389.21  5127.6  392.19  5167.6  393.97
  5237.6  398.61  5259.1  399.19  5267.6  400.44  5287.6  401.88  5342.8  404.73
#Mann= 5 ,-1 , 0
  4708.1      .1       0  4794.9     .16       0  4998.8     .07       0
  5002.8     .16       0    5080      .1       0
Bank Sta=4998.8,5002.8
XS Rating Curve= 0 ,0
Exp/Cntr=0.3,0.1

Type RM Length L Ch R = 1 ,5070    ,388,388,388
BEGIN DESCRIPTION:
DUCK CREEK TRIB 24 2 8 1
END DESCRIPTION:
XS GIS Cut Line= 4
      3517260.19     10421896.63      3516951.18     10421999.06
      3516709.86     10422236.91       3516537.7     10422517.53
#Sta/Elev= 30
  4728.7  396.07  4747.8  395.75  4926.9  384.45  4952.2  383.64    4969  381.78
  4983.9   377.7  4990.1  374.87  4998.6  373.17  4998.8  372.67  5002.6  373.17
  5010.3  375.34  5015.6  374.45  5021.7   375.8  5032.2  375.64  5051.1  376.99
  5069.5  376.98  5076.7  375.96  5083.7  376.27  5104.9  374.73  5161.5  374.84
  5168.5  376.76  5189.8  378.23  5196.8  379.53  5315.2  386.43  5352.4  388.83
  5387.8  392.22  5448.8  395.05  5490.3  396.26  5575.5  400.52  5722.3  405.44
#Mann= 5 ,-1 , 0
  4728.7     .16       0  4998.6     .07       0  5002.6     .16       0
  5315.2     .05       0  5448.8      .1       0
Bank Sta=4998.6,5002.6
XS Rating Curve= 0 ,0
Exp/Cntr=0.3,0.1

Type RM Length L Ch R = 1 ,4682    ,506,506,506
BEGIN DESCRIPTION:
DUCK CREEK TRIB 24 2 8 0
END DESCRIPTION:
XS GIS Cut Line= 2
      3516998.09     10421570.21      3516524.09     10421946.98
#Sta/Elev= 30
  4636.9  394.93  4649.1  394.16  4657.1  394.13  4663.5  393.47  4677.9   393.2
  4684.3  392.53  4692.4  392.56  4698.7   391.9  4727.6   390.9  4772.3  388.41
  4820.5   385.4  4848.9  382.71  4855.7  382.78  4862.1  381.94  4870.2  381.93
  4919.8  378.48    4955  374.32  4983.9  373.17  4996.3  370.77  4996.6  370.27
  5000.1  370.27  5000.3  370.77  5012.7  373.39    5048  373.57  5091.2  374.99
  5120.5  377.02  5190.5  381.71    5205   383.4  5232.2  388.13  5242.4  388.14
#Mann= 5 ,-1 , 0
  4636.9     .05       0  4772.3     .16       0  4996.3     .07       0
  5000.3     .16       0  5120.5      .1       0
Bank Sta=4996.3,5000.3
XS Rating Curve= 0 ,0
Exp/Cntr=0.3,0.1

Type RM Length L Ch R = 1 ,4176    ,344,344,344
BEGIN DESCRIPTION:
DUCK CREEK TRIB 24 2 7 0
END DESCRIPTION:
XS GIS Cut Line= 4
      3516685.55     10421353.23      3516557.08     10421502.53
      3516291.46     10421677.88      3516186.32     10421908.83
#Sta/Elev= 30
  4665.4  396.98  4737.8  391.28  4771.8  387.96  4858.5  379.72  4862.3  378.89
  4866.1  378.89  4887.1  375.74  4893.1  374.18  4902.2  372.63  4923.3  370.14
  4988.1  371.37  4995.5  370.15  5001.5  370.25  5008.6  369.03  5008.8  368.53
  5012.3  368.53  5012.6  369.03  5024.1  370.92  5052.7  371.64  5067.8  373.29
  5086.4  373.47  5153.2  375.49  5265.4  381.28  5357.6  387.29  5386.1  387.05
  5403.7   387.5  5415.5  389.14  5426.5  389.45  5432.3  390.12  5434.4  391.23
#Mann= 6 ,-1 , 0
  4665.4     .05       0  4771.8     .16       0  5008.6     .07       0
  5012.6     .16       0  5086.4     .05       0  5153.2      .1       0
Bank Sta=5008.6,5012.6
XS Rating Curve= 0 ,0
Exp/Cntr=0.3,0.1

Type RM Length L Ch R = 1 ,3832    ,503,503,503
BEGIN DESCRIPTION:
DUCK CREEK TRIB 24 2 6 0
END DESCRIPTION:
XS GIS Cut Line= 4
      3516593.56     10421188.29        3516380.     10421196.97
      3516142.15     10421434.82      3515892.15     10421585.87
#Sta/Elev= 30
  4650.1  395.22  4791.7  384.05  4856.2  379.55  4860.3  378.89  4865.9  378.89
  4872.7  378.18  4901.7  376.62  4936.4  374.62  4964.6  370.57  4978.8  369.62
  4983.9   368.7  4984.1   368.2  4987.6   368.2  4987.9   368.7    5000  369.51
  5021.2  369.09  5028.3  369.55  5058.3  369.46    5099  369.96  5141.4  371.88
  5226.3  378.06  5241.8  379.73  5263.1  381.17  5298.5  384.73  5364.1  389.81
  5379.6  391.63  5400.9  393.11  5453.3  396.09  5480.7  397.09  5492.3  397.13
#Mann= 6 ,-1 , 0
  4650.1     .05       0  4901.7     .16       0  4983.9     .07       0
  4987.9     .16       0  5058.3     .05       0  5298.5     .16       0
Bank Sta=4983.9,4987.9
XS Rating Curve= 0 ,0
Exp/Cntr=0.3,0.1

Type RM Length L Ch R = 1 ,3329    ,348,348,348
BEGIN DESCRIPTION:
DUCK CREEK TRIB 24 2 3 2
END DESCRIPTION:
XS GIS Cut Line= 3
      3516402.57      10420775.1      3515890.41     10420940.03
      3515718.55     10421170.92
#Sta/Elev= 30
  4674.2  384.28  4743.7  379.45  4845.2  373.17  4877.3  370.72  4904.1  367.72
  4916.3  366.95  4971.5  365.92  4971.7  365.42  4975.2  365.42  4975.5  365.92
  4984.6  366.03  4987.7  366.05  5010.9  366.08  5069.7  367.64  5084.4  366.97
  5093.5  367.25    5107  367.55  5115.9  367.19  5133.8  367.73  5208.7  372.89
    5215  372.89  5219.2  373.55  5278.5  378.16  5353.9  384.76  5364.5  385.52
  5404.8  389.23  5419.4  389.75  5463.2  392.73  5472.8  392.84  5500.1   392.9
#Mann= 10 ,-1 , 0
  4674.2     .05       0  4971.5     .03       0  4975.5     .05       0
  4984.6     .16       0  4987.7     .05       0  5093.5      .1       0
  5278.5     .16       0  5353.9      .1       0  5364.5     .16       0
  5472.8     .05       0
Bank Sta=4971.5,4975.5
XS Rating Curve= 0 ,0
Exp/Cntr=0.3,0.1

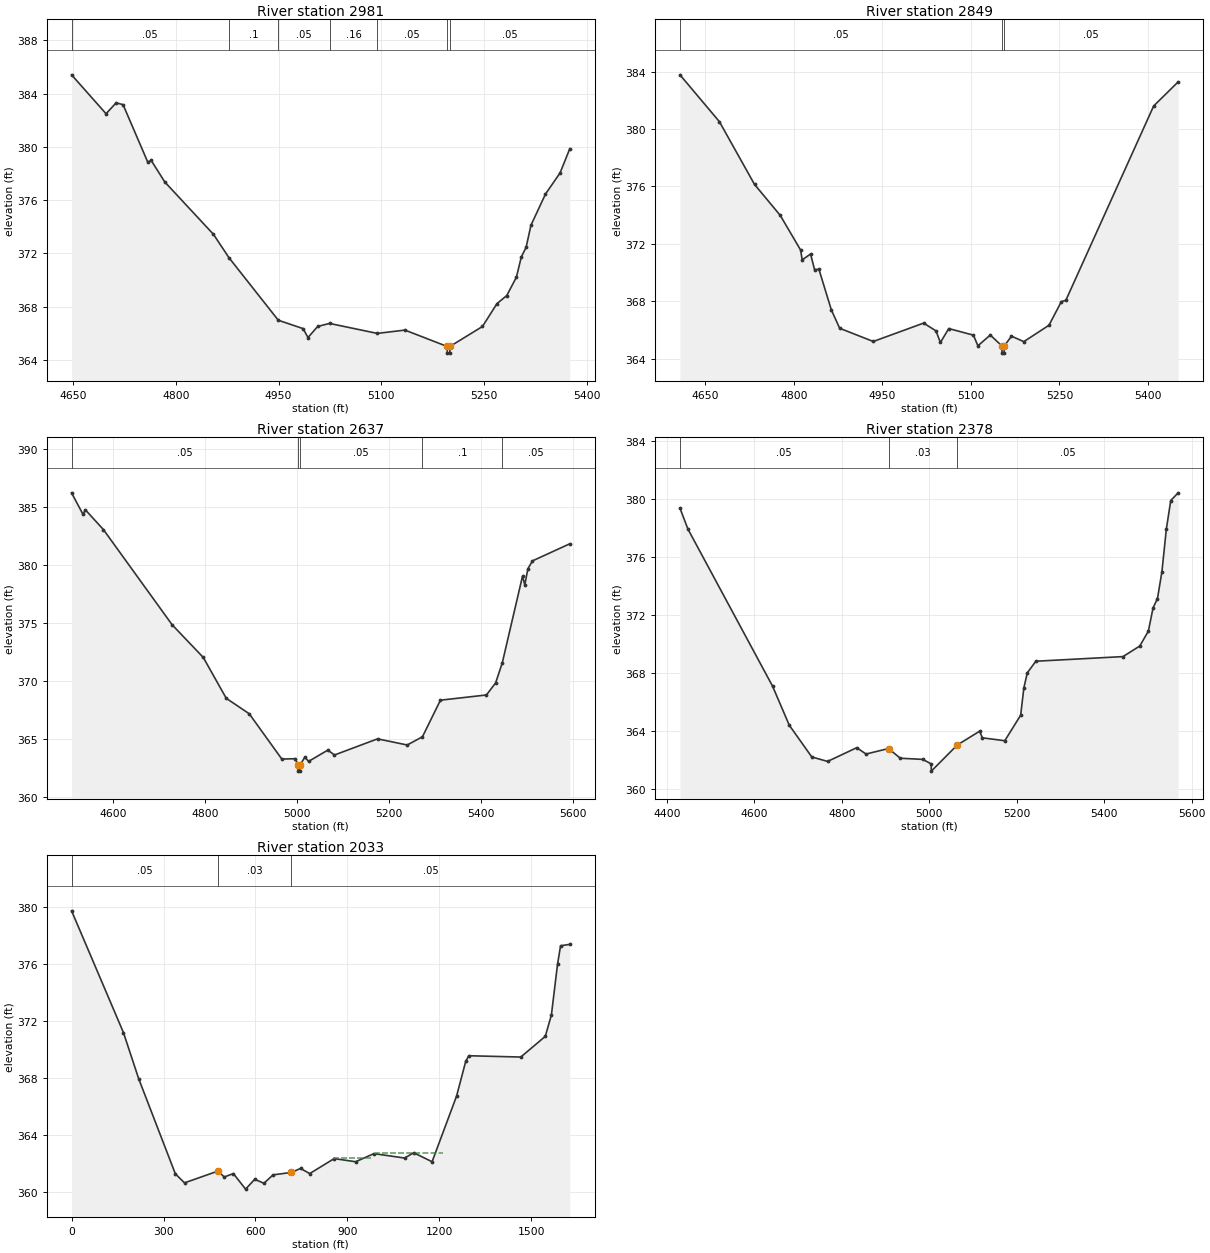
Type RM Length L Ch R = 1 ,2981    ,132,132,132
BEGIN DESCRIPTION:
DUCK CREEK TRIB 24 2 4 0
END DESCRIPTION:
XS GIS Cut Line= 3
      3516316.19     10420468.28      3516016.15     10420518.29
      3515717.45     10420816.99
#Sta/Elev= 30
  4648.1  385.41  4698.4  382.49  4713.1  383.31  4723.2  383.17  4759.2  378.86
  4764.3  378.98    4784  377.37    4855  373.44  4877.7  371.68  4949.6  366.99
  4985.8  366.36  4992.9  365.69    5007  366.52  5024.3  366.75    5094     366
  5134.3  366.25  5195.9  365.02  5196.2  364.52  5199.7  364.52  5199.9  365.02
  5247.4  366.52  5268.6  368.24  5282.8  368.84  5296.9  370.22    5304  371.73
  5311.1  372.47  5318.1  374.12  5339.3  376.46  5360.6  378.05  5374.7  379.86
#Mann= 7 ,-1 , 0
  4648.1     .05       0  4877.7      .1       0  4949.6     .05       0
  5024.3     .16       0    5094     .05       0  5195.9     .03       0
  5199.9     .05       0
Bank Sta=5195.9,5199.9
XS Rating Curve= 0 ,0
Exp/Cntr=0.3,0.1

Type RM Length L Ch R = 1 ,2849    ,212,212,212
BEGIN DESCRIPTION:
DUCK CREEK TRIB 24 2 3 3
END DESCRIPTION:
XS GIS Cut Line= 3
      3516227.22     10420195.24       3516048.4      10420294.2
      3515623.05     10420771.63
#Sta/Elev= 30
  4607.2  383.77    4674  380.51  4733.5  376.14    4777  373.99  4811.6  371.57
  4814.2  370.89  4828.4   371.3  4835.1  370.22  4842.6  370.23  4863.5  367.42
  4877.7  366.13  4934.6  365.21  5019.9  366.49  5040.8  365.95  5048.3  365.14
  5062.5  366.11  5104.3  365.65  5111.8  364.91  5132.8  365.66  5152.5   364.9
  5152.7   364.4  5156.2   364.4  5156.5   364.9  5168.7  365.58  5189.6   365.2
  5232.2  366.34  5253.2  367.99  5260.7  368.07  5409.5   381.6    5451  383.28
#Mann= 3 ,-1 , 0
  4607.2     .05       0  5152.5     .03       0  5156.5     .05       0
Bank Sta=5152.5,5156.5
XS Rating Curve= 0 ,0
Exp/Cntr=0.3,0.1

Type RM Length L Ch R = 1 ,2637    ,259,259,259
BEGIN DESCRIPTION:
DUCK CREEK TRIB 24 2 2 1
END DESCRIPTION:
XS GIS Cut Line= 4
      3516281.03     10420065.03      3516058.82     10420078.92
      3515603.96     10420422.67      3515593.54     10420712.59
#Sta/Elev= 30
  4509.7  386.23  4534.6  384.37  4539.6  384.77  4578.8  383.07  4728.2  374.87
    4796  372.05    4846  368.53  4895.9   367.2  4966.7   363.3  4995.8  363.33
    5002  362.76  5002.2  362.26  5005.7  362.26    5006  362.76  5016.7  363.46
    5025   363.1  5066.7  364.07  5081.2  363.65  5174.8  365.04  5239.3  364.51
  5272.4  365.22  5311.5  368.37  5411.5  368.82  5431.5  369.86  5445.9  371.58
  5489.9  379.05  5494.9  378.31  5501.6  379.69  5511.6  380.37  5592.6  381.84
#Mann= 5 ,-1 , 0
  4509.7     .05       0    5002     .03       0    5006     .05       0
  5272.4      .1       0  5445.9     .05       0
Bank Sta=5002,5006
XS Rating Curve= 0 ,0
Exp/Cntr=0.3,0.1

Type RM Length L Ch R = 1 ,2378    ,345,345,345
BEGIN DESCRIPTION:
DUCK CREEK TRIB 24 2 50
END DESCRIPTION:
XS GIS Cut Line= 4
      3516050.12     10419846.28      3515801.87     10419893.16
        3515505.     10420353.22      3515556.82     10420688.37
#Sta/Elev= 30
  4429.9  379.36  4448.2  377.91  4641.6  367.07  4679.9  364.37  4731.3  362.18
  4767.5  361.87  4834.2  362.82  4855.3  362.38  4906.8  362.76  4933.8  362.09
  4985.3  362.01  5004.4   361.7  5004.7   361.2  5063.9     363  5115.3  363.96
  5121.3   363.5  5172.7   363.3    5209  365.06  5216.3  366.94  5224.2  367.99
  5243.8  368.79  5443.1  369.11  5481.4  369.84  5501.1  370.87  5511.8  372.47
  5521.9  373.12    5532  374.96  5542.2  377.92  5552.3  379.89  5569.2  380.42
#Mann= 3 , 0 , 0
  4429.9     .05       0  4906.8     .03       0  5063.9     .05       0
Bank Sta=4906.8,5063.9
XS Rating Curve= 0 ,0
Exp/Cntr=0.3,0.1

Type RM Length L Ch R = 1 ,2033    ,0,0,0
XS GIS Cut Line= 3
     3516066.605    10419708.064     3515350.917    10419913.558
     3515489.094    10420774.509
#Sta/Elev= 30
       0  379.74  169.33   371.2  219.13  367.96  338.66   361.3  368.54  360.67
  478.11   361.5  498.03  361.08  527.91  361.32  567.75  360.23  597.64  360.92
  627.52  360.64   657.4  361.23  717.16   361.4  747.05  361.68  776.99  361.32
  856.85  362.37  926.72  362.15  986.61  362.72 1086.43  362.41 1116.38  362.78
 1176.27  362.15 1256.13  366.75 1286.07  369.19 1296.06  369.58 1465.75  369.49
 1545.61  370.94 1565.57  372.44 1585.53  375.99 1595.52  377.29 1625.46  377.39
#Mann= 3 , 0 , 0
       0     .05       0  478.11     .03       0  717.16     .05       0
#XS Ineff= 2 ,-1
  856.24  979.58  362.43  990.05 1213.34  362.76
Permanent Ineff=
       F       F
Bank Sta=478.11,717.16
XS Rating Curve= 0 ,0
Exp/Cntr=0.3,0.1

Chan Stop Cuts=-1
Use User Specified Reach Order=0
Composite Channel Slope=5