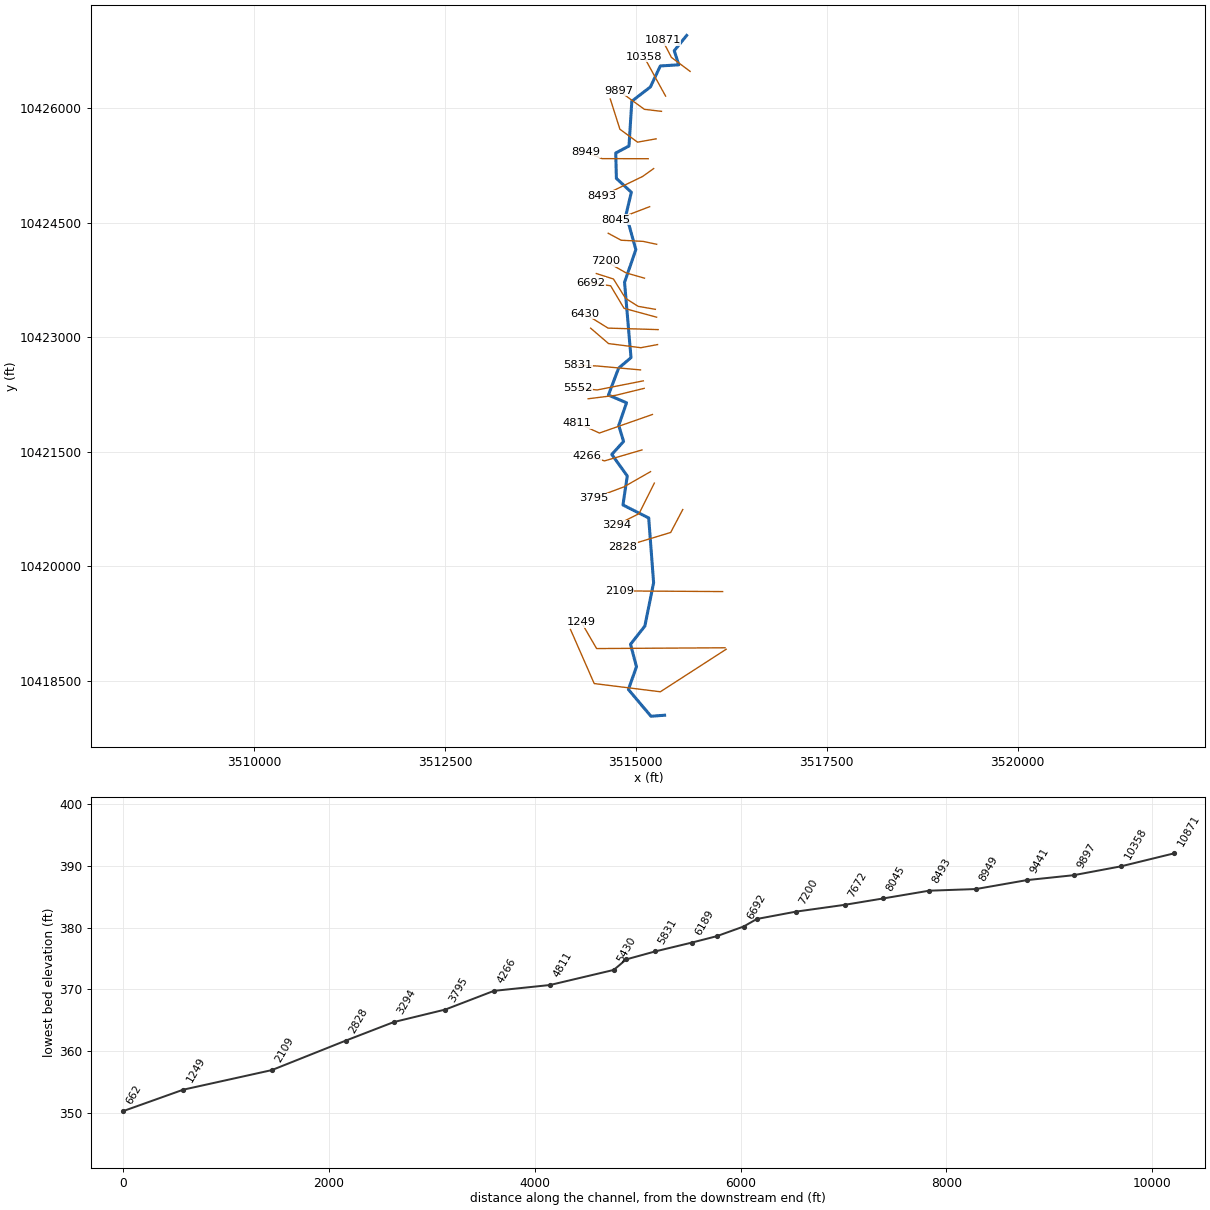
--- DUCK CREEK TRIB 24 3.prj (project) ---

Proj Title=DUCK CREEK TRIB 24 3 Base Level Engineering
Current Plan=p01
Default Exp/Contr=0.3,0.1
English Units
Geom File=g01
Flow File=f01
Plan File=p01
Y Axis Title=Elevation
X Axis Title(PF)=Main Channel Distance
X Axis Title(XS)=Station
BEGIN DESCRIPTION:
DUCK CREEK TRIB 24 3
END DESCRIPTION:
DSS Export Rating Curves= 0
DSS Export Rating Curve Sorted= 0
DSS Export Volume Flow Curves= 0
DXF OffsetX= 0
DXF OffsetY= 0
DXF ScaleX= 1
DXF ScaleY= 10

--- DUCK CREEK TRIB 24 3.p01 (plan) ---

Plan Title=Multiple Run
Short Identifier=Multiple
Geom File=g01
Flow File=f01
Subcritical Flow
K Sum by GR= 0
Std Step Tol= 0.01
Critical Tol= 0.01
Num of Std Step Trials= 20
Max Error Tol= 0.3
Flow Tol Ratio= 0.001
Split Flow NTrial= 30
Split Flow Tol= 0.02
Split Flow Ratio= 0.02
Log Output Level= 0
Friction Slope Method= 1
Unsteady Friction Slope Method= 2
Unsteady Bridges Friction Slope Method= 1
Parabolic Critical Depth
Global Vel Dist=  1 , 1 , 1
Global Log Level= 0
CheckData=True
Encroach Param= -1, 0, 0, 0
BEGIN DESCRIPTION:
Multiple Run
END DESCRIPTION:

--- DUCK CREEK TRIB 24 3.f01 (steady flow) ---

Flow Title=Multiple
Number of Profiles=7
Profile Names=10-year,25-year,50-year,1pct_min,100-year,1pct_plu,500-year
River Rch & RM= DUCK CREEK TRIB ,Reach-1,10871
     888    1216    1486    1324    1791    2422    2597
River Rch & RM= DUCK CREEK TRIB ,Reach-1,6189
    1156    1604    1976    1775    2400    3246    3534
Boundary for River Rch & Prof#=DUCK CREEK TRIB ,Reach-1,1
Up Type=0
Dn Type=3
Dn Slope=0.005
Boundary for River Rch & Prof#=DUCK CREEK TRIB ,Reach-1,2
Up Type=0
Dn Type=3
Dn Slope=0.005
Boundary for River Rch & Prof#=DUCK CREEK TRIB ,Reach-1,3
Up Type=0
Dn Type=3
Dn Slope=0.005
Boundary for River Rch & Prof#=DUCK CREEK TRIB ,Reach-1,4
Up Type=0
Dn Type=3
Dn Slope=0.005
Boundary for River Rch & Prof#=DUCK CREEK TRIB ,Reach-1,5
Up Type=0
Dn Type=3
Dn Slope=0.005
Boundary for River Rch & Prof#=DUCK CREEK TRIB ,Reach-1,6
Up Type=0
Dn Type=3
Dn Slope=0.005
Boundary for River Rch & Prof#=DUCK CREEK TRIB ,Reach-1,7
Up Type=0
Dn Type=3
Dn Slope=0.005

--- DUCK CREEK TRIB 24 3.g01 (geometry) ---

Geom Title=Existing Conditions
Program Version=4.10

River Reach=DUCK CREEK TRIB ,Reach-1
Reach XY= 30
      3515665.34      10426955.3      3515503.11      10426755.7
        3515562.     10426570.85       3515320.6     10426555.88
      3515191.08     10426281.45       3514947.4     10426094.09
       3514910.3     10425507.61      3514736.89     10425415.36
      3514745.13     10425083.13       3514940.9     10424901.51
      3514872.07     10424610.57      3515000.13      10424150.1
      3514851.97     10423721.63      3514936.53     10422734.93
      3514774.03     10422597.43       3514640.7     10422244.65
      3514878.26     10422144.18       3514775.8     10421848.08
       3514839.1     10421637.22      3514685.09      10421467.1
       3514887.5     10421185.08      3514831.22     10420805.42
      3515168.41     10420635.09      3515232.66     10419786.54
      3515117.85     10419218.82      3514930.29     10418980.66
      3515008.27     10418686.38      3514902.45     10418388.37
      3515198.12     10418037.86      3515376.66     10418051.23

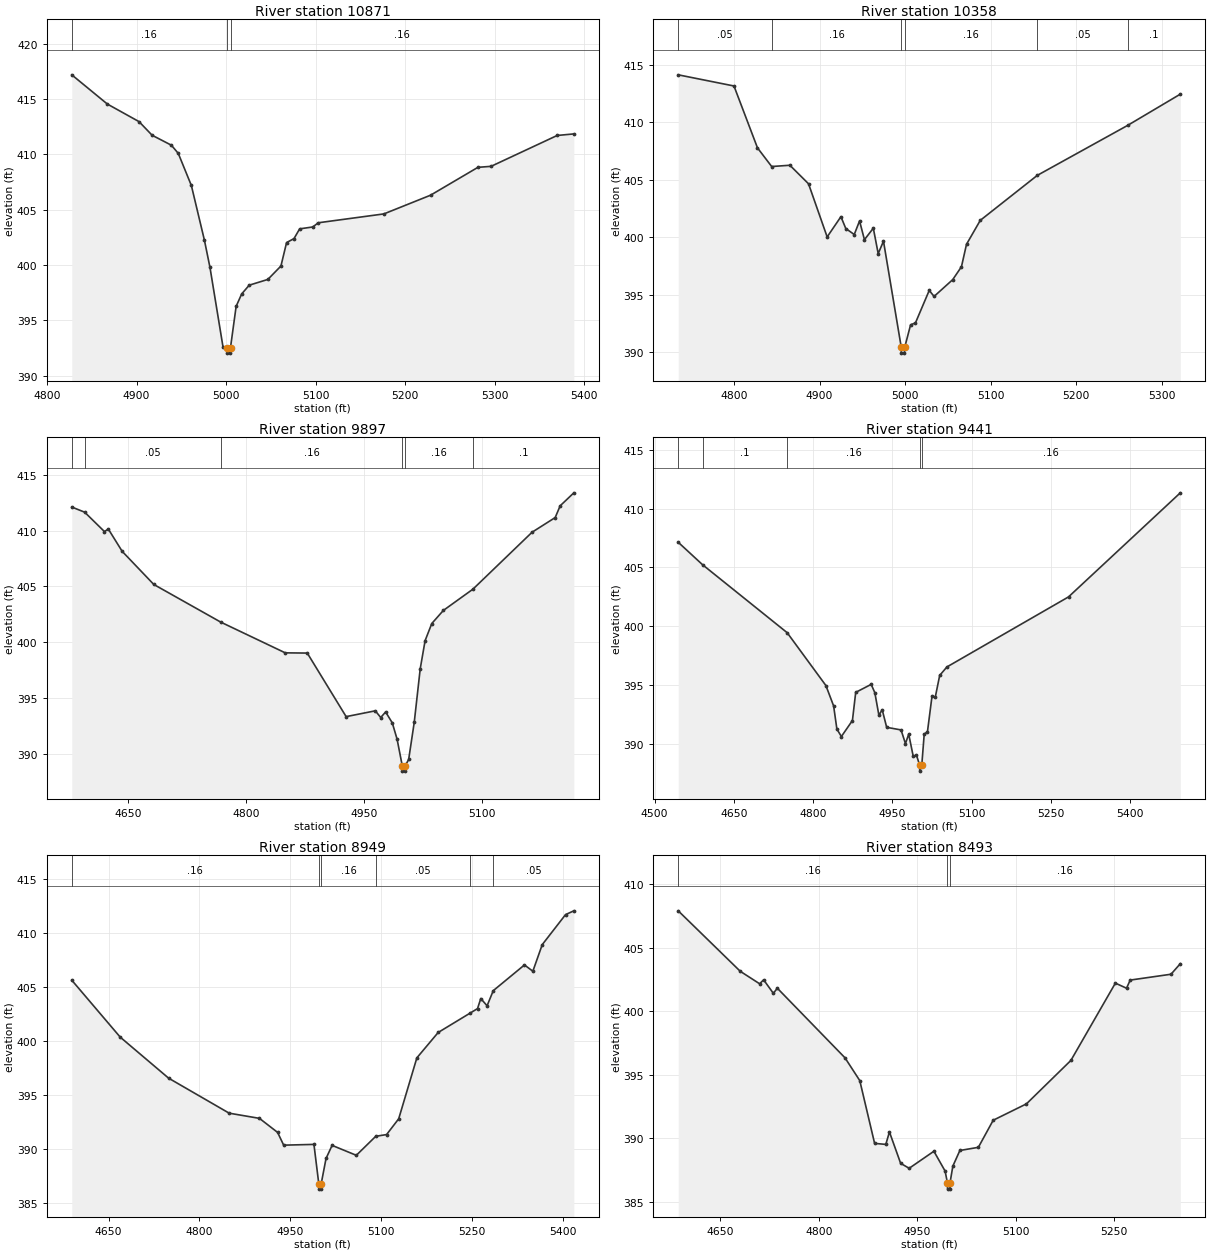
Type RM Length L Ch R = 1 ,10871   ,513,513,513
BEGIN DESCRIPTION:
DUCK CREEK TRIB 24 3 3 0
END DESCRIPTION:
XS GIS Cut Line= 3
      3515711.15     10426484.57      3515465.96     10426667.92
      3515348.75     10426893.64
#Sta/Elev= 30
  4827.7  417.18  4867.4  414.54  4902.8  412.95  4917.4  411.72  4938.9  410.82
  4946.6  410.08  4961.2  407.18  4975.8  402.23    4982  399.77  4996.6  392.56
  5000.9  392.53  5001.1  392.03  5004.6  392.03  5004.9  392.53  5011.2  396.26
  5017.4  397.38  5025.8  398.17  5046.6  398.69  5061.2   399.9  5067.5  402.02
  5075.8  402.38  5082.1  403.26  5096.7  403.43  5102.9  403.81  5176.1  404.61
  5228.2   406.3  5281.1  408.82  5295.8  408.91  5369.6   411.7  5388.2  411.84
#Mann= 3 ,-1 , 0
  4827.7     .16       0  5000.9     .07       0  5004.9     .16       0
Bank Sta=5000.9,5004.9
XS Rating Curve= 0 ,0
Exp/Cntr=0.3,0.1

Type RM Length L Ch R = 1 ,10358   ,461,461,461
BEGIN DESCRIPTION:
DUCK CREEK TRIB 24 3 2 0
END DESCRIPTION:
XS GIS Cut Line= 2
      3515389.37     10426161.17      3515106.81     10426676.03
#Sta/Elev= 30
  4734.7  414.13  4799.9  413.16  4827.4  407.78    4844  406.16  4865.3  406.27
  4887.1  404.66  4908.9  400.04    4925   401.8  4930.7  400.77  4940.6  400.25
  4946.8  401.43  4952.5   399.8  4962.9   400.8  4968.6  398.59  4974.8  399.67
  4995.6  390.44  4995.8  389.94  4999.3  389.94  4999.6  390.44  5006.5   392.4
  5012.2  392.57  5028.3  395.39    5034  394.87  5055.8  396.33    5066  397.45
  5071.9   399.4    5088  401.48  5154.7  405.39  5260.3  409.73    5322  412.45
#Mann= 6 ,-1 , 0
  4734.7     .05       0    4844     .16       0  4995.6     .07       0
  4999.6     .16       0  5154.7     .05       0  5260.3      .1       0
Bank Sta=4995.6,4999.6
XS Rating Curve= 0 ,0
Exp/Cntr=0.3,0.1

Type RM Length L Ch R = 1 ,9897    ,456,456,456
BEGIN DESCRIPTION:
DUCK CREEK TRIB 24 3 18 0
END DESCRIPTION:
XS GIS Cut Line= 3
      3515335.74     10425961.54      3515112.22     10425987.58
        3514778.     10426230.66
#Sta/Elev= 30
  4578.8   412.1  4595.2  411.64  4620.3  409.91  4625.3  410.13  4642.9  408.14
  4683.1  405.18  4768.1  401.82  4850.2  399.07  4878.2  399.05  4927.6  393.37
  4964.7  393.89  4971.6  393.29  4977.8  393.79  4986.3  392.81  4992.4  391.35
  4998.9     389  4999.2   388.5  5002.7   388.5  5002.9     389  5007.1  389.54
  5014.2  392.86  5021.8  397.65    5028  400.16  5036.5  401.69  5051.2  402.86
  5088.8  404.76    5164  409.85  5193.4  411.16  5199.7  412.21  5217.1  413.37
#Mann= 6 ,-1 , 0
  4578.8      .1       0  4595.2     .05       0  4768.1     .16       0
  4998.9     .07       0  5002.9     .16       0  5088.8      .1       0
Bank Sta=4998.9,5002.9
XS Rating Curve= 0 ,0
Exp/Cntr=0.3,0.1

Type RM Length L Ch R = 1 ,9441    ,492,492,492
BEGIN DESCRIPTION:
DUCK CREEK TRIB 24 3 17 0
END DESCRIPTION:
XS GIS Cut Line= 4
      3515266.32      10425601.3      3515022.16     10425557.89
      3514791.04     10425727.16      3514665.18     10426123.19
#Sta/Elev= 30
  4544.9  407.14    4591  405.23    4751  399.46  4824.3  394.97  4838.9  393.24
  4845.1  391.27  4853.6  390.64  4874.5     392  4880.7  394.39    4910  395.07
  4916.9  394.36  4924.6  392.44  4930.8  392.92  4939.3  391.42  4966.5   391.2
  4974.8  390.04    4981  390.84  4989.5  388.97  4995.7  389.06  5001.7   388.2
  5001.9   387.7  5005.7   388.2  5010.3  390.83  5016.5  391.06    5025  394.04
  5031.2  393.97  5039.6  395.83  5053.3  396.55  5283.4   402.5  5494.9  411.34
#Mann= 5 ,-1 , 0
  4544.9     .16       0    4591      .1       0    4751     .16       0
  5001.7     .07       0  5005.7     .16       0
Bank Sta=5001.7,5005.7
XS Rating Curve= 0 ,0
Exp/Cntr=0.3,0.1

Type RM Length L Ch R = 1 ,8949    ,456,456,456
BEGIN DESCRIPTION:
DUCK CREEK TRIB 24 3 16 0
END DESCRIPTION:
XS GIS Cut Line= 3
      3515162.09     10425340.88      3514556.67     10425341.97
      3514349.41     10425426.61
#Sta/Elev= 30
  4589.3   405.6  4669.3  400.33  4749.3  396.53  4849.3  393.29  4899.3  392.81
  4929.3  391.51  4939.3  390.33  4989.3   390.4  4997.3  386.76  4997.5  386.26
    5001  386.26  5001.3  386.76  5009.3   389.1  5019.3  390.31  5059.3  389.39
  5091.4  391.15  5109.3  391.31  5129.3  392.77  5159.3  398.41  5194.5  400.76
  5247.2  402.55  5259.5  402.97  5264.9   403.9  5275.3  403.23  5285.5  404.63
    5337  407.01  5350.9  406.43  5366.4  408.89  5404.9  411.67  5418.6  412.02
#Mann= 6 ,-1 , 0
  4589.3     .16       0  4997.3     .07       0  5001.3     .16       0
  5091.4     .05       0  5247.2      .1       0  5285.5     .05       0
Bank Sta=4997.3,5001.3
XS Rating Curve= 0 ,0
Exp/Cntr=0.3,0.1

Type RM Length L Ch R = 1 ,8493    ,448,448,448
BEGIN DESCRIPTION:
DUCK CREEK TRIB 24 3 15 0
END DESCRIPTION:
XS GIS Cut Line= 3
      3515233.75     10425211.75      3515087.27     10425107.59
      3514559.92      10424852.6
#Sta/Elev= 30
  4585.7  407.89  4680.3  403.13  4709.8  402.15  4715.9  402.46  4730.7   401.4
  4736.8   401.8    4840  396.32  4862.5  394.53  4885.1  389.59  4902.2  389.51
  4907.7  390.49  4924.8  388.02  4937.8  387.63  4975.5  388.97  4992.6  387.41
  4996.1  386.49  4996.4  385.99  4999.9  385.99  5000.1  386.49  5004.4   387.8
  5015.1  389.03  5043.3  389.28  5065.9  391.41  5116.6   392.7  5184.4  396.12
  5252.2   402.2  5269.2   401.8  5274.8  402.44    5337   402.9  5351.2  403.73
#Mann= 3 ,-1 , 0
  4585.7     .16       0  4996.1     .07       0  5000.1     .16       0
Bank Sta=4996.1,5000.1
XS Rating Curve= 0 ,0
Exp/Cntr=0.3,0.1

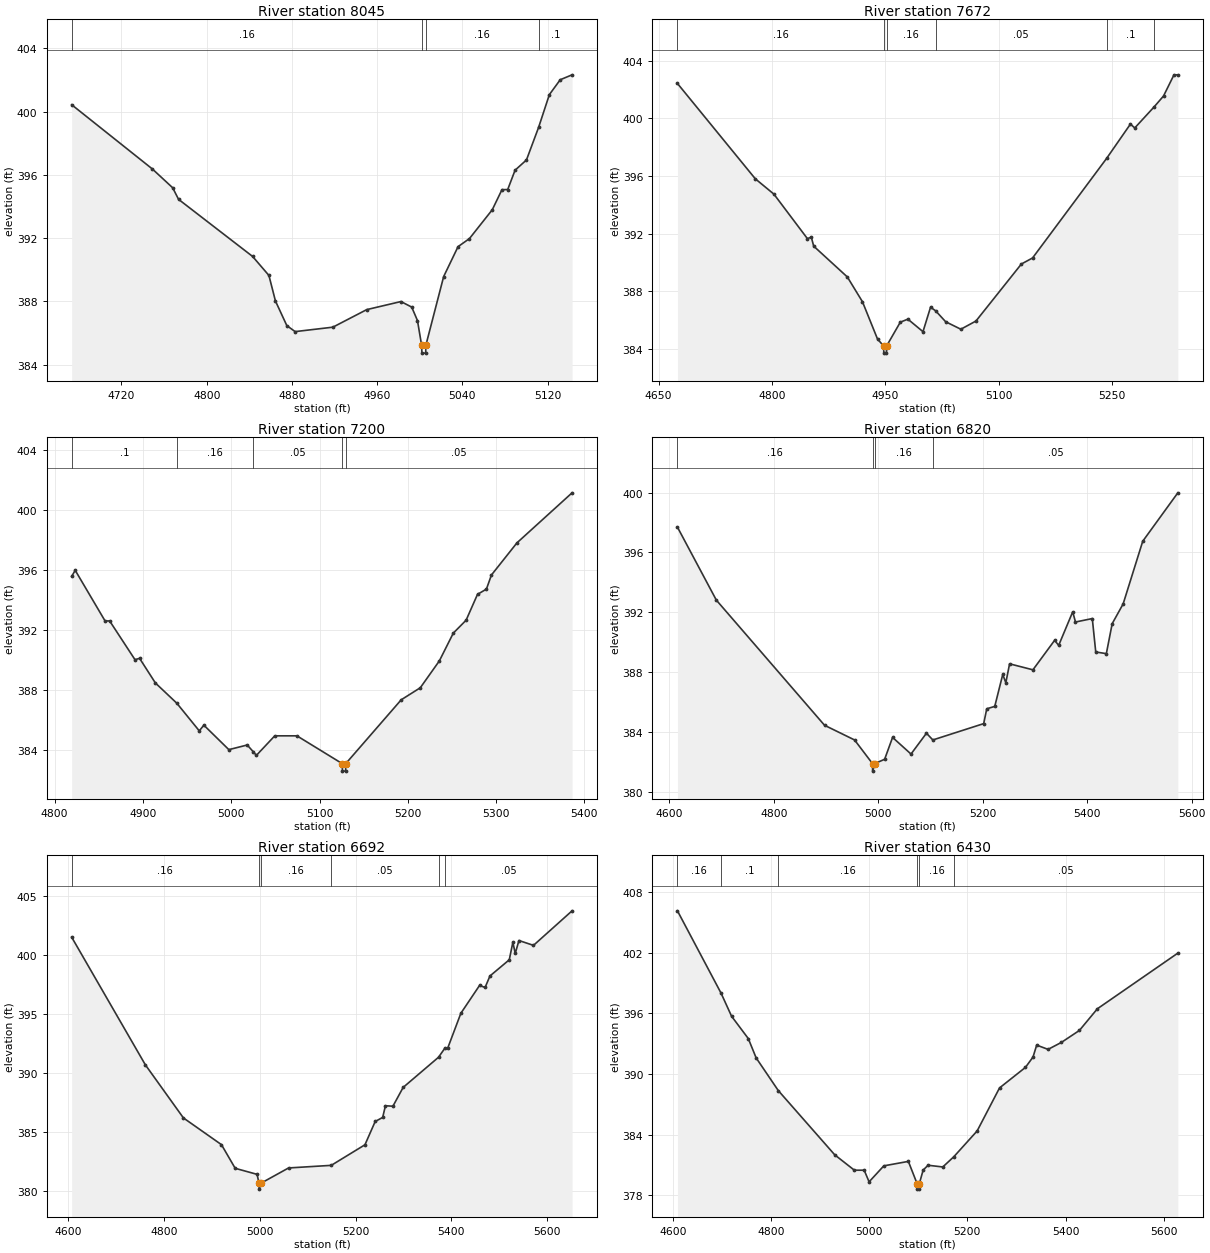
Type RM Length L Ch R = 1 ,8045    ,373,373,373
BEGIN DESCRIPTION:
DUCK CREEK TRIB 24 3 14 0
END DESCRIPTION:
XS GIS Cut Line= 2
      3515180.63     10424712.64      3514742.19     10424544.43
#Sta/Elev= 30
  4673.3  400.43    4749  396.37  4768.1  395.18  4773.6  394.45  4843.1  390.84
  4858.4  389.64  4864.5  388.03  4875.2  386.47    4883  386.09  4918.4  386.37
  4950.2  387.48  4982.3  387.99  4992.4  387.64  4997.8  386.79  5001.7  385.23
    5002  384.73  5005.5  384.73  5005.7  385.23  5022.4  389.57  5035.9  391.46
  5046.6  391.97    5068  393.79  5077.1  395.06  5082.5  395.07  5089.4  396.29
  5100.1  396.94  5111.5     399  5121.6  401.07  5131.8  402.01  5142.9  402.32
#Mann= 4 ,-1 , 0
  4673.3     .16       0  5001.7     .07       0  5005.7     .16       0
  5111.5      .1       0
Bank Sta=5001.7,5005.7
XS Rating Curve= 0 ,0
Exp/Cntr=0.3,0.1

Type RM Length L Ch R = 1 ,7672    ,472,472,472
BEGIN DESCRIPTION:
DUCK CREEK TRIB 24 3 13 0
END DESCRIPTION:
XS GIS Cut Line= 4
      3515272.77     10424220.01      3515095.95     10424257.98
      3514807.32     10424273.17      3514638.07      10424364.3
#Sta/Elev= 30
  4674.9  402.43  4777.9  395.81  4802.6  394.74  4846.9  391.65    4852  391.76
  4855.2  391.13  4899.7  388.99  4919.7  387.27  4939.7  384.67  4947.7   384.2
    4948   383.7  4951.5   383.7  4951.7   384.2  4969.8  385.85  4979.8  386.06
  4999.8  385.19  5009.8  386.89  5016.5  386.64  5029.8  385.88  5049.9  385.36
  5069.9  385.93    5130  389.89  5144.8  390.31  5242.7  397.22  5274.3  399.61
    5280  399.34  5305.4  400.79  5318.1  401.56  5331.9  403.03    5337  403.03
#Mann= 6 ,-1 , 0
  4674.9     .16       0  4947.7     .07       0  4951.7     .16       0
  5016.5     .05       0  5242.7      .1       0  5305.4     .05       0
Bank Sta=4947.7,4951.7
XS Rating Curve= 0 ,0
Exp/Cntr=0.3,0.1

Type RM Length L Ch R = 1 ,7200    ,380,380,380
BEGIN DESCRIPTION:
DUCK CREEK TRIB 24 3 10 1
END DESCRIPTION:
XS GIS Cut Line= 3
       3515113.3     10423776.21      3514873.51     10423844.57
       3514597.9     10424001.91
#Sta/Elev= 30
  4819.3  395.57  4823.3  395.97  4857.1   392.6  4862.3   392.6    4891  390.02
  4896.2  390.11  4914.1  388.47  4938.4  387.12  4963.8  385.28    4969  385.66
  4997.3  384.03  5018.1  384.34  5025.1  383.88  5028.5  383.65  5049.3  384.95
  5074.4  384.95  5125.7   383.1    5126   382.6  5129.5   382.6  5129.7   383.1
  5192.5  387.35  5214.1  388.15  5235.7  389.94  5251.5  391.79    5266  392.65
  5278.9  394.37    5289  394.72  5294.7  395.66  5323.6   397.8    5386  401.13
#Mann= 5 ,-1 , 0
  4819.3      .1       0  4938.4     .16       0  5025.1     .05       0
  5125.7     .07       0  5129.7     .05       0
Bank Sta=5125.7,5129.7
XS Rating Curve= 0 ,0
Exp/Cntr=0.3,0.1

Type RM Length L Ch R = 1 ,6820    ,128,128,128
BEGIN DESCRIPTION:
DUCK CREEK TRIB 24 3 12 0
END DESCRIPTION:
XS GIS Cut Line= 5
      3515255.49     10423368.22      3515029.76     10423407.29
      3514864.83     10423512.54      3514706.41     10423765.36
      3514482.32     10423836.81
#Sta/Elev= 30
  4615.3  397.69  4689.8  392.82    4897  384.47  4954.5  383.49  4988.9  381.91
  4989.1  381.41  4992.9  381.91  5012.1   382.2  5027.3  383.66  5062.6  382.55
  5092.2  383.94  5104.4  383.49  5201.8  384.58  5207.7  385.57    5223  385.73
  5238.3  387.86  5244.2  387.31  5251.4  388.57  5296.1  388.17  5337.7  390.14
  5345.4   389.8  5372.3  392.04  5377.6  391.36  5409.8  391.59  5416.4  389.36
  5436.7  389.25  5447.9  391.25  5468.9  392.57  5506.4  396.75  5573.6  399.98
#Mann= 4 ,-1 , 0
  4615.3     .16       0  4988.9     .07       0  4992.9     .16       0
  5104.4     .05       0
Bank Sta=4988.9,4992.9
XS Rating Curve= 0 ,0
Exp/Cntr=0.3,0.1

Type RM Length L Ch R = 1 ,6692    ,262,262,262
BEGIN DESCRIPTION:
DUCK CREEK TRIB 24 3 9 1
END DESCRIPTION:
XS GIS Cut Line= 4
      3515271.69     10423265.15       3514845.3     10423381.24
      3514669.52     10423676.38      3514412.34     10423714.36
#Sta/Elev= 30
    4607  401.49  4760.9   390.7  4840.4  386.21  4919.9  383.95  4948.6  381.95
  4994.3  381.44  4998.4  380.69  4998.7  380.19  5002.4  380.69  5060.1  381.98
  5149.3   382.2  5219.7  383.94  5241.1  385.91  5256.7  386.25  5262.5  387.24
  5278.1   387.2  5299.5  388.79  5373.4  391.34  5386.2  392.08  5392.4  392.09
  5420.1  395.06  5459.1  397.41  5470.7  397.24  5480.8  398.21  5521.2  399.58
  5528.7  401.06  5533.7  400.12  5541.4  401.21  5571.8   400.8  5652.4  403.72
#Mann= 6 ,-1 , 0
    4607     .16       0  4998.4     .07       0  5002.4     .16       0
  5149.3     .05       0  5373.4     .16       0  5386.2     .05       0
Bank Sta=4998.4,5002.4
XS Rating Curve= 0 ,0
Exp/Cntr=0.3,0.1

Type RM Length L Ch R = 1 ,6430    ,241,241,241
BEGIN DESCRIPTION:
DUCK CREEK TRIB 24 3 6 0
END DESCRIPTION:
XS GIS Cut Line= 3
      3515292.34     10423102.38      3514635.88     10423121.91
      3514327.71     10423312.89
#Sta/Elev= 30
  4609.4  406.12  4698.3  397.98  4719.7   395.7  4753.7   393.5  4769.7  391.59
  4814.8  388.36  4929.8  382.01  4969.8  380.49  4989.8  380.49  4999.8  379.34
  5029.8  380.92  5079.8  381.36  5097.9  379.12  5098.1  378.62  5101.6  378.62
  5101.9  379.12  5109.9   380.5  5119.9  380.98  5149.9  380.81  5172.4  381.82
  5219.9  384.37  5265.5  388.62  5318.3  390.65  5333.7  391.67  5341.2  392.85
  5364.4  392.43  5391.6  393.12  5428.2   394.3  5464.8  396.44  5628.7  401.94
#Mann= 6 ,-1 , 0
  4609.4     .16       0  4698.3      .1       0  4814.8     .16       0
  5097.9     .07       0  5101.9     .16       0  5172.4     .05       0
Bank Sta=5097.9,5101.9
XS Rating Curve= 0 ,0
Exp/Cntr=0.3,0.1

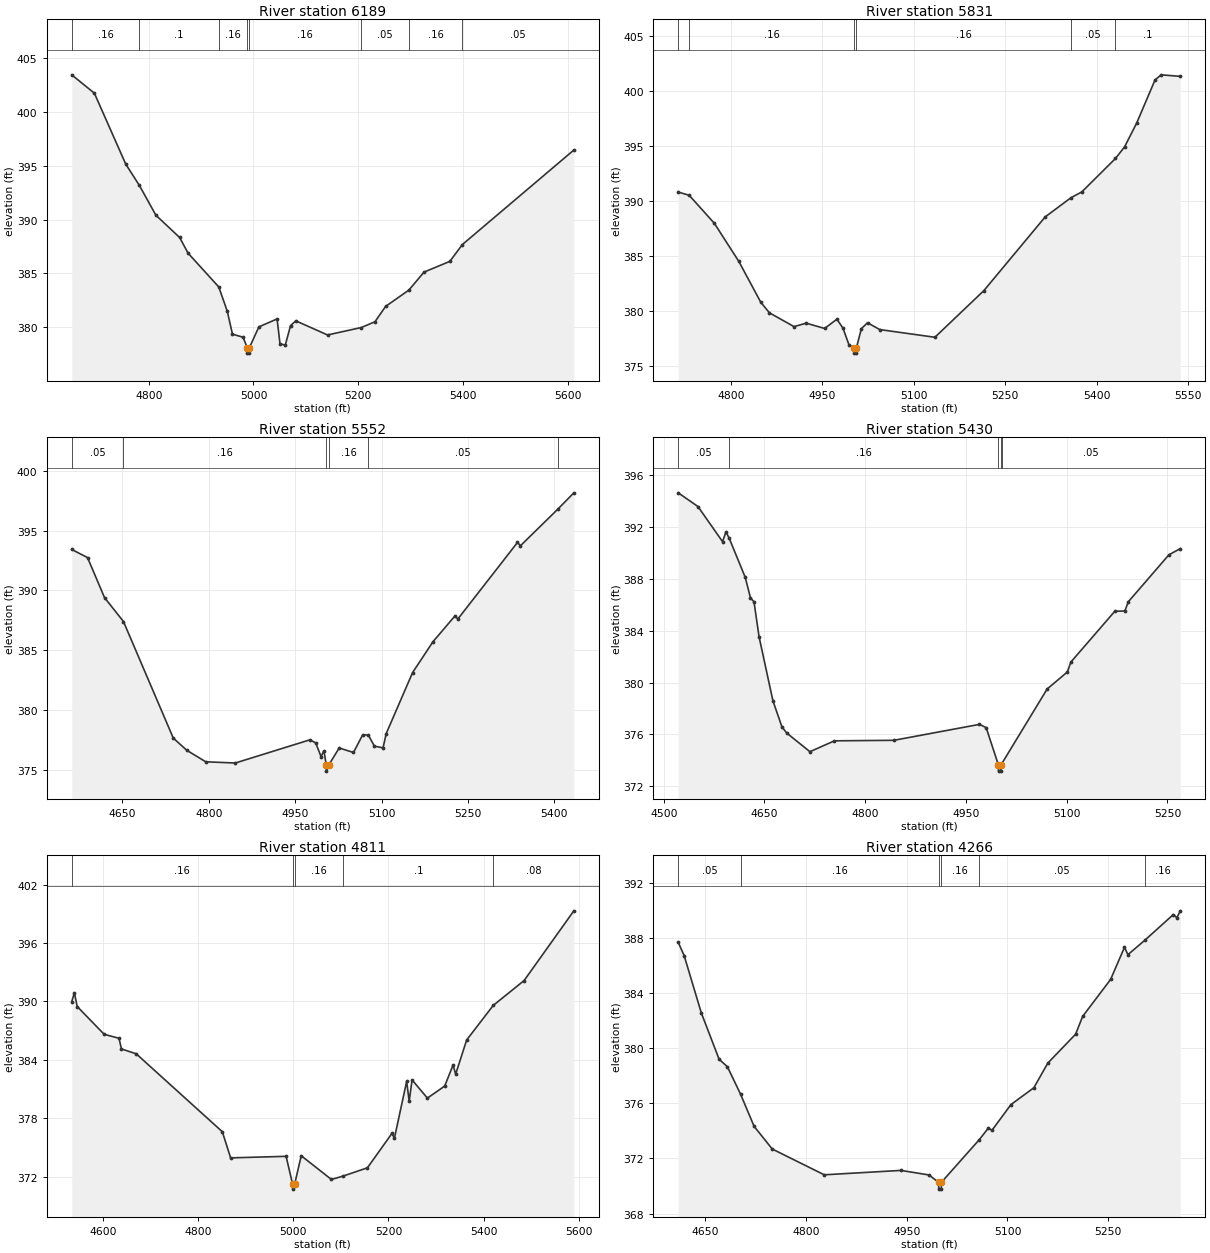
Type RM Length L Ch R = 1 ,6189    ,358,358,358
BEGIN DESCRIPTION:
DUCK CREEK TRIB 24 3 440
END DESCRIPTION:
XS GIS Cut Line= 4
      3515284.57     10422906.44      3515065.39      10422865.2
      3514642.21     10422919.46      3514407.81      10423121.3
#Sta/Elev= 30
  4652.9  403.46  4696.1  401.75    4756  395.16  4781.9  393.19  4813.6  390.41
  4858.9  388.34  4875.1  386.88  4933.7  383.74  4949.8   381.5  4959.9  379.35
  4980.1  379.07  4988.1  378.09  4988.4  377.59  4991.9  377.59  4992.1  378.09
  5010.3  380.03  5045.1  380.77  5050.6  378.47  5060.7  378.33  5070.8  380.15
  5080.9  380.59  5141.4  379.28    5206  379.97  5232.1  380.51  5252.3  381.93
  5296.8  383.45  5325.7  385.12  5375.1  386.12  5398.9  387.68  5611.9  396.47
#Mann= 8 ,-1 , 0
  4652.9     .16       0  4781.9      .1       0  4933.7     .16       0
  4988.1     .07       0  4992.1     .16       0    5206     .05       0
  5296.8     .16       0  5398.9     .05       0
Bank Sta=4988.1,4992.1
XS Rating Curve= 0 ,0
Exp/Cntr=0.3,0.1

Type RM Length L Ch R = 1 ,5831    ,279,279,279
BEGIN DESCRIPTION:
DUCK CREEK TRIB 24 3 7 1
END DESCRIPTION:
XS GIS Cut Line= 3
      3515061.02     10422574.41      3514483.79     10422626.49
      3514240.72     10422635.17
#Sta/Elev= 30
  4713.9  390.78  4731.8  390.49    4773  387.95  4813.2  384.48  4849.2  380.77
  4863.4  379.81  4903.6  378.56  4923.7  378.87  4953.8  378.39  4973.9  379.23
  4983.9  378.42  4993.9  376.87  5001.9  376.65  5002.2  376.15  5005.7  376.15
    5006  376.65    5014  378.37  5024.1  378.91  5044.1  378.29  5134.5  377.59
  5214.8  381.83  5315.2  388.52  5357.6  390.27  5375.2  390.79  5430.4  393.83
  5445.3  394.88  5465.3  397.06  5495.3  400.97  5505.3  401.43  5536.7  401.29
#Mann= 6 ,-1 , 0
  4713.9     .05       0  4731.8     .16       0  5001.9     .07       0
    5006     .16       0  5357.6     .05       0  5430.4      .1       0
Bank Sta=5001.9,5006
XS Rating Curve= 0 ,0
Exp/Cntr=0.3,0.1

Type RM Length L Ch R = 1 ,5552    ,122,122,122
BEGIN DESCRIPTION:
DUCK CREEK TRIB 24 3 9 0
END DESCRIPTION:
XS GIS Cut Line= 3
      3515097.95     10422431.18      3514492.47     10422311.82
      3514238.52     10422335.69
#Sta/Elev= 30
  4561.9  393.42  4589.3  392.74  4618.8  389.39  4651.7  387.39  4738.2  377.64
  4761.5  376.62  4794.7  375.65    4846  375.55  4975.6  377.49  4985.7  377.23
  4994.9  376.09    5000  376.57  5004.1  375.37  5004.3  374.87  5008.2  375.37
  5026.5  376.81  5051.3  376.43  5067.3  377.91    5077  377.89  5087.7  376.96
  5102.7  376.82  5108.1  378.01    5154  383.12  5189.4   385.7  5227.6  387.86
  5232.6   387.6  5336.2  394.01  5341.3  393.73  5405.8  396.77  5434.1  398.16
#Mann= 6 ,-1 , 0
  4561.9     .05       0  4651.7     .16       0  5004.1     .07       0
  5008.2     .16       0    5077     .05       0  5405.8     .16       0
Bank Sta=5004.1,5008.2
XS Rating Curve= 0 ,0
Exp/Cntr=0.3,0.1

Type RM Length L Ch R = 1 ,5430    ,619,619,619
BEGIN DESCRIPTION:
DUCK CREEK TRIB 24 3 6 1
END DESCRIPTION:
XS GIS Cut Line= 3
       3515109.1      10422332.8      3514735.84     10422241.66
      3514375.31     10422196.32
#Sta/Elev= 30
  4521.6  394.65    4551  393.59  4587.6  390.88  4592.7  391.64  4597.6  391.13
  4621.4  388.12  4629.2  386.53  4634.4  386.24    4642  383.52  4662.6  378.59
    4676  376.58  4683.2   376.1  4717.7  374.66  4754.2   375.5  4842.7  375.54
  4970.1  376.77  4980.1  376.52  4998.2  373.66  4998.5  373.16  5002.1  373.16
  5002.3  373.66  5003.4  373.74  5070.9   379.5  5101.1  380.82  5106.2  381.58
  5171.6   385.5  5186.6  385.53  5191.8  386.24  5252.3  389.87  5269.2  390.34
#Mann= 5 ,-1 , 0
  4521.6     .05       0  4597.6     .16       0  4998.2     .07       0
  5002.3     .16       0  5003.4     .05       0
Bank Sta=4998.2,5002.3
XS Rating Curve= 0 ,0
Exp/Cntr=0.3,0.1

Type RM Length L Ch R = 1 ,4811    ,545,545,545
BEGIN DESCRIPTION:
DUCK CREEK TRIB 24 3 7 0
END DESCRIPTION:
XS GIS Cut Line= 3
      3515217.29     10421990.63      3514522.85     10421747.58
      3514232.01     10421879.98
#Sta/Elev= 30
  4534.3  389.99  4539.8  390.89  4545.7  389.48  4602.5  386.62  4633.5  386.22
  4638.8  385.12  4669.8  384.62  4850.7  376.62  4868.2  373.93  4984.8  374.09
  4998.5  371.22  4998.8  370.72  5002.7  371.22  5016.6  374.15  5080.1  371.71
  5105.1  372.07  5155.7  372.91  5207.2  376.44  5212.5  375.96  5238.2  381.79
  5243.5  379.75  5249.6  381.94  5281.8  380.07  5318.2  381.31  5335.7  383.47
  5341.2  382.53  5364.3  386.04  5420.1  389.59  5485.1  392.15  5589.6  399.31
#Mann= 5 ,-1 , 0
  4534.3     .16       0  4998.5     .07       0  5002.7     .16       0
  5105.1      .1       0  5420.1     .08       0
Bank Sta=4998.5,5002.7
XS Rating Curve= 0 ,0
Exp/Cntr=0.3,0.1

Type RM Length L Ch R = 1 ,4266    ,471,471,471
BEGIN DESCRIPTION:
DUCK CREEK TRIB 24 3 6
END DESCRIPTION:
XS GIS Cut Line= 3
      3515080.56     10421526.22      3514590.13       10421383.
      3514362.27      10421448.1
#Sta/Elev= 30
  4609.6  387.69  4618.4  386.73  4644.1  382.55  4670.5   379.2  4682.8  378.66
  4702.4  376.67  4722.6  374.33  4749.7  372.68  4827.1  370.81  4941.4  371.13
    4983   370.8  4997.4  370.27  4997.7  369.77  5001.4  369.77  5001.7  370.27
    5058  373.36  5071.7  374.21  5076.9  374.04  5105.2  375.91  5139.3  377.13
  5160.1  378.92  5201.5  381.02  5212.1  382.32  5253.7     385  5274.3  387.33
  5279.5   386.8  5304.3  387.83  5347.1  389.71  5352.3  389.48  5357.5  389.98
#Mann= 6 ,-1 , 0
  4609.6     .05       0  4702.4     .16       0  4997.4     .07       0
  5001.7     .16       0    5058     .05       0  5304.3     .16       0
Bank Sta=4997.4,5001.7
XS Rating Curve= 0 ,0
Exp/Cntr=0.3,0.1

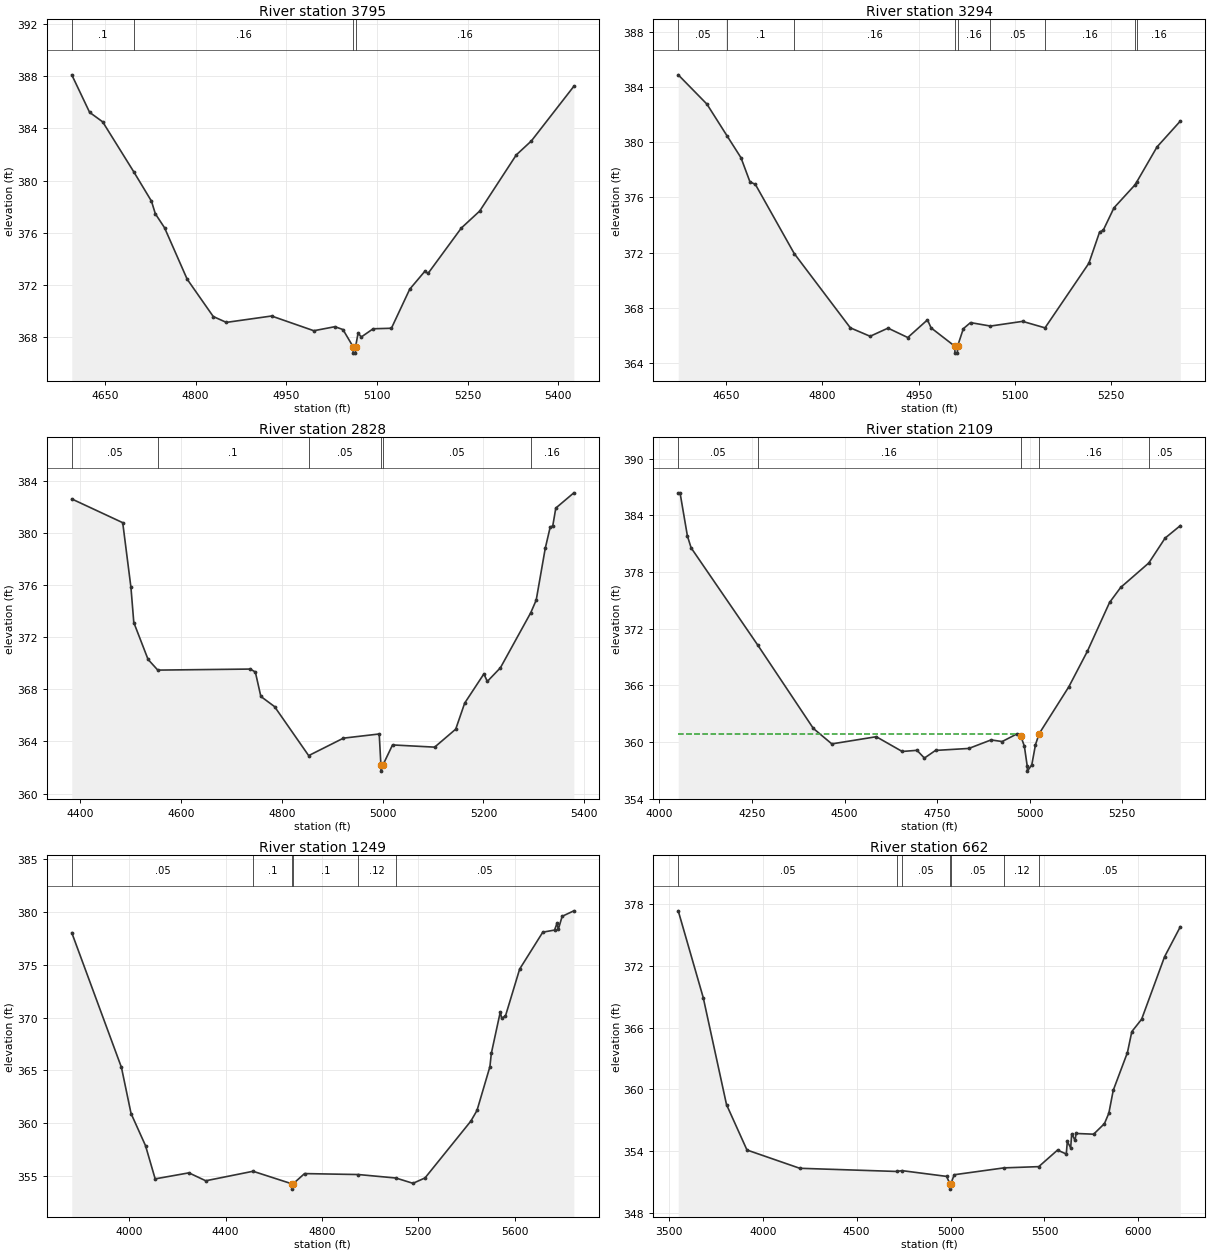
Type RM Length L Ch R = 1 ,3795    ,501,501,501
BEGIN DESCRIPTION:
DUCK CREEK TRIB 24 3 5 0
END DESCRIPTION:
XS GIS Cut Line= 3
      3515192.13     10421241.66      3514842.11     10421041.64
      3514442.15     10420891.66
#Sta/Elev= 30
  4595.2  388.12  4624.7  385.24  4646.3  384.51  4698.3  380.63    4727  378.42
  4733.4  377.45  4748.6  376.38    4786  372.43  4829.2  369.56  4850.8  369.11
  4925.6   369.6  4995.5  368.47  5030.4  368.78  5043.7  368.56  5060.3  367.25
  5060.6  366.75  5064.3  366.75  5064.6  367.25  5068.7  368.29    5074  367.99
  5093.6  368.62  5123.8  368.66  5154.1  371.66    5179  373.03  5184.4  372.87
  5239.5  376.36  5269.8  377.66  5330.3  381.97  5355.2  383.04  5425.5  387.24
#Mann= 4 ,-1 , 0
  4595.2      .1       0  4698.3     .16       0  5060.3     .07       0
  5064.6     .16       0
Bank Sta=5060.3,5064.6
XS Rating Curve= 0 ,0
Exp/Cntr=0.3,0.1

Type RM Length L Ch R = 1 ,3294    ,466,466,466
BEGIN DESCRIPTION:
DUCK CREEK TRIB 24 3 3 1
END DESCRIPTION:
XS GIS Cut Line= 3
      3515242.11     10421091.64      3515042.11     10420691.64
      3514742.13     10420541.65
#Sta/Elev= 30
  4575.2  384.87  4619.9  382.75  4651.3  380.45    4673  378.87    4687  377.12
  4695.4  376.94    4756  371.93  4843.5  366.55  4874.3  365.94  4902.2  366.53
    4933  365.85  4963.7  367.13  4969.3  366.55  5006.3  365.22  5006.5  364.72
  5010.3  364.72  5010.6  365.22  5019.6  366.49  5030.8  366.93  5061.9  366.68
  5111.9  367.02  5146.9  366.55  5215.3  371.23    5232  373.49  5237.6  373.61
  5254.4  375.24  5286.9  376.89  5289.6  377.09  5321.5  379.65  5357.8  381.52
#Mann= 9 ,-1 , 0
  4575.2     .05       0  4651.3      .1       0    4756     .16       0
  5006.3     .07       0  5010.6     .16       0  5061.9     .05       0
  5146.9     .16       0  5286.9     .05       0  5289.6     .16       0
Bank Sta=5006.3,5010.6
XS Rating Curve= 0 ,0
Exp/Cntr=0.3,0.1

Type RM Length L Ch R = 1 ,2828    ,719,719,719
BEGIN DESCRIPTION:
DUCK CREEK TRIB 24 3 2 1
END DESCRIPTION:
XS GIS Cut Line= 3
      3515614.39     10420745.62      3515456.39     10420445.24
      3514827.87     10420254.25
#Sta/Elev= 30
    4383   382.6  4484.1  380.78  4500.4  375.82  4506.1  373.12  4534.4  370.29
  4553.7  369.47  4737.3  369.55  4747.3  369.32  4758.2  367.45  4785.4  366.67
  4853.1  362.91  4922.1  364.25  4993.1  364.57  4996.4  362.22  4996.7  361.72
  5000.8  362.22  5019.5  363.73  5103.1  363.56  5144.9  364.94  5162.7  366.94
  5200.8  369.18  5207.6   368.6  5233.6  369.65  5293.9  373.88  5304.6  374.84
  5322.6  378.82  5332.3  380.43  5337.5  380.54  5343.5   381.9  5379.3  383.07
#Mann= 6 ,-1 , 0
    4383     .05       0  4553.7      .1       0  4853.1     .05       0
  4996.4     .03       0  5000.8     .05       0  5293.9     .16       0
Bank Sta=4996.4,5000.8
XS Rating Curve= 0 ,0
Exp/Cntr=0.3,0.1

Type RM Length L Ch R = 1 ,2109    ,860,860,860
BEGIN DESCRIPTION:
DUCK CREEK TRIB 24 3 4 0
END DESCRIPTION:
XS GIS Cut Line= 2
      3516136.92     10419670.93      3514781.05     10419679.61
#Sta/Elev= 30
  4050.7  386.38  4055.6  386.38  4075.5  381.81  4085.5  380.56  4265.5  370.27
  4415.5  361.46  4465.5  359.82  4585.5  360.58  4655.5  359.02  4695.5  359.14
  4715.5  358.32  4745.5  359.13  4835.5  359.34  4895.5  360.24  4925.5  360.07
  4965.5  360.88  4975.5  360.68  4985.5  359.57  4993.3  357.44  4993.6  356.94
  5005.5   357.6  5015.5  359.74  5025.5  360.91  5105.5  365.86  5155.5  369.61
  5215.5  374.78  5245.5  376.37  5321.5  378.96  5365.5  381.59  5406.6  382.91
#Mann= 5 ,-1 , 0
  4050.7     .05       0  4265.5     .16       0  4975.5     .12       0
  5025.5     .16       0  5321.5     .05       0
#XS Ineff= 2 , 0
       0 4966.36  360.91               0
Permanent Ineff=
       T       F
Bank Sta=4975.5,5025.5
XS Rating Curve= 0 ,0
Exp/Cntr=0.3,0.1

Type RM Length L Ch R = 1 ,1249    ,587,587,587
BEGIN DESCRIPTION:
DUCK CREEK TRIB 24 3 11 0
END DESCRIPTION:
XS GIS Cut Line= 3
      3516168.16     10418934.82       3514485.9     10418924.41
       3514284.5     10419271.64
#Sta/Elev= 30
  3761.7  378.03  3967.8  365.29  4007.8  360.92  4067.8  357.88  4107.8  354.74
  4247.8  355.31  4317.8  354.56    4514  355.46  4675.5  354.27  4675.8  353.77
    4680  354.27  4727.8  355.24  4951.3  355.15  5107.2  354.82  5177.8  354.32
  5227.8  354.83  5417.8   360.2  5443.4  361.21  5497.1  365.36  5502.9  366.61
  5540.2  370.54  5545.9  369.94  5561.7  370.16  5620.5  374.59  5716.5  378.08
  5765.4  378.28  5775.3  378.91  5781.1  378.36  5796.9  379.58  5845.4   380.1
#Mann= 6 ,-1 , 0
  3761.7     .05       0    4514      .1       0  4675.5     .07       0
    4680      .1       0  4951.3     .12       0  5107.2     .05       0
Bank Sta=4675.5,4680
XS Rating Curve= 0 ,0
Exp/Cntr=0.3,0.1

Type RM Length L Ch R = 1 ,662     ,0,0,0
BEGIN DESCRIPTION:
DUCK CREEK TRIB 24 3 1 0
END DESCRIPTION:
XS GIS Cut Line= 4
      3516183.79     10418915.71      3515320.97     10418358.43
      3514454.65     10418466.07       3514143.9     10419174.38
#Sta/Elev= 30
  3549.8  377.38  3682.9  368.93  3806.9  358.51  3915.8  354.09  4196.9  352.31
  4713.4     352  4741.5  352.08  4978.9  351.52  4996.8  350.78  4997.1  350.28
  5001.3  350.78  5019.2  351.68  5284.7  352.35  5469.6  352.47  5569.5  354.08
  5616.2   353.7  5621.7  354.92  5639.6   354.3    5645  355.67  5662.9  355.03
  5668.4   355.7  5761.8  355.63  5819.5  356.66  5842.9  357.68  5866.2   359.9
  5941.8  363.58  5965.2  365.62  6017.3  366.82  6139.6  372.91  6223.4  375.83
#Mann= 7 ,-1 , 0
  3549.8     .05       0  4713.4      .1       0  4741.5     .05       0
  4996.8     .03       0  5001.3     .05       0  5284.7     .12       0
  5469.6     .05       0
Bank Sta=4996.8,5001.3
XS Rating Curve= 0 ,0
Exp/Cntr=0.3,0.1

Chan Stop Cuts=-1
Use User Specified Reach Order=0
Composite Channel Slope=5