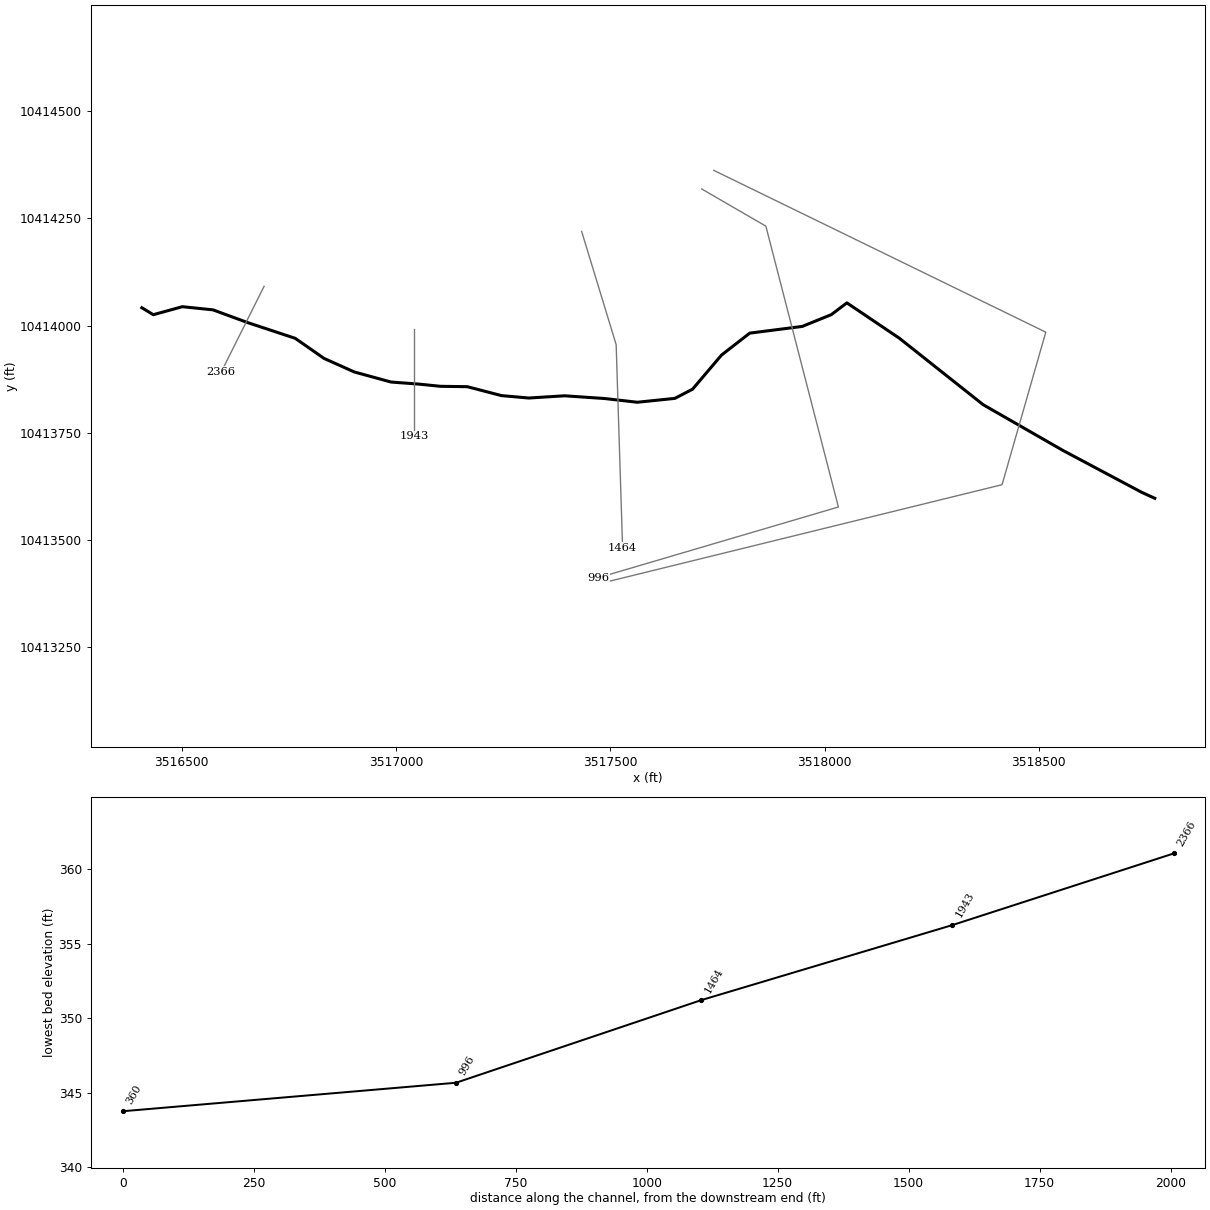
--- DUCK CREEK TRIB 25 1.prj (project) ---

Proj Title=DUCK CREEK TRIB 25 1 Base Level Engineering
Current Plan=p01
Default Exp/Contr=0.3,0.1
English Units
Geom File=g01
Flow File=f01
Plan File=p01
BEGIN DESCRIPTION:
DUCK CREEK TRIB 25 1
END DESCRIPTION:

--- DUCK CREEK TRIB 25 1.p01 (plan) ---

Plan Title=Multiple Run
Short Identifier=Multiple
Geom File=g01
Flow File=f01
Subcritical Flow
K Sum by GR= 0
Std Step Tol= 0.01
Critical Tol= 0.01
Num of Std Step Trials= 20
Max Error Tol= 0.3
Flow Tol Ratio= 0.001
Split Flow NTrial= 30
Split Flow Tol= 0.02
Split Flow Ratio= 0.02
Log Output Level= 0
Friction Slope Method= 1
Unsteady Friction Slope Method= 2
Unsteady Bridges Friction Slope Method= 1
Parabolic Critical Depth
Global Vel Dist=  1 , 1 , 1
Global Log Level= 0
CheckData=True
Encroach Param= -1, 0, 0, 0
BEGIN DESCRIPTION:
Multiple Run
END DESCRIPTION:

--- DUCK CREEK TRIB 25 1.f01 (steady flow) ---

Flow Title=Multiple
Number of Profiles=7
Profile Names=10-year,25-year,50-year,1pct_min,100-year,1pct_plu,500-year
River Rch & RM= DUCK CREEK TRIB ,Reach-1,2366
     309     398     466     401     542     733     728
Boundary for River Rch & Prof#=DUCK CREEK TRIB ,Reach-1,1
Up Type=0
Dn Type=3
Dn Slope=0.005
Boundary for River Rch & Prof#=DUCK CREEK TRIB ,Reach-1,2
Up Type=0
Dn Type=3
Dn Slope=0.005
Boundary for River Rch & Prof#=DUCK CREEK TRIB ,Reach-1,3
Up Type=0
Dn Type=3
Dn Slope=0.005
Boundary for River Rch & Prof#=DUCK CREEK TRIB ,Reach-1,4
Up Type=0
Dn Type=3
Dn Slope=0.005
Boundary for River Rch & Prof#=DUCK CREEK TRIB ,Reach-1,5
Up Type=0
Dn Type=3
Dn Slope=0.005
Boundary for River Rch & Prof#=DUCK CREEK TRIB ,Reach-1,6
Up Type=0
Dn Type=3
Dn Slope=0.005
Boundary for River Rch & Prof#=DUCK CREEK TRIB ,Reach-1,7
Up Type=0
Dn Type=3
Dn Slope=0.005

--- DUCK CREEK TRIB 25 1.g01 (geometry) ---

Geom Title=Existing Conditions

River Reach=DUCK CREEK TRIB ,Reach-1
Reach XY= 30
      3516406.77     10414041.64      3516433.57     10414025.35
      3516501.28     10414044.01      3516572.90     10414036.63
      3516653.19     10414007.12      3516764.74     10413970.22
      3516832.01     10413923.35      3516902.76     10413891.67
      3516988.26     10413868.23      3517052.50     10413863.45
      3517103.71     10413858.25      3517166.21     10413857.38
      3517246.07     10413836.54      3517309.88     10413830.90
      3517393.21     10413836.11      3517486.48     10413829.77
      3517563.01     10413821.04      3517650.68     10413830.09
      3517691.96     10413851.56      3517759.53     10413931.16
      3517825.34     10413982.33      3517947.90     10413998.00
      3517948.85     10413998.39      3518015.78     10414025.52
      3518052.05     10414052.95      3518174.69     10413970.33
      3518370.00     10413815.39      3518556.20     10413708.61
      3518739.80     10413610.96      3518770.51     10413596.95

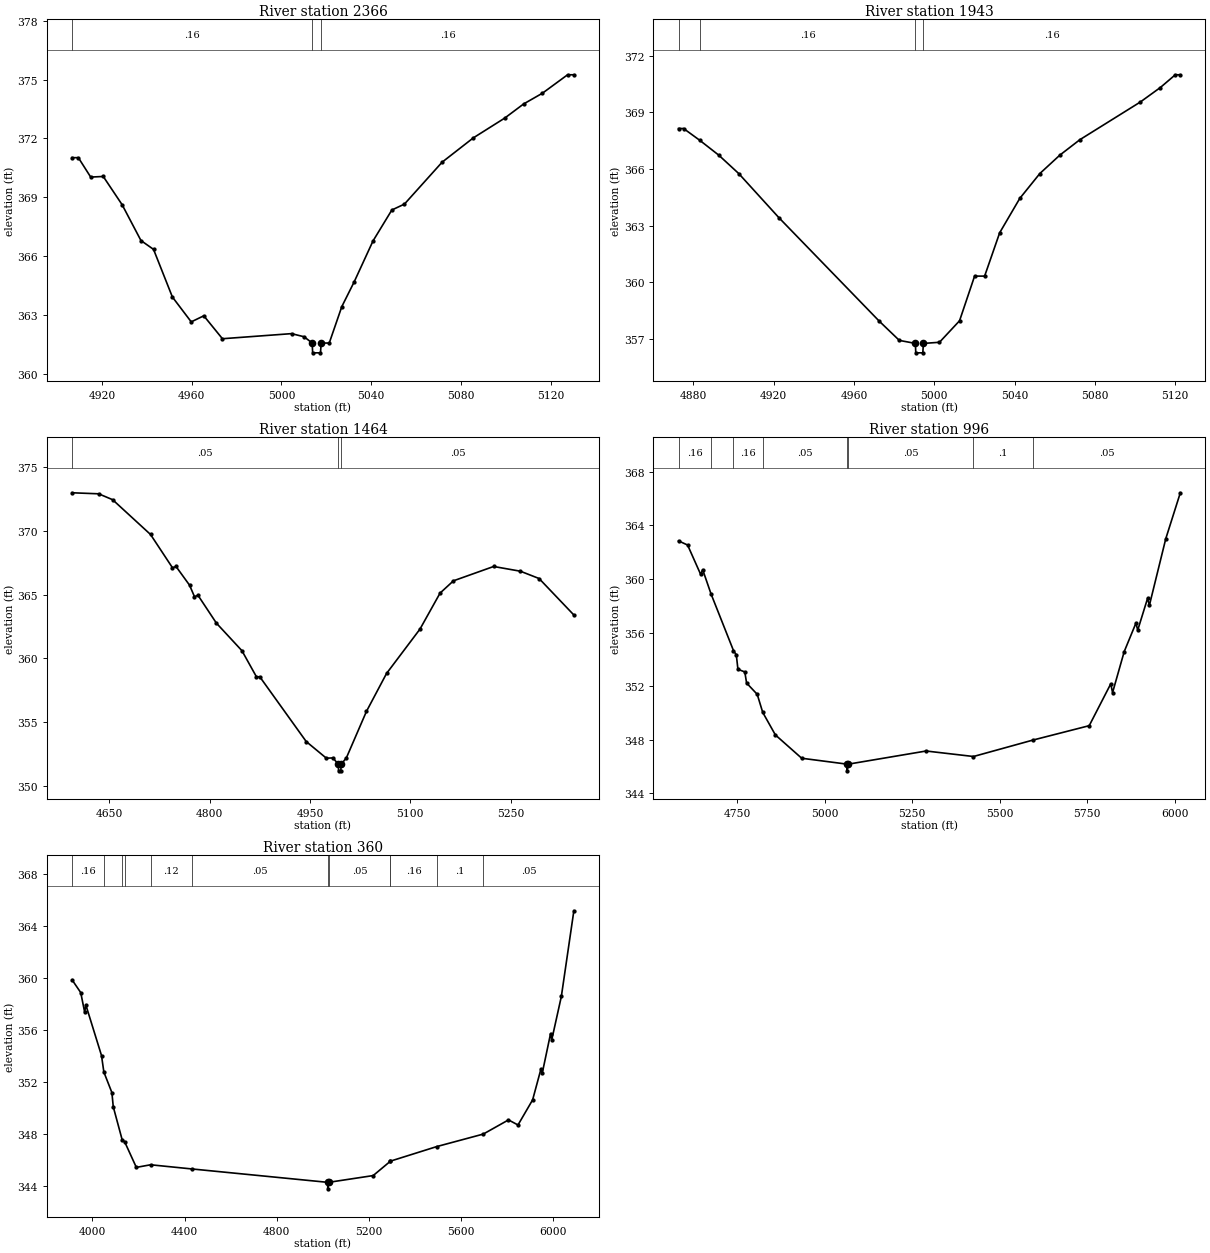
Type RM Length L Ch R = 1,2366,423,423,423
BEGIN DESCRIPTION:
DUCK CREEK TRIB 25 1 16 1
END DESCRIPTION:
XS GIS Cut Line= 3
      3516692.09     10414091.61      3516642.11     10413991.64
      3516592.09     10413891.61
#Sta/Elev= 30
  4906.7  371.02  4909.5  371.02  4915.0  370.03  4920.6  370.06  4929.0  368.62
  4937.4  366.79  4943.0  366.34  4951.4  363.91  4959.8  362.64  4965.4  362.95
  4973.7  361.78  5004.5  362.04  5010.1  361.88  5013.7  361.56  5013.9  361.06
  5017.4  361.06  5017.7  361.56  5021.3  361.56  5026.9  363.42  5032.4  364.68
  5040.8  366.77  5049.2  368.35  5054.8  368.65  5071.6  370.79  5085.5  372.03
  5099.5  373.04  5107.9  373.76  5116.3  374.31  5127.5  375.25  5130.3  375.25
#Mann=3,-1,0
  4906.7    0.16       0  5013.7    0.07       0  5017.7    0.16       0
Bank Sta=5013.7,5017.7
Exp/Cntr=0.3,0.1

Type RM Length L Ch R = 1,1943,479,479,479
BEGIN DESCRIPTION:
DUCK CREEK TRIB 25 1 15 0
END DESCRIPTION:
XS GIS Cut Line= 3
      3517042.11     10413991.63      3517042.11     10413841.64
      3517042.11     10413741.63
#Sta/Elev= 25
  4872.6  368.15  4875.1  368.15  4883.1  367.53  4892.6  366.74  4902.6  365.76
  4922.6  363.42  4972.6  357.93  4982.6  356.91  4990.6  356.75  4990.8  356.25
  4994.3  356.25  4994.6  356.75  5002.6  356.81  5012.6  357.95  5020.1  360.32
  5025.1  360.32  5032.6  362.62  5042.6  364.44  5052.6  365.76  5062.6  366.74
  5072.6  367.56  5102.6  369.55  5112.6  370.32  5120.1  371.00  5122.6  371.00
#Mann=4,-1,0
  4872.6    0.05       0  4883.1    0.16       0  4990.6    0.07       0
  4994.6    0.16       0
Bank Sta=4990.6,4994.6
Exp/Cntr=0.3,0.1

Type RM Length L Ch R = 1,1464,468,468,468
BEGIN DESCRIPTION:
DUCK CREEK TRIB 25 1 11
END DESCRIPTION:
XS GIS Cut Line= 3
      3517433.17     10414219.65      3517513.65     10413955.45
      3517528.66     10413481.78
#Sta/Elev= 30
  4594.5  372.95  4634.2  372.87  4655.1  372.41  4711.8  369.69  4744.6  367.09
  4749.9  367.19  4770.1  365.73  4777.5  364.83  4782.7  364.94  4810.3  362.76
  4848.4  360.61  4870.1  358.57  4875.1  358.57  4944.5  353.51  4974.6  352.21
  4984.6  352.23  4992.6  351.72  4992.8  351.22  4996.3  351.22  4996.6  351.72
  5004.6  352.24  5034.6  355.87  5064.6  358.83  5114.6  362.30  5144.6  365.11
  5164.6  366.07  5224.7  367.19  5264.7  366.82  5292.6  366.25  5344.6  363.40
#Mann=3,-1,0
  4594.5    0.05       0  4992.6    0.03       0  4996.6    0.05       0
Bank Sta=4992.6,4996.6
Exp/Cntr=0.3,0.1

Type RM Length L Ch R = 1,996,636,636,636
BEGIN DESCRIPTION:
DUCK CREEK TRIB 25 1 3 0
END DESCRIPTION:
XS GIS Cut Line= 4
      3517713.21     10414318.80      3517862.98     10414231.98
      3518032.25     10413576.60      3517472.34     10413411.67
#Sta/Elev= 30
  4582.1  362.84  4608.0  362.53  4645.3  360.34  4651.1  360.69  4675.0  358.88
  4739.0  354.66  4747.2  354.33  4751.8  353.26  4771.4  353.06  4776.6  352.23
  4806.9  351.39  4822.7  350.04  4858.8  348.36  4934.0  346.62  5063.4  346.18
  5063.7  345.68  5067.4  346.18  5289.5  347.16  5424.8  346.75  5593.8  347.97
  5755.5  349.05  5817.0  352.17  5822.2  351.52  5855.5  354.58  5888.9  356.70
  5894.1  356.18  5922.2  358.55  5927.4  358.03  5974.3  363.01  6015.8  366.43
#Mann=8,-1,0
  4582.1    0.16       0  4675.0    0.05       0  4739.0    0.16       0
  4822.7    0.05       0  5063.4    0.03       0  5067.4    0.05       0
  5424.8     0.1       0  5593.8    0.05       0
Bank Sta=5063.4,5067.4
Exp/Cntr=0.3,0.1

Type RM Length L Ch R = 1,360,0,0,0
BEGIN DESCRIPTION:
DUCK CREEK TRIB 25 1 1 0
END DESCRIPTION:
XS GIS Cut Line= 4
      3517741.47     10414362.18      3518516.19     10413984.59
      3518414.19     10413628.68      3517496.68     10413403.10
#Sta/Elev= 30
  3912.1  359.84  3949.7  358.86  3966.6  357.37  3972.2  357.89  4039.8  354.02
  4050.0  352.75  4084.9  351.17  4090.8  350.08  4129.3  347.55  4140.7  347.37
  4190.9  345.42  4252.8  345.62  4431.5  345.30  5021.1  344.27  5021.3  343.77
  5025.1  344.27  5218.4  344.79  5292.8  345.89  5293.3  345.90  5494.3  347.02
  5695.9  347.98  5805.4  349.07  5846.6  348.68  5910.1  350.61  5946.5  353.00
  5951.6  352.64  5988.0  355.71  5993.1  355.23  6034.7  358.56  6089.0  365.15
#Mann=12,-1,0
  3912.1    0.16       0  4050.0    0.05       0  4129.3    0.16       0
  4140.7    0.05       0  4252.8    0.12       0  4431.5    0.05       0
  5021.1    0.03       0  5025.1    0.05       0  5292.8     0.1       0
  5293.3    0.16       0  5494.3     0.1       0  5695.9    0.05       0
Bank Sta=5021.1,5025.1
Exp/Cntr=0.3,0.1

Chan Stop Cuts=-1