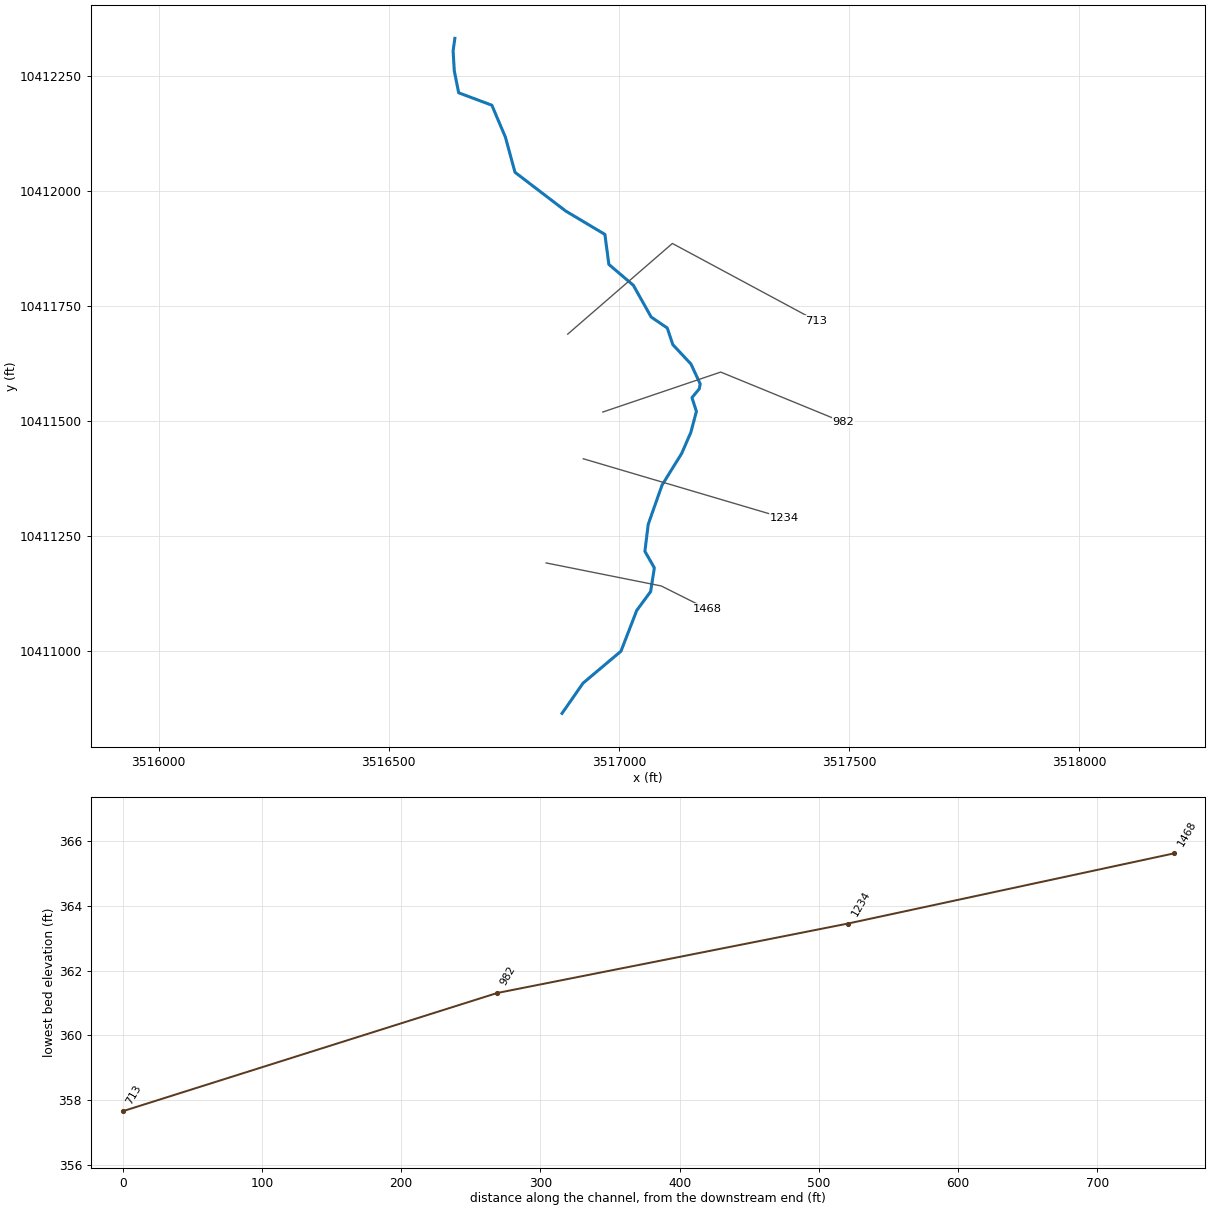
--- DUCK CREEK TRIB 25 2.prj (project) ---

Proj Title=DUCK CREEK TRIB 25 2 Base Level Engineering
Current Plan=p01
Default Exp/Contr=0.3,0.1
English Units
Geom File=g01
Flow File=f01
Plan File=p01
Y Axis Title=Elevation
X Axis Title(PF)=Main Channel Distance
X Axis Title(XS)=Station
BEGIN DESCRIPTION:
DUCK CREEK TRIB 25 2
END DESCRIPTION:
DSS Export Rating Curves= 0
DSS Export Rating Curve Sorted= 0
DSS Export Volume Flow Curves= 0
DXF OffsetX= 0
DXF OffsetY= 0
DXF ScaleX= 1
DXF ScaleY= 10

--- DUCK CREEK TRIB 25 2.p01 (plan) ---

Plan Title=Multiple Run
Short Identifier=Multiple
Geom File=g01
Flow File=f01
Subcritical Flow
K Sum by GR= 0
Std Step Tol= 0.01
Critical Tol= 0.01
Num of Std Step Trials= 20
Max Error Tol= 0.3
Flow Tol Ratio= 0.001
Split Flow NTrial= 30
Split Flow Tol= 0.02
Split Flow Ratio= 0.02
Log Output Level= 0
Friction Slope Method= 1
Unsteady Friction Slope Method= 2
Unsteady Bridges Friction Slope Method= 1
Parabolic Critical Depth
Global Vel Dist=  1 , 1 , 1
Global Log Level= 0
CheckData=True
Encroach Param= -1, 0, 0, 0
BEGIN DESCRIPTION:
Multiple Run
END DESCRIPTION:

--- DUCK CREEK TRIB 25 2.f01 (steady flow) ---

Flow Title=Multiple
Program Version=4.10
Number of Profiles= 7
Profile Names=10-year,25-year,50-year,1pct_min,100-year,1pct_plu,500-year
River Rch & RM=DUCK CREEK TRIB,Reach-1         ,1468
     432     575     691     609     823    1113    1163
Boundary for River Rch & Prof#=DUCK CREEK TRIB,Reach-1         , 1
Up Type= 0
Dn Type= 3
Dn Slope=0.0135
Boundary for River Rch & Prof#=DUCK CREEK TRIB,Reach-1         , 2
Up Type= 0
Dn Type= 3
Dn Slope=0.0135
Boundary for River Rch & Prof#=DUCK CREEK TRIB,Reach-1         , 3
Up Type= 0
Dn Type= 3
Dn Slope=0.0135
Boundary for River Rch & Prof#=DUCK CREEK TRIB,Reach-1         , 4
Up Type= 0
Dn Type= 3
Dn Slope=0.0135
Boundary for River Rch & Prof#=DUCK CREEK TRIB,Reach-1         , 5
Up Type= 0
Dn Type= 3
Dn Slope=0.0135
Boundary for River Rch & Prof#=DUCK CREEK TRIB,Reach-1         , 6
Up Type= 0
Dn Type= 3
Dn Slope=0.0135
Boundary for River Rch & Prof#=DUCK CREEK TRIB,Reach-1         , 7
Up Type= 0
Dn Type= 3
Dn Slope=0.0135
DSS Import GetInterval= 0
DSS Import GetPeak= 0
DSS Import FillOption= 0

--- DUCK CREEK TRIB 25 2.g01 (geometry) ---

Geom Title=Existing Conditions
Program Version=4.10

River Reach=DUCK CREEK TRIB ,Reach-1
Reach XY= 30
      3516876.61     10410864.71       3516922.3     10410930.43
      3517004.77     10410999.88      3517038.91      10411088.3
       3517069.2     10411129.49      3517077.24     10411181.06
      3517056.71     10411216.85      3517063.99     10411275.66
        3517094.     10411360.86      3517136.55     10411429.42
       3517156.5     10411475.17      3517168.69      10411520.9
      3517158.99     10411550.87      3517174.92     10411570.04
      3517176.82     10411580.83       3517156.8     10411623.97
      3517117.42     10411666.03      3517105.33     10411702.18
      3517070.32     10411726.07      3517031.57     10411795.12
      3516978.38     10411840.41      3516969.79      10411905.6
      3516884.67     10411956.39      3516774.43     10412040.59
      3516753.59     10412116.98      3516724.08     10412186.42
      3516652.03     10412213.33      3516642.48     10412261.07
       3516639.9      10412304.5      3516643.71     10412331.72

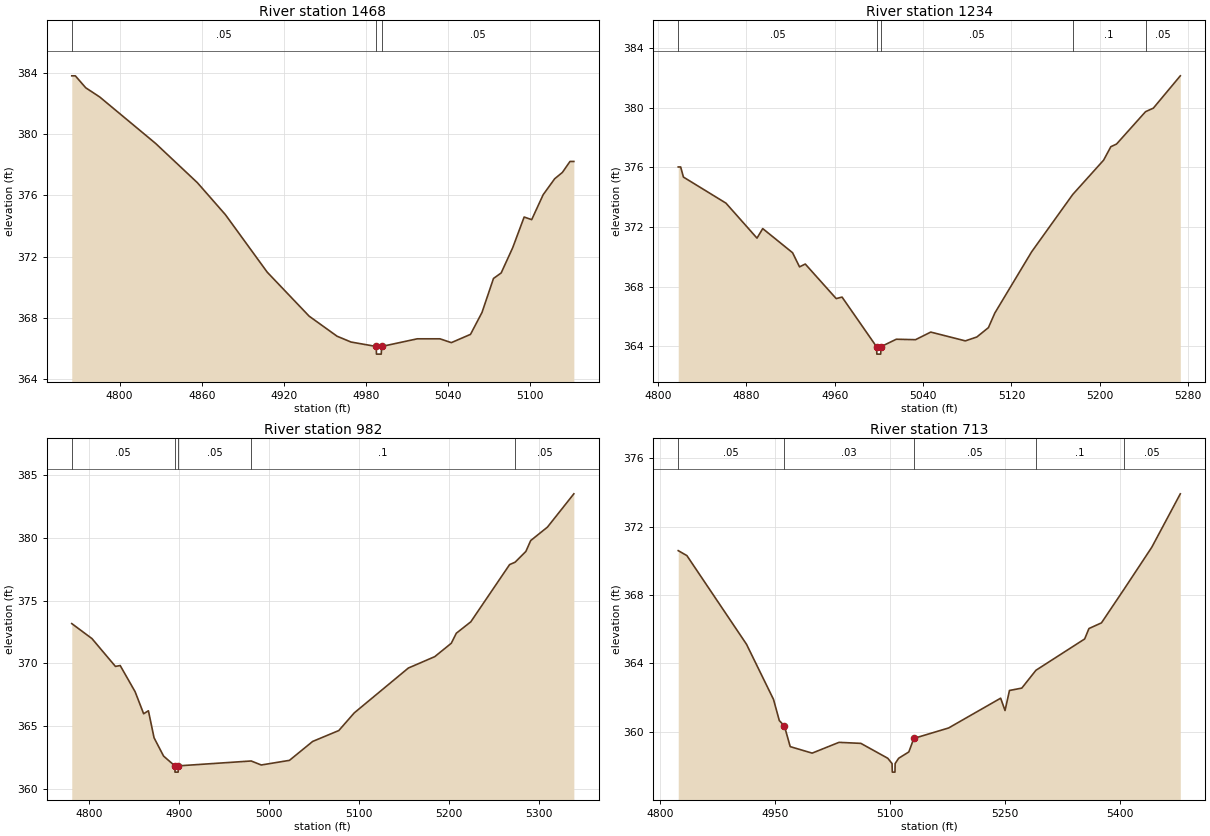
Type RM Length L Ch R = 1 ,1468    ,234,234,234
BEGIN DESCRIPTION:
DUCK CREEK TRIB 25 2 11
END DESCRIPTION:
XS GIS Cut Line= 3
      3516842.07     10411191.65      3517092.11     10411141.64
      3517192.12     10411091.64
#Sta/Elev= 30
    4765   383.8  4767.6   383.8  4775.2  383.02  4785.4  382.42  4826.2  379.39
  4856.8  376.82  4877.2  374.74  4907.8  370.98  4938.4  368.11  4958.8   366.8
    4969  366.42  4987.4  366.13  4987.6  365.63  4991.1  365.63  4991.4  366.13
  5017.4  366.63    5034  366.63  5042.3  366.38  5056.3  366.92  5064.7  368.35
  5073.1  370.57  5078.7  370.93  5087.1  372.57  5095.5  374.58    5101  374.41
  5109.4  376.04  5117.8  377.08  5123.4  377.49    5129  378.21  5131.8  378.21
#Mann= 3 ,-1 , 0
    4765     .05       0  4987.4     .03       0  4991.4     .05       0
Bank Sta=4987.4,4991.4
XS Rating Curve= 0 ,0
Exp/Cntr=0.3,0.1

Type RM Length L Ch R = 1 ,1234    ,252,252,252
BEGIN DESCRIPTION:
Mapping XS 857c0e8f
END DESCRIPTION:
XS GIS Cut Line= 2
      3516922.85     10411418.06       3517358.7      10411289.2
#Sta/Elev= 30
  4818.4  376.03  4820.6  376.03  4823.1  375.35  4861.6   373.6  4889.7  371.25
  4894.9  371.89  4921.9  370.27  4928.2  369.32  4933.4  369.51  4961.4  367.19
  4966.7  367.29  4997.9  363.96  4998.2  363.46  5001.7  363.46  5001.9  363.96
  5015.8  364.46  5033.2  364.43    5047  364.94  5078.3  364.35  5088.7  364.61
  5099.2  365.24    5105  366.22  5138.3  370.33  5175.5  374.18  5203.5  376.49
    5210  377.39  5215.2  377.57  5241.4  379.74  5248.5  379.98  5272.9  382.15
#Mann= 5 ,-1 , 0
  4818.4     .05       0  4997.9     .03       0  5001.9     .05       0
  5175.5      .1       0  5241.4     .05       0
Bank Sta=4997.9,5001.9
XS Rating Curve= 0 ,0
Exp/Cntr=0.3,0.1

Type RM Length L Ch R = 1 ,982     ,269,269,269
BEGIN DESCRIPTION:
DUCK CREEK TRIB 25 2 15 0
END DESCRIPTION:
XS GIS Cut Line= 3
      3516965.32     10411519.61      3517221.45     10411606.43
      3517488.28     10411497.11
#Sta/Elev= 30
  4780.5  373.17    4803  371.97  4829.1  369.75  4834.4  369.82    4851  367.73
  4860.5  365.97  4865.8  366.21  4872.1  364.05  4882.7  362.59  4895.2  361.81
  4895.4  361.31  4898.9  361.31  4899.2  361.81  4980.2   362.2  4991.4  361.88
  5022.8  362.25  5048.6  363.76  5077.7  364.63  5094.9  366.04  5155.1  369.62
  5184.5  370.53  5202.9   371.6  5208.5   372.4  5224.6  373.31  5267.8  377.88
  5273.9  378.07  5285.9  378.93  5291.3   379.8  5309.9  380.87  5339.3  383.53
#Mann= 5 ,-1 , 0
  4780.5     .05       0  4895.2     .07       0  4899.2     .05       0
  4980.2      .1       0  5273.9     .05       0
Bank Sta=4895.2,4899.2
XS Rating Curve= 0 ,0
Exp/Cntr=0.3,0.1

Type RM Length L Ch R = 1 ,713     ,0,0,0
BEGIN DESCRIPTION:
DUCK CREEK TRIB 25 2 3 0
END DESCRIPTION:
XS GIS Cut Line= 3
        3516889.     10411688.91      3517116.41     10411885.94
      3517428.41     10411718.28
#Sta/Elev= 30
  4823.7  370.59    4835   370.3  4912.8  365.12    4948   361.9  4955.6  360.66
  4962.2  360.35  4969.8  359.14  4998.4  358.76  5033.5  359.39    5062  359.33
  5097.1  358.46  5102.7  358.15    5103  357.65  5106.5  357.65  5106.7  358.15
  5111.3  358.46  5124.6  358.83  5131.1  359.62  5176.5  360.23  5244.4  361.97
  5250.1  361.25  5255.9  362.42    5272  362.56  5290.4   363.6    5354  365.43
  5359.6  366.04  5375.9  366.37  5405.6  368.35  5441.6  370.79  5478.8  373.91
#Mann= 5 ,-1 , 0
  4823.7     .05       0  4962.2     .03       0  5131.1     .05       0
  5290.4      .1       0  5405.6     .05       0
Bank Sta=4962.2,5131.1
XS Rating Curve= 0 ,0
Exp/Cntr=0.3,0.1

Chan Stop Cuts=-1
Use User Specified Reach Order=0
Composite Channel Slope=5