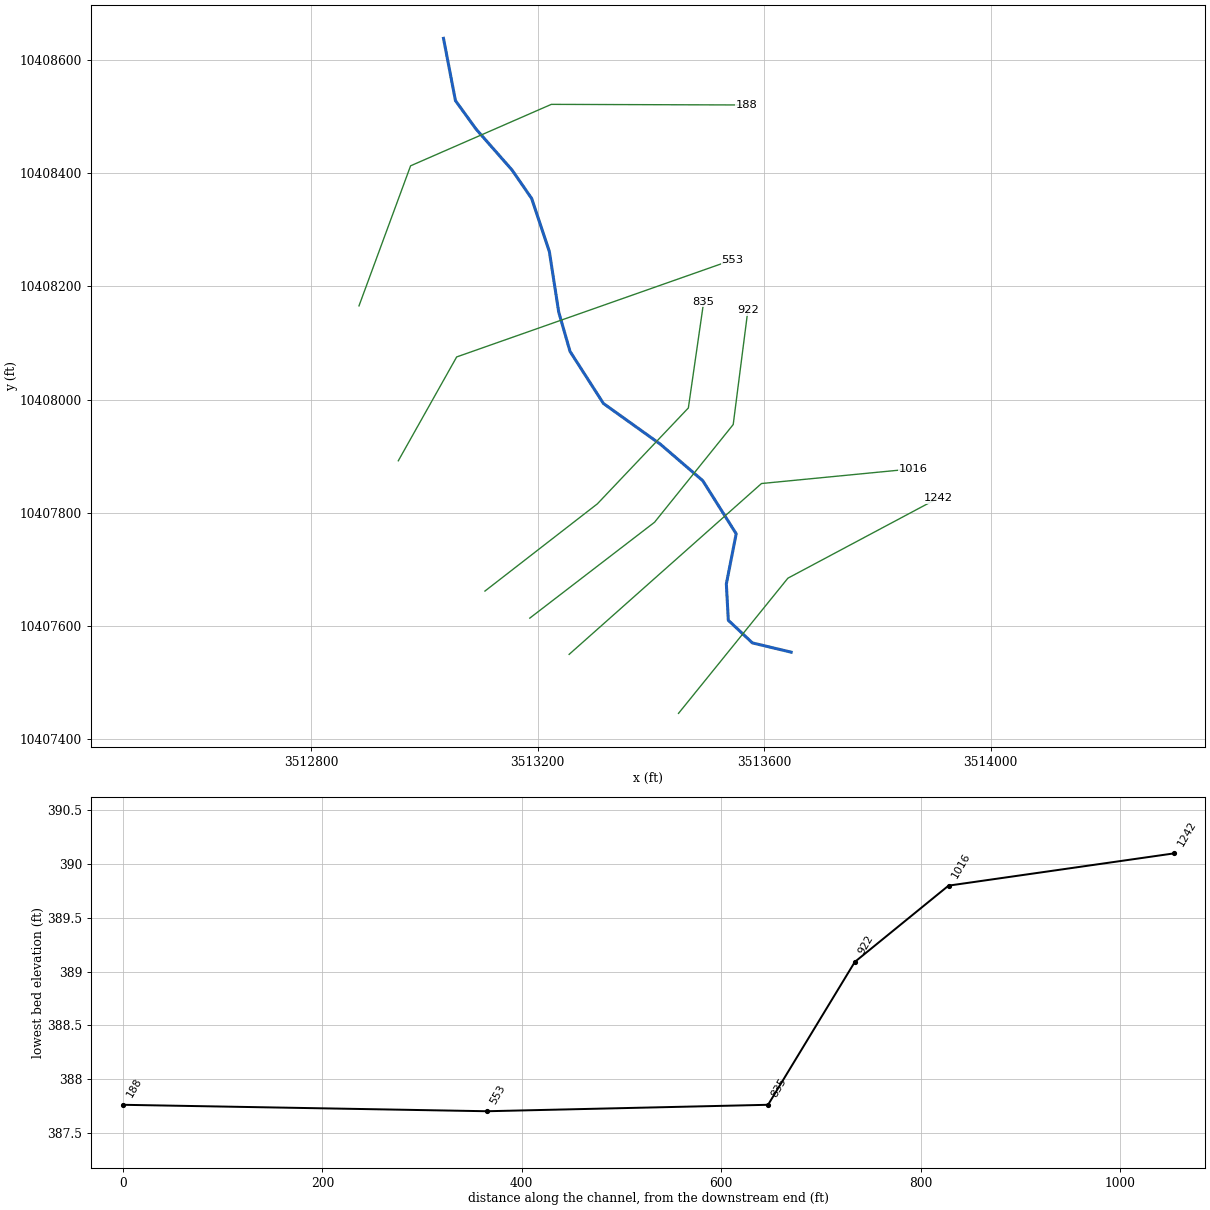
--- DUCK CREEK TRIB 25 3.prj (project) ---

Proj Title=DUCK CREEK TRIB 25 3 Base Level Engineering
Current Plan=p01
Default Exp/Contr=0.3,0.1
English Units
Geom File=g01
Flow File=f01
Plan File=p01
BEGIN DESCRIPTION:
DUCK CREEK TRIB 25 3
END DESCRIPTION:

--- DUCK CREEK TRIB 25 3.p01 (plan) ---

Plan Title=Multiple Run
Short Identifier=Multiple
Geom File=g01
Flow File=f01
Subcritical Flow
K Sum by GR= 0
Std Step Tol= 0.01
Critical Tol= 0.01
Num of Std Step Trials= 20
Max Error Tol= 0.3
Flow Tol Ratio= 0.001
Split Flow NTrial= 30
Split Flow Tol= 0.02
Split Flow Ratio= 0.02
Log Output Level= 0
Friction Slope Method= 1
Unsteady Friction Slope Method= 2
Unsteady Bridges Friction Slope Method= 1
Parabolic Critical Depth
Global Vel Dist=  1 , 1 , 1
Global Log Level= 0
CheckData=True
Encroach Param= -1, 0, 0, 0
BEGIN DESCRIPTION:
Multiple Run
END DESCRIPTION:

--- DUCK CREEK TRIB 25 3.f01 (steady flow) ---

Flow Title=Multiple
Number of Profiles=7
Profile Names=10-year,25-year,50-year,1pct_min,100-year,1pct_plu,500-year
River Rch & RM= DUCK CREEK TRIB ,Reach-1,1242
     558     748     902     796    1076    1455    1526
Boundary for River Rch & Prof#=DUCK CREEK TRIB ,Reach-1,1
Up Type=0
Dn Type=3
Dn Slope=0.005
Boundary for River Rch & Prof#=DUCK CREEK TRIB ,Reach-1,2
Up Type=0
Dn Type=3
Dn Slope=0.005
Boundary for River Rch & Prof#=DUCK CREEK TRIB ,Reach-1,3
Up Type=0
Dn Type=3
Dn Slope=0.005
Boundary for River Rch & Prof#=DUCK CREEK TRIB ,Reach-1,4
Up Type=0
Dn Type=3
Dn Slope=0.005
Boundary for River Rch & Prof#=DUCK CREEK TRIB ,Reach-1,5
Up Type=0
Dn Type=3
Dn Slope=0.005
Boundary for River Rch & Prof#=DUCK CREEK TRIB ,Reach-1,6
Up Type=0
Dn Type=3
Dn Slope=0.005
Boundary for River Rch & Prof#=DUCK CREEK TRIB ,Reach-1,7
Up Type=0
Dn Type=3
Dn Slope=0.005

--- DUCK CREEK TRIB 25 3.g01 (geometry) ---

Geom Title=Existing Conditions

River Reach=DUCK CREEK TRIB ,Reach-1
Reach XY= 16
      3513647.60     10407553.91      3513579.14     10407570.28
      3513536.61     10407610.21      3513533.13     10407674.44
      3513550.49     10407762.99      3513491.47     10407856.74
      3513416.81     10407920.97      3513316.12     10407993.02
      3513257.09     10408085.03      3513237.13     10408154.48
      3513220.63     10408261.25      3513189.38     10408355.00
      3513154.66     10408405.35      3513091.29     10408477.40
      3513054.83     10408527.74      3513033.69     10408637.78

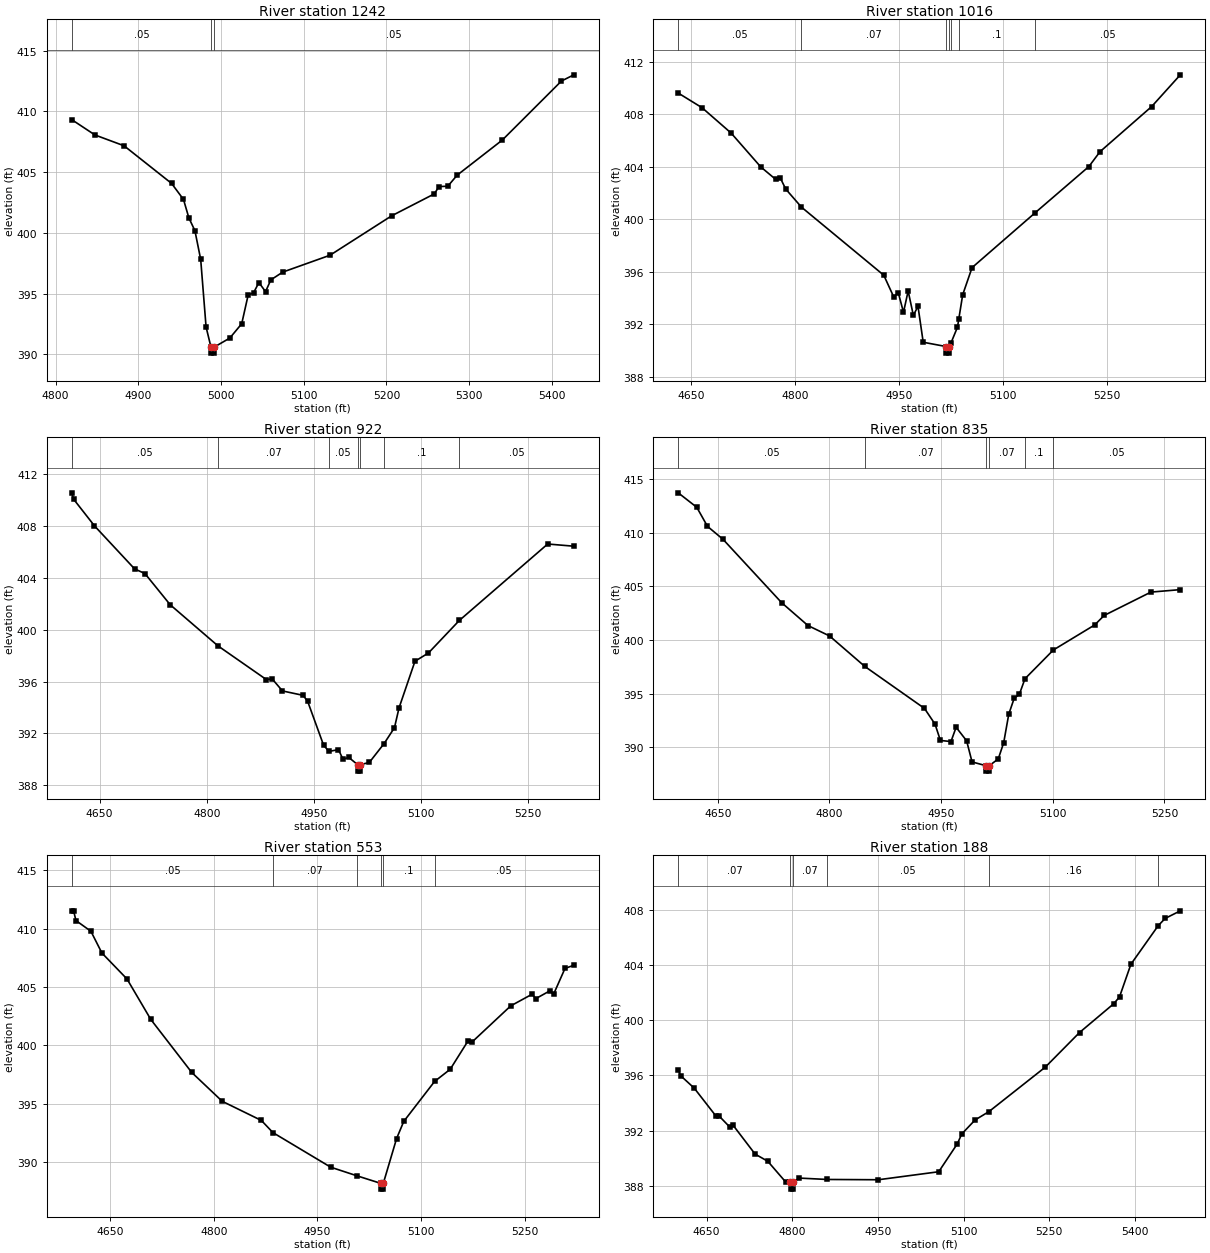
Type RM Length L Ch R = 1,1242,226,226,226
BEGIN DESCRIPTION:
DUCK CREEK TRIB 25 3 2 2
END DESCRIPTION:
XS GIS Cut Line= 3
      3513448.66     10407445.86      3513641.82     10407684.60
      3513906.59     10407825.67
#Sta/Elev= 30
  4819.5  409.32  4847.5  408.06  4882.7  407.17  4940.2  404.07  4954.6  402.75
  4961.1  401.23  4968.4  400.18  4975.4  397.81  4981.9  392.25  4987.8  390.60
  4988.1  390.10  4991.6  390.10  4991.8  390.60  5010.6  391.34  5025.0  392.52
  5032.7  394.86  5039.4  395.08  5045.8  395.91  5053.8  395.16  5060.2  396.13
  5074.6  396.77  5131.8  398.16  5206.2  401.40  5257.9  403.21  5263.5  403.81
  5274.2  403.84  5285.5  404.75  5340.1  407.64  5411.6  412.50  5426.6  413.01
#Mann=3,-1,0
  4819.5    0.05       0  4987.8    0.03       0  4991.8    0.05       0
Bank Sta=4987.8,4991.8
Exp/Cntr=0.3,0.1

Type RM Length L Ch R = 1,1016,94,94,94
BEGIN DESCRIPTION:
DUCK CREEK TRIB 25 3 41
END DESCRIPTION:
XS GIS Cut Line= 3
      3513255.55     10407550.06      3513595.16     10407851.70
      3513863.17     10407877.74
#Sta/Elev= 30
  4632.0  409.63  4666.4  408.51  4708.2  406.58  4750.9  404.00  4772.6  403.04
  4779.3  403.13  4786.9  402.31  4809.6  400.93  4928.2  395.74  4942.4  394.10
  4949.1  394.41  4956.6  392.91  4963.3  394.54  4970.8  392.68  4977.5  393.37
  4985.0  390.63  5018.2  390.30  5018.4  389.80  5021.9  389.80  5022.2  390.30
  5024.9  390.56  5034.4  391.78  5036.4  392.44  5041.9  394.25  5055.4  396.32
  5146.5  400.51  5223.8  404.03  5239.8  405.16  5314.2  408.60  5355.5  411.02
#Mann=7,-1,0
  4632.0    0.05       0  4809.6    0.07       0  5018.2    0.07       0
  5022.2    0.07       0  5024.9    0.05       0  5036.4     0.1       0
  5146.5    0.05       0
Bank Sta=5018.2,5022.2
Exp/Cntr=0.3,0.1

Type RM Length L Ch R = 1,922,87,87,87
BEGIN DESCRIPTION:
DUCK CREEK TRIB 25 3 40
END DESCRIPTION:
XS GIS Cut Line= 4
      3513186.09     10407614.07      3513406.36     10407783.34
      3513545.25     10407955.86      3513571.15     10408157.73
#Sta/Elev= 30
  4611.0  410.57  4613.7  410.07  4642.8  408.02  4698.9  404.70  4713.4  404.34
  4748.8  401.93  4815.6  398.76  4883.3  396.16  4891.5  396.21  4905.9  395.28
  4934.7  394.94  4941.1  394.49  4963.5  391.09  4971.0  390.61  4984.3  390.75
  4990.7  390.00  4998.7  390.15  5011.1  389.59  5011.3  389.09  5014.8  389.09
  5015.1  389.59  5027.5  389.76  5048.1  391.21  5062.7  392.44  5069.1  393.97
  5091.4  397.57  5110.3  398.21  5153.5  400.72  5277.2  406.62  5313.8  406.45
#Mann=7,-1,0
  4611.0    0.05       0  4815.6    0.07       0  4971.0    0.05       0
  5011.1    0.03       0  5015.1    0.05       0  5048.1     0.1       0
  5153.5    0.05       0
Bank Sta=5011.1,5015.1
Exp/Cntr=0.3,0.1

Type RM Length L Ch R = 1,835,282,282,282
BEGIN DESCRIPTION:
DUCK CREEK TRIB 25 3 1 3
END DESCRIPTION:
XS GIS Cut Line= 4
      3513106.91     10407661.84      3513305.45     10407815.89
      3513466.04     10407985.16      3513493.17     10408172.89
#Sta/Elev= 30
  4597.0  413.72  4621.9  412.37  4636.3  410.59  4657.2  409.38  4735.9  403.47
  4771.2  401.34  4800.2  400.37  4847.5  397.53  4927.7  393.61  4941.9  392.14
  4949.1  390.62  4963.3  390.52  4970.2  391.85  4984.3  390.59  4991.6  388.62
  5010.6  388.26  5010.9  387.76  5014.4  387.76  5014.6  388.26  5026.8  388.90
  5034.1  390.41  5040.9  393.07  5048.2  394.56  5055.1  394.92  5062.7  396.38
  5100.8  399.06  5156.4  401.40  5169.0  402.28  5231.8  404.46  5271.3  404.69
#Mann=6,-1,0
  4597.0    0.05       0  4847.5    0.07       0  5010.6    0.07       0
  5014.6    0.07       0  5062.7     0.1       0  5100.8    0.05       0
Bank Sta=5010.6,5014.6
Exp/Cntr=0.3,0.1

Type RM Length L Ch R = 1,553,365,365,365
BEGIN DESCRIPTION:
DUCK CREEK TRIB 25 3 2 1
END DESCRIPTION:
XS GIS Cut Line= 3
      3512953.91     10407891.88      3513056.97     10408075.22
      3513544.16     10408246.66
#Sta/Elev= 30
  4594.3  411.53  4597.0  411.53  4600.3  410.70  4622.0  409.78  4637.9  407.92
  4674.3  405.69  4708.7  402.23  4768.0  397.69  4812.1  395.22  4868.8  393.58
  4885.5  392.54  4969.1  389.58  5007.7  388.83  5041.3  388.20  5041.5  387.70
  5045.0  387.70  5045.3  388.20  5064.5  392.03  5074.9  393.50  5119.5  396.92
  5142.1  397.96  5167.8  400.38  5173.1  400.26  5229.7  403.39  5260.7  404.39
  5266.0  404.01  5286.4  404.68  5291.7  404.38  5308.3  406.60  5321.1  406.87
#Mann=6,-1,0
  4594.3    0.05       0  4885.5    0.07       0  5007.7     0.1       0
  5041.3    0.07       0  5045.3     0.1       0  5119.5    0.05       0
Bank Sta=5041.3,5045.3
Exp/Cntr=0.3,0.1

Type RM Length L Ch R = 1,188,0,0,0
BEGIN DESCRIPTION:
DUCK CREEK TRIB 25 3 1 0
END DESCRIPTION:
XS GIS Cut Line= 4
      3512884.46     10408165.33      3512975.59     10408412.68
      3513224.07     10408521.19      3513568.62     10408520.11
#Sta/Elev= 30
  4600.3  396.38  4604.8  395.97  4628.3  395.08  4665.7  393.09  4671.1  393.09
  4690.8  392.25  4696.2  392.40  4734.9  390.30  4757.1  389.78  4788.2  388.29
  4796.9  388.26  4797.1  387.76  4800.6  387.76  4800.9  388.26  4812.6  388.56
  4861.2  388.46  4950.8  388.44  5056.5  389.02  5089.3  391.06  5096.7  391.75
  5120.1  392.77  5144.5  393.38  5243.1  396.60  5303.1  399.11  5363.1  401.20
  5373.1  401.69  5393.1  404.06  5441.0  406.86  5453.1  407.38  5479.6  407.93
#Mann=6,-1,0
  4600.3    0.07       0  4796.9   0.033       0  4800.9    0.07       0
  4861.2    0.05       0  5144.5    0.16       0  5441.0     0.1       0
Bank Sta=4796.9,4800.9
Exp/Cntr=0.3,0.1

Chan Stop Cuts=-1