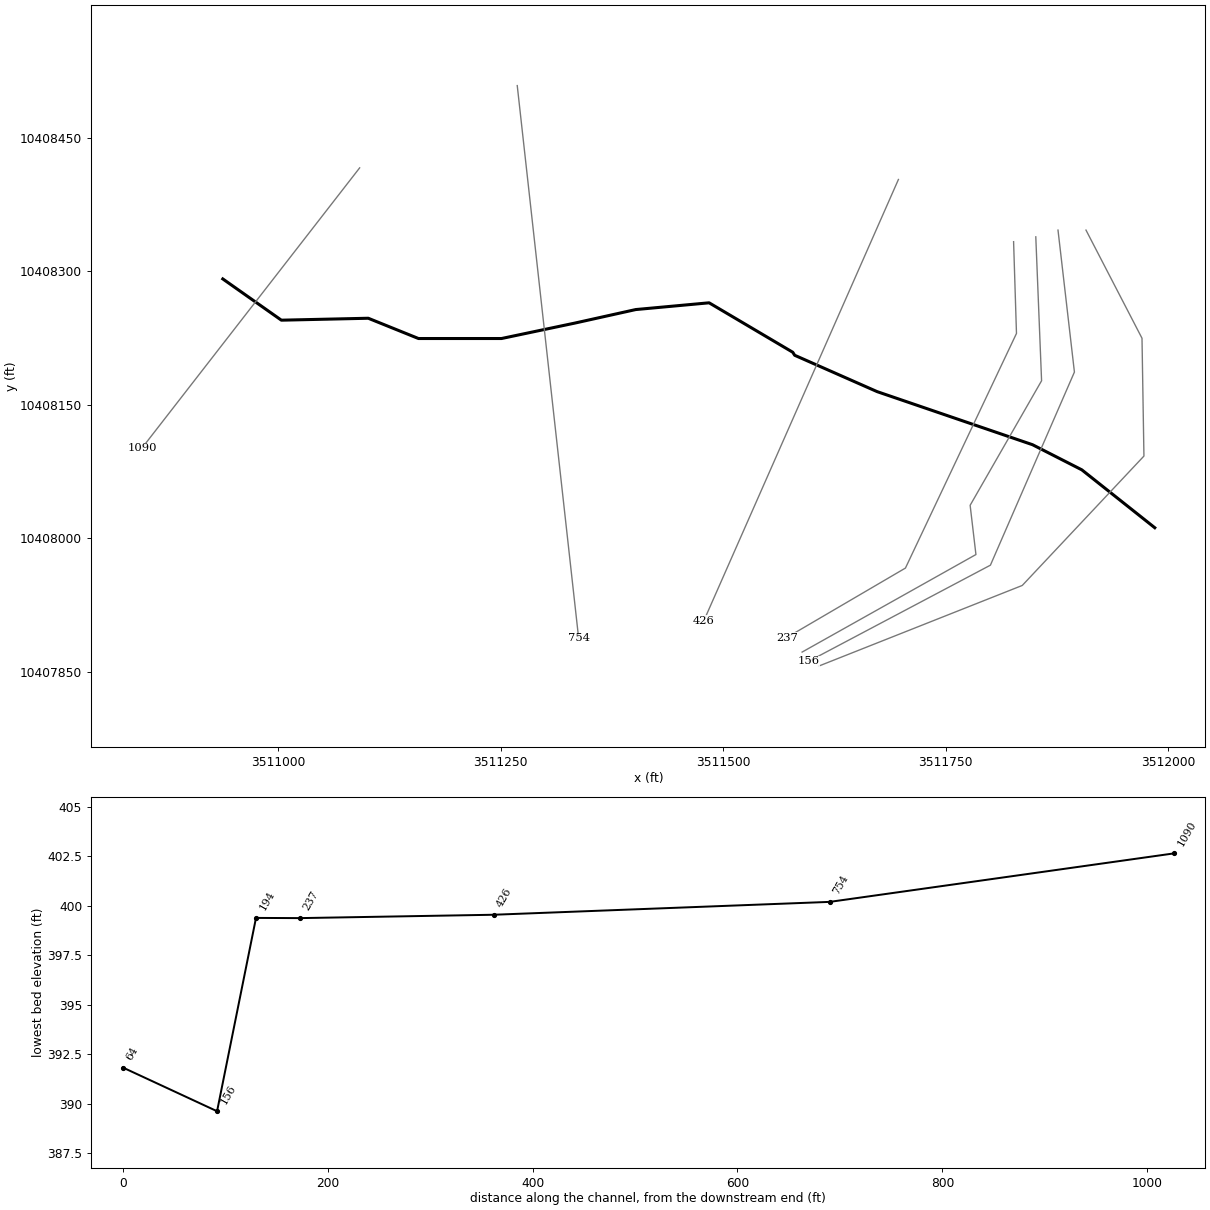
--- DUCK CREEK TRIB 25 4.prj (project) ---

Proj Title=DUCK CREEK TRIB 25 4 Base Level Engineering
Current Plan=p01
Default Exp/Contr=0.3,0.1
English Units
Geom File=g01
Flow File=f01
Plan File=p01
Y Axis Title=Elevation
X Axis Title(PF)=Main Channel Distance
X Axis Title(XS)=Station
BEGIN DESCRIPTION:
DUCK CREEK TRIB 25 4
END DESCRIPTION:
DSS Export Rating Curves= 0
DSS Export Rating Curve Sorted= 0
DSS Export Volume Flow Curves= 0
DXF OffsetX= 0
DXF OffsetY= 0
DXF ScaleX= 1
DXF ScaleY= 10

--- DUCK CREEK TRIB 25 4.p01 (plan) ---

Plan Title=Multiple Run
Short Identifier=Multiple
Geom File=g01
Flow File=f01
Subcritical Flow
K Sum by GR= 0
Std Step Tol= 0.01
Critical Tol= 0.01
Num of Std Step Trials= 20
Max Error Tol= 0.3
Flow Tol Ratio= 0.001
Split Flow NTrial= 30
Split Flow Tol= 0.02
Split Flow Ratio= 0.02
Log Output Level= 0
Friction Slope Method= 1
Unsteady Friction Slope Method= 2
Unsteady Bridges Friction Slope Method= 1
Parabolic Critical Depth
Global Vel Dist=  1 , 1 , 1
Global Log Level= 0
CheckData=True
Encroach Param= -1, 0, 0, 0
BEGIN DESCRIPTION:
Multiple Run
END DESCRIPTION:

--- DUCK CREEK TRIB 25 4.f01 (steady flow) ---

Flow Title=Multiple
Program Version=4.10
Number of Profiles= 7
Profile Names=10-year,25-year,50-year,1pct_min,100-year,1pct_plu,500-year
River Rch & RM=DUCK CREEK TRIB,Reach-1         ,1090
     328     425     500     433     586     792     797
Boundary for River Rch & Prof#=DUCK CREEK TRIB,Reach-1         , 1
Up Type= 0
Dn Type= 3
Dn Slope=0.02
Boundary for River Rch & Prof#=DUCK CREEK TRIB,Reach-1         , 2
Up Type= 0
Dn Type= 3
Dn Slope=0.02
Boundary for River Rch & Prof#=DUCK CREEK TRIB,Reach-1         , 3
Up Type= 0
Dn Type= 3
Dn Slope=0.02
Boundary for River Rch & Prof#=DUCK CREEK TRIB,Reach-1         , 4
Up Type= 0
Dn Type= 3
Dn Slope=0.02
Boundary for River Rch & Prof#=DUCK CREEK TRIB,Reach-1         , 5
Up Type= 0
Dn Type= 3
Dn Slope=0.02
Boundary for River Rch & Prof#=DUCK CREEK TRIB,Reach-1         , 6
Up Type= 0
Dn Type= 3
Dn Slope=0.02
Boundary for River Rch & Prof#=DUCK CREEK TRIB,Reach-1         , 7
Up Type= 0
Dn Type= 3
Dn Slope=0.02
DSS Import GetInterval= 0
DSS Import GetPeak= 0
DSS Import FillOption= 0

--- DUCK CREEK TRIB 25 4.g01 (geometry) ---

Geom Title=Existing Conditions
Program Version=4.10

River Reach=DUCK CREEK TRIB ,Reach-1
Reach XY= 14
      3510937.83     10408291.64      3511003.66     10408245.28
      3511101.31     10408247.45      3511157.74     10408224.67
      3511251.05     10408224.67      3511333.52     10408242.03
      3511401.88     10408257.22      3511484.34     10408264.81
      3511578.34     10408209.24      3511580.47     10408205.86
      3511673.15     10408164.99      3511847.84     10408105.31
      3511903.18      10408077.1      3511985.16     10408012.05

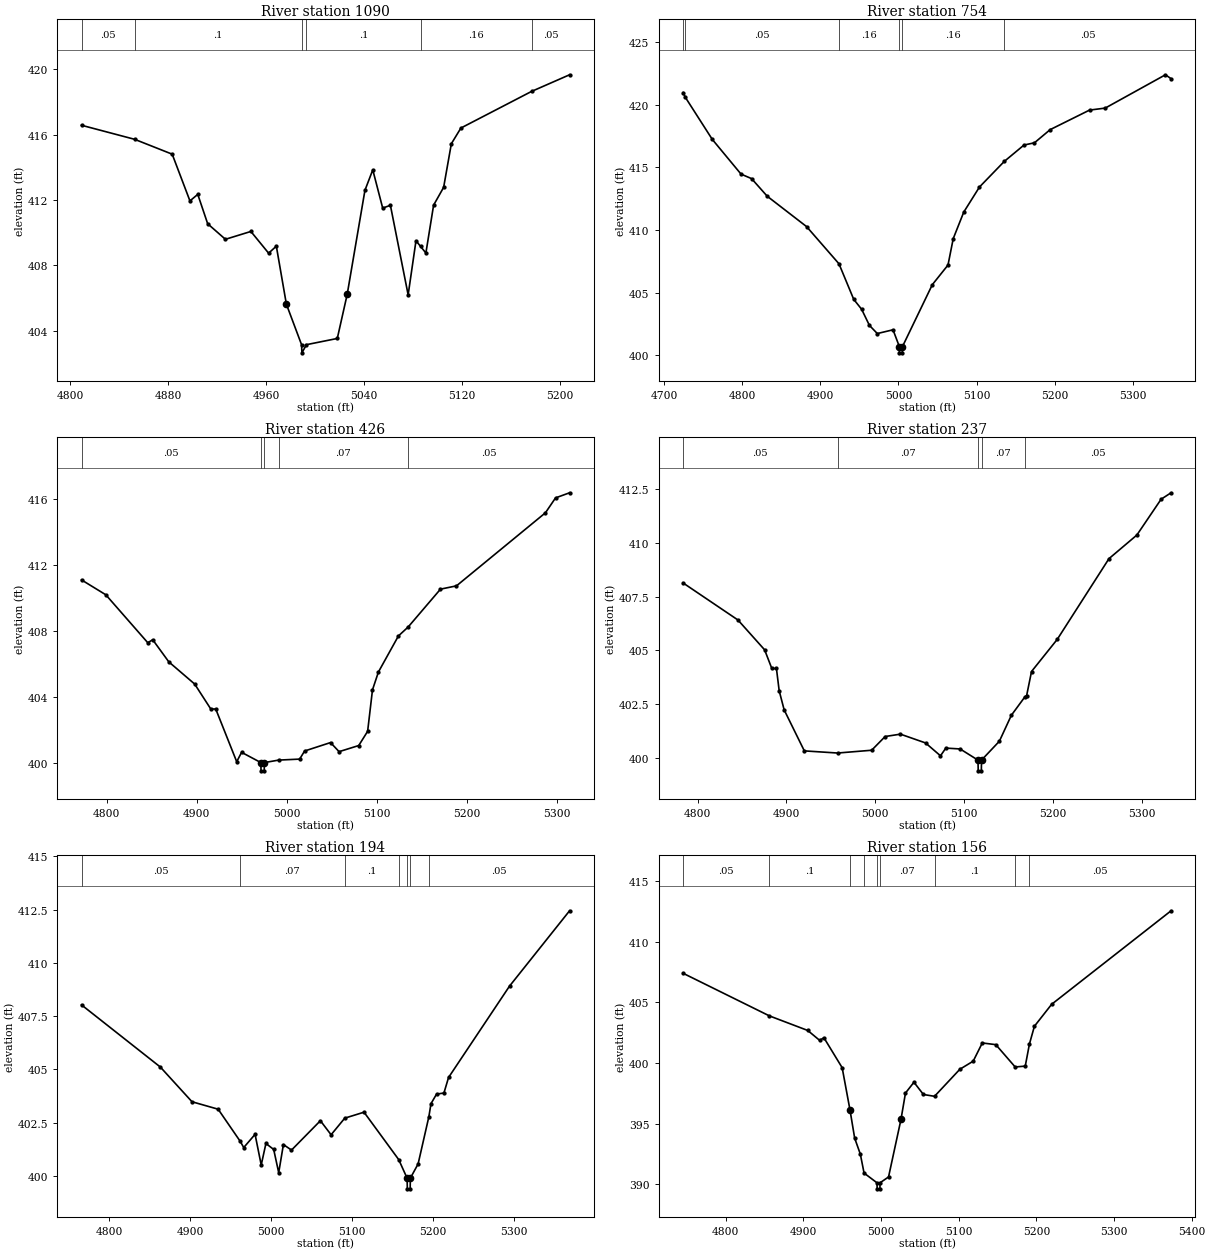
Type RM Length L Ch R = 1 ,1090    ,336,336,336
BEGIN DESCRIPTION:
DUCK CREEK TRIB 25 4 2 2
END DESCRIPTION:
XS GIS Cut Line= 2
      3511091.62     10408416.45      3510846.96     10408101.51
#Sta/Elev= 30
  4809.2  416.58  4852.6  415.72  4883.3  414.81  4897.8  411.95  4904.2  412.35
  4912.3  410.55  4926.8   409.6  4947.6  410.08  4962.1  408.75  4968.4  409.18
  4976.6  405.63    4989  403.15  4989.3  402.65    4993  403.15  5018.2  403.53
  5026.3  406.23  5040.8   412.6  5047.2  413.85  5055.3  411.51  5061.6  411.68
  5076.1   406.2  5082.5  409.51  5086.3  409.16  5090.6  408.76  5096.9  411.69
  5105.1  412.78  5111.4  415.45  5119.2  416.41  5176.9  418.65    5208  419.67
#Mann= 6 ,-1 , 0
  4809.2     .05       0  4852.6      .1       0    4989     .07       0
    4993      .1       0  5086.3     .16       0  5176.9     .05       0
Bank Sta=4976.6,5026.3
XS Rating Curve= 0 ,0
Exp/Cntr=0.3,0.1

Type RM Length L Ch R = 1 ,754     ,328,328,328
BEGIN DESCRIPTION:
DUCK CREEK TRIB 25 4 7 0
END DESCRIPTION:
XS GIS Cut Line= 2
      3511268.72     10408508.91      3511337.73     10407887.83
#Sta/Elev= 30
  4724.2  420.98  4727.2   420.6  4761.7  417.24  4798.5  414.47    4812  414.11
  4832.1   412.7  4882.4  410.28  4923.9  407.31  4942.8  404.47  4952.9  403.68
  4962.9  402.39    4973  401.74  4993.1  402.04  5001.2   400.7  5001.4   400.2
  5004.9   400.2  5005.2   400.7  5043.4  405.64  5063.5  407.21  5070.2  409.32
  5083.7  411.44  5103.8  413.44  5135.5  415.48  5160.8  416.79  5174.2  416.97
  5194.3  418.02  5244.7  419.58  5264.8  419.74  5341.9   422.4  5349.1  422.09
#Mann= 6 ,-1 , 0
  4724.2      .1       0  4727.2     .05       0  4923.9     .16       0
  5001.2     .07       0  5005.2     .16       0  5135.5     .05       0
Bank Sta=5001.2,5005.2
XS Rating Curve= 0 ,0
Exp/Cntr=0.3,0.1

Type RM Length L Ch R = 1 ,426     ,189,189,189
BEGIN DESCRIPTION:
DUCK CREEK TRIB 25 4 50
END DESCRIPTION:
XS GIS Cut Line= 2
      3511697.08      10408403.4      3511478.37     10407907.38
#Sta/Elev= 30
  4772.2   411.1  4799.2   410.2  4845.8   407.3  4851.3  407.48  4869.2  406.14
  4897.9   404.8  4915.8  403.29  4921.3  403.29  4944.6   400.1    4950  400.67
  4971.4  400.05  4971.6  399.55  4975.1  399.55  4975.4  400.05  4991.2   400.2
  5014.5  400.26    5020  400.75  5048.8  401.26  5058.3  400.71  5080.1  401.08
    5090  401.94  5095.4  404.45    5102  405.53  5124.2  407.71    5135  408.25
  5170.9  410.54  5188.7  410.74  5287.5  415.16  5298.7  416.06  5314.3  416.37
#Mann= 5 ,-1 , 0
  4772.2     .05       0  4971.4     .07       0  4975.4     .05       0
  4991.2     .07       0    5135     .05       0
Bank Sta=4971.4,4975.4
XS Rating Curve= 0 ,0
Exp/Cntr=0.3,0.1

Type RM Length L Ch R = 1 ,237     ,43,43,43
BEGIN DESCRIPTION:
Mapping XS 81cceda2
END DESCRIPTION:
XS GIS Cut Line= 4
       3511826.5      10408333.5      3511829.75     10408230.39
      3511704.97     10407966.72      3511571.52      10407888.6
#Sta/Elev= 30
  4783.6  408.14  4845.5  406.41  4875.5  405.02  4883.6  404.15  4888.8  404.15
  4891.9  403.11  4897.5  402.22  4920.2  400.31  4957.7  400.21    4996  400.34
  5011.2  400.98  5028.4  401.09  5056.7  400.68  5073.5  400.08  5079.5  400.44
  5095.6   400.4  5115.7  399.88    5116  399.38  5119.5  399.38  5119.7  399.88
  5139.8  400.76  5153.3  401.97  5168.2  402.81  5170.5  402.89    5176  404.01
    5205  405.51  5263.2  409.27  5294.6  410.37  5321.9  412.04  5333.1  412.34
#Mann= 5 ,-1 , 0
  4783.6     .05       0  4957.7     .07       0  5115.7     .07       0
  5119.7     .07       0  5168.2     .05       0
Bank Sta=5115.7,5119.7
XS Rating Curve= 0 ,0
Exp/Cntr=0.3,0.1

Type RM Length L Ch R = 1 ,194     ,38,38,38
BEGIN DESCRIPTION:
DUCK CREEK TRIB 25 4 2 1
END DESCRIPTION:
XS GIS Cut Line= 5
      3511851.45     10408338.94      3511857.96     10408177.22
      3511777.67     10408037.25      3511784.18     10407981.91
      3511588.86     10407872.31
#Sta/Elev= 30
  4765.5  408.03  4862.9  405.11    4902  403.48  4934.3  403.13  4961.4  401.63
  4965.9  401.33  4979.9  401.95  4987.5  400.51  4993.3  401.52  5002.9  401.24
  5009.1  400.15  5014.9  401.47  5024.9  401.21  5060.6  402.59  5073.8  401.93
  5090.7  402.71  5114.5  402.99  5157.4  400.76  5167.7  399.89    5168  399.39
  5171.5  399.39  5171.7  399.89  5181.3  400.56  5194.6  402.78  5197.2  403.39
  5204.1  403.84  5213.2  403.89  5218.9  404.62  5294.2  408.91  5368.4  412.45
#Mann= 7 ,-1 , 0
  4765.5     .05       0  4961.4     .07       0  5090.7      .1       0
  5157.4     .07       0  5167.7     .07       0  5171.7     .07       0
  5194.6     .05       0
Bank Sta=5167.7,5171.7
XS Rating Curve= 0 ,0
Exp/Cntr=0.3,0.1

Type RM Length L Ch R = 1 ,156     ,92,92,92
BEGIN DESCRIPTION:
Mapping XS ff39c38b
END DESCRIPTION:
XS GIS Cut Line= 4
      3511876.41     10408346.53      3511894.86     10408186.98
      3511800.46     10407969.97      3511596.24     10407861.92
#Sta/Elev= 30
  4745.1   407.4  4856.4  403.88  4905.7  402.68  4921.1  401.86  4926.5  402.08
    4950  399.61    4960  396.15  4966.1   393.8  4973.4  392.48  4978.2  390.92
  4994.8  390.12  4995.1  389.62  4998.6  389.62  4998.8  390.12  5009.7   390.6
  5025.7  395.34  5031.5  397.52  5042.4  398.41  5054.6   397.4  5068.9  397.25
  5101.5  399.48  5118.7  400.15  5130.4  401.65  5147.8  401.51  5172.7  399.67
  5185.7  399.74  5191.1  401.57  5197.5  403.03  5219.7  404.84  5373.4  412.55
#Mann= 9 ,-1 , 0
  4745.1     .05       0  4856.4      .1       0    4960     .16       0
  4978.2     .07       0  4994.8     .07       0  4998.8     .07       0
  5068.9      .1       0  5172.7     .07       0  5191.1     .05       0
Bank Sta=4960,5025.7
XS Rating Curve= 0 ,0
Exp/Cntr=0.3,0.1

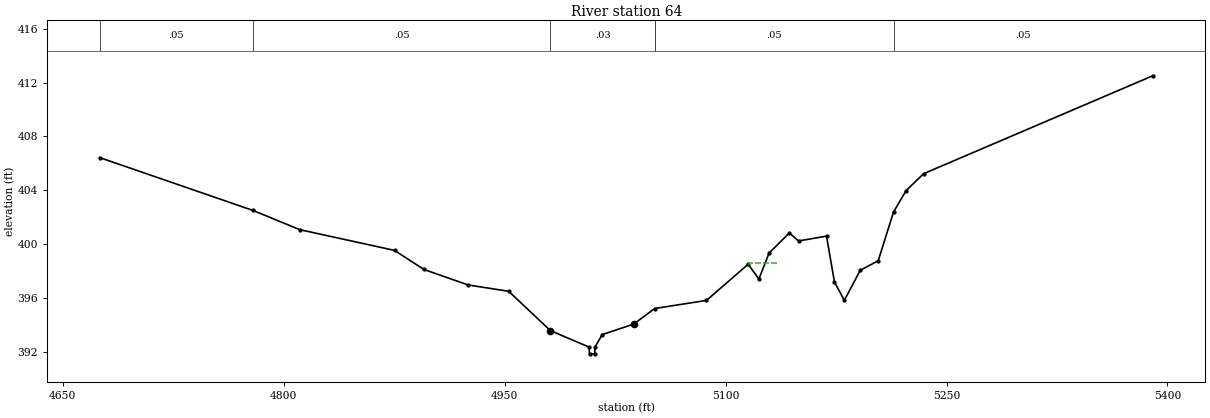
Type RM Length L Ch R = 1 ,64      ,0,0,0
BEGIN DESCRIPTION:
DUCK CREEK TRIB 25 4 1 0
END DESCRIPTION:
XS GIS Cut Line= 5
      3511907.86     10408346.52      3511970.81     10408224.96
      3511972.98     10408092.58      3511836.26     10407947.18
      3511607.44     10407856.52
#Sta/Elev= 30
    4675  406.42  4779.1  402.49  4810.9  401.06  4875.2  399.52  4895.2   398.1
  4925.2  396.95  4952.7  396.48    4981  393.56  5007.3  392.33  5007.6  391.83
  5011.1  391.83  5011.3  392.33  5016.2  393.26  5037.6  394.04  5051.8   395.2
    5087   395.8  5115.3  398.49  5122.6  397.39  5129.5  399.32  5143.3  400.82
  5149.5  400.22  5168.5  400.58  5173.9  397.17  5180.6  395.81  5191.4  398.04
  5203.6  398.75    5214  402.37  5222.5  403.96  5234.4  405.22    5390   412.5
#Mann= 6 ,-1 , 0
    4675     .05       0  4779.1     .05       0    4981     .03       0
  5051.8     .07       0  5051.8     .05       0    5214     .05       0
#XS Ineff= 2 ,-1
 5115.86 5135.05  398.55 5166.41    5390  400.52
Permanent Ineff=
       F       F
Bank Sta=4981,5037.6
XS Rating Curve= 0 ,0
Exp/Cntr=0.3,0.1

Chan Stop Cuts=-1
Use User Specified Reach Order=0
Composite Channel Slope=5