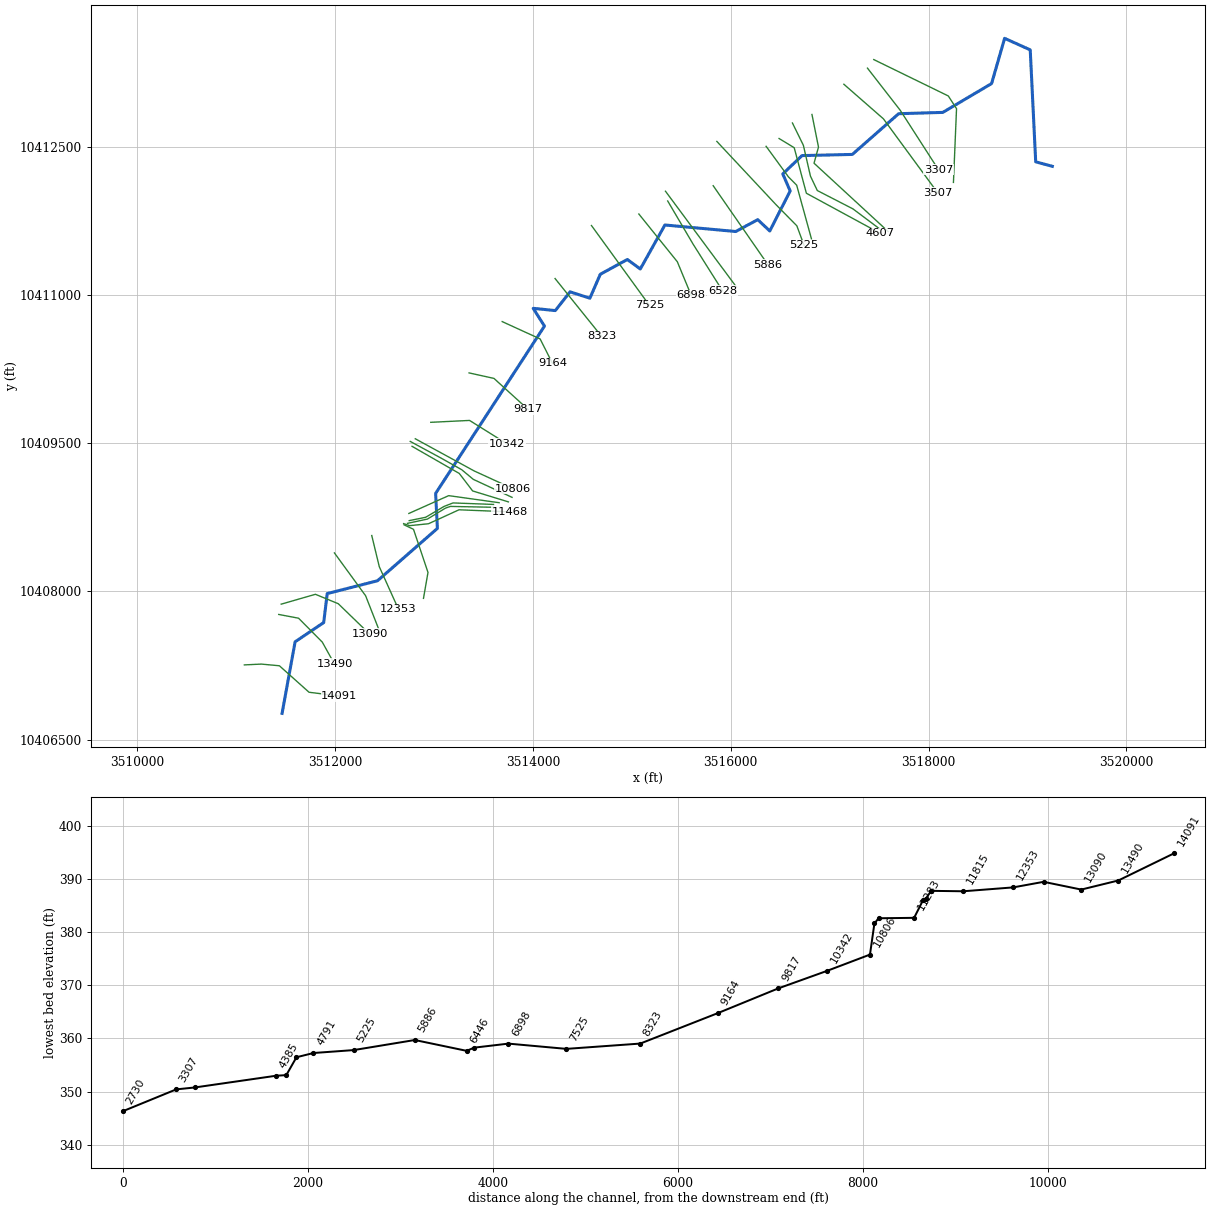
--- DUCK CREEK TRIB 25.prj (project) ---

Proj Title=DUCK CREEK TRIB 25 Base Level Engineering
Current Plan=p01
Default Exp/Contr=0.3,0.1
English Units
Geom File=g01
Flow File=f01
Plan File=p01
Y Axis Title=Elevation
X Axis Title(PF)=Main Channel Distance
X Axis Title(XS)=Station
BEGIN DESCRIPTION:
DUCK CREEK TRIB 25
END DESCRIPTION:
DSS Export Rating Curves= 0
DSS Export Rating Curve Sorted= 0
DSS Export Volume Flow Curves= 0
DXF OffsetX= 0
DXF OffsetY= 0
DXF ScaleX= 1
DXF ScaleY= 10

--- DUCK CREEK TRIB 25.p01 (plan) ---

Plan Title=Multiple Run
Short Identifier=Multiple
Geom File=g01
Flow File=f01
Subcritical Flow
K Sum by GR= 0
Std Step Tol= 0.01
Critical Tol= 0.01
Num of Std Step Trials= 20
Max Error Tol= 0.3
Flow Tol Ratio= 0.001
Split Flow NTrial= 30
Split Flow Tol= 0.02
Split Flow Ratio= 0.02
Log Output Level= 0
Friction Slope Method= 1
Unsteady Friction Slope Method= 2
Unsteady Bridges Friction Slope Method= 1
Parabolic Critical Depth
Global Vel Dist=  1 , 1 , 1
Global Log Level= 0
CheckData=True
Encroach Param= -1, 0, 0, 0
BEGIN DESCRIPTION:
Multiple Run
END DESCRIPTION:

--- DUCK CREEK TRIB 25.f01 (steady flow) ---

Flow Title=Multiple
Number of Profiles=7
Profile Names=10-year,25-year,50-year,1pct_min,100-year,1pct_plu,500-year
River Rch & RM= DUCK CREEK TRIB ,Reach-1,14091
     485     644     771     676     915    1237    1280
River Rch & RM= DUCK CREEK TRIB ,Reach-1,12683
     765    1044    1273    1134    1534    2074    2219
River Rch & RM= DUCK CREEK TRIB ,Reach-1,11468
    1367    1921    2386    2161    2922    3952    4374
River Rch & RM= DUCK CREEK TRIB ,Reach-1,4791
    1525    2152    2682    2435    3293    4453    4954
Boundary for River Rch & Prof#=DUCK CREEK TRIB ,Reach-1,1
Up Type=0
Dn Type=3
Dn Slope=0.005
Boundary for River Rch & Prof#=DUCK CREEK TRIB ,Reach-1,2
Up Type=0
Dn Type=3
Dn Slope=0.005
Boundary for River Rch & Prof#=DUCK CREEK TRIB ,Reach-1,3
Up Type=0
Dn Type=3
Dn Slope=0.005
Boundary for River Rch & Prof#=DUCK CREEK TRIB ,Reach-1,4
Up Type=0
Dn Type=3
Dn Slope=0.005
Boundary for River Rch & Prof#=DUCK CREEK TRIB ,Reach-1,5
Up Type=0
Dn Type=3
Dn Slope=0.005
Boundary for River Rch & Prof#=DUCK CREEK TRIB ,Reach-1,6
Up Type=0
Dn Type=3
Dn Slope=0.005
Boundary for River Rch & Prof#=DUCK CREEK TRIB ,Reach-1,7
Up Type=0
Dn Type=3
Dn Slope=0.005

--- DUCK CREEK TRIB 25.g01 (geometry) ---

Geom Title=Existing Conditions
Program Version=4.10

River Reach=DUCK CREEK TRIB ,Reach-1
Reach XY= 30
      3511463.24      10406766.1      3511595.17     10407490.37
      3511884.12     10407685.19      3511919.72     10407978.43
      3512427.92     10408107.78      3513033.69     10408637.78
      3513015.94     10408991.92      3514116.54     10410684.87
      3514002.39     10410864.84        3514226.     10410841.93
      3514375.31     10411031.51        3514576.     10410966.93
      3514680.86     10411209.29      3514954.47     10411358.59
      3515085.72     10411262.76      3515334.34      10411707.9
      3516050.31     10411641.93      3516273.22     10411762.06
      3516394.67     10411647.21       3516601.1     10412052.26
      3516526.18     10412224.56       3516720.6     10412410.14
      3517229.63     10412421.94      3517697.65     10412834.01
      3518144.72     10412847.28      3518637.75     10413139.01
       3518769.3     10413596.69      3519028.42     10413480.12
      3519083.74     10412347.14      3519252.11     10412301.64

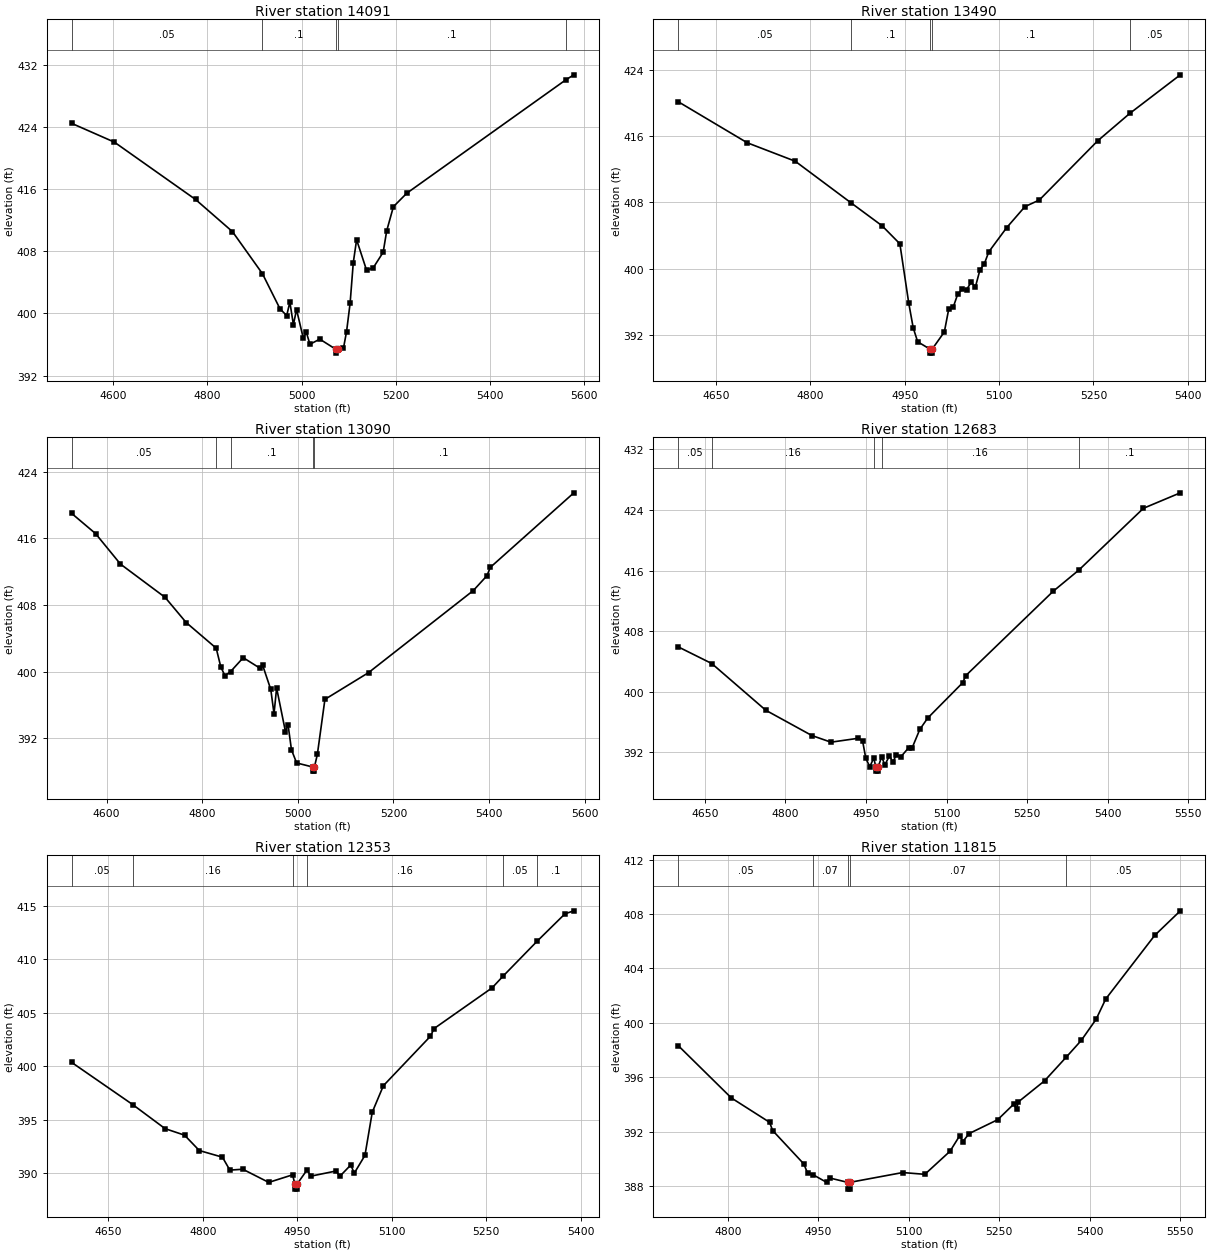
Type RM Length L Ch R = 1 ,14091   ,601,601,601
BEGIN DESCRIPTION:
DUCK CREEK TRIB 25 31 0
END DESCRIPTION:
XS GIS Cut Line= 5
      3511081.84     10407256.62      3511253.93     10407264.73
      3511436.22     10407247.81      3511736.04     10406979.85
      3512042.09     10406941.64
#Sta/Elev= 30
  4511.9  424.46  4602.3  422.05  4774.7  414.67  4853.1  410.53  4916.7  405.12
    4954   400.6  4968.2  399.73  4974.9  401.47  4982.4  398.57  4989.1   400.5
  5003.3  396.85    5010  397.56  5017.5  396.04  5038.4   396.7  5072.4   395.4
  5072.6   394.9  5076.4   395.4  5088.6   395.5  5095.3  397.68  5102.8  401.31
  5109.5  406.52  5116.6  409.49  5137.9  405.54  5152.1   405.9    5173  407.88
  5180.5  410.64  5194.7  413.74  5223.2  415.48  5560.2  430.04  5577.8  430.71
#Mann= 5 ,-1 , 0
  4511.9     .05       0  4916.7      .1       0  5072.4     .07       0
  5076.4      .1       0  5560.2     .05       0
Bank Sta=5072.4,5076.4
XS Rating Curve= 0 ,0
Exp/Cntr=0.3,0.1

Type RM Length L Ch R = 1 ,13490   ,400,400,400
BEGIN DESCRIPTION:
DUCK CREEK TRIB 25 3 0
END DESCRIPTION:
XS GIS Cut Line= 4
      3511429.38     10407767.06       3511630.1     10407729.09
       3511869.9     10407487.11      3511993.03     10407265.69
#Sta/Elev= 30
  4589.8  420.17  4699.5  415.21  4775.8  412.98  4864.9  407.93  4913.9  405.18
  4942.2     403  4956.3  395.84  4963.4  392.85  4970.5  391.16  4989.7  390.29
  4989.9  389.79  4993.4  389.79  4993.7  390.29  5012.9  392.35    5020  395.16
  5027.1  395.36  5034.1   396.9  5041.2   397.5  5048.2  397.45  5055.3  398.33
  5062.4  397.82  5069.5  399.84  5076.5  400.59  5083.6  402.03  5111.9  404.94
    5141  407.49  5163.9  408.29  5256.8  415.45  5307.8  418.76  5388.1  423.42
#Mann= 5 ,-1 , 0
  4589.8     .05       0  4864.9      .1       0  4989.7     .07       0
  4993.7      .1       0  5307.8     .05       0
Bank Sta=4989.7,4993.7
XS Rating Curve= 0 ,0
Exp/Cntr=0.3,0.1

Type RM Length L Ch R = 1 ,13090   ,407,407,407
BEGIN DESCRIPTION:
DUCK CREEK TRIB 25 27 0
END DESCRIPTION:
XS GIS Cut Line= 4
      3511454.32     10407871.23      3511800.46     10407971.06
      3512031.58     10407875.57      3512347.19     10407569.72
#Sta/Elev= 30
  4527.3  418.99    4577  416.58  4629.1  412.92  4722.4  408.93  4766.5  405.91
  4829.3  402.83    4839  400.56  4847.6  399.53  4859.3  400.02  4885.8  401.69
  4920.8  400.43  4926.2  400.82  4943.4  397.88  4950.2  394.97  4955.6  398.06
  4974.1  392.82  4979.5  393.65  4986.7  390.63  4997.5  389.06  5030.7  388.58
    5031  388.08  5034.5  388.08  5034.7  388.58  5040.8  390.08  5056.6  396.69
  5147.9   399.9    5367  409.75  5395.3  411.52  5402.5  412.53  5577.1  421.47
#Mann= 5 ,-1 , 0
  4527.3     .05       0  4829.3     .07       0  4859.3      .1       0
  5030.7     .07       0  5034.7      .1       0
Bank Sta=5030.7,5034.7
XS Rating Curve= 0 ,0
Exp/Cntr=0.3,0.1

Type RM Length L Ch R = 1 ,12683   ,330,330,330
BEGIN DESCRIPTION:
DUCK CREEK TRIB 25 26 0
END DESCRIPTION:
XS GIS Cut Line= 3
      3511992.48     10408389.93      3512308.27     10407955.86
      3512453.29     10407585.74
#Sta/Elev= 30
  4600.6  405.94    4663  403.74  4763.4  397.58  4849.2  394.24  4884.8  393.36
    4935  393.87  4943.5  393.58  4949.7  391.21  4957.1  390.12  4964.4  391.27
  4968.5  390.04  4968.8  389.54  4972.3  389.54  4972.5  390.04    4979  391.42
  4985.2  390.38  4993.7  391.56  4999.9  390.73  5006.6   391.7  5014.6  391.41
  5029.3  392.62  5035.5  392.55  5050.1  395.04  5064.8  396.54  5129.7  401.19
  5135.9  402.16  5298.2  413.27    5346  416.07  5466.3  424.23  5534.9  426.27
#Mann= 5 ,-1 , 0
  4600.6     .05       0    4663     .16       0  4964.4     .12       0
    4979     .16       0    5346      .1       0
Bank Sta=4968.5,4972.5
XS Rating Curve= 0 ,0
Exp/Cntr=0.3,0.1

Type RM Length L Ch R = 1 ,12353   ,538,538,538
BEGIN DESCRIPTION:
DUCK CREEK TRIB 25 25 0
END DESCRIPTION:
XS GIS Cut Line= 3
      3512370.01     10408565.73      3512446.39      10408249.8
      3512640.85     10407819.21
#Sta/Elev= 30
  4591.9  400.34  4688.7   396.4  4740.1  394.15    4771  393.54  4794.5   392.1
  4831.2  391.48    4843  390.27  4863.6  390.35  4904.8  389.12  4942.7  389.83
  4946.1  388.99  4946.4  388.49  4949.9  388.49  4950.1  388.99  4965.8   390.3
  4971.3   389.7    5012  390.19  5017.5  389.68  5035.1  390.75  5040.6  389.98
  5057.6  391.65  5069.2  395.69  5086.9  398.17  5161.7   402.8  5167.3  403.51
  5259.7  407.33    5277  408.42  5331.3   411.7  5375.3  414.25  5389.4  414.53
#Mann= 6 ,-1 , 0
  4591.9     .05       0  4688.7     .16       0  4942.7     .12       0
  4965.8     .16       0    5277     .05       0  5331.3      .1       0
Bank Sta=4946.1,4950.1
XS Rating Curve= 0 ,0
Exp/Cntr=0.3,0.1

Type RM Length L Ch R = 1 ,11815   ,347,347,347
BEGIN DESCRIPTION:
DUCK CREEK TRIB 25 24 0
END DESCRIPTION:
XS GIS Cut Line= 4
      3512696.69     10408674.19      3512792.21     10408628.61
      3512938.69     10408192.41      3512893.12     10407929.81
#Sta/Elev= 30
  4717.9  398.32    4806  394.47  4869.3  392.68  4874.5  392.07    4926  389.62
  4932.3  388.95  4941.1  388.83  4963.9  388.26  4969.1  388.58  4998.7  388.26
  4998.9  387.76  5002.4  387.76  5002.7  388.26    5090  388.98  5126.8  388.85
  5168.6  390.55  5184.6  391.69  5189.8  391.26  5200.3  391.85  5247.6  392.87
  5273.9     394  5279.1  393.66  5281.6  394.17  5325.3  395.73  5361.6  397.49
  5386.1   398.7  5410.8  400.26  5426.7  401.75  5507.9  406.43  5550.4  408.24
#Mann= 5 ,-1 , 0
  4717.9     .05       0  4941.1     .07       0  4998.7     .07       0
  5002.7     .07       0  5361.6     .05       0
Bank Sta=4998.7,5002.7
XS Rating Curve= 0 ,0
Exp/Cntr=0.3,0.1

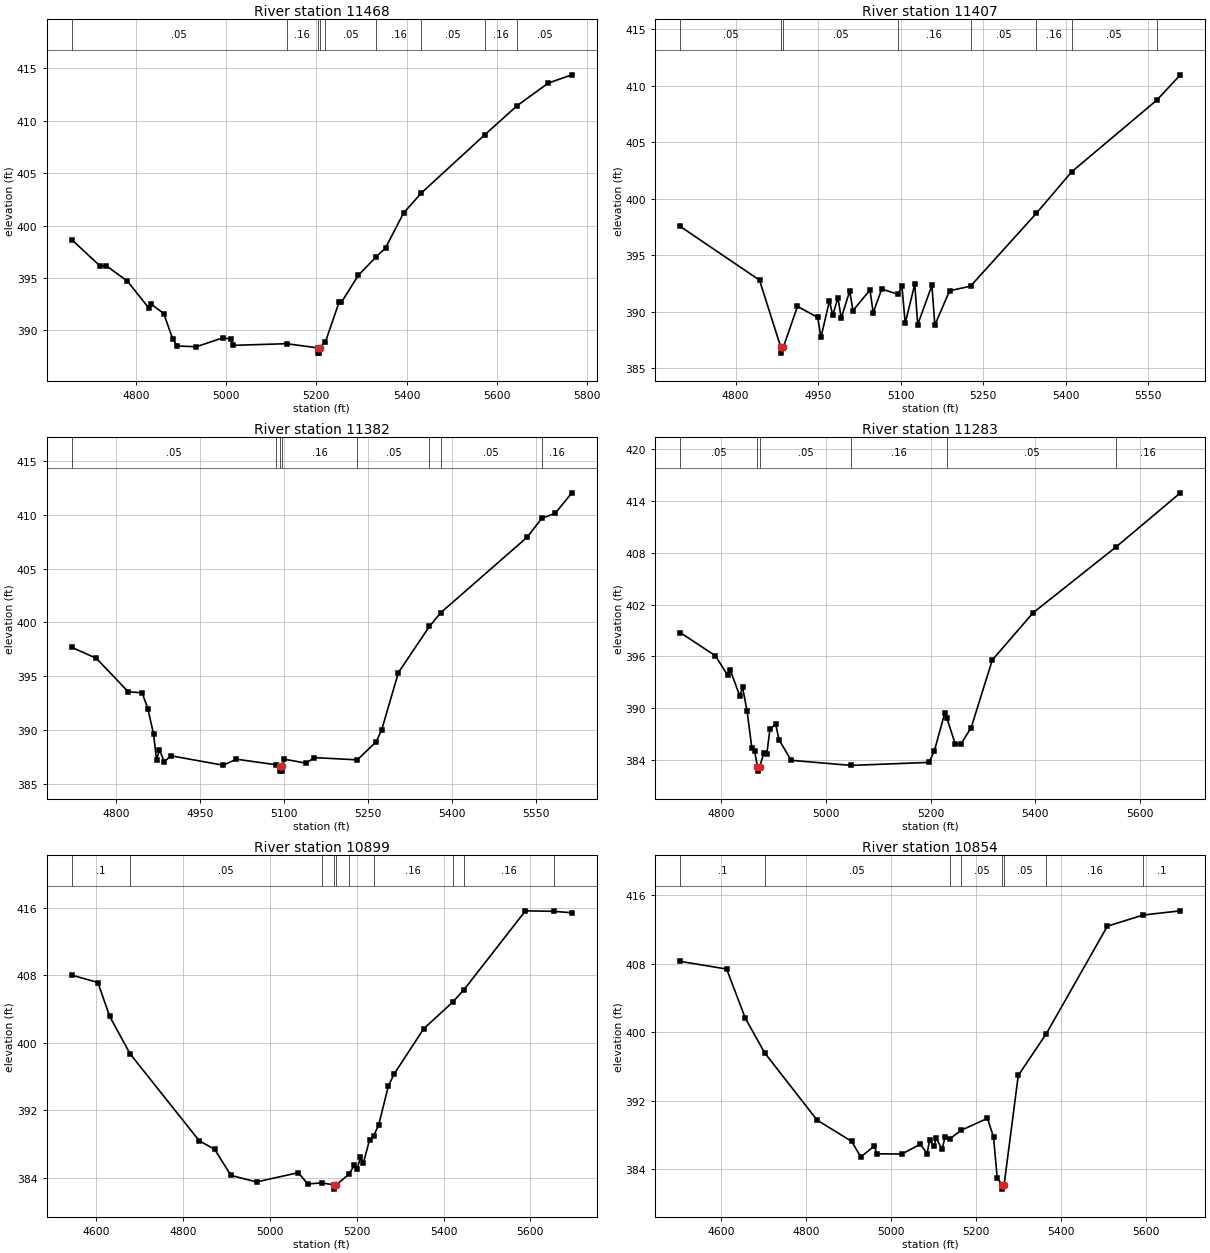
Type RM Length L Ch R = 1 ,11468   ,61,61,61
BEGIN DESCRIPTION:
DUCK CREEK TRIB 25 21 2
END DESCRIPTION:
XS GIS Cut Line= 5
      3512692.34     10408686.13      3512753.15      10408665.5
      3512944.12     10408685.03      3513252.28     10408826.09
      3513764.47     10408805.47
#Sta/Elev= 30
  4658.2  398.67  4720.6  396.17    4735  396.17  4781.7   394.7  4829.4  392.12
  4834.4  392.51  4862.1  391.62  4882.2  389.15  4892.3  388.52  4934.2  388.45
  4992.5  389.29    5010   389.2  5015.5  388.58  5134.2  388.74  5202.9  388.34
  5203.2  387.84  5206.9  387.84  5207.2  388.34    5220  388.89  5250.4   392.7
  5255.7   392.7  5293.2  395.27  5332.5  397.03  5353.2  397.87  5393.2  401.21
  5432.7  403.12  5573.2  408.68  5644.6  411.44  5713.5   413.6  5765.9  414.39
#Mann= 9 ,-1 , 0
  4658.2     .05       0  5134.2     .16       0  5202.9     .03       0
  5207.2     .16       0    5220     .05       0  5332.5     .16       0
  5432.7     .05       0  5573.2     .16       0  5644.6     .05       0
Bank Sta=5202.9,5207.2
XS Rating Curve= 0 ,0
Exp/Cntr=0.3,0.1

Type RM Length L Ch R = 1 ,11407   ,25,25,25
BEGIN DESCRIPTION:
DUCK CREEK TRIB 25 22 0
END DESCRIPTION:
XS GIS Cut Line= 5
       3512731.2     10408688.89      3512932.99     10408732.28
      3513115.28     10408842.96      3513165.19     10408860.32
       3513601.4     10408851.64
#Sta/Elev= 30
  4699.5  397.54  4843.6  392.78  4882.4  386.82  4882.7  386.32  4886.7  386.82
  4912.5  390.46  4949.3  389.48  4955.2  387.72  4970.7  390.96  4976.5  389.66
  4986.1  391.24    4992  389.41  5007.5  391.83  5013.3  390.08  5044.3  391.91
  5050.1  389.89  5065.6     392  5094.9  391.53  5102.4  392.22  5108.3  388.97
  5125.7  392.42    5131  388.84  5156.8  392.32  5162.1   388.8  5188.9  391.84
    5227  392.25  5346.4  398.69  5411.1  402.39  5565.2  408.71  5608.3  410.96
#Mann= 8 ,-1 , 0
  4699.5     .05       0  4882.4     .03       0  4886.7     .05       0
  5094.9     .16       0    5227     .05       0  5346.4     .16       0
  5411.1     .05       0  5565.2     .16       0
Bank Sta=4882.4,4886.7
XS Rating Curve= 0 ,0
Exp/Cntr=0.3,0.1

Type RM Length L Ch R = 1 ,11382   ,99,99,99
BEGIN DESCRIPTION:
DUCK CREEK TRIB 25 23 0
END DESCRIPTION:
XS GIS Cut Line= 5
      3512748.78     10408716.49      3512914.82     10408750.14
      3513100.37     10408859.73      3513191.51     10408895.54
       3513601.7     10408880.34
#Sta/Elev= 30
  4720.2  397.69  4764.4  396.66  4821.1  393.55    4846  393.45  4856.2  391.98
  4866.4  389.63  4871.8  387.19  4876.9  388.14  4885.7  387.03  4897.3  387.59
    4991  386.71  5014.2  387.27  5085.8  386.75  5092.2  386.66  5092.5  386.16
  5096.2  386.16  5096.5  386.66  5100.2  387.27  5139.2   386.9  5153.3  387.42
  5230.3  387.21  5263.7  388.87  5273.7  389.97  5303.7  395.34  5359.1  399.63
  5379.4  400.91  5533.9  407.95  5559.7  409.69  5583.9  410.17  5613.5  412.07
#Mann= 8 ,-1 , 0
  4720.2     .05       0  5085.8     .16       0  5092.2     .03       0
  5096.5     .16       0  5230.3     .05       0  5359.1     .16       0
  5379.4     .05       0  5559.7     .16       0
Bank Sta=5092.2,5096.5
XS Rating Curve= 0 ,0
Exp/Cntr=0.3,0.1

Type RM Length L Ch R = 1 ,11283   ,384,384,384
BEGIN DESCRIPTION:
Mapping XS a654a0ae
END DESCRIPTION:
XS GIS Cut Line= 3
      3512745.52     10408789.19      3513148.11     10408969.32
      3513658.18     10408897.85
#Sta/Elev= 30
  4721.1  398.76  4788.4  396.08  4811.6  393.84  4817.1  394.38  4834.8  391.45
  4840.3  392.42  4848.8  389.74    4858  385.43  4863.5  385.03  4868.6  383.25
  4868.9  382.75  4872.9  383.25  4881.2   384.9  4886.7  384.77  4892.6   387.6
  4903.6  388.18  4909.9  386.38  4933.1     384  5047.8  383.41  5196.5  383.76
  5206.6  385.03  5226.8  389.47  5230.8  388.87    5247  385.85  5257.8  385.89
  5277.3  387.79  5317.6  395.59  5395.5  401.04  5554.5  408.67  5677.2  414.91
#Mann= 6 ,-1 , 0
  4721.1     .05       0  4868.6     .03       0  4872.9     .05       0
  5047.8     .16       0  5230.8     .05       0  5554.5     .16       0
Bank Sta=4868.6,4872.9
XS Rating Curve= 0 ,0
Exp/Cntr=0.3,0.1

Type RM Length L Ch R = 1 ,10899   ,45,45,45
BEGIN DESCRIPTION:
DUCK CREEK TRIB 25 21 0
END DESCRIPTION:
XS GIS Cut Line= 4
      3512777.54     10409468.22      3513254.95     10409193.93
      3513390.37     10409016.85      3513751.78     10408906.18
#Sta/Elev= 30
    4544  408.02  4604.3  407.14  4631.6  403.12  4678.5  398.69  4837.6   388.4
  4873.2  387.38  4910.5   384.3  4969.5  383.52  5065.8  384.62  5087.4  383.28
  5119.5  383.41  5148.6  383.17  5148.9  382.67    5153  383.17  5182.7  384.46
  5194.4  385.47  5200.7     385  5208.9  386.43  5215.2  385.71  5229.8   388.5
  5239.4  389.01  5250.6  390.25  5273.3  394.92  5286.3   396.3  5354.2  401.65
  5421.1  404.82  5447.3   406.3  5588.7  415.63  5653.8  415.57  5695.5   415.4
#Mann= 10 ,-1 , 0
    4544      .1       0  4678.5     .05       0  5119.5     .16       0
  5148.6     .03       0    5153     .16       0  5182.7     .05       0
  5239.4     .16       0  5421.1     .05       0  5447.3     .16       0
  5653.8      .1       0
Bank Sta=5148.6,5153
XS Rating Curve= 0 ,0
Exp/Cntr=0.3,0.1

Type RM Length L Ch R = 1 ,10854   ,48,48,48
BEGIN DESCRIPTION:
DUCK CREEK TRIB 25 20 0
END DESCRIPTION:
XS GIS Cut Line= 5
      3512759.37     10409517.87      3513067.22     10409351.32
      3513280.21     10409231.42       3513397.4     10409133.76
      3513788.64     10408952.19
#Sta/Elev= 30
  4503.3  408.29  4612.7  407.39  4656.4  401.68    4702  397.62  4825.8  389.75
  4907.1  387.27  4928.8  385.45  4960.6  386.73  4966.4  385.81  5025.6  385.79
    5069  386.94  5084.9  385.83  5090.6  387.37  5101.5  386.69    5106  387.66
  5120.3  386.35  5126.8  387.72  5138.1  387.53  5163.9  388.54    5227  389.95
  5241.3   387.8  5250.1  382.96  5261.9  382.19  5262.2  381.69  5266.3  382.19
  5299.6  394.96  5365.7  399.84  5509.6   412.4  5593.9   413.7  5681.6  414.19
#Mann= 8 ,-1 , 0
  4503.3      .1       0    4702     .05       0  5138.1     .16       0
  5163.9     .05       0  5261.9     .03       0  5266.3     .05       0
  5365.7     .16       0  5593.9      .1       0
Bank Sta=5261.9,5266.3
XS Rating Curve= 0 ,0
Exp/Cntr=0.3,0.1

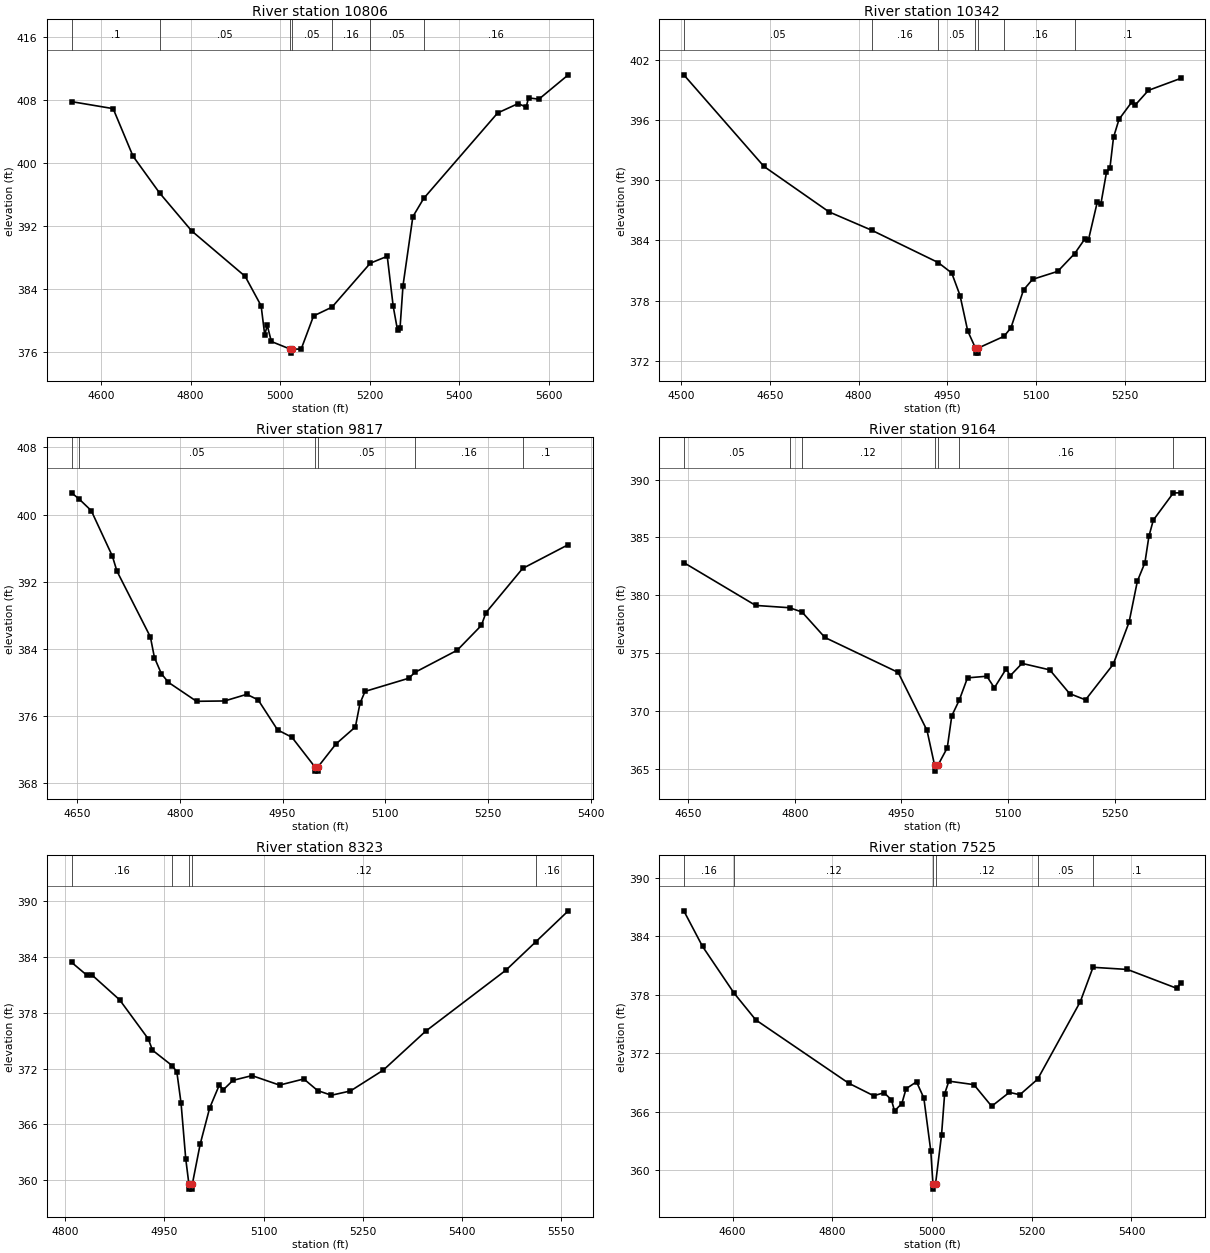
Type RM Length L Ch R = 1 ,10806   ,464,464,464
BEGIN DESCRIPTION:
DUCK CREEK TRIB 25 19 2
END DESCRIPTION:
XS GIS Cut Line= 3
      3512810.49     10409544.64      3513407.73     10409218.23
       3513797.7     10409039.72
#Sta/Elev= 30
  4534.2  407.81  4627.2  406.92  4671.5  400.88  4730.8   396.2  4802.5  391.37
    4922  385.59  4957.7  381.84  4965.7  378.15  4971.4  379.35  4980.5   377.3
  5023.2  376.32  5023.5  375.82  5027.6  376.32  5047.2  376.34  5074.8  380.55
    5116  381.67  5201.5  387.26  5239.4  388.14  5252.6  381.81  5262.4  378.71
  5267.9  378.98  5274.6  384.42  5296.6  393.18  5320.8   395.5    5486  406.37
    5532  407.57  5549.5   407.1    5555  408.29    5578  408.12  5643.7  411.22
#Mann= 7 ,-1 , 0
  4534.2      .1       0  4730.8     .05       0  5023.2     .03       0
  5027.6     .05       0    5116     .16       0  5201.5     .05       0
  5320.8     .16       0
Bank Sta=5023.2,5027.6
XS Rating Curve= 0 ,0
Exp/Cntr=0.3,0.1

Type RM Length L Ch R = 1 ,10342   ,525,525,525
BEGIN DESCRIPTION:
DUCK CREEK TRIB 25 19 1
END DESCRIPTION:
XS GIS Cut Line= 3
      3512966.73     10409711.29      3513359.12     10409730.39
       3513738.2     10409493.24
#Sta/Elev= 30
  4504.6  400.52  4640.1  391.38  4750.3  386.84  4822.8     385  4934.7  381.79
  4957.6  380.75  4971.7   378.5  4984.7  374.96  4997.8  373.25  4998.1  372.75
  5001.9  372.75  5002.2  373.25  5046.1  374.43  5057.8  375.28    5079  379.05
  5094.3  380.11  5136.9  380.91  5165.6  382.69  5182.8  384.15  5188.7  384.02
    5204  387.88  5209.9  387.66  5219.3  390.79  5225.2  391.25  5231.2  394.28
  5240.5  396.08  5261.8  397.78  5267.7  397.49  5290.2  398.97  5344.6  400.16
#Mann= 7 ,-1 , 0
  4504.6     .05       0  4822.8     .16       0  4934.7     .05       0
  4997.8     .03       0  5002.2     .05       0  5046.1     .16       0
  5165.6      .1       0
Bank Sta=4997.8,5002.2
XS Rating Curve= 0 ,0
Exp/Cntr=0.3,0.1

Type RM Length L Ch R = 1 ,9817    ,653,653,653
BEGIN DESCRIPTION:
DUCK CREEK TRIB 25 19 0
END DESCRIPTION:
XS GIS Cut Line= 3
      3513353.95     10410211.28      3513605.65     10410155.73
      3513951.15     10409841.48
#Sta/Elev= 30
    4642  402.58  4652.5  401.89  4670.8  400.46  4701.6  395.05  4708.3  393.26
  4757.1  385.43    4763  382.97  4773.2  381.04  4783.5  380.02  4824.4  377.77
  4865.4  377.81  4897.7   378.6  4914.3  377.94  4942.6  374.37  4963.6  373.49
  4997.1  369.96  4997.4  369.46  5001.3  369.46  5001.6  369.96  5027.8  372.69
  5056.2  374.72  5062.9  377.53  5070.3  378.95  5133.9  380.51  5143.2  381.22
  5204.8  383.85    5240   386.8  5246.7  388.32  5300.2  393.58  5366.8  396.41
#Mann= 6 ,-1 , 0
    4642     .16       0  4652.5     .05       0  4997.1     .03       0
  5001.6     .05       0  5143.2     .16       0  5300.2      .1       0
Bank Sta=4997.1,5001.6
XS Rating Curve= 0 ,0
Exp/Cntr=0.3,0.1

Type RM Length L Ch R = 1 ,9164    ,841,841,841
BEGIN DESCRIPTION:
DUCK CREEK TRIB 25 18 0
END DESCRIPTION:
XS GIS Cut Line= 3
      3513688.99     10410730.38      3514072.66     10410555.04
       3514197.4     10410307.31
#Sta/Elev= 30
  4643.6  382.82  4744.7  379.12  4792.4  378.92    4810  378.55  4842.2  376.35
  4945.3  373.33  4985.9  368.32  4996.6   365.3  4996.9   364.8  5001.2   365.3
  5014.4  366.81  5020.8  369.58  5031.4  370.95  5042.9  372.86  5070.1     373
  5080.7     372  5097.4  373.64    5103  373.04  5119.7  374.11  5158.7  373.55
  5186.6   371.5    5209  370.96    5248  374.03  5270.3  377.67    5282  381.22
  5292.6  382.81  5298.2  385.08  5304.4  386.49  5332.6  388.84  5342.8  388.85
#Mann= 7 ,-1 , 0
  4643.6     .05       0  4792.4     .16       0    4810     .12       0
  4996.6     .07       0  5001.2     .12       0  5031.4     .16       0
  5332.6     .12       0
Bank Sta=4996.6,5001.2
XS Rating Curve= 0 ,0
Exp/Cntr=0.3,0.1

Type RM Length L Ch R = 1 ,8323    ,798,798,798
BEGIN DESCRIPTION:
DUCK CREEK TRIB 25 17 0
END DESCRIPTION:
XS GIS Cut Line= 2
      3514223.72     10411166.14      3514694.22     10410581.05
#Sta/Elev= 30
  4809.6  383.42  4832.8  382.03  4840.8  382.04  4882.4  379.38  4925.6  375.19
    4932  373.97  4961.9   372.3  4968.8  371.64  4975.2  368.26  4982.2  362.33
  4987.1  359.54  4987.4  359.04  4991.7  359.04  4992.1  359.54    5004  363.85
  5018.4  367.76  5032.8   370.2  5039.2  369.73  5053.6  370.73  5082.4  371.24
    5124  370.22  5160.7  370.88  5181.6  369.63  5202.4  369.13  5231.2  369.59
  5280.8  371.83  5344.8  376.01  5466.3  382.58  5511.6  385.64  5560.4  388.95
#Mann= 5 ,-1 , 0
  4809.6     .16       0  4961.9     .12       0  4987.1     .07       0
  4992.1     .12       0  5511.6     .16       0
Bank Sta=4987.1,4992.1
XS Rating Curve= 0 ,0
Exp/Cntr=0.3,0.1

Type RM Length L Ch R = 1 ,7525    ,627,627,627
BEGIN DESCRIPTION:
DUCK CREEK TRIB 25 16 0
END DESCRIPTION:
XS GIS Cut Line= 2
      3514591.79     10411702.57      3515176.75     10410896.08
#Sta/Elev= 30
  4502.2  386.62  4539.8  382.96  4603.1  378.16  4646.5  375.42  4832.8  368.92
    4883  367.63  4903.9  367.94  4918.6  367.21  4924.8  366.07  4939.5  366.83
    4948  368.35  4968.9  369.06  4983.6   367.4  4997.5  361.97  5001.9  358.54
  5002.3  358.04    5007  358.54  5019.1  363.61  5025.3  367.82  5033.8  369.13
    5084  368.77  5119.6  366.55  5155.2  367.98  5176.1  367.73  5211.8  369.33
  5297.4  377.29  5322.9  380.82  5391.8   380.6  5491.6  378.65  5498.5  379.24
#Mann= 6 ,-1 , 0
  4502.2     .16       0  4603.1     .12       0  5001.9     .07       0
    5007     .12       0  5211.8     .05       0  5322.9      .1       0
Bank Sta=5001.9,5007
XS Rating Curve= 0 ,0
Exp/Cntr=0.3,0.1

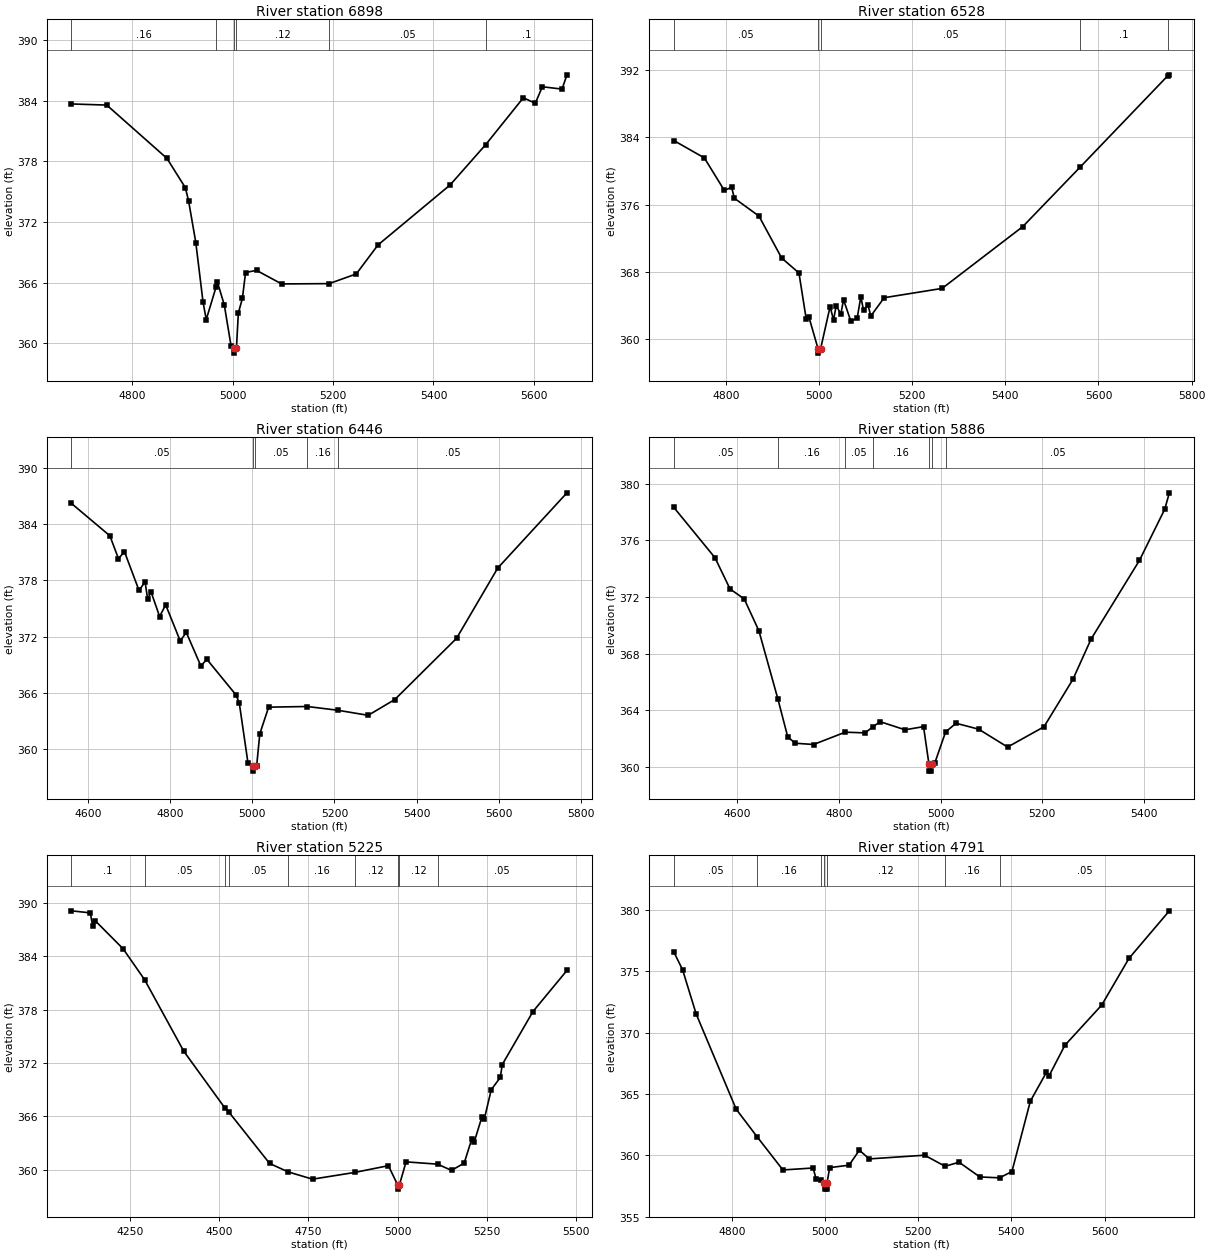
Type RM Length L Ch R = 1 ,6898    ,370,370,370
BEGIN DESCRIPTION:
DUCK CREEK TRIB 25 14 0
END DESCRIPTION:
XS GIS Cut Line= 3
      3515070.94     10411818.92      3515459.82     10411336.29
      3515600.33     10410996.28
#Sta/Elev= 30
  4678.4  383.66  4748.8  383.55  4868.8  378.28  4905.5  375.38  4911.9  374.08
  4926.3  369.96  4940.7  364.08  4947.1  362.35  4966.4  365.52  4969.5  366.03
  4983.1  363.79  4996.7   359.7    5002  359.53  5002.4  359.03  5007.3  359.53
  5011.1     363  5019.1  364.43  5025.5     367  5047.3  367.21  5097.4  365.87
  5192.1   365.9  5246.2  366.86  5289.4  369.72  5433.1  375.65  5504.3  379.65
  5579.1  384.27    5603  383.73    5617  385.36  5656.3  385.13  5666.1  386.54
#Mann= 6 ,-1 , 0
  4678.4     .16       0  4966.4     .12       0    5002     .07       0
  5007.3     .12       0  5192.1     .05       0  5504.3      .1       0
Bank Sta=5002,5007.3
XS Rating Curve= 0 ,0
Exp/Cntr=0.3,0.1

Type RM Length L Ch R = 1 ,6528    ,82,82,82
BEGIN DESCRIPTION:
DUCK CREEK TRIB 25 12 1
END DESCRIPTION:
XS GIS Cut Line= 3
      3515362.59     10411950.88       3515617.8     10411516.85
      3515916.42     10411042.88
#Sta/Elev= 30
  4688.4  383.63  4753.9  381.56  4796.8  377.68  4812.5  378.05  4818.3  376.75
  4871.1  374.62  4919.8  369.62    4957  367.83  4972.6  362.33  4978.4  362.57
  4998.1  358.77  4998.5  358.27  5003.4  358.77  5023.9  363.83  5031.2  362.22
    5037  363.95  5046.9  362.93  5052.7  364.64  5068.3  362.09  5081.9  362.42
  5089.8  364.99  5095.6   363.4  5105.1  364.01  5111.3   362.7  5139.9  364.88
  5264.3  365.99  5437.4  373.36  5560.6  380.46  5748.6  391.35  5752.1  391.47
#Mann= 5 ,-1 , 0
  4688.4     .05       0  4998.1     .03       0  5003.4     .05       0
  5560.6      .1       0  5748.6     .05       0
Bank Sta=4998.1,5003.4
XS Rating Curve= 0 ,0
Exp/Cntr=0.3,0.1

Type RM Length L Ch R = 1 ,6446    ,560,560,560
BEGIN DESCRIPTION:
DUCK CREEK TRIB 25 9 2
END DESCRIPTION:
XS GIS Cut Line= 2
      3515340.02     10412049.83      3516057.02     10411081.11
#Sta/Elev= 30
  4560.4  386.21  4653.9  382.76  4674.7  380.33  4689.4  381.06  4724.8  376.93
  4739.5  377.85  4745.7  376.02  4754.1  376.77  4774.9  374.15  4789.6   375.4
    4825  371.55  4839.7  372.46  4875.1  368.89  4889.8  369.59  4960.7  365.79
  4968.7  364.91  4989.9   358.5  5001.9  358.17  5002.3  357.67  5007.3  358.17
  5010.8  358.19  5018.5  361.64    5040  364.49  5133.9  364.56  5208.2  364.16
  5282.1  363.62  5346.8   365.3  5497.1  371.83  5597.3  379.32  5765.6  387.34
#Mann= 5 ,-1 , 0
  4560.4     .05       0  5001.9     .03       0  5007.3     .05       0
  5133.9     .16       0  5208.2     .05       0
Bank Sta=5001.9,5007.3
XS Rating Curve= 0 ,0
Exp/Cntr=0.3,0.1

Type RM Length L Ch R = 1 ,5886    ,661,661,661
BEGIN DESCRIPTION:
DUCK CREEK TRIB 25 8 2
END DESCRIPTION:
XS GIS Cut Line= 2
      3515822.65      10412105.4      3516377.64     10411304.13
#Sta/Elev= 30
  4475.4  378.33  4556.3  374.78    4586  372.57  4613.8  371.87  4642.7  369.62
  4680.2  364.79  4699.5  362.12  4714.4  361.68  4750.2  361.59  4812.6  362.46
  4851.5  362.41  4867.5  362.85  4881.2   363.2  4930.1  362.63  4966.6  362.85
  4977.2  360.21  4977.6  359.71  4982.1  359.71  4982.6  360.21  4988.7  360.28
    5010  362.48  5030.6  363.09  5075.1  362.67  5131.9  361.41  5203.5  362.84
  5260.3  366.18  5296.1  369.03  5391.3  374.59    5441   378.2  5450.1  379.36
#Mann= 7 ,-1 , 0
  4475.4     .05       0  4680.2     .16       0  4812.6     .05       0
  4867.5     .16       0  4977.2     .07       0  4982.6     .16       0
    5010     .05       0
Bank Sta=4977.2,4982.6
XS Rating Curve= 0 ,0
Exp/Cntr=0.3,0.1

Type RM Length L Ch R = 1 ,5225    ,434,434,434
BEGIN DESCRIPTION:
DUCK CREEK TRIB 25 9 0
END DESCRIPTION:
XS GIS Cut Line= 4
       3515859.6      10412553.6      3516456.81     10411914.73
      3516668.62     10411699.45      3516741.55      10411501.5
#Sta/Elev= 30
  4086.8  389.14  4139.6  388.91  4146.4   387.4  4153.7  388.01  4231.4  384.87
  4291.6  381.39  4401.4  373.33  4516.2  366.96  4527.1  366.51  4641.7   360.7
  4693.6  359.75  4761.9  358.93  4880.1  359.69  4974.3  360.45  4999.9  358.31
  5000.3  357.81  5005.3  358.31  5023.8  360.88    5112  360.62  5151.1  359.92
  5186.5  360.74  5207.7  363.44  5214.8  363.14  5235.9   365.9  5243.1  365.74
  5262.3     369  5287.8  370.39  5293.1  371.83  5379.1   377.8  5474.3  382.43
#Mann= 9 ,-1 , 0
  4086.8      .1       0  4291.6     .05       0  4516.2     .16       0
  4527.1     .05       0  4693.6     .16       0  4880.1     .12       0
  4999.9     .07       0  5005.3     .12       0    5112     .05       0
Bank Sta=4999.9,5005.3
XS Rating Curve= 0 ,0
Exp/Cntr=0.3,0.1

Type RM Length L Ch R = 1 ,4791    ,184,184,184
BEGIN DESCRIPTION:
DUCK CREEK TRIB 25 9 1
END DESCRIPTION:
XS GIS Cut Line= 4
      3516357.72     10412504.02      3516583.43     10412194.97
      3516666.76     10412110.77      3516816.07     10411568.21
#Sta/Elev= 30
  4675.3  376.56    4694  375.12  4723.4   371.5  4809.1  363.77  4854.9  361.48
  4909.5  358.82  4974.4  358.98  4980.5  358.12  4991.7  357.99  4998.7  357.76
  4999.1  357.26  5003.7  357.26  5004.2  357.76  5009.9  359.01  5051.6  359.21
  5073.6  360.43  5094.8  359.72  5213.7  360.02  5257.7  359.12  5287.6  359.45
  5332.4  358.25  5374.6  358.18  5401.2  358.69  5440.8  364.42  5475.2  366.76
  5480.4  366.44  5514.8  368.96    5594  372.24  5652.7  376.05  5739.2  379.91
#Mann= 7 ,-1 , 0
  4675.3     .05       0  4854.9     .16       0  4991.7     .12       0
  4998.7     .07       0  5004.2     .12       0  5257.7     .16       0
  5374.6     .05       0
Bank Sta=4998.7,5004.2
XS Rating Curve= 0 ,0
Exp/Cntr=0.3,0.1

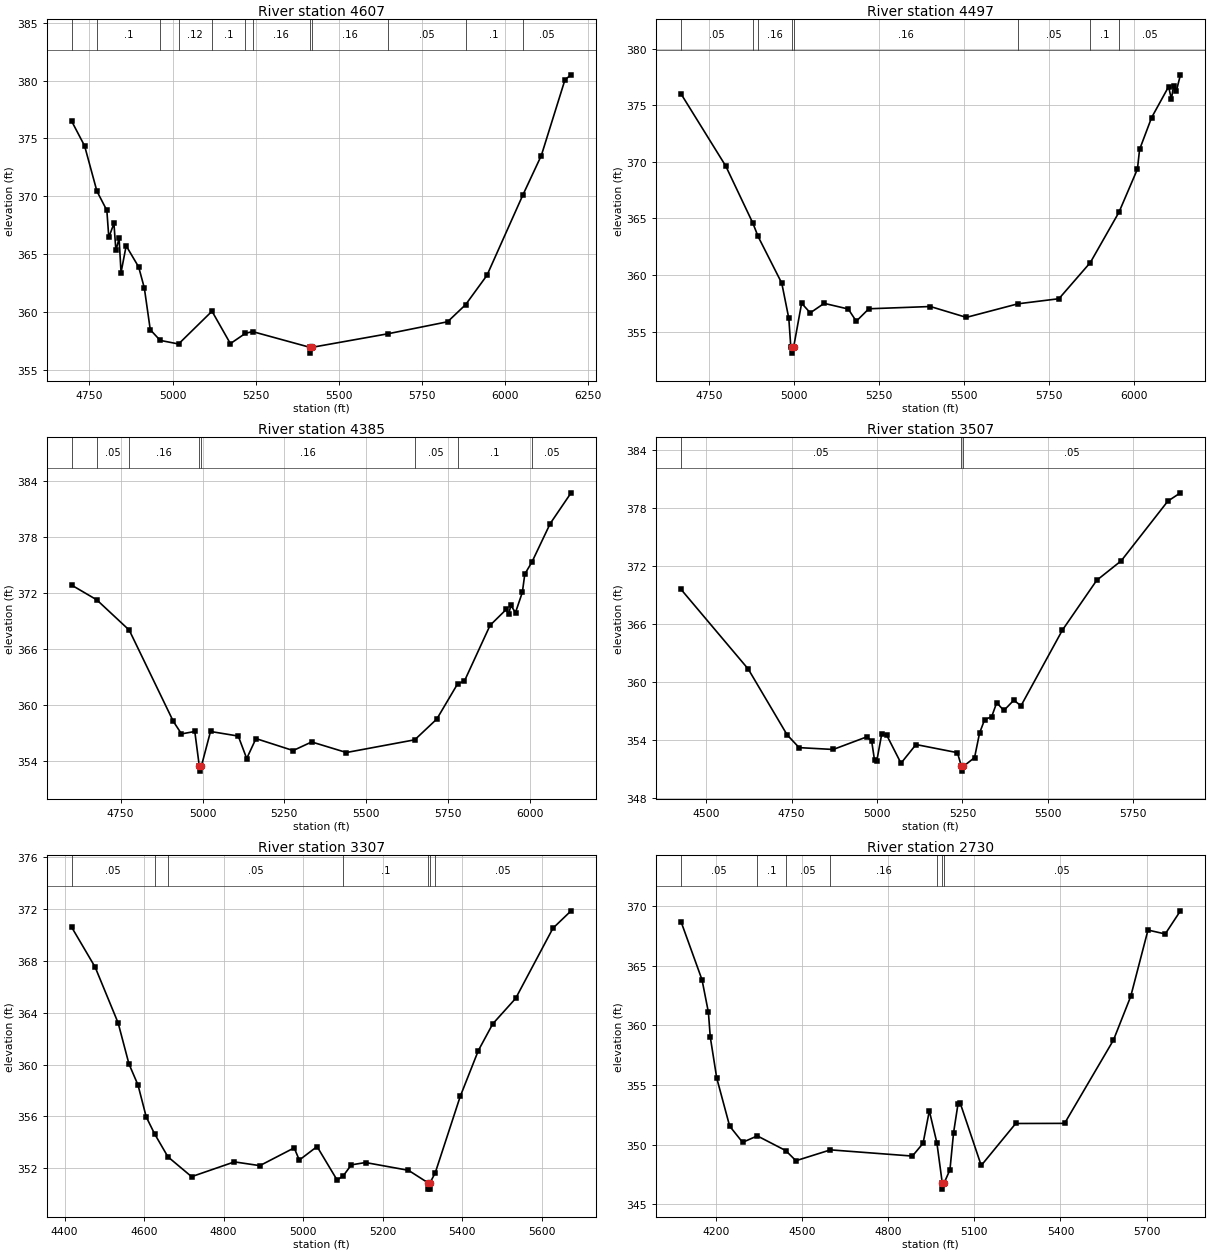
Type RM Length L Ch R = 1 ,4607    ,110,110,110
BEGIN DESCRIPTION:
DUCK CREEK TRIB 25 7 3
END DESCRIPTION:
XS GIS Cut Line= 4
       3516488.8       10412583.      3516641.59     10412490.11
      3516764.85     10412029.17      3517508.42     10411625.32
#Sta/Elev= 30
  4696.6   376.5  4735.6  374.36  4772.6  370.45  4802.5  368.79  4808.4  366.45
  4823.8  367.67  4829.7  365.33  4839.3  366.37  4845.2  363.42  4860.6  365.73
  4898.2   363.9  4915.2  362.09  4933.1  358.48  4962.9  357.56  5018.2  357.25
  5118.7  360.08    5174  357.28  5219.3  358.17  5240.7  358.32  5413.4  356.96
  5413.9  356.46  5419.3  356.96  5647.5  358.13  5827.4  359.17  5881.3  360.64
  5945.7  363.18  6053.5  370.11  6109.2  373.53  6180.4  380.08  6198.7   380.5
#Mann= 12 ,-1 , 0
  4696.6     .05       0  4772.6      .1       0  4962.9     .16       0
  5018.2     .12       0  5118.7      .1       0  5219.3     .12       0
  5240.7     .16       0  5413.4     .07       0  5419.3     .16       0
  5647.5     .05       0  5881.3      .1       0  6053.5     .05       0
Bank Sta=5413.4,5419.3
XS Rating Curve= 0 ,0
Exp/Cntr=0.3,0.1

Type RM Length L Ch R = 1 ,4497    ,112,112,112
BEGIN DESCRIPTION:
DUCK CREEK TRIB 25 8 1
END DESCRIPTION:
XS GIS Cut Line= 6
      3516623.86     10412740.08      3516734.55     10412514.36
      3516806.16     10412201.86      3516875.61     10412056.46
      3517235.21     10411871.31      3517500.59     10411672.36
#Sta/Elev= 30
  4667.2  376.01  4799.1  369.62  4878.9  364.57    4894  363.41  4963.9  359.27
  4984.6  356.16  4990.4  353.66  4992.7  353.59  4993.2  353.09  4998.6  353.59
  5022.3   357.5  5047.7  356.65  5088.6  357.49  5159.5  356.99  5183.2  355.91
  5220.2  357.01  5401.3  357.21  5507.2  356.25  5659.2  357.45  5779.8   357.9
  5872.3   361.1  5956.6  365.55  6010.9  369.36  6017.2  371.09  6052.6  373.91
  6102.6  376.64  6110.9  375.54  6117.2  376.71  6125.5  376.27  6137.5  377.69
#Mann= 8 ,-1 , 0
  4667.2     .05       0  4878.9      .1       0    4894     .16       0
  4992.7     .07       0  4998.6     .16       0  5659.2     .05       0
  5872.3      .1       0  5956.6     .05       0
Bank Sta=4992.7,4998.6
XS Rating Curve= 0 ,0
Exp/Cntr=0.3,0.1

Type RM Length L Ch R = 1 ,4385    ,878,878,878
BEGIN DESCRIPTION:
DUCK CREEK TRIB 25 7 2
END DESCRIPTION:
XS GIS Cut Line= 4
       3516821.4     10412826.18      3516887.37     10412496.33
      3516842.23     10412333.13      3517592.07     10411641.67
#Sta/Elev= 30
  4600.2  372.86  4676.8  371.29  4776.1  368.05  4910.8  358.29  4935.8  356.95
  4976.4  357.21  4990.3  353.47  4990.8  352.97  4996.3  353.47  5024.4  357.21
  5109.2  356.72    5135  354.32  5163.3  356.45  5276.8  355.17  5333.5  356.09
  5439.5  354.96  5648.4  356.32  5715.7  358.54  5779.2   362.3  5800.2  362.61
  5878.4  368.56  5927.8  370.26  5935.1  369.72  5941.9  370.69  5956.1  369.93
  5977.1   372.1  5984.5  374.04  6006.3  375.33  6062.1  379.44  6125.9  382.73
#Mann= 8 ,-1 , 0
  4600.2      .1       0  4676.8     .05       0  4776.1     .16       0
  4990.3     .07       0  4996.3     .16       0  5648.4     .05       0
  5779.2      .1       0  6006.3     .05       0
Bank Sta=4990.3,4996.3
XS Rating Curve= 0 ,0
Exp/Cntr=0.3,0.1

Type RM Length L Ch R = 1 ,3507    ,200,200,200
BEGIN DESCRIPTION:
DUCK CREEK TRIB 25 7 1
END DESCRIPTION:
XS GIS Cut Line= 3
      3517144.19     10413131.92      3517544.19     10412781.92
      3518094.22     10412031.88
#Sta/Elev= 30
  4426.4  369.56  4623.1  361.32    4737  354.51  4772.1  353.19  4871.8     353
  4970.6  354.31  4984.5  353.84  4992.9  351.86  4999.2  351.79  5013.8  354.59
  5028.5  354.47  5070.2  351.58  5114.1  353.51  5235.3  352.67    5247  351.26
  5247.5  350.76    5253  351.26  5285.5  352.16  5300.1  354.69  5314.8  356.07
  5335.7   356.4  5350.3  357.84  5371.2  357.03  5400.5   358.1  5421.3  357.51
  5542.5  365.34  5642.9  370.49  5714.7  372.51  5851.1  378.68    5888  379.54
#Mann= 3 ,-1 , 0
  4426.4     .05       0    5247     .03       0    5253     .05       0
Bank Sta=5247,5253
XS Rating Curve= 0 ,0
Exp/Cntr=0.3,0.1

Type RM Length L Ch R = 1 ,3307    ,577,577,577
BEGIN DESCRIPTION:
Mapping XS 7f3a49f8
END DESCRIPTION:
XS GIS Cut Line= 3
      3517382.48     10413295.35       3517714.5     10412867.85
      3518100.77     10412266.75
#Sta/Elev= 30
  4417.7  370.59  4476.8  367.51  4534.7   363.2  4561.8  360.05  4584.5  358.43
  4605.3  355.96  4626.3  354.66  4659.8  352.89  4719.3  351.36    4827   352.5
  4890.9  352.21  4977.3  353.58  4990.1  352.64  5034.8  353.68  5085.2   351.1
  5100.8  351.43  5120.9  352.27  5156.6  352.45  5264.6  351.85  5313.1   350.9
  5313.6   350.4  5318.6   350.4  5319.1   350.9  5332.1  351.67  5394.7  357.54
  5440.3  361.08  5476.6  363.14  5534.1   365.1  5627.9  370.51  5673.5  371.85
#Mann= 7 ,-1 , 0
  4417.7     .05       0  4626.3      .1       0  4659.8     .05       0
  5100.8      .1       0  5313.1     .03       0  5319.1      .1       0
  5332.1     .05       0
Bank Sta=5313.1,5319.1
XS Rating Curve= 0 ,0
Exp/Cntr=0.3,0.1

Type RM Length L Ch R = 1 ,2730    ,674,674,674
BEGIN DESCRIPTION:
DUCK CREEK TRIB 25 35 0
END DESCRIPTION:
XS GIS Cut Line= 4
      3517446.37     10413381.76      3518199.87     10413013.69
       3518283.2     10412885.21      3518251.95     10412138.69
#Sta/Elev= 30
  4078.8   368.7    4152  363.82  4174.2   361.1  4180.7  359.03  4203.2  355.59
  4248.2  351.56  4293.3   350.2  4344.5  350.74  4443.4  349.51    4479  348.66
  4599.2  349.57  4884.4  349.05  4921.6  350.12  4943.4  352.84  4969.7  350.16
  4988.5  346.78    4989  346.28  4994.6  346.78  5015.2   347.9  5027.8  351.01
    5043  353.38  5050.9  353.49  5124.1  348.26  5244.2  351.78  5414.4  351.79
  5584.5  358.77  5644.6  362.43  5704.7  367.99  5764.7  367.66  5817.7   369.6
#Mann= 7 ,-1 , 0
  4078.8     .05       0  4344.5      .1       0  4443.4     .05       0
  4599.2     .16       0  4969.7     .05       0  4988.5     .03       0
  4994.6     .05       0
Bank Sta=4988.5,4994.6
XS Rating Curve= 0 ,0
Exp/Cntr=0.3,0.1