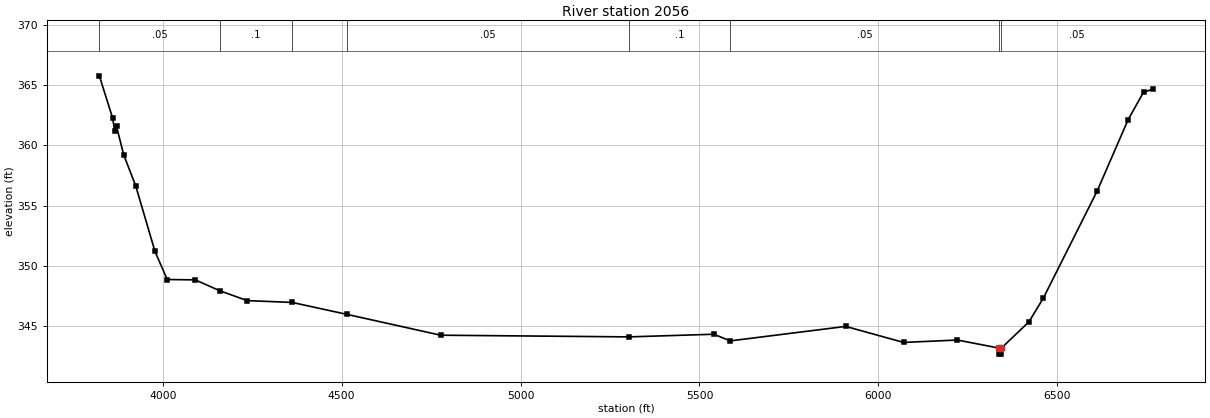
HEC-RAS study DUCK CREEK TRIB 25.prj: DUCK CREEK TRIB 25 Base Level Engineering

--- DUCK CREEK TRIB 25.g01 (geometry) --- (continued)

Type RM Length L Ch R = 1 ,2056    ,0,0,0
BEGIN DESCRIPTION:
DUCK CREEK TRIB 25 12 0
END DESCRIPTION:
XS GIS Cut Line= 4
      3517545.38     10413604.31      3518592.23     10413416.81
      3518831.81     10413172.02      3518753.71     10411636.13
#Sta/Elev= 30
  3822.9  365.76  3860.2  362.24  3865.8  361.17  3870.9  361.57  3890.7  359.23
  3924.7  356.62  3978.4  351.19  4012.6  348.86    4091  348.83  4159.3  347.93
  4236.1  347.11  4361.6  346.96  4514.6  345.97  4776.8  344.24  5302.8   344.1
  5539.7  344.32  5586.4  343.77  5908.8  344.97  6070.4  343.64  6220.6  343.84
  6337.7  343.17  6338.2  342.67  6343.3  342.67  6343.8  343.17  6420.8  345.35
  6460.9  347.31  6611.1  356.18  6698.1  362.13  6741.3  364.42  6766.8  364.64
#Mann= 8 ,-1 , 0
  3822.9     .05       0  4159.3      .1       0  4361.6     .16       0
  4514.6     .05       0  5302.8      .1       0  5586.4     .05       0
  6337.7     .03       0  6343.8     .05       0
Bank Sta=6337.7,6343.8
XS Rating Curve= 0 ,0
Exp/Cntr=0.3,0.1

Chan Stop Cuts=-1
Use User Specified Reach Order=0
Composite Channel Slope=5