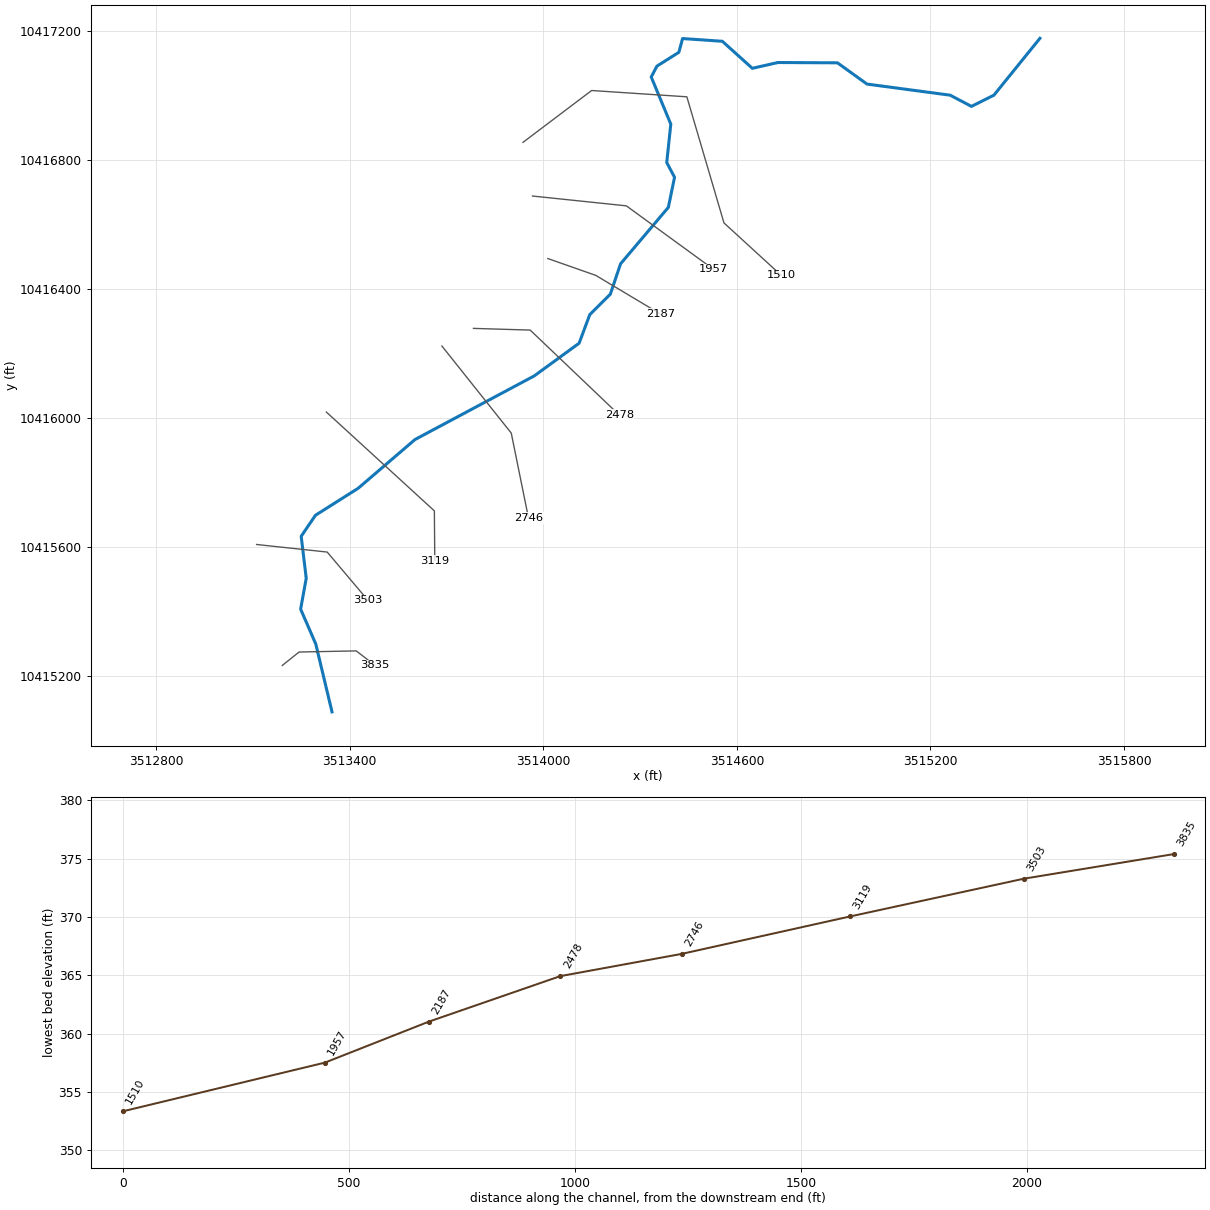
--- DUCK CREEK TRIB 26.prj (project) ---

Proj Title=DUCK CREEK TRIB 26 Base Level Engineering
Current Plan=p01
Default Exp/Contr=0.3,0.1
English Units
Geom File=g01
Flow File=f01
Plan File=p01
Y Axis Title=Elevation
X Axis Title(PF)=Main Channel Distance
X Axis Title(XS)=Station
BEGIN DESCRIPTION:
DUCK CREEK TRIB 26
END DESCRIPTION:
DSS Export Rating Curves= 0
DSS Export Rating Curve Sorted= 0
DSS Export Volume Flow Curves= 0
DXF OffsetX= 0
DXF OffsetY= 0
DXF ScaleX= 1
DXF ScaleY= 10

--- DUCK CREEK TRIB 26.p01 (plan) ---

Plan Title=Multiple Run
Short Identifier=Multiple
Geom File=g01
Flow File=f01
Subcritical Flow
K Sum by GR= 0
Std Step Tol= 0.01
Critical Tol= 0.01
Num of Std Step Trials= 20
Max Error Tol= 0.3
Flow Tol Ratio= 0.001
Split Flow NTrial= 30
Split Flow Tol= 0.02
Split Flow Ratio= 0.02
Log Output Level= 0
Friction Slope Method= 1
Unsteady Friction Slope Method= 2
Unsteady Bridges Friction Slope Method= 1
Parabolic Critical Depth
Global Vel Dist=  1 , 1 , 1
Global Log Level= 0
CheckData=True
Encroach Param= -1, 0, 0, 0
BEGIN DESCRIPTION:
Multiple Run
END DESCRIPTION:

--- DUCK CREEK TRIB 26.f01 (steady flow) ---

Flow Title=Multiple
Program Version=4.10
Number of Profiles= 7
Profile Names=10-year,25-year,50-year,1pct_min,100-year,1pct_plu,500-year
River Rch & RM=DUCK CREEK TRIB,Reach-1         ,3835
     445     586     698     609     824    1114    1142
Boundary for River Rch & Prof#=DUCK CREEK TRIB,Reach-1         , 1
Up Type= 0
Dn Type= 3
Dn Slope=0.005
Boundary for River Rch & Prof#=DUCK CREEK TRIB,Reach-1         , 2
Up Type= 0
Dn Type= 3
Dn Slope=0.005
Boundary for River Rch & Prof#=DUCK CREEK TRIB,Reach-1         , 3
Up Type= 0
Dn Type= 3
Dn Slope=0.005
Boundary for River Rch & Prof#=DUCK CREEK TRIB,Reach-1         , 4
Up Type= 0
Dn Type= 3
Dn Slope=0.005
Boundary for River Rch & Prof#=DUCK CREEK TRIB,Reach-1         , 5
Up Type= 0
Dn Type= 3
Dn Slope=0.005
Boundary for River Rch & Prof#=DUCK CREEK TRIB,Reach-1         , 6
Up Type= 0
Dn Type= 3
Dn Slope=0.005
Boundary for River Rch & Prof#=DUCK CREEK TRIB,Reach-1         , 7
Up Type= 0
Dn Type= 3
Dn Slope=0.005
DSS Import GetInterval= 0
DSS Import GetPeak= 0
DSS Import FillOption= 0

--- DUCK CREEK TRIB 26.g01 (geometry) ---

Geom Title=Existing Conditions
Program Version=4.10

River Reach=DUCK CREEK TRIB ,Reach-1
Reach XY= 30
      3513345.45     10415090.36       3513295.1     10415300.86
      3513248.23      10415408.5      3513265.59     10415503.99
      3513249.97      10415634.2      3513294.24      10415699.3
      3513426.18     10415782.63       3513602.4     10415933.68
      3513972.24     10416130.94      3514111.18      10416232.1
      3514144.37     10416320.86      3514207.96     10416384.08
      3514239.64     10416478.01      3514387.81     10416653.03
       3514406.9     10416746.13      3514382.73     10416791.77
      3514395.29     10416910.62      3514334.68      10417056.6
      3514352.22     10417090.15      3514420.25     10417133.06
      3514431.85     10417175.72      3514555.02     10417167.24
      3514647.95     10417083.51       3514727.1     10417101.42
      3514911.64     10417100.53      3515003.37      10417034.7
      3515261.23     10417000.23      3515326.94     10416965.62
      3515396.58     10417000.34      3515539.26     10417176.57

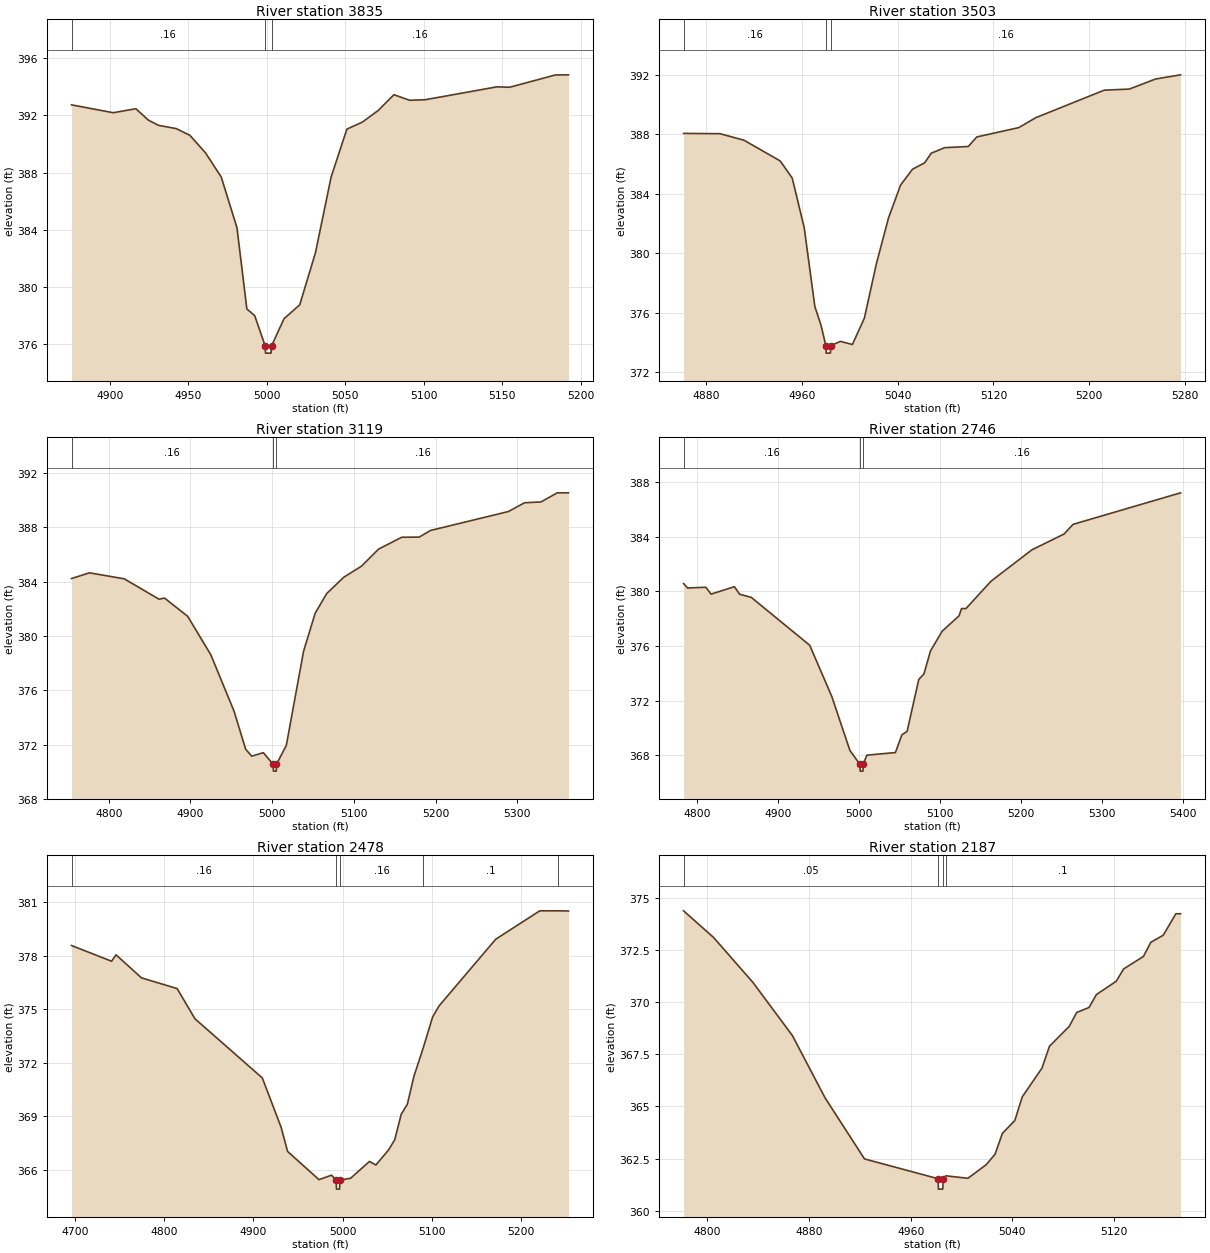
Type RM Length L Ch R = 1 ,3835    ,332,332,332
BEGIN DESCRIPTION:
DUCK CREEK TRIB 26 20
END DESCRIPTION:
XS GIS Cut Line= 4
      3513191.32      10415234.1      3513243.37     10415275.73
      3513420.45     10415279.21      3513478.31     10415234.96
#Sta/Elev= 30
  4875.7  392.74  4902.3  392.19  4916.7  392.47  4924.7  391.67  4931.1  391.31
  4942.4  391.08  4951.1  390.61  4961.1  389.38  4971.1  387.69  4981.1  384.15
  4987.4  378.47  4992.4     378  4999.1  375.88  4999.3  375.38  5002.8  375.38
  5003.1  375.88  5011.1  377.79  5021.1  378.76  5031.1   382.4  5041.1   387.7
  5051.1  391.04  5061.1  391.54  5071.1  392.35  5081.1  393.45  5091.1  393.06
  5101.1   393.1  5146.7     394  5154.8  393.97  5183.9  394.83  5192.3  394.84
#Mann= 3 ,-1 , 0
  4875.7     .16       0  4999.1     .07       0  5003.1     .16       0
Bank Sta=4999.1,5003.1
XS Rating Curve= 0 ,0
Exp/Cntr=0.3,0.1

Type RM Length L Ch R = 1 ,3503    ,384,384,384
BEGIN DESCRIPTION:
DUCK CREEK TRIB 26 20
END DESCRIPTION:
XS GIS Cut Line= 3
      3513111.86     10415608.75      3513330.61     10415585.31
      3513456.64     10415436.13
#Sta/Elev= 30
  4861.1  388.05  4891.5  388.03  4911.6  387.59  4941.8   386.2  4951.9  385.04
  4961.9  381.71  4970.8   376.4  4975.9  375.16    4980  373.77  4980.3  373.27
  4983.8  373.27    4984  373.77  4992.1  374.06  5002.2  373.85  5012.2  375.63
  5022.3  379.31  5032.3  382.35  5042.4  384.57  5052.4  385.64  5062.5  386.07
  5068.1  386.72  5079.3  387.09    5099  387.17  5106.1  387.81  5141.2  388.44
  5155.5  389.11  5212.7  390.96  5233.5  391.03  5255.6  391.71  5276.4  391.99
#Mann= 3 ,-1 , 0
  4861.1     .16       0    4980     .07       0    4984     .16       0
Bank Sta=4980,4984
XS Rating Curve= 0 ,0
Exp/Cntr=0.3,0.1

Type RM Length L Ch R = 1 ,3119    ,373,373,373
BEGIN DESCRIPTION:
Mapping XS b7abe7eb
END DESCRIPTION:
XS GIS Cut Line= 3
      3513328.03     10416018.88      3513662.64     10415712.91
      3513663.95     10415557.93
#Sta/Elev= 30
  4754.4  384.22  4776.4  384.64  4818.9   384.2  4861.5   382.7  4868.3  382.78
  4896.6  381.44    4925   378.6  4953.4  374.45  4967.6  371.65    4975  371.14
  4989.2   371.4  5001.3  370.54  5001.6  370.04  5005.1  370.04  5005.3  370.54
  5017.4  371.94  5038.5  378.87  5052.7  381.67  5066.9  383.12  5087.8  384.32
  5109.4  385.13  5130.4  386.39  5158.7  387.26    5180  387.27  5193.9  387.76
  5289.1  389.15  5309.1   389.8  5329.1  389.86  5349.1  390.53  5362.8  390.53
#Mann= 3 ,-1 , 0
  4754.4     .16       0  5001.3     .07       0  5005.3     .16       0
Bank Sta=5001.3,5005.3
XS Rating Curve= 0 ,0
Exp/Cntr=0.3,0.1

Type RM Length L Ch R = 1 ,2746    ,268,268,268
BEGIN DESCRIPTION:
DUCK CREEK TRIB 26 10
END DESCRIPTION:
XS GIS Cut Line= 3
      3513686.11     10416223.29      3513900.93      10415953.8
      3513954.31     10415690.79
#Sta/Elev= 30
  4783.7  380.57  4788.7  380.25  4811.2   380.3  4817.6   379.8  4846.4  380.34
  4852.8  379.79  4867.2  379.56  4939.3  376.05  4966.5   372.3  4988.9  368.34
  5001.2  367.33  5001.5  366.83    5005  366.83  5005.2  367.33  5009.8     368
    5045  368.19    5053  369.49  5059.4  369.74  5073.8  373.55  5080.2  373.95
  5088.2  375.63  5102.6  377.08  5123.5  378.21  5126.5  378.74    5132  378.74
  5162.8  380.74  5213.5  383.05    5253   384.2  5264.1  384.91  5396.7  387.22
#Mann= 3 ,-1 , 0
  4783.7     .16       0  5001.2     .07       0  5005.2     .16       0
Bank Sta=5001.2,5005.2
XS Rating Curve= 0 ,0
Exp/Cntr=0.3,0.1

Type RM Length L Ch R = 1 ,2478    ,291,291,291
BEGIN DESCRIPTION:
Mapping XS 1239d17e
END DESCRIPTION:
XS GIS Cut Line= 3
      3513783.76     10416278.02      3513959.52     10416272.81
      3514235.54     10416009.81
#Sta/Elev= 30
  4696.1  378.56    4741  377.68    4746  378.04  4774.5  376.75  4814.5  376.15
  4834.5  374.46    4910  371.15    4931   368.4  4938.3  367.04  4973.5  365.46
  4987.6  365.71  4992.9  365.43  4993.1  364.93  4996.6  364.93  4996.9  365.43
    5009  365.54  5030.1  366.48  5037.3  366.28  5051.5  367.12  5058.4  367.69
  5065.7  369.12  5072.6  369.68  5079.8  371.22  5090.6  372.87  5100.9  374.56
  5108.1  375.18  5171.6  378.91    5221   380.5  5241.9   380.5  5253.2  380.49
#Mann= 5 ,-1 , 0
  4696.1     .16       0  4992.9     .07       0  4996.9     .16       0
  5090.6      .1       0  5241.9     .05       0
Bank Sta=4992.9,4996.9
XS Rating Curve= 0 ,0
Exp/Cntr=0.3,0.1

Type RM Length L Ch R = 1 ,2187    ,230,230,230
BEGIN DESCRIPTION:
DUCK CREEK TRIB 26 6 0
END DESCRIPTION:
XS GIS Cut Line= 3
      3514014.42     10416494.29      3514162.83     10416442.22
      3514363.39      10416322.4
#Sta/Elev= 30
  4781.4  374.39    4805  373.11    4836  370.95    4867   368.4  4892.7  365.41
  4923.7  362.48  4981.6  361.53  4981.8  361.03  4985.3  361.03  4985.6  361.53
  4987.7  361.67    5005  361.55  5019.4   362.2  5026.4  362.71  5032.2  363.71
  5041.9  364.32  5047.8  365.46  5063.3  366.84  5069.2  367.89  5084.7  368.84
  5090.6  369.51  5100.3  369.75  5106.1  370.37  5121.7  371.01  5127.5   371.6
  5143.1   372.2  5148.9  372.88  5158.7  373.22  5168.6  374.25  5172.3  374.25
#Mann= 4 ,-1 , 0
  4781.4     .05       0  4981.6     .07       0  4985.6     .05       0
  4987.7      .1       0
Bank Sta=4981.6,4985.6
XS Rating Curve= 0 ,0
Exp/Cntr=0.3,0.1

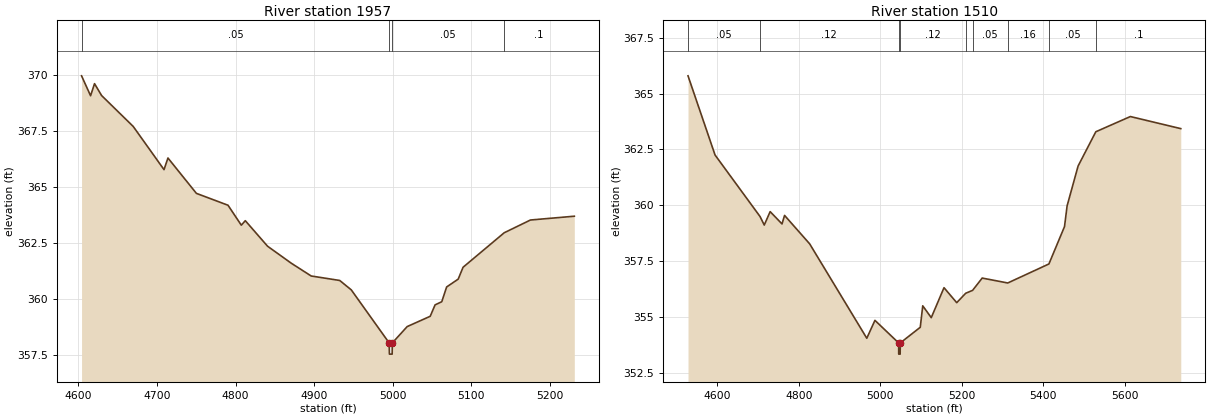
Type RM Length L Ch R = 1 ,1957    ,447,447,447
BEGIN DESCRIPTION:
DUCK CREEK TRIB 26 6 2
END DESCRIPTION:
XS GIS Cut Line= 3
      3513966.77     10416687.95      3514257.56     10416657.57
      3514527.93     10416460.74
#Sta/Elev= 30
  4604.1  369.95  4615.6  369.06  4620.6   369.6  4629.6  369.07  4669.8  367.69
    4709  365.76    4714  366.28  4750.2   364.7  4790.4  364.17  4807.3  363.28
  4812.4  363.48  4840.7  362.34  4870.9  361.58  4896.2  361.01  4932.5  360.81
  4947.2  360.39  4995.4  358.02  4995.7  357.52  4999.2  357.52  4999.4  358.02
  5018.3  358.75  5047.6  359.21  5053.8  359.72  5062.3  359.86  5068.5  360.52
  5083.2  360.87  5089.4   361.4  5141.7  362.94  5175.1  363.51  5230.9  363.68
#Mann= 4 ,-1 , 0
  4604.1     .05       0  4995.4    .035       0  4999.4     .05       0
  5141.7      .1       0
Bank Sta=4995.4,4999.4
XS Rating Curve= 0 ,0
Exp/Cntr=0.3,0.1

Type RM Length L Ch R = 1 ,1510    ,0,0,0
BEGIN DESCRIPTION:
DUCK CREEK TRIB 26 6 1
END DESCRIPTION:
XS GIS Cut Line= 5
       3513937.3     10416854.21      3514149.95     10417014.78
      3514445.09     10416995.25      3514560.11     10416604.62
       3514737.6     10416442.28
#Sta/Elev= 30
  4527.7  365.79  4594.1  362.25  4704.6   359.5  4714.9  359.12  4729.4  359.72
  4758.5  359.17  4764.8  359.55  4826.4  358.28  4966.7  354.06  4986.7  354.86
  5044.9  353.85  5045.1  353.35  5048.6  353.35  5048.9  353.85    5098  354.55
  5104.1  355.51    5125  354.98  5156.3  356.32  5187.5  355.65  5209.5  356.07
  5226.5   356.2  5250.1  356.75  5312.8  356.53  5413.9  357.38  5452.2  359.05
  5458.6  359.98  5485.6  361.76  5529.1  363.29  5613.9  363.97  5737.7  363.43
#Mann= 9 ,-1 , 0
  4527.7     .05       0  4704.6     .12       0  5044.9     .07       0
  5048.9     .12       0  5209.5     .16       0  5226.5     .05       0
  5312.8     .16       0  5413.9     .05       0  5529.1      .1       0
Bank Sta=5044.9,5048.9
XS Rating Curve= 0 ,0
Exp/Cntr=0.3,0.1

Chan Stop Cuts=-1
Use User Specified Reach Order=0
Composite Channel Slope=5