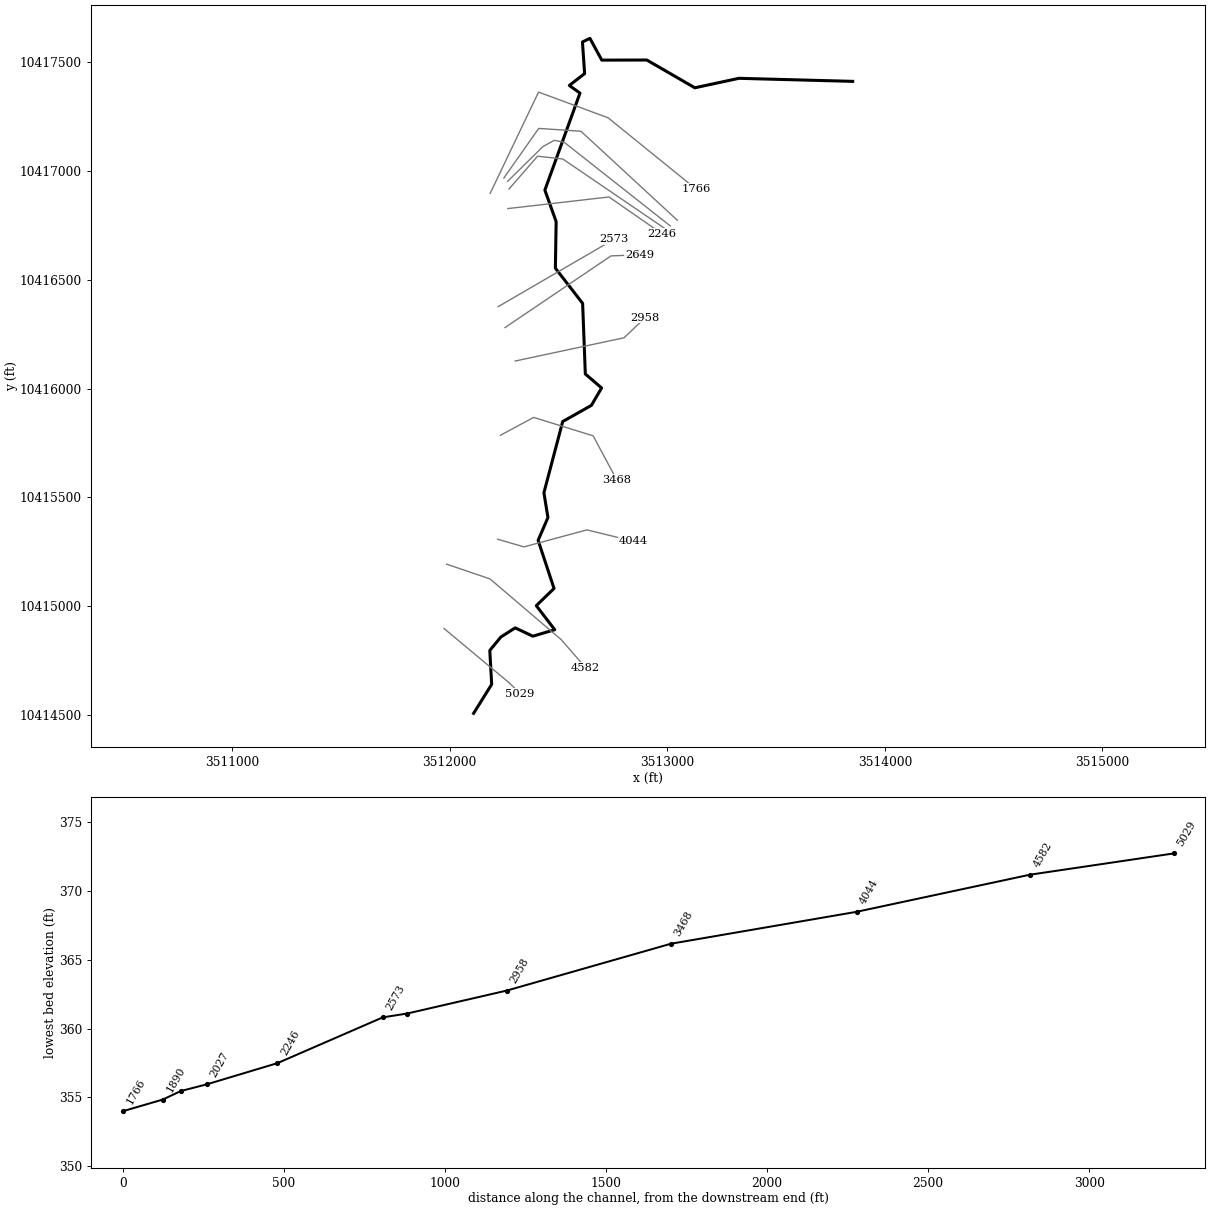
--- DUCK CREEK TRIB 27.prj (project) ---

Proj Title=DUCK CREEK TRIB 27 Base Level Engineering
Current Plan=p01
Default Exp/Contr=0.3,0.1
English Units
Geom File=g01
Flow File=f01
Plan File=p01
BEGIN DESCRIPTION:
DUCK CREEK TRIB 27
END DESCRIPTION:

--- DUCK CREEK TRIB 27.p01 (plan) ---

Plan Title=Multiple Run
Short Identifier=Multiple
Geom File=g01
Flow File=f01
Subcritical Flow
K Sum by GR= 0
Std Step Tol= 0.01
Critical Tol= 0.01
Num of Std Step Trials= 20
Max Error Tol= 0.3
Flow Tol Ratio= 0.001
Split Flow NTrial= 30
Split Flow Tol= 0.02
Split Flow Ratio= 0.02
Log Output Level= 0
Friction Slope Method= 1
Unsteady Friction Slope Method= 2
Unsteady Bridges Friction Slope Method= 1
Parabolic Critical Depth
Global Vel Dist=  1 , 1 , 1
Global Log Level= 0
CheckData=True
Encroach Param= -1, 0, 0, 0
BEGIN DESCRIPTION:
Multiple Run
END DESCRIPTION:

--- DUCK CREEK TRIB 27.f01 (steady flow) ---

Flow Title=Multiple
Number of Profiles=7
Profile Names=10-year,25-year,50-year,1pct_min,100-year,1pct_plu,500-year
River Rch & RM= DUCK CREEK TRIB ,Reach-1,5029
     637     858    1037     917    1240    1676    1764
Boundary for River Rch & Prof#=DUCK CREEK TRIB ,Reach-1,1
Up Type=0
Dn Type=3
Dn Slope=0.005
Boundary for River Rch & Prof#=DUCK CREEK TRIB ,Reach-1,2
Up Type=0
Dn Type=3
Dn Slope=0.005
Boundary for River Rch & Prof#=DUCK CREEK TRIB ,Reach-1,3
Up Type=0
Dn Type=3
Dn Slope=0.005
Boundary for River Rch & Prof#=DUCK CREEK TRIB ,Reach-1,4
Up Type=0
Dn Type=3
Dn Slope=0.005
Boundary for River Rch & Prof#=DUCK CREEK TRIB ,Reach-1,5
Up Type=0
Dn Type=3
Dn Slope=0.005
Boundary for River Rch & Prof#=DUCK CREEK TRIB ,Reach-1,6
Up Type=0
Dn Type=3
Dn Slope=0.005
Boundary for River Rch & Prof#=DUCK CREEK TRIB ,Reach-1,7
Up Type=0
Dn Type=3
Dn Slope=0.005

--- DUCK CREEK TRIB 27.g01 (geometry) ---

Geom Title=Existing Conditions

River Reach=DUCK CREEK TRIB ,Reach-1
Reach XY= 30
      3512109.93     10414507.10      3512193.05     10414640.41
      3512184.42     10414796.36      3512235.44     10414858.20
      3512301.21     10414900.13      3512382.22     10414861.79
      3512482.86     10414891.61      3512398.05     10415002.11
      3512479.67     10415081.18      3512406.48     10415302.36
      3512451.60     10415406.98      3512433.12     10415521.04
      3512519.49     10415848.26      3512651.35     10415922.59
      3512698.23     10416002.66      3512623.46     10416066.91
      3512611.03     10416391.36      3512485.81     10416553.18
      3512489.34     10416767.10      3512437.50     10416911.91
      3512598.89     10417357.60      3512549.89     10417392.80
      3512620.23     10417447.40      3512610.19     10417592.60
      3512644.56     10417609.38      3512699.00     10417509.28
      3512906.08     10417509.73      3513126.62     10417382.08
      3513329.41     10417425.66      3513852.11     10417411.64

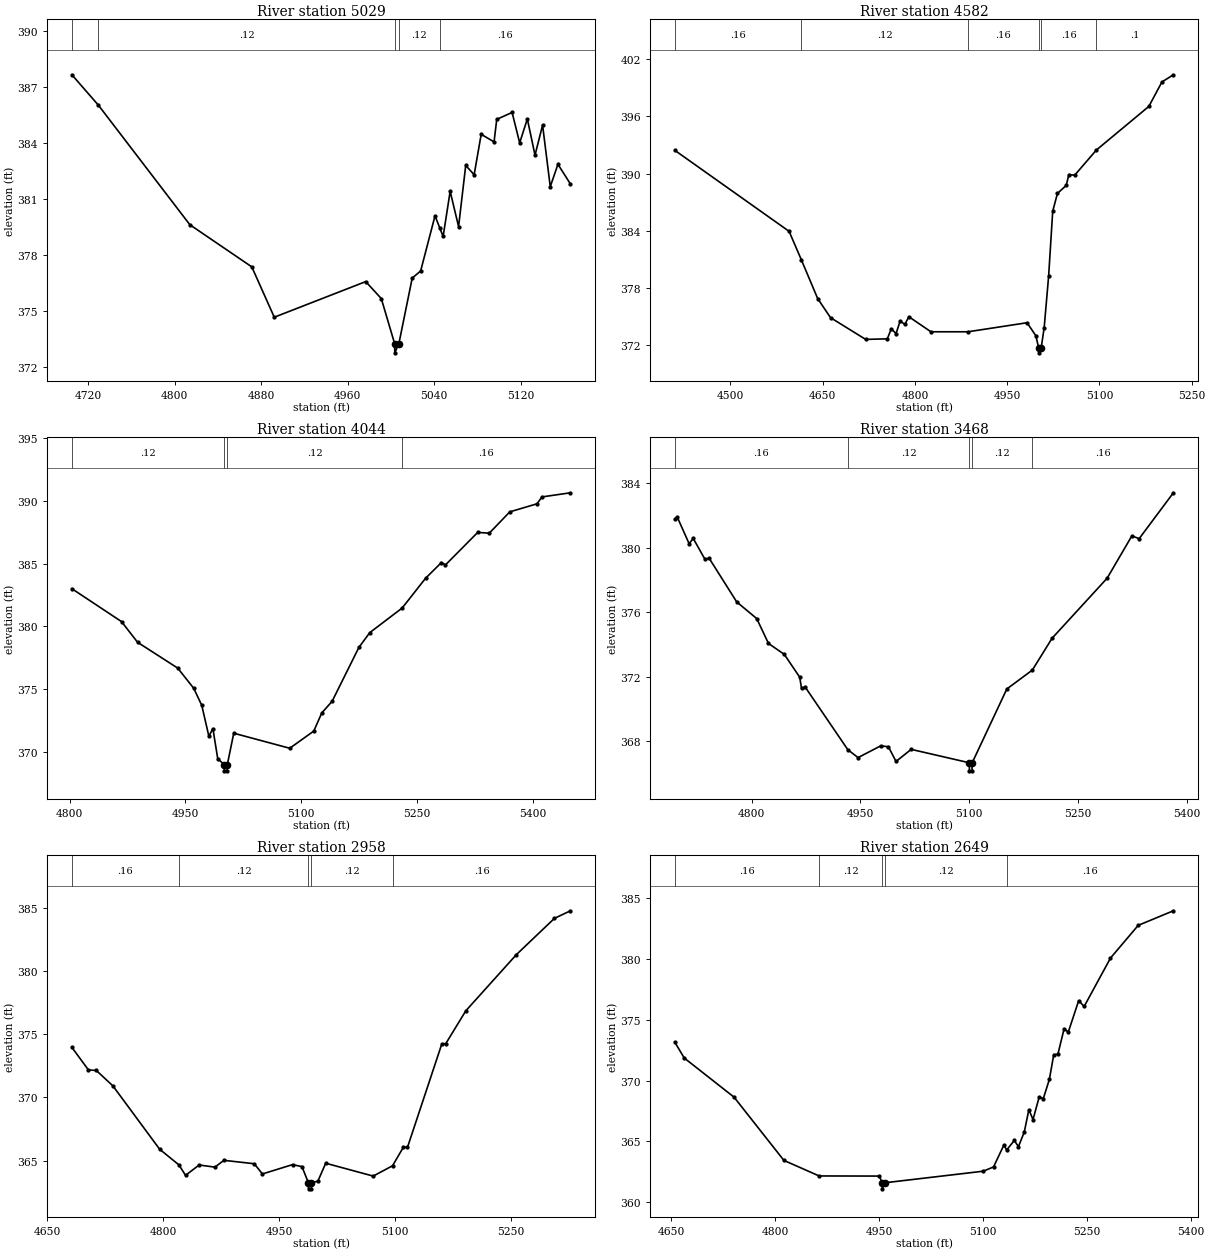
Type RM Length L Ch R = 1,5029,447,447,447
BEGIN DESCRIPTION:
DUCK CREEK TRIB 27 17 0
END DESCRIPTION:
XS GIS Cut Line= 3
      3511974.08     10414897.17      3512274.05     10414647.20
      3512324.06     10414597.18
#Sta/Elev= 30
  4705.0  387.65  4729.5  386.02  4814.1  379.61  4871.4  377.35  4892.2  374.65
  4976.8  376.56  4991.2  375.65  5003.5  373.24  5003.7  372.74  5007.5  373.24
  5019.8  376.75  5027.6  377.13  5040.9  380.09  5045.4  379.42  5048.4  378.98
  5054.9  381.40  5062.7  379.51  5069.3  382.79  5077.1  382.29  5083.6  384.46
  5095.5  384.05  5098.0  385.26  5112.2  385.63  5119.2  384.00  5126.3  385.28
  5133.4  383.34  5140.4  384.95  5147.5  381.65  5154.6  382.85  5166.2  381.79
#Mann=5,-1,0
  4705.0    0.16       0  4729.5    0.12       0  5003.5    0.07       0
  5007.5    0.12       0  5045.4    0.16       0
Bank Sta=5003.5,5007.5
Exp/Cntr=0.3,0.1

Type RM Length L Ch R = 1,4582,538,538,538
BEGIN DESCRIPTION:
Mapping XS 9000c4f5
END DESCRIPTION:
XS GIS Cut Line= 4
      3511986.15     10415192.81      3512185.34     10415125.11
      3512513.47     10414845.16      3512624.13     10414717.57
#Sta/Elev= 30
  4409.6  392.44  4595.4  383.94  4615.2  380.97  4641.9  376.88  4662.8  374.88
  4719.9  372.60  4755.0  372.66  4761.6  373.71  4769.3  373.21  4775.9  374.53
  4783.6  374.18  4790.1  374.98  4826.0  373.40  4886.3  373.40  4982.3  374.35
  4996.6  372.98  5001.2  371.69  5001.4  371.19  5005.2  371.69  5010.1  373.82
  5017.4  379.28  5024.0  386.05  5031.7  387.92  5046.0  388.76  5050.2  389.89
  5059.7  389.83  5095.1  392.48  5180.3  397.05  5201.6  399.62  5220.2  400.37
#Mann=6,-1,0
  4409.6    0.16       0  4615.2    0.12       0  4886.3    0.16       0
  5001.2    0.07       0  5005.2    0.16       0  5095.1     0.1       0
Bank Sta=5001.2,5005.2
Exp/Cntr=0.3,0.1

Type RM Length L Ch R = 1,4044,576,576,576
BEGIN DESCRIPTION:
DUCK CREEK TRIB 27 11 0
END DESCRIPTION:
XS GIS Cut Line= 4
      3512220.48     10415307.41      3512341.59     10415272.25
      3512630.66     10415350.37      3512844.25     10415298.28
#Sta/Elev= 30
  4803.0  383.01  4867.2  380.39  4888.0  378.74  4940.0  376.68  4960.7  375.07
  4971.1  373.71  4980.3  371.25  4985.5  371.86  4991.8  369.45  5000.2  368.99
  5000.4  368.49  5003.9  368.49  5004.2  368.99  5012.5  371.49  5085.0  370.29
  5116.1  371.66  5126.5  373.11  5139.8  374.03  5174.5  378.33  5188.6  379.51
  5230.5  381.47  5260.9  383.85  5281.4  385.10  5286.6  384.91  5328.3  387.50
  5343.3  387.44  5369.9  389.14  5405.0  389.78  5411.6  390.33  5448.4  390.66
#Mann=4,-1,0
  4803.0    0.12       0  5000.2    0.07       0  5004.2    0.12       0
  5230.5    0.16       0
Bank Sta=5000.2,5004.2
Exp/Cntr=0.3,0.1

Type RM Length L Ch R = 1,3468,510,510,510
BEGIN DESCRIPTION:
DUCK CREEK TRIB 27 7 0
END DESCRIPTION:
XS GIS Cut Line= 4
      3512233.53     10415785.27      3512385.86     10415867.30
      3512659.30     10415782.66      3512767.24     10415581.09
#Sta/Elev= 30
  4694.0  381.76  4697.5  381.87  4713.7  380.24  4719.4  380.56  4735.6  379.27
  4741.3  379.34  4779.4  376.63  4807.0  375.60  4823.2  374.06  4845.1  373.38
  4866.3  371.97  4868.8  371.28  4874.0  371.35  4932.7  367.48  4946.8  366.99
  4978.2  367.72  4988.7  367.66  4999.2  366.75  5020.1  367.50  5100.3  366.67
  5100.5  366.17  5104.0  366.17  5104.3  366.67  5152.1  371.24  5187.3  372.41
  5214.5  374.38  5290.5  378.10  5324.6  380.72  5334.7  380.55  5381.9  383.39
#Mann=5,-1,0
  4694.0    0.16       0  4932.7    0.12       0  5100.3    0.07       0
  5104.3    0.12       0  5187.3    0.16       0
Bank Sta=5100.3,5104.3
Exp/Cntr=0.3,0.1

Type RM Length L Ch R = 1,2958,309,309,309
BEGIN DESCRIPTION:
DUCK CREEK TRIB 27 2 3
END DESCRIPTION:
XS GIS Cut Line= 3
      3512301.24     10416126.41      3512801.23     10416233.18
      3512897.99     10416324.78
#Sta/Elev= 30
  4682.2  373.97  4703.5  372.19  4713.8  372.14  4735.2  370.92  4795.6  365.90
  4820.5  364.66  4829.1  363.83  4846.7  364.65  4867.1  364.48  4878.7  365.02
  4917.9  364.75  4928.5  363.94  4967.4  364.68  4979.6  364.52  4987.8  363.26
  4988.1  362.76  4991.6  362.76  4991.8  363.26  5000.1  363.36  5010.3  364.79
  5071.7  363.77  5096.7  364.59  5110.8  366.07  5116.0  366.05  5160.4  374.25
  5165.5  374.27  5191.4  376.87  5256.7  381.32  5306.0  384.20  5326.7  384.80
#Mann=5,-1,0
  4682.2    0.16       0  4820.5    0.12       0  4987.8    0.07       0
  4991.8    0.12       0  5096.7    0.16       0
Bank Sta=4987.8,4991.8
Exp/Cntr=0.3,0.1

Type RM Length L Ch R = 1,2649,76,76,76
BEGIN DESCRIPTION:
DUCK CREEK TRIB 27 2 2
END DESCRIPTION:
XS GIS Cut Line= 3
      3512254.34     10416280.05      3512741.33     10416609.49
      3512872.87     10416614.70
#Sta/Elev= 30
  4654.9  373.15  4668.5  371.85  4740.4  368.63  4812.3  363.43  4863.2  362.15
  4950.1  362.14  4954.1  361.59  4954.4  361.09  4958.1  361.59  5100.0  362.54
  5114.9  362.89  5129.9  364.70  5133.8  364.28  5144.9  365.07  5150.9  364.56
  5159.3  365.77  5165.9  367.60  5171.9  366.79  5180.8  368.65  5186.8  368.52
  5195.5  370.09  5201.8  372.12  5207.8  372.17  5216.8  374.26  5222.8  373.98
  5237.8  376.57  5245.7  376.09  5283.7  380.07  5323.7  382.76  5374.5  383.96
#Mann=5,-1,0
  4654.9    0.16       0  4863.2    0.12       0  4954.1    0.07       0
  4958.1    0.12       0  5133.8    0.16       0
Bank Sta=4954.1,4958.1
Exp/Cntr=0.3,0.1

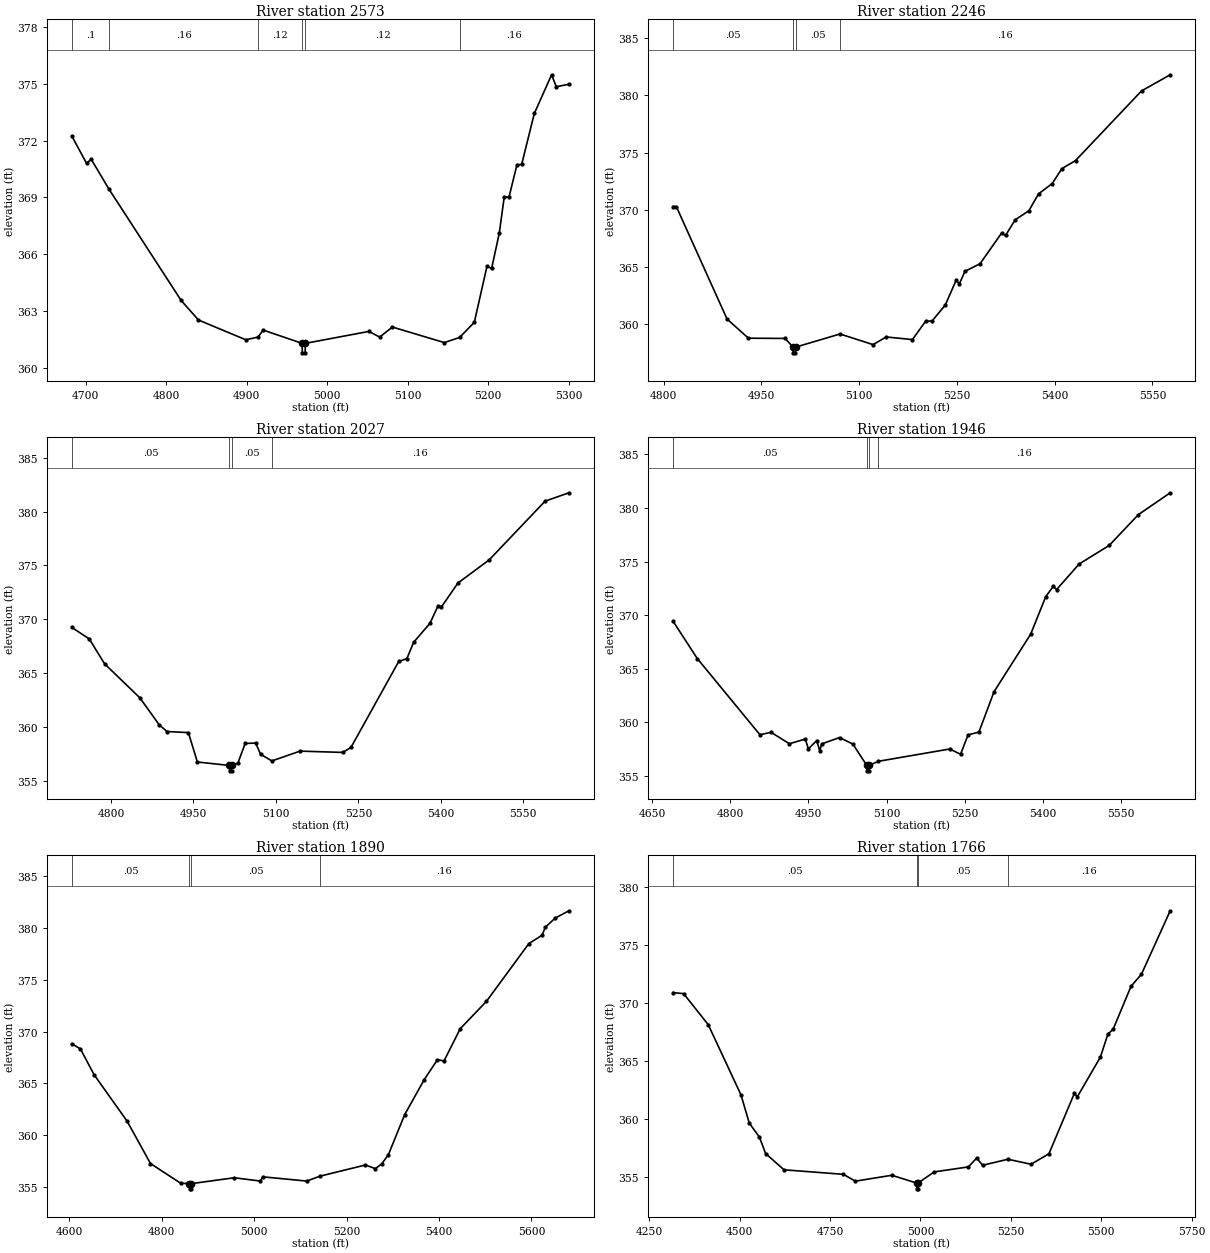
Type RM Length L Ch R = 1,2573,327,327,327
BEGIN DESCRIPTION:
DUCK CREEK TRIB 27 5 0
END DESCRIPTION:
XS GIS Cut Line= 2
      3512223.12     10416376.42      3512756.84     10416686.78
#Sta/Elev= 30
  4683.0  372.24  4701.3  370.80  4707.0  371.02  4729.3  369.43  4818.8  363.57
  4840.3  362.54  4899.0  361.50  4914.3  361.64  4920.6  362.01  4969.0  361.31
  4969.3  360.81  4972.8  360.81  4973.0  361.31  5052.0  361.94  5065.4  361.64
  5081.1  362.17  5145.7  361.35  5164.6  361.62  5182.9  362.42  5198.6  365.37
  5204.4  365.26  5213.9  367.12  5220.1  369.04  5225.9  369.01  5235.9  370.73
  5241.7  370.74  5257.4  373.43  5278.9  375.47  5284.7  374.84  5300.4  374.97
#Mann=6,-1,0
  4683.0     0.1       0  4729.3    0.16       0  4914.3    0.12       0
  4969.0    0.07       0  4973.0    0.12       0  5164.6    0.16       0
Bank Sta=4969,4973
Exp/Cntr=0.3,0.1

Type RM Length L Ch R = 1,2246,219,219,219
BEGIN DESCRIPTION:
Mapping XS c43c62bc
END DESCRIPTION:
XS GIS Cut Line= 3
      3512267.37     10416826.93      3512732.22     10416880.32
      3512974.37     10416712.37
#Sta/Elev= 30
  4814.6  370.28  4819.5  370.28  4897.3  360.44  4930.1  358.76  4986.4  358.74
  4998.6  357.98  4998.8  357.48  5002.3  357.48  5002.6  357.98  5070.6  359.13
  5121.3  358.20  5141.5  358.87  5181.7  358.64  5201.9  360.24  5211.9  360.27
  5232.1  361.66  5248.7  363.82  5253.8  363.53  5262.3  364.61  5285.5  365.28
  5318.4  367.95  5324.5  367.75  5339.4  369.12  5360.3  369.91  5375.2  371.39
  5396.1  372.29  5411.0  373.60  5431.9  374.30  5533.2  380.40  5577.2  381.81
#Mann=4,-1,0
  4814.6    0.05       0  4998.6    0.03       0  5002.6    0.05       0
  5070.6    0.16       0
Bank Sta=4998.6,5002.6
Exp/Cntr=0.3,0.1

Type RM Length L Ch R = 1,2027,81,81,81
BEGIN DESCRIPTION:
Mapping XS 710a5d3b
END DESCRIPTION:
XS GIS Cut Line= 4
      3512272.60     10416916.79      3512404.09     10417067.82
      3512519.98     10417054.80      3513005.69     10416724.04
#Sta/Elev= 30
  4728.7  369.25  4760.5  368.18  4788.2  365.88  4852.6  362.71  4887.7  360.21
  4902.0  359.59  4940.8  359.49  4957.1  356.76  5015.5  356.44  5015.8  355.94
  5019.3  355.94  5019.5  356.44  5030.8  356.65  5044.1  358.48  5063.2  358.52
  5072.1  357.48  5092.7  356.86  5143.9  357.77  5221.8  357.65  5236.7  358.12
  5323.5  366.09  5338.4  366.36  5350.6  367.87  5380.3  369.63  5395.3  371.28
  5401.3  371.16  5431.2  373.37  5488.1  375.52  5589.8  380.97  5633.2  381.75
#Mann=4,-1,0
  4728.7    0.05       0  5015.5    0.03       0  5019.5    0.05       0
  5092.7    0.16       0
Bank Sta=5015.5,5019.5
Exp/Cntr=0.3,0.1

Type RM Length L Ch R = 1,1946,56,56,56
BEGIN DESCRIPTION:
DUCK CREEK TRIB 27 4 0
END DESCRIPTION:
XS GIS Cut Line= 5
      3512266.05     10416951.91      3512428.83     10417112.09
      3512480.92     10417140.74      3512526.49     10417131.62
      3513013.44     10416747.53
#Sta/Elev= 30
  4690.1  369.41  4736.6  365.93  4856.8  358.82  4878.1  359.05  4913.4  357.98
  4944.0  358.42  4949.7  357.50  4965.8  358.28  4971.5  357.34  4975.7  357.97
  5009.7  358.56  5035.2  357.95  5062.1  355.95  5062.3  355.45  5065.8  355.45
  5066.1  355.95  5084.1  356.34  5221.2  357.49  5242.0  357.00  5256.5  358.81
  5277.3  359.07  5306.2  362.83  5376.7  368.22  5405.5  371.71  5420.0  372.68
  5426.4  372.38  5469.7  374.77  5527.4  376.50  5583.5  379.38  5644.6  381.42
#Mann=4,-1,0
  4690.1    0.05       0  5062.1    0.03       0  5066.1    0.05       0
  5084.1    0.16       0
Bank Sta=5062.1,5066.1
Exp/Cntr=0.3,0.1

Type RM Length L Ch R = 1,1890,124,124,124
BEGIN DESCRIPTION:
Mapping XS b32c1d28
END DESCRIPTION:
XS GIS Cut Line= 4
      3512249.15     10416967.56      3512409.30     10417195.42
      3512603.31     10417182.40      3513046.03     10416773.54
#Sta/Elev= 30
  4605.5  368.83  4624.1  368.33  4653.7  365.84  4725.1  361.36  4775.7  357.27
  4841.0  355.37  4859.9  355.33  4860.2  354.83  4863.7  354.83  4863.9  355.33
  4957.0  355.90  5013.6  355.58  5018.6  355.99  5113.6  355.58  5142.2  356.05
  5240.7  357.13  5262.2  356.78  5276.4  357.25  5290.6  358.14  5325.7  361.99
  5368.2  365.38  5396.6  367.29  5410.8  367.17  5445.9  370.28  5502.6  372.92
  5594.5  378.50  5622.8  379.29  5630.2  380.08  5651.2  380.95  5681.1  381.66
#Mann=4,-1,0
  4605.5    0.05       0  4859.9    0.03       0  4863.9    0.05       0
  5142.2    0.16       0
Bank Sta=4859.9,4863.9
Exp/Cntr=0.3,0.1

Type RM Length L Ch R = 1,1766,0,0,0
BEGIN DESCRIPTION:
DUCK CREEK TRIB 27 1
END DESCRIPTION:
XS GIS Cut Line= 4
      3512186.25     10416897.05      3512408.49     10417362.36
      3512727.93     10417244.30      3513130.68     10416917.93
#Sta/Elev= 30
  4316.1  370.89  4345.1  370.80  4413.1  368.13  4503.7  362.08  4526.6  359.65
  4554.8  358.43  4571.9  357.02  4622.8  355.62  4787.2  355.23  4819.9  354.64
  4920.9  355.15  4989.3  354.48  4989.6  353.98  4993.1  353.98  4993.3  354.48
  5038.2  355.44  5132.7  355.87  5155.4  356.63  5171.9  356.01  5241.9  356.53
  5305.8  356.10  5355.3  357.00  5425.7  362.21  5433.6  361.90  5497.6  365.33
  5518.4  367.32  5532.8  367.73  5582.3  371.43  5611.1  372.47  5690.7  377.94
#Mann=4,-1,0
  4316.1    0.05       0  4989.3    0.03       0  4993.3    0.05       0
  5241.9    0.16       0
Bank Sta=4989.3,4993.3
Exp/Cntr=0.3,0.1

Chan Stop Cuts=-1