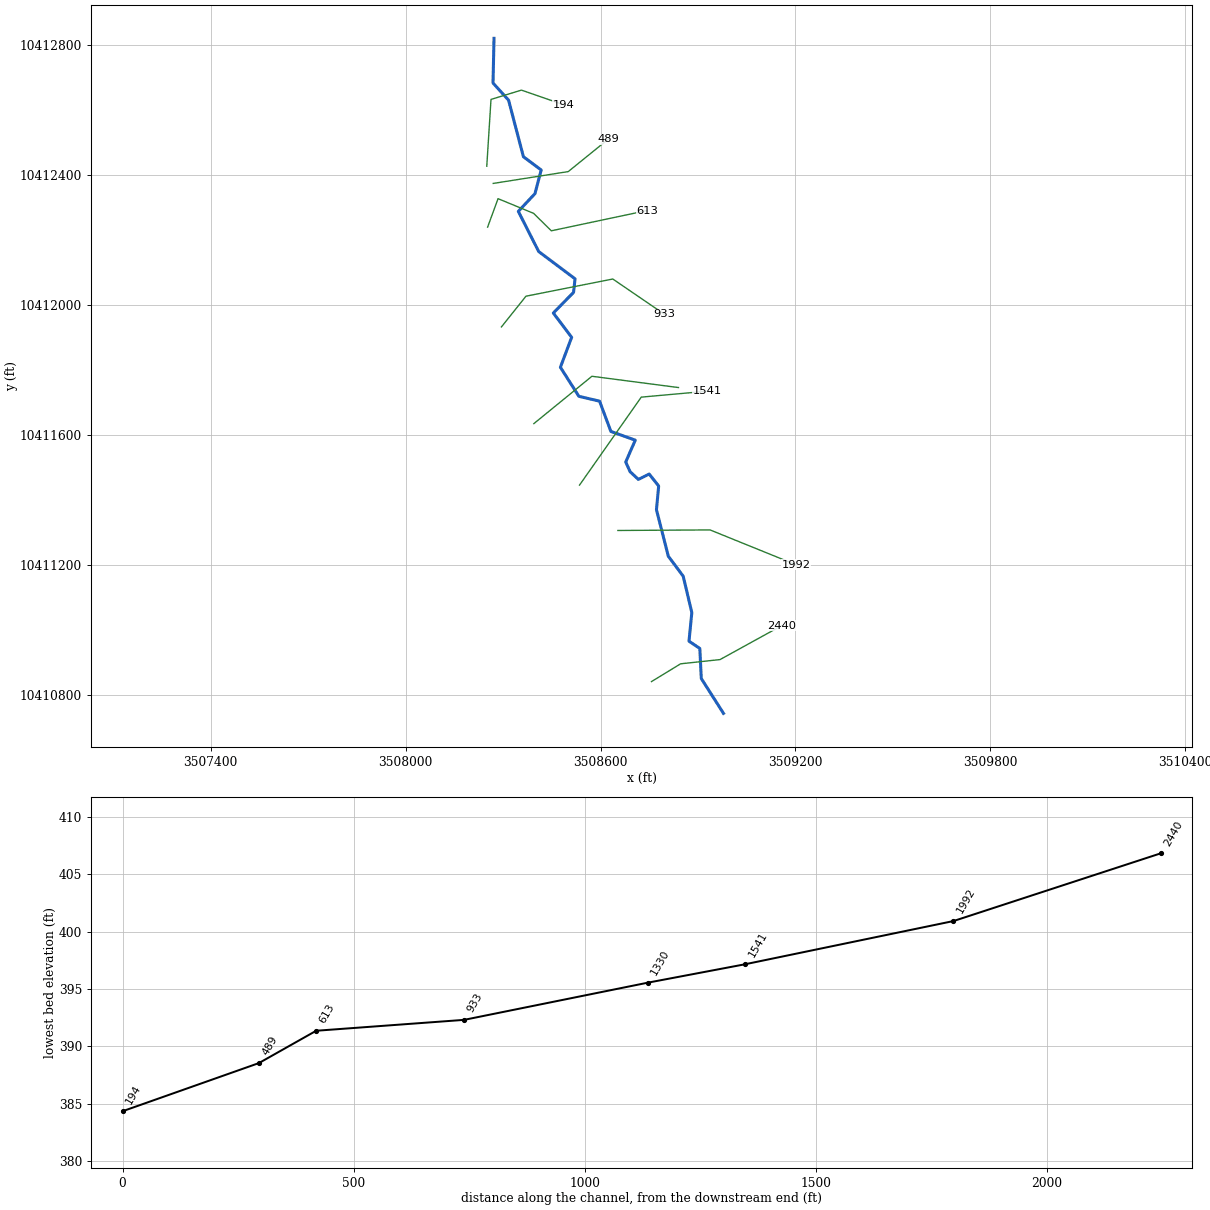
--- DUCK CREEK TRIB 28 1.prj (project) ---

Proj Title=DUCK CREEK TRIB 28 1 Base Level Engineering
Current Plan=p01
Default Exp/Contr=0.3,0.1
English Units
Geom File=g01
Flow File=f01
Plan File=p01
Y Axis Title=Elevation
X Axis Title(PF)=Main Channel Distance
X Axis Title(XS)=Station
BEGIN DESCRIPTION:
DUCK CREEK TRIB 28 1
END DESCRIPTION:
DSS Export Rating Curves= 0
DSS Export Rating Curve Sorted= 0
DSS Export Volume Flow Curves= 0
DXF OffsetX= 0
DXF OffsetY= 0
DXF ScaleX= 1
DXF ScaleY= 10

--- DUCK CREEK TRIB 28 1.p01 (plan) ---

Plan Title=Multiple Run
Short Identifier=Multiple
Geom File=g01
Flow File=f01
Subcritical Flow
K Sum by GR= 0
Std Step Tol= 0.01
Critical Tol= 0.01
Num of Std Step Trials= 20
Max Error Tol= 0.3
Flow Tol Ratio= 0.001
Split Flow NTrial= 30
Split Flow Tol= 0.02
Split Flow Ratio= 0.02
Log Output Level= 0
Friction Slope Method= 1
Unsteady Friction Slope Method= 2
Unsteady Bridges Friction Slope Method= 1
Parabolic Critical Depth
Global Vel Dist=  1 , 1 , 1
Global Log Level= 0
CheckData=True
Encroach Param= -1, 0, 0, 0
BEGIN DESCRIPTION:
Multiple Run
END DESCRIPTION:

--- DUCK CREEK TRIB 28 1.f01 (steady flow) ---

Flow Title=Multiple
Number of Profiles=7
Profile Names=10-year,25-year,50-year,1pct_min,100-year,1pct_plu,500-year
River Rch & RM= DUCK CREEK TRIB ,Reach-1,2440
     293     375     439     377     509     689     683
Boundary for River Rch & Prof#=DUCK CREEK TRIB ,Reach-1,1
Up Type=0
Dn Type=3
Dn Slope=0.005
Boundary for River Rch & Prof#=DUCK CREEK TRIB ,Reach-1,2
Up Type=0
Dn Type=3
Dn Slope=0.005
Boundary for River Rch & Prof#=DUCK CREEK TRIB ,Reach-1,3
Up Type=0
Dn Type=3
Dn Slope=0.005
Boundary for River Rch & Prof#=DUCK CREEK TRIB ,Reach-1,4
Up Type=0
Dn Type=3
Dn Slope=0.005
Boundary for River Rch & Prof#=DUCK CREEK TRIB ,Reach-1,5
Up Type=0
Dn Type=3
Dn Slope=0.005
Boundary for River Rch & Prof#=DUCK CREEK TRIB ,Reach-1,6
Up Type=0
Dn Type=3
Dn Slope=0.005
Boundary for River Rch & Prof#=DUCK CREEK TRIB ,Reach-1,7
Up Type=0
Dn Type=3
Dn Slope=0.005

--- DUCK CREEK TRIB 28 1.g01 (geometry) ---

Geom Title=Existing Conditions
Program Version=4.10

River Reach=DUCK CREEK TRIB ,Reach-1
Reach XY= 30
      3508978.66     10410743.17      3508910.31     10410850.47
      3508905.76       10410943.      3508872.48     10410965.48
      3508881.14      10411053.6      3508854.58     10411165.58
      3508808.75     10411227.04      3508772.29     10411370.26
      3508779.06     10411443.18      3508749.89     10411480.16
      3508716.56     10411463.49      3508691.04     10411487.45
      3508677.66     10411517.27      3508707.06     10411584.34
       3508631.9     10411611.32      3508597.15     10411704.47
      3508533.38     10411719.42       3508476.5     10411808.83
      3508511.15     10411901.04       3508454.7     10411975.85
      3508516.95     10412039.38      3508521.62     10412081.16
      3508409.65     10412165.24      3508346.92     10412288.87
      3508398.15     10412343.35      3508417.37     10412416.27
      3508362.64     10412456.99      3508316.94     10412631.27
      3508269.02     10412684.05      3508272.11     10412821.64

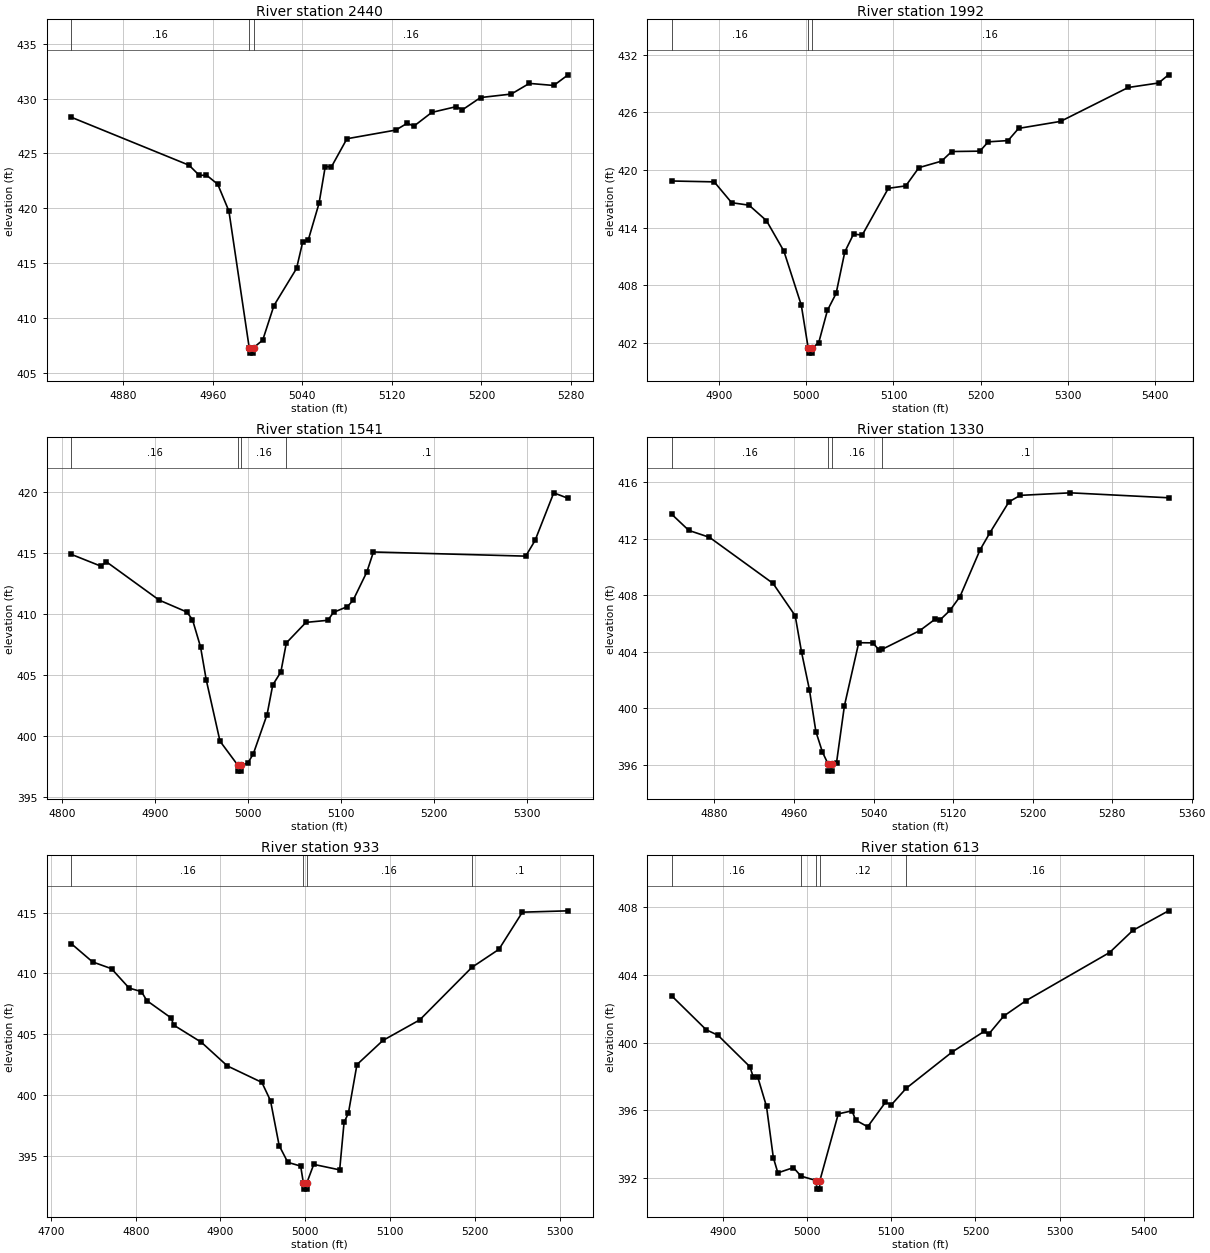
Type RM Length L Ch R = 1 ,2440    ,448,448,448
BEGIN DESCRIPTION:
DUCK CREEK TRIB 28 1 11 0
END DESCRIPTION:
XS GIS Cut Line= 4
      3508757.07     10410841.08      3508846.68     10410895.79
      3508968.04     10410908.81      3509157.65     10411013.22
#Sta/Elev= 30
  4833.9  428.29  4938.9  423.93  4948.1     423  4954.4  423.03  4964.5   422.2
  4974.5  419.75  4992.6  407.32  4992.9  406.82  4996.4  406.82  4996.6  407.32
  5004.7  408.01  5014.7  411.15  5034.9  414.53  5040.3   416.9  5045.3   417.1
    5055  420.47  5060.5  423.79  5066.1  423.79  5079.9  426.34  5123.5  427.13
  5133.9  427.76  5139.6  427.48  5155.7  428.74  5177.4  429.26  5183.1  428.98
  5199.2  430.09  5226.7  430.41  5242.8  431.38  5264.6  431.19  5277.4  432.16
#Mann= 3 ,-1 , 0
  4833.9     .16       0  4992.6     .07       0  4996.6     .16       0
Bank Sta=4992.6,4996.6
XS Rating Curve= 0 ,0
Exp/Cntr=0.3,0.1

Type RM Length L Ch R = 1 ,1992    ,451,451,451
BEGIN DESCRIPTION:
DUCK CREEK TRIB 28 1 6
END DESCRIPTION:
XS GIS Cut Line= 3
      3508653.47      10411306.3       3508937.3     10411308.04
      3509202.88     10411200.41
#Sta/Elev= 30
  4845.5  418.85  4894.1  418.76  4914.1  416.59  4934.1  416.33  4954.1  414.72
  4974.1  411.55  4994.1  405.92  5002.1  401.42  5002.4  400.92  5005.9  400.92
  5006.1  401.42  5014.1     402  5024.1  405.37  5034.1  407.14  5044.1  411.47
  5054.1  413.32  5064.1  413.22  5094.1  418.09  5114.1  418.34  5129.2  420.24
  5155.2  420.92  5166.9  421.92  5199.3  421.96  5208.8  422.93  5231.6  423.06
  5243.7  424.33  5291.9  425.06  5369.6  428.59  5404.5  429.06  5415.9  429.91
#Mann= 3 ,-1 , 0
  4845.5     .16       0  5002.1     .07       0  5006.1     .16       0
Bank Sta=5002.1,5006.1
XS Rating Curve= 0 ,0
Exp/Cntr=0.3,0.1

Type RM Length L Ch R = 1 ,1541    ,211,211,211
BEGIN DESCRIPTION:
Mapping XS 3992326a
END DESCRIPTION:
XS GIS Cut Line= 3
      3508535.36     10411446.02      3508725.49     10411716.89
      3508927.43     10411735.09
#Sta/Elev= 30
  4810.5  414.88  4841.8  413.93  4848.1  414.27  4904.8  411.14  4934.4  410.17
  4940.5  409.55  4949.2  407.31  4955.3  404.62  4970.1   399.6  4989.1  397.65
  4989.3  397.15  4992.8  397.15  4993.1  397.65  4999.8  397.78  5005.9  398.56
  5020.7  401.78  5026.8   404.2  5035.5  405.26  5041.4  407.64  5062.5  409.32
    5086  409.49  5092.1  410.14    5107  410.61  5113.1  411.12  5127.9  413.44
    5135  415.08  5298.7  414.74  5308.7  416.02  5328.8  419.92  5344.2  419.47
#Mann= 4 ,-1 , 0
  4810.5     .16       0  4989.1     .07       0  4993.1     .16       0
  5041.4      .1       0
Bank Sta=4989.1,4993.1
XS Rating Curve= 0 ,0
Exp/Cntr=0.3,0.1

Type RM Length L Ch R = 1 ,1330    ,397,397,397
BEGIN DESCRIPTION:
DUCK CREEK TRIB 28 1 5 0
END DESCRIPTION:
XS GIS Cut Line= 3
      3508394.75     10411635.28      3508573.58     10411781.13
      3508840.06     10411746.41
#Sta/Elev= 30
  4837.2  413.71  4854.2  412.58    4875  412.09  4938.9  408.83  4961.2  406.54
  4967.6  403.96  4975.5  401.31    4982  398.34  4988.6  396.89  4994.3  396.04
  4994.6  395.54  4998.1  395.54  4998.3  396.04  5002.8  396.15  5010.7  400.16
  5025.1  404.63  5039.4  404.62  5045.9  404.08  5048.9  404.17  5086.6  405.49
  5102.2  406.31  5107.3  406.27  5116.9  406.92    5127   407.9  5147.2  411.21
  5157.2  412.43  5176.2   414.6  5187.5  415.06  5237.9  415.24  5336.7  414.89
#Mann= 4 ,-1 , 0
  4837.2     .16       0  4994.3     .07       0  4998.3     .16       0
  5048.9      .1       0
Bank Sta=4994.3,4998.3
XS Rating Curve= 0 ,0
Exp/Cntr=0.3,0.1

Type RM Length L Ch R = 1 ,933     ,320,320,320
BEGIN DESCRIPTION:
DUCK CREEK TRIB 28 1 4 0
END DESCRIPTION:
XS GIS Cut Line= 4
      3508294.96     10411933.08      3508370.46     10412027.66
      3508637.82     10412080.61      3508796.63     10411972.12
#Sta/Elev= 30
  4724.2  412.43    4749  410.95  4771.4  410.39  4792.2   408.8  4806.7  408.51
  4813.1  407.77  4841.9  406.34  4844.6  405.77  4877.5  404.35  4908.1  402.41
  4948.8  401.06    4959  399.56  4969.2  395.88  4979.4   394.5  4994.6  394.19
  4997.8   392.8  4998.1   392.3  5001.6   392.3  5001.8   392.8    5010  394.33
  5040.6  393.88  5045.8  397.78  5050.9  398.53    5061  402.52  5091.6   404.5
  5135.1  406.19  5196.6   410.5  5228.5  411.98  5256.2  415.03  5310.1  415.14
#Mann= 4 ,-1 , 0
  4724.2     .16       0  4997.8     .07       0  5001.8     .16       0
  5196.6      .1       0
Bank Sta=4997.8,5001.8
XS Rating Curve= 0 ,0
Exp/Cntr=0.3,0.1

Type RM Length L Ch R = 1 ,613     ,124,124,124
BEGIN DESCRIPTION:
Mapping XS c0280a1e
END DESCRIPTION:
XS GIS Cut Line= 5
      3508252.39     10412240.29      3508284.52       10412328.
      3508393.89     10412282.86      3508448.58     10412229.04
      3508743.67     10412291.53
#Sta/Elev= 30
  4839.3  402.74  4880.1  400.75    4894  400.43    4932  398.57  4935.9  397.97
  4941.3  397.96  4951.7  396.23  4959.8  393.21  4965.2  392.31  4983.7  392.62
  4992.6  392.12  5011.1  391.85  5011.3  391.35  5014.8  391.35  5015.1  391.85
    5037  395.79  5053.3  395.97  5057.7  395.42  5071.9  395.03    5093  396.47
  5100.2  396.33  5117.7   397.3  5172.3  399.44  5210.4  400.66  5215.5  400.48
  5233.6  401.56  5260.1  402.47  5359.4  405.31  5386.9  406.61  5429.4  407.77
#Mann= 5 ,-1 , 0
  4839.3     .16       0  4992.6     .12       0  5011.1     .07       0
  5015.1     .12       0  5117.7     .16       0
Bank Sta=5011.1,5015.1
XS Rating Curve= 0 ,0
Exp/Cntr=0.3,0.1

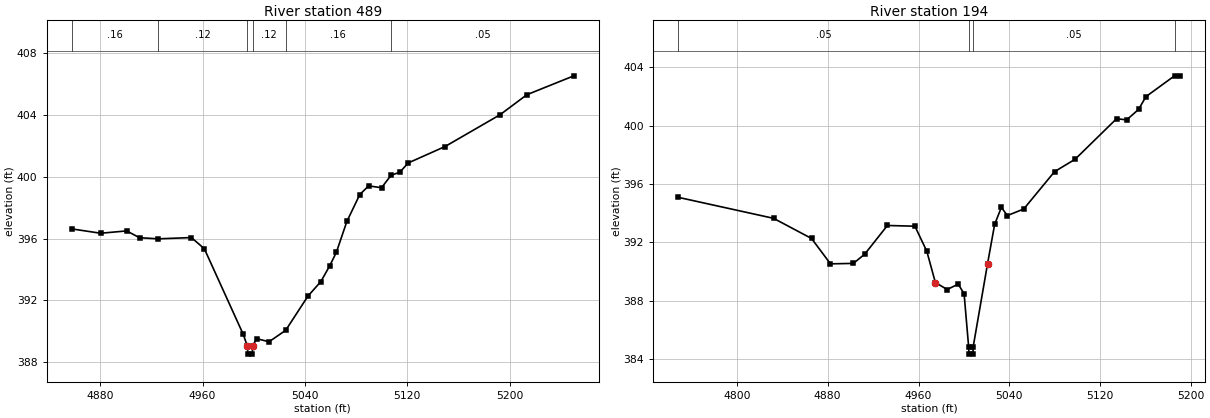
Type RM Length L Ch R = 1 ,489     ,295,295,295
BEGIN DESCRIPTION:
Mapping XS af5fabce
END DESCRIPTION:
XS GIS Cut Line= 3
      3508269.75     10412374.88      3508500.66     10412411.34
      3508623.94     10412511.17
#Sta/Elev= 30
  4857.8  396.62  4880.4  396.34  4900.7  396.49  4910.8  396.05  4925.5  395.98
  4951.3  396.06  4961.4  395.34  4991.8  389.81  4995.1  389.03  4995.4  388.53
  4998.9  388.53  4999.1  389.03  5002.2  389.53    5012  389.33    5025  390.07
  5042.4  392.28  5052.5  393.22  5059.5  394.25  5064.6  395.11  5072.8   397.1
  5082.9  398.84  5089.8   399.4  5099.9  399.28  5107.3  400.08  5114.3  400.29
  5120.7  400.88  5149.5  401.94  5192.6     404  5213.5  405.29  5250.2  406.51
#Mann= 6 ,-1 , 0
  4857.8     .16       0  4925.5     .12       0  4995.1     .07       0
  4999.1     .12       0    5025     .16       0  5107.3     .05       0
Bank Sta=4995.1,4999.1
XS Rating Curve= 0 ,0
Exp/Cntr=0.3,0.1

Type RM Length L Ch R = 1 ,194     ,0,0,0
BEGIN DESCRIPTION:
DUCK CREEK TRIB 28 1 1 0
END DESCRIPTION:
XS GIS Cut Line= 4
       3508249.8     10412427.88      3508262.82     10412633.56
      3508356.57      10412662.2      3508486.75     10412617.08
#Sta/Elev= 30
  4748.5  395.08  4832.4  393.64  4865.8  392.26  4882.5  390.52  4902.6  390.55
  4912.6  391.18  4932.6  393.15  4956.8   393.1  4967.3  391.38  4974.8  389.24
  4985.2  388.76  4994.9  389.13  5000.1  388.47  5004.1  384.83  5004.4  384.33
  5007.9  384.33  5008.1  384.83  5020.7  390.51    5027  393.23  5032.9  394.39
  5038.2  393.83  5052.6  394.28  5079.7  396.84  5097.8  397.69  5134.3  400.47
  5143.2  400.39  5153.7  401.11  5160.1  401.98  5185.3  403.41  5190.4  403.41
#Mann= 4 ,-1 , 0
  4748.5     .05       0  5004.1     .03       0  5008.1     .05       0
  5185.3     .05       0
Bank Sta=4974.8,5020.7
XS Rating Curve= 0 ,0
Exp/Cntr=0.3,0.1

Chan Stop Cuts=-1
Use User Specified Reach Order=0
Composite Channel Slope=5