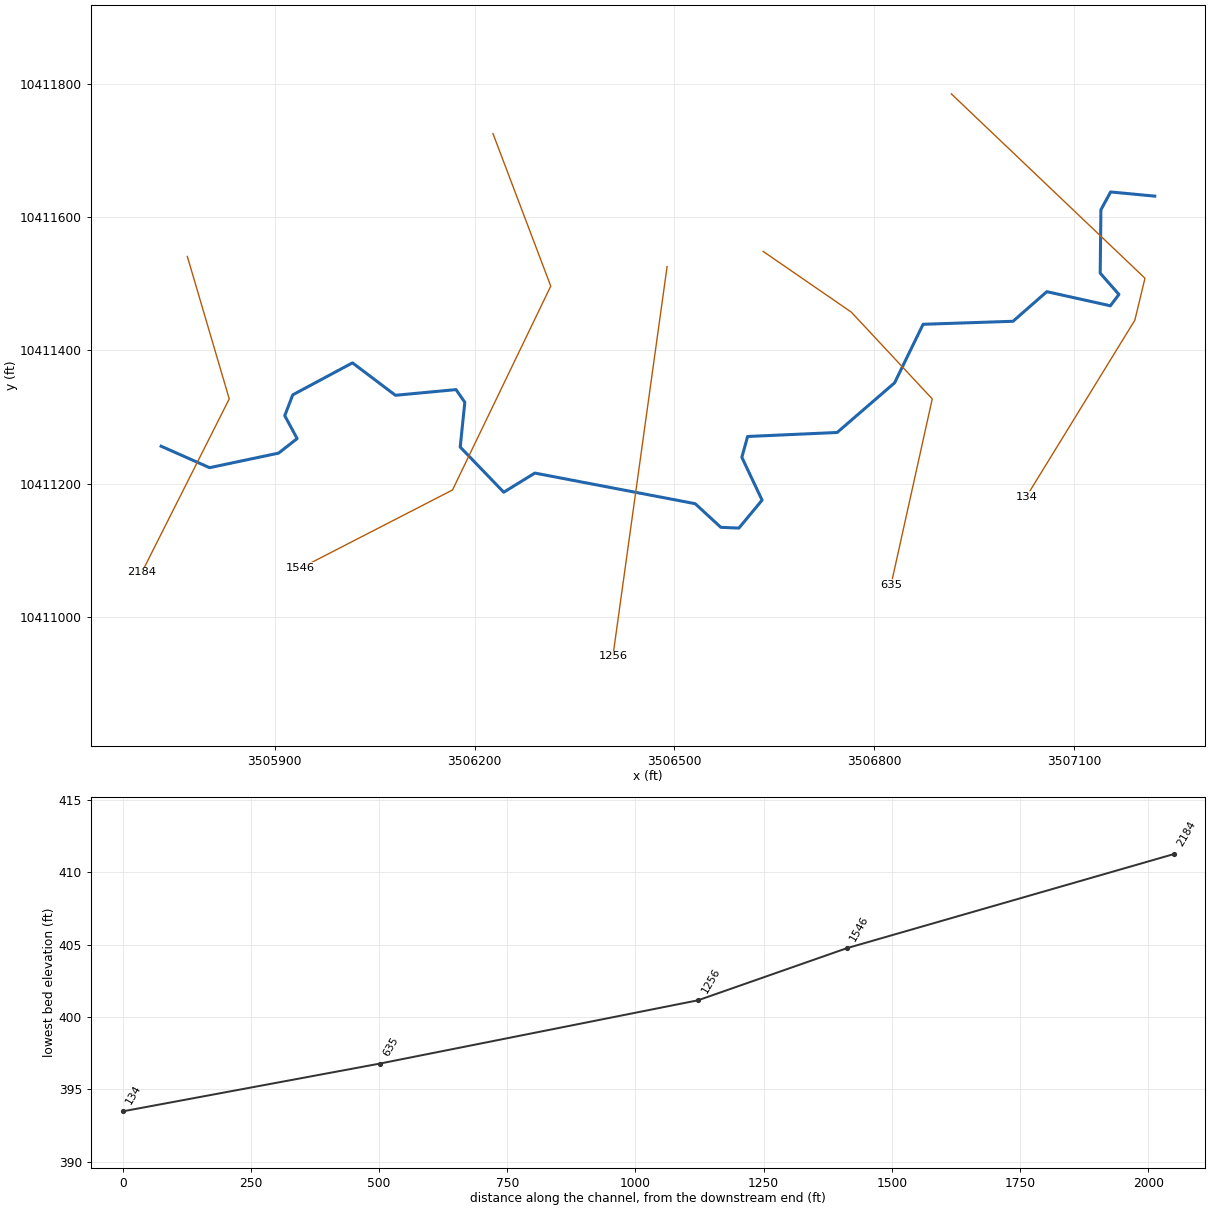
--- DUCK CREEK TRIB 28 2.prj (project) ---

Proj Title=DUCK CREEK TRIB 28 2 Base Level Engineering
Current Plan=p01
Default Exp/Contr=0.3,0.1
English Units
Geom File=g01
Flow File=f01
Plan File=p01
BEGIN DESCRIPTION:
DUCK CREEK TRIB 28 2
END DESCRIPTION:

--- DUCK CREEK TRIB 28 2.p01 (plan) ---

Plan Title=Multiple Run
Short Identifier=Multiple
Geom File=g01
Flow File=f01
Subcritical Flow
K Sum by GR= 0
Std Step Tol= 0.01
Critical Tol= 0.01
Num of Std Step Trials= 20
Max Error Tol= 0.3
Flow Tol Ratio= 0.001
Split Flow NTrial= 30
Split Flow Tol= 0.02
Split Flow Ratio= 0.02
Log Output Level= 0
Friction Slope Method= 1
Unsteady Friction Slope Method= 2
Unsteady Bridges Friction Slope Method= 1
Parabolic Critical Depth
Global Vel Dist=  1 , 1 , 1
Global Log Level= 0
CheckData=True
Encroach Param= -1, 0, 0, 0
BEGIN DESCRIPTION:
Multiple Run
END DESCRIPTION:

--- DUCK CREEK TRIB 28 2.f01 (steady flow) ---

Flow Title=Multiple
Number of Profiles=7
Profile Names=10-year,25-year,50-year,1pct_min,100-year,1pct_plu,500-year
River Rch & RM= DUCK CREEK TRIB ,Reach-1,2184
     342     441     518     446     604     817     814
Boundary for River Rch & Prof#=DUCK CREEK TRIB ,Reach-1,1
Up Type=0
Dn Type=3
Dn Slope=0.005
Boundary for River Rch & Prof#=DUCK CREEK TRIB ,Reach-1,2
Up Type=0
Dn Type=3
Dn Slope=0.005
Boundary for River Rch & Prof#=DUCK CREEK TRIB ,Reach-1,3
Up Type=0
Dn Type=3
Dn Slope=0.005
Boundary for River Rch & Prof#=DUCK CREEK TRIB ,Reach-1,4
Up Type=0
Dn Type=3
Dn Slope=0.005
Boundary for River Rch & Prof#=DUCK CREEK TRIB ,Reach-1,5
Up Type=0
Dn Type=3
Dn Slope=0.005
Boundary for River Rch & Prof#=DUCK CREEK TRIB ,Reach-1,6
Up Type=0
Dn Type=3
Dn Slope=0.005
Boundary for River Rch & Prof#=DUCK CREEK TRIB ,Reach-1,7
Up Type=0
Dn Type=3
Dn Slope=0.005

--- DUCK CREEK TRIB 28 2.g01 (geometry) ---

Geom Title=Existing Conditions

River Reach=DUCK CREEK TRIB ,Reach-1
Reach XY= 30
      3505729.31     10411256.15      3505802.09     10411223.95
      3505905.79     10411245.82      3505933.58     10411267.64
      3505914.97     10411301.98      3505926.93     10411333.24
      3506016.69     10411381.28      3506081.21     10411332.59
      3506172.22     10411341.13      3506185.38     10411322.06
      3506178.49     10411254.91      3506243.85     10411187.10
      3506290.54     10411215.85      3506531.36     10411169.89
      3506569.88     10411134.41      3506597.03     10411133.28
      3506631.83     10411175.22      3506601.43     10411239.51
      3506610.11     10411270.76      3506744.56     10411276.78
      3506830.84     10411351.31      3506873.65     10411439.16
      3507008.72     10411443.68      3507059.42     10411488.12
      3507154.91     10411466.94      3507167.75     10411483.96
      3507139.63     10411515.90      3507140.67     10411611.04
      3507155.25     10411637.78      3507221.57     10411631.53

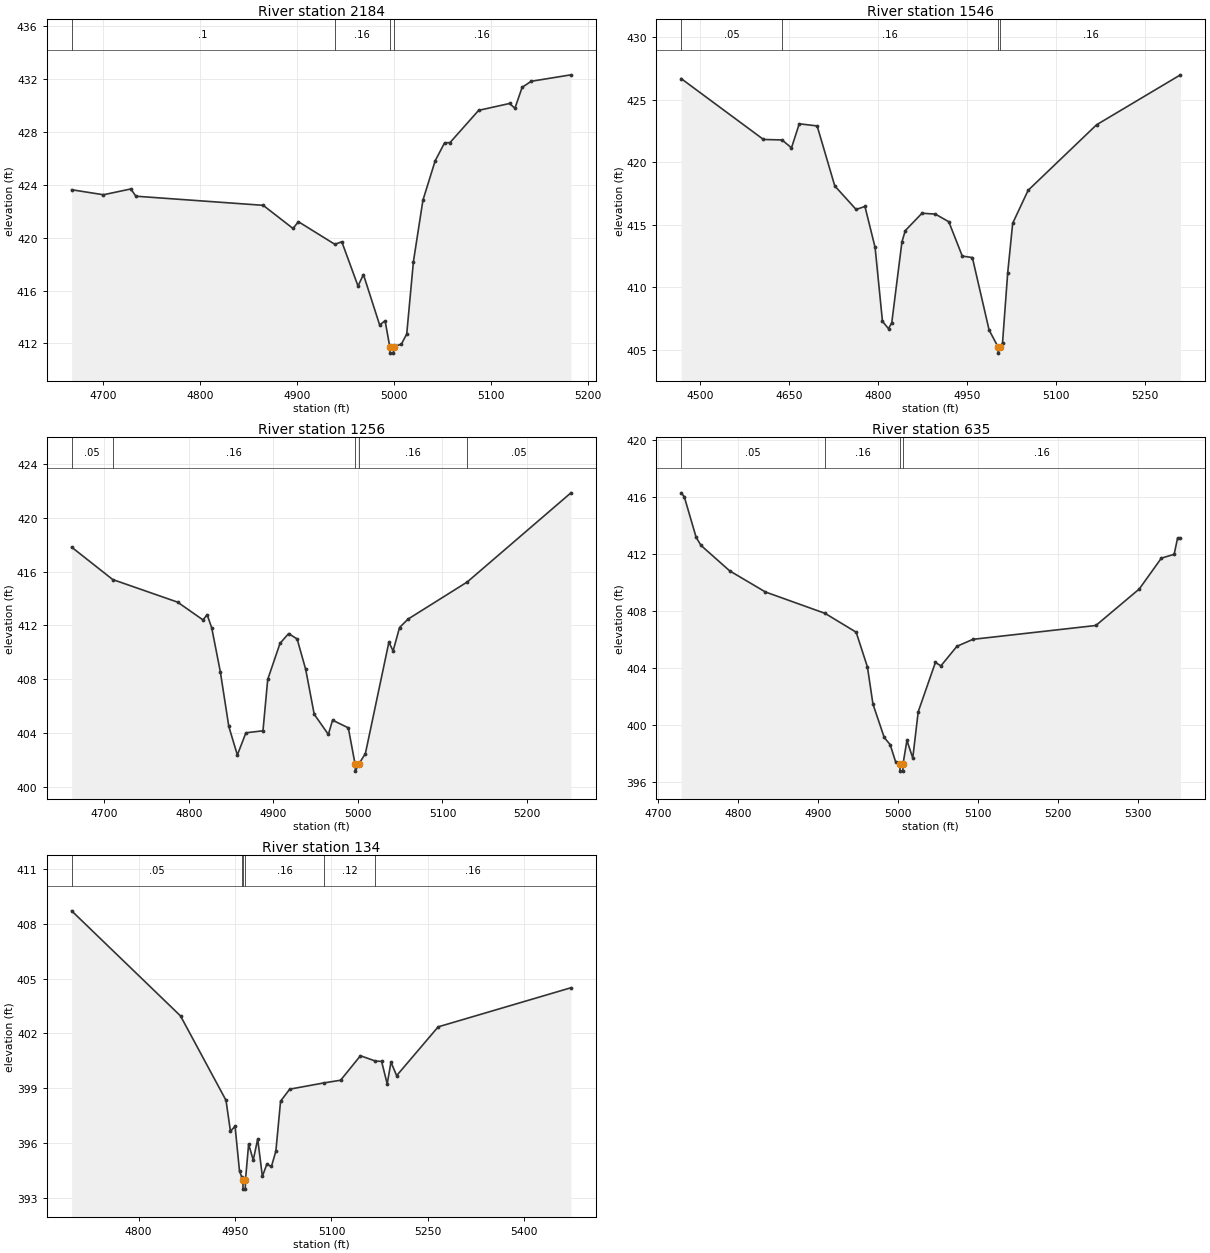
Type RM Length L Ch R = 1,2184,638,638,638
BEGIN DESCRIPTION:
DUCK CREEK TRIB 28 2 5 0
END DESCRIPTION:
XS GIS Cut Line= 3
      3505768.67     10411540.96      3505831.60     10411327.19
      3505700.30     10411066.76
#Sta/Elev= 30
  4667.6  423.64  4700.4  423.26  4728.6  423.70  4733.8  423.15  4865.0  422.46
  4895.7  420.71  4901.3  421.22  4938.8  419.51  4946.0  419.70  4962.7  416.35
  4968.3  417.22  4985.0  413.40  4990.6  413.72  4995.4  411.77  4995.7  411.27
  4999.2  411.27  4999.4  411.77  5007.3  411.94  5012.9  412.72  5019.8  418.20
  5029.6  422.85  5042.2  425.83  5051.9  427.19  5057.5  427.21  5087.0  429.65
  5118.8  430.17  5124.4  429.81  5131.8  431.39  5141.1  431.85  5182.1  432.34
#Mann=4,-1,0
  4667.6     0.1       0  4938.8    0.16       0  4995.4    0.07       0
  4999.4    0.16       0
Bank Sta=4995.4,4999.4
Exp/Cntr=0.3,0.1

Type RM Length L Ch R = 1,1546,290,290,290
BEGIN DESCRIPTION:
DUCK CREEK TRIB 28 2 4 1
END DESCRIPTION:
XS GIS Cut Line= 4
      3506227.67     10411725.39      3506314.46     10411496.46
      3506166.89     10411190.47      3505939.00     10411073.27
#Sta/Elev= 30
  4468.4  426.68  4607.0  421.82  4638.3  421.78  4654.2  421.15  4667.3  423.07
  4697.4  422.90  4727.1  418.11  4763.0  416.23  4777.9  416.47  4795.0  413.20
  4807.4  407.30  4817.6  406.71  4823.1  407.20  4840.2  413.64  4845.8  414.54
  4874.0  415.93  4896.5  415.86  4919.1  415.25  4941.8  412.51  4958.8  412.39
  4987.0  406.60  5002.0  405.26  5002.3  404.76  5006.0  405.26  5009.6  405.59
  5018.3  411.17  5026.7  415.13  5052.7  417.76  5167.9  422.99  5309.2  426.98
#Mann=4,-1,0
  4468.4    0.05       0  4638.3    0.16       0  5002.0    0.07       0
  5006.0    0.16       0
Bank Sta=5002,5006
Exp/Cntr=0.3,0.1

Type RM Length L Ch R = 1,1256,621,621,621
BEGIN DESCRIPTION:
DUCK CREEK TRIB 28 2 4 0
END DESCRIPTION:
XS GIS Cut Line= 2
      3506489.16     10411525.76      3506407.77     10410940.89
#Sta/Elev= 30
  4661.4  417.82  4710.0  415.41  4786.7  413.73  4816.7  412.41  4821.7  412.79
  4827.1  411.81  4837.2  408.57  4847.3  404.48  4857.4  402.36  4867.5  404.01
  4887.7  404.16  4893.3  407.98  4907.9  410.67  4918.0  411.39  4928.1  410.99
  4938.2  408.73  4948.3  405.39  4965.0  403.89  4970.0  404.95  4988.6  404.38
  4996.7  401.66  4997.0  401.16  5000.7  401.66  5008.8  402.46  5036.6  410.75
  5041.6  410.10  5049.2  411.84  5059.3  412.47  5129.3  415.23  5251.9  421.86
#Mann=5,-1,0
  4661.4    0.05       0  4710.0    0.16       0  4996.7    0.07       0
  5000.7    0.16       0  5129.3    0.05       0
Bank Sta=4996.7,5000.7
Exp/Cntr=0.3,0.1

Type RM Length L Ch R = 1,635,501,501,501
BEGIN DESCRIPTION:
DUCK CREEK TRIB 28 2 2 0
END DESCRIPTION:
XS GIS Cut Line= 4
      3506633.44     10411548.56      3506765.85     10411457.40
      3506887.38     10411327.19      3506825.53     10411048.33
#Sta/Elev= 30
  4728.6  416.29  4732.5  416.02  4747.4  413.16  4753.5  412.60  4789.3  410.82
  4834.0  409.34  4908.6  407.84  4947.5  406.52  4961.6  404.08  4968.5  401.48
  4982.6  399.14  4990.0  398.64  4996.8  397.44  5002.1  397.28  5002.4  396.78
  5005.9  396.78  5006.1  397.28  5011.0  398.93  5018.3  397.70  5025.1  400.94
  5046.6  404.40  5053.5  404.16  5073.5  405.53  5093.6  406.02  5247.3  406.99
  5301.6  409.55  5329.2  411.71  5345.2  411.98  5349.5  413.11  5353.1  413.11
#Mann=4,-1,0
  4728.6    0.05       0  4908.6    0.16       0  5002.1    0.07       0
  5006.1    0.16       0
Bank Sta=5002.1,5006.1
Exp/Cntr=0.3,0.1

Type RM Length L Ch R = 1,134,0,0,0
BEGIN DESCRIPTION:
DUCK CREEK TRIB 28 2 1 0
END DESCRIPTION:
XS GIS Cut Line= 4
      3506916.05     10411784.99      3507206.86     10411508.29
      3507191.67     10411445.36      3507028.93     10411180.63
#Sta/Elev= 30
  4695.7  408.71  4865.1  402.96  4935.9  398.34  4942.8  396.65  4950.0  396.92
  4956.9  394.47  4960.1  394.17  4962.2  393.98  4962.4  393.48  4965.9  393.48
  4966.2  393.98  4971.1  395.94  4978.3  395.07  4985.2  396.22  4992.5  394.18
  4999.4  394.84  5006.6  394.72  5013.5  395.56  5020.8  398.29  5035.0  398.95
  5087.8  399.29  5114.2  399.44  5145.1  400.78  5168.2  400.49  5178.0  400.47
  5186.7  399.24  5192.6  400.43  5201.4  399.69  5266.0  402.36  5472.6  404.50
#Mann=6,-1,0
  4695.7    0.05       0  4960.1    0.16       0  4962.2    0.07       0
  4966.2    0.16       0  5087.8    0.12       0  5168.2    0.16       0
Bank Sta=4962.2,4966.2
Exp/Cntr=0.3,0.1

Chan Stop Cuts=-1