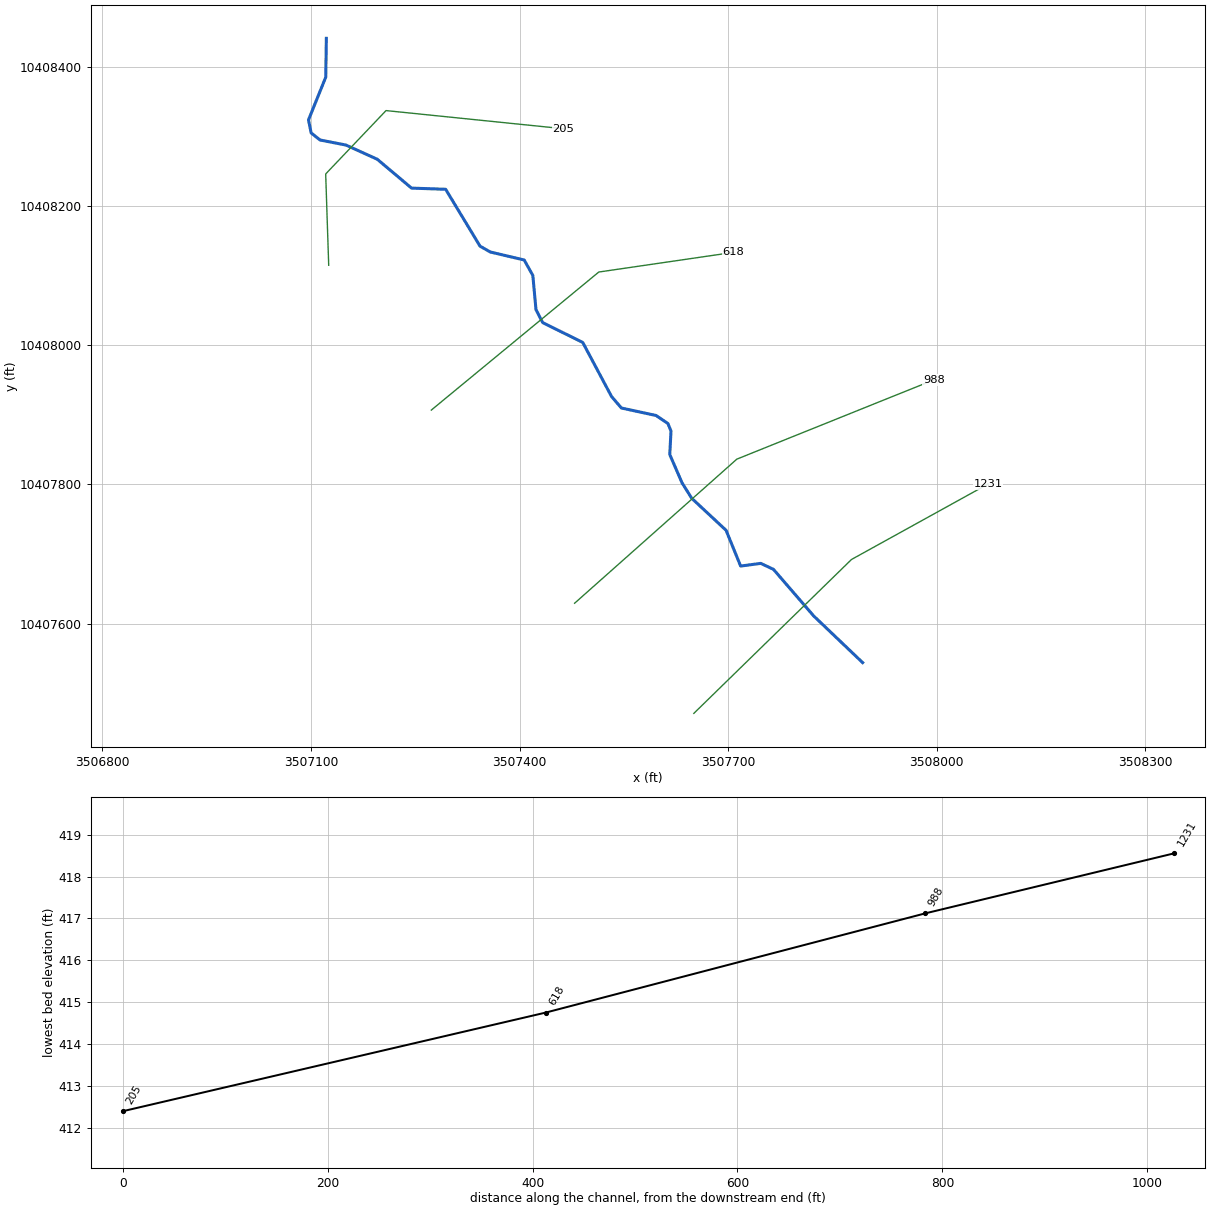
--- DUCK CREEK TRIB 28 3 1.prj (project) ---

Proj Title=DUCK CREEK TRIB 28 3 1 Base Level Engineering
Current Plan=p01
Default Exp/Contr=0.3,0.1
English Units
Geom File=g01
Flow File=f01
Plan File=p01
Y Axis Title=Elevation
X Axis Title(PF)=Main Channel Distance
X Axis Title(XS)=Station
BEGIN DESCRIPTION:
DUCK CREEK TRIB 28 3 1
END DESCRIPTION:
DSS Export Rating Curves= 0
DSS Export Rating Curve Sorted= 0
DSS Export Volume Flow Curves= 0
DXF OffsetX= 0
DXF OffsetY= 0
DXF ScaleX= 1
DXF ScaleY= 10

--- DUCK CREEK TRIB 28 3 1.p01 (plan) ---

Plan Title=Multiple Run
Short Identifier=Multiple
Geom File=g01
Flow File=f01
Subcritical Flow
K Sum by GR= 0
Std Step Tol= 0.01
Critical Tol= 0.01
Num of Std Step Trials= 20
Max Error Tol= 0.3
Flow Tol Ratio= 0.001
Split Flow NTrial= 30
Split Flow Tol= 0.02
Split Flow Ratio= 0.02
Log Output Level= 0
Friction Slope Method= 1
Unsteady Friction Slope Method= 2
Unsteady Bridges Friction Slope Method= 1
Parabolic Critical Depth
Global Vel Dist=  1 , 1 , 1
Global Log Level= 0
CheckData=True
Encroach Param= -1, 0, 0, 0
BEGIN DESCRIPTION:
Multiple Run
END DESCRIPTION:

--- DUCK CREEK TRIB 28 3 1.f01 (steady flow) ---

Flow Title=Multiple
Number of Profiles=7
Profile Names=10-year,25-year,50-year,1pct_min,100-year,1pct_plu,500-year
River Rch & RM= DUCK CREEK TRIB ,Reach-1,1231
     254     322     374     320     432     585     572
Boundary for River Rch & Prof#=DUCK CREEK TRIB ,Reach-1,1
Up Type=0
Dn Type=3
Dn Slope=0.005
Boundary for River Rch & Prof#=DUCK CREEK TRIB ,Reach-1,2
Up Type=0
Dn Type=3
Dn Slope=0.005
Boundary for River Rch & Prof#=DUCK CREEK TRIB ,Reach-1,3
Up Type=0
Dn Type=3
Dn Slope=0.005
Boundary for River Rch & Prof#=DUCK CREEK TRIB ,Reach-1,4
Up Type=0
Dn Type=3
Dn Slope=0.005
Boundary for River Rch & Prof#=DUCK CREEK TRIB ,Reach-1,5
Up Type=0
Dn Type=3
Dn Slope=0.005
Boundary for River Rch & Prof#=DUCK CREEK TRIB ,Reach-1,6
Up Type=0
Dn Type=3
Dn Slope=0.005
Boundary for River Rch & Prof#=DUCK CREEK TRIB ,Reach-1,7
Up Type=0
Dn Type=3
Dn Slope=0.005

--- DUCK CREEK TRIB 28 3 1.g01 (geometry) ---

Geom Title=Existing Conditions
Program Version=4.10

River Reach=DUCK CREEK TRIB ,Reach-1
Reach XY= 30
      3507893.41     10407543.75      3507822.94     10407610.94
      3507765.17      10407677.9      3507746.86     10407686.48
      3507717.95     10407682.62      3507697.03     10407734.01
      3507647.54     10407780.15      3507633.66     10407802.35
      3507616.03     10407843.03       3507617.8     10407876.81
      3507613.37      10407887.6       3507596.4     10407899.15
      3507546.46     10407909.95      3507532.28     10407926.48
      3507490.83     10408004.27      3507433.23     10408032.78
      3507423.63     10408051.38      3507419.07     10408100.62
      3507406.65     10408122.84      3507357.83     10408134.34
      3507343.12     10408142.76      3507293.68     10408224.56
      3507244.67      10408226.2      3507195.28     10408267.75
      3507150.33     10408288.13      3507113.06     10408295.42
      3507100.21      10408305.6      3507096.44     10408324.34
      3507121.22     10408385.78      3507122.11     10408441.64

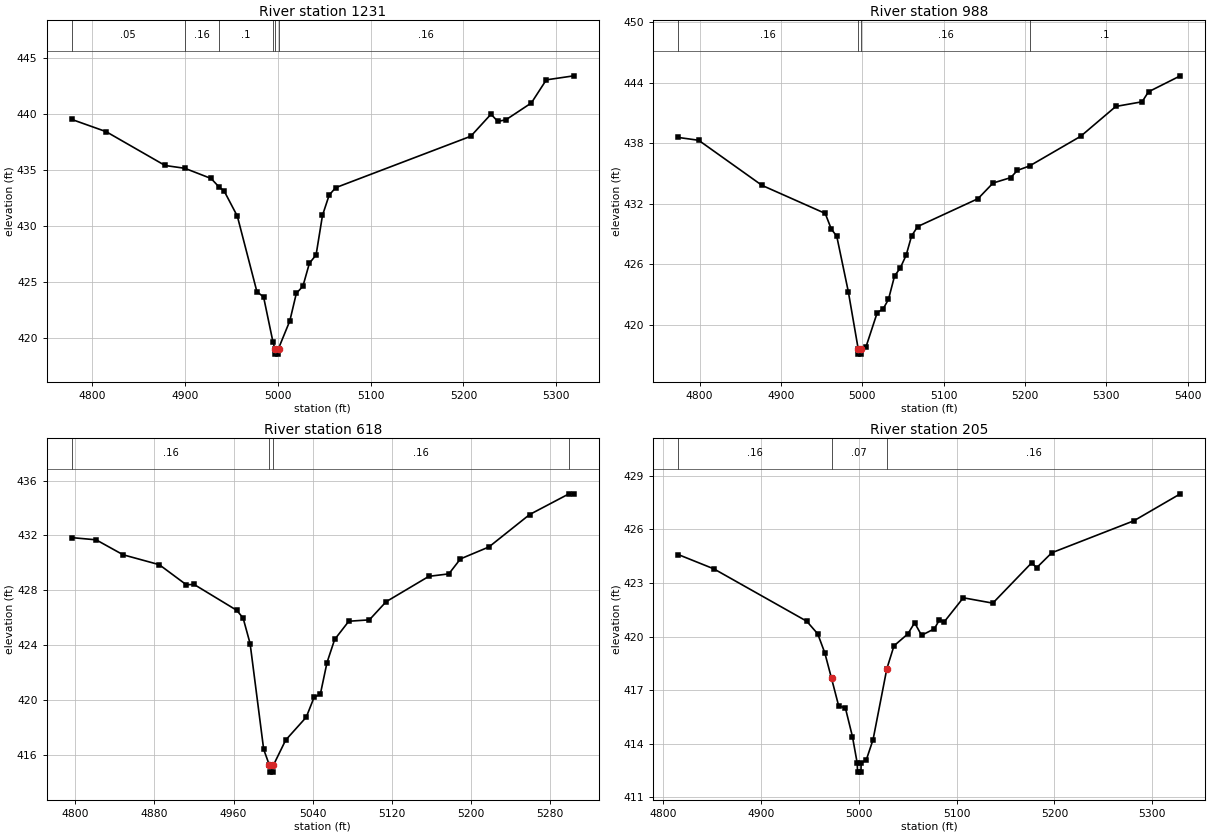
Type RM Length L Ch R = 1 ,1231    ,243,243,243
BEGIN DESCRIPTION:
DUCK CREEK TRIB 28 3 1 20
END DESCRIPTION:
XS GIS Cut Line= 3
      3507650.64     10407470.74      3507877.43      10407692.1
      3508073.84     10407800.61
#Sta/Elev= 30
  4777.8  439.49  4814.8   438.4  4878.4  435.38  4899.7  435.13    4928  434.22
  4936.6  433.46  4942.1   433.1  4956.3  430.86  4977.4  424.12  4984.6  423.65
  4994.8   419.6  4996.7  419.05    4997  418.55  5000.5  418.55  5000.7  419.05
  5012.9  421.52  5019.9  423.97    5027  424.61    5034  426.66  5041.2   427.4
  5048.1  430.93  5055.3  432.74  5062.3   433.4    5208  437.99  5229.8  439.96
  5237.1  439.31  5245.9  439.46  5273.3  440.96  5289.4  443.02  5319.1  443.38
#Mann= 6 ,-1 , 0
  4777.8     .05       0  4899.7     .16       0  4936.6      .1       0
  4994.8     .16       0  4996.7     .07       0  5000.7     .16       0
Bank Sta=4996.7,5000.7
XS Rating Curve= 0 ,0
Exp/Cntr=0.3,0.1

Type RM Length L Ch R = 1 ,988     ,370,370,370
BEGIN DESCRIPTION:
DUCK CREEK TRIB 28 3 1 3 0
END DESCRIPTION:
XS GIS Cut Line= 3
      3507479.19     10407629.15       3507712.5     10407836.41
      3507995.67     10407950.33
#Sta/Elev= 30
  4773.8  438.57  4798.9  438.29  4876.7  433.83  4954.5  431.05    4962   429.5
  4968.7  428.79  4982.9  423.31  4995.1  417.62  4995.4  417.12  4998.9  417.12
  4999.1  417.62  5004.7  417.85  5018.5  421.24  5025.6  421.58  5032.3  422.54
  5039.8  424.87  5046.5   425.6    5054  426.91  5060.7  428.82  5068.2  429.75
  5142.4  432.51  5160.9  434.06  5182.5  434.59  5190.8  435.31  5205.8  435.75
  5268.7  438.69  5311.8  441.64  5344.1   442.1    5352  443.09  5391.1  444.67
#Mann= 4 ,-1 , 0
  4773.8     .16       0  4995.1     .07       0  4999.1     .16       0
  5205.8      .1       0
Bank Sta=4995.1,4999.1
XS Rating Curve= 0 ,0
Exp/Cntr=0.3,0.1

Type RM Length L Ch R = 1 ,618     ,413,413,413
BEGIN DESCRIPTION:
DUCK CREEK TRIB 28 3 1 2 0
END DESCRIPTION:
XS GIS Cut Line= 3
      3507273.08     10407906.97      3507513.93     10408105.51
      3507707.05     10408133.72
#Sta/Elev= 30
  4796.5  431.84  4821.1  431.68  4848.4  430.59  4884.9  429.87  4912.2  428.41
  4920.1  428.43  4963.1  426.55  4969.6  425.99  4976.7  424.12  4990.4  416.42
  4996.2  415.26  4996.5  414.76    5000  414.76  5000.2  415.26  5012.6  417.09
  5033.4  418.76  5041.3   420.2  5047.7  420.45  5054.4  422.74  5062.1  424.42
  5076.4  425.75  5097.2  425.85  5114.1  427.17  5157.3  429.02  5177.5   429.2
  5189.2  430.29    5218  431.16  5259.1  433.52  5298.9  435.03  5303.8  435.03
#Mann= 4 ,-1 , 0
  4796.5     .16       0  4996.2     .07       0  5000.2     .16       0
  5298.9      .1       0
Bank Sta=4996.2,5000.2
XS Rating Curve= 0 ,0
Exp/Cntr=0.3,0.1

Type RM Length L Ch R = 1 ,205     ,0,0,0
BEGIN DESCRIPTION:
DUCK CREEK TRIB 28 3 1 1 0
END DESCRIPTION:
XS GIS Cut Line= 4
      3507125.48     10408115.25      3507121.14     10408246.57
      3507207.94     10408337.72      3507462.96     10408311.67
#Sta/Elev= 30
  4815.2  424.59  4851.6  423.79  4946.6  420.86  4957.9  420.15  4965.1  419.09
    4972  417.66  4979.3  416.12  4986.2     416  4993.4   414.4  4998.3  412.91
  4998.6  412.41  5002.1  412.41  5002.3  412.91  5007.6   413.1  5014.5  414.23
  5028.6   418.2  5035.9  419.48  5050.1  420.15    5057  420.77  5064.1  420.07
  5077.1  420.43  5082.4  420.93  5087.4  420.83  5106.8  422.17    5137  421.87
  5176.8  424.13  5181.8  423.85  5197.3  424.69  5281.3  426.48  5328.8  427.99
#Mann= 3 , 0 , 0
  4815.2     .16       0    4972     .07       0  5028.6     .16       0
Bank Sta=4972,5028.6
XS Rating Curve= 0 ,0
Exp/Cntr=0.3,0.1

Chan Stop Cuts=-1
Use User Specified Reach Order=0
Composite Channel Slope=5