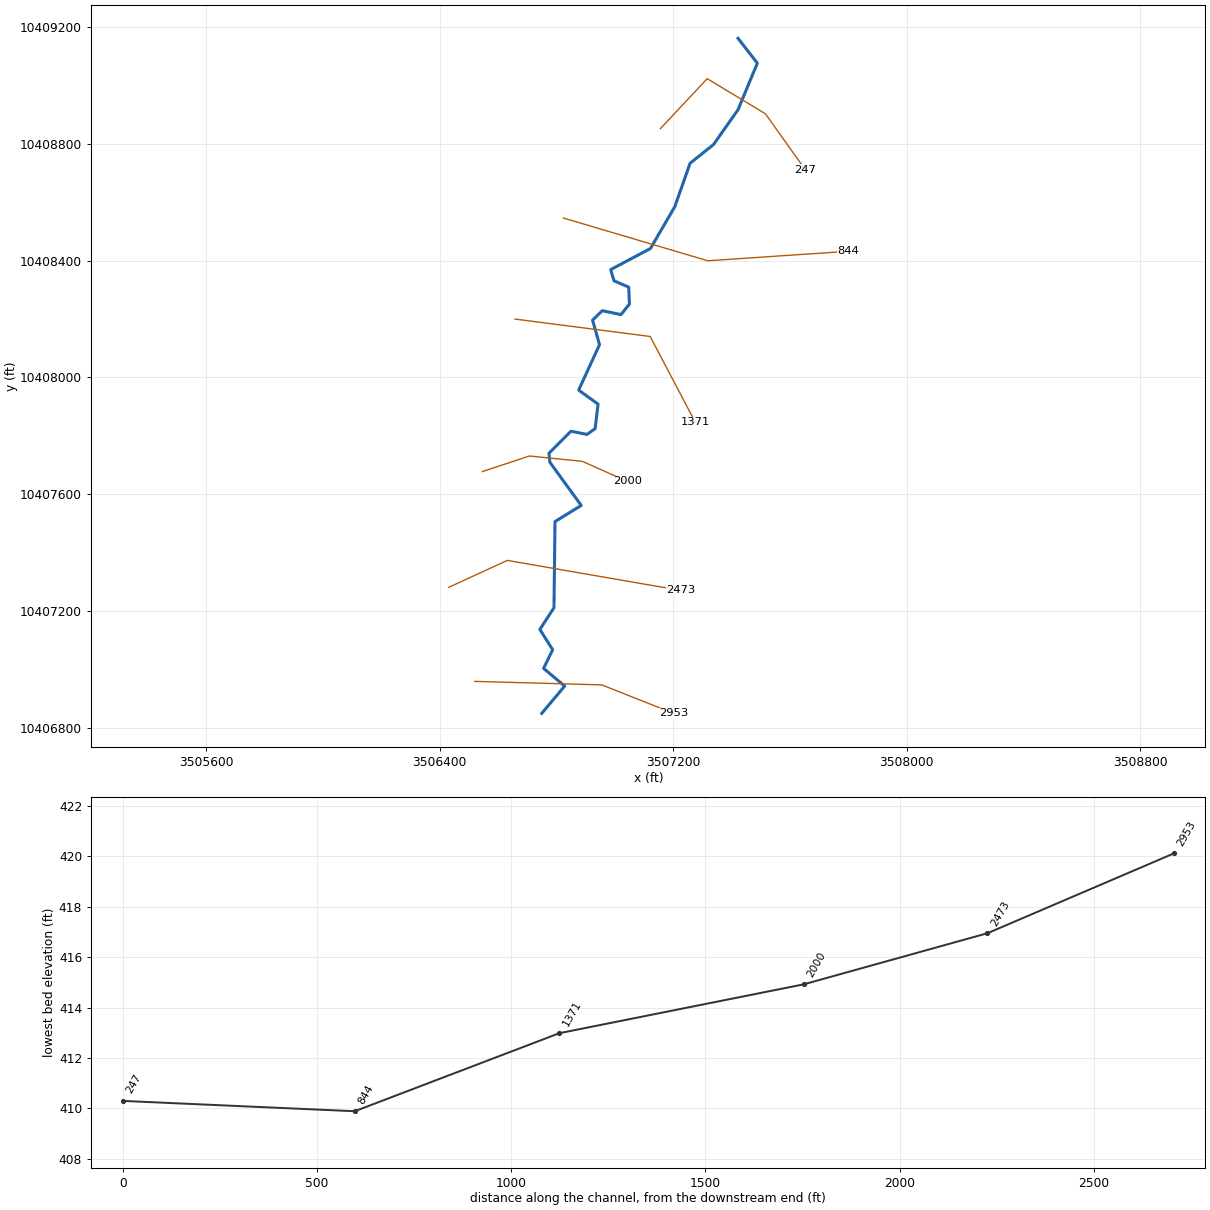
--- DUCK CREEK TRIB 28 3.prj (project) ---

Proj Title=DUCK CREEK TRIB 28 3 Base Level Engineering
Current Plan=p01
Default Exp/Contr=0.3,0.1
English Units
Geom File=g01
Flow File=f01
Plan File=p01
Y Axis Title=Elevation
X Axis Title(PF)=Main Channel Distance
X Axis Title(XS)=Station
BEGIN DESCRIPTION:
DUCK CREEK TRIB 28 3
END DESCRIPTION:
DSS Export Rating Curves= 0
DSS Export Rating Curve Sorted= 0
DSS Export Volume Flow Curves= 0
DXF OffsetX= 0
DXF OffsetY= 0
DXF ScaleX= 1
DXF ScaleY= 10

--- DUCK CREEK TRIB 28 3.p01 (plan) ---

Plan Title=Multiple Run
Short Identifier=Multiple
Geom File=g01
Flow File=f01
Subcritical Flow
K Sum by GR= 0
Std Step Tol= 0.01
Critical Tol= 0.01
Num of Std Step Trials= 20
Max Error Tol= 0.3
Flow Tol Ratio= 0.001
Split Flow NTrial= 30
Split Flow Tol= 0.02
Split Flow Ratio= 0.02
Log Output Level= 0
Friction Slope Method= 1
Unsteady Friction Slope Method= 2
Unsteady Bridges Friction Slope Method= 1
Parabolic Critical Depth
Global Vel Dist=  1 , 1 , 1
Global Log Level= 0
CheckData=True
Encroach Param= -1, 0, 0, 0
BEGIN DESCRIPTION:
Multiple Run
END DESCRIPTION:

--- DUCK CREEK TRIB 28 3.f01 (steady flow) ---

Flow Title=Multiple
Number of Profiles=7
Profile Names=10-year,25-year,50-year,1pct_min,100-year,1pct_plu,500-year
River Rch & RM= DUCK CREEK TRIB ,Reach-1,2953
     384     502     594     516     698     944     958
River Rch & RM= DUCK CREEK TRIB ,Reach-1,844
     547     732     880     775    1048    1417    1479
Boundary for River Rch & Prof#=DUCK CREEK TRIB ,Reach-1,1
Up Type=0
Dn Type=3
Dn Slope=0.005
Boundary for River Rch & Prof#=DUCK CREEK TRIB ,Reach-1,2
Up Type=0
Dn Type=3
Dn Slope=0.005
Boundary for River Rch & Prof#=DUCK CREEK TRIB ,Reach-1,3
Up Type=0
Dn Type=3
Dn Slope=0.005
Boundary for River Rch & Prof#=DUCK CREEK TRIB ,Reach-1,4
Up Type=0
Dn Type=3
Dn Slope=0.005
Boundary for River Rch & Prof#=DUCK CREEK TRIB ,Reach-1,5
Up Type=0
Dn Type=3
Dn Slope=0.005
Boundary for River Rch & Prof#=DUCK CREEK TRIB ,Reach-1,6
Up Type=0
Dn Type=3
Dn Slope=0.005
Boundary for River Rch & Prof#=DUCK CREEK TRIB ,Reach-1,7
Up Type=0
Dn Type=3
Dn Slope=0.005

--- DUCK CREEK TRIB 28 3.g01 (geometry) ---

Geom Title=Existing Conditions
Program Version=4.10

River Reach=DUCK CREEK TRIB ,Reach-1
Reach XY= 30
      3506749.68     10406849.06      3506828.26     10406942.53
      3506755.91     10407003.13      3506787.06     10407067.08
      3506743.23     10407136.65      3506791.57     10407210.89
      3506795.08     10407505.99      3506884.97     10407561.43
      3506777.33     10407709.48      3506774.49     10407740.47
      3506849.71     10407815.76      3506904.53     10407804.58
      3506932.51     10407824.28      3506942.56     10407908.51
      3506876.13     10407956.53      3506947.62     10408112.34
      3506923.86     10408196.27      3506957.19     10408228.63
      3507021.09      10408215.2      3507050.14     10408251.28
       3507047.6     10408309.28      3506997.22     10408330.93
      3506985.76     10408369.27      3507122.11     10408441.64
       3507205.5     10408584.95      3507257.94     10408733.73
      3507337.81     10408797.47      3507421.92     10408916.72
      3507488.31     10409076.58      3507422.11     10409161.64

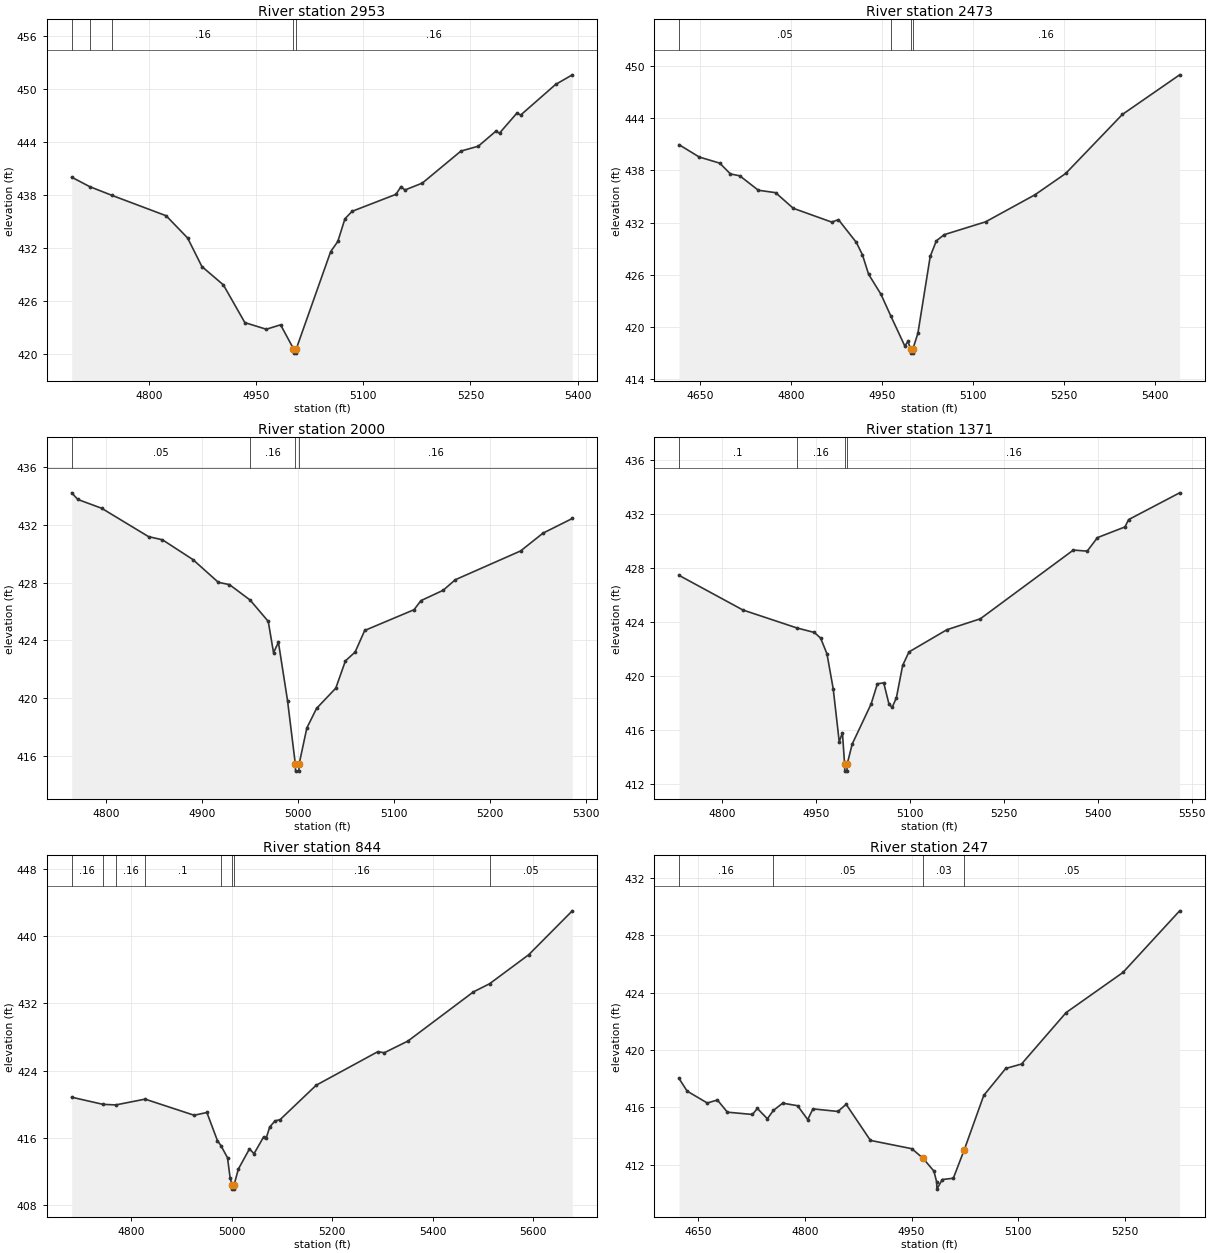
Type RM Length L Ch R = 1 ,2953    ,480,480,480
BEGIN DESCRIPTION:
DUCK CREEK TRIB 28 3 4 1
END DESCRIPTION:
XS GIS Cut Line= 3
      3506520.03     10406958.59      3506955.12     10406946.66
      3507201.41     10406849.01
#Sta/Elev= 30
  4692.2  440.01  4717.4  438.94    4748  437.97  4824.3  435.65  4854.3  433.14
  4874.3  429.91  4904.4  427.83  4934.4  423.57  4964.4  422.82  4984.4  423.32
  5002.4  420.62  5002.6  420.12  5006.1  420.12  5006.4  420.62  5054.4  431.59
  5064.4  432.74  5074.4  435.31  5084.4  436.15  5145.7  438.07  5152.9  438.95
  5158.2  438.56  5182.6  439.34  5236.6  442.96  5260.9  443.51  5285.2  445.19
  5290.6  444.99  5314.9  447.25  5320.3  447.04    5369  450.49  5392.4  451.58
#Mann= 5 ,-1 , 0
  4692.2      .1       0  4717.4     .05       0    4748     .16       0
  5002.4     .07       0  5006.4     .16       0
Bank Sta=5002.4,5006.4
XS Rating Curve= 0 ,0
Exp/Cntr=0.3,0.1

Type RM Length L Ch R = 1 ,2473    ,473,473,473
BEGIN DESCRIPTION:
DUCK CREEK TRIB 28 3 6 0
END DESCRIPTION:
XS GIS Cut Line= 3
      3506431.03     10407280.86      3506631.77     10407373.09
       3507227.3     10407270.04
#Sta/Elev= 30
  4615.4  440.97  4648.7  439.55  4682.6  438.84  4700.1   437.6  4715.6  437.38
  4746.1  435.72  4774.6  435.44  4803.7  433.64  4867.1  432.05  4878.2  432.33
  4907.7  429.71  4917.8  428.27  4927.9  426.04  4948.3  423.73  4964.2  421.28
  4987.6  417.77  4992.7   418.3    4997  417.45  4997.3  416.95  5000.8  416.95
    5001  417.45  5009.2  419.24  5029.5   428.1  5039.6  429.89  5052.5   430.6
  5120.8  432.08    5202  435.19  5252.8  437.65  5346.2  444.45  5440.7  449.02
#Mann= 4 ,-1 , 0
  4615.4     .05       0  4964.2     .16       0    4997     .07       0
    5001     .16       0
Bank Sta=4997,5001
XS Rating Curve= 0 ,0
Exp/Cntr=0.3,0.1

Type RM Length L Ch R = 1 ,2000    ,629,629,629
BEGIN DESCRIPTION:
DUCK CREEK TRIB 28 3 5 0
END DESCRIPTION:
XS GIS Cut Line= 4
      3506546.06     10407677.35      3506707.51     10407730.73
       3506888.5      10407712.5      3507043.47     10407643.48
#Sta/Elev= 30
  4764.1  434.23  4770.5  433.77  4795.3  433.16  4844.2  431.19  4858.7  430.97
  4890.4   429.6  4916.9  428.02  4928.5  427.86    4950  426.79  4968.9  425.31
  4974.4  423.14  4979.5  423.86    4989  419.81  4997.1  415.42  4997.3  414.92
  5000.8  414.92  5001.1  415.42  5009.1  417.91  5019.2  419.27  5039.3  420.68
  5049.3  422.57  5059.4  423.18  5069.4  424.68  5120.8  426.12    5128  426.75
  5151.2  427.47  5163.8   428.2  5231.9   430.2  5255.1  431.43  5285.7  432.45
#Mann= 4 ,-1 , 0
  4764.1     .05       0    4950     .16       0  4997.1     .07       0
  5001.1     .16       0
Bank Sta=4997.1,5001.1
XS Rating Curve= 0 ,0
Exp/Cntr=0.3,0.1

Type RM Length L Ch R = 1 ,1371    ,527,527,527
BEGIN DESCRIPTION:
DUCK CREEK TRIB 28 3 4 0
END DESCRIPTION:
XS GIS Cut Line= 3
      3506657.79     10408199.92      3507121.14     10408140.23
      3507275.87     10407845.91
#Sta/Elev= 30
  4731.2  427.45  4833.2  424.89  4919.7  423.56  4947.3  423.23  4957.4  422.81
  4967.5  421.65  4977.5  419.06  4987.1  415.15  4992.2  415.82  4995.7  413.48
    4996  412.98  4999.5  412.98  4999.7  413.48  5007.8  414.98    5038  417.94
  5048.1  419.44  5058.2   419.5  5066.6  417.93  5071.6  417.69  5078.4   418.4
  5088.4  420.79  5098.5  421.79    5159  423.43  5212.5  424.24  5361.1  429.32
  5383.2  429.24  5399.6  430.24  5443.6  431.03  5449.3  431.57  5530.9  433.55
#Mann= 4 ,-1 , 0
  4731.2      .1       0  4919.7     .16       0  4995.7     .07       0
  4999.7     .16       0
Bank Sta=4995.7,4999.7
XS Rating Curve= 0 ,0
Exp/Cntr=0.3,0.1

Type RM Length L Ch R = 1 ,844     ,597,597,597
BEGIN DESCRIPTION:
DUCK CREEK TRIB 28 3 2 0
END DESCRIPTION:
XS GIS Cut Line= 3
      3506823.87     10408546.04      3507318.62     10408399.57
      3507798.74     10408432.01
#Sta/Elev= 30
  4681.2  420.83  4743.4  419.98  4768.9  419.91  4827.4   420.6  4925.1  418.68
  4950.5  419.01  4971.4  415.67  4978.5  415.06  4991.6  413.61  4996.8  411.22
  5000.7  410.38  5000.9  409.88  5004.4  409.88  5004.7  410.38  5013.1  412.26
  5035.3  414.67  5044.4   414.1  5063.3  416.08  5068.5  415.93  5075.7  417.29
  5086.1     418  5096.5  418.17  5168.3  422.26  5290.9  426.25    5304  426.13
    5351  427.52  5481.3  433.37  5513.5  434.34  5591.6   437.8  5678.4  443.03
#Mann= 8 ,-1 , 0
  4681.2     .16       0  4743.4      .1       0  4768.9     .16       0
  4827.4      .1       0  4978.5     .16       0  5000.7     .07       0
  5004.7     .16       0  5513.5     .05       0
Bank Sta=5000.7,5004.7
XS Rating Curve= 0 ,0
Exp/Cntr=0.3,0.1

Type RM Length L Ch R = 1 ,247     ,0,0,0
BEGIN DESCRIPTION:
DUCK CREEK TRIB 28 3 1 0
END DESCRIPTION:
XS GIS Cut Line= 4
      3507155.86     10408852.04      3507316.45     10409023.48
       3507516.1     10408903.04       3507652.8       10408711.
#Sta/Elev= 30
  4623.1  418.01  4634.5  417.13  4662.8   416.3    4677  416.51  4691.1  415.66
  4726.3   415.5  4733.2  415.92  4747.3   415.2  4755.7  415.78  4768.8  416.29
  4789.8  416.11    4804  415.14  4811.3  415.89  4846.5  415.71    4858  416.21
  4892.2  413.69  4950.4  413.11    4966  412.45  4981.4  411.55  4985.3  410.79
  4985.6  410.29  4993.2  410.96  5008.7  411.05  5024.2  413.05  5051.5  416.83
  5082.4  418.71  5104.6  419.02  5167.3  422.61  5247.2  425.41  5326.9  429.71
#Mann= 4 ,-1 , 0
  4623.1     .16       0  4755.7     .05       0    4966     .03       0
  5024.2     .05       0
Bank Sta=4966,5024.2
XS Rating Curve= 0 ,0
Exp/Cntr=0.3,0.1

Chan Stop Cuts=-1
Use User Specified Reach Order=0
Composite Channel Slope=5