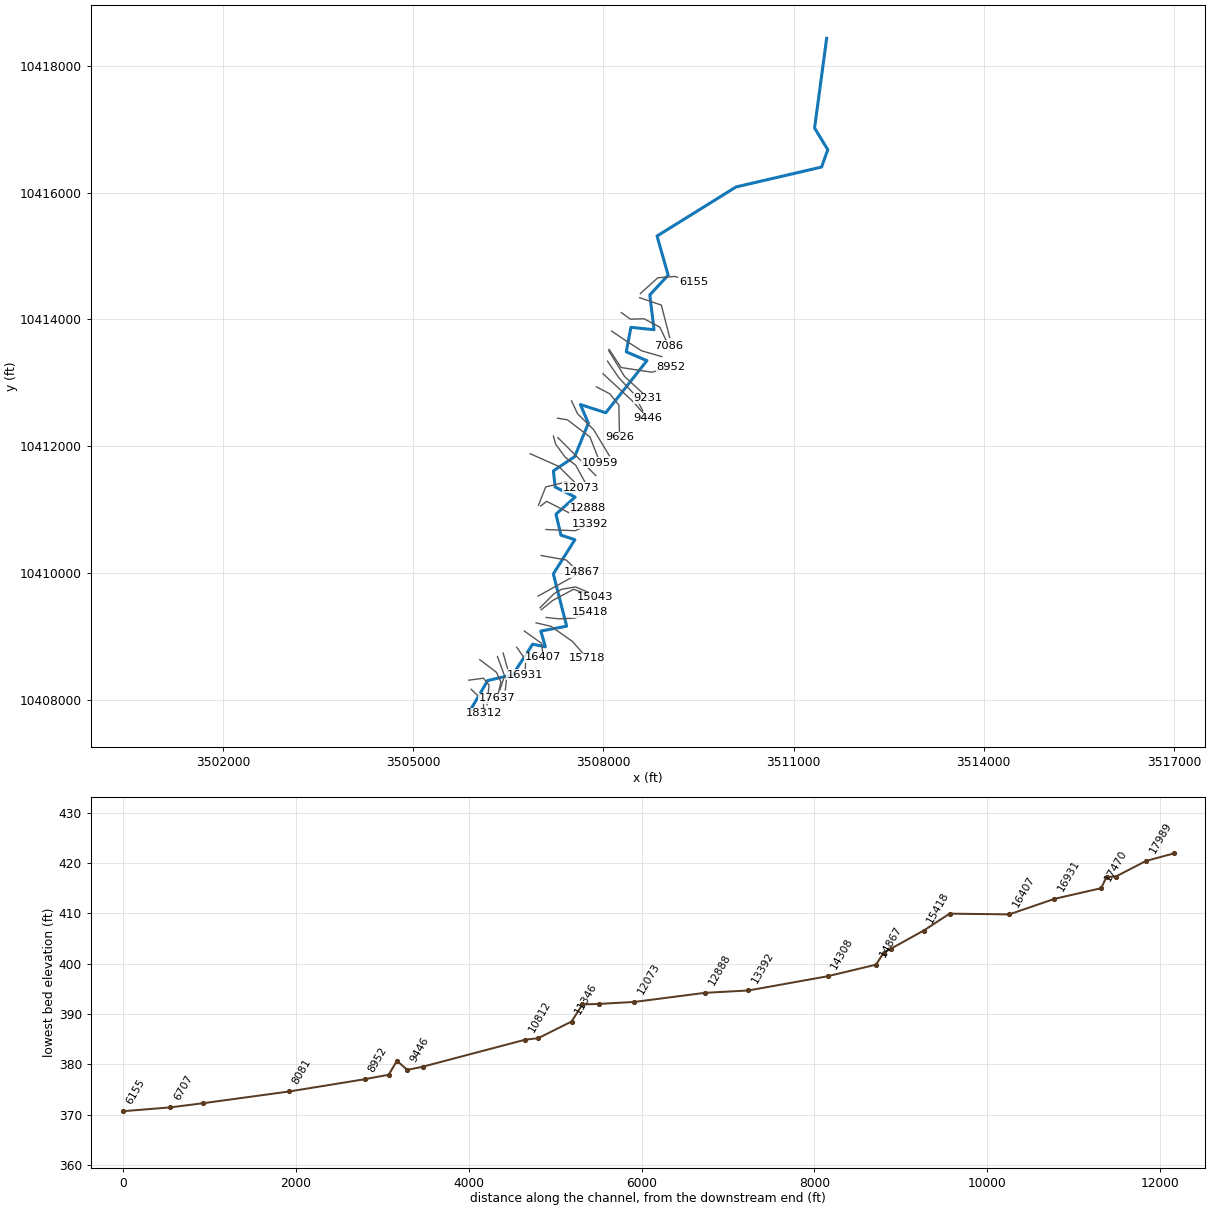
--- DUCK CREEK TRIB 28.prj (project) ---

Proj Title=DUCK CREEK TRIB 28 Base Level Engineering
Current Plan=p01
Default Exp/Contr=0.3,0.1
English Units
Geom File=g01
Flow File=f01
Plan File=p01
Y Axis Title=Elevation
X Axis Title(PF)=Main Channel Distance
X Axis Title(XS)=Station
BEGIN DESCRIPTION:
DUCK CREEK TRIB 28
END DESCRIPTION:
DSS Export Rating Curves= 0
DSS Export Rating Curve Sorted= 0
DSS Export Volume Flow Curves= 0
DXF OffsetX= 0
DXF OffsetY= 0
DXF ScaleX= 1
DXF ScaleY= 10

--- DUCK CREEK TRIB 28.p01 (plan) ---

Plan Title=Multiple Run
Short Identifier=Multiple
Geom File=g01
Flow File=f01
Subcritical Flow
K Sum by GR= 0
Std Step Tol= 0.01
Critical Tol= 0.01
Num of Std Step Trials= 20
Max Error Tol= 0.3
Flow Tol Ratio= 0.001
Split Flow NTrial= 30
Split Flow Tol= 0.02
Split Flow Ratio= 0.02
Log Output Level= 0
Friction Slope Method= 1
Unsteady Friction Slope Method= 2
Unsteady Bridges Friction Slope Method= 1
Parabolic Critical Depth
Global Vel Dist=  1 , 1 , 1
Global Log Level= 0
CheckData=True
Encroach Param= -1, 0, 0, 0
BEGIN DESCRIPTION:
Multiple Run
END DESCRIPTION:

--- DUCK CREEK TRIB 28.f01 (steady flow) ---

Flow Title=Multiple
Program Version=4.10
Number of Profiles= 7
Profile Names=10-year,25-year,50-year,1pct_min,100-year,1pct_plu,500-year
River Rch & RM=DUCK CREEK TRIB,Reach-1         ,18312
     430     563     668     580     785    1061    1078
River Rch & RM=DUCK CREEK TRIB,Reach-1         ,15718
     959    1324    1627    1458    1972    2667    2892
River Rch & RM=DUCK CREEK TRIB,Reach-1         ,15418
     959    1324    1627    1458    1972    2667    2892
River Rch & RM=DUCK CREEK TRIB,Reach-1         ,11668
    1201    1679    2079    1878    2540    3435    3782
River Rch & RM=DUCK CREEK TRIB,Reach-1         ,9446
    1368    1919    2382    2155    2914    3941    4353
River Rch & RM=DUCK CREEK TRIB,Reach-1         ,5822
    1503    2113    2624    2374    3211    4342    4797
Boundary for River Rch & Prof#=DUCK CREEK TRIB,Reach-1         , 1
Up Type= 0
Dn Type= 3
Dn Slope=0.005
Boundary for River Rch & Prof#=DUCK CREEK TRIB,Reach-1         , 2
Up Type= 0
Dn Type= 3
Dn Slope=0.005
Boundary for River Rch & Prof#=DUCK CREEK TRIB,Reach-1         , 3
Up Type= 0
Dn Type= 3
Dn Slope=0.005
Boundary for River Rch & Prof#=DUCK CREEK TRIB,Reach-1         , 4
Up Type= 0
Dn Type= 3
Dn Slope=0.005
Boundary for River Rch & Prof#=DUCK CREEK TRIB,Reach-1         , 5
Up Type= 0
Dn Type= 3
Dn Slope=0.005
Boundary for River Rch & Prof#=DUCK CREEK TRIB,Reach-1         , 6
Up Type= 0
Dn Type= 3
Dn Slope=0.005
Boundary for River Rch & Prof#=DUCK CREEK TRIB,Reach-1         , 7
Up Type= 0
Dn Type= 3
Dn Slope=0.005
DSS Import GetInterval= 0
DSS Import GetPeak= 0
DSS Import FillOption= 0

--- DUCK CREEK TRIB 28.g01 (geometry) ---

Geom Title=Existing Conditions
Program Version=4.10

River Reach=DUCK CREEK TRIB ,Reach-1
Reach XY= 30
      3505892.74     10407818.46      3506176.79     10408304.12
      3506573.31     10408397.37      3506885.48      10408877.1
      3507087.05     10408836.82      3507014.49     10409085.12
      3507422.11     10409161.64      3507212.22      10409986.4
      3507552.35      10410525.8      3507332.29     10410596.98
      3507253.73     10410928.14      3507556.25     10411197.67
      3507240.71     10411356.96      3507213.37      10411611.3
      3507548.66     10411834.51       3507764.8     10412363.15
      3507638.93     10412656.55      3508039.11     10412527.21
      3508688.08      10413348.9      3508362.53     10413488.03
      3508435.27     10413874.32       3508799.9     10413837.08
      3508733.64     10414385.61      3509022.93      10414696.8
      3508847.54     10415314.14      3510093.63     10416088.07
      3511441.82     10416401.64      3511539.94     10416675.59
      3511331.82     10417016.61      3511522.28     10418431.59

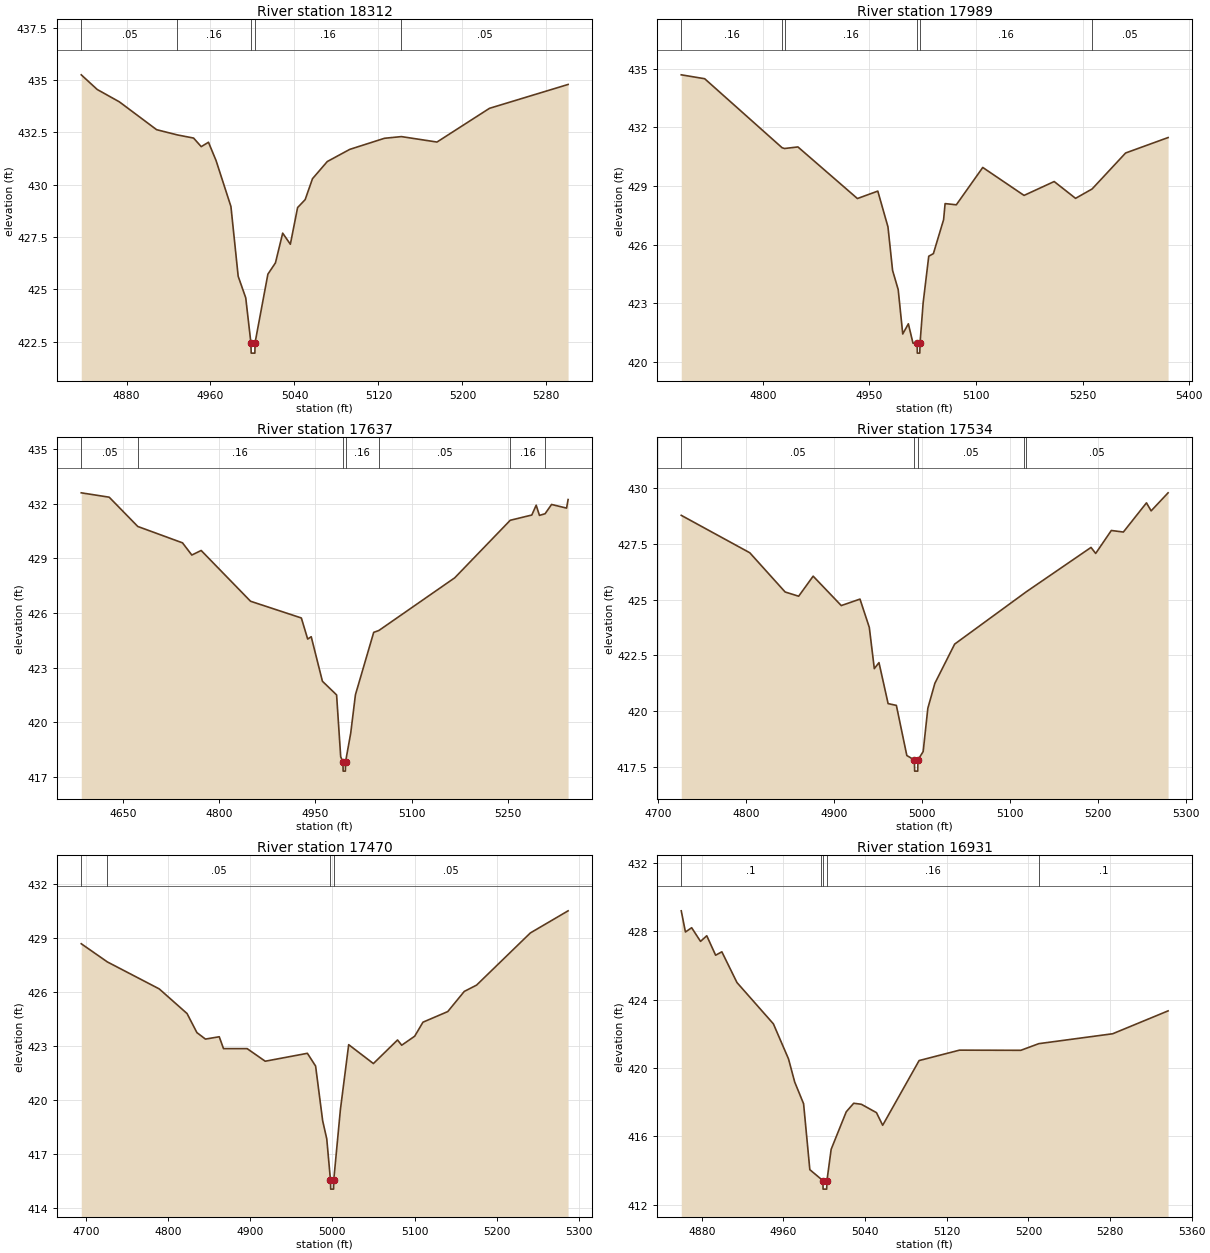
Type RM Length L Ch R = 1 ,18312   ,323,323,323
BEGIN DESCRIPTION:
DUCK CREEK TRIB 28 6 0
END DESCRIPTION:
XS GIS Cut Line= 3
      3505915.87      10408166.9      3506111.15     10407980.73
      3506111.15     10407786.73
#Sta/Elev= 30
  4836.9  435.24  4852.1  434.54  4873.2  433.95  4908.7  432.62  4928.5  432.37
  4943.9  432.22  4951.2  431.81  4958.1  432.02  4965.3  431.15  4979.5  428.95
  4986.4  425.62  4993.6  424.59  4998.5  422.45  4998.8  421.95  5002.3  421.95
  5002.5  422.45  5014.7  425.72  5021.9  426.26  5028.8  427.68  5036.1  427.15
    5043   428.9  5050.2  429.28  5057.2  430.28  5071.3   431.1  5092.7  431.68
  5125.8  432.21  5141.9  432.29  5175.8  432.03  5225.8  433.64  5300.7  434.78
#Mann= 5 ,-1 , 0
  4836.9     .05       0  4928.5     .16       0  4998.5     .07       0
  5002.5     .16       0  5141.9     .05       0
Bank Sta=4998.5,5002.5
XS Rating Curve= 0 ,0
Exp/Cntr=0.3,0.1

Type RM Length L Ch R = 1 ,17989   ,352,352,352
BEGIN DESCRIPTION:
Mapping XS eec03cb3
END DESCRIPTION:
XS GIS Cut Line= 4
      3505879.36     10408310.15      3506109.85     10408341.41
      3506198.39     10408233.33      3506167.14     10407922.11
#Sta/Elev= 30
  4685.3  434.69  4718.3  434.49  4827.2  430.96  4830.7  430.92  4849.5     431
  4933.2  428.36  4961.9  428.74  4976.2  426.91  4982.7  424.68  4990.6   423.7
    4997  421.43  5004.9  421.95  5011.4  420.96  5017.3  420.95  5017.5  420.45
    5021  420.45  5021.3  420.95  5025.7  423.02  5033.6  425.41  5040.1  425.54
  5054.5  427.28  5056.6   428.1  5072.4  428.04  5109.6  429.95  5167.7  428.52
  5210.1  429.23  5240.2  428.37  5263.5  428.85  5310.6  430.69  5370.4  431.48
#Mann= 6 ,-1 , 0
  4685.3     .16       0  4827.2     .05       0  4830.7     .16       0
  5017.3     .07       0  5021.3     .16       0  5263.5     .05       0
Bank Sta=5017.3,5021.3
XS Rating Curve= 0 ,0
Exp/Cntr=0.3,0.1

Type RM Length L Ch R = 1 ,17637   ,103,103,103
BEGIN DESCRIPTION:
DUCK CREEK TRIB 28 10
END DESCRIPTION:
XS GIS Cut Line= 4
      3506052.55     10408633.08      3506315.58     10408433.85
      3506385.89     10408280.21      3506326.05     10408026.51
#Sta/Elev= 30
  4584.6  432.61  4628.2  432.37  4672.8  430.76  4742.6  429.86  4757.1  429.19
  4771.7  429.44  4848.7  426.65    4928  425.73  4937.9  424.57  4943.4   424.7
  4960.9  422.25    4983   421.5  4989.4   418.1  4992.9  417.81  4993.2  417.31
  4996.7  417.31  4996.9  417.81    5005  419.39  5012.4  421.51  5040.9  424.94
  5048.9  425.04  5167.4  427.94  5253.9   431.1  5287.6  431.39  5294.4  431.93
  5299.5  431.37  5308.3  431.46  5318.4  431.97  5341.8  431.77  5344.2  432.24
#Mann= 7 ,-1 , 0
  4584.6     .05       0  4672.8     .16       0  4992.9     .07       0
  4996.9     .16       0  5048.9     .05       0  5253.9     .16       0
  5308.3     .05       0
Bank Sta=4992.9,4996.9
XS Rating Curve= 0 ,0
Exp/Cntr=0.3,0.1

Type RM Length L Ch R = 1 ,17534   ,64,64,64
BEGIN DESCRIPTION:
DUCK CREEK TRIB 28 29 4
END DESCRIPTION:
XS GIS Cut Line= 3
      3506331.21     10408682.55      3506443.19     10408377.86
      3506370.26     10408160.38
#Sta/Elev= 30
  4726.1  428.78  4804.1   427.1  4844.3  425.34  4859.7  425.15  4876.2  426.05
  4908.2  424.73  4929.5  425.02  4940.1  423.75  4945.8   421.9  4951.1  422.17
  4961.5  420.33  4970.9  420.25  4982.8     418  4991.4   417.8  4991.7   417.3
  4995.2   417.3  4995.4   417.8  5001.4  418.18  5006.7  420.12  5014.7  421.24
  5037.2     423    5116  425.27  5118.4  425.34  5192.4  427.34  5197.7  427.07
  5215.5   428.1  5229.2  428.03  5255.5  429.34  5260.8  428.98  5280.1  429.79
#Mann= 5 ,-1 , 0
  4726.1     .05       0  4991.4    .035       0  4995.4     .05       0
    5116     .16       0  5118.4     .05       0
Bank Sta=4991.4,4995.4
XS Rating Curve= 0 ,0
Exp/Cntr=0.3,0.1

Type RM Length L Ch R = 1 ,17470   ,539,539,539
BEGIN DESCRIPTION:
DUCK CREEK TRIB 28 29 1
END DESCRIPTION:
XS GIS Cut Line= 3
      3506421.05     10408737.25      3506491.36     10408488.54
      3506454.98     10408155.89
#Sta/Elev= 30
    4694  428.67  4725.8  427.66    4789  426.16  4822.9  424.79  4834.9  423.73
  4845.3  423.37  4862.1   423.5  4867.3  422.84  4896.1  422.84  4918.1  422.14
  4969.5  422.58  4979.5  421.87  4988.1  418.83  4993.1  417.82  4997.6  415.53
  4997.9  415.03  5001.4  415.03  5001.6  415.53  5009.7  419.45  5019.8  423.06
  5049.9  422.01  5079.3  423.32  5084.4  423.03  5100.2  423.53  5110.3  424.31
  5140.5   424.9  5160.6  426.02  5175.6  426.37  5241.1  429.27  5287.1   430.5
#Mann= 4 ,-1 , 0
    4694     .08       0  4725.8     .05       0  4997.6    .035       0
  5001.6     .05       0
Bank Sta=4997.6,5001.6
XS Rating Curve= 0 ,0
Exp/Cntr=0.3,0.1

Type RM Length L Ch R = 1 ,16931   ,524,524,524
BEGIN DESCRIPTION:
DUCK CREEK TRIB 28 3 0
END DESCRIPTION:
XS GIS Cut Line= 3
      3506634.57     10408829.72      3506775.22     10408630.47
      3506768.71     10408397.36
#Sta/Elev= 30
  4859.8  429.21  4863.9  427.97    4870  428.22  4878.7  427.42  4884.8  427.75
  4893.5  426.61  4899.6  426.81  4914.4  425.01  4950.1  422.59  4964.9  420.54
    4971  419.18  4979.7  417.91  4985.8  414.05  4996.6  413.51  4998.6  413.41
  4998.8  412.91  5002.3  412.91  5002.6  413.41  5006.7  415.24  5021.5  417.44
  5028.8  417.94  5036.3  417.88  5051.1  417.39  5057.2  416.65  5092.9  420.44
  5132.5  421.05  5192.6  421.04  5210.2  421.43  5282.6  422.01  5336.9  423.35
#Mann= 5 ,-1 , 0
  4859.8      .1       0  4996.6     .16       0  4998.6     .07       0
  5002.6     .16       0  5210.2      .1       0
Bank Sta=4998.6,5002.6
XS Rating Curve= 0 ,0
Exp/Cntr=0.3,0.1

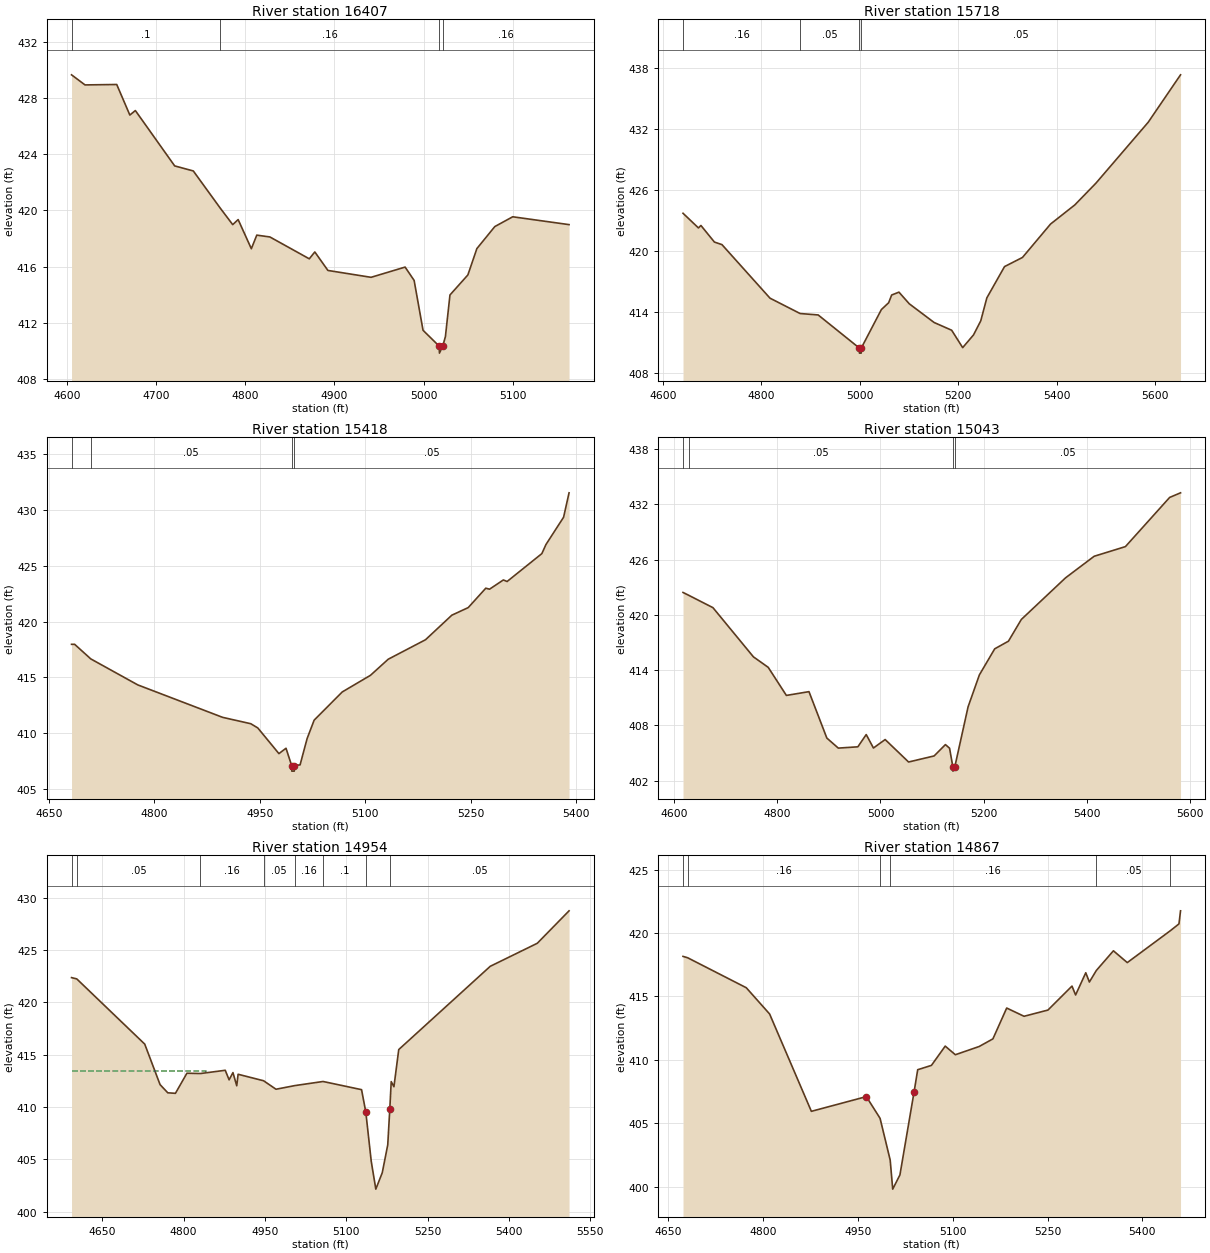
Type RM Length L Ch R = 1 ,16407   ,689,689,689
BEGIN DESCRIPTION:
DUCK CREEK TRIB 28 311 0
END DESCRIPTION:
XS GIS Cut Line= 3
       3506754.9     10409085.47      3507028.36     10408888.84
       3507051.8     10408668.79
#Sta/Elev= 30
  4605.1  429.68  4620.2  428.96  4655.8  428.99  4670.5  426.81  4676.7  427.13
  4720.8  423.18  4741.7  422.82    4772  420.16  4785.9  418.99    4792  419.35
  4806.8  417.27  4812.9  418.24  4827.6  418.11  4871.8  416.55    4878  417.04
  4892.7  415.72  4941.1  415.23  4979.3  415.96  4989.4  415.01  4999.4  411.45
  5017.5  410.32  5017.8  409.82  5021.5  410.32  5024.5     411  5029.6  413.97
  5049.7   415.4  5059.8  417.28  5079.9  418.85    5100  419.55  5163.2  418.99
#Mann= 4 ,-1 , 0
  4605.1      .1       0    4772     .16       0  5017.5     .07       0
  5021.5     .16       0
Bank Sta=5017.5,5021.5
XS Rating Curve= 0 ,0
Exp/Cntr=0.3,0.1

Type RM Length L Ch R = 1 ,15718   ,300,300,300
BEGIN DESCRIPTION:
DUCK CREEK TRIB 28 29 0
END DESCRIPTION:
XS GIS Cut Line= 4
      3506939.94     10409214.45      3507174.31      10409160.2
       3507516.1     10408919.31      3507747.72     10408654.14
#Sta/Elev= 30
  4640.9  423.71  4672.2  422.27  4677.3  422.51  4704.7  420.88    4720  420.63
  4817.6  415.37  4878.8  413.86  4915.5  413.72  4999.1  410.47  4999.4  409.97
  5002.9  409.97  5003.1  410.47  5043.9  414.25  5058.7  414.92  5064.8  415.68
  5079.6  415.96  5100.5  414.82    5151  412.98  5186.7  412.22  5209.1  410.51
  5231.1  411.76  5245.8  413.14  5258.2   415.4  5294.1  418.47  5330.6  419.37
  5387.6  422.65  5436.9  424.53  5479.7  426.66    5586  432.65  5651.7  437.31
#Mann= 4 ,-1 , 0
  4640.9     .16       0  4878.8     .05       0  4999.1     .03       0
  5003.1     .05       0
Bank Sta=4999.1,5003.1
XS Rating Curve= 0 ,0
Exp/Cntr=0.3,0.1

Type RM Length L Ch R = 1 ,15418   ,375,375,375
BEGIN DESCRIPTION:
DUCK CREEK TRIB 28 29 2
END DESCRIPTION:
XS GIS Cut Line= 4
      3507098.38     10409299.08       3507305.6     10409277.39
      3507547.57     10409288.24      3507788.37     10409377.86
#Sta/Elev= 30
  4682.1  417.97  4686.5  417.97  4709.5  416.66  4776.3  414.33    4897  411.42
    4937  410.85    4947  410.47    4977  408.17  4987.1  408.65  4995.1   407.1
  4995.3   406.6  4998.8   406.6  4999.1   407.1  5007.1  407.16  5017.1  409.52
  5027.1  411.17  5067.1   413.7  5107.2  415.19  5132.4  416.63  5185.5  418.38
  5222.9  420.58  5246.2  421.26  5271.2     423  5276.5  422.91  5296.2  423.74
  5301.5   423.6  5350.9   426.1  5356.8  426.92  5381.8  429.36  5389.6  431.55
#Mann= 4 ,-1 , 0
  4682.1     .16       0  4709.5     .05       0  4995.1     .03       0
  4999.1     .05       0
Bank Sta=4995.1,4999.1
XS Rating Curve= 0 ,0
Exp/Cntr=0.3,0.1

Type RM Length L Ch R = 1 ,15043   ,89,89,89
BEGIN DESCRIPTION:
DUCK CREEK TRIB 28 28 0
END DESCRIPTION:
XS GIS Cut Line= 4
      3507021.35     10409420.64       3507203.6     10409568.19
      3507531.29     10409743.97      3507866.57     10409619.19
#Sta/Elev= 30
  4617.4  422.43  4628.9  422.11  4675.4  420.78  4753.8  415.44  4782.5   414.3
  4817.7  411.25  4861.5  411.66  4896.1  406.62  4918.3  405.53  4956.2  405.67
  4972.4     407  4986.4  405.54  5009.1  406.46  5054.5  404.02    5104  404.68
  5125.9  405.91  5133.9  405.52  5140.2  403.53  5140.4  403.03  5144.2  403.53
  5169.8  410.01  5191.7  413.48  5221.4  416.31    5248  417.14    5273   419.5
  5358.7  424.02  5414.1  426.36  5474.7  427.41  5560.4  432.75  5581.5  433.25
#Mann= 4 ,-1 , 0
  4617.4     .16       0  4628.9     .05       0  5140.2     .03       0
  5144.2     .05       0
Bank Sta=5140.2,5144.2
XS Rating Curve= 0 ,0
Exp/Cntr=0.3,0.1

Type RM Length L Ch R = 1 ,14954   ,87,87,87
BEGIN DESCRIPTION:
DUCK CREEK TRIB 28 26 1
END DESCRIPTION:
XS GIS Cut Line= 6
      3507001.78       10409451.      3507219.88     10409670.18
      3507271.96     10409703.82      3507346.83     10409743.97
      3507561.68     10409780.86      3507786.11     10409686.53
#Sta/Elev= 30
  4593.4  422.36    4603  422.24  4728.4  416.01  4756.7  412.14  4770.9  411.36
    4785  411.31  4806.2  413.23  4831.1   413.2  4876.9  413.51    4884   412.6
  4891.1  413.29  4898.1  412.03  4900.6  413.13  4947.6  412.51  4970.5   411.7
  5005.5  412.05  5057.3  412.44  5128.3  411.66  5136.1  409.53  5146.2   404.8
  5154.6  402.16  5166.5  403.73  5176.6  406.39 5180.44  409.86    5183  412.43
    5188  411.94  5196.9  415.49  5365.6  423.44  5452.4  425.64    5511  428.74
#Mann= 8 ,-1 , 0
  4593.4     .16       0    4603     .05       0  4831.1     .16       0
  4947.6     .05       0  5005.5     .16       0  5057.3      .1       0
  5136.1     .07       0 5180.44     .05       0
#XS Ineff= 2 , 0
         4842.06  413.48
Permanent Ineff=
       F       F
Bank Sta=5136.1,5180.44
XS Rating Curve= 0 ,0
Exp/Cntr=0.3,0.1

Type RM Length L Ch R = 1 ,14867   ,559,559,559
BEGIN DESCRIPTION:
DUCK CREEK TRIB 28 27 0
END DESCRIPTION:
XS GIS Cut Line= 3
      3506972.46     10409636.53      3507473.79     10409915.41
      3507660.79     10410017.02
#Sta/Elev= 30
  4673.8  418.16  4681.2  418.05  4773.8  415.69  4810.7  413.62  4876.7  405.95
  4963.6  407.11  4985.3   405.4  5001.3  402.11  5005.3  399.82  5016.7  400.94
  5039.1  407.49  5044.8  409.23  5066.5  409.57  5088.3  411.09  5104.3  410.41
    5142  411.06  5163.7  411.66  5185.5  414.09  5212.9  413.44  5250.7  413.93
  5288.7  415.82  5294.4  415.12  5310.5  416.87  5316.2  416.14  5327.2  417.05
  5354.2   418.6  5376.1  417.67  5444.1  420.18  5457.8  420.72  5460.3  421.75
#Mann= 6 ,-1 , 0
  4673.8     .05       0  4681.2     .16       0  4985.3     .07       0
  5001.3     .16       0  5327.2     .05       0  5444.1     .16       0
Bank Sta=4963.6,5039.1
XS Rating Curve= 0 ,0
Exp/Cntr=0.3,0.1

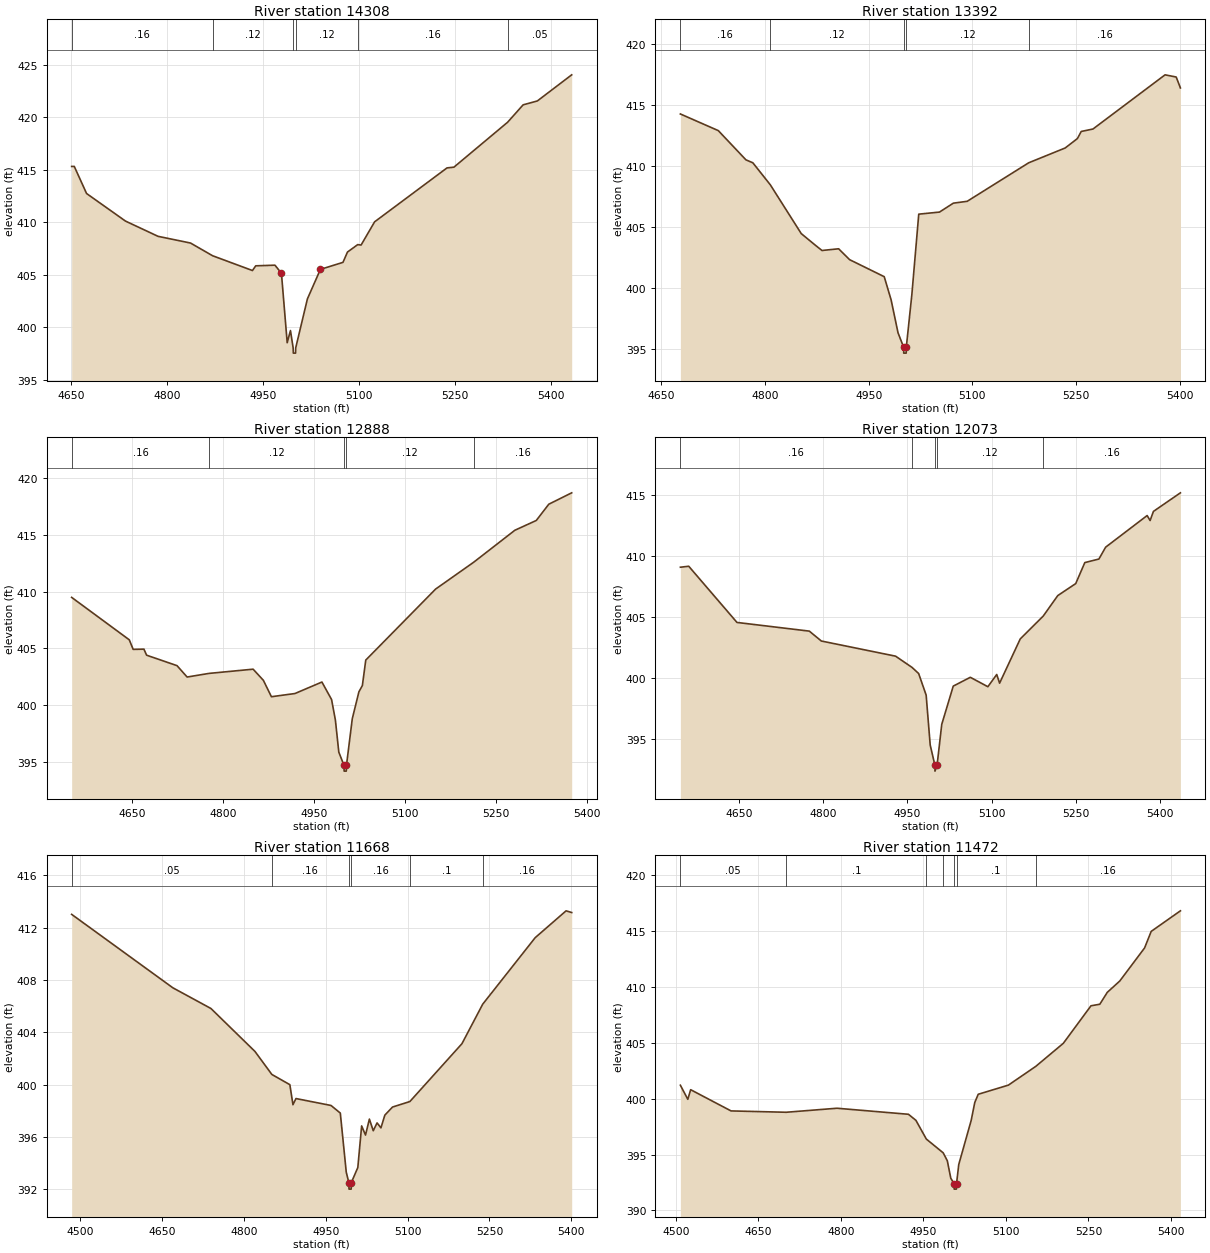
Type RM Length L Ch R = 1 ,14308   ,916,916,916
BEGIN DESCRIPTION:
DUCK CREEK TRIB 28 26 0
END DESCRIPTION:
XS GIS Cut Line= 4
      3507019.13     10410275.65      3507414.11     10410206.21
      3507554.08      10410068.4      3507737.84     10410080.29
#Sta/Elev= 30
  4651.1  415.31  4655.2  415.31  4674.4  412.73  4735.3   410.1  4786.1  408.65
  4836.9  408.01  4871.4   406.8  4933.7  405.39  4938.8  405.84  4968.9   405.9
    4979  405.13    4988  398.51  4993.1  399.67  4997.3  398.02  4997.6  397.52
  5001.1  397.52  5001.3  398.02  5019.6  402.69  5039.9   405.5  5075.2  406.17
  5082.2  407.15  5098.2  407.86  5103.5  407.82  5124.6  410.03  5237.8  415.17
  5248.6  415.24  5332.5  419.52  5356.8  421.18    5379  421.55  5432.7  424.04
#Mann= 6 ,-1 , 0
  4651.1     .16       0  4871.4     .12       0  4997.3     .07       0
  5001.3     .12       0  5098.2     .16       0  5332.5     .05       0
Bank Sta=4979,5039.9
XS Rating Curve= 0 ,0
Exp/Cntr=0.3,0.1

Type RM Length L Ch R = 1 ,13392   ,504,504,504
BEGIN DESCRIPTION:
DUCK CREEK TRIB 28 25 1
END DESCRIPTION:
XS GIS Cut Line= 3
      3507097.27     10410685.81      3507556.25     10410667.36
      3507797.64     10410775.61
#Sta/Elev= 30
  4677.4  414.24  4732.3  412.88  4772.3  410.49  4782.3  410.25  4807.6  408.45
  4852.4  404.46  4872.4  403.53  4882.4  403.08  4906.5  403.22  4922.4  402.33
  4972.5  400.94  4982.5  399.04  4992.5  396.35  5000.5  395.19  5000.8  394.69
  5004.3  394.69  5004.5  395.19  5012.5  399.47  5022.5  406.05  5052.5  406.22
  5072.6  406.95  5092.6   407.1  5181.7  410.25  5234.5  411.46  5252.2  412.23
  5257.7  412.81  5274.7  413.01  5379.1  417.44  5395.2  417.26  5401.3  416.37
#Mann= 5 ,-1 , 0
  4677.4     .16       0  4807.6     .12       0  5000.5     .07       0
  5004.5     .12       0  5181.7     .16       0
Bank Sta=5000.5,5004.5
XS Rating Curve= 0 ,0
Exp/Cntr=0.3,0.1

Type RM Length L Ch R = 1 ,12888   ,815,815,815
BEGIN DESCRIPTION:
DUCK CREEK TRIB 28 25 0
END DESCRIPTION:
XS GIS Cut Line= 4
      3507013.71      10411056.9      3507107.03     10411130.69
       3507465.1     10410947.31      3507758.72     10411018.55
#Sta/Elev= 30
  4550.7  409.49  4645.6  405.76    4652  404.92  4669.7  404.94  4674.1  404.41
  4724.2  403.49  4740.8  402.49    4777  402.81  4849.5  403.18  4866.4   402.2
  4879.6  400.76  4918.4  401.04  4962.8  402.05  4978.7  400.51    4985   398.7
  4990.6  395.89  4999.2  394.72  4999.4  394.22  5002.9  394.22  5003.2  394.72
  5012.8  398.83  5023.7  401.19  5029.4  401.74    5035  403.98    5150  410.22
  5212.7  412.58  5280.5  415.39  5315.8  416.25  5336.4  417.68  5374.1  418.68
#Mann= 5 ,-1 , 0
  4550.7     .16       0    4777     .12       0  4999.2     .07       0
  5003.2     .12       0  5212.7     .16       0
Bank Sta=4999.2,5003.2
XS Rating Curve= 0 ,0
Exp/Cntr=0.3,0.1

Type RM Length L Ch R = 1 ,12073   ,405,405,405
BEGIN DESCRIPTION:
DUCK CREEK TRIB 28 23 0
END DESCRIPTION:
XS GIS Cut Line= 4
      3506977.91     10411067.76      3507091.84     10411357.46
      3507411.94      10411434.5      3507647.22     10411347.76
#Sta/Elev= 30
  4545.4   409.1  4560.3  409.18  4646.3  404.58  4775.2  403.87  4796.7  403.06
    4929  401.82  4958.3   400.9  4970.1   400.4  4983.5  398.63  4990.7  394.55
    4999  392.91  4999.2  392.41    5003  392.91  5011.3  396.24  5031.8  399.37
  5062.2  400.09  5093.5  399.32  5109.3  400.32  5114.4  399.61  5151.2  403.23
  5192.3  405.11  5218.1  406.78  5250.1  407.76  5266.3  409.48  5291.4  409.77
  5303.4  410.74  5377.4  413.33  5382.7  412.92  5388.6  413.67  5436.7  415.19
#Mann= 5 ,-1 , 0
  4545.4     .16       0  4958.3     .12       0    4999     .07       0
    5003     .12       0  5192.3     .16       0
Bank Sta=4999,5003
XS Rating Curve= 0 ,0
Exp/Cntr=0.3,0.1

Type RM Length L Ch R = 1 ,11668   ,196,196,196
BEGIN DESCRIPTION:
DUCK CREEK TRIB 28 22 0
END DESCRIPTION:
XS GIS Cut Line= 3
      3506846.56     10411881.53      3507296.57     10411681.53
      3507596.55     10411381.54
#Sta/Elev= 30
  4484.1  413.01  4669.6   407.4  4739.4  405.82  4820.1  402.54  4851.1  400.78
  4884.1     400  4889.8  398.47  4895.3  398.94  4959.6  398.41  4976.6  397.83
  4987.5  393.32  4992.2  392.52  4992.6  392.02  4996.5  392.02  4996.8  392.52
  5008.7  393.67  5015.7  396.85  5022.8  396.15  5029.9  397.37    5037  396.48
    5044  397.08  5051.1   396.7  5058.2  397.67  5072.3  398.29  5104.1  398.71
  5199.6  403.13  5237.7  406.15  5333.9  411.23  5390.5  413.28  5400.8  413.15
#Mann= 6 ,-1 , 0
  4484.1     .05       0  4851.1     .16       0  4992.2     .07       0
  4996.8     .16       0  5104.1      .1       0  5237.7     .16       0
Bank Sta=4992.2,4996.8
XS Rating Curve= 0 ,0
Exp/Cntr=0.3,0.1

Type RM Length L Ch R = 1 ,11472   ,126,126,126
BEGIN DESCRIPTION:
DUCK CREEK TRIB 28 2 0
END DESCRIPTION:
XS GIS Cut Line= 5
      3507213.38     10412159.29      3507249.18     10412031.29
      3507396.75     10411828.39      3507563.85     10411701.43
      3507716.03     10411425.13
#Sta/Elev= 30
  4508.2  401.21  4521.7  399.95  4526.9  400.81  4600.3  398.91  4700.6  398.79
  4792.9  399.15  4922.8  398.61  4936.4  398.07  4955.4  396.39    4986  395.16
  4993.5  394.45  4999.8  392.89  5005.7  392.41    5006  391.91    5010  391.91
  5010.3  392.41  5014.3  394.11  5036.9  398.06  5043.4  399.66  5049.7   400.4
  5104.6  401.22  5154.4   402.9  5204.4  404.96  5254.7  408.32  5270.8  408.46
  5284.3  409.52  5307.1  410.54  5352.2   413.5  5364.2  414.98  5417.3  416.82
#Mann= 7 ,-1 , 0
  4508.2     .05       0  4700.6      .1       0  4955.4     .16       0
    4986      .1       0  5005.7     .07       0  5010.3      .1       0
  5154.4     .16       0
Bank Sta=5005.7,5010.3
XS Rating Curve= 0 ,0
Exp/Cntr=0.3,0.1

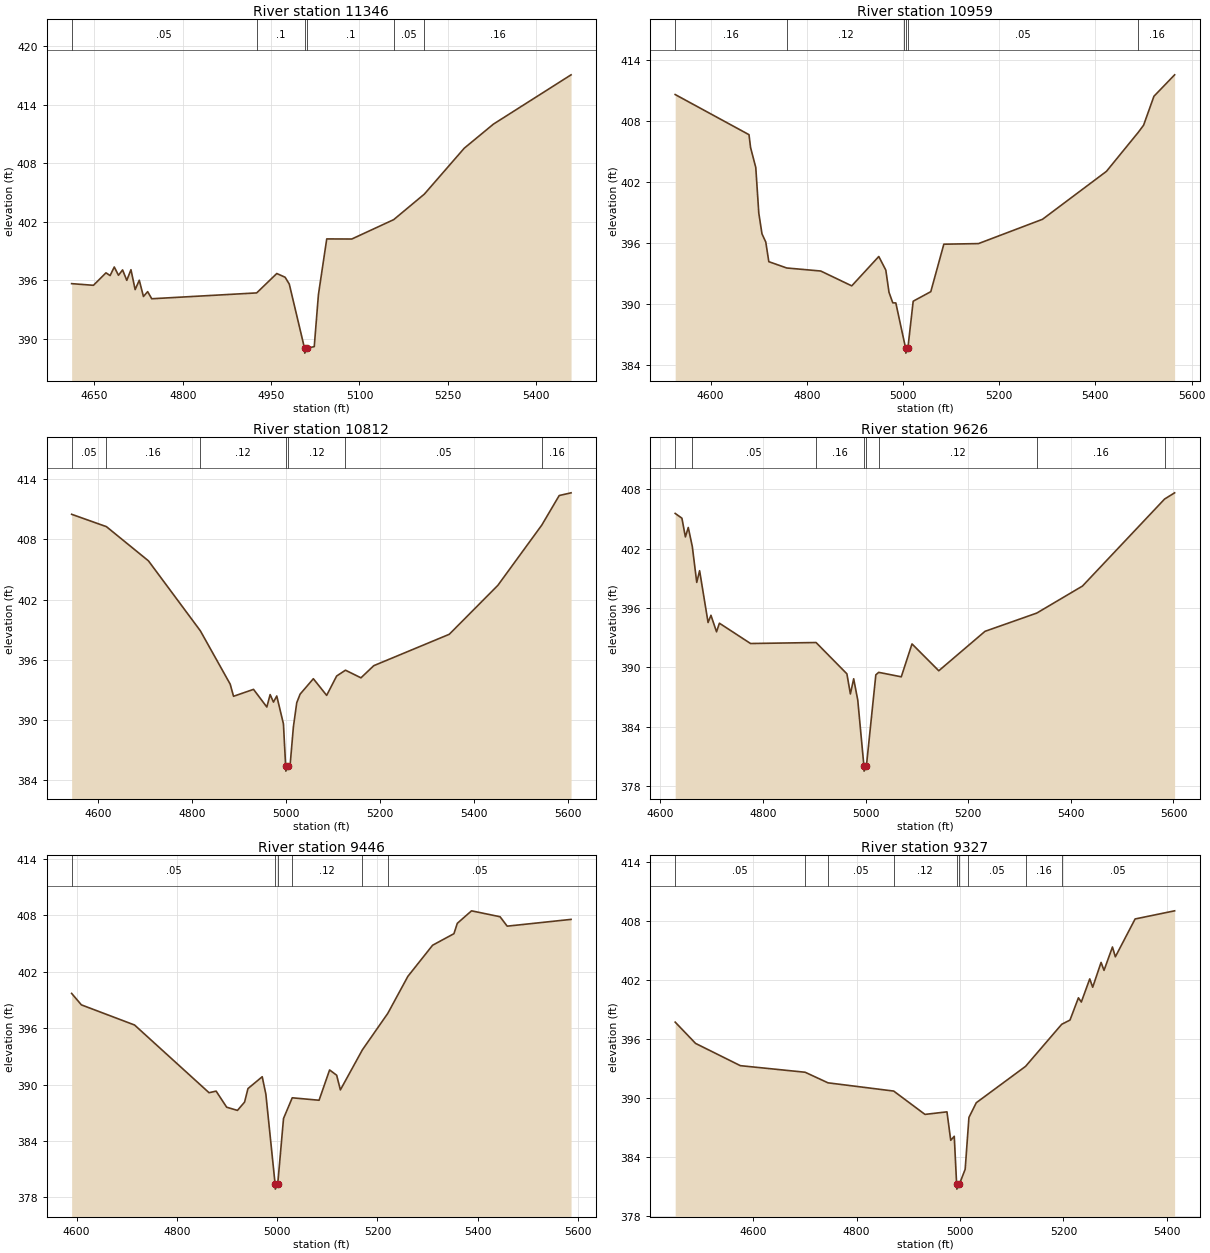
Type RM Length L Ch R = 1 ,11346   ,387,387,387
BEGIN DESCRIPTION:
DUCK CREEK TRIB 28 19 3
END DESCRIPTION:
XS GIS Cut Line= 3
      3507283.57      10412135.5       3507533.6     10411885.48
      3507882.99     10411536.09
#Sta/Elev= 30
  4611.5  395.64  4648.5  395.47  4669.8  396.75  4676.8  396.47  4683.9  397.35
    4691   396.5    4698  397.05  4705.1  395.98  4712.2  397.07  4719.3  395.03
  4726.3  395.99  4733.4  394.32  4740.5  394.82  4747.5  394.09  4925.6  394.69
  4959.7  396.68  4973.8   396.3  4980.9   395.6  5006.8  389.01  5007.2  388.51
  5011.5  389.01  5023.3  389.18  5030.4  394.52  5044.5  400.23    5087  400.22
  5158.2  402.21  5210.2  404.83  5277.9  409.54  5327.4  412.01  5459.2  417.07
#Mann= 6 ,-1 , 0
  4611.5     .05       0  4925.6      .1       0  5006.8     .07       0
  5011.5      .1       0  5158.2     .05       0  5210.2     .16       0
Bank Sta=5006.8,5011.5
XS Rating Curve= 0 ,0
Exp/Cntr=0.3,0.1

Type RM Length L Ch R = 1 ,10959   ,147,147,147
BEGIN DESCRIPTION:
DUCK CREEK TRIB 28 19 2
END DESCRIPTION:
XS GIS Cut Line= 4
      3507278.46     10412441.45      3507433.64     10412416.49
      3507789.54     10412145.23      3507947.52     10411741.61
#Sta/Elev= 30
  4526.5  410.64  4679.9  406.69  4683.2  405.42    4694  403.46  4700.3  398.96
  4706.9  396.93  4714.8  396.12  4721.1  394.19  4758.3  393.57  4829.1  393.27
  4893.5  391.81  4949.7   394.7  4964.3  393.36  4970.9  391.18  4978.8  390.14
  4985.1  390.13  5002.3  386.36  5005.5  385.69  5005.9  385.19  5010.2  385.69
  5021.2   390.3  5057.8  391.24  5084.9  395.91  5156.9  395.97  5289.9  398.36
  5422.9  403.08  5489.2  406.93  5500.1  407.62  5521.6  410.47  5564.6  412.58
#Mann= 6 ,-1 , 0
  4526.5     .16       0  4758.3     .12       0  5002.3     .05       0
  5005.5     .07       0  5010.2     .05       0  5489.2     .16       0
Bank Sta=5005.5,5010.2
XS Rating Curve= 0 ,0
Exp/Cntr=0.3,0.1

Type RM Length L Ch R = 1 ,10812   ,1186,1186,1186
BEGIN DESCRIPTION:
DUCK CREEK TRIB 28 19 1
END DESCRIPTION:
XS GIS Cut Line= 4
      3507498.76     10412715.93      3507593.14     10412513.06
      3507847.05     10412261.33      3508095.54     10411850.07
#Sta/Elev= 30
  4544.2  410.51  4618.1  409.28  4707.5  405.87  4817.8   398.9  4881.3  393.58
  4888.4  392.37  4930.9  393.06  4959.2   391.3  4966.2  392.54  4973.3  391.79
  4980.3   392.4  4994.5  389.62  4999.2  385.41  4999.6  384.91  5003.9  385.41
  5008.6  385.46  5015.7  389.34  5022.8  391.73  5029.9  392.58  5058.1  394.12
  5086.4  392.46  5107.6  394.39  5126.4  394.97  5159.3  394.21  5186.5  395.42
  5347.1  398.55  5450.4  403.43  5543.7  409.43  5580.8  412.38    5606  412.65
#Mann= 7 ,-1 , 0
  4544.2     .05       0  4618.1     .16       0  4817.8     .12       0
  4999.2     .07       0  5003.9     .12       0  5126.4     .05       0
  5543.7     .16       0
Bank Sta=4999.2,5003.9
XS Rating Curve= 0 ,0
Exp/Cntr=0.3,0.1

Type RM Length L Ch R = 1 ,9626    ,180,180,180
BEGIN DESCRIPTION:
DUCK CREEK TRIB 28 19 0
END DESCRIPTION:
XS GIS Cut Line= 4
      3507890.48     10412936.37      3508103.14      10412825.7
      3508245.28     10412648.84      3508256.13     10412142.09
#Sta/Elev= 30
  4628.7  405.54  4641.8  405.06  4648.6  403.17  4654.2  404.12  4662.1  402.19
  4670.7  398.58  4676.3  399.76  4692.8  394.53  4698.4  395.26  4709.3  393.59
  4714.9  394.46  4775.6  392.41  4903.3  392.51  4963.4  389.35  4970.2  387.32
  4976.6  388.85  4984.6  386.69  4996.6  380.03  4996.9  379.53  5001.4  380.03
  5019.8  389.25  5025.4   389.5  5069.4  389.05  5090.3  392.37  5142.5  389.66
  5232.6  393.64  5333.4  395.48  5422.6  398.21  5582.6  406.99  5602.2  407.62
#Mann= 8 ,-1 , 0
  4628.7      .1       0  4662.1     .05       0  4903.3     .16       0
  4996.6     .07       0  5001.4     .16       0  5025.4     .12       0
  5333.4     .16       0  5582.6     .05       0
Bank Sta=4996.6,5001.4
XS Rating Curve= 0 ,0
Exp/Cntr=0.3,0.1

Type RM Length L Ch R = 1 ,9446    ,119,119,119
BEGIN DESCRIPTION:
DUCK CREEK TRIB 28 57 0
END DESCRIPTION:
XS GIS Cut Line= 3
       3507995.7     10413142.55      3508453.62     10412718.28
      3508702.07     10412441.62
#Sta/Elev= 30
    4590   399.7  4609.5  398.48  4715.5  396.34  4864.1  389.14  4878.2  389.31
  4899.2   387.6  4920.7  387.26  4934.9  388.14  4941.7  389.58  4970.1  390.84
  4977.4  388.98  4995.9  379.39  4996.2  378.89    5001  379.39  5012.6   386.4
    5030   388.6  5083.5  388.34  5104.5  391.56  5118.6     391    5126  389.44
  5169.9   393.7  5220.6  397.58  5260.6  401.51  5309.9  404.82  5352.5  406.05
  5359.2  407.15  5387.6  408.48  5444.5  407.85  5458.7  406.85  5586.1  407.57
#Mann= 6 ,-1 , 0
    4590     .05       0  4995.9     .03       0    5001     .05       0
    5030     .12       0  5169.9     .16       0  5220.6     .05       0
Bank Sta=4995.9,5001
XS Rating Curve= 0 ,0
Exp/Cntr=0.3,0.1

Type RM Length L Ch R = 1 ,9327    ,96,96,96
BEGIN DESCRIPTION:
DUCK CREEK TRIB 28 16 0
END DESCRIPTION:
XS GIS Cut Line= 4
      3508066.23     10413341.13      3508245.28     10413079.61
       3508476.4     10412832.21      3508622.88     10412558.78
#Sta/Elev= 30
  4449.2  397.72  4488.6  395.55  4575.2  393.28  4700.4  392.61  4744.7  391.53
  4871.7  390.69  4932.2  388.31  4974.7  388.57    4982  385.67  4988.8  386.08
  4993.4  381.19  4993.8  380.69  4998.7  381.19  5009.9  382.71    5015  386.41
  5017.2     388  5031.4   389.5  5126.7  393.21  5196.6   397.5  5212.6  397.93
  5228.9   400.2  5234.5  399.77  5250.8  402.13  5256.5  401.28  5272.7  403.81
  5278.4     403  5294.7  405.38  5300.3  404.38  5338.5  408.24  5414.9  409.07
#Mann= 9 ,-1 , 0
  4449.2     .05       0  4700.4     .12       0  4744.7     .05       0
  4871.7     .12       0  4993.4     .07       0  4998.7     .12       0
    5015     .05       0  5126.7     .16       0  5196.6     .05       0
Bank Sta=4993.4,4998.7
XS Rating Curve= 0 ,0
Exp/Cntr=0.3,0.1

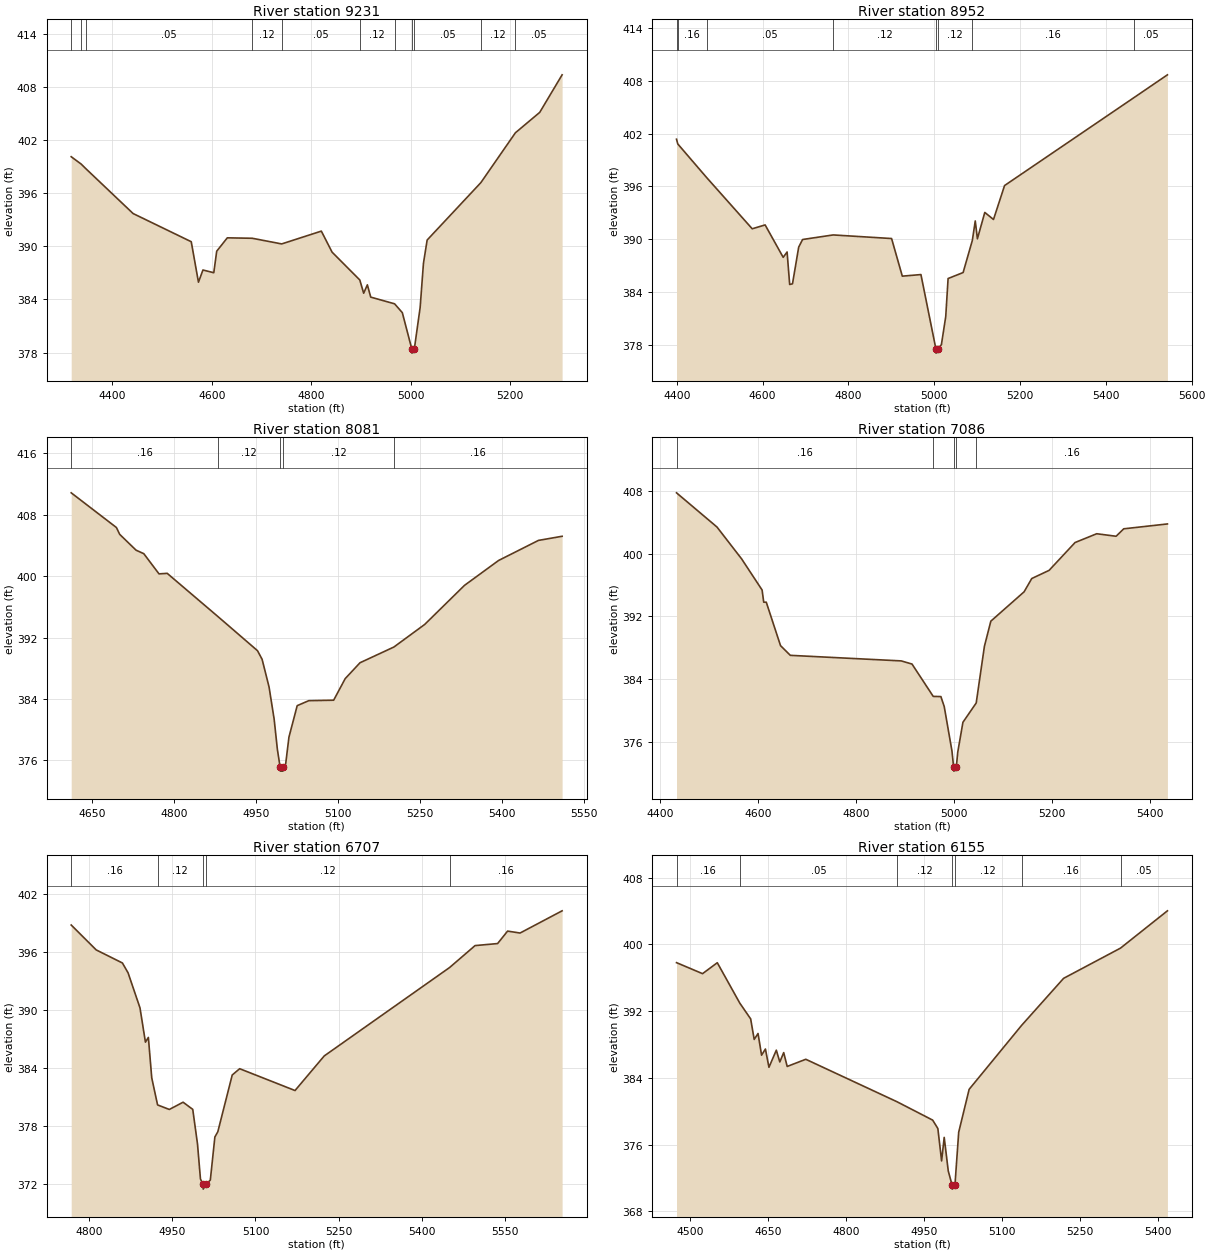
Type RM Length L Ch R = 1 ,9231    ,279,279,279
BEGIN DESCRIPTION:
DUCK CREEK TRIB 28 15 1
END DESCRIPTION:
XS GIS Cut Line= 3
      3508084.67     10413507.15      3508336.43     10413098.05
      3508709.35      10412755.4
#Sta/Elev= 30
  4317.4  400.16  4337.4  399.33  4346.4  398.83  4441.8  393.73  4558.7  390.54
  4573.2  385.96  4582.2  387.34    4604  387.03  4609.9  389.47  4631.2  390.98
  4681.4  390.93  4740.5  390.29  4820.2  391.74  4841.8  389.36  4897.5  386.21
  4905.3  384.71  4912.7  385.66  4919.5  384.27  4967.5  383.51    4983  382.51
  5001.9  378.43  5002.3  377.93  5007.2  378.43  5018.8  383.09  5025.5  388.11
  5032.9  390.73  5140.9  397.23  5210.3  402.87  5259.2  405.18  5304.2  409.43
#Mann= 11 ,-1 , 0
  4317.4     .05       0  4337.4     .16       0  4346.4     .05       0
  4681.4     .12       0  4740.5     .05       0  4897.5     .12       0
  4967.5     .05       0  5001.9     .04       0  5007.2     .05       0
  5140.9     .12       0  5210.3     .05       0
Bank Sta=5001.9,5007.2
XS Rating Curve= 0 ,0
Exp/Cntr=0.3,0.1

Type RM Length L Ch R = 1 ,8952    ,871,871,871
BEGIN DESCRIPTION:
DUCK CREEK TRIB 28 14 1
END DESCRIPTION:
XS GIS Cut Line= 4
      3508092.11     10413527.14      3508281.37     10413240.65
      3508767.48       10413166.      3509064.37     10413251.07
#Sta/Elev= 30
  4399.5  401.37  4402.5  400.83  4469.7  397.01  4575.9  391.18    4606  391.62
  4648.1  387.93  4657.2  388.54  4663.2  384.84  4669.8  384.92  4684.2  389.09
  4693.3  389.96  4764.6  390.48  4900.7  390.07  4925.7  385.79  4969.1  385.97
  5003.9  377.53  5004.3  377.03  5009.3  377.53  5016.8     378  5026.9  381.19
  5032.4  385.52  5067.4   386.2  5088.9  389.86  5095.7  392.07  5100.7  390.04
  5117.9  393.04  5138.2  392.24    5164   396.1  5465.7  406.11  5543.5   408.7
#Mann= 8 ,-1 , 0
  4399.5     .05       0  4402.5     .16       0  4469.7     .05       0
  4764.6     .12       0  5003.9     .07       0  5009.3     .12       0
  5088.9     .16       0  5465.7     .05       0
Bank Sta=5003.9,5009.3
XS Rating Curve= 0 ,0
Exp/Cntr=0.3,0.1

Type RM Length L Ch R = 1 ,8081    ,995,995,995
BEGIN DESCRIPTION:
DUCK CREEK TRIB 28 14 0
END DESCRIPTION:
XS GIS Cut Line= 4
      3508132.08     10413815.29      3508373.38     10413652.11
      3508602.55     10413504.54      3508923.76     10413412.52
#Sta/Elev= 30
  4611.9  410.86  4694.6  406.34  4700.6  405.45  4730.5  403.39  4744.7  402.93
  4772.5   400.3  4787.5  400.37  4881.1  394.69  4952.7  390.29  4961.1  389.17
  4973.8  385.57  4983.1  381.39    4989  377.46  4994.1   375.1  4994.5   374.6
  4999.1   374.6  4999.6   375.1  5004.2  375.53  5010.2  379.03  5025.3  383.13
  5046.5  383.78    5092  383.84  5113.1  386.65  5140.2  388.72  5202.2  390.77
  5258.5  393.71  5331.3   398.8  5393.8  402.05  5466.6  404.66  5509.9   405.2
#Mann= 5 ,-1 , 0
  4611.9     .16       0  4881.1     .12       0  4994.1     .07       0
  4999.6     .12       0  5202.2     .16       0
Bank Sta=4994.1,4999.6
XS Rating Curve= 0 ,0
Exp/Cntr=0.3,0.1

Type RM Length L Ch R = 1 ,7086    ,379,379,379
BEGIN DESCRIPTION:
Mapping XS b0b85826
END DESCRIPTION:
XS GIS Cut Line= 5
      3508283.11     10414106.97      3508428.94     10414002.81
      3508642.48     10414009.75      3508892.48     10413876.07
      3509031.35     10413580.97
#Sta/Elev= 30
  4433.9  407.77  4516.5  403.41  4566.9  399.34  4608.7  395.37    4612  393.82
  4617.2  393.82  4646.3  388.28  4666.3  387.04  4892.8  386.33  4914.8  385.93
  4958.2   381.8  4973.8  381.78  4980.6  380.51  4996.4  374.84  4999.8  372.77
  5000.3  372.27  5005.3  372.77  5008.2  374.68  5018.8   378.5  5045.9  380.96
  5062.7   388.2  5075.8   391.4  5143.7  395.14  5159.4  396.84  5194.8  397.88
  5247.8  401.43    5292  402.55  5331.6  402.23  5347.2  403.18  5436.4   403.8
#Mann= 5 ,-1 , 0
  4433.9     .16       0  4958.2     .12       0  4999.8     .07       0
  5005.3     .12       0  5045.9     .16       0
Bank Sta=4999.8,5005.3
XS Rating Curve= 0 ,0
Exp/Cntr=0.3,0.1

Type RM Length L Ch R = 1 ,6707    ,552,552,552
BEGIN DESCRIPTION:
DUCK CREEK TRIB 28 13 0
END DESCRIPTION:
XS GIS Cut Line= 3
      3508574.74     10414341.36      3508915.05     10414225.03
      3509046.95      10413716.5
#Sta/Elev= 30
  4767.8  398.79  4812.9  396.21  4860.1  394.86  4870.3  393.84  4891.8  390.21
  4901.6  386.66  4906.9  387.15    4913  382.96  4923.5  380.16  4944.7  379.69
  4969.5  380.44  4986.9   379.7  4995.5  376.11  5000.8  372.49  5005.3  371.94
  5005.8  371.44  5010.8  371.94  5018.6  372.38  5026.8  376.84  5032.1  377.38
  5058.1  383.26  5071.5  383.91  5171.3  381.65  5223.9  385.23    5450  394.39
  5495.9  396.66  5536.5  396.87  5554.5  398.16    5577  397.96  5652.8  400.26
#Mann= 5 ,-1 , 0
  4767.8     .16       0  4923.5     .12       0  5005.3     .07       0
  5010.8     .12       0    5450     .16       0
Bank Sta=5005.3,5010.8
XS Rating Curve= 0 ,0
Exp/Cntr=0.3,0.1

Type RM Length L Ch R = 1 ,6155    ,333,333,333
BEGIN DESCRIPTION:
DUCK CREEK TRIB 28 12 0
END DESCRIPTION:
XS GIS Cut Line= 4
      3508585.19     10414407.32      3508859.49     10414655.58
      3509126.85     10414676.42      3509421.97     10414593.09
#Sta/Elev= 30
  4473.1  397.81  4523.2  396.49  4551.6   397.8  4594.9  392.96  4615.8  391.07
  4622.6  388.61    4630  389.32  4636.8  386.72  4644.2  387.46    4651  385.27
  4665.2  387.32  4671.9  385.91  4679.4  387.03  4686.1  385.37  4721.9  386.23
  4897.5  381.14  4966.1  378.94  4976.1  377.93  4983.3  374.05  4988.3  376.87
  4996.1  372.85  5003.4  371.17  5003.8  370.67    5009  371.17  5016.2  377.49
  5036.3  382.63  5137.1  390.28  5218.1  395.93  5327.6  399.55  5417.9  404.02
#Mann= 7 ,-1 , 0
  4473.1     .16       0  4594.9     .05       0  4897.5     .12       0
  5003.4     .07       0    5009     .12       0  5137.1     .16       0
  5327.6     .05       0
Bank Sta=5003.4,5009
XS Rating Curve= 0 ,0
Exp/Cntr=0.3,0.1