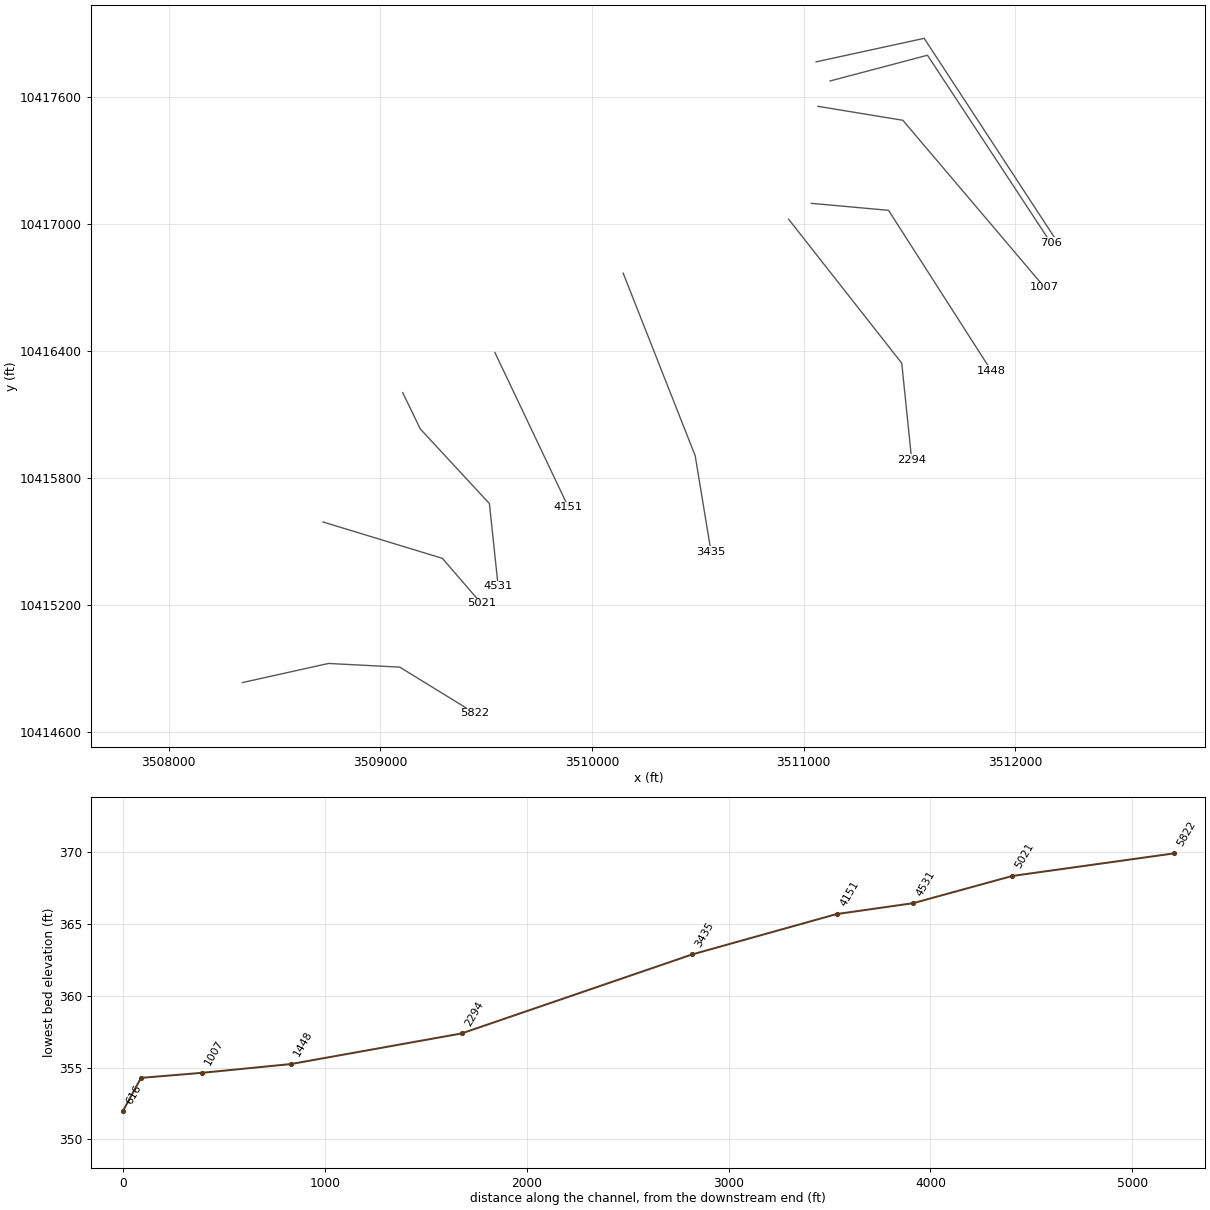
HEC-RAS study DUCK CREEK TRIB 28.prj: DUCK CREEK TRIB 28 Base Level Engineering

--- DUCK CREEK TRIB 28.g01 (geometry) --- (continued)

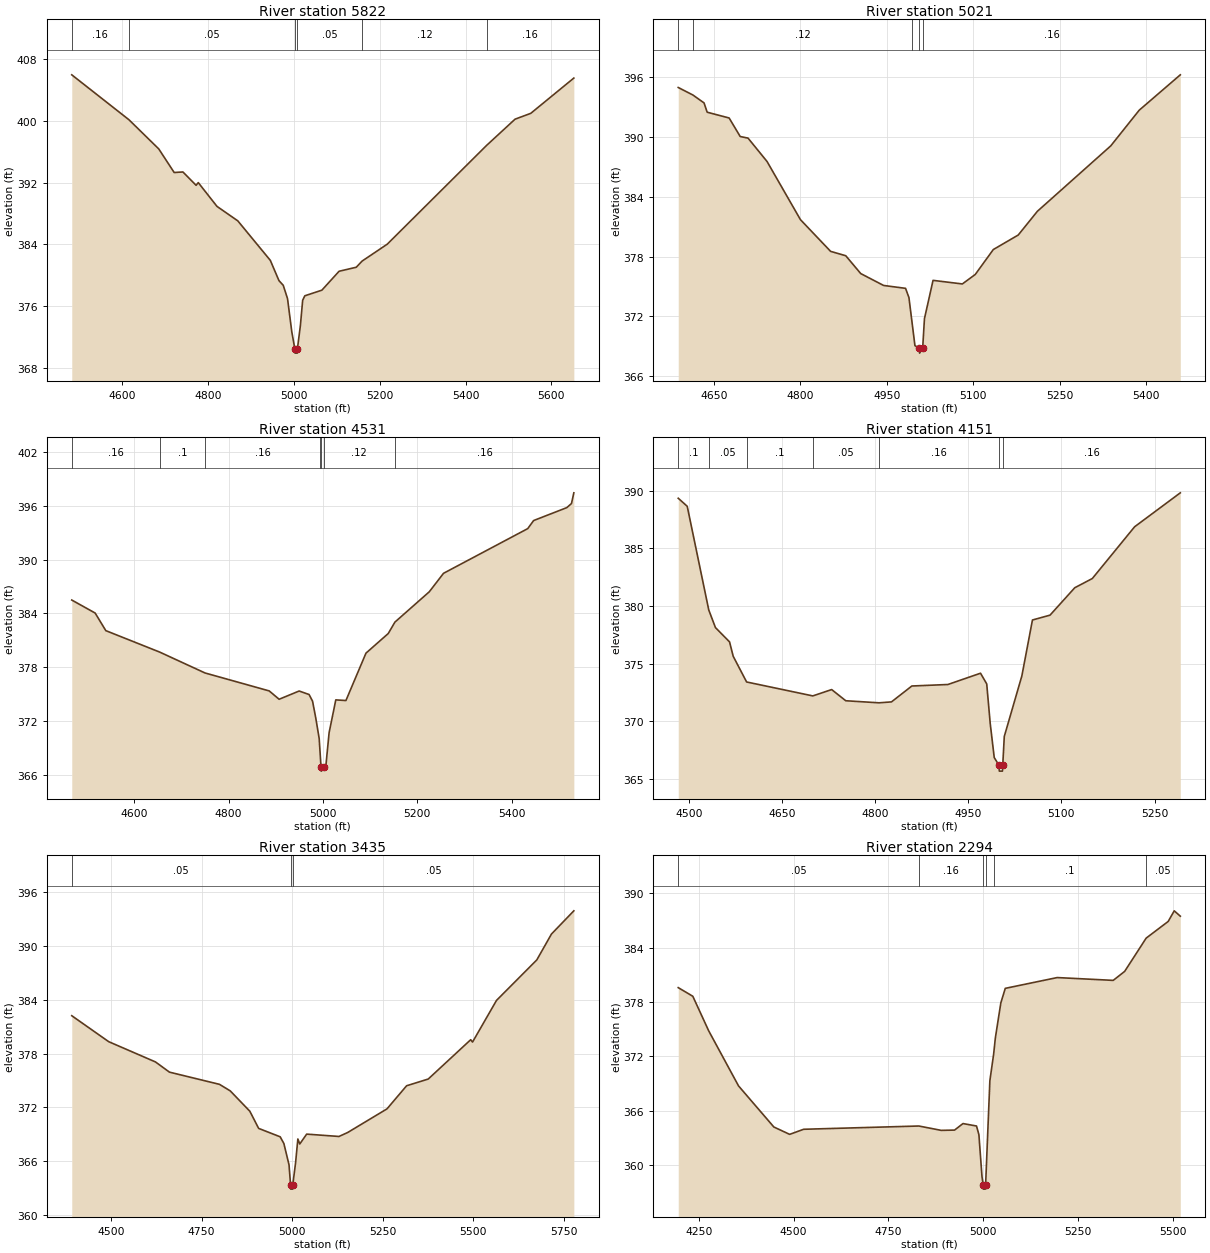
Type RM Length L Ch R = 1 ,5822    ,801,801,801
BEGIN DESCRIPTION:
DUCK CREEK TRIB 28 17 0
END DESCRIPTION:
XS GIS Cut Line= 4
      3508349.03     10414832.66      3508755.33     10414922.94
      3509092.13     10414905.58       3509447.6      10414687.1
#Sta/Elev= 30
  4481.8  405.96  4615.1  400.14  4684.6  396.36  4720.6   393.3    4741  393.37
  4771.7  391.64  4776.8  391.99  4820.4  388.91    4869  387.03  4944.8  381.91
  4964.9  379.29  4974.9  378.68  4984.9  376.95  4994.9  372.63  5002.1  370.39
  5002.5  369.89  5007.3  369.89  5007.8  370.39  5014.9  373.47  5020.2  376.74
  5025.2  377.32    5065  378.05  5105.1   380.5  5145.1  381.02  5158.8  381.82
  5217.4  384.01  5449.2  396.82  5515.4  400.21  5552.1  400.97  5652.5  405.54
#Mann= 6 ,-1 , 0
  4481.8     .16       0  4615.1     .05       0  5002.1     .04       0
  5007.8     .05       0  5158.8     .12       0  5449.2     .16       0
Bank Sta=5002.1,5007.8
XS Rating Curve= 0 ,0
Exp/Cntr=0.3,0.1

Type RM Length L Ch R = 1 ,5021    ,490,490,490
BEGIN DESCRIPTION:
DUCK CREEK TRIB 28 17
END DESCRIPTION:
XS GIS Cut Line= 3
      3508729.28     10415591.35      3509293.52     10415419.47
      3509477.14     10415206.68
#Sta/Elev= 30
    4588  394.97  4613.6  394.21  4632.8  393.42  4638.2  392.49  4676.3  391.91
  4695.5  390.05  4709.1  389.89    4742  387.55    4800  381.71  4852.3  378.53
  4878.6  378.09  4904.6   376.3  4944.2  375.11  4982.3  374.82  4988.2  373.89
  4994.1  371.16  4998.6  369.07  5006.2  368.82  5006.7  368.32    5012  368.82
  5015.1  371.78    5030  375.62  5080.8  375.26  5103.2  376.21  5134.5  378.71
  5177.8  380.17    5211  382.55  5338.2  389.11  5387.6  392.69  5458.9  396.24
#Mann= 5 ,-1 , 0
    4588     .16       0  4613.6     .12       0  4994.1     .16       0
  5006.2     .07       0    5012     .16       0
Bank Sta=5006.2,5012
XS Rating Curve= 0 ,0
Exp/Cntr=0.3,0.1

Type RM Length L Ch R = 1 ,4531    ,380,380,380
BEGIN DESCRIPTION:
DUCK CREEK TRIB 28 9 0
END DESCRIPTION:
XS GIS Cut Line= 4
      3509106.03     10416202.45      3509189.35     10416030.58
      3509515.74     10415678.15      3509557.12     10415286.78
#Sta/Elev= 30
  4467.2   385.5  4516.8  384.05  4539.4  382.09  4653.6   379.7  4749.9  377.37
    4886  375.37    4907  374.44  4949.5  375.36  4970.5  374.97  4977.9  374.23
  4984.7  372.36    4992  370.05  4994.7  367.83  4995.8  366.93  4996.3  366.43
  5001.8  366.93  5006.2  367.04    5013  370.71  5027.2  374.37  5048.7   374.3
  5091.2  379.58  5138.5  381.77  5152.6  383.04  5225.5  386.42  5255.7  388.48
  5434.3  393.46  5446.8  394.36  5517.2   395.8  5527.1  396.26  5532.1  397.45
#Mann= 7 ,-1 , 0
  4467.2     .16       0  4653.6      .1       0  4749.9     .16       0
  4994.7     .12       0  4995.8     .07       0  5001.8     .12       0
  5152.6     .16       0
Bank Sta=4995.8,5001.8
XS Rating Curve= 0 ,0
Exp/Cntr=0.3,0.1

Type RM Length L Ch R = 1 ,4151    ,716,716,716
BEGIN DESCRIPTION:
DUCK CREEK TRIB 28 8 0
END DESCRIPTION:
XS GIS Cut Line= 2
      3509541.79     10416391.68      3509889.02     10415660.77
#Sta/Elev= 30
  4482.4  389.36  4496.9  388.66  4531.6  379.66  4542.4  378.13  4565.1  376.89
    4571  375.64  4592.6  373.41  4699.3   372.2  4729.7  372.75  4752.4  371.78
    4806   371.6  4826.1  371.68  4858.9  373.06    4917  373.19  4969.6  374.17
  4979.6  373.24  4985.2  369.82  4991.7  366.85  4999.4  366.17  4999.9  365.67
  5004.9  365.67  5005.4  366.17  5007.9  368.68  5036.2  373.93  5053.3  378.79
  5081.6  379.21  5121.5  381.59  5149.8  382.39  5217.9  386.88  5291.6  389.83
#Mann= 7 ,-1 , 0
  4482.4      .1       0  4531.6     .05       0  4592.6      .1       0
  4699.3     .05       0    4806     .16       0  4999.4     .07       0
  5005.4     .16       0
Bank Sta=4999.4,5005.4
XS Rating Curve= 0 ,0
Exp/Cntr=0.3,0.1

Type RM Length L Ch R = 1 ,3435    ,1141,1141,1141
BEGIN DESCRIPTION:
DUCK CREEK TRIB 28 7 0
END DESCRIPTION:
XS GIS Cut Line= 3
      3510147.68     10416766.72      3510487.97     10415903.85
      3510562.62      10415450.7
#Sta/Elev= 30
  4391.2  382.22  4493.3  379.32  4622.4  377.06  4661.1  375.92  4799.1  374.56
  4828.9  373.83    4883  371.56  4907.4  369.64  4966.9   368.7  4977.1  367.95
  4991.3  365.57  4995.5  363.36    4996  362.86  5001.2  362.86  5001.7  363.36
  5009.4   365.8  5015.7  368.46    5021   367.9    5040     369  5129.3  368.74
  5153.7  369.19  5261.9  371.82  5316.1   374.4  5375.8  375.15  5493.1  379.54
  5498.2  379.28  5564.4  383.93  5675.7  388.45  5716.2  391.34    5778  393.93
#Mann= 3 ,-1 , 0
  4391.2     .05       0  4995.5     .03       0  5001.7     .05       0
Bank Sta=4995.5,5001.7
XS Rating Curve= 0 ,0
Exp/Cntr=0.3,0.1

Type RM Length L Ch R = 1 ,2294    ,846,846,846
BEGIN DESCRIPTION:
DUCK CREEK TRIB 28 31
END DESCRIPTION:
XS GIS Cut Line= 3
      3510928.97     10417021.86      3511463.66     10416341.35
      3511510.44     10415885.69
#Sta/Elev= 30
    4196  379.59  4234.4  378.64  4276.4  374.82    4355  368.75  4448.1  364.22
  4489.7  363.41  4526.7  363.97  4830.3  364.33  4889.2  363.85  4924.4  363.88
  4946.6   364.6  4982.3  364.33  4988.6  363.37  4996.7  358.76  4999.9  357.87
  5000.4  357.37  5005.8  357.37  5006.3  357.87  5017.5  369.33  5027.4  372.24
    5032  374.06  5046.4  377.91  5058.1  379.51    5195   380.7  5342.6  380.39
  5372.8  381.38  5429.5  385.05  5487.6  386.89  5503.5  388.06  5519.5  387.47
#Mann= 6 ,-1 , 0
    4196     .05       0  4830.3     .16       0  4999.9     .07       0
  5006.3     .16       0  5027.4      .1       0  5429.5     .05       0
Bank Sta=4999.9,5006.3
XS Rating Curve= 0 ,0
Exp/Cntr=0.3,0.1

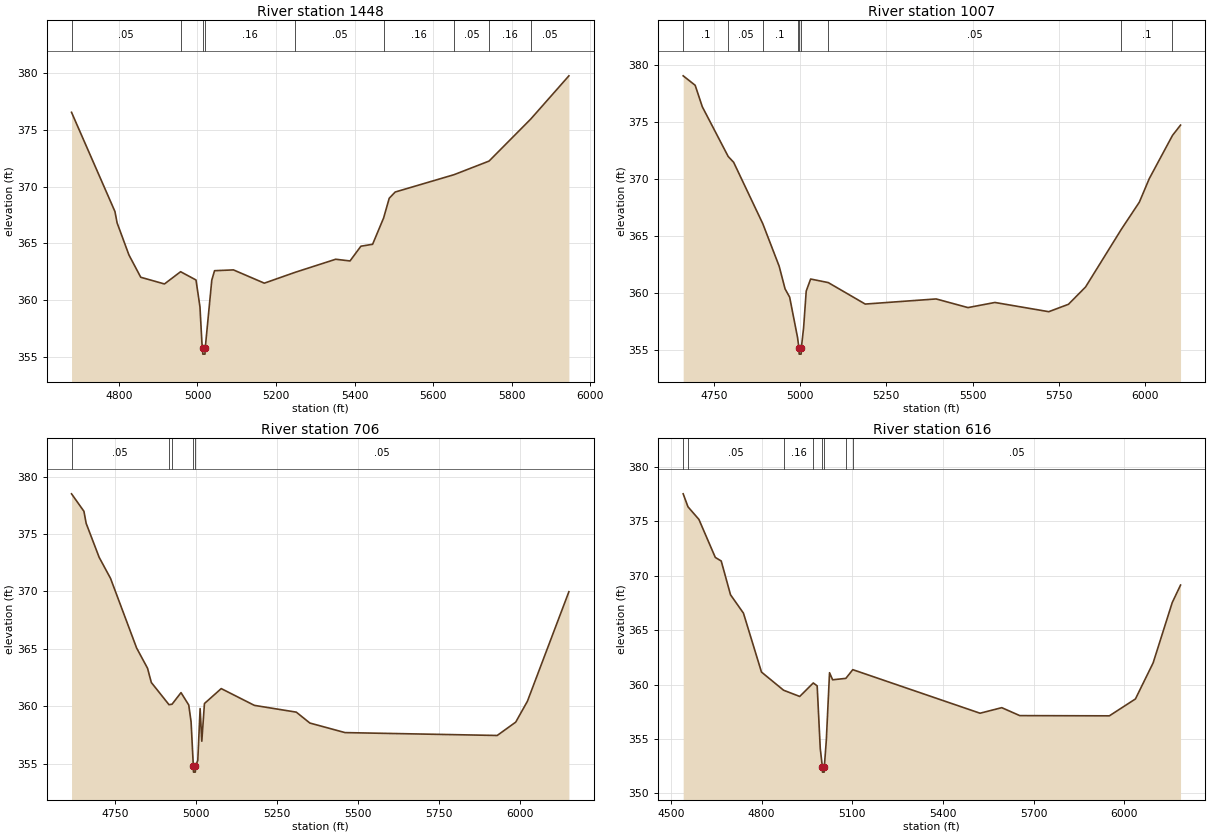
Type RM Length L Ch R = 1 ,1448    ,441,441,441
BEGIN DESCRIPTION:
DUCK CREEK TRIB 28 11 0
END DESCRIPTION:
XS GIS Cut Line= 3
      3511036.57     10417096.56      3511401.16     10417063.57
      3511886.61     10416305.93
#Sta/Elev= 30
  4679.4  376.57  4789.9  367.82  4795.4  366.82  4825.5  363.99  4855.6  362.02
  4915.9  361.43    4957  362.51  4996.2  361.78  5006.3  359.41  5011.3  356.21
    5013  355.74  5013.5  355.24  5019.1  355.24  5019.6  355.74  5036.4  361.77
  5043.4   362.6  5091.5  362.67  5170.1   361.5  5248.8  362.46  5351.8  363.61
  5388.2  363.46  5415.9  364.76  5445.7  364.93  5473.7  367.25    5488  368.99
  5503.2  369.54    5653  371.07  5742.1  372.27  5848.3  375.98  5945.3  379.79
#Mann= 9 ,-1 , 0
  4679.4     .05       0    4957     .16       0    5013     .07       0
  5019.6     .16       0  5248.8     .05       0  5473.7     .16       0
    5653     .05       0  5742.1     .16       0  5848.3     .05       0
Bank Sta=5013,5019.6
XS Rating Curve= 0 ,0
Exp/Cntr=0.3,0.1

Type RM Length L Ch R = 1 ,1007    ,301,301,301
BEGIN DESCRIPTION:
DUCK CREEK TRIB 28 21 0
END DESCRIPTION:
XS GIS Cut Line= 3
      3511067.84     10417554.89      3511468.87     10417488.92
      3512138.03     10416700.14
#Sta/Elev= 30
  4661.6  379.09  4696.3  378.26    4717  376.37    4792     372  4807.8  371.49
  4892.1   366.1  4939.6  362.36  4956.8  360.36    4970  359.64  4992.9  356.09
  4997.1  355.13  4997.6  354.63  5003.2  354.63  5003.7  355.13  5010.5  356.97
    5018  360.17  5030.8  361.23  5081.7  360.92    5189  359.03  5394.4  359.48
  5486.6  358.72  5564.6  359.17  5720.6  358.36  5777.7  359.01  5827.2  360.53
  5931.3  365.62  5983.1  367.99  6011.7  370.05    6079  373.85  6102.4  374.76
#Mann= 9 ,-1 , 0
  4661.6      .1       0    4792     .05       0  4892.1      .1       0
  4992.9     .16       0  4997.1     .07       0  5003.7     .16       0
  5081.7     .05       0  5931.3      .1       0    6079     .05       0
Bank Sta=4997.1,5003.7
XS Rating Curve= 0 ,0
Exp/Cntr=0.3,0.1

Type RM Length L Ch R = 1 ,706     ,90,90,90
BEGIN DESCRIPTION:
DUCK CREEK TRIB 28 20 0
END DESCRIPTION:
XS GIS Cut Line= 3
      3511125.08     10417674.67      3511585.19     10417796.21
      3512167.84     10416910.09
#Sta/Elev= 30
  4614.4   378.5  4652.7  376.98  4659.6  375.93  4699.8  372.97  4734.9  371.14
  4815.5  365.08  4849.2  363.32  4860.9  362.08  4915.5  360.15  4924.9  360.19
  4952.6   361.2  4976.5  360.12  4983.7  358.66  4990.7  354.78  4991.2  354.28
  4996.8  354.28  4997.3  354.78  5004.4   355.3  5011.6  359.81  5016.8  356.97
    5025  360.25  5076.8  361.55  5179.2  360.09  5308.7   359.5  5350.8  358.55
  5459.3  357.72  5929.3  357.47  5986.5  358.63  6022.7  360.45  6150.8  369.98
#Mann= 5 ,-1 , 0
  4614.4     .05       0  4915.5      .1       0  4924.9     .05       0
  4990.7     .03       0  4997.3     .05       0
Bank Sta=4990.7,4997.3
XS Rating Curve= 0 ,0
Exp/Cntr=0.3,0.1

Type RM Length L Ch R = 1 ,616     ,0,0,0
BEGIN DESCRIPTION:
DUCK CREEK TRIB 28 47
END DESCRIPTION:
XS GIS Cut Line= 3
      3511059.17     10417764.96      3511569.56     10417876.07
      3512184.15     10416936.82
#Sta/Elev= 30
  4540.8  377.52  4556.6  376.33  4592.8  375.17    4647  371.68  4666.6  371.35
  4697.3  368.25  4740.1  366.56  4799.7  361.15  4872.9  359.48  4926.2  358.91
    4971  360.15  4983.9  359.88  4994.1  354.14    5001  352.46  5001.5  351.96
  5007.1  351.96  5007.6  352.46  5014.1  354.87  5024.8  361.09    5035  360.44
  5078.7  360.57  5101.7  361.37  5522.6  357.37  5594.3  357.88    5654  357.15
  5950.2  357.13  6036.4  358.68  6094.9  361.99  6158.2  367.54  6185.6  369.14
#Mann= 8 ,-1 , 0
  4540.8      .1       0  4556.6     .05       0  4872.9     .16       0
    4971     .12       0    5001     .07       0  5007.6     .12       0
  5078.7     .07       0  5101.7     .05       0
Bank Sta=5001,5007.6
XS Rating Curve= 0 ,0
Exp/Cntr=0.3,0.1

Chan Stop Cuts=-1
Use User Specified Reach Order=0
Composite Channel Slope=5