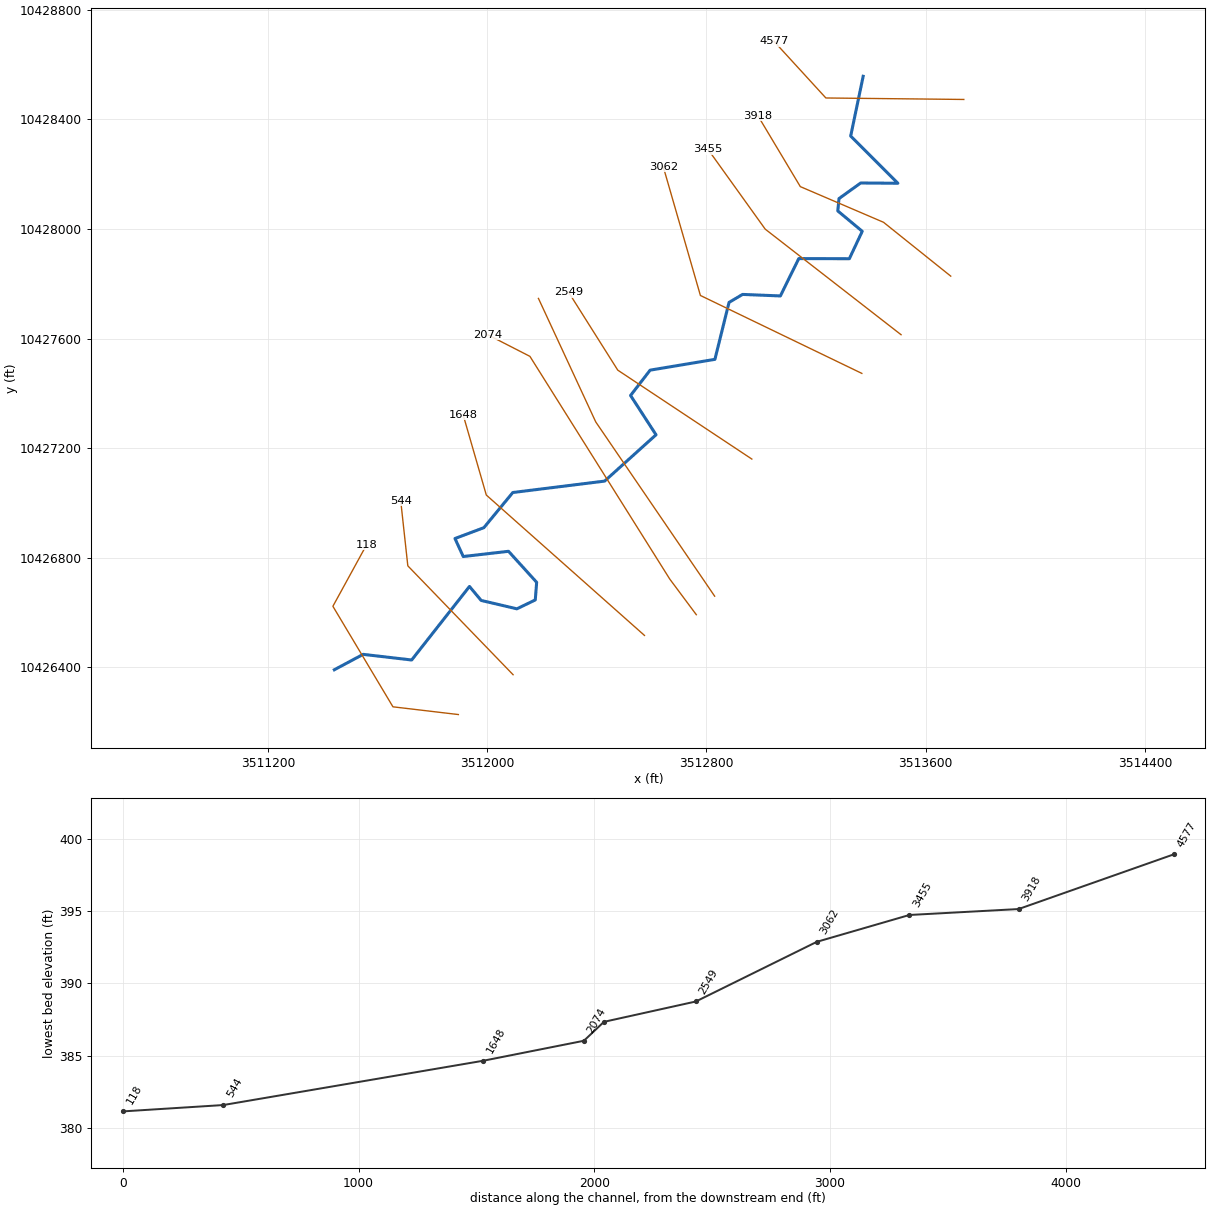
--- DUCK CREEK TRIB 29 2.prj (project) ---

Proj Title=DUCK CREEK TRIB 29 2 Base Level Engineering
Current Plan=p01
Default Exp/Contr=0.3,0.1
English Units
Geom File=g01
Flow File=f01
Plan File=p01
Y Axis Title=Elevation
X Axis Title(PF)=Main Channel Distance
X Axis Title(XS)=Station
BEGIN DESCRIPTION:
DUCK CREEK TRIB 29 2
END DESCRIPTION:
DSS Export Rating Curves= 0
DSS Export Rating Curve Sorted= 0
DSS Export Volume Flow Curves= 0
DXF OffsetX= 0
DXF OffsetY= 0
DXF ScaleX= 1
DXF ScaleY= 10

--- DUCK CREEK TRIB 29 2.p01 (plan) ---

Plan Title=Multiple Run
Short Identifier=Multiple
Geom File=g01
Flow File=f01
Subcritical Flow
K Sum by GR= 0
Std Step Tol= 0.01
Critical Tol= 0.01
Num of Std Step Trials= 20
Max Error Tol= 0.3
Flow Tol Ratio= 0.001
Split Flow NTrial= 30
Split Flow Tol= 0.02
Split Flow Ratio= 0.02
Log Output Level= 0
Friction Slope Method= 1
Unsteady Friction Slope Method= 2
Unsteady Bridges Friction Slope Method= 1
Parabolic Critical Depth
Global Vel Dist=  1 , 1 , 1
Global Log Level= 0
CheckData=True
Encroach Param= -1, 0, 0, 0
BEGIN DESCRIPTION:
Multiple Run
END DESCRIPTION:

--- DUCK CREEK TRIB 29 2.f01 (steady flow) ---

Flow Title=Multiple
Number of Profiles=7
Profile Names=10-year,25-year,50-year,1pct_min,100-year,1pct_plu,500-year
River Rch & RM= DUCK CREEK TRIB ,Reach-1,4577
     840    1145    1393    1237    1673    2263    2408
Boundary for River Rch & Prof#=DUCK CREEK TRIB ,Reach-1,1
Up Type=0
Dn Type=3
Dn Slope=0.005
Boundary for River Rch & Prof#=DUCK CREEK TRIB ,Reach-1,2
Up Type=0
Dn Type=3
Dn Slope=0.005
Boundary for River Rch & Prof#=DUCK CREEK TRIB ,Reach-1,3
Up Type=0
Dn Type=3
Dn Slope=0.005
Boundary for River Rch & Prof#=DUCK CREEK TRIB ,Reach-1,4
Up Type=0
Dn Type=3
Dn Slope=0.005
Boundary for River Rch & Prof#=DUCK CREEK TRIB ,Reach-1,5
Up Type=0
Dn Type=3
Dn Slope=0.005
Boundary for River Rch & Prof#=DUCK CREEK TRIB ,Reach-1,6
Up Type=0
Dn Type=3
Dn Slope=0.005
Boundary for River Rch & Prof#=DUCK CREEK TRIB ,Reach-1,7
Up Type=0
Dn Type=3
Dn Slope=0.005

--- DUCK CREEK TRIB 29 2.g01 (geometry) ---

Geom Title=Existing Conditions
Program Version=4.10

River Reach=DUCK CREEK TRIB ,Reach-1
Reach XY= 30
      3513372.06     10428556.67      3513326.52     10428338.67
      3513498.65     10428166.41      3513363.05     10428167.41
      3513283.84     10428110.49      3513279.51     10428065.45
      3513368.69     10427991.19      3513321.61     10427891.11
      3513137.04     10427891.62      3513069.89     10427755.36
      3512931.84     10427760.87      3512882.58     10427731.71
      3512830.98     10427524.01       3512594.6     10427484.62
      3512523.15     10427392.12      3512616.12     10427248.82
      3512428.55     10427079.85      3512093.44      10427038.2
       3511987.8     10426909.89      3511882.33     10426870.38
      3511912.55     10426804.66      3512077.79     10426823.74
      3512180.44     10426710.61      3512175.39     10426646.26
      3512108.29     10426613.88      3511977.95     10426644.45
      3511935.27     10426695.48       3511724.3     10426427.23
      3511547.24     10426447.76      3511442.11     10426391.64

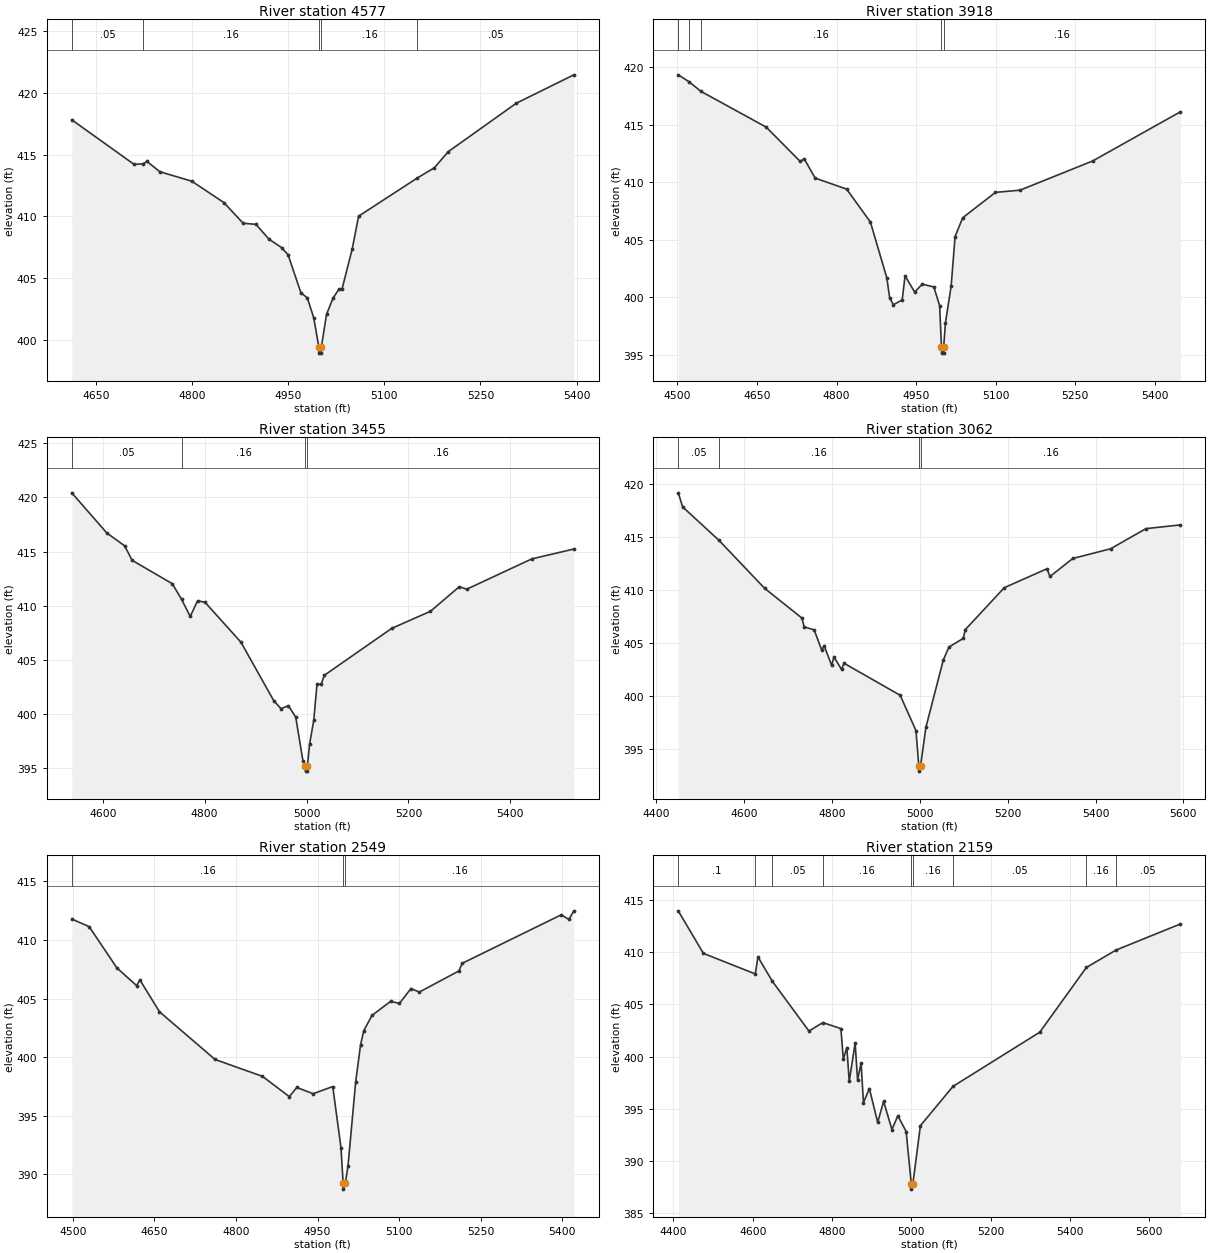
Type RM Length L Ch R = 1 ,4577    ,659,659,659
BEGIN DESCRIPTION:
DUCK CREEK TRIB 29 2 22 0
END DESCRIPTION:
XS GIS Cut Line= 3
      3513739.38     10428472.11      3513235.94     10428477.53
      3513047.15     10428683.68
#Sta/Elev= 30
  4612.6  417.81  4709.9   414.2  4724.3  414.26  4729.9  414.44  4749.9  413.61
  4799.9  412.84  4849.9  411.11  4879.9  409.44  4899.9  409.35  4919.9  408.16
  4939.9  407.47  4949.9  406.89  4969.9  403.82  4979.9   403.4  4989.9   401.8
  4997.9  399.43  4998.1  398.93  5001.6  398.93  5001.9  399.43  5009.9  402.07
  5019.9  403.36  5029.1   404.1  5034.1  404.12  5049.9  407.34  5059.9  410.01
  5151.7  413.11  5178.1  413.93  5199.7  415.23  5305.8  419.15  5395.6  421.45
#Mann= 5 ,-1 , 0
  4612.6     .05       0  4724.3     .16       0  4997.9     .07       0
  5001.9     .16       0  5151.7     .05       0
Bank Sta=4997.9,5001.9
XS Rating Curve= 0 ,0
Exp/Cntr=0.3,0.1

Type RM Length L Ch R = 1 ,3918    ,463,463,463
BEGIN DESCRIPTION:
DUCK CREEK TRIB 29 2 10 0
END DESCRIPTION:
XS GIS Cut Line= 4
      3513691.66     10427827.58      3513446.45     10428023.97
      3513142.63     10428154.18      3512987.47      10428413.5
#Sta/Elev= 30
  4501.4  419.34  4521.4  418.75  4544.3   417.9  4667.4  414.79  4731.4  411.81
  4738.9  412.04  4759.7  410.36    4819   409.4  4863.8  406.54  4894.8  401.68
  4900.2  399.93  4907.3  399.35  4923.8  399.77  4929.2  401.86  4947.3  400.45
  4961.7  401.14  4983.5  400.89  4994.4  399.26  4997.9  395.64  4998.2  395.14
  5001.7  395.14  5001.9  395.64  5005.4  397.79  5016.1  400.97  5023.5  405.27
  5037.9  406.91  5099.7  409.12  5146.1  409.31    5283  411.85  5448.3  416.12
#Mann= 5 ,-1 , 0
  4501.4     .16       0  4521.4     .05       0  4544.3     .16       0
  4997.9     .07       0  5001.9     .16       0
Bank Sta=4997.9,5001.9
XS Rating Curve= 0 ,0
Exp/Cntr=0.3,0.1

Type RM Length L Ch R = 1 ,3455    ,393,393,393
BEGIN DESCRIPTION:
DUCK CREEK TRIB 29 2 9 0
END DESCRIPTION:
XS GIS Cut Line= 3
      3513510.44     10427613.84      3513014.59     10427999.02
      3512806.11     10428289.59
#Sta/Elev= 30
  4539.2  420.43  4607.8  416.73  4643.1  415.53  4657.6   414.2  4736.4  412.04
  4754.8  410.59  4771.7  409.01  4786.1  410.46  4800.6  410.33  4871.2  406.64
  4935.5  401.25    4950  400.49  4964.4  400.78  4978.9   399.7  4992.9  395.69
  4997.7  395.23    4998  394.73  5001.5  394.73  5001.7  395.23  5006.1  397.25
  5014.2  399.43  5020.5  402.73  5028.7  402.77    5035  403.58  5167.1  407.91
  5243.3  409.49  5299.8  411.76  5314.5  411.53  5442.2  414.33  5524.7  415.24
#Mann= 4 ,-1 , 0
  4539.2     .05       0  4754.8     .16       0  4997.7     .07       0
  5001.7     .16       0
Bank Sta=4997.7,5001.7
XS Rating Curve= 0 ,0
Exp/Cntr=0.3,0.1

Type RM Length L Ch R = 1 ,3062    ,513,513,513
BEGIN DESCRIPTION:
DUCK CREEK TRIB 29 2 8 0
END DESCRIPTION:
XS GIS Cut Line= 3
       3513367.2     10427472.78      3512778.05     10427757.05
      3512642.46     10428226.72
#Sta/Elev= 30
    4450  419.15  4460.1  417.82  4543.1  414.65  4646.5  410.14  4731.4  407.33
  4736.9  406.49  4759.5  406.21  4776.6  404.29  4782.1  404.72  4799.2  402.86
  4804.7  403.64  4821.8  402.47  4827.3  403.06  4955.3  400.03  4991.2   396.7
  4997.7  393.37    4998  392.87  5001.7  393.37  5013.8     397  5053.4  403.36
  5066.3  404.59  5098.7   405.4  5103.7  406.24  5192.2  410.19  5289.4  411.98
  5296.3  411.25  5348.3  412.95  5434.4  413.87  5514.9  415.77    5593  416.12
#Mann= 4 ,-1 , 0
    4450     .05       0  4543.1     .16       0  4997.7     .07       0
  5001.7     .16       0
Bank Sta=4997.7,5001.7
XS Rating Curve= 0 ,0
Exp/Cntr=0.3,0.1

Type RM Length L Ch R = 1 ,2549    ,390,390,390
BEGIN DESCRIPTION:
DUCK CREEK TRIB 29 2 7 0
END DESCRIPTION:
XS GIS Cut Line= 3
      3512965.77     10427160.25       3512476.4     10427484.69
      3512296.71     10427769.37
#Sta/Elev= 30
  4497.8  411.78  4529.8  411.13    4581   407.6  4617.1   406.1  4623.1  406.59
  4659.2  403.87  4761.4   399.8  4848.7  398.36  4898.1  396.63  4911.8  397.41
  4941.9  396.88    4978  397.49  4993.1  392.28  4997.1  389.24  4997.3  388.74
  5001.1  389.24  5006.1  390.73  5020.1  397.86  5029.2  401.06  5035.2  402.27
  5050.2  403.56  5084.5  404.76  5100.7  404.58  5121.9  405.85  5137.2  405.55
  5210.1  407.35  5216.1     408  5398.4  412.14  5412.5  411.75  5421.6  412.48
#Mann= 3 ,-1 , 0
  4497.8     .16       0  4997.1     .07       0  5001.1     .16       0
Bank Sta=4997.1,5001.1
XS Rating Curve= 0 ,0
Exp/Cntr=0.3,0.1

Type RM Length L Ch R = 1 ,2159    ,85,85,85
BEGIN DESCRIPTION:
Mapping XS f1a726c8
END DESCRIPTION:
XS GIS Cut Line= 3
      3512830.03     10426660.06      3512396.01     10427295.89
      3512186.97     10427746.31
#Sta/Elev= 30
    4412  413.95  4475.5  409.88  4606.5  407.91    4613  409.55  4649.4  407.21
  4741.7  402.45  4776.9  403.26  4822.3  402.68  4828.4  399.76  4837.3  400.87
  4843.3  397.63  4858.2   401.3  4864.3  397.77  4873.2   399.4  4879.2  395.61
  4894.1  396.95  4915.1  393.72    4930  395.73    4951  393.03  4965.9  394.35
  4986.9  392.84  4999.8  387.83  5000.1  387.33  5003.8  387.83  5022.8   393.4
  5105.1  397.16  5323.9  402.34  5441.4  408.53  5516.4   410.2  5678.4  412.69
#Mann= 9 ,-1 , 0
    4412      .1       0  4606.5     .16       0  4649.4     .05       0
  4776.9     .16       0  4999.8     .07       0  5003.8     .16       0
  5105.1     .05       0  5441.4     .16       0  5516.4     .05       0
Bank Sta=4999.8,5003.8
XS Rating Curve= 0 ,0
Exp/Cntr=0.3,0.1

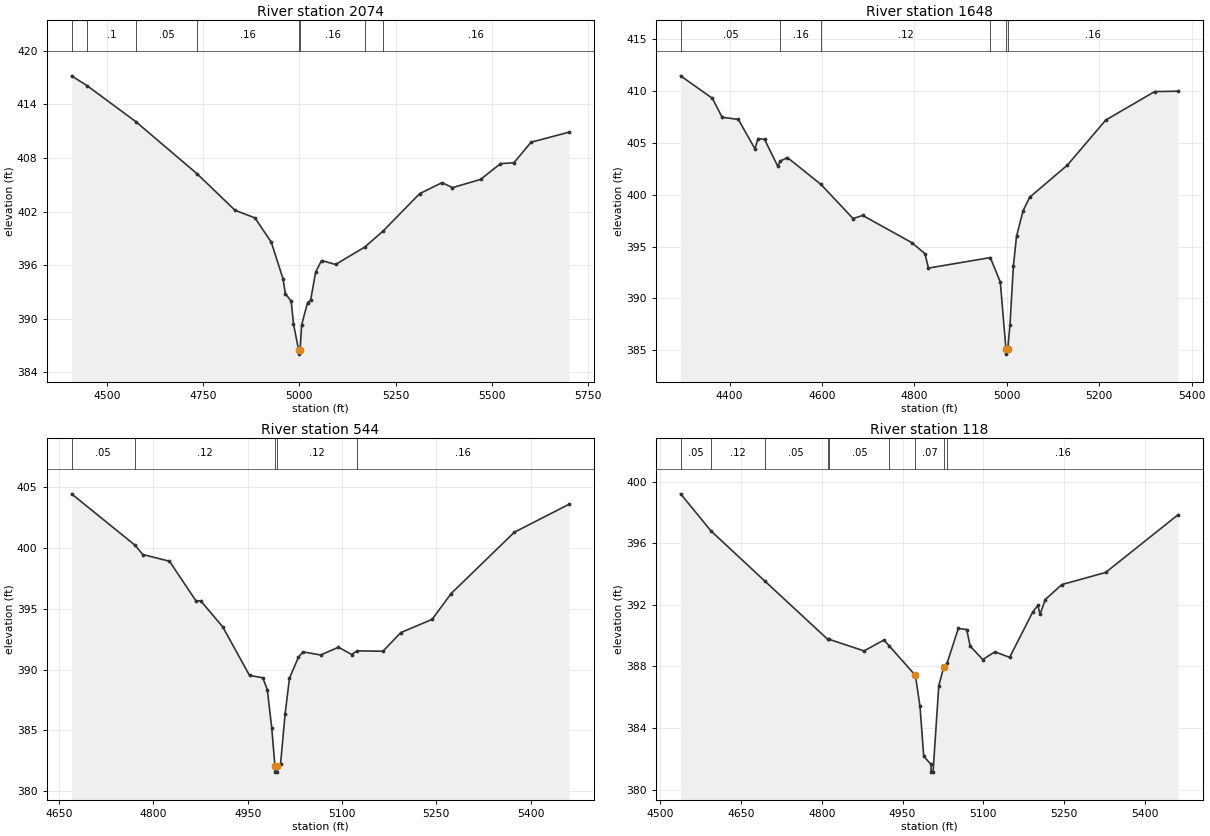
Type RM Length L Ch R = 1 ,2074    ,426,426,426
BEGIN DESCRIPTION:
DUCK CREEK TRIB 29 2 6 0
END DESCRIPTION:
XS GIS Cut Line= 4
      3512763.06      10426592.5      3512666.23     10426722.46
      3512155.81     10427534.96      3512002.68     10427613.32
#Sta/Elev= 30
  4407.5  417.21  4448.2   416.1  4575.4  412.05    4734  406.23  4832.7  402.14
  4884.5  401.29  4926.9  398.57  4957.6  394.44  4963.5  392.81  4978.8  391.94
  4984.7  389.39    4998  386.52  4998.2  386.02    5002  386.52  5005.9   389.3
  5021.2  391.78  5029.2  392.05  5042.4  395.23  5057.7  396.51  5094.2  396.07
  5170.1  398.02  5218.3  399.84  5312.6     404    5371  405.24  5398.1  404.68
  5471.1   405.6    5523  407.37    5558  407.47  5602.5  409.77  5701.1  410.89
#Mann= 8 ,-1 , 0
  4407.5     .05       0  4448.2      .1       0  4575.4     .05       0
    4734     .16       0    4998     .07       0    5002     .16       0
  5170.1     .05       0  5218.3     .16       0
Bank Sta=4998,5002
XS Rating Curve= 0 ,0
Exp/Cntr=0.3,0.1

Type RM Length L Ch R = 1 ,1648    ,1104,1104,1104
BEGIN DESCRIPTION:
DUCK CREEK TRIB 29 2 5 0
END DESCRIPTION:
XS GIS Cut Line= 3
      3512573.99     10426516.79       3511996.7     10427028.97
      3511912.07     10427321.94
#Sta/Elev= 30
  4293.9  411.45  4362.8  409.28  4383.7  407.46  4418.8  407.25  4454.8  404.42
  4461.5  405.41  4475.7  405.32  4504.1  402.75  4509.8  403.24    4525  403.58
  4597.7  400.99  4667.2   397.7  4688.1     398  4794.3  395.38  4822.8  394.32
  4830.3  392.93  4964.3  393.94  4985.9  391.58  4998.1  385.14  4998.3  384.64
  5002.1  385.14  5006.8  387.47  5014.3  393.17    5021  395.99  5035.2  398.45
  5049.4  399.75  5130.9  402.84  5214.2  407.19  5319.9  409.93  5370.6  409.97
#Mann= 6 ,-1 , 0
  4293.9     .05       0  4509.8     .16       0  4597.7     .12       0
  4964.3     .16       0  4998.1     .07       0  5002.1     .16       0
Bank Sta=4998.1,5002.1
XS Rating Curve= 0 ,0
Exp/Cntr=0.3,0.1

Type RM Length L Ch R = 1 ,544     ,426,426,426
BEGIN DESCRIPTION:
DUCK CREEK TRIB 29 2 11 0
END DESCRIPTION:
XS GIS Cut Line= 3
      3512094.38     10426373.57      3511710.25     10426770.72
      3511684.35     10427008.08
#Sta/Elev= 30
  4669.8  404.45  4770.7  400.23  4783.2  399.46  4825.6  398.91    4868  395.63
  4875.2  395.66  4910.5   393.5  4952.9  389.52    4974  389.33  4981.2  388.36
  4988.2  385.23  4993.4  382.07  4993.6  381.57  4997.1  381.57  4997.4  382.07
  5002.3  382.24  5009.5  386.34  5016.5   389.3  5030.6     391  5037.8  391.46
  5066.1   391.2  5094.4  391.84  5115.5  391.24    5124  391.54  5165.2  391.51
  5193.5  393.04  5243.4  394.13  5273.6  396.25  5374.1  401.29  5461.1  403.59
#Mann= 5 ,-1 , 0
  4669.8     .05       0  4770.7     .12       0  4993.4     .07       0
  4997.4     .12       0    5124     .16       0
Bank Sta=4993.4,4997.4
XS Rating Curve= 0 ,0
Exp/Cntr=0.3,0.1

Type RM Length L Ch R = 1 ,118     ,0,0,0
BEGIN DESCRIPTION:
DUCK CREEK TRIB 29 2 1 0
END DESCRIPTION:
XS GIS Cut Line= 4
      3511894.74     10426228.18      3511655.99      10426256.4
      3511436.81     10426623.15      3511559.91     10426847.76
#Sta/Elev= 30
  4537.9  399.22  4594.3  396.81  4694.3  393.55  4811.2  389.76    4814  389.76
  4878.5  389.01  4915.5  389.72  4925.7  389.32  4973.9  387.42  4982.5   385.4
  4989.4  382.16    5003  381.63  5003.2  381.13  5006.7  381.13  5017.4  386.75
  5026.4  387.94  5032.7   388.2  5053.6  390.47  5069.2   390.4  5075.7  389.32
    5099  388.45  5121.7  388.95  5148.9  388.59  5192.2  391.56  5201.5  391.97
  5205.3  391.38  5215.2  392.35  5245.8  393.32  5327.3  394.11  5461.7  397.86
#Mann= 9 ,-1 , 0
  4537.9     .05       0  4594.3     .12       0  4694.3     .05       0
  4811.2     .12       0    4814     .05       0  4925.7     .12       0
  4973.9     .07       0  5026.4     .12       0  5032.7     .16       0
Bank Sta=4973.9,5026.4
XS Rating Curve= 0 ,0
Exp/Cntr=0.3,0.1

Chan Stop Cuts=-1
Use User Specified Reach Order=0
Composite Channel Slope=5