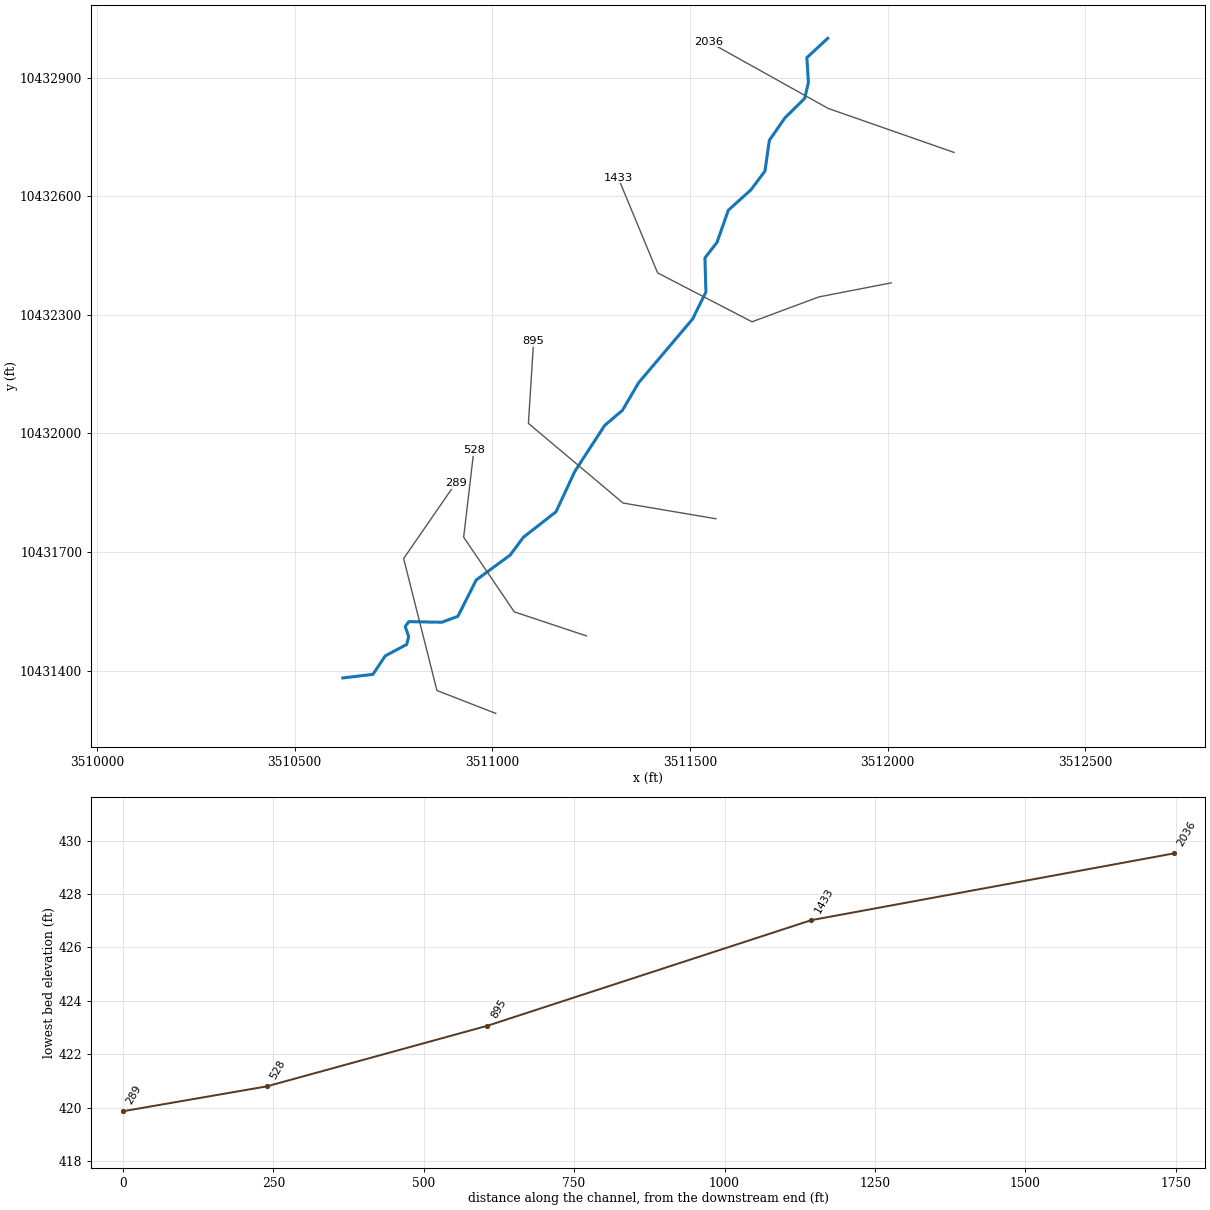
--- DUCK CREEK TRIB 29 3.prj (project) ---

Proj Title=DUCK CREEK TRIB 29 3 Base Level Engineering
Current Plan=p01
Default Exp/Contr=0.3,0.1
English Units
Geom File=g01
Flow File=f01
Plan File=p01
BEGIN DESCRIPTION:
DUCK CREEK TRIB 29 3
END DESCRIPTION:

--- DUCK CREEK TRIB 29 3.p01 (plan) ---

Plan Title=Multiple Run
Short Identifier=Multiple
Geom File=g01
Flow File=f01
Subcritical Flow
K Sum by GR= 0
Std Step Tol= 0.01
Critical Tol= 0.01
Num of Std Step Trials= 20
Max Error Tol= 0.3
Flow Tol Ratio= 0.001
Split Flow NTrial= 30
Split Flow Tol= 0.02
Split Flow Ratio= 0.02
Log Output Level= 0
Friction Slope Method= 1
Unsteady Friction Slope Method= 2
Unsteady Bridges Friction Slope Method= 1
Parabolic Critical Depth
Global Vel Dist=  1 , 1 , 1
Global Log Level= 0
CheckData=True
Encroach Param= -1, 0, 0, 0
BEGIN DESCRIPTION:
Multiple Run
END DESCRIPTION:

--- DUCK CREEK TRIB 29 3.f01 (steady flow) ---

Flow Title=Multiple
Number of Profiles=7
Profile Names=10-year,25-year,50-year,1pct_min,100-year,1pct_plu,500-year
River Rch & RM= DUCK CREEK TRIB ,Reach-1,2036
     268     339     393     334     452     612     594
Boundary for River Rch & Prof#=DUCK CREEK TRIB ,Reach-1,1
Up Type=0
Dn Type=3
Dn Slope=0.005
Boundary for River Rch & Prof#=DUCK CREEK TRIB ,Reach-1,2
Up Type=0
Dn Type=3
Dn Slope=0.005
Boundary for River Rch & Prof#=DUCK CREEK TRIB ,Reach-1,3
Up Type=0
Dn Type=3
Dn Slope=0.005
Boundary for River Rch & Prof#=DUCK CREEK TRIB ,Reach-1,4
Up Type=0
Dn Type=3
Dn Slope=0.005
Boundary for River Rch & Prof#=DUCK CREEK TRIB ,Reach-1,5
Up Type=0
Dn Type=3
Dn Slope=0.005
Boundary for River Rch & Prof#=DUCK CREEK TRIB ,Reach-1,6
Up Type=0
Dn Type=3
Dn Slope=0.005
Boundary for River Rch & Prof#=DUCK CREEK TRIB ,Reach-1,7
Up Type=0
Dn Type=3
Dn Slope=0.005

--- DUCK CREEK TRIB 29 3.g01 (geometry) ---

Geom Title=Existing Conditions

River Reach=DUCK CREEK TRIB ,Reach-1
Reach XY= 30
      3511848.35     10432999.05      3511795.65     10432950.20
      3511799.47     10432887.03      3511790.26     10432847.52
      3511739.99     10432797.71      3511700.72     10432741.21
      3511689.60     10432663.30      3511654.19     10432615.96
      3511596.99     10432564.42      3511568.34     10432483.16
      3511537.88     10432443.93      3511540.30     10432357.49
      3511506.61     10432289.21      3511370.21     10432128.24
      3511329.32     10432058.49      3511284.62     10432020.55
      3511208.91     10431904.22      3511161.29     10431801.88
      3511079.16     10431737.72      3511045.33     10431692.38
      3510959.65     10431629.46      3510913.14     10431537.50
      3510872.42     10431522.48      3510789.02     10431524.05
      3510779.89     10431511.76      3510788.72     10431486.14
      3510783.69     10431466.32      3510729.45     10431437.47
      3510698.40     10431390.76      3510622.11     10431381.64

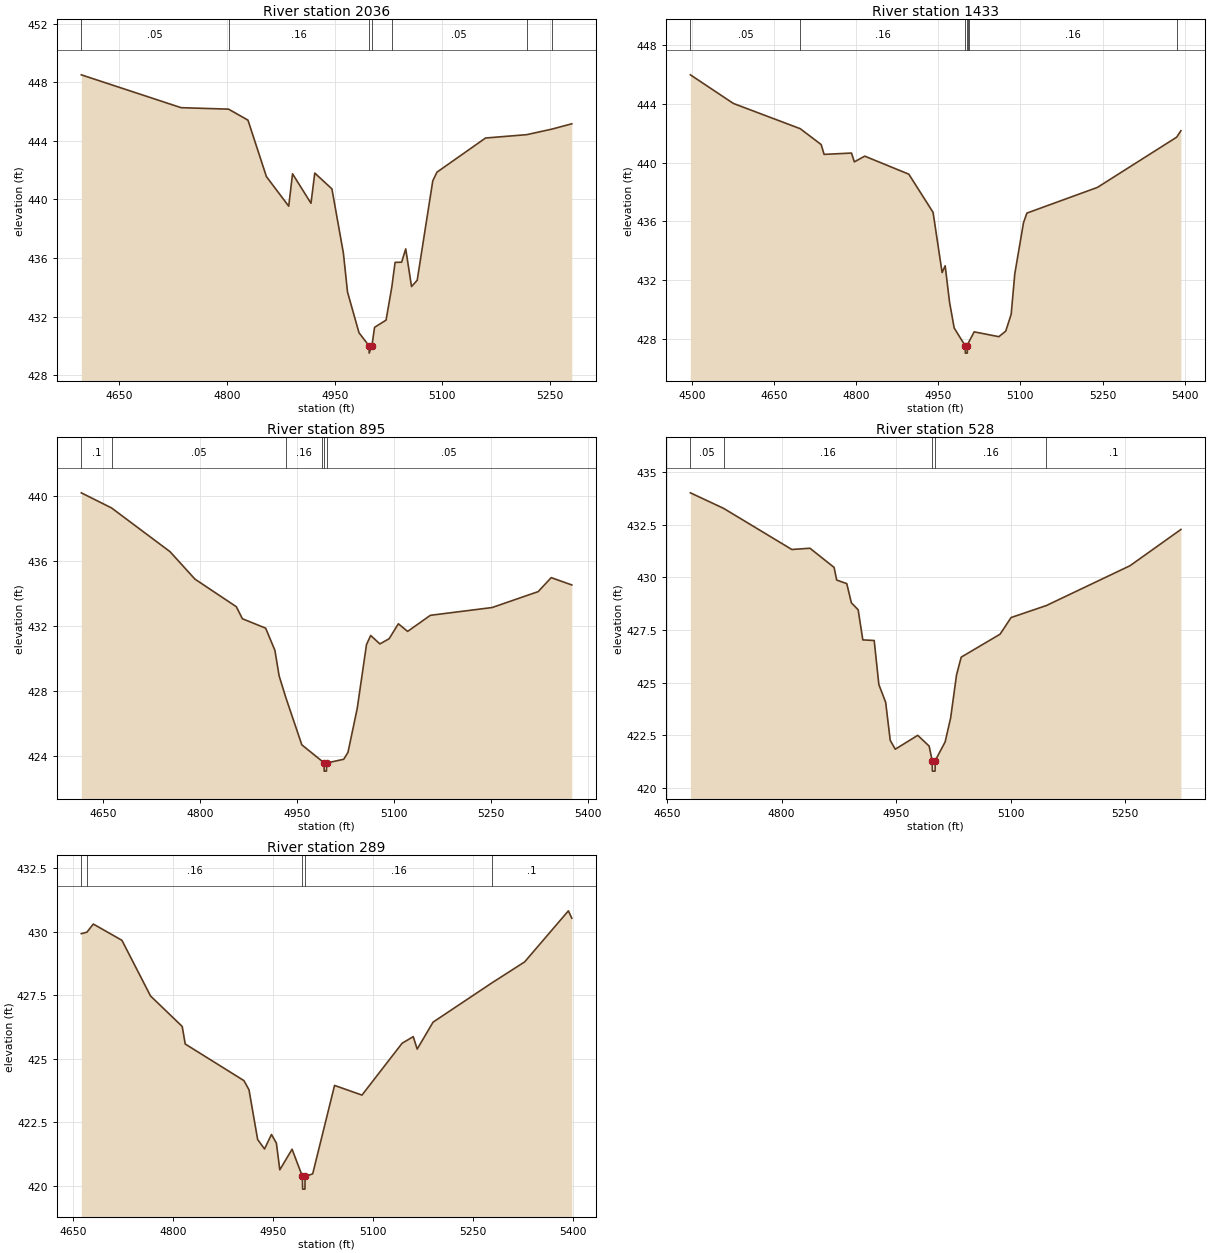
Type RM Length L Ch R = 1,2036,603,603,603
BEGIN DESCRIPTION:
DUCK CREEK TRIB 29 3 6 0
END DESCRIPTION:
XS GIS Cut Line= 3
      3512167.75     10432710.56      3511849.58     10432821.76
      3511547.11     10432990.51
#Sta/Elev= 30
  4597.0  448.50  4736.0  446.26  4802.1  446.16  4829.2  445.41  4854.9  441.56
  4886.0  439.54  4891.3  441.75  4917.0  439.74  4922.3  441.80  4946.2  440.72
  4962.2  436.33  4967.9  433.69  4983.9  430.91  4997.9  430.02  4998.1  429.52
  5001.9  430.02  5005.6  431.28  5021.6  431.77  5029.6  434.02  5034.2  435.71
  5043.3  435.72  5049.0  436.63  5057.1  434.06  5065.0  434.49  5086.7  441.27
  5092.5  441.86  5160.2  444.19  5217.7  444.42  5252.9  444.80  5280.4  445.16
#Mann=7,-1,0
  4597.0    0.05       0  4802.1    0.16       0  4997.9    0.07       0
  5001.9    0.16       0  5029.6    0.05       0  5217.7     0.1       0
  5252.9    0.05       0
Bank Sta=4997.9,5001.9
Exp/Cntr=0.3,0.1

Type RM Length L Ch R = 1,1433,538,538,538
BEGIN DESCRIPTION:
DUCK CREEK TRIB 29 3 5 0
END DESCRIPTION:
XS GIS Cut Line= 5
      3512008.89     10432380.68      3511826.17     10432345.20
      3511656.90     10432282.27      3511418.18     10432405.96
      3511318.41     10432646.72
#Sta/Elev= 30
  4497.0  445.98  4575.5  444.03  4697.7  442.31  4735.9  441.23  4741.3  440.56
  4791.3  440.65  4796.6  440.05  4815.5  440.44  4896.1  439.21  4940.4  436.61
  4956.9  432.51  4962.5  432.97  4970.5  430.49  4979.0  428.73  4999.1  427.52
  4999.4  427.02  5002.9  427.02  5003.1  427.52  5004.8  427.69  5005.6  427.77
  5015.5  428.47  5060.6  428.14  5073.2  428.52  5083.1  429.67  5089.7  432.42
  5105.6  435.90  5111.8  436.56  5240.7  438.31  5385.4  441.73  5393.2  442.17
#Mann=7,-1,0
  4497.0    0.05       0  4697.7    0.16       0  4999.1    0.07       0
  5003.1    0.16       0  5004.8    0.05       0  5005.6    0.16       0
  5385.4    0.05       0
Bank Sta=4999.1,5003.1
Exp/Cntr=0.3,0.1

Type RM Length L Ch R = 1,895,367,367,367
BEGIN DESCRIPTION:
DUCK CREEK TRIB 29 3 3 0
END DESCRIPTION:
XS GIS Cut Line= 4
      3511565.51     10431784.26      3511330.96     10431823.91
      3511091.46     10432025.42      3511104.67     10432233.52
#Sta/Elev= 30
  4615.8  440.20  4662.6  439.27  4753.1  436.58  4791.7  434.89  4855.8  433.19
  4865.2  432.45  4901.2  431.87  4915.5  430.51  4922.1  428.93  4932.7  427.57
  4957.2  424.69  4988.6  423.68  4991.6  423.57  4991.8  423.07  4995.3  423.07
  4995.6  423.57  5022.1  423.80  5028.7  424.23  5043.0  426.93  5057.3  430.85
  5063.8  431.42  5078.1  430.90  5092.4  431.22  5106.7  432.14  5121.0  431.67
  5156.2  432.66  5251.9  433.14  5323.2  434.12  5343.3  434.98  5375.2  434.53
#Mann=6,-1,0
  4615.8     0.1       0  4662.6    0.05       0  4932.7    0.16       0
  4988.6    0.05       0  4991.6   0.035       0  4995.6    0.05       0
Bank Sta=4991.6,4995.6
Exp/Cntr=0.3,0.1

Type RM Length L Ch R = 1,528,239,239,239
BEGIN DESCRIPTION:
DUCK CREEK TRIB 29 3 4 0
END DESCRIPTION:
XS GIS Cut Line= 4
      3511238.10     10431487.98      3511055.77     10431548.76
      3510927.73     10431737.56      3510953.64     10431957.82
#Sta/Elev= 30
  4680.7  434.01  4724.3  433.27  4813.5  431.32  4837.2  431.38  4868.8  430.47
  4872.2  429.87  4885.4  429.70  4891.4  428.79  4900.3  428.46  4906.4  427.03
  4921.3  427.00  4927.4  424.91  4936.3  424.07  4942.3  422.26  4948.9  421.84
  4978.3  422.50  4993.2  421.99  4997.2  421.30  4997.5  420.80  5001.0  420.80
  5001.2  421.30  5014.2  422.19  5021.4  423.33  5029.1  425.37  5035.2  426.21
  5086.1  427.30  5100.5  428.09  5146.7  428.66  5256.2  430.55  5322.8  432.27
#Mann=5,-1,0
  4680.7    0.05       0  4724.3    0.16       0  4997.2    0.07       0
  5001.2    0.16       0  5146.7     0.1       0
Bank Sta=4997.2,5001.2
Exp/Cntr=0.3,0.1

Type RM Length L Ch R = 1,289,0,0,0
BEGIN DESCRIPTION:
DUCK CREEK TRIB 29 3 1 0
END DESCRIPTION:
XS GIS Cut Line= 4
      3511008.83     10431292.07      3510860.22     10431349.86
      3510775.98     10431683.51      3510907.60     10431874.35
#Sta/Elev= 30
  4662.3  429.92  4670.7  429.98  4680.3  430.30  4723.2  429.66  4766.1  427.47
  4813.6  426.27  4818.1  425.58  4906.1  424.14  4913.7  423.78  4926.7  421.82
  4937.0  421.45  4947.4  422.02  4954.8  421.68  4959.9  420.63  4978.3  421.44
  4993.8  420.37  4994.1  419.87  4997.6  419.87  4997.8  420.37  5009.2  420.47
  5042.0  423.95  5083.1  423.57  5143.3  425.61  5160.0  425.87  5165.9  425.38
  5189.7  426.44  5278.2  427.99  5327.0  428.81  5392.6  430.82  5397.7  430.53
#Mann=5,-1,0
  4662.3    0.05       0  4670.7    0.16       0  4993.8    0.07       0
  4997.8    0.16       0  5278.2     0.1       0
Bank Sta=4993.8,4997.8
Exp/Cntr=0.3,0.1

Chan Stop Cuts=-1