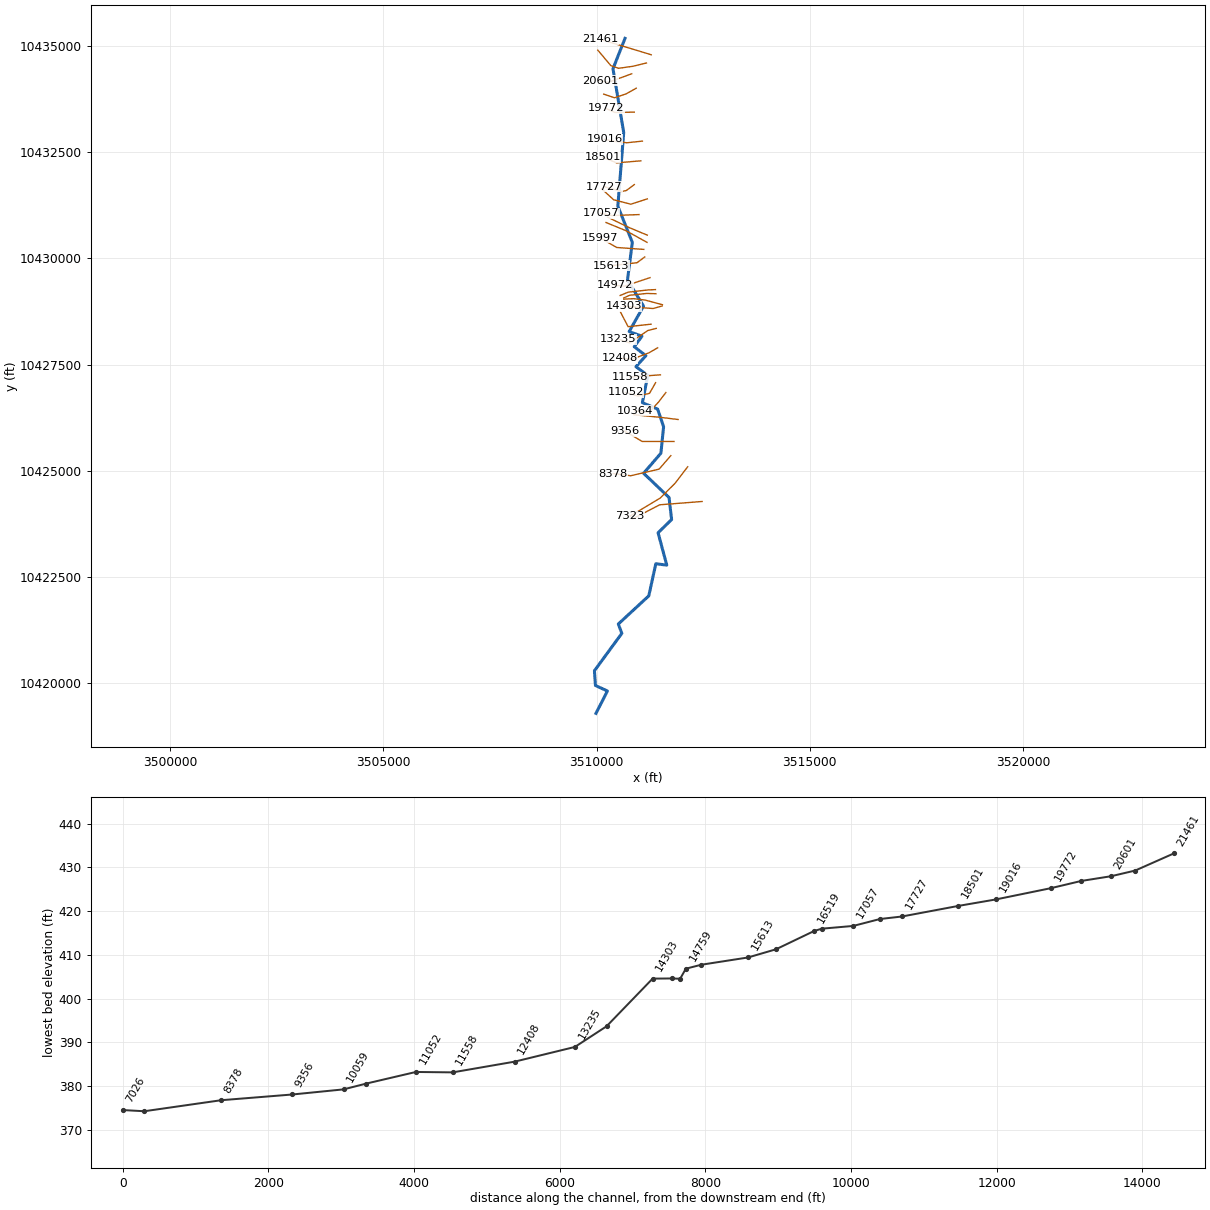
--- DUCK CREEK TRIB 29.prj (project) ---

Proj Title=DUCK CREEK TRIB 29 Base Level Engineering
Current Plan=p01
Default Exp/Contr=0.3,0.1
English Units
Geom File=g01
Flow File=f01
Plan File=p01
BEGIN DESCRIPTION:
DUCK CREEK TRIB 29
END DESCRIPTION:

--- DUCK CREEK TRIB 29.p01 (plan) ---

Plan Title=Multiple Run
Short Identifier=Multiple
Geom File=g01
Flow File=f01
Subcritical Flow
K Sum by GR= 0
Std Step Tol= 0.01
Critical Tol= 0.01
Num of Std Step Trials= 20
Max Error Tol= 0.3
Flow Tol Ratio= 0.001
Split Flow NTrial= 30
Split Flow Tol= 0.02
Split Flow Ratio= 0.02
Log Output Level= 0
Friction Slope Method= 1
Unsteady Friction Slope Method= 2
Unsteady Bridges Friction Slope Method= 1
Parabolic Critical Depth
Global Vel Dist=  1 , 1 , 1
Global Log Level= 0
CheckData=True
Encroach Param= -1, 0, 0, 0
BEGIN DESCRIPTION:
Multiple Run
END DESCRIPTION:

--- DUCK CREEK TRIB 29.f01 (steady flow) ---

Flow Title=Multiple
Number of Profiles=7
Profile Names=10-year,25-year,50-year,1pct_min,100-year,1pct_plu,500-year
River Rch & RM= DUCK CREEK TRIB ,Reach-1,21461
     478     631     751     655     886    1198    1226
River Rch & RM= DUCK CREEK TRIB ,Reach-1,17424
    1027    1419    1743    1562    2112    2856    3094
River Rch & RM= DUCK CREEK TRIB ,Reach-1,10059
    1652    2328    2898    2626    3551    4803    5324
River Rch & RM= DUCK CREEK TRIB ,Reach-1,5369
    1753    2476    3086    2799    3785    5118    5685
Boundary for River Rch & Prof#=DUCK CREEK TRIB ,Reach-1,1
Up Type=0
Dn Type=3
Dn Slope=0.005
Boundary for River Rch & Prof#=DUCK CREEK TRIB ,Reach-1,2
Up Type=0
Dn Type=3
Dn Slope=0.005
Boundary for River Rch & Prof#=DUCK CREEK TRIB ,Reach-1,3
Up Type=0
Dn Type=3
Dn Slope=0.005
Boundary for River Rch & Prof#=DUCK CREEK TRIB ,Reach-1,4
Up Type=0
Dn Type=3
Dn Slope=0.005
Boundary for River Rch & Prof#=DUCK CREEK TRIB ,Reach-1,5
Up Type=0
Dn Type=3
Dn Slope=0.005
Boundary for River Rch & Prof#=DUCK CREEK TRIB ,Reach-1,6
Up Type=0
Dn Type=3
Dn Slope=0.005
Boundary for River Rch & Prof#=DUCK CREEK TRIB ,Reach-1,7
Up Type=0
Dn Type=3
Dn Slope=0.005

--- DUCK CREEK TRIB 29.g01 (geometry) ---

Geom Title=Existing Conditions

River Reach=DUCK CREEK TRIB ,Reach-1
Reach XY= 30
      3510667.25     10435179.92      3510384.79     10434464.56
      3510636.41     10432961.60      3510498.15     10431230.24
      3510838.04     10430377.83      3510725.34     10429491.30
      3511101.17     10428876.81      3510764.94     10428277.11
      3511064.76     10428167.66      3510882.74     10427921.51
      3511155.21     10427709.04      3510923.18     10427450.51
      3511200.43     10427246.00      3511074.70     10426602.99
      3511431.83     10426451.77      3511572.07     10426036.62
      3511508.19     10425412.61      3511102.78     10424941.17
      3511699.79     10424370.69      3511759.76     10423851.63
      3511442.67     10423541.15      3511646.37     10422778.54
      3511389.34     10422811.88      3511224.87     10422055.41
      3510509.64     10421392.57      3510591.94     10421172.26
      3509949.53     10420293.18      3509973.40     10419945.96
      3510253.79     10419815.31      3509985.40     10419289.09

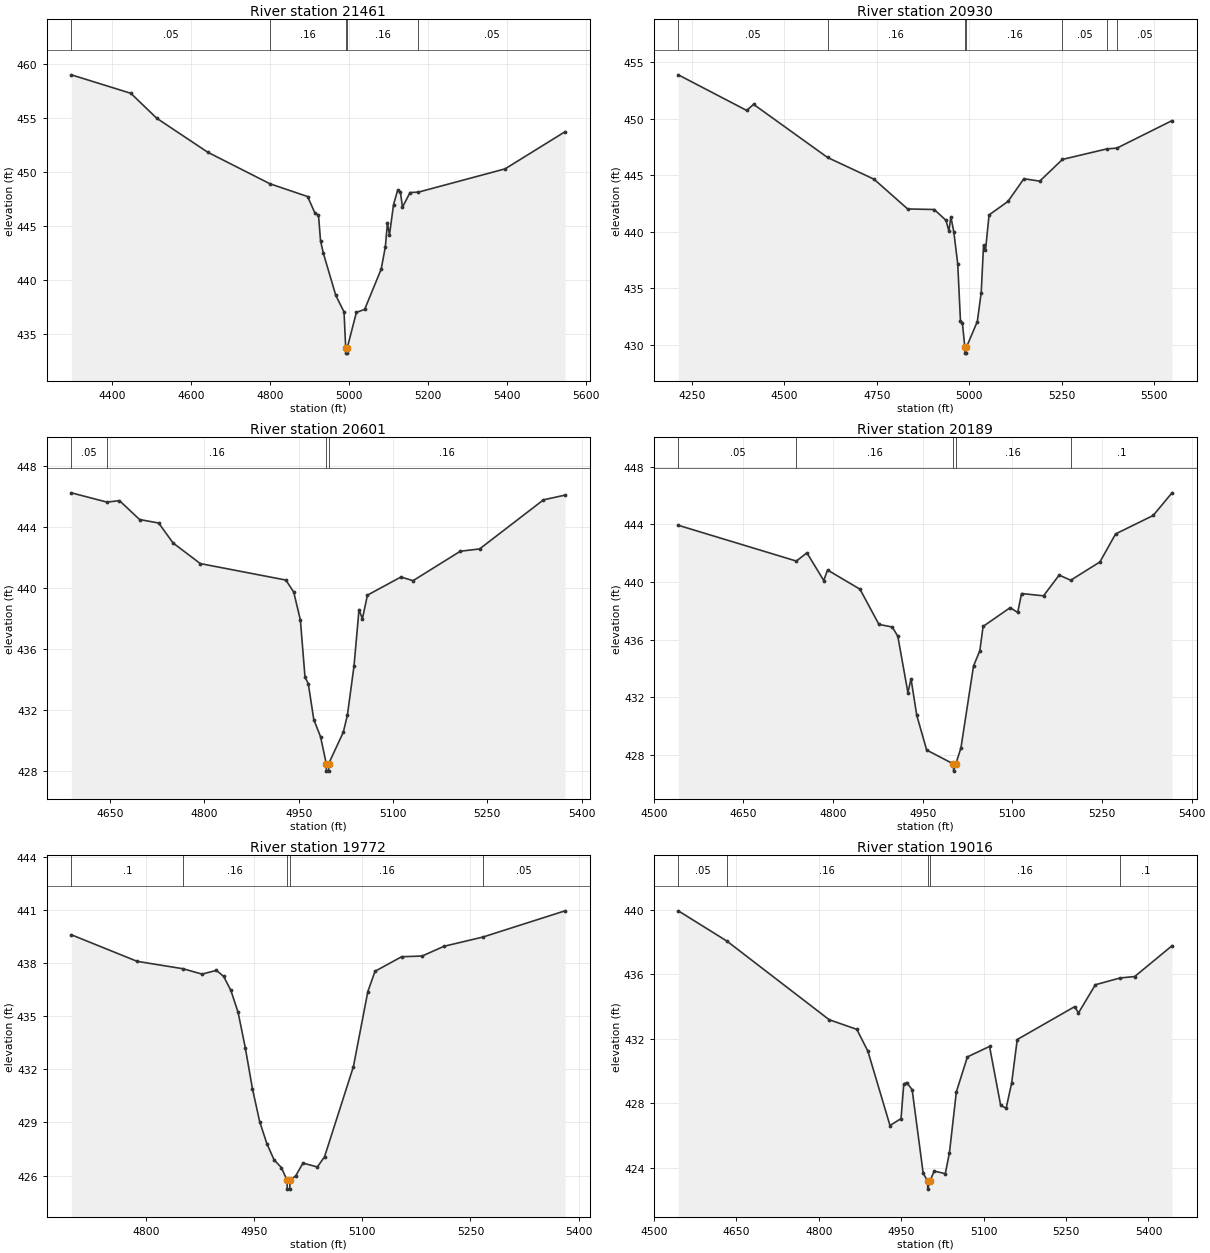
Type RM Length L Ch R = 1,21461,531,531,531
BEGIN DESCRIPTION:
DUCK CREEK TRIB 29 40 0
END DESCRIPTION:
XS GIS Cut Line= 2
      3511282.56     10434793.16      3510086.80     10435157.75
#Sta/Elev= 30
  4297.6  458.96  4448.2  457.25  4513.8  454.94  4643.1  451.79  4800.6  448.87
  4895.8  447.69  4914.9  446.12  4923.4  445.98  4928.6  443.58  4935.8  442.43
  4967.2  438.54  4988.1  437.00  4992.3  433.69  4992.5  433.19  4996.0  433.19
  4996.3  433.69  5019.4  436.96  5040.3  437.24  5082.2  440.97  5092.6  443.01
  5098.0  445.21  5103.2  444.15  5113.5  446.95  5124.0  448.30  5130.8  448.10
  5136.1  446.71  5155.3  448.06  5176.5  448.10  5395.8  450.25  5547.7  453.69
#Mann=5,-1,0
  4297.6    0.05       0  4800.6    0.16       0  4992.3    0.07       0
  4996.3    0.16       0  5176.5    0.05       0
Bank Sta=4992.3,4996.3
Exp/Cntr=0.3,0.1

Type RM Length L Ch R = 1,20930,329,329,329
BEGIN DESCRIPTION:
DUCK CREEK TRIB 29 7 0
END DESCRIPTION:
XS GIS Cut Line= 5
      3511169.71     10434600.03      3510851.77     10434521.85
      3510517.57     10434474.11      3510335.28     10434537.04
      3510028.18     10434901.70
#Sta/Elev= 30
  4213.0  453.88  4397.9  450.73  4416.5  451.27  4616.5  446.57  4742.1  444.65
  4833.0  442.02  4904.9  441.97  4936.7  441.01  4944.5  440.06  4949.8  441.33
  4957.8  439.99  4968.4  437.16  4975.7  432.15  4981.0  431.94  4987.6  429.77
  4987.8  429.27  4991.3  429.27  4991.6  429.77  5021.3  432.06  5031.9  434.63
  5038.1  438.81  5043.4  438.36  5053.1  441.49  5104.3  442.69  5147.2  444.69
  5190.1  444.48  5251.5  446.40  5371.4  447.33  5398.7  447.40  5547.6  449.83
#Mann=7,-1,0
  4213.0    0.05       0  4616.5    0.16       0  4987.6    0.07       0
  4991.6    0.16       0  5251.5    0.05       0  5371.4     0.1       0
  5398.7    0.05       0
Bank Sta=4987.6,4991.6
Exp/Cntr=0.3,0.1

Type RM Length L Ch R = 1,20601,412,412,412
BEGIN DESCRIPTION:
DUCK CREEK TRIB 29 40 1
END DESCRIPTION:
XS GIS Cut Line= 3
      3510823.87     10434346.08      3510273.86     10434142.92
      3510078.98     10434182.56
#Sta/Elev= 30
  4588.5  446.23  4645.2  445.62  4665.0  445.72  4697.0  444.48  4727.4  444.25
  4750.3  442.94  4793.6  441.59  4929.7  440.51  4942.2  439.72  4952.8  437.88
  4960.1  434.16  4965.4  433.70  4974.1  431.36  4984.8  430.24  4993.9  428.48
  4994.1  427.98  4997.6  427.98  4997.9  428.48  5021.0  430.53  5027.5  431.64
  5038.1  434.88  5046.0  438.57  5051.4  437.97  5059.4  439.52  5112.7  440.71
  5132.0  440.47  5207.2  442.40  5237.8  442.55  5339.4  445.77  5373.7  446.08
#Mann=4,-1,0
  4588.5    0.05       0  4645.2    0.16       0  4993.9    0.07       0
  4997.9    0.16       0
Bank Sta=4993.9,4997.9
Exp/Cntr=0.3,0.1

Type RM Length L Ch R = 1,20189,417,417,417
BEGIN DESCRIPTION:
DUCK CREEK TRIB 29 4 1
END DESCRIPTION:
XS GIS Cut Line= 4
      3510929.62     10434005.85      3510695.05     10433873.69
      3510420.86     10433781.20      3510167.43     10433866.77
#Sta/Elev= 30
  4541.0  443.93  4738.5  441.45  4756.2  442.02  4784.4  440.10  4790.7  440.83
  4845.0  439.50  4876.7  437.06  4899.0  436.88  4908.3  436.24  4925.2  432.33
  4930.4  433.29  4940.0  430.76  4956.6  428.35  5001.3  427.39  5001.6  426.89
  5005.3  427.39  5013.9  428.49  5035.0  434.18  5045.5  435.23  5051.0  436.92
  5096.3  438.22  5108.9  437.89  5115.4  439.20  5152.1  439.04  5178.3  440.48
  5197.6  440.12  5246.5  441.39  5272.7  443.33  5335.6  444.61  5367.1  446.18
#Mann=5,-1,0
  4541.0    0.05       0  4738.5    0.16       0  5001.3    0.07       0
  5005.3    0.16       0  5197.6     0.1       0
Bank Sta=5001.3,5005.3
Exp/Cntr=0.3,0.1

Type RM Length L Ch R = 1,19772,756,756,756
BEGIN DESCRIPTION:
DUCK CREEK TRIB 29 38 1
END DESCRIPTION:
XS GIS Cut Line= 3
      3510883.35     10433442.59      3510429.12     10433434.33
      3510219.36     10433530.13
#Sta/Elev= 30
  4696.3  439.59  4787.6  438.09  4851.6  437.67  4877.6  437.37  4897.6  437.58
  4907.6  437.24  4917.6  436.45  4927.6  435.22  4937.6  433.22  4947.6  430.89
  4957.6  429.04  4967.6  427.80  4977.6  426.89  4987.6  426.46  4995.6  425.74
  4995.8  425.24  4999.3  425.24  4999.6  425.74  5007.6  425.99  5017.6  426.71
  5037.6  426.49  5047.6  427.07  5087.6  432.15  5107.6  436.38  5117.6  437.53
  5154.5  438.35  5183.0  438.39  5213.3  438.94  5267.2  439.46  5381.2  440.94
#Mann=5,-1,0
  4696.3     0.1       0  4851.6    0.16       0  4995.6    0.07       0
  4999.6    0.16       0  5267.2    0.05       0
Bank Sta=4995.6,4999.6
Exp/Cntr=0.3,0.1

Type RM Length L Ch R = 1,19016,515,515,515
BEGIN DESCRIPTION:
DUCK CREEK TRIB 29 38 0
END DESCRIPTION:
XS GIS Cut Line= 4
      3511075.17     10432760.60      3510710.57     10432721.54
      3510400.68     10432757.99      3510185.78     10432804.60
#Sta/Elev= 30
  4544.2  439.94  4632.7  438.06  4818.8  433.18  4869.1  432.58  4889.2  431.23
  4929.5  426.61  4949.6  427.04  4954.6  429.19  4959.7  429.28  4969.8  428.84
  4989.9  423.65  4998.0  423.16  4998.2  422.66  5002.0  423.16  5010.0  423.78
  5030.2  423.62  5037.7  424.92  5050.3  428.70  5070.4  430.87  5110.7  431.52
  5130.9  427.87  5140.9  427.68  5151.0  429.26  5161.1  431.95  5265.6  433.99
  5272.6  433.60  5303.3  435.35  5348.1  435.77  5374.9  435.86  5442.8  437.77
#Mann=5,-1,0
  4544.2    0.05       0  4632.7    0.16       0  4998.0    0.07       0
  5002.0    0.16       0  5348.1     0.1       0
Bank Sta=4998,5002
Exp/Cntr=0.3,0.1

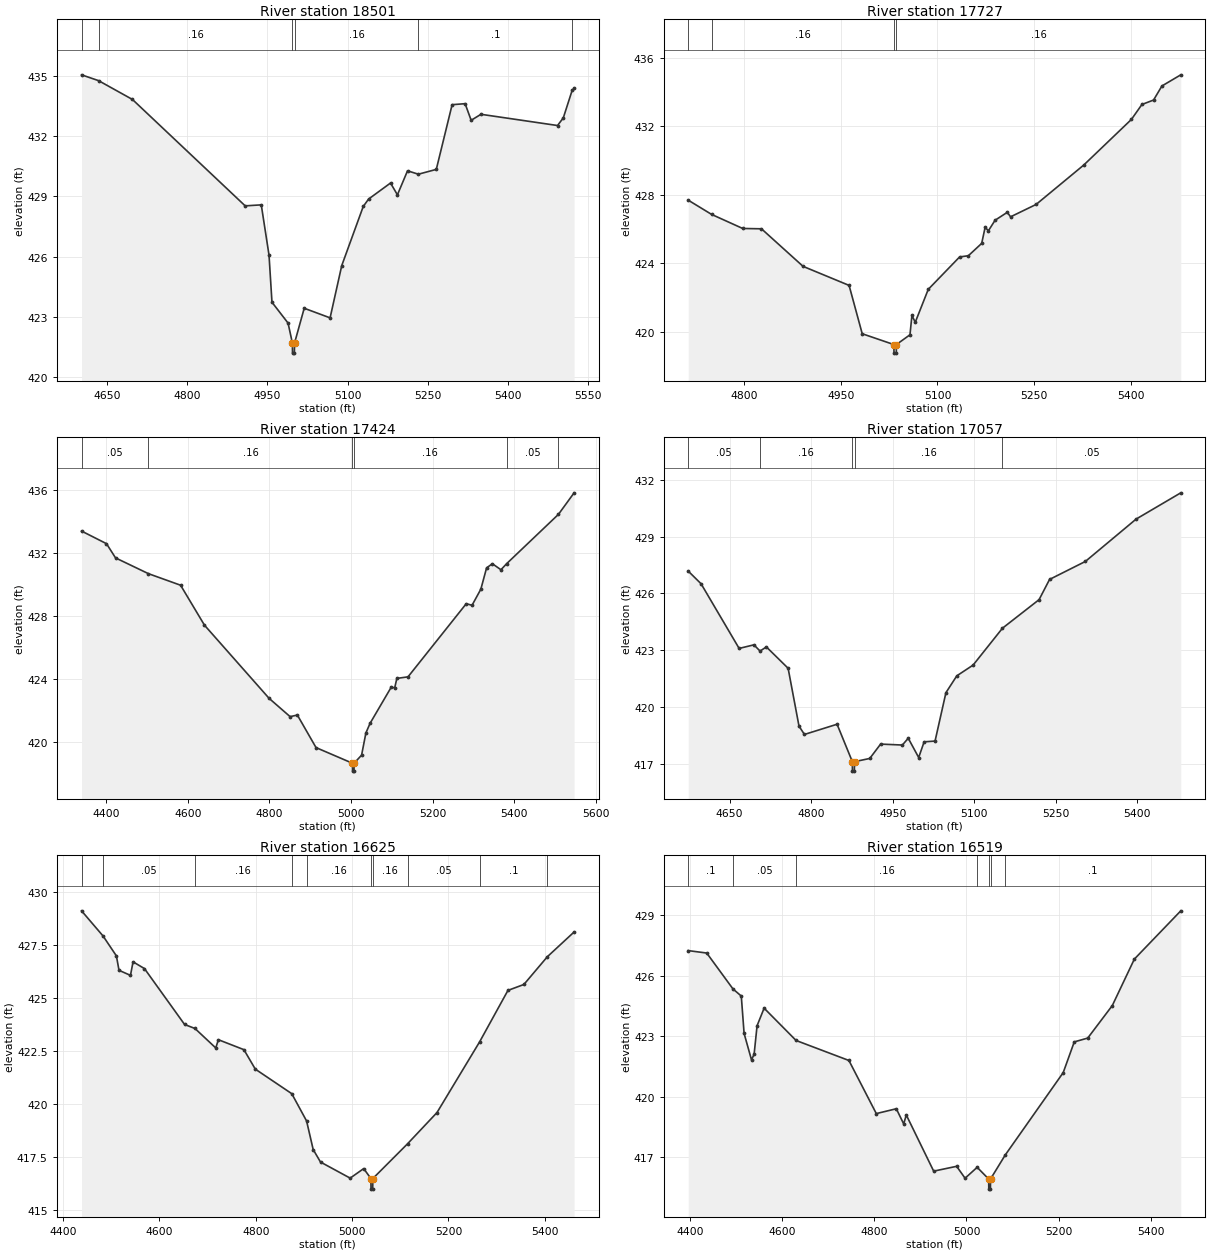
Type RM Length L Ch R = 1,18501,774,774,774
BEGIN DESCRIPTION:
DUCK CREEK TRIB 29 37 0
END DESCRIPTION:
XS GIS Cut Line= 3
      3511036.96     10432296.30      3510473.72     10432248.40
      3510143.35     10432380.55
#Sta/Elev= 30
  4602.6  435.07  4634.4  434.78  4697.8  433.84  4908.6  428.53  4938.7  428.58
  4953.2  426.07  4958.7  423.72  4988.8  422.68  4996.9  421.68  4997.1  421.18
  5000.6  421.18  5000.9  421.68  5019.0  423.42  5067.4  422.94  5089.2  425.55
  5129.4  428.50  5139.4  428.87  5180.4  429.67  5193.3  429.08  5212.2  430.28
  5232.5  430.11  5266.0  430.35  5295.6  433.58  5319.9  433.63  5331.2  432.80
  5349.5  433.10  5492.7  432.54  5503.5  432.92  5520.0  434.29  5523.7  434.39
#Mann=6,-1,0
  4602.6    0.05       0  4634.4    0.16       0  4996.9    0.07       0
  5000.9    0.16       0  5232.5     0.1       0  5520.0    0.05       0
Bank Sta=4996.9,5000.9
Exp/Cntr=0.3,0.1

Type RM Length L Ch R = 1,17727,303,303,303
BEGIN DESCRIPTION:
DUCK CREEK TRIB 29 35 0
END DESCRIPTION:
XS GIS Cut Line= 4
      3510885.05     10431737.16      3510697.27     10431596.81
      3510592.05     10431575.01      3510183.86     10431687.15
#Sta/Elev= 30
  4712.8  427.68  4749.1  426.85  4797.4  426.03  4826.6  426.01  4891.2  423.82
  4962.7  422.71  4983.1  419.89  5032.2  419.26  5032.5  418.76  5036.0  418.76
  5036.2  419.26  5057.3  419.83  5060.3  420.96  5065.5  420.56  5085.7  422.48
  5134.4  424.37  5148.0  424.44  5168.7  425.16  5174.0  426.09  5179.2  425.90
  5189.5  426.51  5208.4  426.97  5213.6  426.71  5253.2  427.43  5327.3  429.73
  5401.3  432.39  5417.6  433.26  5435.7  433.52  5448.7  434.34  5478.0  434.99
#Mann=4,-1,0
  4712.8     0.1       0  4749.1    0.16       0  5032.2    0.07       0
  5036.2    0.16       0
Bank Sta=5032.2,5036.2
Exp/Cntr=0.3,0.1

Type RM Length L Ch R = 1,17424,367,367,367
BEGIN DESCRIPTION:
DUCK CREEK TRIB 29 34 0
END DESCRIPTION:
XS GIS Cut Line= 4
      3511190.29     10431401.18      3510804.03     10431275.32
      3510400.39     10431379.49      3510116.58     10431639.46
#Sta/Elev= 30
  4339.1  433.38  4400.3  432.58  4422.5  431.68  4503.3  430.68  4582.0  429.95
  4640.6  427.42  4799.0  422.79  4850.6  421.63  4868.4  421.73  4914.2  419.67
  5003.5  418.68  5003.8  418.18  5007.3  418.18  5007.5  418.68  5025.9  419.19
  5036.5  420.60  5046.8  421.21  5098.5  423.49  5107.2  423.46  5112.4  424.05
  5139.8  424.15  5282.6  428.78  5296.8  428.68  5318.4  429.70  5332.5  431.05
  5346.7  431.31  5367.7  430.93  5381.5  431.31  5508.8  434.44  5547.1  435.80
#Mann=6,-1,0
  4339.1    0.05       0  4503.3    0.16       0  5003.5    0.07       0
  5007.5    0.16       0  5381.5    0.05       0  5508.8    0.16       0
Bank Sta=5003.5,5007.5
Exp/Cntr=0.3,0.1

Type RM Length L Ch R = 1,17057,432,432,432
BEGIN DESCRIPTION:
DUCK CREEK TRIB 29 32 1
END DESCRIPTION:
XS GIS Cut Line= 3
      3510995.67     10431031.08      3510354.79     10431007.95
      3510096.28     10431063.94
#Sta/Elev= 30
  4574.1  427.18  4597.7  426.51  4667.7  423.09  4694.9  423.28  4706.2  422.95
  4717.8  423.17  4757.8  422.04  4777.8  418.98  4787.8  418.54  4847.8  419.08
  4875.9  417.10  4876.1  416.60  4879.6  416.60  4879.9  417.10  4907.9  417.27
  4927.9  418.03  4967.9  417.98  4978.7  418.34  4997.9  417.32  5007.9  418.15
  5028.0  418.19  5048.0  420.75  5068.0  421.64  5098.0  422.21  5152.0  424.16
  5219.3  425.67  5238.6  426.74  5304.4  427.69  5397.7  429.93  5479.9  431.32
#Mann=5,-1,0
  4574.1    0.05       0  4706.2    0.16       0  4875.9    0.07       0
  4879.9    0.16       0  5152.0    0.05       0
Bank Sta=4875.9,4879.9
Exp/Cntr=0.3,0.1

Type RM Length L Ch R = 1,16625,106,106,106
BEGIN DESCRIPTION:
DUCK CREEK TRIB 29 26 1
END DESCRIPTION:
XS GIS Cut Line= 3
      3511189.47     10430546.82      3510744.60     10430733.45
      3510258.52     10430969.97
#Sta/Elev= 30
  4438.1  429.12  4482.8  427.93  4510.5  426.99  4515.9  426.31  4539.7  426.07
  4545.1  426.71  4568.8  426.39  4652.1  423.75  4673.7  423.56  4716.9  422.64
  4722.3  423.03  4775.3  422.56  4799.0  421.64  4874.7  420.48  4905.5  419.19
  4919.2  417.84  4934.4  417.25  4996.0  416.49  5024.1  416.94  5039.1  416.47
  5039.3  415.97  5042.8  415.97  5043.1  416.47  5115.1  418.11  5176.4  419.59
  5264.9  422.93  5323.7  425.36  5356.8  425.64  5405.5  426.95  5461.1  428.12
#Mann=10,-1,0
  4438.1     0.1       0  4482.8    0.05       0  4673.7    0.16       0
  4874.7    0.05       0  4905.5    0.16       0  5039.1    0.07       0
  5043.1    0.16       0  5115.1    0.05       0  5264.9     0.1       0
  5405.5    0.05       0
Bank Sta=5039.1,5043.1
Exp/Cntr=0.3,0.1

Type RM Length L Ch R = 1,16519,522,522,522
BEGIN DESCRIPTION:
DUCK CREEK TRIB 29 32 0
END DESCRIPTION:
XS GIS Cut Line= 3
      3511182.95     10430377.55      3510686.00     10430653.15
      3510221.58     10430844.13
#Sta/Elev= 30
  4395.3  427.24  4435.5  427.12  4492.6  425.34  4510.6  424.99  4516.7  423.14
  4532.8  421.83  4538.5  422.11  4544.9  423.52  4560.2  424.39  4629.7  422.79
  4744.5  421.80  4804.0  419.17  4847.5  419.41  4863.5  418.66  4869.2  419.10
  4928.7  416.32  4978.6  416.56  4996.9  415.97  5023.2  416.51  5048.2  415.93
  5048.5  415.43  5052.0  415.43  5052.2  415.93  5084.2  417.12  5210.2  421.20
  5234.2  422.72  5263.5  422.91  5316.9  424.52  5364.8  426.82  5465.7  429.21
#Mann=7,-1,0
  4395.3     0.1       0  4492.6    0.05       0  4629.7    0.16       0
  5023.2    0.05       0  5048.2    0.07       0  5052.2    0.05       0
  5084.2     0.1       0
Bank Sta=5048.2,5052.2
Exp/Cntr=0.3,0.1

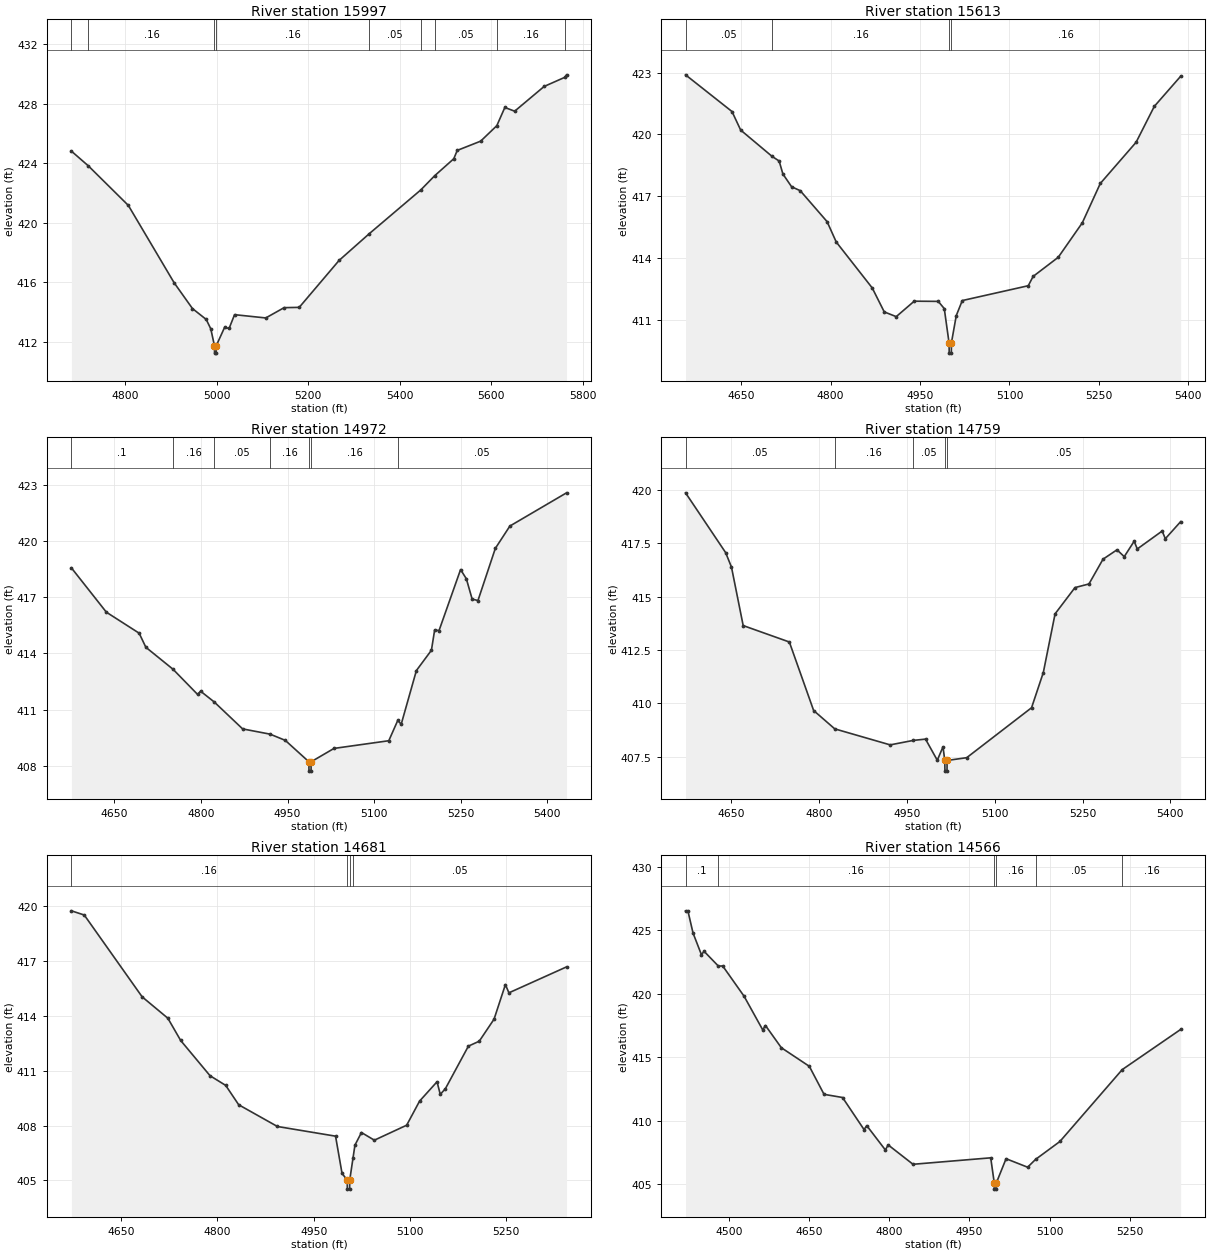
Type RM Length L Ch R = 1,15997,384,384,384
BEGIN DESCRIPTION:
DUCK CREEK TRIB 29 26 3
END DESCRIPTION:
XS GIS Cut Line= 3
      3511106.27     10430211.83      3510472.06     10430256.42
      3510085.53     10430481.76
#Sta/Elev= 30
  4681.7  424.81  4718.8  423.82  4806.2  421.17  4906.4  415.98  4946.5  414.25
  4976.6  413.52  4986.6  412.89  4994.6  411.76  4994.9  411.26  4998.4  411.26
  4998.6  411.76  5016.7  412.98  5026.7  412.92  5038.6  413.84  5106.9  413.62
  5147.0  414.31  5180.1  414.33  5267.3  417.48  5333.6  419.28  5446.1  422.21
  5476.4  423.16  5518.2  424.30  5525.8  424.86  5577.0  425.48  5612.4  426.52
  5629.9  427.74  5651.4  427.49  5715.9  429.15  5760.9  429.76  5764.9  429.93
#Mann=9,-1,0
  4681.7    0.05       0  4718.8    0.16       0  4994.6    0.07       0
  4998.6    0.16       0  5333.6    0.05       0  5446.1    0.16       0
  5476.4    0.05       0  5612.4    0.16       0  5760.9     0.1       0
Bank Sta=4994.6,4998.6
Exp/Cntr=0.3,0.1

Type RM Length L Ch R = 1,15613,641,641,641
BEGIN DESCRIPTION:
DUCK CREEK TRIB 29 31 0
END DESCRIPTION:
XS GIS Cut Line= 3
      3511129.44     10430033.43      3510949.41     10429898.00
      3510348.18     10429828.63
#Sta/Elev= 30
  4556.7  422.89  4634.6  421.11  4649.2  420.21  4702.0  418.93  4713.7  418.71
  4720.0  418.08  4734.6  417.46  4749.1  417.27  4794.1  415.77  4809.5  414.78
  4869.9  412.55  4890.0  411.39  4910.1  411.16  4940.3  411.91  4980.6  411.90
  4990.7  411.55  4998.7  409.89  4999.0  409.39  5002.5  409.39  5002.7  409.89
  5010.8  411.21  5020.9  411.94  5131.6  412.66  5139.7  413.11  5181.9  414.04
  5222.2  415.71  5252.4  417.62  5312.5  419.62  5343.0  421.36  5387.2  422.82
#Mann=4,-1,0
  4556.7    0.05       0  4702.0    0.16       0  4998.7    0.07       0
  5002.7    0.16       0
Bank Sta=4998.7,5002.7
Exp/Cntr=0.3,0.1

Type RM Length L Ch R = 1,14972,213,213,213
BEGIN DESCRIPTION:
DUCK CREEK TRIB 29 29 0
END DESCRIPTION:
XS GIS Cut Line= 3
      3511253.32     10429546.18      3510655.40     10429346.32
      3510429.17     10429364.49
#Sta/Elev= 30
  4575.8  418.56  4636.3  416.20  4693.1  415.08  4704.7  414.33  4751.7  413.16
  4794.2  411.82  4799.5  411.99  4823.3  411.41  4872.3  409.98  4919.9  409.70
  4946.1  409.37  4987.0  408.23  4987.2  407.73  4990.7  407.73  4991.0  408.23
  5030.5  408.94  5125.4  409.35  5140.9  410.43  5146.9  410.23  5173.2  413.09
  5199.2  414.17  5204.8  415.25  5212.4  415.22  5249.7  418.47  5259.7  417.98
  5269.7  416.90  5279.8  416.82  5309.9  419.60  5335.1  420.79  5433.2  422.56
#Mann=7,-1,0
  4575.8     0.1       0  4751.7    0.16       0  4823.3    0.05       0
  4919.9    0.16       0  4987.0    0.07       0  4991.0    0.16       0
  5140.9    0.05       0
Bank Sta=4987,4991
Exp/Cntr=0.3,0.1

Type RM Length L Ch R = 1,14759,78,78,78
BEGIN DESCRIPTION:
DUCK CREEK TRIB 29 28 0
END DESCRIPTION:
XS GIS Cut Line= 4
      3511380.50     10429265.39      3511205.43     10429257.13
      3510741.29     10429204.27      3510552.97     10429126.63
#Sta/Elev= 30
  4571.5  419.86  4640.0  417.06  4650.0  416.38  4670.0  413.64  4748.9  412.87
  4790.4  409.66  4826.5  408.80  4921.2  408.05  4960.8  408.26  4981.6  408.32
  5001.7  407.33  5011.5  407.96  5014.5  407.32  5014.8  406.82  5018.3  406.82
  5018.5  407.32  5052.0  407.45  5162.8  409.79  5182.9  411.44  5203.0  414.19
  5237.0  415.42  5260.9  415.59  5284.9  416.75  5308.8  417.19  5321.2  416.87
  5338.1  417.59  5343.5  417.23  5386.0  418.07  5391.4  417.71  5417.6  418.51
#Mann=5,-1,0
  4571.5    0.05       0  4826.5    0.16       0  4960.8    0.05       0
  5014.5    0.04       0  5018.5    0.05       0
Bank Sta=5014.5,5018.5
Exp/Cntr=0.3,0.1

Type RM Length L Ch R = 1,14681,115,115,115
BEGIN DESCRIPTION:
DUCK CREEK TRIB 29 26 2
END DESCRIPTION:
XS GIS Cut Line= 4
      3511392.11     10429167.94      3511175.70     10429174.54
      3510775.98     10429131.60      3510637.25     10429068.84
#Sta/Elev= 30
  4572.9  419.76  4592.9  419.53  4683.0  415.05  4723.0  413.88  4743.0  412.66
  4788.7  410.73  4813.1  410.20  4833.3  409.14  4893.6  407.95  4984.1  407.42
  4994.2  405.38  5002.2  405.02  5002.5  404.52  5006.0  404.52  5006.2  405.02
  5011.4  406.25  5014.3  406.93  5024.4  407.62  5044.5  407.20  5094.8  408.02
  5114.9  409.34  5142.1  410.40  5147.1  409.71  5155.1  410.02  5190.9  412.35
  5207.8  412.62  5230.9  413.83  5248.5  415.72  5254.0  415.27  5343.7  416.69
#Mann=4,-1,0
  4572.9    0.16       0  5002.2    0.07       0  5006.2    0.16       0
  5011.4    0.05       0
Bank Sta=5002.2,5006.2
Exp/Cntr=0.3,0.1

Type RM Length L Ch R = 1,14566,263,263,263
BEGIN DESCRIPTION:
DUCK CREEK TRIB 29 26 0
END DESCRIPTION:
XS GIS Cut Line= 4
      3511545.63     10428908.95      3511132.46     10429020.05
      3510872.05     10429051.30      3510636.51     10429040.91
#Sta/Elev= 30
  4419.3  426.55  4423.7  426.55  4433.3  424.80  4448.9  423.10  4454.1  423.35
  4480.7  422.19  4488.8  422.20  4528.8  419.81  4563.6  417.16  4568.8  417.50
  4598.4  415.75  4650.8  414.28  4678.3  412.07  4712.9  411.82  4753.1  409.29
  4758.2  409.60  4793.0  407.68  4798.2  408.08  4844.7  406.55  4990.0  407.06
  4996.6  405.09  4996.8  404.59  5000.3  404.59  5000.6  405.09  5018.7  406.99
  5059.0  406.32  5074.0  406.94  5119.4  408.35  5235.9  414.02  5345.2  417.19
#Mann=6,-1,0
  4419.3     0.1       0  4480.7    0.16       0  4996.6    0.07       0
  5000.6    0.16       0  5074.0    0.05       0  5235.9    0.16       0
Bank Sta=4996.6,5000.6
Exp/Cntr=0.3,0.1

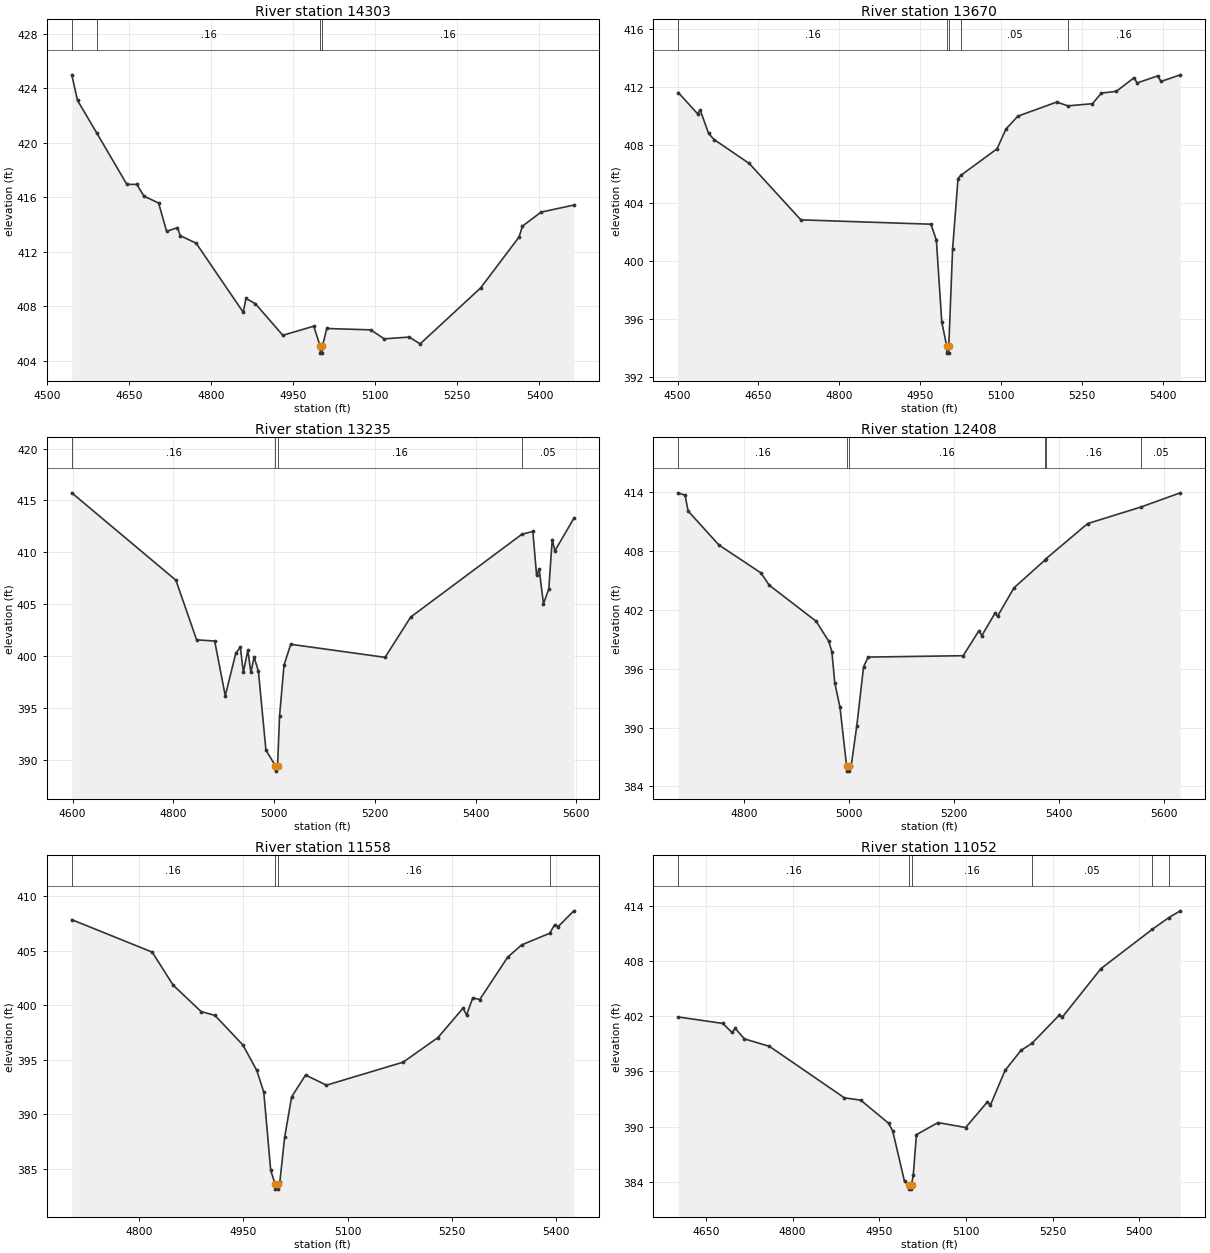
Type RM Length L Ch R = 1,14303,633,633,633
BEGIN DESCRIPTION:
DUCK CREEK TRIB 29 25 2
END DESCRIPTION:
XS GIS Cut Line= 3
      3511539.11     10428878.90      3511322.70     10428819.42
      3510632.28     10428873.93
#Sta/Elev= 30
  4545.8  425.00  4556.3  423.12  4591.8  420.70  4646.4  416.95  4664.7  416.95
  4677.5  416.09  4704.4  415.58  4719.0  413.50  4738.8  413.77  4744.0  413.18
  4773.0  412.63  4859.0  407.55  4864.0  408.57  4881.2  408.18  4931.3  405.86
  4987.8  406.53  4999.5  405.05  4999.8  404.55  5003.3  404.55  5003.5  405.05
  5011.6  406.36  5091.8  406.26  5116.5  405.60  5162.0  405.73  5182.1  405.23
  5292.5  409.34  5362.7  413.08  5368.9  413.88  5402.8  414.91  5462.8  415.43
#Mann=4,-1,0
  4545.8     0.1       0  4591.8    0.16       0  4999.5    0.07       0
  5003.5    0.16       0
Bank Sta=4999.5,5003.5
Exp/Cntr=0.3,0.1

Type RM Length L Ch R = 1,13670,435,435,435
BEGIN DESCRIPTION:
DUCK CREEK TRIB 29 25 3
END DESCRIPTION:
XS GIS Cut Line= 3
      3511278.06     10428451.09      3510739.64     10428391.63
      3510560.06     10428737.61
#Sta/Elev= 30
  4501.1  411.61  4536.9  410.15  4541.9  410.40  4557.4  408.79  4567.5  408.37
  4632.8  406.72  4728.6  402.83  4969.9  402.53  4980.0  401.44  4990.0  395.80
  4999.1  394.14  4999.4  393.64  5002.9  393.64  5003.1  394.14  5010.1  400.81
  5020.2  405.68  5025.1  405.89  5092.6  407.73  5109.1  409.09  5131.2  409.98
  5203.2  410.95  5224.2  410.69  5269.6  410.84  5286.1  411.57  5313.8  411.69
  5346.8  412.63  5352.4  412.27  5391.0  412.76  5396.7  412.37  5432.6  412.83
#Mann=5,-1,0
  4501.1    0.16       0  4999.1    0.07       0  5003.1    0.16       0
  5025.1    0.05       0  5224.2    0.16       0
Bank Sta=4999.1,5003.1
Exp/Cntr=0.3,0.1

Type RM Length L Ch R = 1,13235,827,827,827
BEGIN DESCRIPTION:
DUCK CREEK TRIB 29 25 1
END DESCRIPTION:
XS GIS Cut Line= 4
      3511400.32     10428351.98      3511203.78     10428302.43
      3510774.33     10428010.08      3510515.19     10428100.29
#Sta/Elev= 30
  4598.3  415.73  4805.0  407.31  4846.1  401.57  4882.0  401.45  4903.0  396.18
  4924.0  400.30  4932.9  400.84  4938.9  398.44  4947.8  400.57  4953.8  398.43
  4960.3  399.90  4968.8  398.54  4983.7  390.95  5002.6  389.42  5002.9  388.92
  5006.8  389.42  5010.7  394.20  5019.6  399.12  5032.9  401.14  5220.2  399.88
  5271.0  403.76  5491.5  411.73  5513.5  412.01  5520.9  407.82  5526.2  408.35
  5534.6  405.04  5545.2  406.47  5552.0  411.23  5557.2  410.14  5594.9  413.27
#Mann=4,-1,0
  4598.3    0.16       0  5002.6    0.07       0  5006.8    0.16       0
  5491.5    0.05       0
Bank Sta=5002.6,5006.8
Exp/Cntr=0.3,0.1

Type RM Length L Ch R = 1,12408,850,850,850
BEGIN DESCRIPTION:
DUCK CREEK TRIB 29 25 0
END DESCRIPTION:
XS GIS Cut Line= 4
      3511433.37     10427896.11      3511230.20     10427777.19
      3510828.84     10427625.23      3510538.17     10427653.30
#Sta/Elev= 30
  4674.0  413.86  4687.0  413.66  4692.8  412.04  4751.5  408.58  4831.6  405.74
  4847.3  404.49  4936.7  400.82  4960.8  398.78  4966.8  397.70  4972.2  394.56
  4982.2  392.05  4994.8  386.06  4995.1  385.56  4998.8  385.56  4999.1  386.06
  5003.6  386.13  5014.3  390.20  5027.1  396.17  5035.7  397.17  5216.9  397.31
  5247.0  399.86  5252.4  399.35  5277.2  401.61  5282.5  401.34  5313.7  404.22
  5372.6  407.04  5374.9  407.19  5454.1  410.76  5555.3  412.44  5630.6  413.89
#Mann=6,-1,0
  4674.0    0.16       0  4994.8    0.07       0  4999.1    0.16       0
  5372.6    0.05       0  5374.9    0.16       0  5555.3    0.05       0
Bank Sta=4994.8,4999.1
Exp/Cntr=0.3,0.1

Type RM Length L Ch R = 1,11558,506,506,506
BEGIN DESCRIPTION:
DUCK CREEK TRIB 29 23 0
END DESCRIPTION:
XS GIS Cut Line= 2
      3511497.58     10427259.00      3510777.12     10427204.75
#Sta/Elev= 30
  4703.0  407.84  4818.8  404.86  4848.9  401.83  4889.0  399.41  4909.1  399.05
  4949.2  396.34  4969.2  394.01  4979.3  392.01  4989.3  384.83  4995.4  383.61
  4995.6  383.11  4999.4  383.11  4999.7  383.61  5002.5  383.81  5009.3  387.85
  5019.4  391.58  5039.4  393.58  5069.5  392.65  5179.8  394.76  5230.0  397.02
  5266.1  399.72  5271.1  399.09  5280.1  400.67  5290.1  400.51  5330.2  404.39
  5350.3  405.52  5390.7  406.59  5397.9  407.38  5402.9  407.20  5425.5  408.65
#Mann=4,-1,0
  4703.0    0.16       0  4995.4    0.07       0  4999.7    0.16       0
  5390.7    0.05       0
Bank Sta=4995.4,4999.7
Exp/Cntr=0.3,0.1

Type RM Length L Ch R = 1,11052,688,688,688
BEGIN DESCRIPTION:
Mapping XS 7762d81e
END DESCRIPTION:
XS GIS Cut Line= 4
      3511384.74     10427074.56      3511241.50     10426822.80
      3510968.06     10426759.87      3510681.64     10426844.49
#Sta/Elev= 30
  4602.1  401.90  4679.2  401.20  4695.1  400.22  4700.8  400.65  4716.7  399.52
  4759.9  398.71  4889.6  393.12  4918.0  392.86  4966.0  390.36  4973.2  389.54
  4993.7  384.03  5001.4  383.70  5001.7  383.20  5005.5  383.20  5005.8  383.70
  5008.8  384.71  5014.3  389.11  5051.6  390.43  5099.5  389.89  5137.2  392.68
  5142.3  392.32  5167.7  396.09  5195.2  398.27  5214.1  399.03  5261.8  402.12
  5267.0  401.90  5333.6  407.15  5422.7  411.43  5451.0  412.69  5471.0  413.43
#Mann=6,-1,0
  4602.1    0.16       0  5001.4    0.07       0  5005.8    0.16       0
  5214.1    0.05       0  5422.7    0.16       0  5451.0    0.05       0
Bank Sta=5001.4,5005.8
Exp/Cntr=0.3,0.1

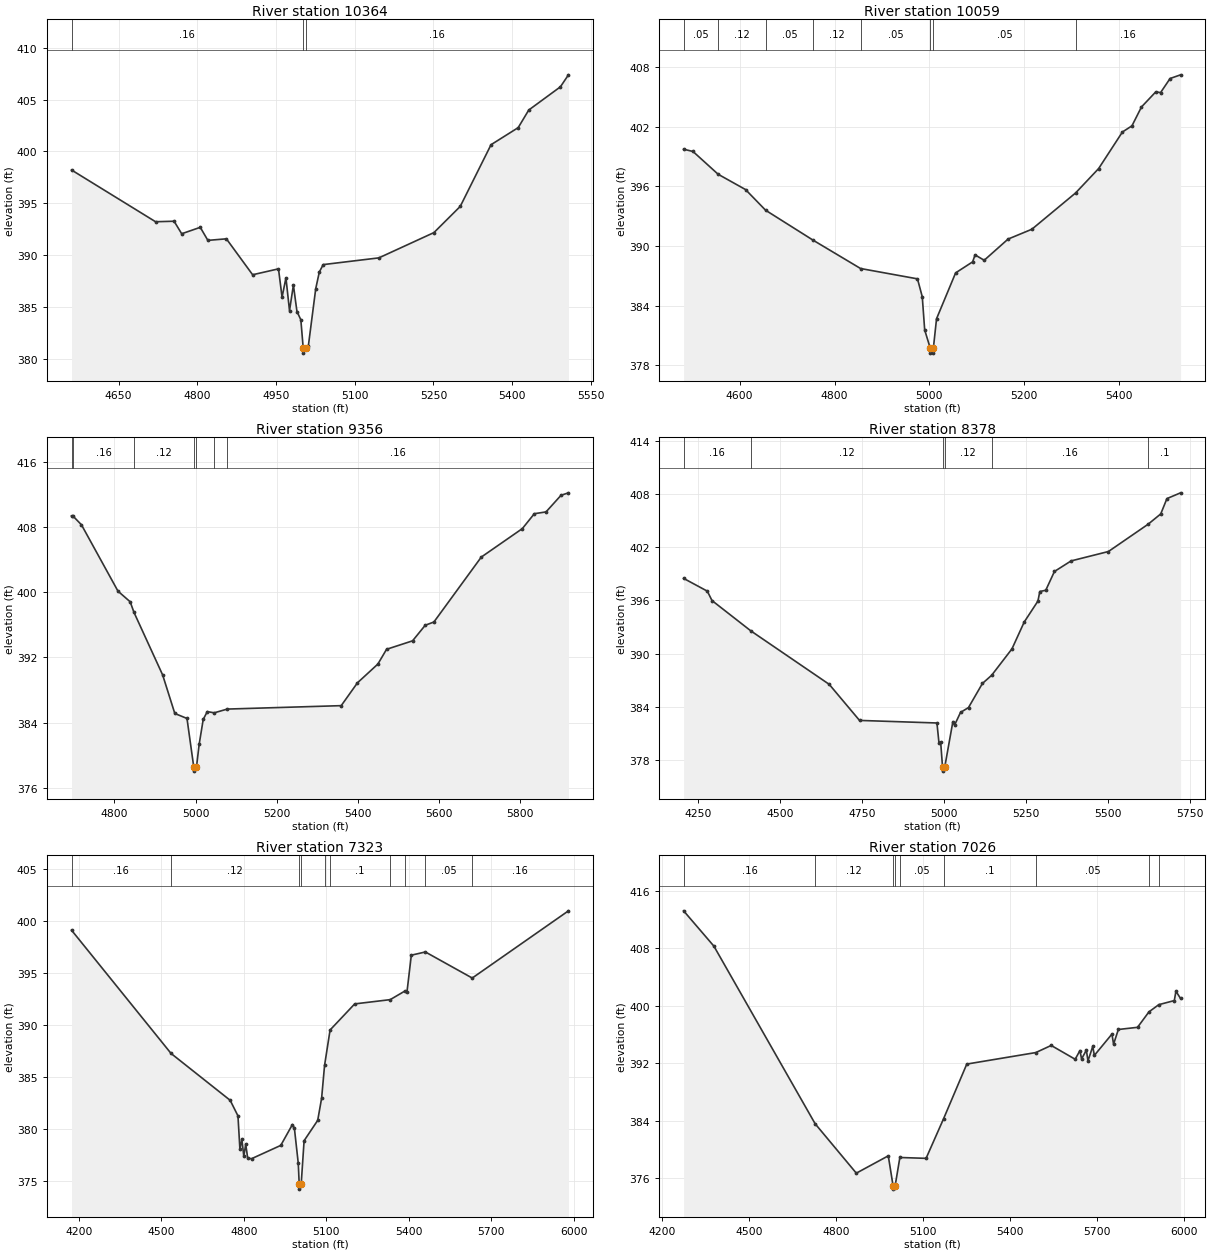
Type RM Length L Ch R = 1,10364,305,305,305
BEGIN DESCRIPTION:
DUCK CREEK TRIB 29 21
END DESCRIPTION:
XS GIS Cut Line= 4
      3511625.64     10426842.37      3511454.17     10426618.81
      3511234.99     10426377.92      3510896.77     10426410.44
#Sta/Elev= 30
  4560.2  398.21  4720.4  393.21  4755.7  393.26  4770.2  392.05  4805.6  392.67
  4820.1  391.41  4855.4  391.56  4905.4  388.09  4954.7  388.66  4961.5  385.92
  4968.9  387.79  4975.7  384.62  4983.1  387.09  4989.9  384.54  4997.3  383.74
  5001.8  381.02  5002.2  380.52  5006.3  381.02  5011.5  381.17  5025.7  386.75
  5032.5  388.35  5039.9  389.07  5146.0  389.72  5250.9  392.16  5301.1  394.69
  5359.8  400.65  5411.6  402.30  5431.7  404.00  5492.0  406.24  5507.4  407.40
#Mann=3,-1,0
  4560.2    0.16       0  5001.8    0.07       0  5006.3    0.16       0
Bank Sta=5001.8,5006.3
Exp/Cntr=0.3,0.1

Type RM Length L Ch R = 1,10059,703,703,703
BEGIN DESCRIPTION:
DUCK CREEK TRIB 29 2 0
END DESCRIPTION:
XS GIS Cut Line= 3
      3511911.75     10426206.78      3511529.80     10426254.52
      3510870.12     10426319.62
#Sta/Elev= 30
  4481.8  399.73  4501.6  399.50  4554.6  397.21  4612.4  395.67  4654.7  393.59
  4754.8  390.58  4854.9  387.73  4974.9  386.69  4985.0  384.89  4990.1  381.55
  5001.8  379.72  5002.3  379.22  5007.9  379.22  5008.4  379.72  5015.1  382.68
  5055.3  387.29  5091.2  388.40  5096.3  389.10  5115.6  388.56  5165.9  390.69
  5216.1  391.68  5308.3  395.33  5356.8  397.78  5407.0  401.46  5427.1  402.08
  5447.2  403.98  5477.4  405.50  5487.4  405.42  5507.5  406.84  5529.6  407.21
#Mann=8,-1,0
  4481.8    0.05       0  4554.6    0.12       0  4654.7    0.05       0
  4754.8    0.12       0  4854.9    0.05       0  5001.8    0.03       0
  5008.4    0.05       0  5308.3    0.16       0
Bank Sta=5001.8,5008.4
Exp/Cntr=0.3,0.1

Type RM Length L Ch R = 1,9356,978,978,978
BEGIN DESCRIPTION:
DUCK CREEK TRIB 29 19 0
END DESCRIPTION:
XS GIS Cut Line= 3
      3511816.62     10425689.99      3511070.06     10425689.99
      3510659.94     10425935.19
#Sta/Elev= 30
  4694.2  409.36  4697.3  409.36  4718.7  408.26  4808.7  400.12  4838.7  398.82
  4848.1  397.52  4918.7  389.85  4948.7  385.12  4978.7  384.51  4995.4  378.55
  4995.9  378.05  5002.1  378.55  5008.7  381.34  5018.7  384.39  5028.7  385.35
  5045.8  385.20  5078.0  385.66  5358.7  386.08  5398.7  388.88  5449.0  391.18
  5470.4  392.99  5534.5  394.03  5565.7  395.94  5587.1  396.34  5703.8  404.30
  5804.9  407.79  5834.5  409.62  5863.3  409.84  5900.3  411.88  5918.6  412.18
#Mann=7,-1,0
  4694.2    0.05       0  4697.3    0.16       0  4848.1    0.12       0
  4995.4    0.07       0  5002.1    0.12       0  5045.8    0.05       0
  5078.0    0.16       0
Bank Sta=4995.4,5002.1
Exp/Cntr=0.3,0.1

Type RM Length L Ch R = 1,8378,1055,1055,1055
BEGIN DESCRIPTION:
DUCK CREEK TRIB 29 18 0
END DESCRIPTION:
XS GIS Cut Line= 4
      3511740.60     10425355.76      3511467.19     10425038.95
      3510798.79     10424882.70      3510390.80     10424934.78
#Sta/Elev= 30
  4206.0  398.48  4278.3  397.04  4292.6  395.98  4411.1  392.56  4650.2  386.53
  4742.7  382.46  4978.9  382.17  4985.0  379.96  4990.2  380.05  4995.9  377.24
  4996.4  376.74  5002.9  377.24  5027.5  382.32  5032.7  381.93  5050.8  383.36
  5075.2  383.91  5117.7  386.63  5145.8  387.55  5207.8  390.53  5245.2  393.56
  5287.0  395.92  5292.8  397.00  5310.9  397.14  5337.4  399.26  5388.2  400.45
  5502.1  401.51  5622.9  404.58  5661.7  405.75  5680.6  407.48  5722.2  408.13
#Mann=6,-1,0
  4206.0    0.16       0  4411.1    0.12       0  4995.9    0.07       0
  5002.9    0.12       0  5145.8    0.16       0  5622.9     0.1       0
Bank Sta=4995.9,5002.9
Exp/Cntr=0.3,0.1

Type RM Length L Ch R = 1,7323,297,297,297
BEGIN DESCRIPTION:
DUCK CREEK TRIB 29 17 0
END DESCRIPTION:
XS GIS Cut Line= 4
      3512137.79     10425095.40      3511840.45     10424704.75
      3511495.40     10424359.69      3510786.43     10423932.58
#Sta/Elev= 30
  4173.9  399.15  4535.8  387.28  4750.7  382.77  4779.0  381.27  4786.1  378.05
  4793.1  379.03  4800.2  377.40  4807.3  378.53  4814.4  377.19  4828.5  377.15
  4934.6  378.43  4977.0  380.44  4984.1  380.09  4998.2  376.71  5001.6  374.72
  5002.1  374.22  5008.9  374.72  5019.4  378.88  5068.9  380.84  5083.1  382.97
  5093.8  386.13  5113.9  389.54  5203.4  392.05  5332.4  392.46  5387.2  393.31
  5393.6  393.24  5409.2  396.74  5460.3  397.05  5630.7  394.54  5980.5  401.01
#Mann=10,-1,0
  4173.9    0.16       0  4535.8    0.12       0  5001.6    0.07       0
  5008.9    0.12       0  5093.8    0.05       0  5113.9     0.1       0
  5332.4    0.05       0  5387.2     0.1       0  5460.3    0.05       0
  5630.7    0.16       0
Bank Sta=5001.6,5008.9
Exp/Cntr=0.3,0.1

Type RM Length L Ch R = 1,7026,505,505,505
BEGIN DESCRIPTION:
Mapping XS dd020272
END DESCRIPTION:
XS GIS Cut Line= 3
      3512476.28     10424277.23      3511480.21     10424199.10
      3510845.74     10423867.79
#Sta/Elev= 30
  4272.9  413.19  4377.4  408.28  4726.8  383.58  4868.9  376.71  4979.2  379.12
  4995.6  374.99  4996.1  374.49  5003.0  374.99  5019.2  378.89  5109.6  378.77
  5170.0  384.28  5250.1  391.88  5488.2  393.48  5541.4  394.47  5624.1  392.55
  5640.6  393.76  5646.2  392.59  5662.7  393.82  5668.3  392.32  5684.7  394.33
  5690.4  393.09  5751.0  396.05  5756.6  394.65  5773.1  396.69  5839.3  396.99
  5878.7  399.14  5912.6  400.14  5966.2  400.71  5971.8  402.01  5987.8  401.00
#Mann=9,-1,0
  4272.9    0.16       0  4726.8    0.12       0  4995.6    0.07       0
  5003.0    0.12       0  5019.2    0.05       0  5170.0     0.1       0
  5488.2    0.05       0  5878.7    0.16       0  5912.6    0.05       0
Bank Sta=4995.6,5003
Exp/Cntr=0.3,0.1