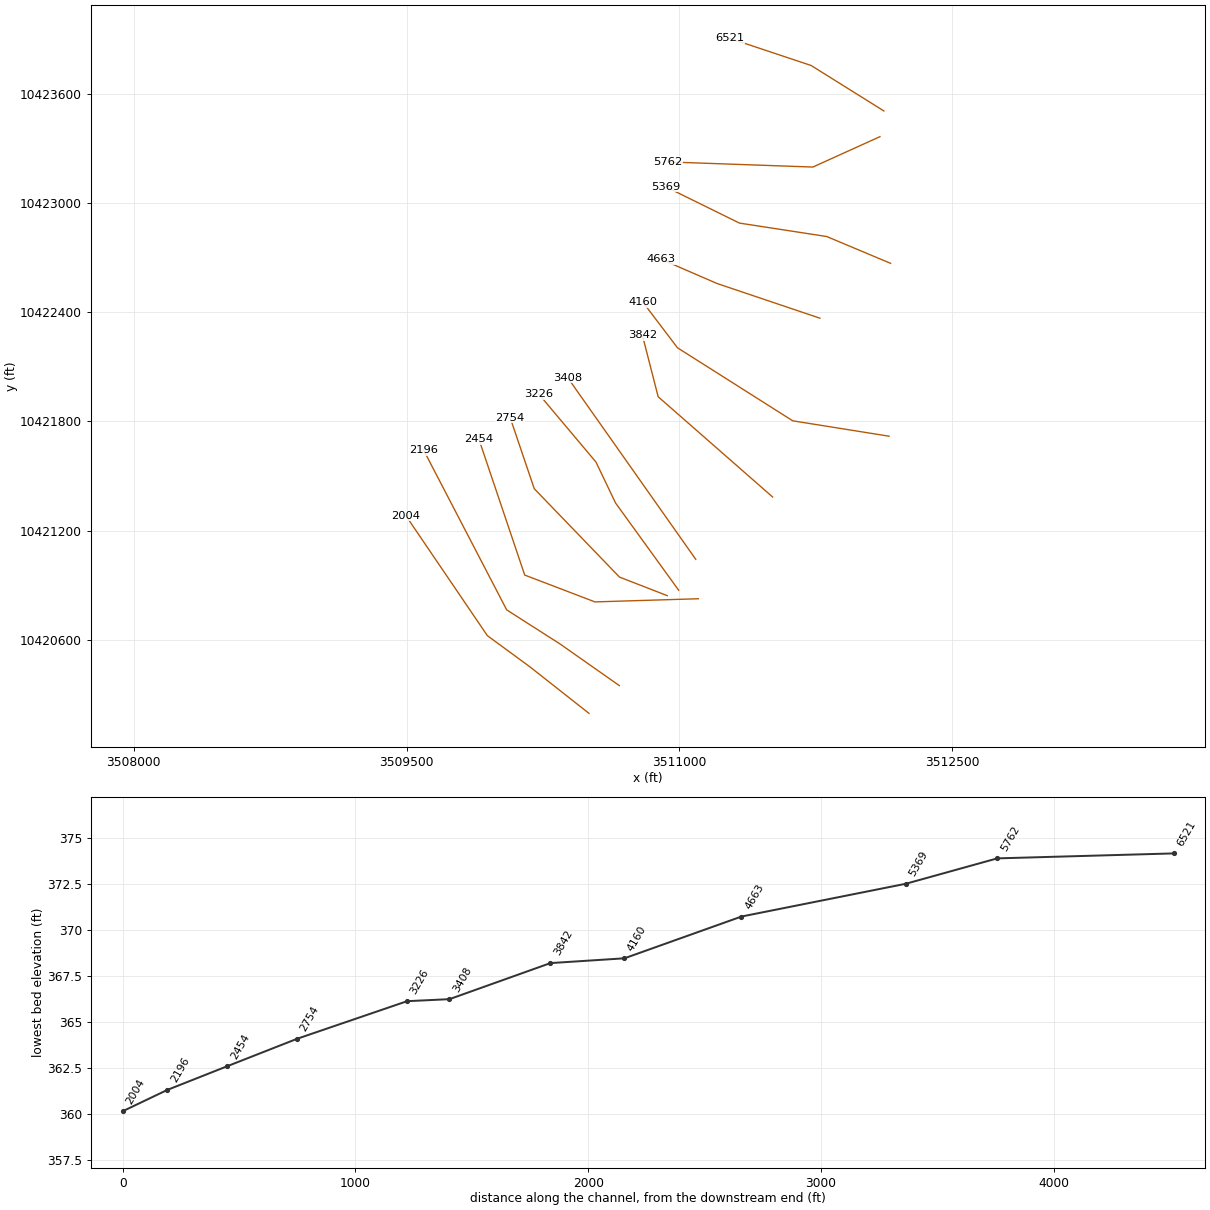
HEC-RAS study DUCK CREEK TRIB 29.prj: DUCK CREEK TRIB 29 Base Level Engineering

--- DUCK CREEK TRIB 29.g01 (geometry) --- (continued)

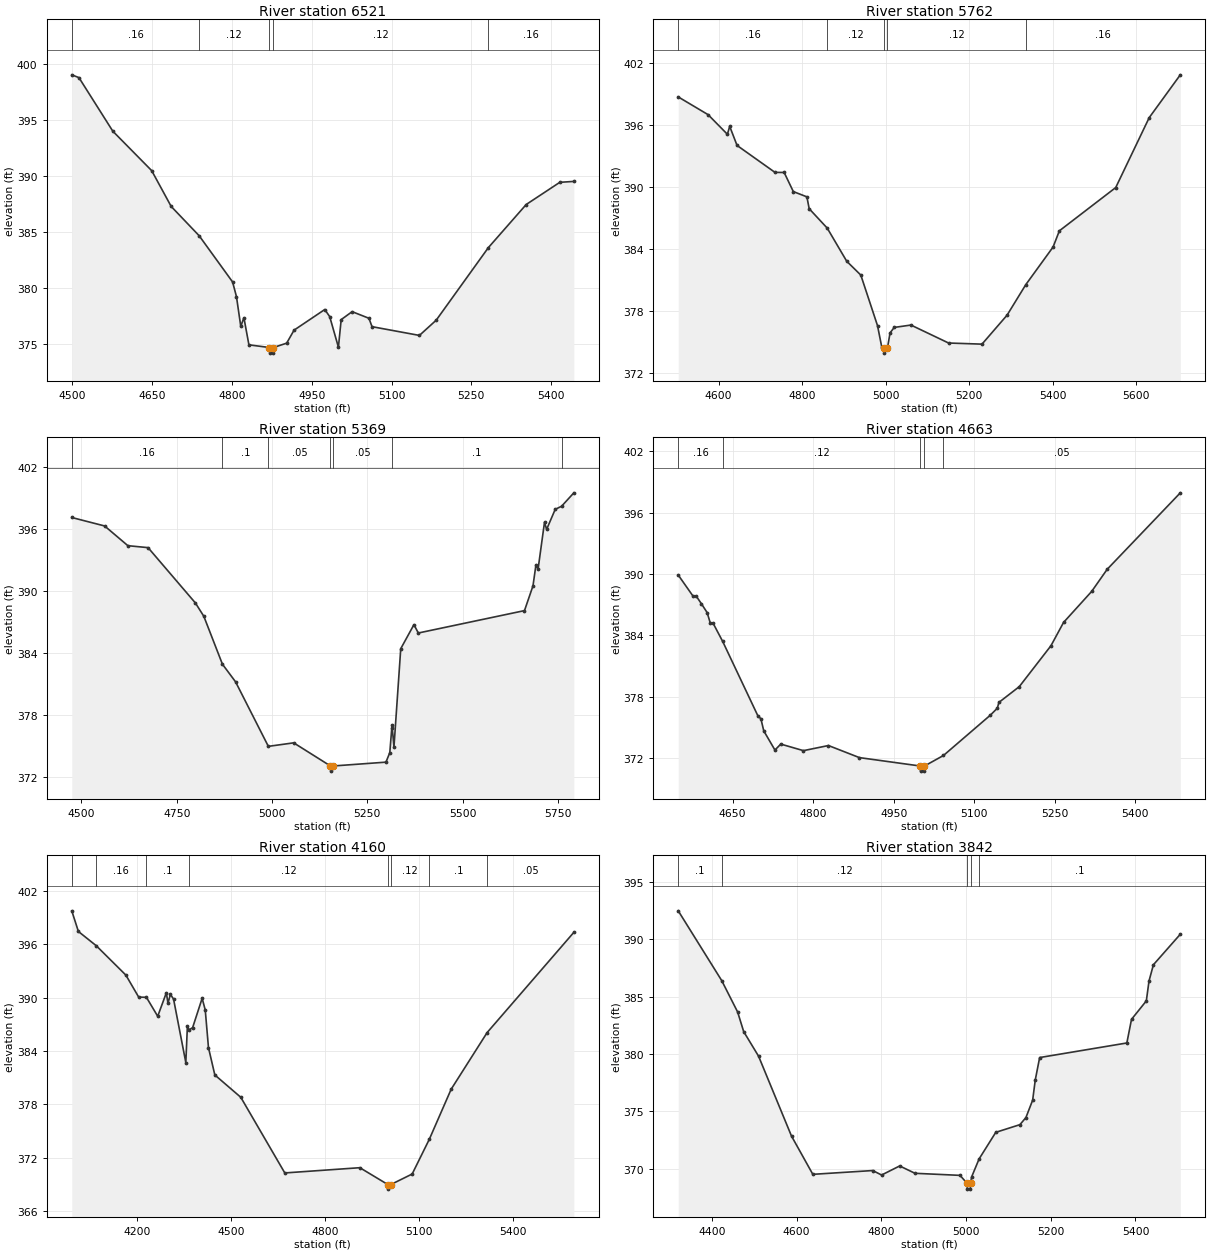
Type RM Length L Ch R = 1,6521,759,759,759
BEGIN DESCRIPTION:
DUCK CREEK TRIB 29 15 0
END DESCRIPTION:
XS GIS Cut Line= 3
      3512124.75     10423507.09      3511724.74     10423757.09
      3511276.59     10423906.48
#Sta/Elev= 30
  4498.7  399.01  4512.2  398.76  4575.9  393.98  4649.0  390.46  4685.6  387.27
  4738.3  384.65  4801.1  380.53  4808.4  379.22  4816.5  376.57  4822.4  377.34
  4831.8  374.92  4870.5  374.68  4871.0  374.18  4877.4  374.18  4877.9  374.68
  4902.8  375.07  4916.7  376.23  4974.4  378.07  4983.7  377.44  5000.1  374.71
  5005.3  377.17  5025.9  377.88  5057.5  377.29  5063.3  376.54  5152.4  375.76
  5184.0  377.12  5282.0  383.59  5353.2  387.44  5416.4  389.42  5442.8  389.50
#Mann=5,-1,0
  4498.7    0.16       0  4738.3    0.12       0  4870.5    0.07       0
  4877.9    0.12       0  5282.0    0.16       0
Bank Sta=4870.5,4877.9
Exp/Cntr=0.3,0.1

Type RM Length L Ch R = 1,5762,393,393,393
BEGIN DESCRIPTION:
DUCK CREEK TRIB 29 92 0
END DESCRIPTION:
XS GIS Cut Line= 3
      3512103.07     10423365.78      3511734.12     10423198.67
      3510937.65     10423226.88
#Sta/Elev= 30
  4503.2  398.73  4574.7  397.01  4620.9  395.11  4626.4  395.88  4644.0  394.03
  4734.8  391.42  4756.8  391.41  4778.7  389.56  4811.2  389.05  4816.7  387.90
  4859.9  386.02  4906.6  382.81  4940.3  381.47  4980.3  376.57  4990.3  374.53
  4996.5  374.41  4997.0  373.91  5004.1  374.41  5010.3  375.87  5020.3  376.40
  5060.3  376.63  5150.4  374.89  5230.4  374.78  5290.5  377.59  5335.2  380.54
  5400.6  384.19  5415.7  385.76  5550.6  389.95  5630.7  396.72  5705.2  400.87
#Mann=5,-1,0
  4503.2    0.16       0  4859.9    0.12       0  4996.5    0.07       0
  5004.1    0.12       0  5335.2    0.16       0
Bank Sta=4996.5,5004.1
Exp/Cntr=0.3,0.1

Type RM Length L Ch R = 1,5369,706,706,706
BEGIN DESCRIPTION:
DUCK CREEK TRIB 29 91 0
END DESCRIPTION:
XS GIS Cut Line= 4
      3512161.63     10422669.16      3511810.07     10422816.73
      3511330.47     10422890.51      3510925.90     10423089.55
#Sta/Elev= 30
  4474.5  397.10  4560.7  396.28  4621.7  394.37  4674.7  394.18  4798.9  388.82
  4821.0  387.53  4869.8  382.89  4904.3  381.18  4990.3  374.93  5056.8  375.27
  5153.3  373.03  5153.8  372.53  5161.1  373.03  5298.9  373.40  5309.0  374.32
  5314.8  376.99  5315.6  376.66  5319.9  374.87  5337.7  384.39  5372.3  386.72
  5383.8  385.91  5662.4  388.08  5684.7  390.48  5692.5  392.52  5698.0  392.09
  5714.9  396.64  5720.5  395.95  5743.0  397.89  5759.7  398.19  5791.9  399.49
#Mann=7,-1,0
  4474.5    0.16       0  4869.8     0.1       0  4990.3    0.05       0
  5153.3    0.03       0  5161.1    0.05       0  5315.6     0.1       0
  5759.7    0.16       0
Bank Sta=5153.3,5161.1
Exp/Cntr=0.3,0.1

Type RM Length L Ch R = 1,4663,503,503,503
BEGIN DESCRIPTION:
DUCK CREEK TRIB 29 9 0
END DESCRIPTION:
XS GIS Cut Line= 3
      3511773.16     10422367.51      3511206.77     10422558.48
      3510896.77     10422692.89
#Sta/Elev= 30
  4548.6  389.90  4576.6  387.81  4581.9  387.86  4591.9  387.09  4602.5  386.23
  4608.1  385.25  4613.4  385.21  4631.4  383.42  4697.3  376.12  4702.6  375.87
  4708.0  374.68  4728.8  372.81  4739.7  373.39  4781.9  372.75  4828.5  373.25
  4886.2  372.07  4999.6  371.25  5000.1  370.75  5007.0  370.75  5007.5  371.25
  5042.9  372.28  5130.1  376.21  5143.3  376.90  5146.1  377.46  5184.1  379.00
  5243.2  383.00  5266.6  385.27  5319.0  388.30  5347.9  390.46  5484.2  397.93
#Mann=5,-1,0
  4548.6    0.16       0  4631.4    0.12       0  4999.6    0.07       0
  5007.5    0.12       0  5042.9    0.05       0
Bank Sta=4999.6,5007.5
Exp/Cntr=0.3,0.1

Type RM Length L Ch R = 1,4160,318,318,318
BEGIN DESCRIPTION:
DUCK CREEK TRIB 29 8 0
END DESCRIPTION:
XS GIS Cut Line= 4
      3512152.97     10421718.63      3511623.44     10421803.27
      3510989.76     10422204.75      3510798.78     10422456.50
#Sta/Elev= 30
  3992.1  399.78  4013.2  397.46  4070.4  395.85  4164.8  392.55  4205.6  390.08
  4230.4  390.05  4266.4  387.92  4294.0  390.57  4299.1  389.38  4306.9  390.39
  4317.0  389.85  4356.1  382.72  4361.1  386.78  4366.3  386.39  4377.8  386.64
  4408.2  389.94  4418.1  388.63  4428.4  384.39  4448.7  381.32  4531.5  378.81
  4672.0  370.30  4911.5  370.89  5001.6  368.98  5002.1  368.48  5009.5  368.98
  5078.5  370.18  5133.4  374.10  5203.0  379.72  5317.8  386.09  5594.5  397.36
#Mann=8,-1,0
  3992.1    0.05       0  4070.4    0.16       0  4230.4     0.1       0
  4366.3    0.12       0  5001.6    0.07       0  5009.5    0.12       0
  5133.4     0.1       0  5317.8    0.05       0
Bank Sta=5001.6,5009.5
Exp/Cntr=0.3,0.1

Type RM Length L Ch R = 1,3842,434,434,434
BEGIN DESCRIPTION:
DUCK CREEK TRIB 29 4 2
END DESCRIPTION:
XS GIS Cut Line= 3
      3511512.79     10421384.41      3510883.42     10421935.65
      3510796.87     10422273.20
#Sta/Elev= 30
  4320.7  392.48  4423.3  386.40  4460.9  383.66  4475.2  381.95  4510.3  379.81
  4588.1  372.84  4638.4  369.51  4779.8  369.84  4800.7  369.45  4843.4  370.24
  4879.5  369.60  4985.8  369.42  5002.7  368.72  5003.2  368.22  5010.1  368.22
  5010.6  368.72  5013.3  369.29  5030.8  370.85  5070.2  373.17  5127.2  373.84
  5141.4  374.46  5157.3  375.98  5163.5  377.75  5173.8  379.69  5379.6  380.96
  5390.6  383.02  5425.6  384.63  5431.9  386.36  5442.3  387.78  5505.8  390.44
#Mann=5,-1,0
  4320.7     0.1       0  4423.3    0.12       0  5002.7    0.07       0
  5010.6    0.12       0  5030.8     0.1       0
Bank Sta=5002.7,5010.6
Exp/Cntr=0.3,0.1

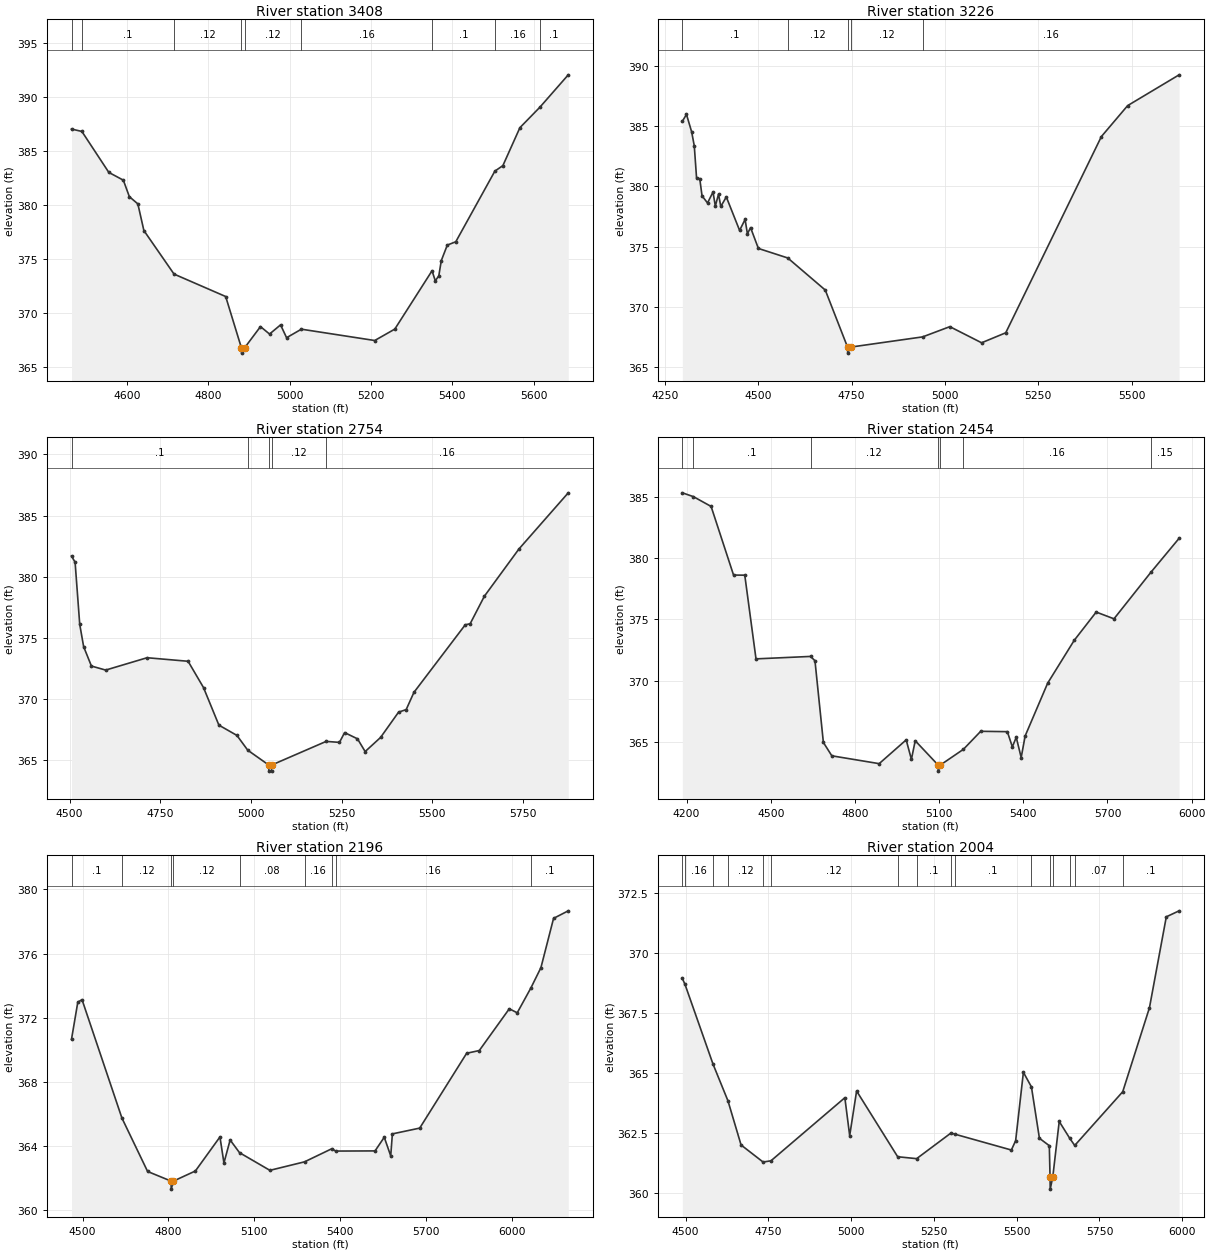
Type RM Length L Ch R = 1,3408,182,182,182
BEGIN DESCRIPTION:
DUCK CREEK TRIB 29 4 0
END DESCRIPTION:
XS GIS Cut Line= 2
      3511090.02     10421041.70      3510386.11     10422040.35
#Sta/Elev= 30
  4463.3  387.04  4488.8  386.82  4555.1  383.02  4590.8  382.30  4605.6  380.77
  4626.5  380.10  4641.3  377.63  4715.5  373.59  4842.5  371.51  4881.1  366.76
  4881.6  366.26  4889.2  366.76  4928.1  368.72  4950.4  368.03  4977.5  368.88
  4992.3  367.69  5028.7  368.48  5209.1  367.43  5258.5  368.49  5350.1  373.90
  5358.0  372.97  5366.7  373.42  5372.8  374.84  5387.6  376.28  5408.5  376.59
  5504.6  383.14  5524.3  383.65  5566.2  387.17  5615.4  389.07  5685.1  392.07
#Mann=9,-1,0
  4463.3    0.05       0  4488.8     0.1       0  4715.5    0.12       0
  4881.1    0.07       0  4889.2    0.12       0  5028.7    0.16       0
  5350.1     0.1       0  5504.6    0.16       0  5615.4     0.1       0
Bank Sta=4881.1,4889.2
Exp/Cntr=0.3,0.1

Type RM Length L Ch R = 1,3226,472,472,472
BEGIN DESCRIPTION:
DUCK CREEK TRIB 29 4 4
END DESCRIPTION:
XS GIS Cut Line= 4
      3510996.30     10420871.53      3510649.10     10421351.40
      3510541.41     10421576.43      3510226.86     10421950.48
#Sta/Elev= 30
  4296.9  385.42  4307.9  385.99  4321.7  384.55  4328.8  383.38  4334.9  380.72
  4343.5  380.64  4349.6  379.22  4364.3  378.63  4379.0  379.54  4385.2  378.37
  4393.7  379.36  4399.9  378.34  4414.6  379.13  4450.2  376.35  4464.9  377.26
  4471.1  376.07  4479.6  376.58  4500.5  374.85  4579.1  374.06  4679.7  371.39
  4739.3  366.65  4739.8  366.15  4747.4  366.65  4940.5  367.50  5013.3  368.35
  5098.4  367.01  5163.0  367.84  5419.2  384.15  5489.5  386.72  5627.4  389.28
#Mann=5,-1,0
  4296.9     0.1       0  4579.1    0.12       0  4739.3    0.07       0
  4747.4    0.12       0  4940.5    0.16       0
Bank Sta=4739.3,4747.4
Exp/Cntr=0.3,0.1

Type RM Length L Ch R = 1,2754,300,300,300
BEGIN DESCRIPTION:
DUCK CREEK TRIB 29 4 3
END DESCRIPTION:
XS GIS Cut Line= 4
      3510933.30     10420841.91      3510670.75     10420943.90
      3510202.00     10421430.01      3510069.62     10421820.63
#Sta/Elev= 30
  4505.5  381.69  4515.4  381.19  4528.2  376.10  4539.0  374.28  4560.4  372.70
  4599.7  372.37  4713.9  373.38  4826.9  373.09  4869.4  370.94  4911.8  367.87
  4961.5  367.03  4991.4  365.82  5049.2  364.61  5049.7  364.11  5056.9  364.11
  5057.4  364.61  5207.5  366.54  5244.2  366.46  5258.4  367.26  5293.9  366.75
  5315.0  365.71  5357.4  366.86  5407.1  368.93  5428.1  369.14  5449.5  370.55
  5590.9  376.07  5604.5  376.16  5643.7  378.41  5738.7  382.26  5874.9  386.86
#Mann=5,-1,0
  4505.5     0.1       0  4991.4    0.12       0  5049.2    0.07       0
  5057.4    0.12       0  5207.5    0.16       0
Bank Sta=5049.2,5057.4
Exp/Cntr=0.3,0.1

Type RM Length L Ch R = 1,2454,258,258,258
BEGIN DESCRIPTION:
DUCK CREEK TRIB 29 22 0
END DESCRIPTION:
XS GIS Cut Line= 4
      3511104.42     10420824.83      3510535.88     10420807.47
      3510149.59     10420955.04      3509897.84     10421701.62
#Sta/Elev= 30
  4185.2  385.33  4224.4  385.02  4287.6  384.22  4367.6  378.62  4407.6  378.61
  4447.6  371.78  4642.0  371.98  4657.7  371.63  4687.7  364.96  4717.8  363.87
  4886.5  363.23  4982.8  365.17  5001.4  363.58  5015.0  365.10  5096.5  363.12
  5097.0  362.62  5104.7  363.12  5186.7  364.40  5248.4  365.87  5343.3  365.84
  5361.1  364.60  5375.0  365.38  5392.6  363.73  5406.7  365.49  5487.0  369.80
  5581.5  373.29  5659.9  375.60  5723.3  375.05  5854.6  378.84  5955.4  381.62
#Mann=7,-1,0
  4185.2    0.05       0  4224.4     0.1       0  4642.0    0.12       0
  5096.5    0.07       0  5104.7    0.12       0  5186.7    0.16       0
  5854.6    0.15       0
Bank Sta=5096.5,5104.7
Exp/Cntr=0.3,0.1

Type RM Length L Ch R = 1,2196,192,192,192
BEGIN DESCRIPTION:
DUCK CREEK TRIB 29 4 6
END DESCRIPTION:
XS GIS Cut Line= 4
      3510669.85     10420347.28      3510343.49     10420576.43
      3510050.52     10420763.64      3509593.47     10421642.45
#Sta/Elev= 30
  4460.9  370.66  4482.9  372.97  4497.7  373.13  4637.1  365.76  4727.0  362.43
  4809.1  361.83  4809.6  361.33  4817.3  361.83  4894.1  362.46  4980.0  364.58
  4993.9  362.96  5015.6  364.39  5048.4  363.60  5154.6  362.50  5275.8  363.03
  5371.6  363.85  5384.2  363.70  5522.3  363.71  5554.5  364.56  5577.1  363.40
  5582.9  364.77  5678.5  365.13  5842.6  369.79  5886.8  369.96  5991.7  372.56
  6019.5  372.31  6067.3  373.86  6102.3  375.12  6146.5  378.19  6197.9  378.66
#Mann=9,-1,0
  4460.9     0.1       0  4637.1    0.12       0  4809.1    0.07       0
  4817.3    0.12       0  5048.4    0.08       0  5275.8    0.16       0
  5371.6    0.05       0  5384.2    0.16       0  6067.3     0.1       0
Bank Sta=4809.1,4817.3
Exp/Cntr=0.3,0.1

Type RM Length L Ch R = 1,2004,0,0,0
BEGIN DESCRIPTION:
DUCK CREEK TRIB 29 4 7
END DESCRIPTION:
XS GIS Cut Line= 4
      3510503.22     10420194.48      3510176.82     10420451.43
      3509944.23     10420621.89      3509496.68     10421280.68
#Sta/Elev= 30
  4490.3  368.95  4498.1  368.71  4582.9  365.38  4628.0  363.85  4667.6  362.01
  4734.0  361.30  4757.8  361.35  4981.0  363.98  4995.6  362.40  5016.5  364.26
  5140.5  361.52  5197.8  361.44  5301.6  362.51  5313.4  362.46  5483.9  361.80
  5496.8  362.19  5520.2  365.04  5544.5  364.43  5568.6  362.29  5598.5  361.98
  5600.7  360.67  5601.2  360.17  5608.9  360.67  5628.4  362.99  5660.1  362.29
  5675.2  361.99  5820.2  364.23  5900.9  367.73  5951.8  371.52  5990.5  371.77
#Mann=16,-1,0
  4490.3    0.08       0  4498.1    0.16       0  4582.9    0.08       0
  4628.0    0.12       0  4734.0    0.08       0  4757.8    0.12       0
  5140.5    0.05       0  5197.8     0.1       0  5301.6    0.05       0
  5313.4     0.1       0  5544.5    0.07       0  5600.7    0.07       0
  5608.9    0.07       0  5660.1    0.05       0  5675.2    0.07       0
  5820.2     0.1       0
Bank Sta=5600.7,5608.9
Exp/Cntr=0.3,0.1

Chan Stop Cuts=-1