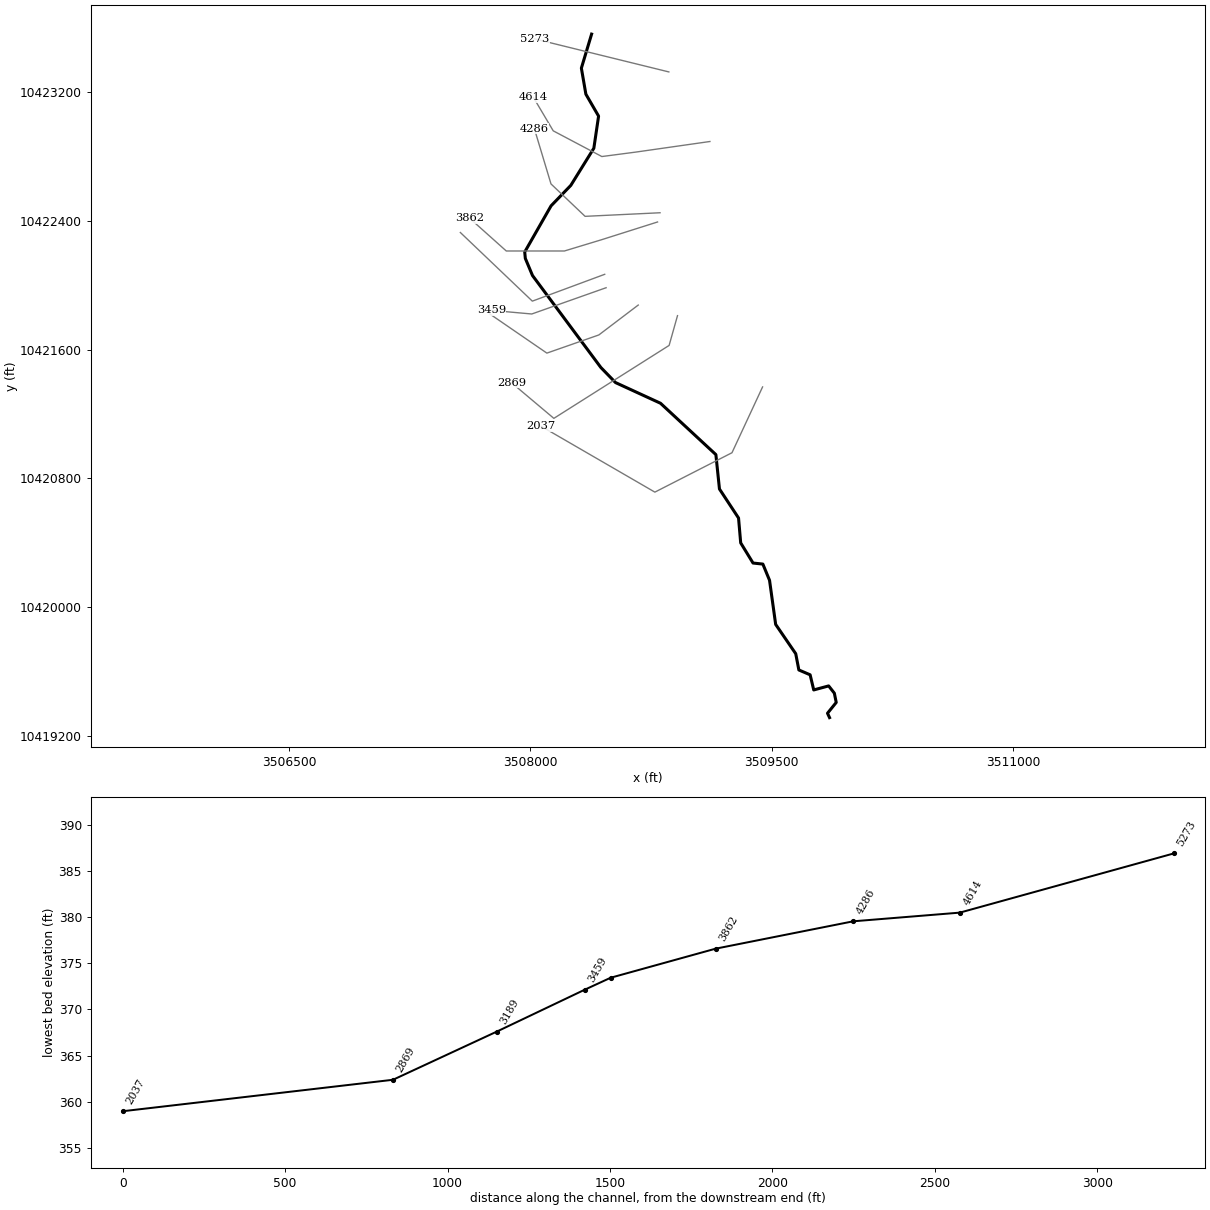
--- DUCK CREEK TRIB 30.prj (project) ---

Proj Title=DUCK CREEK TRIB 30 Base Level Engineering
Current Plan=p01
Default Exp/Contr=0.3,0.1
English Units
Geom File=g01
Flow File=f01
Plan File=p01
Y Axis Title=Elevation
X Axis Title(PF)=Main Channel Distance
X Axis Title(XS)=Station
BEGIN DESCRIPTION:
DUCK CREEK TRIB 30
END DESCRIPTION:
DSS Export Rating Curves= 0
DSS Export Rating Curve Sorted= 0
DSS Export Volume Flow Curves= 0
DXF OffsetX= 0
DXF OffsetY= 0
DXF ScaleX= 1
DXF ScaleY= 10

--- DUCK CREEK TRIB 30.p01 (plan) ---

Plan Title=Multiple Run
Short Identifier=Multiple
Geom File=g01
Flow File=f01
Subcritical Flow
K Sum by GR= 0
Std Step Tol= 0.01
Critical Tol= 0.01
Num of Std Step Trials= 20
Max Error Tol= 0.3
Flow Tol Ratio= 0.001
Split Flow NTrial= 30
Split Flow Tol= 0.02
Split Flow Ratio= 0.02
Log Output Level= 0
Friction Slope Method= 1
Unsteady Friction Slope Method= 2
Unsteady Bridges Friction Slope Method= 1
Parabolic Critical Depth
Global Vel Dist=  1 , 1 , 1
Global Log Level= 0
CheckData=True
Encroach Param= -1, 0, 0, 0
BEGIN DESCRIPTION:
Multiple Run
END DESCRIPTION:

--- DUCK CREEK TRIB 30.f01 (steady flow) ---

Flow Title=Multiple
Program Version=4.10
Number of Profiles= 7
Profile Names=10-year,25-year,50-year,1pct_min,100-year,1pct_plu,500-year
River Rch & RM=DUCK CREEK TRIB,Reach-1         ,5273
     513     682     816     715     967    1308    1351
Boundary for River Rch & Prof#=DUCK CREEK TRIB,Reach-1         , 1
Up Type= 0
Dn Type= 3
Dn Slope=0.009
Boundary for River Rch & Prof#=DUCK CREEK TRIB,Reach-1         , 2
Up Type= 0
Dn Type= 3
Dn Slope=0.009
Boundary for River Rch & Prof#=DUCK CREEK TRIB,Reach-1         , 3
Up Type= 0
Dn Type= 3
Dn Slope=0.009
Boundary for River Rch & Prof#=DUCK CREEK TRIB,Reach-1         , 4
Up Type= 0
Dn Type= 3
Dn Slope=0.009
Boundary for River Rch & Prof#=DUCK CREEK TRIB,Reach-1         , 5
Up Type= 0
Dn Type= 3
Dn Slope=0.009
Boundary for River Rch & Prof#=DUCK CREEK TRIB,Reach-1         , 6
Up Type= 0
Dn Type= 3
Dn Slope=0.009
Boundary for River Rch & Prof#=DUCK CREEK TRIB,Reach-1         , 7
Up Type= 0
Dn Type= 3
Dn Slope=0.009
DSS Import GetInterval= 0
DSS Import GetPeak= 0
DSS Import FillOption= 0

--- DUCK CREEK TRIB 30.g01 (geometry) ---

Geom Title=Existing Conditions
Program Version=4.10

River Reach=DUCK CREEK TRIB ,Reach-1
Reach XY= 30
      3508380.19     10423559.95      3508316.63     10423348.53
       3508344.6     10423186.68      3508423.59      10423050.4
      3508394.08     10422850.75      3508250.85     10422619.84
      3508128.46     10422493.11      3507964.64     10422206.12
      3507968.37     10422166.48        3508013.     10422059.95
       3508437.7     10421488.55      3508528.85      10421394.8
      3508808.36     10421266.33      3509152.33     10420947.32
      3509174.57     10420733.67       3509293.1     10420553.35
      3509306.51     10420398.84      3509383.13     10420273.65
      3509444.22     10420267.19      3509485.72      10420166.3
      3509523.78     10419892.33      3509648.45     10419710.26
      3509667.85      10419609.3       3509737.9     10419579.22
      3509760.29     10419485.21      3509852.99     10419510.19
      3509888.37     10419465.04      3509900.03     10419407.54
      3509845.83     10419340.42      3509858.47      10419313.3

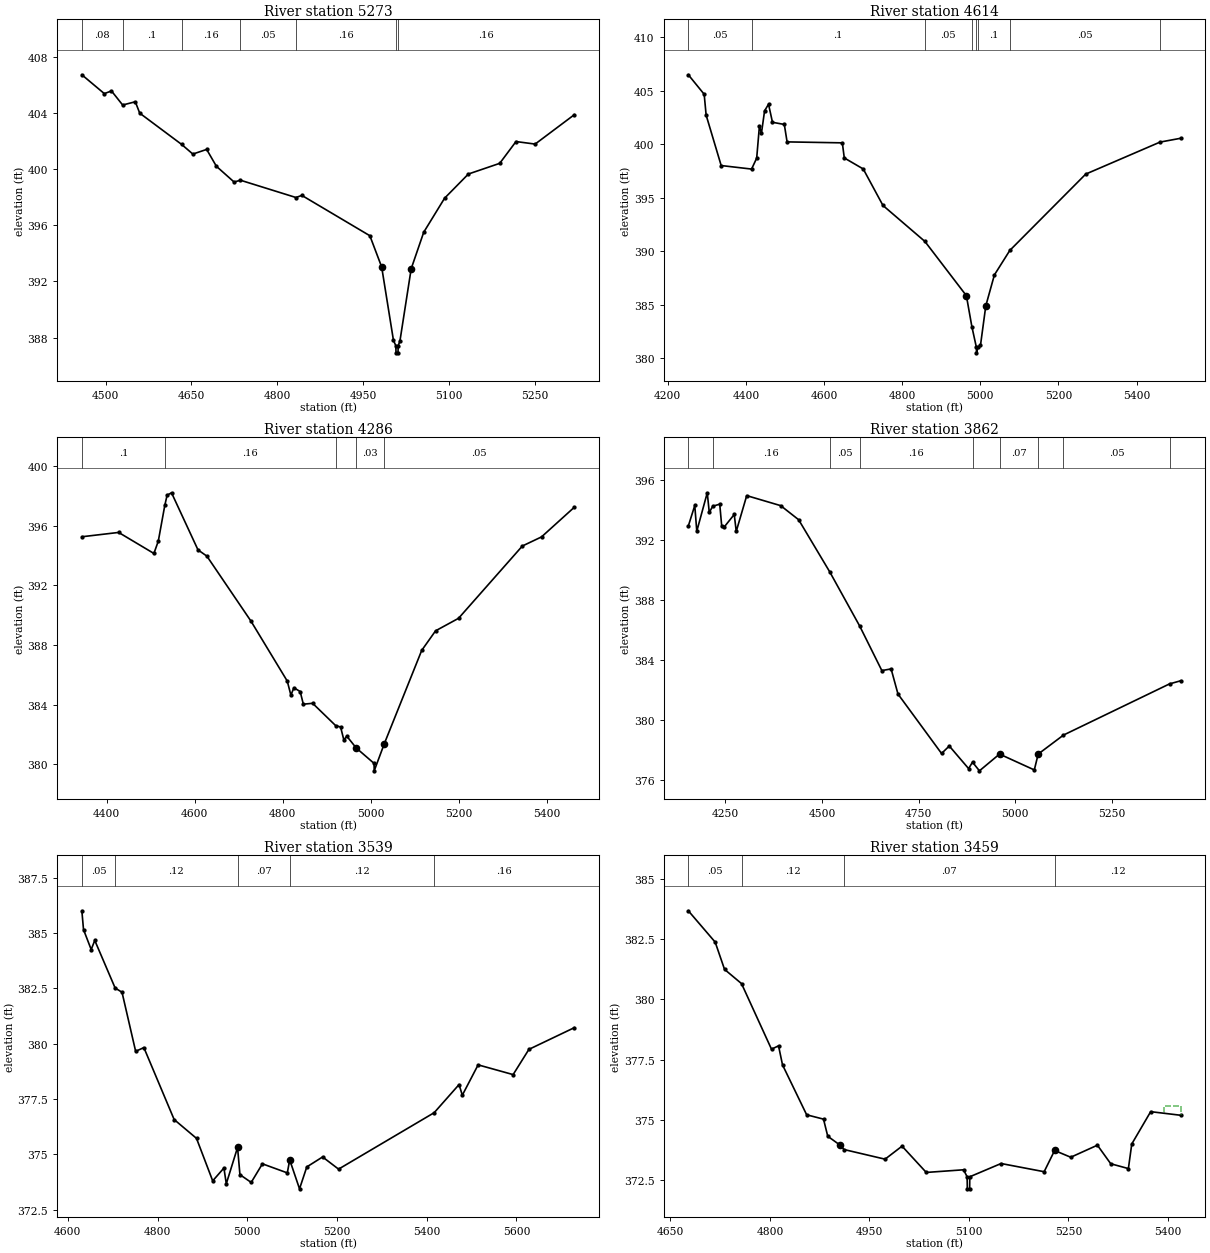
Type RM Length L Ch R = 1 ,5273    ,659,659,659
BEGIN DESCRIPTION:
DUCK CREEK TRIB 30 6 0
END DESCRIPTION:
XS GIS Cut Line= 2
      3508860.15     10423324.96      3508025.65     10423530.34
#Sta/Elev= 30
  4458.7   406.7  4497.9  405.36  4510.4  405.55  4529.9  404.55    4552  404.78
  4559.7  403.97  4632.7  401.75  4652.4  401.06  4676.5  401.39  4693.5  400.19
  4724.4  399.07  4735.4   399.2  4832.3  397.97  4842.6  398.12  4961.3  395.25
  4981.9  393.03  5002.5   387.8  5006.7  387.42  5006.9  386.92  5010.4  386.92
  5010.7  387.42  5013.8  387.77  5033.4   392.9  5055.3   395.5  5091.7  397.92
  5133.2  399.64  5187.9   400.4  5216.3  401.95  5249.7  401.77  5318.1  403.86
#Mann= 7 ,-1 , 0
  4458.7     .08       0  4529.9      .1       0  4632.7     .16       0
  4735.4     .05       0  4832.3     .16       0  5006.7     .07       0
  5010.7     .16       0
Bank Sta=4981.9,5033.4
XS Rating Curve= 0 ,0
Exp/Cntr=0.3,0.1

Type RM Length L Ch R = 1 ,4614    ,328,328,328
BEGIN DESCRIPTION:
DUCK CREEK TRIB 30 12 0
END DESCRIPTION:
XS GIS Cut Line= 5
      3509115.33     10422892.66      3508655.64     10422827.01
      3508443.83     10422799.23      3508141.75     10422958.95
      3508019.01     10423166.14
#Sta/Elev= 30
  4252.8  406.48  4293.4  404.66  4298.4  402.71  4336.9     398  4414.7  397.67
  4427.8  398.69  4434.8   401.7  4439.9     401    4448  403.11  4458.1  403.73
  4468.2  402.04  4498.5  401.84  4505.6  400.21    4647  400.12    4652  398.71
  4700.5  397.68    4751  394.27  4858.3  390.91  4964.5  385.84  4978.5  382.96
  4990.2     381  4990.4   380.5  4994.2     381  5000.6   381.2  5014.2  384.89
  5036.2  387.78  5075.7  390.07    5270   397.2  5460.1  400.19  5513.3  400.55
#Mann= 8 ,-1 , 0
  4252.8     .05       0  4414.7      .1       0  4858.3     .05       0
  4978.5      .1       0  4990.2     .07       0  4994.2      .1       0
  5075.7     .05       0  5460.1     .16       0
Bank Sta=4964.5,5014.2
XS Rating Curve= 0 ,0
Exp/Cntr=0.3,0.1

Type RM Length L Ch R = 1 ,4286    ,424,424,424
BEGIN DESCRIPTION:
DUCK CREEK TRIB 30 10
END DESCRIPTION:
XS GIS Cut Line= 4
       3508805.5     10422449.96      3508339.67      10422427.7
      3508127.86     10422629.09      3508024.23      10422973.4
#Sta/Elev= 30
  4343.9  395.26  4427.4  395.55  4507.5  394.14  4517.5  394.97  4532.2  397.36
  4537.5  398.05  4547.5  398.21  4607.6  394.38  4627.8  393.96  4727.7  389.61
  4810.3  385.58  4818.5  384.64  4825.4  385.13  4839.6  384.88  4846.8  384.03
  4867.9  384.09  4920.3  382.59  4931.4   382.5  4938.7  381.64  4945.6  381.88
    4967  381.09  5007.4  380.06  5007.7  379.56  5030.5  381.37  5115.6  387.64
    5147  388.95  5199.2  389.79  5344.1  394.64  5387.6  395.25  5462.1  397.24
#Mann= 5 ,-1 , 0
  4343.9      .1       0  4532.2     .16       0  4920.3     .05       0
    4967     .03       0  5030.5     .05       0
Bank Sta=4967,5030.5
XS Rating Curve= 0 ,0
Exp/Cntr=0.3,0.1

Type RM Length L Ch R = 1 ,3862    ,323,323,323
BEGIN DESCRIPTION:
DUCK CREEK TRIB 30 4 1
END DESCRIPTION:
XS GIS Cut Line= 5
       3508789.9     10422392.68      3508440.36     10422281.87
       3508211.2     10422212.42      3507850.08     10422212.42
      3507621.24     10422416.99
#Sta/Elev= 30
  4154.3  392.95    4171  394.32  4176.2   392.6  4203.3  395.17  4208.5  393.86
  4217.5  394.27  4235.6  394.41  4240.8  392.92  4246.4  392.86  4273.1  393.72
  4278.3  392.59  4305.4  394.98  4393.3  394.31  4439.7  393.37  4520.1  389.89
  4597.8  386.26    4655  383.29    4679   383.4  4696.8  381.72  4809.5  377.75
  4829.5  378.25  4879.5  376.74  4889.6  377.17  4907.5  376.59  4959.5  377.71
  5049.5  376.65  5059.5  377.71    5125  378.98  5399.4   382.4  5428.5  382.61
#Mann= 9 ,-1 , 0
  4154.3      .1       0  4217.5     .16       0  4520.1     .05       0
  4597.8     .16       0  4889.6     .12       0  4959.5     .07       0
  5059.5     .12       0    5125     .05       0  5399.4     .16       0
Bank Sta=4959.5,5059.5
XS Rating Curve= 0 ,0
Exp/Cntr=0.3,0.1

Type RM Length L Ch R = 1 ,3539    ,80,80,80
BEGIN DESCRIPTION:
DUCK CREEK TRIB 30 4 2
END DESCRIPTION:
XS GIS Cut Line= 3
      3508461.65     10422067.54      3508011.96     10421900.86
      3507564.75     10422327.26
#Sta/Elev= 30
  4631.4     386  4635.1  385.15  4652.2  384.25  4660.2  384.66  4705.6  382.51
  4720.9  382.32  4751.3  379.65  4769.6  379.82  4837.1  376.57  4886.9  375.72
    4923   373.8    4948  374.38  4953.3  373.67  4978.4  375.31  4983.7  374.08
  5008.8  373.73  5033.8  374.57  5089.3  374.16  5094.6  374.75  5116.5  373.44
  5132.7  374.43  5167.9  374.88  5203.5  374.33  5416.6  376.88    5472  378.15
  5479.3  377.67  5514.5  379.04  5592.5   378.6  5627.7  379.74  5728.9  380.72
#Mann= 5 ,-1 , 0
  4631.4     .05       0  4705.6     .12       0  4978.4     .07       0
  5094.6     .12       0  5416.6     .16       0
Bank Sta=4978.4,5094.6
XS Rating Curve= 0 ,0
Exp/Cntr=0.3,0.1

Type RM Length L Ch R = 1 ,3459    ,270,270,270
BEGIN DESCRIPTION:
DUCK CREEK TRIB 30 2 0
END DESCRIPTION:
XS GIS Cut Line= 3
      3508470.31      10421984.2      3508008.48       10421821.
       3507756.9     10421843.55
#Sta/Elev= 30
    4677  383.67  4717.5  382.37  4731.6  381.24  4757.2  380.65  4802.4  377.93
    4813  378.07    4819  377.28  4855.4  375.21  4880.8  375.03  4887.2  374.32
  4906.4  373.94  4911.7  373.77  4973.6  373.37  4999.2  373.91  5035.7  372.82
  5091.9  372.93  5097.3  372.64  5097.6  372.14  5101.1  372.14  5101.3  372.64
  5148.5  373.19  5213.4  372.85  5229.2  373.73  5253.5  373.45  5293.7  373.95
  5313.8  373.18  5340.4  372.98  5345.5     374    5374  375.34  5419.4  375.19
#Mann= 4 ,-1 , 0
    4677     .05       0  4757.2     .12       0  4911.7     .07       0
  5229.2     .12       0
#XS Ineff= 2 , 0
                         5394.46          375.59
Permanent Ineff=
       F       F
Bank Sta=4906.4,5229.2
XS Rating Curve= 0 ,0
Exp/Cntr=0.3,0.1

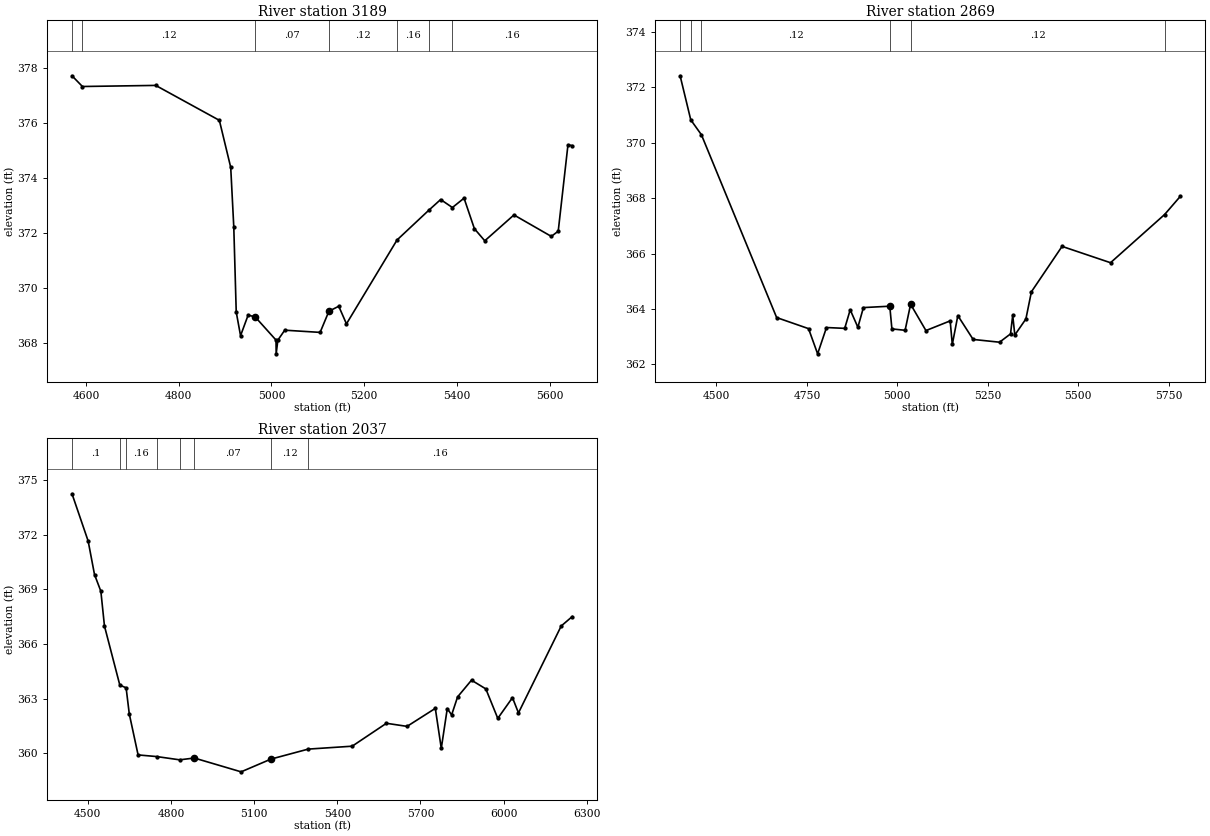
Type RM Length L Ch R = 1 ,3189    ,320,320,320
BEGIN DESCRIPTION:
DUCK CREEK TRIB 30 22 0
END DESCRIPTION:
XS GIS Cut Line= 4
      3508669.92     10421876.54      3508425.15     10421690.79
      3508102.23     10421577.94      3507748.05     10421821.01
#Sta/Elev= 30
  4569.8  377.72  4592.3  377.33  4750.3  377.37  4887.6   376.1  4912.1  374.39
  4918.7  372.23    4924  369.13  4933.3  368.27  4949.7  369.02    4965  368.95
  5009.8  368.11  5010.1  367.61  5013.8  368.11  5028.6  368.47  5104.9  368.39
  5123.9  369.16  5145.1  369.34  5161.7   368.7  5270.8  371.75  5339.2  372.83
  5364.8  373.22  5390.2  372.93  5415.3  373.27  5437.6  372.16    5460  371.72
  5522.9  372.66  5603.5  371.88  5618.4  372.07  5639.4  375.21  5648.7  375.18
#Mann= 7 ,-1 , 0
  4569.8      .1       0  4592.3     .12       0    4965     .07       0
  5123.9     .12       0  5270.8     .16       0  5339.2     .12       0
  5390.2     .16       0
Bank Sta=4965,5123.9
XS Rating Curve= 0 ,0
Exp/Cntr=0.3,0.1

Type RM Length L Ch R = 1 ,2869    ,832,832,832
BEGIN DESCRIPTION:
DUCK CREEK TRIB 30 6 1
END DESCRIPTION:
XS GIS Cut Line= 4
      3508913.87      10421810.6      3508861.78     10421625.68
      3508145.64     10421172.56      3507882.64     10421393.89
#Sta/Elev= 30
  4399.5  372.42  4428.9  370.83  4458.4  370.29  4666.4  363.69  4754.6  363.29
  4779.7  362.38  4804.2  363.33  4854.6   363.3  4869.8  363.97    4891  363.34
  4906.3  364.05  4979.2   364.1  4985.1  363.28  5021.6  363.23  5036.8  364.17
  5079.2  363.22  5146.2  363.57  5152.1  362.72  5167.4  363.76  5209.7   362.9
  5282.7   362.8  5313.1   363.1  5319.1  363.77    5325  363.06  5355.6  363.64
  5370.8  364.62  5455.6  366.26  5589.6  365.67  5739.1  367.41  5782.8  368.07
#Mann= 6 ,-1 , 0
  4399.5     .05       0  4428.9     .16       0  4458.4     .12       0
  4979.2     .07       0  5036.8     .12       0  5739.1     .16       0
Bank Sta=4979.2,5036.8
XS Rating Curve= 0 ,0
Exp/Cntr=0.3,0.1

Type RM Length L Ch R = 1 ,2037    ,0,0,0
BEGIN DESCRIPTION:
DUCK CREEK TRIB 30 6 2
END DESCRIPTION:
XS GIS Cut Line= 4
       3509442.5     10421367.85      3509252.41     10420959.02
      3508773.24     10420714.23      3508067.55     10421123.06
#Sta/Elev= 30
    4443  374.26  4501.3  371.66  4524.2  369.82  4547.1   368.9  4560.1  366.99
  4615.5  363.74  4638.2  363.59  4649.7  362.15  4681.4   359.9  4748.4  359.81
  4831.4  359.63  4884.1  359.73    5053  358.97  5160.5  359.67    5295  360.22
  5453.6  360.38  5577.1  361.64  5651.6  361.47  5753.5  362.46    5775  360.26
  5796.6  362.45  5812.3   362.1  5833.8  363.09    5884  364.01  5935.7  363.53
  5978.8  361.91  6031.8  363.05  6053.4  362.21  6207.6  366.99  6247.5  367.51
#Mann= 8 ,-1 , 0
    4443      .1       0  4615.5     .12       0  4638.2     .16       0
  4748.4      .1       0  4831.4     .12       0  4884.1     .07       0
  5160.5     .12       0    5295     .16       0
#XS Ineff= 2 , 0
                         5750.16          362.41
Permanent Ineff=
       F       F
Bank Sta=4884.1,5160.5
XS Rating Curve= 0 ,0
Exp/Cntr=0.3,0.1

Chan Stop Cuts=-1
Use User Specified Reach Order=0
Composite Channel Slope=5