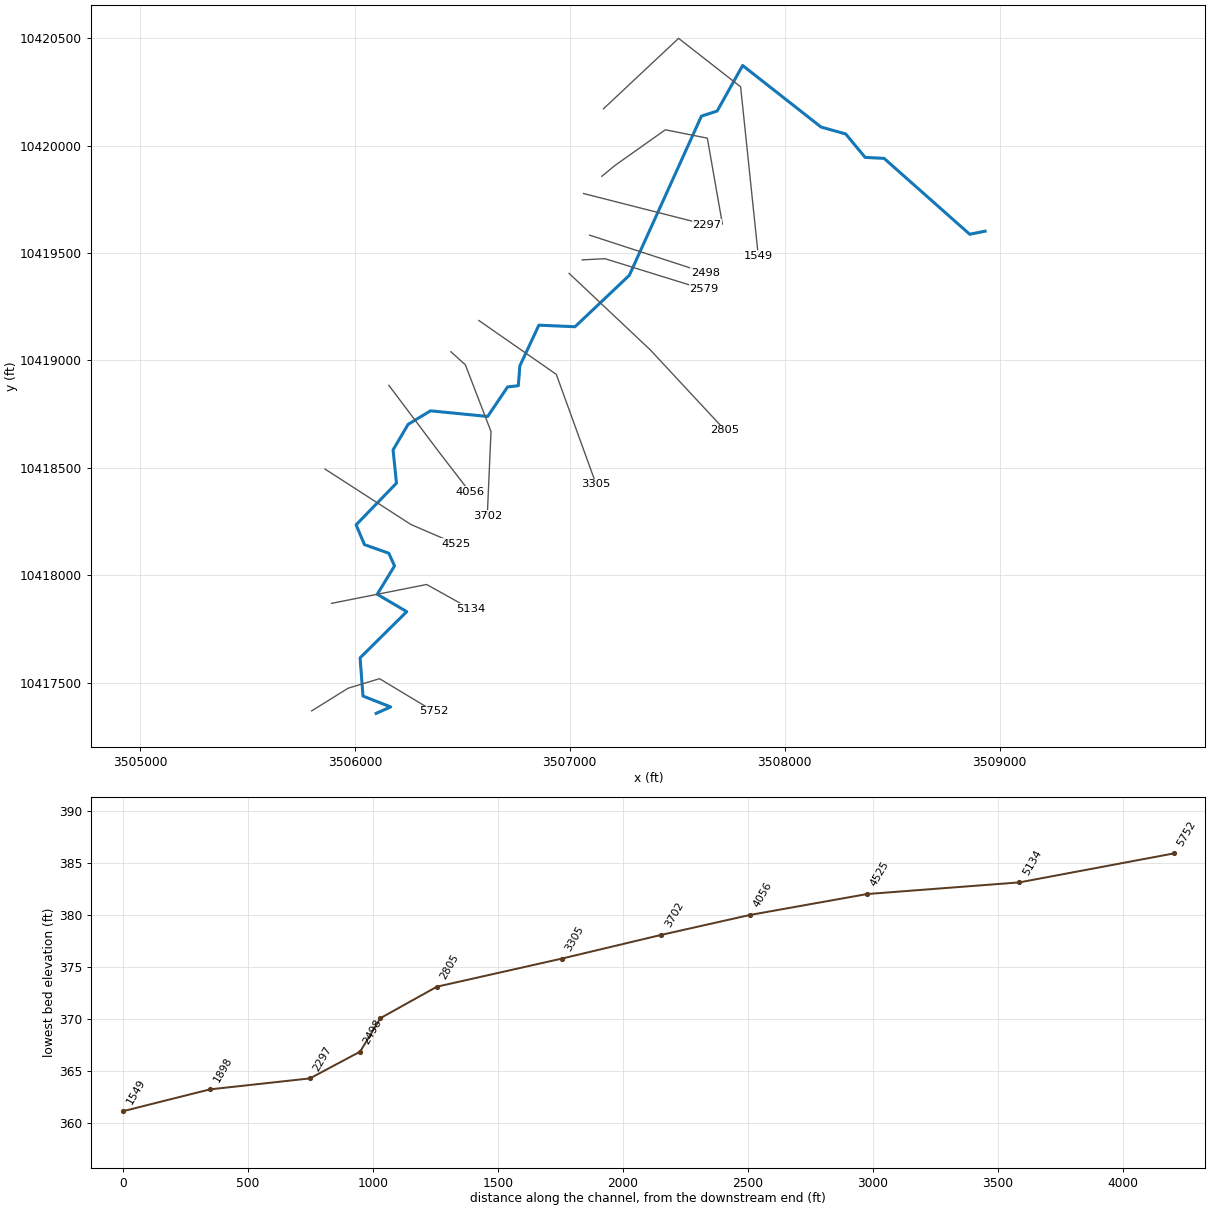
--- DUCK CREEK TRIB 31.prj (project) ---

Proj Title=DUCK CREEK TRIB 31 Base Level Engineering
Current Plan=p01
Default Exp/Contr=0.3,0.1
English Units
Geom File=g01
Flow File=f01
Plan File=p01
BEGIN DESCRIPTION:
DUCK CREEK TRIB 31
END DESCRIPTION:

--- DUCK CREEK TRIB 31.p01 (plan) ---

Plan Title=Multiple Run
Short Identifier=Multiple
Geom File=g01
Flow File=f01
Subcritical Flow
K Sum by GR= 0
Std Step Tol= 0.01
Critical Tol= 0.01
Num of Std Step Trials= 20
Max Error Tol= 0.3
Flow Tol Ratio= 0.001
Split Flow NTrial= 30
Split Flow Tol= 0.02
Split Flow Ratio= 0.02
Log Output Level= 0
Friction Slope Method= 1
Unsteady Friction Slope Method= 2
Unsteady Bridges Friction Slope Method= 1
Parabolic Critical Depth
Global Vel Dist=  1 , 1 , 1
Global Log Level= 0
CheckData=True
Encroach Param= -1, 0, 0, 0
BEGIN DESCRIPTION:
Multiple Run
END DESCRIPTION:

--- DUCK CREEK TRIB 31.f01 (steady flow) ---

Flow Title=Multiple
Number of Profiles=7
Profile Names=10-year,25-year,50-year,1pct_min,100-year,1pct_plu,500-year
River Rch & RM= DUCK CREEK TRIB ,Reach-1,5752
     677     910    1098     967    1308    1769    1852
Boundary for River Rch & Prof#=DUCK CREEK TRIB ,Reach-1,1
Up Type=0
Dn Type=3
Dn Slope=0.005
Boundary for River Rch & Prof#=DUCK CREEK TRIB ,Reach-1,2
Up Type=0
Dn Type=3
Dn Slope=0.005
Boundary for River Rch & Prof#=DUCK CREEK TRIB ,Reach-1,3
Up Type=0
Dn Type=3
Dn Slope=0.005
Boundary for River Rch & Prof#=DUCK CREEK TRIB ,Reach-1,4
Up Type=0
Dn Type=3
Dn Slope=0.005
Boundary for River Rch & Prof#=DUCK CREEK TRIB ,Reach-1,5
Up Type=0
Dn Type=3
Dn Slope=0.005
Boundary for River Rch & Prof#=DUCK CREEK TRIB ,Reach-1,6
Up Type=0
Dn Type=3
Dn Slope=0.005
Boundary for River Rch & Prof#=DUCK CREEK TRIB ,Reach-1,7
Up Type=0
Dn Type=3
Dn Slope=0.005

--- DUCK CREEK TRIB 31.g01 (geometry) ---

Geom Title=Existing Conditions

River Reach=DUCK CREEK TRIB ,Reach-1
Reach XY= 30
      3506098.80     10417358.02      3506166.52     10417387.90
      3506037.71     10417438.53      3506024.26     10417616.34
      3506241.22     10417831.25      3506104.13     10417912.26
      3506184.40     10418044.11      3506158.01     10418103.17
      3506044.58     10418143.15      3506005.71     10418235.29
      3506193.53     10418429.22      3506177.75     10418584.00
      3506247.72     10418702.87      3506352.07     10418765.80
      3506617.91     10418739.58      3506710.50     10418876.80
      3506760.57     10418882.79      3506767.55     10418974.73
      3506856.11     10419164.35      3507024.30     10419157.06
      3507277.00     10419396.34      3507612.43     10420136.92
      3507685.78     10420160.83      3507804.31     10420372.64
      3508169.29     10420086.21      3508283.94     10420054.02
      3508374.25     10419944.97      3508462.49     10419940.44
      3508860.82     10419587.35      3508932.11     10419601.64

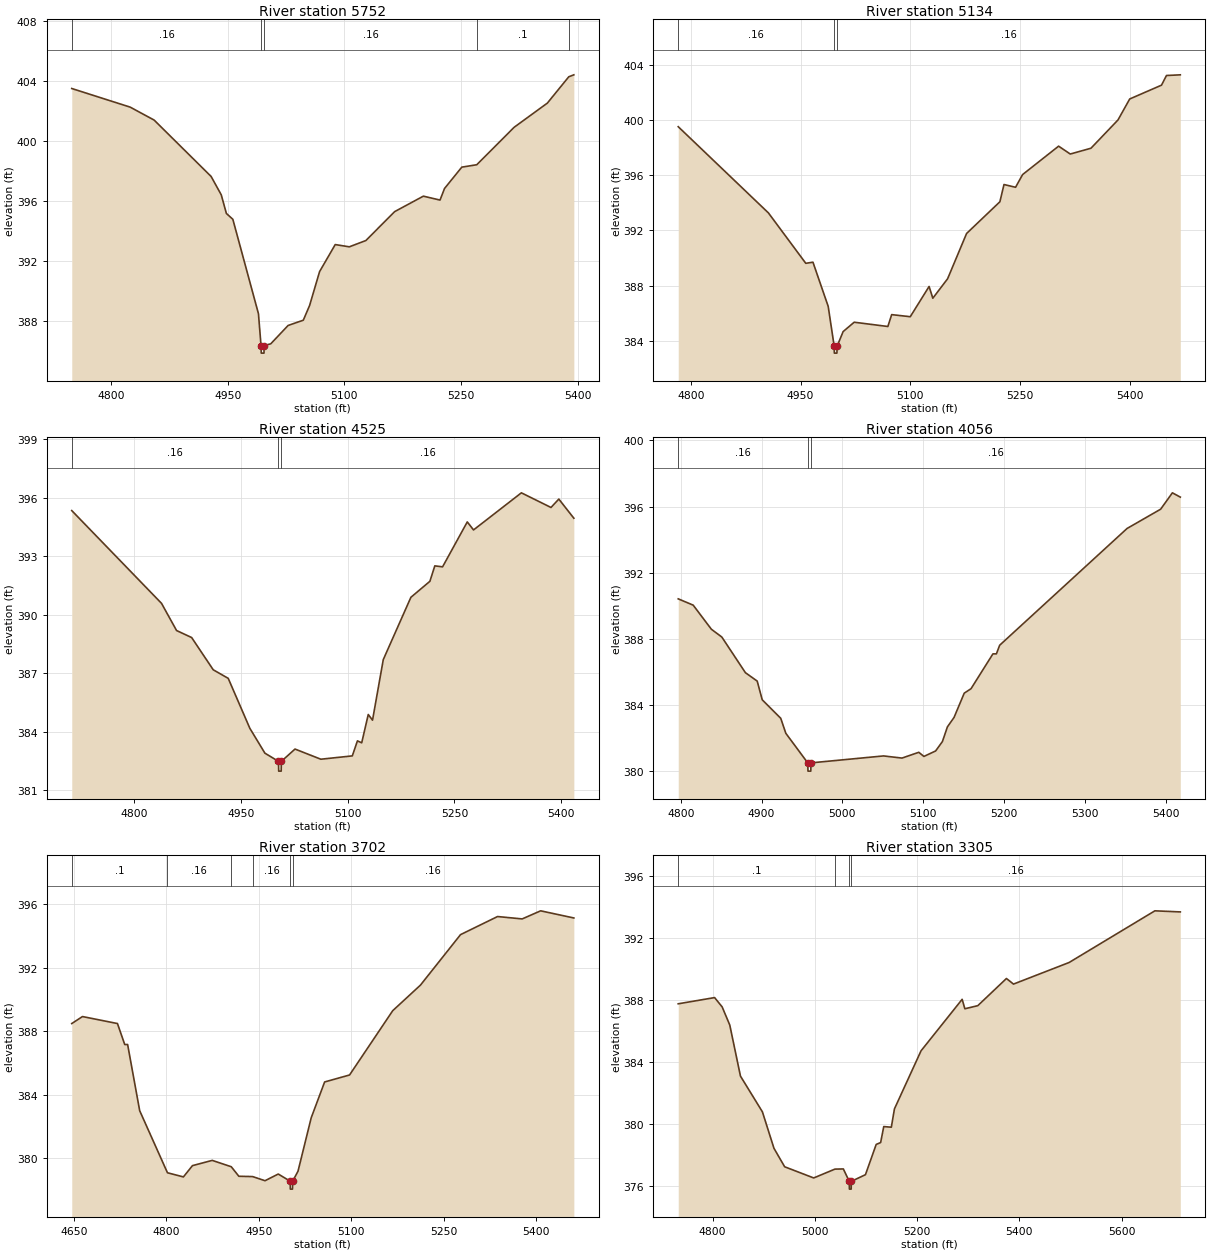
Type RM Length L Ch R = 1,5752,618,618,618
BEGIN DESCRIPTION:
DUCK CREEK TRIB 31 10 0
END DESCRIPTION:
XS GIS Cut Line= 4
      3505799.02     10417369.67      3505968.29     10417474.92
      3506114.77     10417519.41      3506365.38     10417368.61
#Sta/Elev= 30
  4749.8  403.49  4824.9  402.25  4855.6  401.39  4928.8  397.64  4941.8  396.42
  4948.4  395.18  4956.7  394.79  4989.6  388.51  4992.9  386.39  4993.2  385.89
  4996.7  385.89  4996.9  386.39  5005.4  386.51  5027.7  387.73  5047.2  388.08
  5055.3  389.06  5068.1  391.31  5088.2  393.11  5106.3  392.96  5127.6  393.38
  5164.5  395.30  5201.4  396.33  5222.8  396.07  5228.6  396.84  5250.8  398.26
  5270.0  398.42  5318.0  400.91  5360.7  402.52  5388.2  404.27  5394.7  404.40
#Mann=5,-1,0
  4749.8    0.16       0  4992.9    0.07       0  4996.9    0.16       0
  5270.0     0.1       0  5388.2    0.16       0
Bank Sta=4992.9,4996.9
Exp/Cntr=0.3,0.1

Type RM Length L Ch R = 1,5134,609,609,609
BEGIN DESCRIPTION:
DUCK CREEK TRIB 31 11 0
END DESCRIPTION:
XS GIS Cut Line= 3
      3505891.25     10417869.88      3506333.96     10417957.77
      3506538.62     10417843.60
#Sta/Elev= 30
  4782.9  399.52  4906.1  393.27  4957.1  389.62  4966.9  389.70  4987.7  386.50
  4995.9  383.61  4996.1  383.11  4999.6  383.11  4999.9  383.61  5008.1  384.67
  5023.2  385.35  5069.2  385.04  5074.4  385.90  5099.8  385.75  5125.5  387.94
  5130.6  387.09  5150.8  388.50  5176.7  391.78  5222.2  394.08  5227.8  395.33
  5243.6  395.13  5253.2  396.05  5302.4  398.11  5318.3  397.54  5346.6  397.96
  5383.5  400.01  5399.5  401.53  5442.9  402.53  5449.7  403.23  5468.6  403.28
#Mann=3,-1,0
  4782.9    0.16       0  4995.9    0.07       0  4999.9    0.16       0
Bank Sta=4995.9,4999.9
Exp/Cntr=0.3,0.1

Type RM Length L Ch R = 1,4525,469,469,469
BEGIN DESCRIPTION:
DUCK CREEK TRIB 31 9 0
END DESCRIPTION:
XS GIS Cut Line= 3
      3505860.91     10418494.86      3506261.26     10418236.64
      3506471.48     10418146.08
#Sta/Elev= 30
  4712.4  395.33  4838.5  390.58  4859.6  389.19  4880.8  388.83  4911.1  387.18
  4932.2  386.74  4962.6  384.18  4983.7  382.91  5002.8  382.49  5003.1  381.99
  5006.6  381.99  5006.8  382.49  5026.0  383.12  5062.3  382.60  5106.5  382.77
  5113.7  383.54  5119.7  383.44  5128.9  384.89  5134.9  384.60  5150.0  387.70
  5188.8  390.89  5215.5  391.71  5222.4  392.50  5233.3  392.45  5268.0  394.75
  5276.8  394.34  5344.0  396.24  5385.6  395.49  5396.6  395.92  5417.7  394.94
#Mann=3,-1,0
  4712.4    0.16       0  5002.8    0.07       0  5006.8    0.16       0
Bank Sta=5002.8,5006.8
Exp/Cntr=0.3,0.1

Type RM Length L Ch R = 1,4056,354,354,354
BEGIN DESCRIPTION:
DUCK CREEK TRIB 31 8 0
END DESCRIPTION:
XS GIS Cut Line= 3
      3506158.19     10418884.40      3506394.72     10418569.75
      3506533.62     10418389.62
#Sta/Elev= 30
  4796.9  390.41  4815.4  390.03  4837.9  388.57  4850.8  388.10  4880.0  385.94
  4894.6  385.43  4900.8  384.30  4923.7  383.18  4930.0  382.27  4957.1  380.48
  4957.4  379.98  4960.9  379.98  4961.1  380.48  5050.8  380.90  5073.7  380.77
  5094.5  381.12  5100.8  380.87  5115.3  381.20  5123.7  381.77  5129.9  382.66
  5138.1  383.23  5150.7  384.70  5159.1  384.97  5186.2  387.08  5190.5  387.08
  5194.5  387.60  5352.1  394.67  5393.7  395.84  5408.2  396.83  5418.0  396.57
#Mann=3,-1,0
  4796.9    0.16       0  4957.1    0.07       0  4961.1    0.16       0
Bank Sta=4957.1,4961.1
Exp/Cntr=0.3,0.1

Type RM Length L Ch R = 1,3702,397,397,397
BEGIN DESCRIPTION:
DUCK CREEK TRIB 31 5 1
END DESCRIPTION:
XS GIS Cut Line= 4
      3506446.78     10419040.70      3506514.08     10418979.91
      3506633.44     10418669.58      3506616.07     10418277.84
#Sta/Elev= 30
  4646.2  388.50  4663.6  388.94  4720.4  388.50  4732.2  387.18  4736.9  387.18
  4756.5  383.01  4801.6  379.10  4827.5  378.84  4842.2  379.55  4874.3  379.88
  4905.2  379.48  4917.5  378.88  4939.9  378.86  4960.0  378.60  4981.5  379.02
  5000.9  378.57  5001.1  378.07  5004.6  378.07  5004.9  378.57  5013.6  379.20
  5035.0  382.56  5056.8  384.82  5097.3  385.26  5167.4  389.31  5212.4  390.92
  5277.5  394.10  5337.6  395.24  5377.6  395.09  5407.6  395.60  5461.5  395.15
#Mann=6,-1,0
  4646.2     0.1       0  4801.6    0.16       0  4905.2     0.1       0
  4939.9    0.16       0  5000.9    0.07       0  5004.9    0.16       0
Bank Sta=5000.9,5004.9
Exp/Cntr=0.3,0.1

Type RM Length L Ch R = 1,3305,500,500,500
BEGIN DESCRIPTION:
Mapping XS 53267de9
END DESCRIPTION:
XS GIS Cut Line= 3
      3506577.03     10419186.06      3506937.26     10418935.42
      3507122.20     10418424.93
#Sta/Elev= 30
  4732.9  387.74  4804.0  388.14  4818.8  387.54  4833.7  386.37  4854.6  383.08
  4897.5  380.78  4920.1  378.43  4941.0  377.24  4997.8  376.52  5039.4  377.09
  5055.8  377.10  5067.3  376.30  5067.6  375.80  5071.1  375.80  5071.3  376.30
  5099.0  376.73  5120.0  378.68  5128.7  378.80  5134.8  379.83  5149.6  379.79
  5155.7  380.97  5207.7  384.71  5288.1  388.03  5293.4  387.42  5318.7  387.62
  5374.7  389.37  5388.5  389.01  5497.2  390.40  5665.0  393.73  5714.7  393.66
#Mann=4,-1,0
  4732.9     0.1       0  5039.4    0.16       0  5067.3    0.07       0
  5071.3    0.16       0
Bank Sta=5067.3,5071.3
Exp/Cntr=0.3,0.1

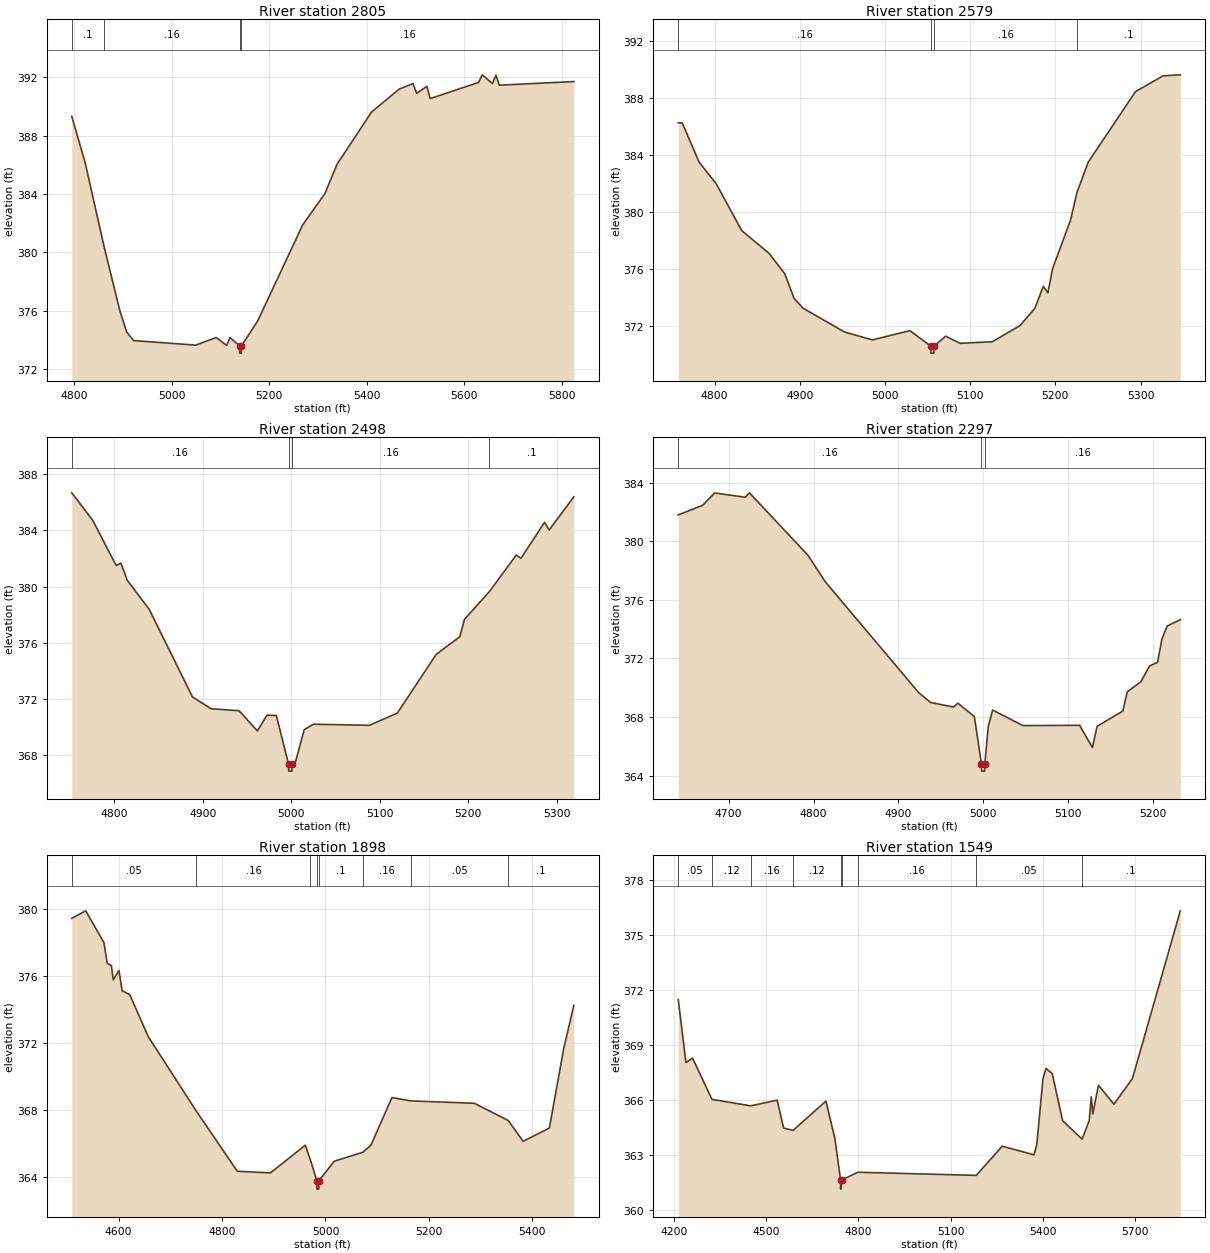
Type RM Length L Ch R = 1,2805,226,226,226
BEGIN DESCRIPTION:
DUCK CREEK TRIB 31 4 1
END DESCRIPTION:
XS GIS Cut Line= 3
      3506996.94     10419405.25      3507374.54     10419049.35
      3507722.09     10418675.82
#Sta/Elev= 30
  4795.4  389.33  4822.8  386.16  4861.0  380.50  4893.6  376.05  4907.8  374.56
  4921.9  373.96  5049.4  373.65  5091.5  374.17  5112.9  373.63  5119.8  374.17
  5139.2  373.60  5139.5  373.10  5143.0  373.10  5143.2  373.60  5176.4  375.30
  5268.7  381.89  5314.3  384.04  5339.0  386.04  5409.9  389.63  5466.5  391.20
  5494.9  391.58  5502.2  390.91  5523.2  391.39  5530.1  390.55  5629.2  391.66
  5636.6  392.18  5657.6  391.59  5664.9  392.15  5671.8  391.47  5824.5  391.72
#Mann=4,-1,0
  4795.4     0.1       0  4861.0    0.16       0  5139.2    0.07       0
  5143.2    0.16       0
Bank Sta=5139.2,5143.2
Exp/Cntr=0.3,0.1

Type RM Length L Ch R = 1,2579,81,81,81
BEGIN DESCRIPTION:
DUCK CREEK TRIB 31 7 0
END DESCRIPTION:
XS GIS Cut Line= 3
      3507057.70     10419468.19      3507164.04     10419473.62
      3507625.23     10419330.37
#Sta/Elev= 30
  4757.3  386.27  4762.0  386.27  4781.7  383.52  4801.8  382.00  4831.8  378.70
  4863.8  377.10  4882.4  375.66  4893.2  373.94  4903.6  373.25  4952.7  371.56
  4985.3  371.01  5029.3  371.66  5053.7  370.58  5053.9  370.08  5057.4  370.08
  5057.7  370.58  5071.2  371.27  5088.2  370.77  5126.0  370.88  5158.6  372.02
  5175.9  373.23  5185.9  374.78  5191.2  374.32  5196.8  376.02  5217.8  379.43
  5225.4  381.38  5238.7  383.52  5294.1  388.47  5326.6  389.58  5346.7  389.65
#Mann=4,-1,0
  4757.3    0.16       0  5053.7    0.07       0  5057.7    0.16       0
  5225.4     0.1       0
Bank Sta=5053.7,5057.7
Exp/Cntr=0.3,0.1

Type RM Length L Ch R = 1,2498,201,201,201
BEGIN DESCRIPTION:
DUCK CREEK TRIB 31 4 0
END DESCRIPTION:
XS GIS Cut Line= 3
      3507092.43     10419583.21      3507195.50     10419549.57
      3507631.70     10419407.43
#Sta/Elev= 30
  4752.1  386.68  4775.7  384.73  4802.3  381.50  4807.6  381.67  4814.9  380.44
  4839.5  378.40  4888.5  372.15  4909.5  371.31  4941.1  371.17  4961.8  369.73
  4972.6  370.85  4983.2  370.83  4997.0  367.37  4997.3  366.87  5000.8  366.87
  5001.0  367.37  5004.3  367.40  5014.7  369.82  5025.2  370.21  5088.3  370.13
  5119.9  371.00  5163.8  375.18  5190.5  376.44  5195.8  377.68  5223.9  379.65
  5254.3  382.25  5259.6  382.02  5286.2  384.58  5291.5  384.04  5319.3  386.40
#Mann=4,-1,0
  4752.1    0.16       0  4997.0    0.07       0  5001.0    0.16       0
  5223.9     0.1       0
Bank Sta=4997,5001
Exp/Cntr=0.3,0.1

Type RM Length L Ch R = 1,2297,399,399,399
BEGIN DESCRIPTION:
DUCK CREEK TRIB 31 5 0
END DESCRIPTION:
XS GIS Cut Line= 2
      3507064.15     10419776.88      3507637.08     10419631.04
#Sta/Elev= 30
  4640.7  381.80  4669.5  382.46  4683.6  383.30  4719.4  383.01  4724.5  383.31
  4793.4  379.05  4814.0  377.22  4923.9  369.66  4937.8  368.99  4964.8  368.68
  4970.0  368.94  4989.4  368.03  4997.7  364.80  4998.0  364.30  5001.5  364.30
  5001.7  364.80  5005.7  367.32  5010.9  368.47  5046.6  367.41  5113.3  367.43
  5128.4  365.91  5133.9  367.36  5164.2  368.40  5169.3  369.71  5185.5  370.41
  5195.8  371.49  5205.1  371.73  5210.2  373.31  5216.4  374.21  5231.9  374.65
#Mann=3,-1,0
  4640.7    0.16       0  4997.7    0.07       0  5001.7    0.16       0
Bank Sta=4997.7,5001.7
Exp/Cntr=0.3,0.1

Type RM Length L Ch R = 1,1898,349,349,349
BEGIN DESCRIPTION:
DUCK CREEK TRIB 31 3 0
END DESCRIPTION:
XS GIS Cut Line= 5
      3507149.09     10419857.14      3507212.93     10419909.47
      3507444.70     10420073.54      3507640.02     10420034.47
      3507710.04     10419635.06
#Sta/Elev= 30
  4509.3  379.46  4536.3  379.91  4571.5  378.01  4578.0  376.76  4585.9  376.64
  4589.6  375.78  4600.6  376.34  4606.7  375.13  4621.5  374.89  4657.2  372.38
  4750.5  367.91  4829.5  364.32  4893.6  364.22  4960.9  365.88  4970.9  365.00
  4983.3  363.75  4983.6  363.25  4987.1  363.25  4987.3  363.75  5017.0  364.92
  5072.5  365.46  5088.0  365.88  5128.6  368.73  5165.4  368.53  5287.9  368.39
  5353.6  367.36  5382.4  366.11  5433.2  366.91  5461.0  371.68  5480.5  374.25
#Mann=8,-1,0
  4509.3    0.05       0  4750.5    0.16       0  4970.9     0.1       0
  4983.3    0.07       0  4987.3     0.1       0  5072.5    0.16       0
  5165.4    0.05       0  5353.6     0.1       0
Bank Sta=4983.3,4987.3
Exp/Cntr=0.3,0.1

Type RM Length L Ch R = 1,1549,0,0,0
BEGIN DESCRIPTION:
DUCK CREEK TRIB 31 5 2
END DESCRIPTION:
XS GIS Cut Line= 4
      3507156.88     10420171.30      3507506.28     10420499.01
      3507794.91     10420273.31      3507877.07     10419486.32
#Sta/Elev= 30
  4212.4  371.49  4237.5  368.05  4259.0  368.29  4322.5  366.04  4448.8  365.69
  4534.9  366.00  4555.9  364.48  4586.6  364.35  4693.9  365.95  4722.8  363.93
  4741.6  361.65  4741.9  361.15  4745.6  361.65  4797.6  362.07  5184.0  361.90
  5268.6  363.49  5372.1  363.02  5381.2  363.57  5401.4  367.17  5411.4  367.73
  5431.5  367.45  5465.5  364.88  5529.0  363.87  5552.2  364.89  5558.8  366.18
  5563.9  365.25  5582.3  366.81  5632.6  365.78  5692.9  367.17  5849.1  376.32
#Mann=9,-1,0
  4212.4    0.05       0  4322.5    0.12       0  4448.8    0.16       0
  4586.6    0.12       0  4741.6    0.07       0  4745.6    0.12       0
  4797.6    0.16       0  5184.0    0.05       0  5529.0     0.1       0
Bank Sta=4741.6,4745.6
Exp/Cntr=0.3,0.1

Chan Stop Cuts=-1