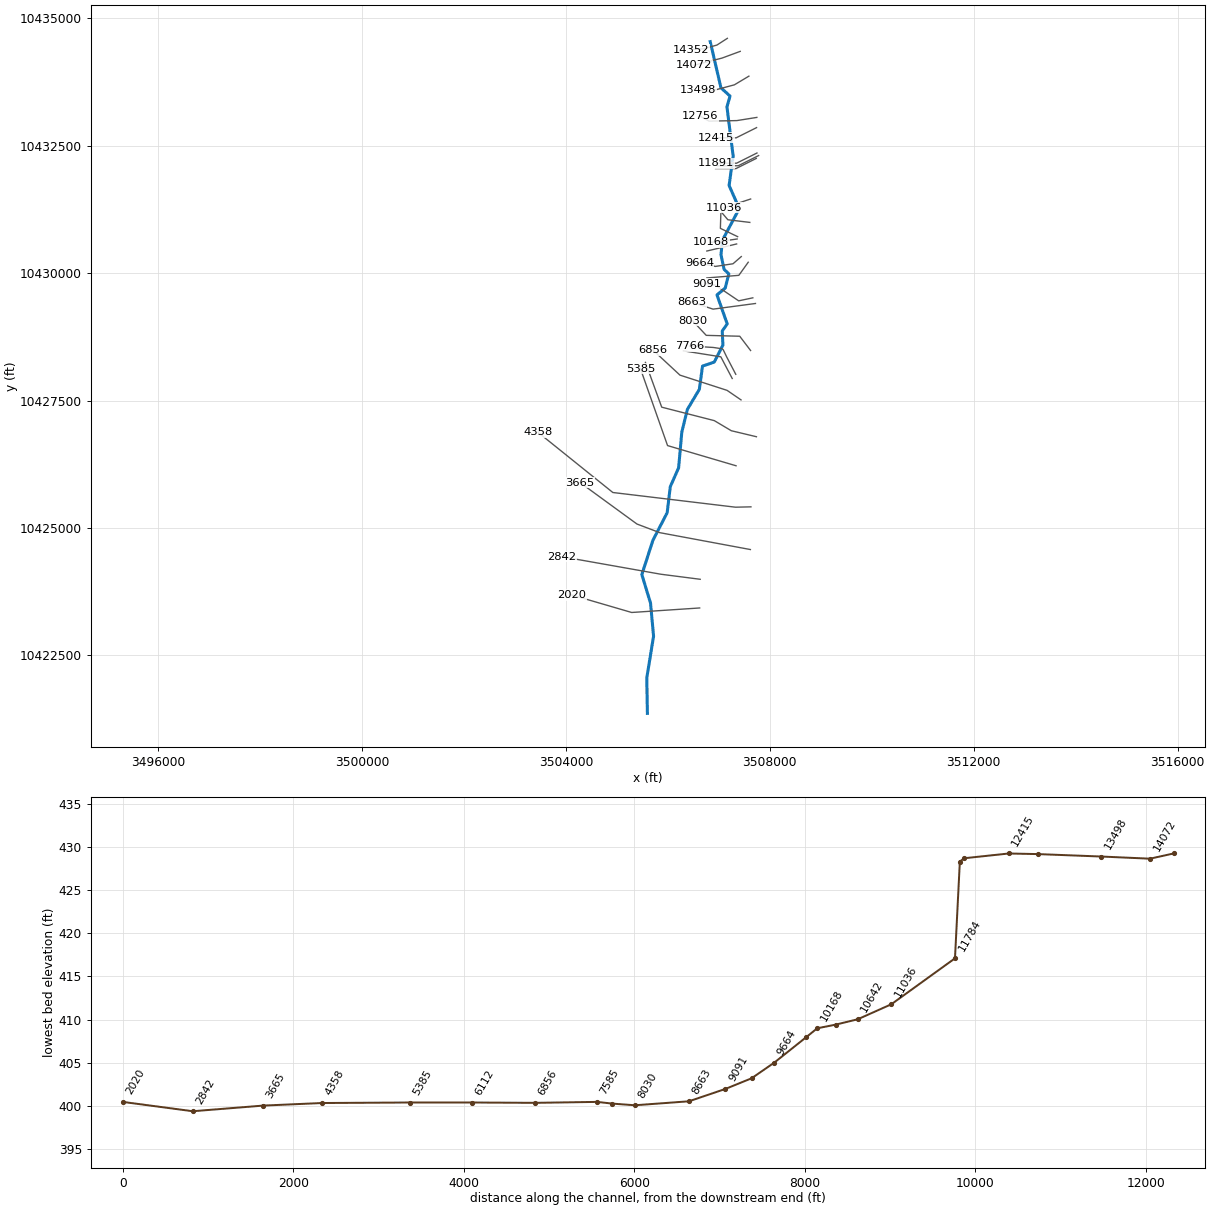
--- DUCK CREEK TRIB 32.prj (project) ---

Proj Title=DUCK CREEK TRIB 32 Base Level Engineering
Current Plan=p01
Default Exp/Contr=0.3,0.1
English Units
Geom File=g01
Flow File=f01
Plan File=p01
Y Axis Title=Elevation
X Axis Title(PF)=Main Channel Distance
X Axis Title(XS)=Station
BEGIN DESCRIPTION:
DUCK CREEK TRIB 32
END DESCRIPTION:
DSS Export Rating Curves= 0
DSS Export Rating Curve Sorted= 0
DSS Export Volume Flow Curves= 0
DXF OffsetX= 0
DXF OffsetY= 0
DXF ScaleX= 1
DXF ScaleY= 10

--- DUCK CREEK TRIB 32.p01 (plan) ---

Plan Title=Multiple Run
Short Identifier=Multiple
Geom File=g01
Flow File=f01
Subcritical Flow
K Sum by GR= 0
Std Step Tol= 0.01
Critical Tol= 0.01
Num of Std Step Trials= 20
Max Error Tol= 0.3
Flow Tol Ratio= 0.001
Split Flow NTrial= 30
Split Flow Tol= 0.02
Split Flow Ratio= 0.02
Log Output Level= 0
Friction Slope Method= 1
Unsteady Friction Slope Method= 2
Unsteady Bridges Friction Slope Method= 1
Parabolic Critical Depth
Global Vel Dist=  1 , 1 , 1
Global Log Level= 0
CheckData=True
Encroach Param= -1, 0, 0, 0
BEGIN DESCRIPTION:
Multiple Run
END DESCRIPTION:

--- DUCK CREEK TRIB 32.f01 (steady flow) ---

Flow Title=Multiple
Program Version=4.10
Number of Profiles= 7
Profile Names=10-year,25-year,50-year,1pct_min,100-year,1pct_plu,500-year
River Rch & RM=DUCK CREEK TRIB,Reach-1         ,14352
     605     808     970     851    1151    1557    1617
River Rch & RM=DUCK CREEK TRIB,Reach-1         ,11784
     904    1240    1517    1354    1832    2477    2663
River Rch & RM=DUCK CREEK TRIB,Reach-1         ,9398
    1057    1455    1782    1592    2153    2912    3135
River Rch & RM=DUCK CREEK TRIB,Reach-1         ,4358
    1361    1891    2330    2090    2826    3822    4152
Boundary for River Rch & Prof#=DUCK CREEK TRIB,Reach-1         , 1
Up Type= 0
Dn Type= 3
Dn Slope=0.005
Boundary for River Rch & Prof#=DUCK CREEK TRIB,Reach-1         , 2
Up Type= 0
Dn Type= 3
Dn Slope=0.005
Boundary for River Rch & Prof#=DUCK CREEK TRIB,Reach-1         , 3
Up Type= 0
Dn Type= 3
Dn Slope=0.005
Boundary for River Rch & Prof#=DUCK CREEK TRIB,Reach-1         , 4
Up Type= 0
Dn Type= 3
Dn Slope=0.005
Boundary for River Rch & Prof#=DUCK CREEK TRIB,Reach-1         , 5
Up Type= 0
Dn Type= 3
Dn Slope=0.005
Boundary for River Rch & Prof#=DUCK CREEK TRIB,Reach-1         , 6
Up Type= 0
Dn Type= 3
Dn Slope=0.005
Boundary for River Rch & Prof#=DUCK CREEK TRIB,Reach-1         , 7
Up Type= 0
Dn Type= 3
Dn Slope=0.005
DSS Import GetInterval= 0
DSS Import GetPeak= 0
DSS Import FillOption= 0

--- DUCK CREEK TRIB 32.g01 (geometry) ---

Geom Title=Existing Conditions
Program Version=4.10

River Reach=DUCK CREEK TRIB ,Reach-1
Reach XY= 30
      3506832.41     10434538.04      3507042.91     10433633.09
      3507220.87     10433470.33       3507160.1     10433259.83
      3507282.11     10432293.76      3507202.49     10431716.69
      3507402.51     10431265.45      3507070.74     10430641.93
      3507043.57     10430356.82       3507104.8     10430071.95
      3507197.31     10429983.34      3507125.64     10429704.59
      3506964.75     10429570.58      3507165.62     10429002.73
      3507068.22     10428864.18      3507081.07     10428586.67
      3506911.81     10428254.03      3506681.07     10428174.81
      3506618.97     10427718.53      3506384.66     10427326.27
      3506274.95     10426880.39      3506212.64     10426180.73
      3506048.94     10425809.86        3505988.     10425299.61
      3505708.22     10424758.28      3505491.19     10424086.65
      3505661.76     10423525.16      3505721.22     10422876.37
      3505587.61      10422059.1      3505600.36     10421364.03

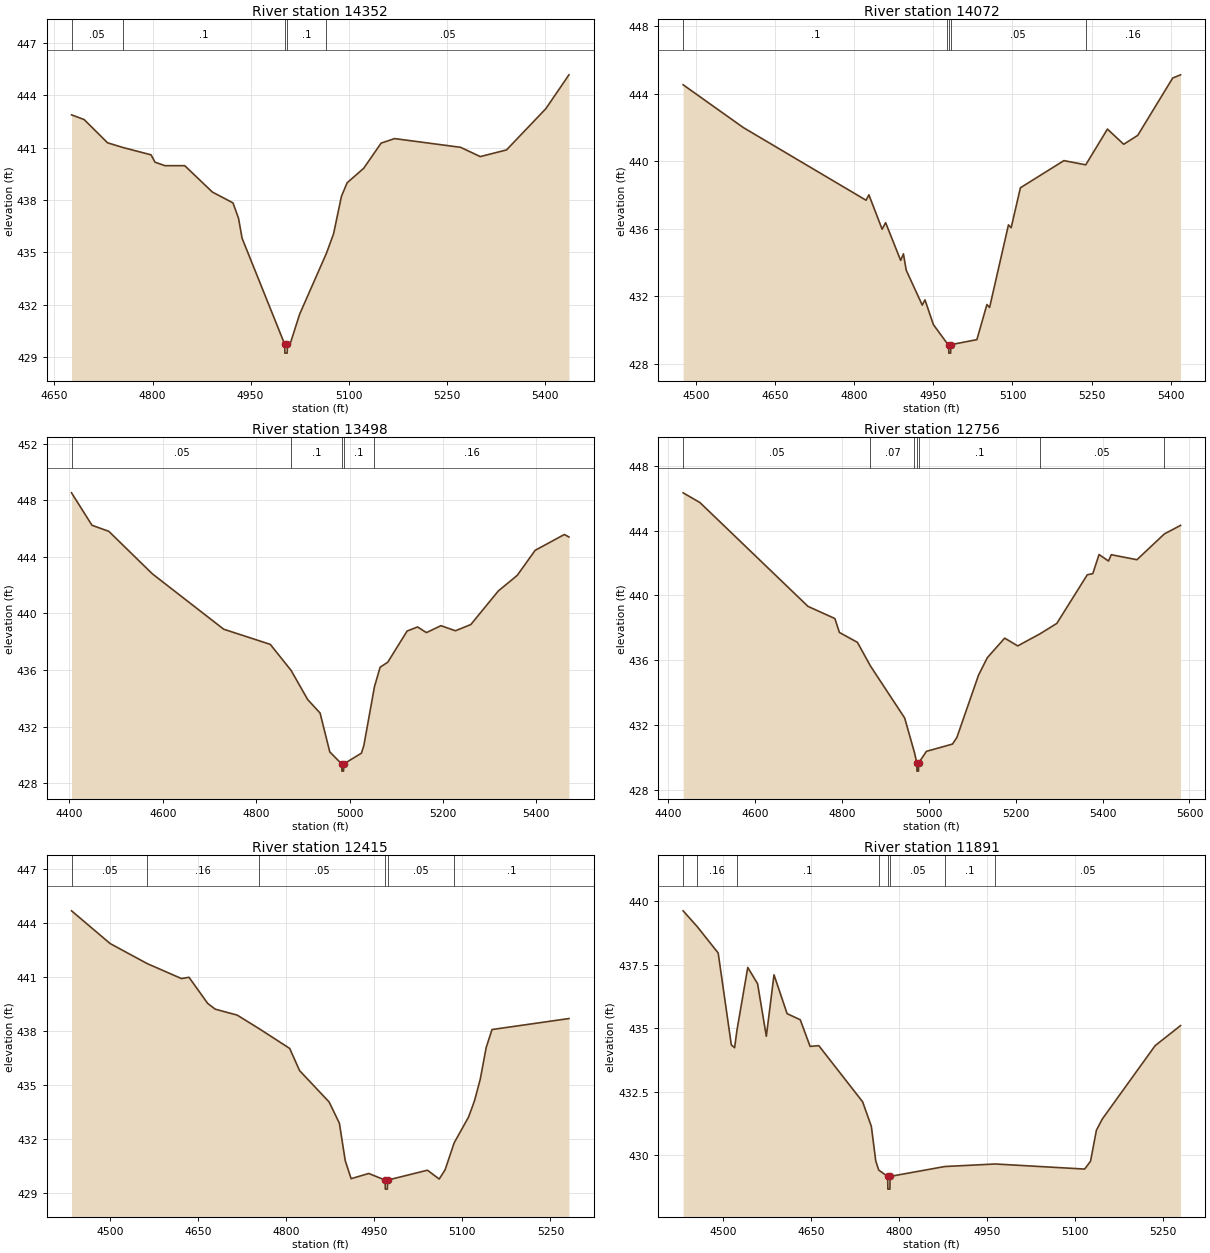
Type RM Length L Ch R = 1 ,14352   ,280,280,280
BEGIN DESCRIPTION:
DUCK CREEK TRIB 32 14 0
END DESCRIPTION:
XS GIS Cut Line= 4
      3507168.34     10434603.28      3506963.46     10434471.32
      3506703.05      10434398.4      3506456.79     10434381.06
#Sta/Elev= 30
  4676.1  442.87  4695.4   442.6  4731.2  441.27  4754.7     441  4797.8  440.58
  4803.8  440.16    4819  439.96  4849.3  439.96  4891.6  438.45  4923.1  437.83
  4931.6  436.95    4937  435.81  5002.3  429.73  5002.5  429.23    5006  429.23
  5006.3  429.73  5010.4  429.74  5025.1  431.46    5066  434.94    5077  436.06
    5089   438.2  5097.7  438.98  5123.1  439.81  5149.7  441.25  5170.4  441.51
  5271.4  441.01  5301.4  440.48  5341.5  440.86  5401.7  443.22  5437.1  445.16
#Mann= 5 ,-1 , 0
  4676.1     .05       0  4754.7      .1       0  5002.3     .07       0
  5006.3      .1       0    5066     .05       0
Bank Sta=5002.3,5006.3
XS Rating Curve= 0 ,0
Exp/Cntr=0.3,0.1

Type RM Length L Ch R = 1 ,14072   ,574,574,574
BEGIN DESCRIPTION:
Mapping XS 917231c8
END DESCRIPTION:
XS GIS Cut Line= 3
      3507420.51     10434347.63      3507062.86     10434215.68
      3506517.69     10434076.78
#Sta/Elev= 30
  4475.1  444.54  4589.4     442  4822.2  437.69  4827.6  438.01  4852.7  435.97
  4859.3  436.36  4887.9  434.12  4893.1  434.51  4898.4  433.54  4928.8  431.47
    4934  431.78    4950  430.31  4976.7  429.17  4978.9  429.12  4979.2  428.62
  4982.7  428.62  4982.9  429.12  5032.5  429.42  5051.5   431.5  5056.6  431.33
  5092.4  436.23  5097.5  436.06  5115.1  438.43  5197.6  440.04    5239  439.79
  5280.2  441.91  5311.1  441.01  5337.7  441.54    5404  444.94  5418.9  445.13
#Mann= 5 ,-1 , 0
  4475.1      .1       0  4976.7     .05       0  4978.9     .03       0
  4982.9     .05       0    5239     .16       0
Bank Sta=4978.9,4982.9
XS Rating Curve= 0 ,0
Exp/Cntr=0.3,0.1

Type RM Length L Ch R = 1 ,13498   ,742,742,742
BEGIN DESCRIPTION:
Mapping XS 7a191988
END DESCRIPTION:
XS GIS Cut Line= 4
      3507590.67     10433861.53      3507305.91     10433691.37
      3506798.97     10433555.96      3506592.52     10433586.92
#Sta/Elev= 30
  4404.5  448.52  4448.3  446.23  4484.4   445.8  4577.6   442.8  4730.4  438.89
  4830.1  437.82  4874.7  435.98  4910.3  433.92  4936.8  432.97  4957.5  430.23
  4983.2  429.37  4983.5  428.87    4987  428.87  4987.2  429.37  5025.3  430.14
  5030.5  430.68  5053.2  434.83  5065.4  436.21  5081.7  436.56  5123.1  438.76
  5145.5  439.05  5164.5  438.65  5195.6  439.14  5226.6  438.78  5259.6  439.22
  5318.4  441.59  5358.9  442.69  5397.3  444.46    5460  445.58  5469.7   445.4
#Mann= 5 ,-1 , 0
  4404.5     .05       0  4874.7      .1       0  4983.2     .07       0
  4987.2      .1       0  5053.2     .16       0
Bank Sta=4983.2,4987.2
XS Rating Curve= 0 ,0
Exp/Cntr=0.3,0.1

Type RM Length L Ch R = 1 ,12756   ,341,341,341
BEGIN DESCRIPTION:
Mapping XS 71b7b769
END DESCRIPTION:
XS GIS Cut Line= 4
      3507746.86     10433052.48      3507354.52     10432989.98
      3506809.38     10432979.57      3506632.42     10433076.73
#Sta/Elev= 30
  4435.1  446.33  4473.8  445.73  4722.4  439.32  4784.2  438.57  4794.7  437.71
  4836.1   437.1  4866.1  435.64  4944.8  432.43  4967.3   430.3  4972.8  429.65
  4973.1  429.15  4976.6  429.15  4976.8  429.65  4994.8  430.37  5054.8  430.82
  5064.8  431.22  5114.8  435.08  5134.9  436.15  5174.9  437.36  5204.9  436.88
  5256.4  437.63  5294.9  438.27  5364.9  441.27  5377.6  441.34    5392  442.52
  5413.8  442.12  5420.1  442.51  5479.2   442.2  5542.1  443.79  5579.5  444.32
#Mann= 7 ,-1 , 0
  4435.1     .05       0  4866.1     .07       0  4967.3      .1       0
  4972.8     .07       0  4976.8      .1       0  5256.4     .05       0
  5542.1     .16       0
Bank Sta=4972.8,4976.8
XS Rating Curve= 0 ,0
Exp/Cntr=0.3,0.1

Type RM Length L Ch R = 1 ,12415   ,524,524,524
BEGIN DESCRIPTION:
DUCK CREEK TRIB 32 14 1
END DESCRIPTION:
XS GIS Cut Line= 3
      3507741.06     10432852.06      3507341.06     10432652.06
      3506941.08     10432652.06
#Sta/Elev= 30
  4434.3  444.67  4500.2  442.85  4563.2  441.74  4621.5  440.91  4634.4  440.98
  4666.2  439.53  4679.1  439.21  4716.5  438.88  4754.2  438.12  4805.9  437.03
  4822.7   435.8    4873  434.06  4890.5  432.88  4900.5   430.8  4910.5   429.8
  4940.5  430.09  4968.5  429.72  4968.7  429.22  4972.2  429.22  4972.5  429.72
  5040.5  430.27  5060.5  429.78  5070.5  430.29    5086  431.79  5110.5  433.22
  5120.5  434.11  5130.5  435.33  5140.5  437.08  5150.5  438.08  5281.5  438.69
#Mann= 6 ,-1 , 0
  4434.3     .05       0  4563.2     .16       0  4754.2     .05       0
  4968.5    .035       0  4972.5     .05       0    5086      .1       0
Bank Sta=4968.5,4972.5
XS Rating Curve= 0 ,0
Exp/Cntr=0.3,0.1

Type RM Length L Ch R = 1 ,11891   ,50,50,50
BEGIN DESCRIPTION:
DUCK CREEK TRIB 32 34 0
END DESCRIPTION:
XS GIS Cut Line= 3
      3507748.84     10432354.21      3507348.88     10432154.23
      3506948.85     10432154.23
#Sta/Elev= 30
  4432.2  439.63  4455.8  439.02  4491.9  437.97  4514.3  434.35  4519.9  434.24
  4523.9  434.93  4542.3   437.4    4559  436.76  4573.9  434.69    4587  437.11
  4609.3  435.58  4631.7  435.34  4648.5  434.29  4663.3  434.32  4737.9  432.11
  4752.8  431.14  4760.3  429.78  4765.4  429.42  4780.6  429.17  4780.9  428.67
  4784.4  428.67  4784.6  429.17  4877.8  429.56    4964  429.66  5116.1  429.46
  5126.1  429.77  5136.1  430.99  5146.1  431.43  5236.1  434.32  5279.4  435.11
#Mann= 8 ,-1 , 0
  4432.2     .05       0  4455.8     .16       0  4523.9      .1       0
  4765.4     .05       0  4780.6    .033       0  4784.6     .05       0
  4877.8      .1       0    4964     .05       0
Bank Sta=4780.6,4784.6
XS Rating Curve= 0 ,0
Exp/Cntr=0.3,0.1

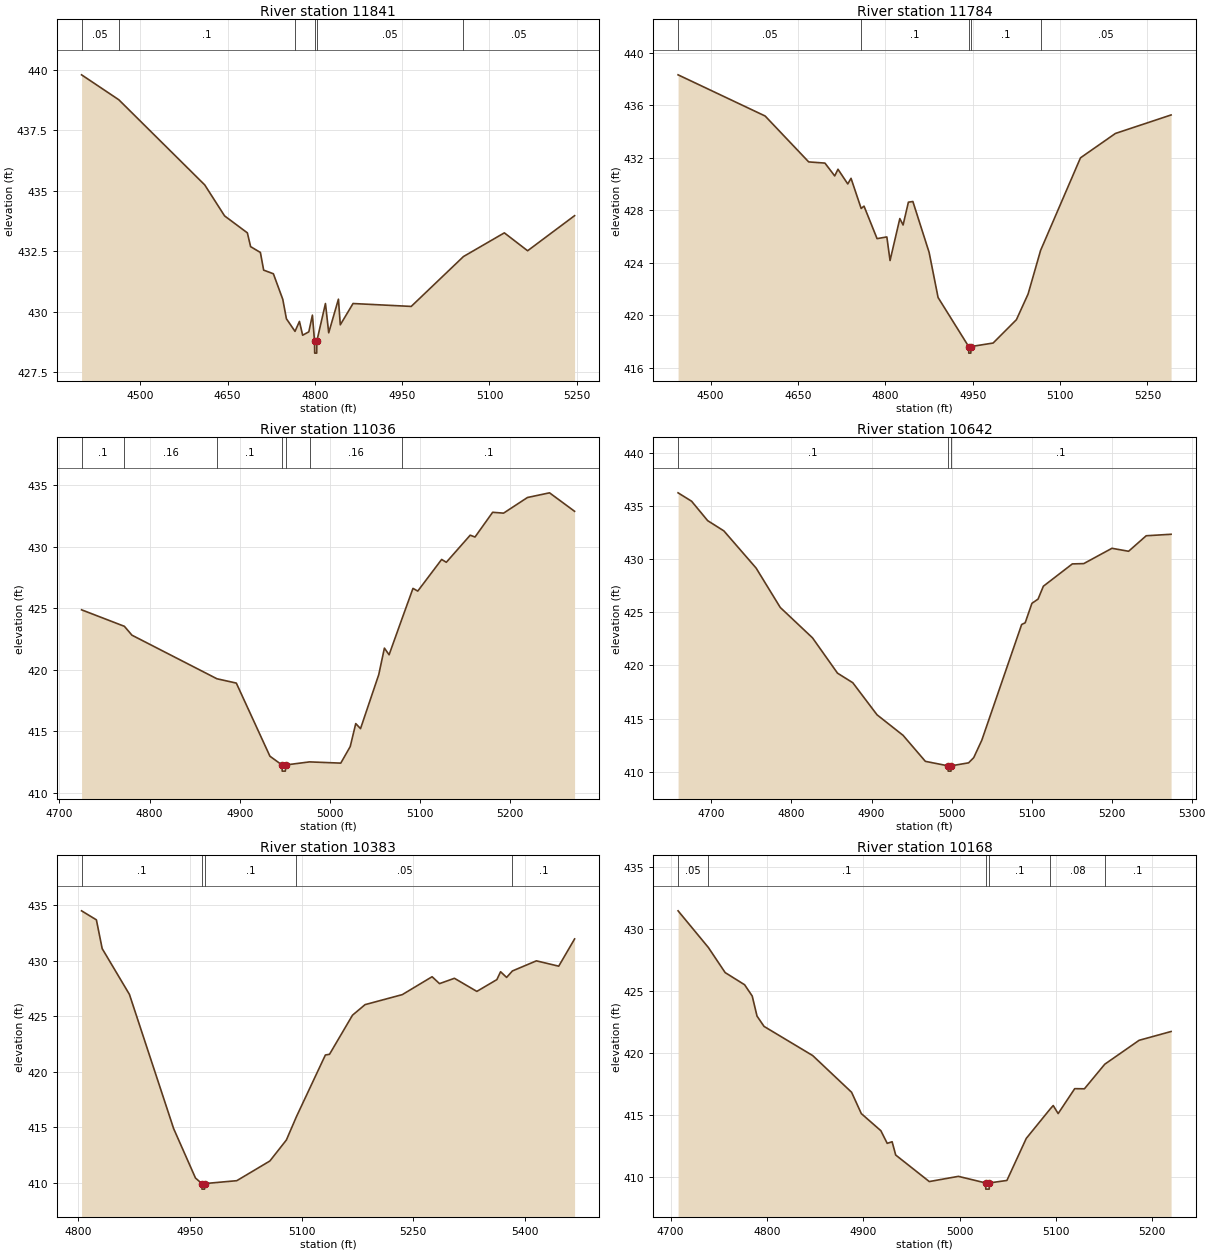
Type RM Length L Ch R = 1 ,11841   ,57,57,57
BEGIN DESCRIPTION:
DUCK CREEK TRIB 32 24 0
END DESCRIPTION:
XS GIS Cut Line= 3
      3507781.42     10432304.31      3507381.43     10432104.32
      3506981.44     10432104.32
#Sta/Elev= 30
  4399.1  439.78  4463.1  438.75  4610.8  435.23  4644.9  433.95    4684  433.25
  4689.6  432.68  4706.4  432.44    4712  431.71  4728.7  431.56  4744.9   430.5
  4751.1   429.7  4765.9  429.18  4773.5  429.59    4779  429.02  4789.6  429.16
  4795.8  429.85  4799.4  428.78  4799.7  428.28  4803.2  428.28  4803.4  428.78
  4818.2  430.33  4823.8  429.12  4840.5  430.51  4843.7  429.45  4865.6  430.33
  4965.6  430.21  5055.3  432.27  5125.6  433.25  5165.6  432.51  5246.3  433.96
#Mann= 6 ,-1 , 0
  4399.1     .05       0  4463.1      .1       0  4765.9     .05       0
  4799.4     .07       0  4803.4     .05       0  5055.3     .05       0
Bank Sta=4799.4,4803.4
XS Rating Curve= 0 ,0
Exp/Cntr=0.3,0.1

Type RM Length L Ch R = 1 ,11784   ,748,748,748
BEGIN DESCRIPTION:
DUCK CREEK TRIB 32 4 0
END DESCRIPTION:
XS GIS Cut Line= 3
      3507735.85     10432247.89      3507335.86     10432047.89
      3506936.46     10432047.89
#Sta/Elev= 30
  4444.1  438.32  4593.6  435.18  4668.4  431.68  4696.3  431.59  4713.1  430.61
  4718.7  431.12  4735.5     430  4741.1  430.43  4758.5  428.13  4763.4  428.31
  4785.8  425.83  4802.6  425.96  4808.1  424.16  4824.9  427.36  4830.5  426.87
  4839.6  428.61  4847.3  428.66  4875.2  424.78  4890.6  421.34  4943.1   417.6
  4943.3   417.1  4946.8   417.1  4947.1   417.6  4985.1  417.87  5025.1  419.65
  5045.1   421.6  5066.6  424.93  5135.1  431.99  5195.1  433.85  5290.7  435.26
#Mann= 5 ,-1 , 0
  4444.1     .05       0  4758.5      .1       0  4943.1     .07       0
  4947.1      .1       0  5066.6     .05       0
Bank Sta=4943.1,4947.1
XS Rating Curve= 0 ,0
Exp/Cntr=0.3,0.1

Type RM Length L Ch R = 1 ,11036   ,394,394,394
BEGIN DESCRIPTION:
DUCK CREEK TRIB 32 21 0
END DESCRIPTION:
XS GIS Cut Line= 2
       3507625.2     10431452.24      3507105.75     10431280.83
#Sta/Elev= 30
  4724.5  424.88    4772  423.54  4780.4  422.82  4874.7  419.28  4896.2  418.93
  4933.5  412.99  4946.9  412.28  4947.1  411.78  4950.6  411.78  4950.9  412.28
  4977.4  412.53  5012.1  412.43  5022.6  413.78  5028.7  415.64    5034  415.23
  5054.2  419.61  5060.5  421.77  5065.7  421.23  5080.2  424.19  5092.2  426.62
  5097.5   426.4    5124  428.97  5129.2  428.74  5155.7  430.94    5161  430.79
  5180.6   432.8  5192.7  432.73  5219.2     434  5243.7  434.38  5271.5  432.88
#Mann= 7 ,-1 , 0
  4724.5      .1       0    4772     .16       0  4874.7      .1       0
  4946.9     .07       0  4950.9      .1       0  4977.4     .16       0
  5080.2      .1       0
Bank Sta=4946.9,4950.9
XS Rating Curve= 0 ,0
Exp/Cntr=0.3,0.1

Type RM Length L Ch R = 1 ,10642   ,259,259,259
BEGIN DESCRIPTION:
DUCK CREEK TRIB 32 19 0
END DESCRIPTION:
XS GIS Cut Line= 3
      3507608.87     10430993.21       3507178.3      10431045.3
      3507060.24     10431184.19
#Sta/Elev= 30
  4658.3  436.24  4675.2  435.45  4695.3  433.62  4715.5  432.66  4755.8  429.16
    4786  425.45  4826.3  422.59  4857.5  419.27  4876.6  418.37  4906.9  415.35
  4939.4  413.42  4967.3  410.97  4995.5  410.55  4995.8  410.05  4999.3  410.05
  4999.5  410.55  5021.3  410.83  5027.7  411.32  5037.8  412.96  5087.6  423.85
    5092  424.01  5100.4  425.84  5108.1  426.24  5114.7  427.45  5150.9  429.55
  5165.2  429.58  5200.4  431.02  5221.2  430.74  5243.2   432.2  5274.3  432.34
#Mann= 3 ,-1 , 0
  4658.3      .1       0  4995.5     .07       0  4999.5      .1       0
Bank Sta=4995.5,4999.5
XS Rating Curve= 0 ,0
Exp/Cntr=0.3,0.1

Type RM Length L Ch R = 1 ,10383   ,215,215,215
BEGIN DESCRIPTION:
DUCK CREEK TRIB 32 17 0
END DESCRIPTION:
XS GIS Cut Line= 3
      3507370.04     10430713.71      3507031.53     10430876.45
      3507040.21     10431162.92
#Sta/Elev= 30
  4804.5  434.47  4824.4  433.66  4832.2  431.07  4868.8  426.95  4928.2  414.87
  4957.5  410.43    4966  409.93  4966.2  409.43  4969.7  409.43    4970  409.93
    5013  410.19  5057.4  411.96  5079.6  413.85  5093.1  415.95    5132   421.5
  5137.5  421.56  5168.4  425.08  5185.3  426.03  5235.3  426.93  5275.3  428.54
  5285.3  427.92  5305.3   428.4  5335.4  427.22  5362.3  428.28  5367.3  428.99
  5375.4  428.48  5383.2  429.06  5415.4  429.97  5445.4  429.49  5466.7  431.94
#Mann= 5 ,-1 , 0
  4804.5      .1       0    4966     .07       0    4970      .1       0
  5093.1     .05       0  5383.2      .1       0
Bank Sta=4966,4970
XS Rating Curve= 0 ,0
Exp/Cntr=0.3,0.1

Type RM Length L Ch R = 1 ,10168   ,127,127,127
BEGIN DESCRIPTION:
DUCK CREEK TRIB 32 2 0
END DESCRIPTION:
XS GIS Cut Line= 3
      3507360.47     10430668.13      3507136.52     10430635.57
      3506852.68     10430603.02
#Sta/Elev= 30
  4707.7  431.45  4739.2  428.49  4756.6  426.47  4776.8  425.49  4784.7  424.58
  4789.7  422.96    4797  422.13  4847.5  419.78  4887.9  416.82    4898   415.1
  4918.3  413.72  4924.9   412.7    4930  412.83  4933.7  411.76  4968.6  409.62
  4998.8  410.04    5027  409.51  5027.3  409.01  5030.8  409.01    5031  409.51
  5049.2  409.71  5069.3   413.1  5094.2  415.48  5097.3  415.75  5102.4   415.1
  5119.6  417.11  5129.7   417.1  5150.8  419.08  5186.5  421.01  5219.7  421.72
#Mann= 6 ,-1 , 0
  4707.7     .05       0  4739.2      .1       0    5027     .07       0
    5031      .1       0  5094.2     .08       0  5150.8      .1       0
Bank Sta=5027,5031
XS Rating Curve= 0 ,0
Exp/Cntr=0.3,0.1

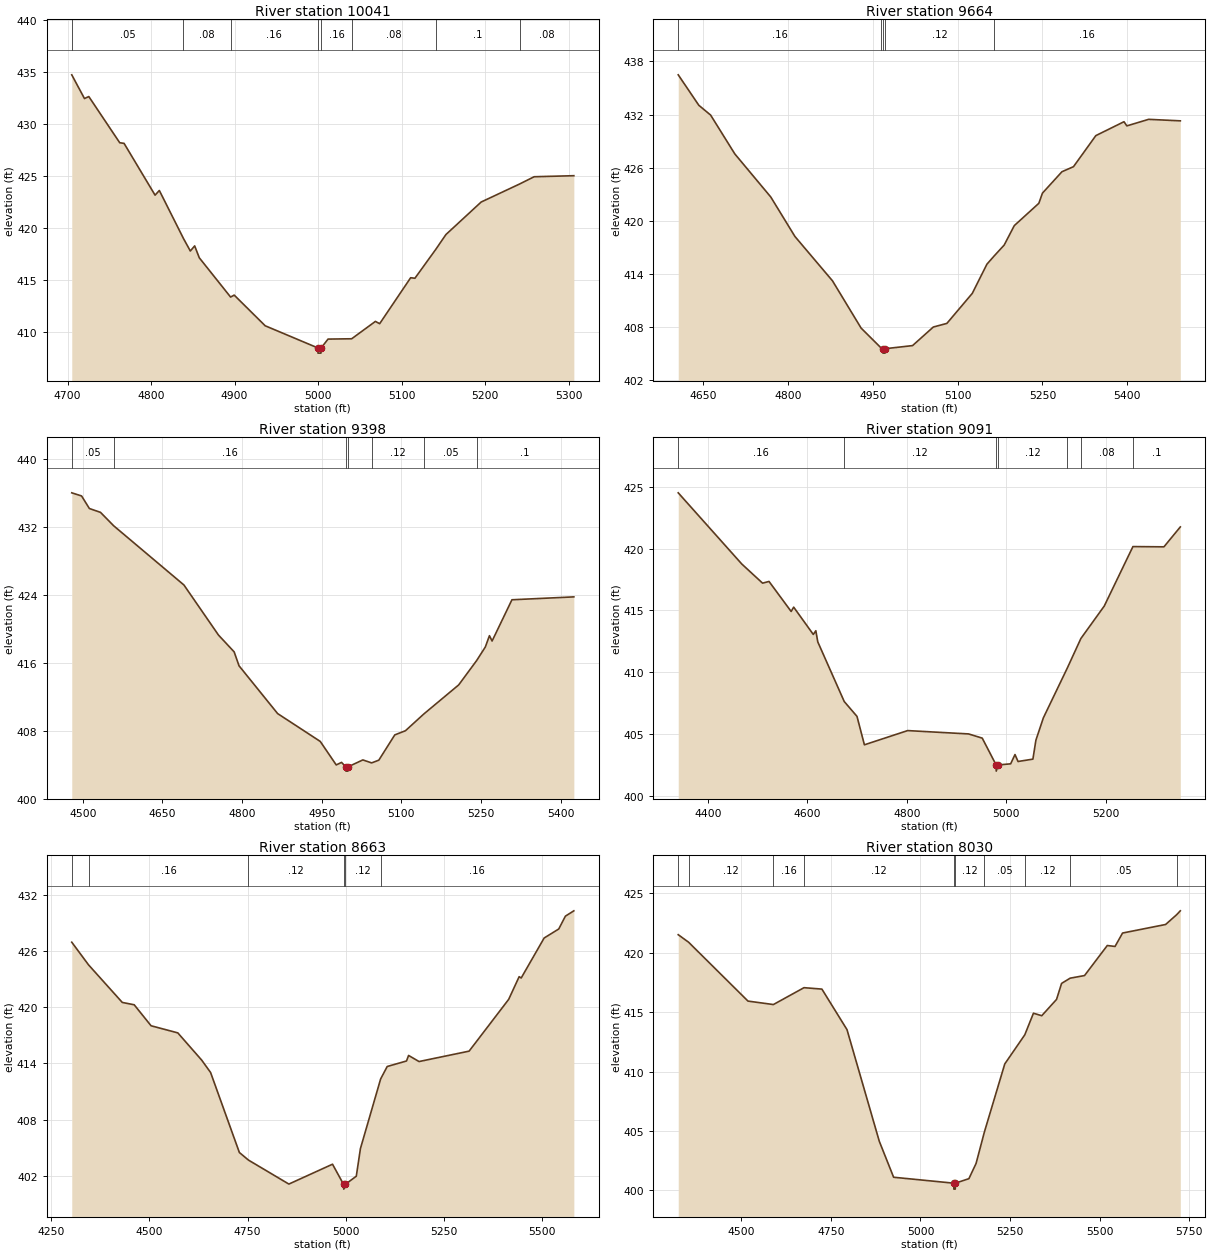
Type RM Length L Ch R = 1 ,10041   ,377,377,377
BEGIN DESCRIPTION:
DUCK CREEK TRIB 32 16 2
END DESCRIPTION:
XS GIS Cut Line= 2
      3507350.57     10430570.47      3506765.87     10430431.87
#Sta/Elev= 30
  4705.1  434.76  4720.3  432.48  4725.5  432.67  4762.5  428.23  4767.7  428.17
  4804.8  423.19  4809.9  423.64  4838.8  419.02    4847  417.82  4852.2  418.31
  4857.7  417.17  4895.2  413.39  4899.5  413.58  4936.6  410.63  4999.6   408.5
  4999.8     408  5003.3     408  5003.6   408.5  5011.8  409.35  5040.1  409.38
  5068.5  411.05  5073.6  410.83  5110.7  415.25  5115.8   415.2  5140.7  417.97
  5152.9   419.4  5195.1  422.53  5241.3  424.27  5258.5  424.96    5306  425.06
#Mann= 8 ,-1 , 0
  4705.1     .05       0  4838.8     .08       0  4895.2     .16       0
  4999.6     .07       0  5003.6     .16       0  5040.1     .08       0
  5140.7      .1       0  5241.3     .08       0
Bank Sta=4999.6,5003.6
XS Rating Curve= 0 ,0
Exp/Cntr=0.3,0.1

Type RM Length L Ch R = 1 ,9664    ,266,266,266
BEGIN DESCRIPTION:
DUCK CREEK TRIB 32 16 3
END DESCRIPTION:
XS GIS Cut Line= 4
      3507441.68     10430323.07      3507278.93     10430182.01
      3506933.87     10430129.93      3506617.27     10430196.69
#Sta/Elev= 30
  4605.9  436.49  4642.3  433.05  4663.2  431.94    4706  427.55  4769.6  422.68
  4812.3  418.22  4878.7  413.21  4929.3  407.87  4965.2  405.59  4967.8  405.54
    4968  405.04  4971.5  405.04  4971.8  405.54  5020.3  405.89    5057  407.99
    5081   408.4  5125.9  411.79  5151.8  415.09  5163.9  415.97  5182.3  417.25
  5200.2  419.45  5243.6  421.97    5250  423.12  5284.5  425.54  5304.9  426.11
  5344.4  429.62  5394.2  431.19  5399.3  430.72  5437.8  431.46  5493.8  431.29
#Mann= 5 ,-1 , 0
  4605.9     .16       0  4965.2     .12       0  4967.8     .07       0
  4971.8     .12       0  5163.9     .16       0
Bank Sta=4967.8,4971.8
XS Rating Curve= 0 ,0
Exp/Cntr=0.3,0.1

Type RM Length L Ch R = 1 ,9398    ,307,307,307
BEGIN DESCRIPTION:
DUCK CREEK TRIB 32 17 1
END DESCRIPTION:
XS GIS Cut Line= 3
      3507577.63       10430212.      3507393.57     10429955.02
      3506765.94     10429903.98
#Sta/Elev= 30
  4479.3  436.02  4497.8  435.65  4512.5  434.17  4533.4  433.72  4558.2  432.14
  4690.6  425.16  4755.7  419.26  4785.2  417.28  4794.4  415.64  4867.1  410.01
  4947.4  406.73  4977.5  403.96  4987.5  404.26  4995.5  403.73  4995.8  403.23
  4999.3  403.23  4999.5  403.73  5027.6  404.55  5044.2   404.2  5057.7  404.52
  5087.8   407.5  5107.9  407.99    5143  409.99  5208.2  413.39  5241.9  416.25
  5258.4  417.86  5266.1  419.19  5271.1  418.56  5308.5  423.42  5425.1  423.76
#Mann= 7 ,-1 , 0
  4479.3     .05       0  4558.2     .16       0  4995.5     .07       0
  4999.5     .16       0  5044.2     .12       0    5143     .05       0
  5241.9      .1       0
Bank Sta=4995.5,4999.5
XS Rating Curve= 0 ,0
Exp/Cntr=0.3,0.1

Type RM Length L Ch R = 1 ,9091    ,428,428,428
BEGIN DESCRIPTION:
DUCK CREEK TRIB 32 16 1
END DESCRIPTION:
XS GIS Cut Line= 4
      3507667.92     10429514.05       3507390.1     10429455.02
      3506938.71     10429760.57      3506761.65     10429791.82
#Sta/Elev= 30
  4340.6  424.52  4468.3  418.76  4510.1  417.21    4523  417.35  4567.5  414.92
  4572.6  415.27    4612  413.06  4617.1  413.36    4621  412.46  4674.2  407.63
  4699.8  406.43  4714.7  404.13  4801.6  405.28  4924.1  405.01  4951.5  404.67
  4979.4   402.5  4979.6     402  4983.4   402.5  5008.6  402.59  5017.3  403.34
  5023.4  402.78  5053.3  402.97  5059.3   404.5  5074.3  406.31  5122.3  410.33
  5149.7  412.73  5196.7  415.36  5254.3  420.17  5316.6  420.15  5349.5  421.76
#Mann= 7 ,-1 , 0
  4340.6     .16       0  4674.2     .12       0  4979.4     .07       0
  4983.4     .12       0  5122.3     .05       0  5149.7     .08       0
  5254.3      .1       0
Bank Sta=4979.4,4983.4
XS Rating Curve= 0 ,0
Exp/Cntr=0.3,0.1

Type RM Length L Ch R = 1 ,8663    ,633,633,633
BEGIN DESCRIPTION:
DUCK CREEK TRIB 32 13 2
END DESCRIPTION:
XS GIS Cut Line= 3
      3507719.47     10429402.93       3506888.3     10429292.25
      3506471.66     10429428.96
#Sta/Elev= 30
    4303  426.93  4345.7  424.51  4431.5   420.5  4461.8  420.25  4504.7  418.01
  4572.7  417.25  4633.3  414.35  4656.1  413.02  4729.3  404.48  4752.4  403.67
  4855.2  401.11  4966.2  403.23  4994.4  401.07  4994.7  400.57  4998.5  401.07
  5026.7  401.95  5037.2   404.9  5088.6  412.33  5105.3  413.66  5154.4  414.25
  5159.7  414.84  5186.3  414.19  5313.6   415.3  5414.3  420.83  5440.9  423.25
  5446.1  423.11  5504.5  427.38  5541.6  428.34  5558.5  429.71    5580  430.28
#Mann= 6 ,-1 , 0
    4303     .05       0  4345.7     .16       0  4752.4     .12       0
  4994.4     .07       0  4998.5     .12       0  5088.6     .16       0
Bank Sta=4994.4,4998.5
XS Rating Curve= 0 ,0
Exp/Cntr=0.3,0.1

Type RM Length L Ch R = 1 ,8030    ,264,264,264
BEGIN DESCRIPTION:
DUCK CREEK TRIB 32 16 0
END DESCRIPTION:
XS GIS Cut Line= 4
      3507623.98     10428480.61       3507411.3     10428760.57
      3506753.75     10428777.93      3506486.97     10429064.24
#Sta/Elev= 30
  4324.2  421.53    4353   420.9  4518.8  415.94  4589.7  415.65  4675.1  417.07
    4725  416.95    4795  413.54  4885.1  404.14  4925.1  401.11  5092.9  400.61
  5093.2  400.11    5097  400.11  5097.3  400.61  5135.1  400.99  5155.1  402.27
  5178.6  404.95  5235.2  410.65    5291   413.1  5315.2  414.92  5338.4  414.71
  5379.6  416.08  5393.7  417.43  5417.6  417.87  5457.7  418.09  5521.2  420.62
  5542.8  420.54  5563.8  421.67  5683.9  422.39  5714.6  423.21  5724.9  423.54
#Mann= 10 ,-1 , 0
  4324.2     .16       0    4353     .12       0  4589.7     .16       0
  4675.1     .12       0  5092.9     .07       0  5097.3     .12       0
  5178.6     .05       0    5291     .12       0  5417.6     .05       0
  5714.6     .16       0
Bank Sta=5092.9,5097.3
XS Rating Curve= 0 ,0
Exp/Cntr=0.3,0.1

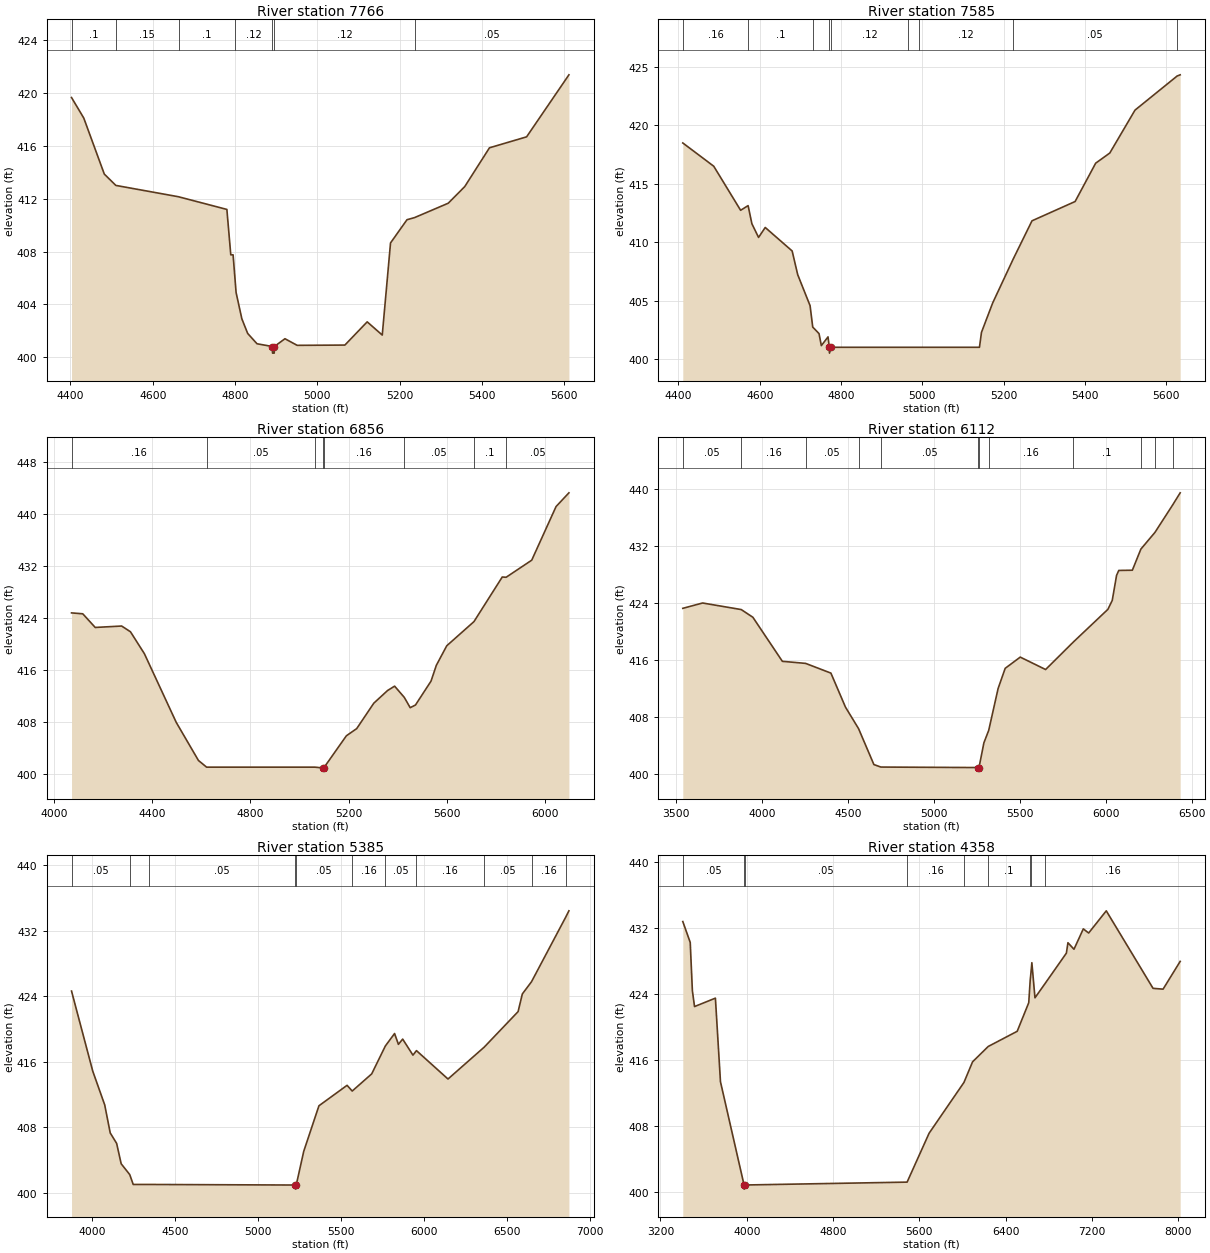
Type RM Length L Ch R = 1 ,7766    ,181,181,181
BEGIN DESCRIPTION:
DUCK CREEK TRIB 32 13 1
END DESCRIPTION:
XS GIS Cut Line= 6
      3507333.12     10428014.52      3507153.45     10428358.23
      3507088.35     10428493.65      3507067.51     10428514.48
      3506892.61     10428540.53      3506429.49     10428569.17
#Sta/Elev= 30
  4402.8  419.67  4432.6  418.11  4482.4  413.87  4510.4  413.01  4662.7  412.15
  4780.2  411.19  4789.7  407.75  4795.3  407.75    4800  405.91  4802.6  404.89
  4816.6   402.9  4830.8  401.79  4853.4  401.01  4890.8   400.8  4891.2   400.3
  4895.2   400.3  4895.5   400.8  4921.3  401.39    4951  400.89  5066.9  400.91
  5121.1  402.67  5157.7  401.67  5177.8  408.65  5217.8  410.41  5236.2  410.57
    5318  411.66  5358.1  412.92  5418.2  415.86  5508.4  416.69  5611.2  421.39
#Mann= 7 ,-1 , 0
  4402.8      .1       0  4510.4     .15       0  4662.7      .1       0
    4800     .12       0  4890.8     .07       0  4895.5     .12       0
  5236.2     .05       0
Bank Sta=4890.8,4895.5
XS Rating Curve= 0 ,0
Exp/Cntr=0.3,0.1

Type RM Length L Ch R = 1 ,7585    ,729,729,729
BEGIN DESCRIPTION:
DUCK CREEK TRIB 32 13 3
END DESCRIPTION:
XS GIS Cut Line= 3
      3507263.73     10427931.58      3507040.21     10428356.92
       3506306.9     10428474.08
#Sta/Elev= 30
  4410.9  418.48    4487  416.49  4553.1  412.72  4571.5  413.12  4580.8  411.57
  4597.2   410.4  4613.6  411.25  4679.8  409.24  4693.4  407.22  4723.9  404.56
  4730.4  402.73  4745.9  402.17  4751.6  401.14    4768  401.89  4771.2     401
  4771.6   400.5  4775.9     401  4964.1     401  4991.5     401  5140.4     401
  5145.4  402.28    5173   404.8  5223.7  408.57  5269.6  411.82  5375.6  413.47
  5426.2  416.75  5460.9  417.62  5522.9  421.29  5626.6  424.21    5634  424.31
#Mann= 9 ,-1 , 0
  4410.9     .16       0  4571.5      .1       0  4730.4     .12       0
  4771.2     .07       0  4775.9     .12       0  4964.1     .05       0
  4991.5     .12       0  5223.7     .05       0  5626.6      .1       0
Bank Sta=4771.2,4775.9
XS Rating Curve= 0 ,0
Exp/Cntr=0.3,0.1

Type RM Length L Ch R = 1 ,6856    ,744,744,744
BEGIN DESCRIPTION:
DUCK CREEK TRIB 32 13 0
END DESCRIPTION:
XS GIS Cut Line= 4
      3507436.51     10427511.85      3507162.17     10427699.37
      3506238.56     10427997.98       3505707.3     10428491.04
#Sta/Elev= 30
  4070.6  424.73  4116.4  424.59  4167.2  422.49  4274.9  422.71  4310.8  421.83
  4367.7  418.45  4497.6  407.88    4588  402.03  4621.3     401  5062.6     401
  5094.2  400.89  5094.6  400.39    5099  400.89  5191.2  405.83  5233.2  406.93
  5302.9  410.84  5359.4   412.8  5387.8  413.46  5427.3  411.73  5451.3  410.15
  5472.8  410.56  5536.3  414.24  5557.8  416.66  5600.3  419.67  5711.3  423.39
  5826.6  430.25  5842.4  430.21  5946.8  432.84    6046  441.09  6098.4   443.2
#Mann= 8 ,-1 , 0
  4070.6     .16       0  4621.3     .05       0  5062.6     .16       0
  5094.2    .033       0    5099     .16       0  5427.3     .05       0
  5711.3      .1       0  5842.4     .05       0
Bank Sta=5094.2,5099
XS Rating Curve= 0 ,0
Exp/Cntr=0.3,0.1

Type RM Length L Ch R = 1 ,6112    ,727,727,727
BEGIN DESCRIPTION:
DUCK CREEK TRIB 32 42 0
END DESCRIPTION:
XS GIS Cut Line= 5
      3507738.53     10426789.66      3507245.51      10426907.7
      3506912.17     10427105.62      3505880.92     10427369.51
      3505561.73     10428247.28
#Sta/Elev= 30
  3540.4  423.23  3655.6  423.98  3880.2  423.06    3948  421.98  4119.5  415.81
  4254.8  415.52  4401.9  414.16  4486.7  409.39  4562.8  406.38  4651.9  401.35
  4692.7     401  5258.5  400.93  5258.8  400.43  5263.3  400.93  5291.8   404.4
  5319.8  406.14  5374.4     412  5415.7  414.83  5503.3   416.4  5650.7  414.66
  5812.8  418.53    6013  423.09  6038.3  424.34  6063.5  427.85  6076.4  428.54
  6155.3  428.57  6204.9  431.53  6286.8  433.87  6389.7  437.71  6433.5  439.41
#Mann= 12 ,-1 , 0
  3540.4     .05       0  3880.2     .16       0  4254.8     .05       0
  4562.8     .16       0  4692.7     .05       0  5258.5    .033       0
  5263.3     .05       0  5319.8     .16       0  5812.8      .1       0
  6204.9     .05       0  6286.8     .16       0  6389.7     .05       0
Bank Sta=5258.5,5263.3
XS Rating Curve= 0 ,0
Exp/Cntr=0.3,0.1

Type RM Length L Ch R = 1 ,5385    ,1027,1027,1027
BEGIN DESCRIPTION:
DUCK CREEK TRIB 32 8 0
END DESCRIPTION:
XS GIS Cut Line= 3
      3507339.22     10426220.21      3505995.51     10426616.04
      3505464.27     10428122.94
#Sta/Elev= 30
  3874.4  424.64  4002.5  414.84  4074.4  410.73  4107.7   407.3  4146.3  406.02
  4173.7  403.53  4225.2  402.21  4246.3     401    4340     401  5224.2  400.93
  5224.5  400.43  5229.1  400.93  5274.4  405.06    5366  410.62  5535.6  413.12
  5566.6  412.42  5684.1  414.52  5766.4  417.93  5821.9  419.45  5845.1  418.13
  5870.8  418.77  5932.7  416.81  5953.9  417.36    6144  413.89  6362.5  417.79
  6566.6  422.13  6592.2  424.29  6647.4  425.78  6852.7  433.64    6873  434.45
#Mann= 11 ,-1 , 0
  3874.4     .05       0  4225.2     .16       0    4340     .05       0
  5224.2    .033       0  5229.1     .05       0  5566.6     .16       0
  5766.4     .05       0  5953.9     .16       0  6362.5     .05       0
  6647.4     .16       0  6852.7     .05       0
Bank Sta=5224.2,5229.1
XS Rating Curve= 0 ,0
Exp/Cntr=0.3,0.1

Type RM Length L Ch R = 1 ,4358    ,693,693,693
BEGIN DESCRIPTION:
DUCK CREEK TRIB 32 7 0
END DESCRIPTION:
XS GIS Cut Line= 4
      3507630.92     10425414.65      3507328.84      10425407.7
      3504922.59      10425695.9      3503453.84     10426876.45
#Sta/Elev= 30
  3407.2  432.82    3476  430.29    3496  424.43    3516  422.51  3709.4  423.53
  3756.4  413.39    3975  400.87  3975.5  400.37  3981.1  400.87  5486.2  401.22
  5690.1  407.15  6013.1  413.31    6093  415.81    6238  417.67  6506.5  419.51
  6613.7  422.98  6627.1   425.7    6631  426.18  6642.5  427.83  6671.3  423.57
    6762  425.25  6962.5  428.99  6976.9  430.25  7032.9  429.46  7119.3  431.93
  7168.9  431.43  7332.1  434.12  7765.7  424.72  7858.5  424.62  8017.2  427.99
#Mann= 9 ,-1 , 0
  3407.2     .05       0    3975    .033       0  3981.1     .05       0
  5486.2     .16       0  6013.1     .05       0    6238      .1       0
  6627.1     .08       0    6631      .1       0    6762     .16       0
Bank Sta=3975,3981.1
XS Rating Curve= 0 ,0
Exp/Cntr=0.3,0.1

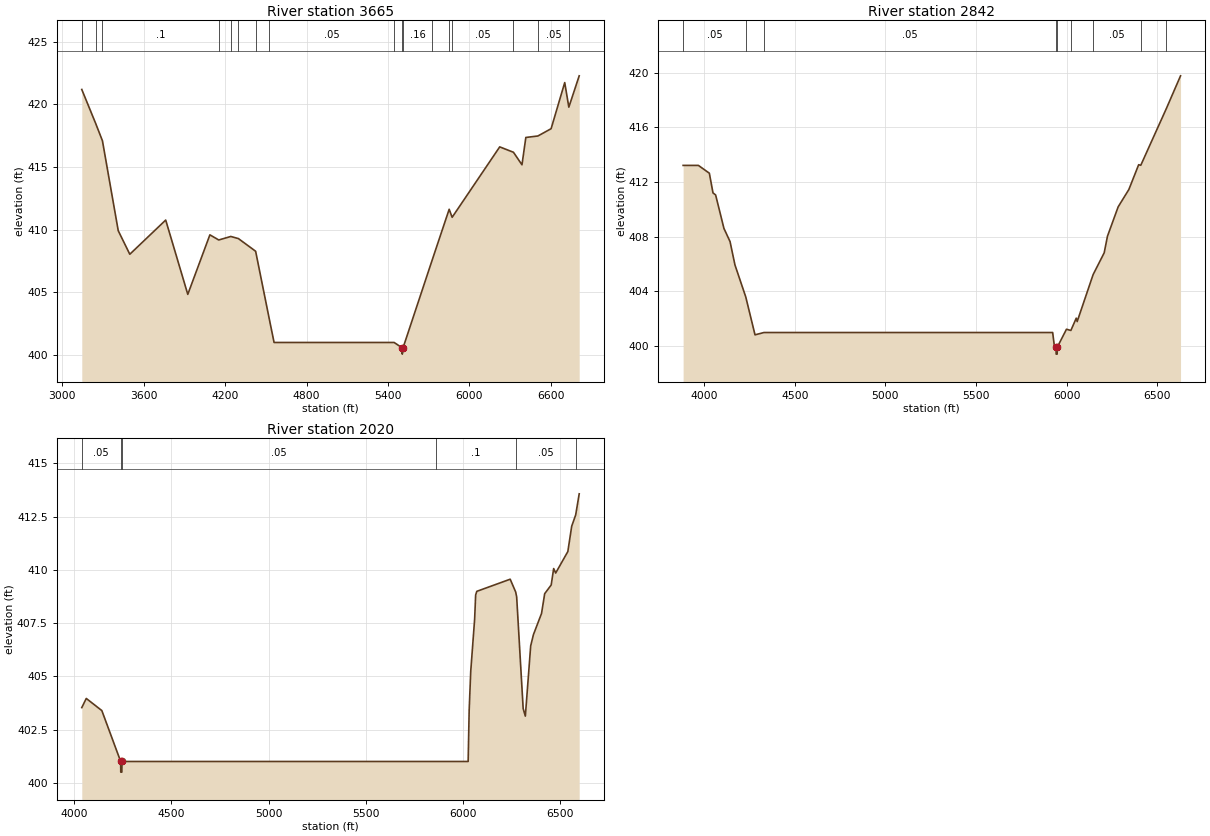
Type RM Length L Ch R = 1 ,3665    ,823,823,823
BEGIN DESCRIPTION:
DUCK CREEK TRIB 32 3 0
END DESCRIPTION:
XS GIS Cut Line= 4
      3507619.93     10424577.24      3505843.35     10424908.17
        3505396.     10425077.24      3504281.39     10425889.76
#Sta/Elev= 30
  3144.3  421.19  3246.6  418.48  3296.4   417.1  3412.9  409.92  3498.1  408.04
  3762.6  410.77  3925.3  404.84  4088.1  409.59  4153.4  409.18  4242.1  409.46
  4298.3  409.29  4425.1  408.28  4526.4  402.84    4561     401  5445.4     401
    5505  400.57  5505.5  400.07  5511.1  400.57    5725  407.55    5851  411.63
  5872.9  410.99  6223.4  416.61  6324.6  416.18  6387.4  415.18  6415.8  417.36
    6505  417.48    6602  418.06  6702.4  421.74  6732.6  419.78    6809  422.28
#Mann= 17 ,-1 , 0
  3144.3      .1       0  3246.6     .05       0  3296.4      .1       0
  4153.4     .05       0  4242.1      .1       0  4298.3     .05       0
  4425.1     .16       0  4526.4     .05       0  5445.4     .16       0
    5505    .033       0  5511.1     .16       0    5725     .08       0
    5851     .16       0  5872.9     .05       0  6324.6      .1       0
    6505     .05       0  6732.6     .16       0
Bank Sta=5505,5511.1
XS Rating Curve= 0 ,0
Exp/Cntr=0.3,0.1

Type RM Length L Ch R = 1 ,2842    ,822,822,822
BEGIN DESCRIPTION:
DUCK CREEK TRIB 32 5 0
END DESCRIPTION:
XS GIS Cut Line= 3
      3506635.58      10423993.9      3505864.75     10424092.86
      3503927.27     10424436.61
#Sta/Elev= 30
  3883.7  413.22  3967.9  413.22  4028.4  412.65  4048.5  411.21    4063  411.06
    4109  408.61  4142.6  407.65  4169.5  405.95  4229.4   403.6  4280.4  400.83
  4329.6     401  5922.9     401  5933.1  399.93  5941.9  399.92  5942.4  399.42
  5947.7  399.42  5948.2  399.92  5999.1  401.24  6023.4  401.15  6053.1  402.05
  6058.2   401.8    6146  405.23  6207.3  406.83  6225.3  408.04  6284.4  410.19
  6343.5  411.46  6397.5  413.27  6409.2  413.23  6550.4  417.38  6628.6  419.77
#Mann= 9 ,-1 , 0
  3883.7     .05       0  4229.4     .16       0  4329.6     .05       0
  5941.9    .033       0  5948.2     .05       0  6023.4      .1       0
    6146     .05       0  6409.2      .1       0  6550.4     .08       0
Bank Sta=5941.9,5948.2
XS Rating Curve= 0 ,0
Exp/Cntr=0.3,0.1

Type RM Length L Ch R = 1 ,2020    ,0,0,0
BEGIN DESCRIPTION:
DUCK CREEK TRIB 32 1 0
END DESCRIPTION:
XS GIS Cut Line= 3
      3506625.15      10423431.4      3505291.84     10423342.86
      3504115.91     10423686.27
#Sta/Elev= 30
  4038.5  403.53  4061.6  403.96  4141.8  403.39  4238.7     401  4239.2   400.5
  4244.8   400.5  4245.3     401  5864.4     401    6028     401  6033.2   403.4
  6041.2  405.22  6061.4  407.69  6066.6  408.82  6072.5  408.99  6244.4  409.56
  6272.7  408.96  6277.8  408.73  6311.3  403.48  6322.5  403.13    6350  406.43
  6364.2  406.96  6405.8  407.95  6422.1  408.88  6455.6  409.29  6468.3  410.06
  6478.7  409.85  6541.3  410.86  6561.2  412.05  6581.7  412.58  6599.8  413.57
#Mann= 6 ,-1 , 0
  4038.5     .05       0  4238.7    .033       0  4245.3     .05       0
  5864.4      .1       0  6272.7     .05       0  6581.7      .1       0
Bank Sta=4238.7,4245.3
XS Rating Curve= 0 ,0
Exp/Cntr=0.3,0.1

Chan Stop Cuts=-1
Use User Specified Reach Order=0
Composite Channel Slope=5