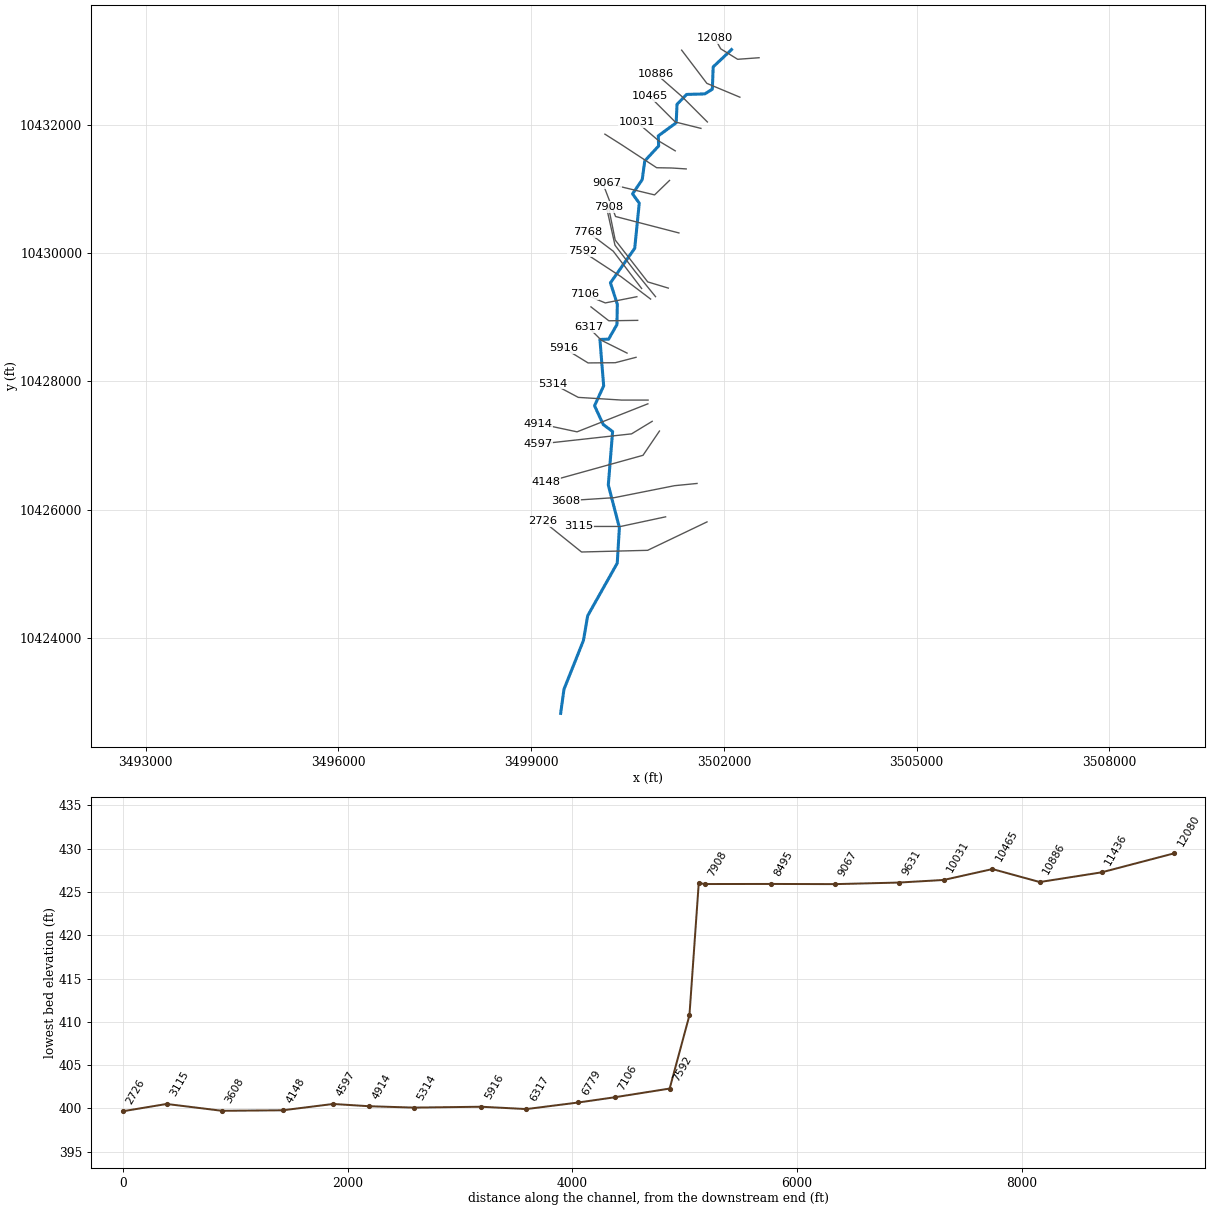
--- DUCK CREEK TRIB 34.prj (project) ---

Proj Title=DUCK CREEK TRIB 34 Base Level Engineering
Current Plan=p01
Default Exp/Contr=0.3,0.1
English Units
Geom File=g01
Flow File=f01
Plan File=p01
Y Axis Title=Elevation
X Axis Title(PF)=Main Channel Distance
X Axis Title(XS)=Station
BEGIN DESCRIPTION:
DUCK CREEK TRIB 34
END DESCRIPTION:
DSS Export Rating Curves= 0
DSS Export Rating Curve Sorted= 0
DSS Export Volume Flow Curves= 0
DXF OffsetX= 0
DXF OffsetY= 0
DXF ScaleX= 1
DXF ScaleY= 10

--- DUCK CREEK TRIB 34.p01 (plan) ---

Plan Title=Multiple Run
Short Identifier=Multiple
Geom File=g01
Flow File=f01
Subcritical Flow
K Sum by GR= 0
Std Step Tol= 0.01
Critical Tol= 0.01
Num of Std Step Trials= 20
Max Error Tol= 0.3
Flow Tol Ratio= 0.001
Split Flow NTrial= 30
Split Flow Tol= 0.02
Split Flow Ratio= 0.02
Log Output Level= 0
Friction Slope Method= 1
Unsteady Friction Slope Method= 2
Unsteady Bridges Friction Slope Method= 1
Parabolic Critical Depth
Global Vel Dist=  1 , 1 , 1
Global Log Level= 0
CheckData=True
Encroach Param= -1, 0, 0, 0
BEGIN DESCRIPTION:
Multiple Run
END DESCRIPTION:

--- DUCK CREEK TRIB 34.f01 (steady flow) ---

Flow Title=Multiple
Program Version=4.10
Number of Profiles= 7
Profile Names=10-year,25-year,50-year,1pct_min,100-year,1pct_plu,500-year
River Rch & RM=DUCK CREEK TRIB,Reach-1         ,12080
     965    1321    1613    1436    1942    2627    2809
River Rch & RM=DUCK CREEK TRIB,Reach-1         ,7768
    1241    1727    2132    1917    2593    3506    3827
River Rch & RM=DUCK CREEK TRIB,Reach-1         ,4148
    1377    1917    2366    2127    2877    3890    4243
Boundary for River Rch & Prof#=DUCK CREEK TRIB,Reach-1         , 1
Up Type= 0
Dn Type= 3
Dn Slope=0.005
Boundary for River Rch & Prof#=DUCK CREEK TRIB,Reach-1         , 2
Up Type= 0
Dn Type= 3
Dn Slope=0.005
Boundary for River Rch & Prof#=DUCK CREEK TRIB,Reach-1         , 3
Up Type= 0
Dn Type= 3
Dn Slope=0.005
Boundary for River Rch & Prof#=DUCK CREEK TRIB,Reach-1         , 4
Up Type= 0
Dn Type= 3
Dn Slope=0.005
Boundary for River Rch & Prof#=DUCK CREEK TRIB,Reach-1         , 5
Up Type= 0
Dn Type= 3
Dn Slope=0.005
Boundary for River Rch & Prof#=DUCK CREEK TRIB,Reach-1         , 6
Up Type= 0
Dn Type= 3
Dn Slope=0.005
Boundary for River Rch & Prof#=DUCK CREEK TRIB,Reach-1         , 7
Up Type= 0
Dn Type= 3
Dn Slope=0.005
DSS Import GetInterval= 0
DSS Import GetPeak= 0
DSS Import FillOption= 0

--- DUCK CREEK TRIB 34.g01 (geometry) ---

Geom Title=Existing Conditions
Program Version=4.10

River Reach=DUCK CREEK TRIB ,Reach-1
Reach XY= 30
      3502118.99     10433168.65      3501832.54     10432899.56
      3501819.51     10432552.33      3501702.33     10432478.55
      3501420.24     10432470.46       3501270.2     10432318.24
      3501256.54       10432029.      3500977.62     10431824.46
      3500983.93     10431668.36      3500767.48     10431434.04
      3500728.36     10431143.19      3500577.24     10430921.37
      3500682.09     10430777.07      3500611.51     10430074.01
      3500233.45     10429536.07      3500340.67     10429202.92
       3500334.6     10428885.21      3500204.39     10428658.64
      3500069.84      10428654.3        3500128.     10427931.21
      3499986.16     10427621.67      3500120.88       10427330.
      3500267.26     10427220.34      3500200.36     10426387.84
      3500373.01     10425723.45      3500339.17     10425169.32
      3499879.59     10424350.98      3499813.07     10423965.55
      3499510.35     10423205.95      3499458.63     10422830.39

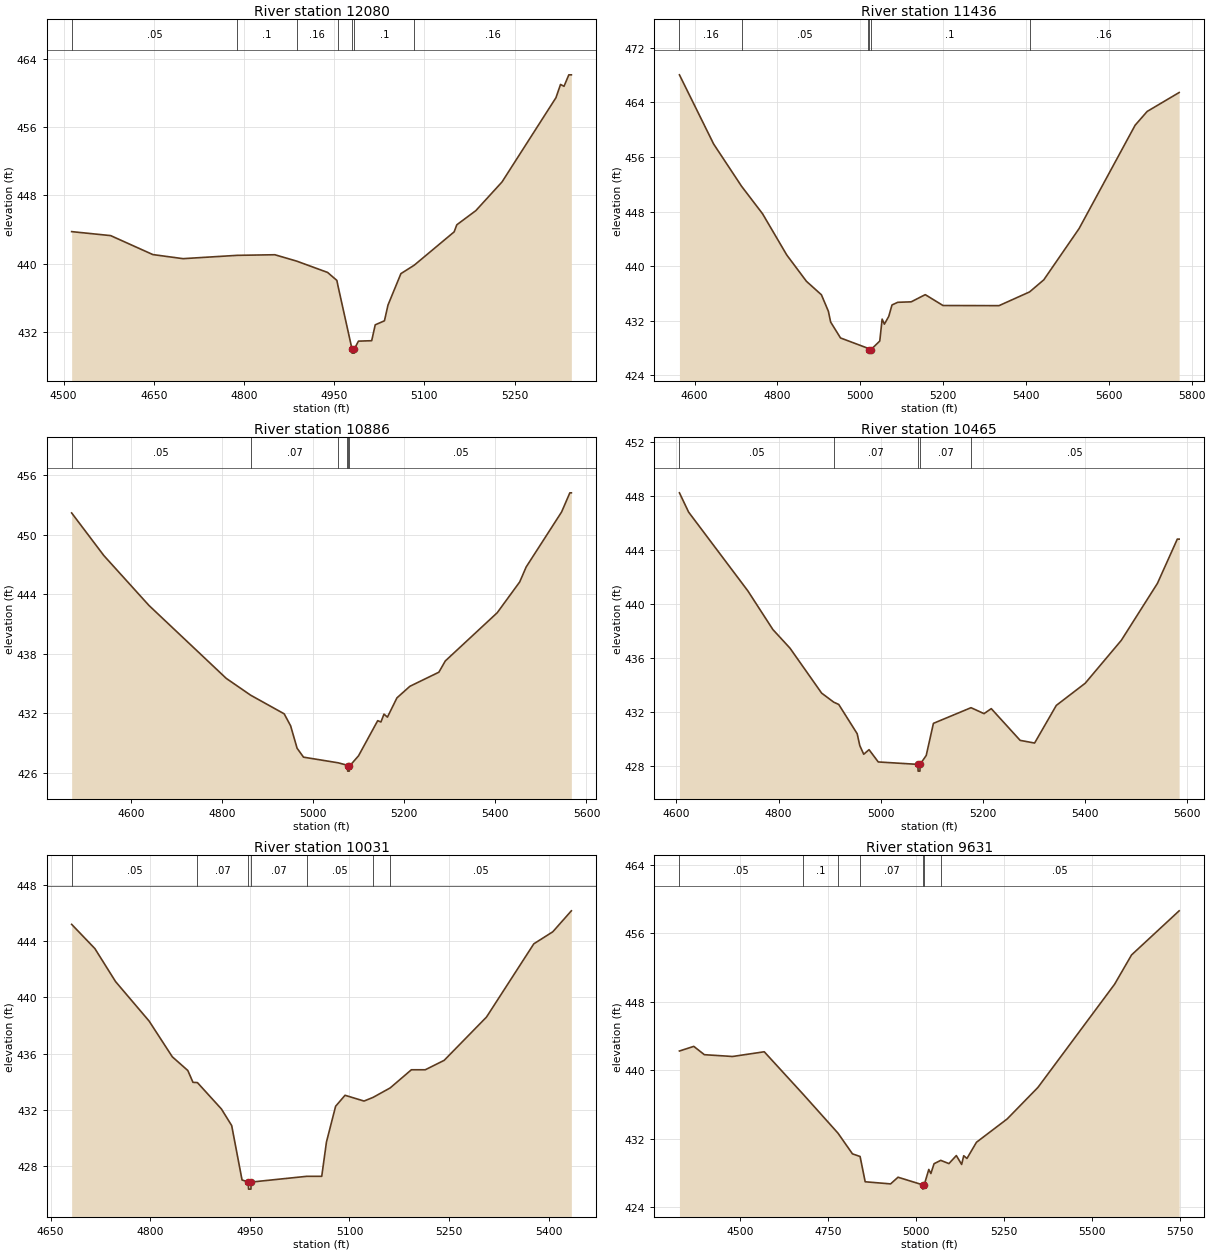
Type RM Length L Ch R = 1 ,12080   ,644,644,644
BEGIN DESCRIPTION:
DUCK CREEK TRIB 34 6 0
END DESCRIPTION:
XS GIS Cut Line= 4
      3502546.79     10433042.03       3502213.5     10433017.73
      3501949.62     10433180.92      3501859.36     10433344.08
#Sta/Elev= 30
  4513.5  443.75  4578.4  443.28  4648.5  441.05  4698.7  440.57  4788.7  440.96
  4851.4  441.03  4887.7  440.28  4939.1  438.95  4954.5  438.01  4956.2  437.42
  4979.6  429.96  4979.9  429.46  4983.4  429.46  4983.6  429.96  4990.4  430.87
  5012.4  430.92  5018.3  432.79  5033.6  433.26  5039.5  435.11    5061  438.81
  5083.1   439.8  5149.5  443.72  5153.9  444.55  5185.6  446.22  5229.1  449.59
  5318.8   459.5  5326.4  461.06  5332.2  460.84  5340.2  462.19  5344.4  462.19
#Mann= 7 ,-1 , 0
  4513.5     .05       0  4788.7      .1       0  4887.7     .16       0
  4956.2      .1       0  4979.6     .07       0  4983.6      .1       0
  5083.1     .16       0
Bank Sta=4979.6,4983.6
XS Rating Curve= 0 ,0
Exp/Cntr=0.3,0.1

Type RM Length L Ch R = 1 ,11436   ,550,550,550
BEGIN DESCRIPTION:
Mapping XS b3f6a198
END DESCRIPTION:
XS GIS Cut Line= 3
      3502248.25     10432427.44      3501734.34     10432642.73
      3501341.98     10433160.09
#Sta/Elev= 30
  4563.4  468.01    4646  457.88  4713.5  451.69  4764.1  447.67  4822.5  441.64
  4870.1  437.78  4906.2  435.81    4923   433.4  4928.5  431.82  4952.3  429.49
  5018.1  427.99  5021.6  427.77  5021.8  427.27  5025.6  427.77  5047.1  429.04
  5052.8  432.25  5058.2  431.51  5068.8  432.65  5076.6  434.32  5090.5  434.71
    5123  434.78  5156.9  435.83  5199.8  434.24    5335  434.22  5408.8  436.23
  5443.1     438  5528.4  445.51  5663.6  460.63  5692.7  462.65  5769.9  465.42
#Mann= 6 ,-1 , 0
  4563.4     .16       0  4713.5     .05       0  5018.1      .1       0
  5021.6    .035       0  5025.6      .1       0  5408.8     .16       0
Bank Sta=5021.6,5025.6
XS Rating Curve= 0 ,0
Exp/Cntr=0.3,0.1

Type RM Length L Ch R = 1 ,10886   ,421,421,421
BEGIN DESCRIPTION:
DUCK CREEK TRIB 34 6 0
END DESCRIPTION:
XS GIS Cut Line= 3
      3501742.11     10432041.64      3501342.11     10432441.64
      3500942.11     10432791.64
#Sta/Elev= 30
  4469.6   452.2  4540.3   447.9  4639.3  442.87    4809  435.51  4862.7  433.81
  4936.3  431.93  4950.4  430.72  4964.6  428.46  4978.7  427.56  5054.7  426.99
  5074.4  426.75  5075.5  426.65  5075.7  426.15  5079.3  426.15  5079.6  426.65
  5099.4  427.69  5141.6  431.24  5148.7  431.11  5155.4   431.9    5163   431.6
  5183.8  433.54  5212.3  434.71  5275.9  436.13  5290.1  437.27    5404  442.13
  5453.4  445.24  5467.6  446.75  5545.4   452.3  5563.5  454.23  5566.8  454.23
#Mann= 6 ,-1 , 0
  4469.6     .05       0  4862.7     .07       0  5054.7      .1       0
  5074.4     .05       0  5075.5     .07       0  5079.6     .05       0
Bank Sta=5075.5,5079.6
XS Rating Curve= 0 ,0
Exp/Cntr=0.3,0.1

Type RM Length L Ch R = 1 ,10465   ,434,434,434
BEGIN DESCRIPTION:
DUCK CREEK TRIB 34 5 0
END DESCRIPTION:
XS GIS Cut Line= 3
      3501642.08     10431941.65      3501242.11     10432041.64
      3500842.09     10432441.66
#Sta/Elev= 30
  4606.1  448.27  4624.1  446.84  4740.1     441    4789  438.14  4822.5  436.76
  4884.4  433.43  4908.1  432.76  4917.9  432.59    4954  430.42  4959.1  429.54
  4966.8   428.9  4977.2  429.24  4995.2  428.33  5072.9  428.15  5073.2  427.65
  5076.8  427.65    5077  428.15  5089.1  428.81  5103.2  431.19  5176.8  432.35
  5202.2  431.91  5216.4  432.28  5272.9  429.93  5301.2  429.73  5343.7  432.52
  5400.2  434.16  5470.9  437.34  5541.6  441.56  5580.5  444.84  5584.1  444.84
#Mann= 5 ,-1 , 0
  4606.1     .05       0  4908.1     .07       0  5072.9     .07       0
    5077     .07       0  5176.8     .05       0
Bank Sta=5072.9,5077
XS Rating Curve= 0 ,0
Exp/Cntr=0.3,0.1

Type RM Length L Ch R = 1 ,10031   ,400,400,400
BEGIN DESCRIPTION:
DUCK CREEK TRIB 34 22 0
END DESCRIPTION:
XS GIS Cut Line= 3
      3501242.11     10431591.64      3500992.11     10431741.64
      3500642.13     10432041.62
#Sta/Elev= 30
  4681.6  445.18  4716.6  443.46  4747.7  441.12  4798.2  438.32  4833.2  435.78
  4856.5  434.81  4864.3  433.97    4871  433.95  4907.1  432.08  4922.6   430.9
  4938.2  427.04  4947.7  426.89    4948  426.39  4951.6  426.39  4951.9  426.89
  5035.8   427.3  5058.2   427.3  5065.3  429.73  5079.1  432.27  5093.3  433.05
  5121.9  432.64  5135.5   432.9  5161.2  433.57  5193.2  434.86  5214.1  434.86
  5242.6  435.53  5306.3   438.6  5377.6   443.8  5406.1  444.65  5434.1  446.14
#Mann= 7 ,-1 , 0
  4681.6     .05       0    4871     .07       0  4947.7     .07       0
  4951.9     .07       0  5035.8     .05       0  5135.5      .1       0
  5161.2     .05       0
Bank Sta=4947.7,4951.9
XS Rating Curve= 0 ,0
Exp/Cntr=0.3,0.1

Type RM Length L Ch R = 1 ,9631    ,564,564,564
BEGIN DESCRIPTION:
DUCK CREEK TRIB 34 21 0
END DESCRIPTION:
XS GIS Cut Line= 5
      3501412.85     10431310.15      3501187.31     10431324.57
      3500952.94     10431328.91       3500410.4     10431684.81
      3500147.19     10431851.84
#Sta/Elev= 30
  4327.6  442.22  4368.4  442.76  4398.5  441.79  4478.7  441.58  4568.8  442.13
  4679.4  437.17  4778.4  432.63  4819.6  430.21  4841.3   429.9  4855.8  426.95
  4928.1   426.7  4949.2  427.48  5019.4  426.59  5019.7  426.09  5023.7  426.59
  5036.7  428.39  5042.6  427.91  5051.7  429.06  5070.7  429.45  5093.9  429.07
    5115  430.01  5130.1  428.97    5136  429.99  5145.2  429.67  5172.2  431.56
  5259.7  434.29  5347.1  437.97  5565.1  450.02  5613.3  453.44  5748.6  458.59
#Mann= 7 ,-1 , 0
  4327.6     .05       0  4679.4      .1       0  4778.4     .05       0
  4841.3     .07       0  5019.4     .07       0  5023.7     .07       0
  5070.7     .05       0
Bank Sta=5019.4,5023.7
XS Rating Curve= 0 ,0
Exp/Cntr=0.3,0.1

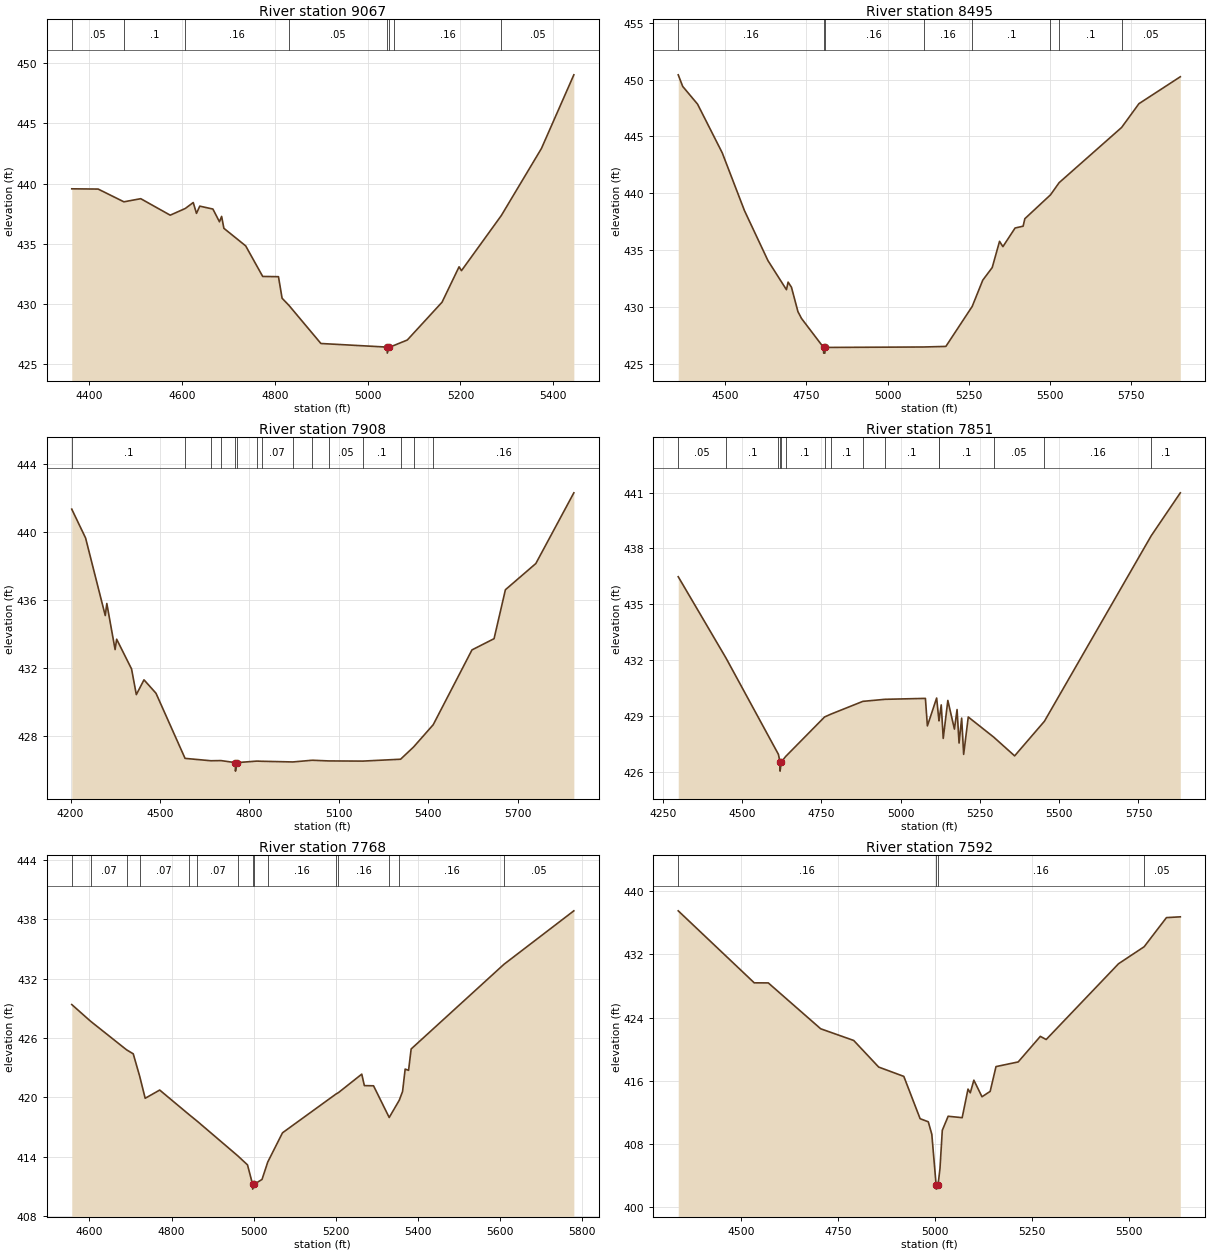
Type RM Length L Ch R = 1 ,9067    ,572,572,572
BEGIN DESCRIPTION:
Mapping XS 2bf35689
END DESCRIPTION:
XS GIS Cut Line= 3
      3501153.15     10431130.86       3500920.5     10430905.53
      3500183.08     10431084.03
#Sta/Elev= 30
  4361.9  439.56  4418.8  439.54  4474.3  438.48  4510.6  438.74  4574.2  437.37
  4606.8  437.93  4623.8  438.42  4630.8  437.52  4637.9  438.12  4666.2  437.88
  4680.4  436.82    4685  437.27  4689.9  436.28  4736.9  434.82  4773.6  432.28
  4807.6  432.26  4815.4  430.47  4829.9  429.89  4899.1  426.71    5042  426.41
  5042.3  425.91  5046.4  426.41  5057.4  426.56  5085.4     427  5160.3  430.14
    5197  433.08  5202.2  432.76  5288.1  437.34  5374.6  442.91  5444.5  449.03
#Mann= 8 ,-1 , 0
  4361.9     .05       0  4474.3      .1       0  4606.8     .16       0
  4829.9     .05       0    5042    .033       0  5046.4     .05       0
  5057.4     .16       0  5288.1     .05       0
Bank Sta=5042,5046.4
XS Rating Curve= 0 ,0
Exp/Cntr=0.3,0.1

Type RM Length L Ch R = 1 ,8495    ,587,587,587
BEGIN DESCRIPTION:
DUCK CREEK TRIB 34 20 0
END DESCRIPTION:
XS GIS Cut Line= 3
      3501299.46     10430312.94      3500313.28       10430569.
      3500124.53     10431060.62
#Sta/Elev= 30
  4355.7  450.42  4369.5   449.4  4415.2  447.84  4491.1  443.56  4559.6  438.47
  4631.9  434.07  4688.8  431.51  4693.9  432.18  4704.2  431.73  4724.2  429.58
  4735.2  428.98    4803  426.43  4803.3  425.93  4807.2  425.93  4807.6  426.43
  5111.1  426.47  5179.5  426.52  5260.6  430.04  5293.1  432.35  5322.2  433.46
  5344.8  435.77  5355.1   435.3  5392.6  436.94  5417.3   437.1  5422.7  437.76
  5501.6  439.86  5528.2  440.93  5720.6  445.79  5773.8  447.88  5901.2  450.25
#Mann= 8 ,-1 , 0
  4355.7     .16       0    4803    .033       0  4807.6     .16       0
  5111.1     .16       0  5260.6      .1       0  5501.6     .16       0
  5528.2      .1       0  5720.6     .05       0
Bank Sta=4803,4807.6
XS Rating Curve= 0 ,0
Exp/Cntr=0.3,0.1

Type RM Length L Ch R = 1 ,7908    ,57,57,57
BEGIN DESCRIPTION:
DUCK CREEK TRIB 34 18 0
END DESCRIPTION:
XS GIS Cut Line= 4
      3501134.14     10429454.05      3500813.68     10429550.63
      3500307.42      10430203.2      3500203.56     10430716.68
#Sta/Elev= 30
    4204  441.33  4250.4  439.63  4316.4  435.07  4321.6  435.78  4349.4  433.07
  4354.6  433.68  4404.6  431.93  4420.6  430.42  4446.3  431.29  4486.6   430.5
  4584.1  426.67    4671  426.53  4704.7  426.54  4752.8  426.42  4753.2  425.92
  4757.4  426.42  4825.2  426.51  4840.9   426.5  4945.7  426.46  5010.9  426.56
  5066.2  426.52  5180.8  426.51  5307.2  426.62  5350.8  427.34  5416.7  428.65
  5546.7  433.05  5620.8  433.71  5658.9  436.59  5760.9  438.13  5888.5  442.29
#Mann= 15 ,-1 , 0
    4204      .1       0  4584.1     .07       0    4671      .1       0
  4704.7     .07       0  4752.8    .033       0  4757.4     .07       0
  4825.2     .05       0  4840.9     .07       0  4945.7     .05       0
  5010.9      .1       0  5066.2     .05       0  5180.8      .1       0
  5307.2     .16       0  5350.8     .05       0  5416.7     .16       0
Bank Sta=4752.8,4757.4
XS Rating Curve= 0 ,0
Exp/Cntr=0.3,0.1

Type RM Length L Ch R = 1 ,7851    ,83,83,83
BEGIN DESCRIPTION:
Mapping XS 2e6f8fc1
END DESCRIPTION:
XS GIS Cut Line= 4
      3500935.15     10429320.88      3500620.54     10429708.65
       3500304.5     10430121.26      3500181.59     10430671.42
#Sta/Elev= 30
  4299.2  436.48  4450.1   432.1  4615.1  426.93  4619.8  426.53  4620.2  426.03
  4624.4  426.53    4638  426.82  4760.5  428.94    4780  429.09  4881.2  429.78
  4950.7  429.89  5078.4  429.94  5084.7  428.46  5113.8  429.96  5121.2  428.73
  5122.1  428.84  5128.3  429.59  5134.6  427.79  5149.1  429.83  5169.9  428.29
  5178.2  429.34  5184.5  427.54  5192.7  428.88    5199  426.93  5213.5  428.94
  5293.6  427.86  5359.7  426.85  5453.6  428.71  5790.2  438.68    5882  440.99
#Mann= 15 ,-1 , 0
  4299.2     .05       0  4450.1      .1       0  4615.1     .07       0
  4619.8     .07       0  4624.4     .07       0    4638      .1       0
  4760.5     .07       0    4780      .1       0  4881.2     .07       0
  4950.7      .1       0  5121.2     .05       0  5122.1      .1       0
  5293.6     .05       0  5453.6     .16       0  5790.2      .1       0
Bank Sta=4619.8,4624.4
XS Rating Curve= 0 ,0
Exp/Cntr=0.3,0.1

Type RM Length L Ch R = 1 ,7768    ,176,176,176
BEGIN DESCRIPTION:
DUCK CREEK TRIB 34 19 0
END DESCRIPTION:
XS GIS Cut Line= 3
      3500718.57     10429448.21       3500276.7     10430029.08
      3499882.26      10430327.1
#Sta/Elev= 30
  4556.8  429.39  4602.5  427.71  4690.3  424.82  4706.7  424.41  4722.3  422.16
  4735.8  419.92  4771.2  420.75    4842   418.3  4862.5  417.61  4961.7   414.1
  4985.3  413.19  4997.6  411.24  4997.9  410.74  5002.2  411.24  5020.7  411.72
  5034.7  413.48  5070.6  416.43  5201.1  420.35    5207  420.49  5263.9  422.36
  5270.2   421.2  5292.6  421.18  5330.8  417.98  5355.3  419.72  5363.4  420.61
  5369.7  422.87    5378  422.74  5384.3   424.9  5610.7  433.46    5781  438.86
#Mann= 15 ,-1 , 0
  4556.8     .16       0  4602.5     .07       0  4690.3     .16       0
  4722.3     .07       0    4842      .1       0  4862.5     .07       0
  4961.7      .1       0  4997.6     .07       0  5002.2      .1       0
  5034.7     .16       0  5201.1      .1       0    5207     .16       0
  5330.8     .05       0  5355.3     .16       0  5610.7     .05       0
Bank Sta=4997.6,5002.2
XS Rating Curve= 0 ,0
Exp/Cntr=0.3,0.1

Type RM Length L Ch R = 1 ,7592    ,486,486,486
BEGIN DESCRIPTION:
DUCK CREEK TRIB 34 17 0
END DESCRIPTION:
XS GIS Cut Line= 3
      3500858.61     10429283.21      3500400.27     10429630.44
      3499796.61     10430025.94
#Sta/Elev= 30
  4336.7  437.53    4533  428.41  4569.3   428.4  4704.6  422.59  4789.9  421.11
  4854.4  417.74  4919.3  416.56  4961.4   411.2  4982.5  410.81  4991.6  409.23
  5002.8  402.78  5003.1  402.28  5007.6  402.78  5012.7  404.89  5018.7  409.73
  5033.8  411.51    5070  411.33  5085.1  414.95    5091  414.48  5100.2  416.08
  5121.2  413.98  5142.3  414.66  5157.4   417.8  5214.7  418.39  5271.9  421.63
    5287  421.23  5473.9  430.83    5540  432.98  5597.6  436.67  5633.4  436.77
#Mann= 4 ,-1 , 0
  4336.7     .16       0  5002.8     .07       0  5007.6     .16       0
    5540     .05       0
Bank Sta=5002.8,5007.6
XS Rating Curve= 0 ,0
Exp/Cntr=0.3,0.1

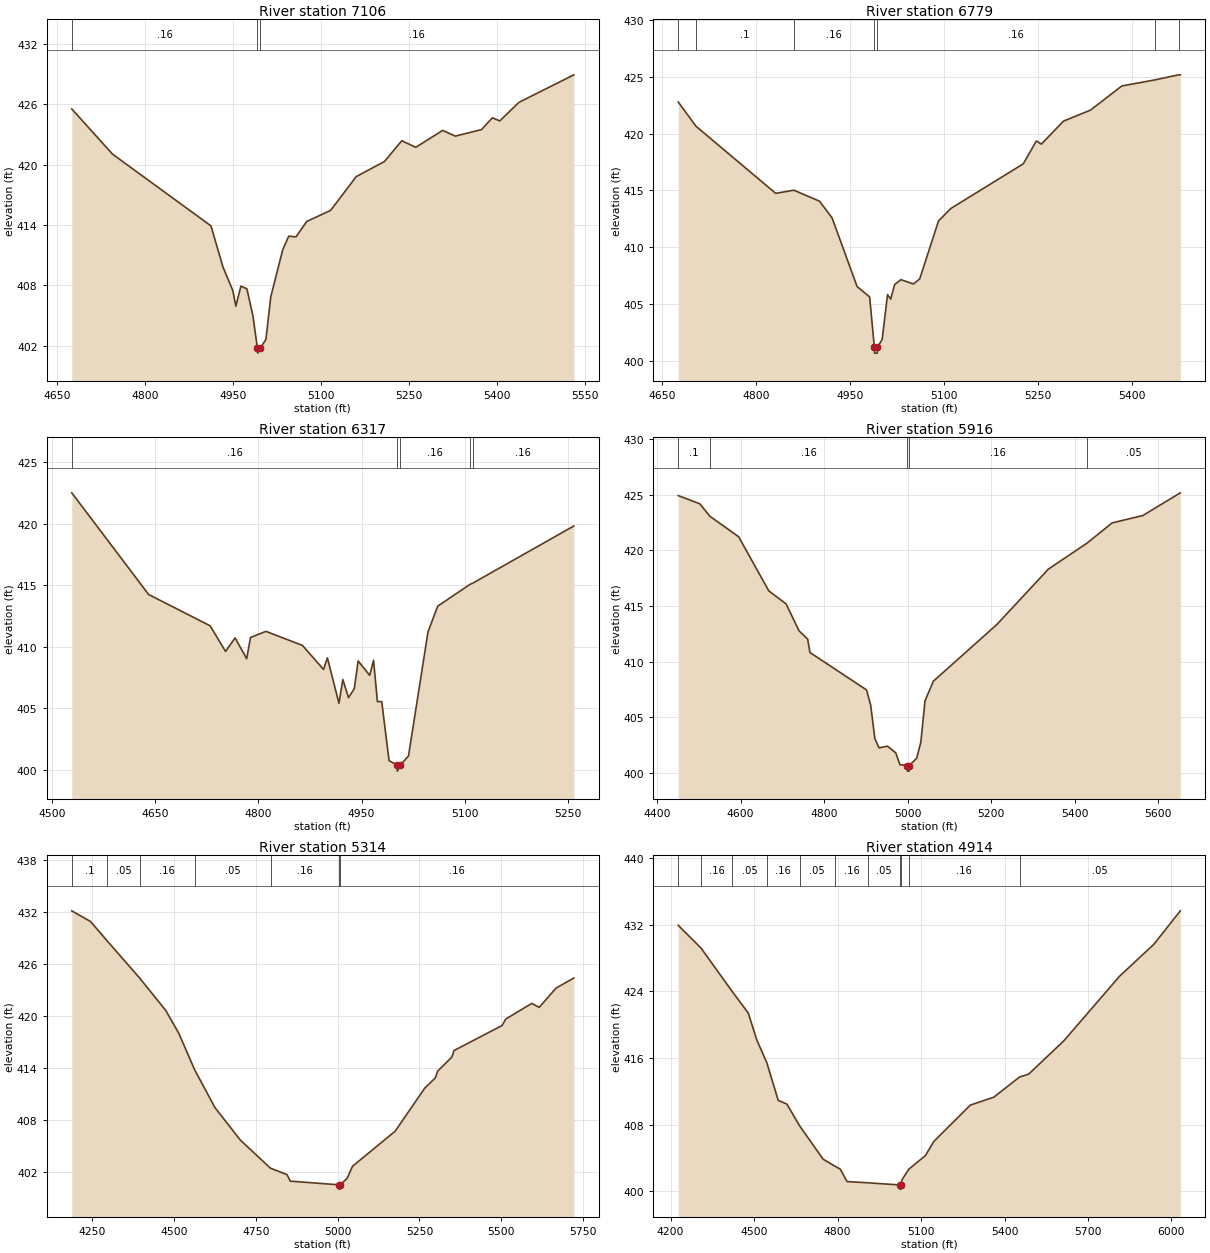
Type RM Length L Ch R = 1 ,7106    ,327,327,327
BEGIN DESCRIPTION:
DUCK CREEK TRIB 34 16 0
END DESCRIPTION:
XS GIS Cut Line= 3
      3500644.93     10429320.09      3500153.45     10429223.09
      3499825.43     10429358.15
#Sta/Elev= 30
  4675.1  425.54  4744.4  421.06  4912.4  413.92  4932.8  409.83  4949.6   407.5
  4954.7  405.94  4963.4  407.94  4973.6  407.66  4983.8     405  4991.5  401.78
  4991.9  401.28  4996.4  401.78    5006  402.64  5014.3  406.88  5034.7  411.56
  5044.9   412.9  5057.3  412.83  5075.5  414.36  5116.3  415.46  5159.9  418.82
  5208.1  420.32  5237.5  422.38  5261.4  421.73  5307.3  423.41  5328.9  422.84
  5373.4  423.49    5392  424.66  5404.6  424.35  5437.1  426.19  5530.8  428.93
#Mann= 3 ,-1 , 0
  4675.1     .16       0  4991.5     .07       0  4996.4     .16       0
Bank Sta=4991.5,4996.4
XS Rating Curve= 0 ,0
Exp/Cntr=0.3,0.1

Type RM Length L Ch R = 1 ,6779    ,462,462,462
BEGIN DESCRIPTION:
DUCK CREEK TRIB 34 15 0
END DESCRIPTION:
XS GIS Cut Line= 3
      3500657.78      10428951.5      3500208.41     10428945.04
      3499930.35     10429161.67
#Sta/Elev= 30
  4675.8  422.79  4704.2  420.65  4831.5  414.74  4860.4  415.02  4901.5  414.05
  4921.5  412.58  4961.5  406.53  4981.5  405.62  4989.1  401.17  4989.4  400.67
  4993.6  400.67    4994  401.17  5001.5  401.88  5010.1  405.82  5015.1  405.42
  5021.5  406.72  5031.5  407.14  5051.5  406.76  5061.5  407.21  5091.5  412.31
  5111.5  413.42  5226.9  417.34  5247.7  419.35  5255.8  419.08  5291.1   421.1
  5334.5  422.08  5384.3   424.2  5436.9  424.73  5475.1  425.18  5477.7  425.18
#Mann= 7 ,-1 , 0
  4675.8     .05       0  4704.2      .1       0  4860.4     .16       0
  4989.1     .07       0    4994     .16       0  5436.9     .05       0
  5475.1     .16       0
Bank Sta=4989.1,4994
XS Rating Curve= 0 ,0
Exp/Cntr=0.3,0.1

Type RM Length L Ch R = 1 ,6317    ,401,401,401
BEGIN DESCRIPTION:
DUCK CREEK TRIB 34 14 0
END DESCRIPTION:
XS GIS Cut Line= 3
      3500492.07     10428441.66      3500092.11     10428641.64
      3499892.11     10428841.63
#Sta/Elev= 30
  4528.6  422.49  4640.4  414.24  4729.8   411.7  4752.2  409.62  4766.1  410.72
  4782.9  409.03  4788.5  410.75  4810.9  411.25    4864  410.11  4894.7  408.16
  4900.3   409.1  4917.1  405.42  4922.7  407.34    4931  405.87  4939.4   406.6
    4945  408.85  4961.8  407.68  4967.4   408.9    4973  405.55  4979.3  405.55
  4989.9  400.76  5001.6  400.41    5002  399.91  5006.5  400.41  5018.2  401.14
  5046.5  411.19  5060.6  413.29  5107.8  415.07  5111.3  415.15  5258.6   419.8
#Mann= 5 ,-1 , 0
  4528.6     .16       0  5001.6     .07       0  5006.5     .16       0
  5107.8     .05       0  5111.3     .16       0
Bank Sta=5001.6,5006.5
XS Rating Curve= 0 ,0
Exp/Cntr=0.3,0.1

Type RM Length L Ch R = 1 ,5916    ,602,602,602
BEGIN DESCRIPTION:
DUCK CREEK TRIB 34 13 0
END DESCRIPTION:
XS GIS Cut Line= 4
      3500631.97     10428376.01      3500308.64     10428291.94
       3499885.1     10428288.71      3499506.99     10428521.39
#Sta/Elev= 30
  4450.8  424.91  4502.3  424.18  4526.8  423.05  4595.3  421.22  4667.6  416.36
    4709  415.19    4740  412.77  4760.6  412.03    4766  410.83  4901.4  407.47
  4911.4   406.1  4921.4   403.1  4931.4  402.27  4951.4  402.42  4971.4  401.82
  4981.4  400.76  4998.9  400.68  4999.3  400.18  5003.5  400.18  5003.9  400.68
  5021.4  401.34  5031.4  402.77  5041.4  406.49  5061.4  408.25  5213.1  413.33
  5336.6  418.31    5429  420.64  5489.3  422.46  5562.7  423.12  5652.4  425.16
#Mann= 5 ,-1 , 0
  4450.8      .1       0  4526.8     .16       0  4998.9     .07       0
  5003.9     .16       0    5429     .05       0
Bank Sta=4998.9,5003.9
XS Rating Curve= 0 ,0
Exp/Cntr=0.3,0.1

Type RM Length L Ch R = 1 ,5314    ,400,400,400
BEGIN DESCRIPTION:
DUCK CREEK TRIB 34 12 0
END DESCRIPTION:
XS GIS Cut Line= 4
      3500819.53     10427709.98      3500408.87     10427709.98
      3499733.14     10427752.01      3499338.72     10427962.15
#Sta/Elev= 30
  4187.2  432.16  4244.6  430.93  4295.6  428.69  4394.5  424.42  4474.6  420.67
  4514.6  418.02  4562.9  413.83  4624.7  409.49  4702.5  405.73  4794.7  402.49
  4845.1  401.75  4855.1     401  5002.8  400.58  5003.2  400.08  5007.6  400.08
    5008  400.58  5028.9  401.33  5045.5  402.72  5175.7  406.76  5265.9  411.71
  5298.7  412.92  5305.2  413.67  5349.1  415.31  5355.4  416.05  5502.9  418.95
  5513.5  419.68  5593.3  421.49    5616  421.03  5667.3  423.25  5721.8  424.42
#Mann= 7 ,-1 , 0
  4187.2      .1       0  4295.6     .05       0  4394.5     .16       0
  4562.9     .05       0  4794.7     .16       0  5002.8     .07       0
    5008     .16       0
Bank Sta=5002.8,5008
XS Rating Curve= 0 ,0
Exp/Cntr=0.3,0.1

Type RM Length L Ch R = 1 ,4914    ,317,317,317
BEGIN DESCRIPTION:
DUCK CREEK TRIB 34 11 0
END DESCRIPTION:
XS GIS Cut Line= 3
      3500816.24     10427651.78      3499713.74      10427215.3
      3499109.17     10427344.62
#Sta/Elev= 30
  4227.7  431.93  4309.5   429.2  4421.5  423.99  4479.5  421.38  4509.9  418.17
  4545.9  415.43  4587.1  410.89    4618  410.46  4663.5  407.86  4748.4  403.83
  4790.6     403  4809.9  402.64  4834.2  401.15  4909.6     401  5023.4  400.74
  5023.8  400.24  5028.3  400.24  5028.7  400.74  5031.4  401.35  5056.2  402.64
  5115.2  404.25  5146.3  405.98  5277.4  410.34  5361.4  411.28  5454.1  413.71
  5486.7  414.05  5612.8  418.04  5813.9  425.83  5936.7  429.65  6031.7  433.67
#Mann= 11 ,-1 , 0
  4227.7      .1       0  4309.5     .16       0  4421.5     .05       0
  4545.9     .16       0  4663.5     .05       0  4790.6     .16       0
  4909.6     .05       0  5023.4    .033       0  5028.7     .05       0
  5056.2     .16       0  5454.1     .05       0
Bank Sta=5023.4,5028.7
XS Rating Curve= 0 ,0
Exp/Cntr=0.3,0.1

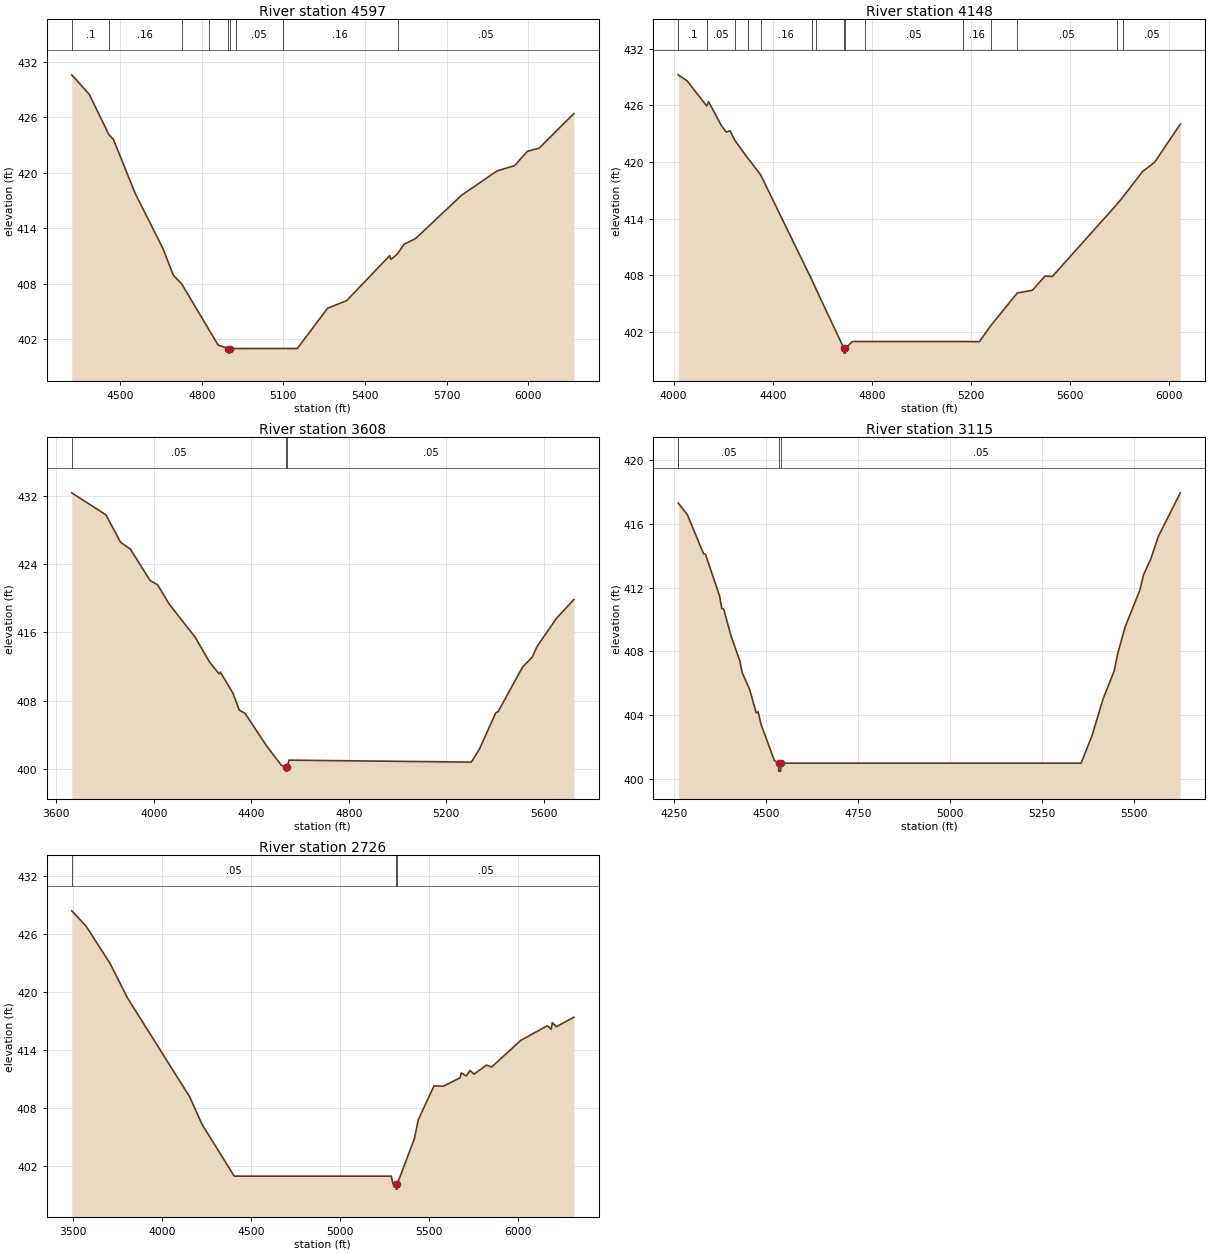
Type RM Length L Ch R = 1 ,4597    ,449,449,449
BEGIN DESCRIPTION:
DUCK CREEK TRIB 34 10
END DESCRIPTION:
XS GIS Cut Line= 3
      3500883.46     10427379.24      3500562.31     10427183.94
      3499102.38     10427022.47
#Sta/Elev= 30
  4322.5  430.57  4386.8  428.46    4459  424.11  4475.9  423.57  4555.4  417.77
  4656.2  411.89  4695.8  408.92  4726.4  407.98  4825.4  403.09  4860.2  401.37
  4897.1     401  4897.5   400.5    4902   400.5  4902.4     401  4924.4     401
  5096.8     401  5151.3     401    5262  405.34  5332.4  406.17  5490.4  411.03
  5495.5  410.62  5519.5  411.24  5543.7  412.26  5586.2  412.89    5755  417.57
  5885.8   420.2  5949.3  420.75  5996.4  422.31    6040  422.65  6167.2  426.38
#Mann= 9 ,-1 , 0
  4322.5      .1       0    4459     .16       0  4726.4     .05       0
  4825.4     .16       0  4897.1    .033       0  4902.4     .16       0
  4924.4     .05       0  5096.8     .16       0  5519.5     .05       0
Bank Sta=4897.1,4902.4
XS Rating Curve= 0 ,0
Exp/Cntr=0.3,0.1

Type RM Length L Ch R = 1 ,4148    ,540,540,540
BEGIN DESCRIPTION:
DUCK CREEK TRIB 34 9 0
END DESCRIPTION:
XS GIS Cut Line= 3
      3500996.37     10427227.39      3500740.26     10426849.74
      3499226.34     10426428.97
#Sta/Elev= 30
  4018.4  429.23  4054.1   428.6  4133.6  425.93    4141  426.39  4191.9  423.89
  4212.8  423.16  4227.8  423.31  4247.4  422.28  4299.9  420.39  4350.7  418.67
  4558.6  407.49  4576.2  406.48  4687.6  400.27  4688.1  399.77  4693.3  399.77
  4693.8  400.27  4721.9     401  4773.9     401  5167.4     401  5234.4  400.98
  5281.2   402.7  5387.7  406.14  5448.4  406.42  5500.3  407.94  5529.1  407.88
  5788.5  415.48  5815.3  416.33  5894.7  419.03    5942  419.96    6046  424.02
#Mann= 15 ,-1 , 0
  4018.4      .1       0  4133.6     .05       0  4247.4     .16       0
  4299.9     .05       0  4350.7     .16       0  4558.6     .05       0
  4576.2     .16       0  4687.6    .033       0  4693.8     .16       0
  4773.9     .05       0  5167.4     .16       0  5281.2      .1       0
  5387.7     .05       0  5788.5      .1       0  5815.3     .05       0
Bank Sta=4687.6,4693.8
XS Rating Curve= 0 ,0
Exp/Cntr=0.3,0.1

Type RM Length L Ch R = 1 ,3608    ,493,493,493
BEGIN DESCRIPTION:
DUCK CREEK TRIB 34 8 0
END DESCRIPTION:
XS GIS Cut Line= 4
      3501581.55     10426411.36      3501230.72     10426376.65
      3500293.22     10426190.02      3499542.12     10426141.64
#Sta/Elev= 30
  3663.1   432.4  3803.2  429.82  3863.5  426.59  3903.7  425.79  3984.1  422.12
  4015.6  421.59  4063.5  419.31  4170.8   415.4  4228.4  412.54  4267.9  411.13
    4273  411.34  4324.1  408.91  4350.7  406.89  4375.2  406.47  4462.9  402.67
  4523.4   400.4  4541.3  400.21  4541.8  399.71    4547  399.71  4547.5  400.21
  4554.6     401  5303.3  400.77  5336.8  402.31  5403.5  406.55  5413.6  406.71
  5513.8  411.93  5553.9  413.13  5573.9  414.39  5654.1   417.7  5724.2  419.86
#Mann= 3 ,-1 , 0
  3663.1     .05       0  4541.3    .033       0  4547.5     .05       0
Bank Sta=4541.3,4547.5
XS Rating Curve= 0 ,0
Exp/Cntr=0.3,0.1

Type RM Length L Ch R = 1 ,3115    ,389,389,389
BEGIN DESCRIPTION:
DUCK CREEK TRIB 34 7 0
END DESCRIPTION:
XS GIS Cut Line= 3
      3501092.12     10425891.64      3500392.11     10425741.64
      3499742.11     10425741.64
#Sta/Elev= 30
  4260.8  417.29  4285.5  416.57  4329.8  414.11    4335  414.08  4373.3  411.47
  4379.3  410.68  4384.4  410.65    4404     409  4428.7  407.38  4434.7  406.68
  4455.1  405.61    4473  404.15  4478.1  404.21  4485.8  403.45  4522.5  401.16
  4533.8     401  4534.3   400.5  4539.5   400.5    4540     401  5356.7     401
  5386.7  402.73  5416.7  405.03  5446.7  406.77  5456.7  407.89  5476.7  409.54
  5516.7  411.84  5526.7   412.8  5546.7   413.8  5566.7  415.19  5626.7  417.93
#Mann= 3 ,-1 , 0
  4260.8     .05       0  4533.8    .033       0    4540     .05       0
Bank Sta=4533.8,4540
XS Rating Curve= 0 ,0
Exp/Cntr=0.3,0.1

Type RM Length L Ch R = 1 ,2726    ,0,0,0
BEGIN DESCRIPTION:
DUCK CREEK TRIB 34 1 0
END DESCRIPTION:
XS GIS Cut Line= 4
      3501736.56     10425812.59      3500812.09     10425369.89
      3499783.45     10425343.85      3499185.77     10425824.59
#Sta/Elev= 30
  3494.5   428.4  3574.6  426.83  3710.1  422.95  3806.8  419.43  4157.9  409.16
  4225.8  406.37  4407.2     401  5289.7     401  5299.7  400.19  5316.6  400.16
  5317.1  399.66  5322.4  399.66  5322.9  400.16  5419.8  404.88  5441.4  406.82
  5529.8  410.32  5583.6   410.3  5676.3  411.16  5682.8  411.66  5711.6  411.35
  5732.4  411.92  5754.7  411.54  5825.1  412.47  5853.9  412.27  6017.1  415.02
  6166.2  416.53  6188.3  416.17  6194.7  416.85  6217.1  416.43  6315.5  417.41
#Mann= 3 ,-1 , 0
  3494.5     .05       0  5316.6    .033       0  5322.9     .05       0
Bank Sta=5316.6,5322.9
XS Rating Curve= 0 ,0
Exp/Cntr=0.3,0.1

Chan Stop Cuts=-1
Use User Specified Reach Order=0
Composite Channel Slope=5