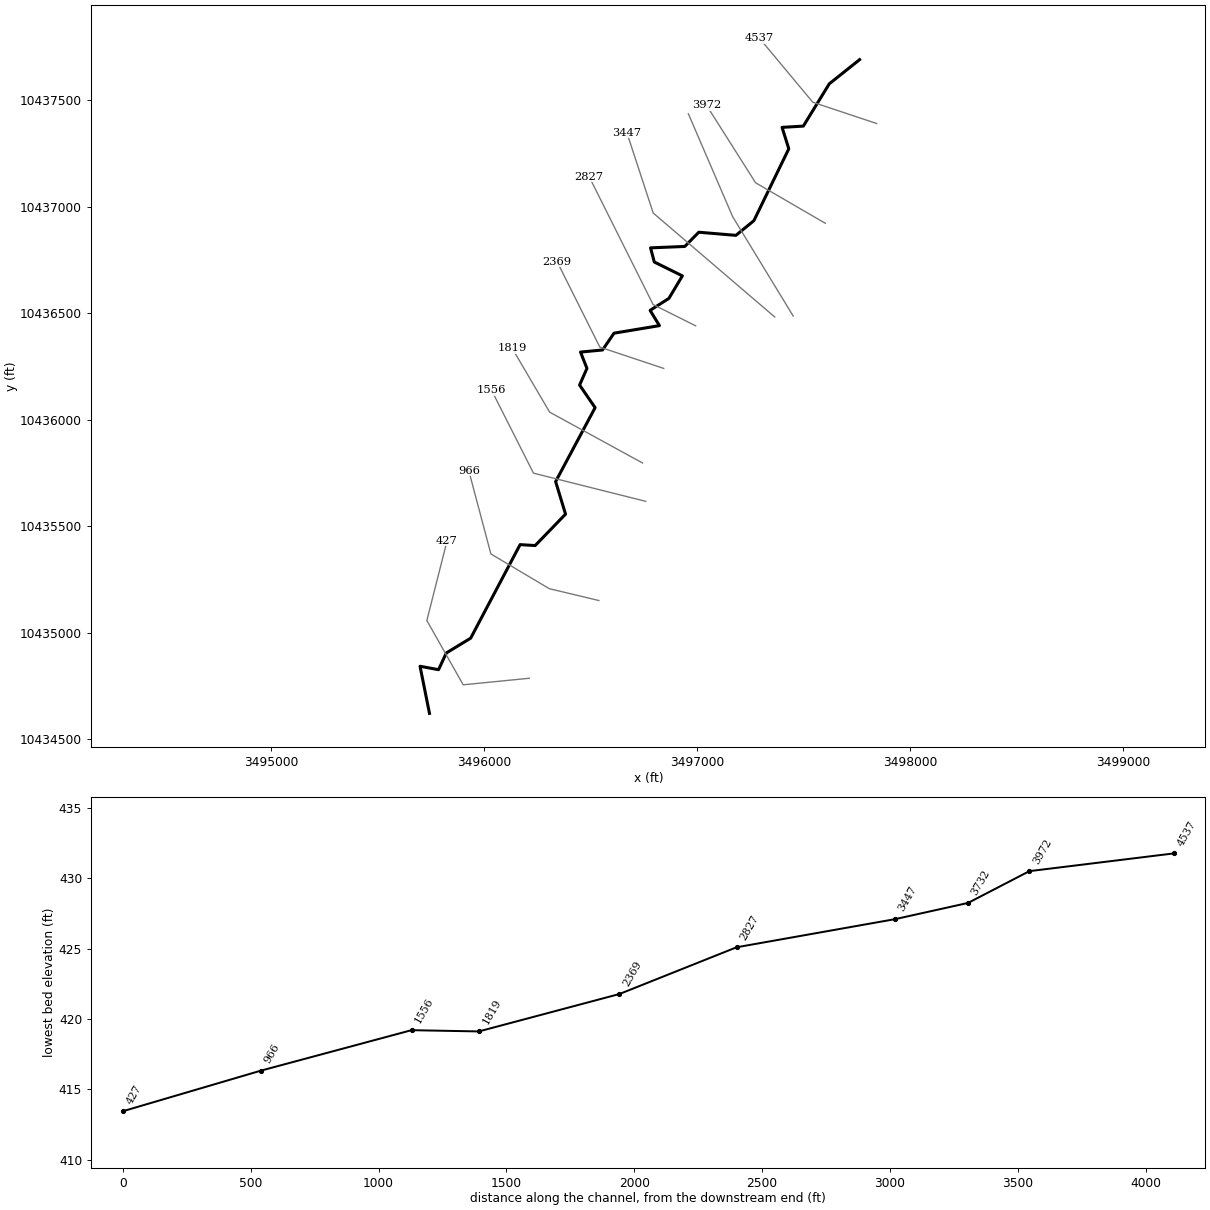
--- DUCK CREEK TRIB 40 2.prj (project) ---

Proj Title=DUCK CREEK TRIB 40 2 Base Level Engineering
Current Plan=p01
Default Exp/Contr=0.3,0.1
English Units
Geom File=g01
Flow File=f01
Plan File=p01
BEGIN DESCRIPTION:
DUCK CREEK TRIB 40 2
END DESCRIPTION:

--- DUCK CREEK TRIB 40 2.p01 (plan) ---

Plan Title=Multiple Run
Short Identifier=Multiple
Geom File=g01
Flow File=f01
Subcritical Flow
K Sum by GR= 0
Std Step Tol= 0.01
Critical Tol= 0.01
Num of Std Step Trials= 20
Max Error Tol= 0.3
Flow Tol Ratio= 0.001
Split Flow NTrial= 30
Split Flow Tol= 0.02
Split Flow Ratio= 0.02
Log Output Level= 0
Friction Slope Method= 1
Unsteady Friction Slope Method= 2
Unsteady Bridges Friction Slope Method= 1
Parabolic Critical Depth
Global Vel Dist=  1 , 1 , 1
Global Log Level= 0
CheckData=True
Encroach Param= -1, 0, 0, 0
BEGIN DESCRIPTION:
Multiple Run
END DESCRIPTION:

--- DUCK CREEK TRIB 40 2.f01 (steady flow) ---

Flow Title=Multiple
Number of Profiles=7
Profile Names=10-year,25-year,50-year,1pct_min,100-year,1pct_plu,500-year
River Rch & RM= DUCK CREEK TRIB ,Reach-1,4537
     713     967    1175    1043    1410    1907    2025
Boundary for River Rch & Prof#=DUCK CREEK TRIB ,Reach-1,1
Up Type=0
Dn Type=3
Dn Slope=0.005
Boundary for River Rch & Prof#=DUCK CREEK TRIB ,Reach-1,2
Up Type=0
Dn Type=3
Dn Slope=0.005
Boundary for River Rch & Prof#=DUCK CREEK TRIB ,Reach-1,3
Up Type=0
Dn Type=3
Dn Slope=0.005
Boundary for River Rch & Prof#=DUCK CREEK TRIB ,Reach-1,4
Up Type=0
Dn Type=3
Dn Slope=0.005
Boundary for River Rch & Prof#=DUCK CREEK TRIB ,Reach-1,5
Up Type=0
Dn Type=3
Dn Slope=0.005
Boundary for River Rch & Prof#=DUCK CREEK TRIB ,Reach-1,6
Up Type=0
Dn Type=3
Dn Slope=0.005
Boundary for River Rch & Prof#=DUCK CREEK TRIB ,Reach-1,7
Up Type=0
Dn Type=3
Dn Slope=0.005

--- DUCK CREEK TRIB 40 2.g01 (geometry) ---

Geom Title=Existing Conditions

River Reach=DUCK CREEK TRIB ,Reach-1
Reach XY= 30
      3497762.11     10437691.64      3497619.63     10437578.16
      3497497.75     10437379.46      3497397.91     10437373.58
      3497429.45     10437272.97      3497265.50     10436935.26
      3497181.11     10436866.41      3497006.77     10436881.14
      3496941.04     10436814.33      3496780.28     10436807.78
      3496797.88     10436741.32      3496929.67     10436676.15
      3496866.49     10436570.45      3496778.20     10436514.15
      3496821.99     10436442.52      3496608.76     10436407.08
      3496554.77     10436328.13      3496451.47     10436318.39
      3496481.58     10436241.72      3496447.08     10436163.46
      3496519.91     10436057.27      3496334.52     10435710.16
      3496381.11     10435557.21      3496238.40     10435409.73
      3496167.67     10435414.07      3495935.57     10434974.81
      3495821.19     10434905.30      3495784.71     10434826.78
      3495697.79     10434842.90      3495742.11     10434621.64

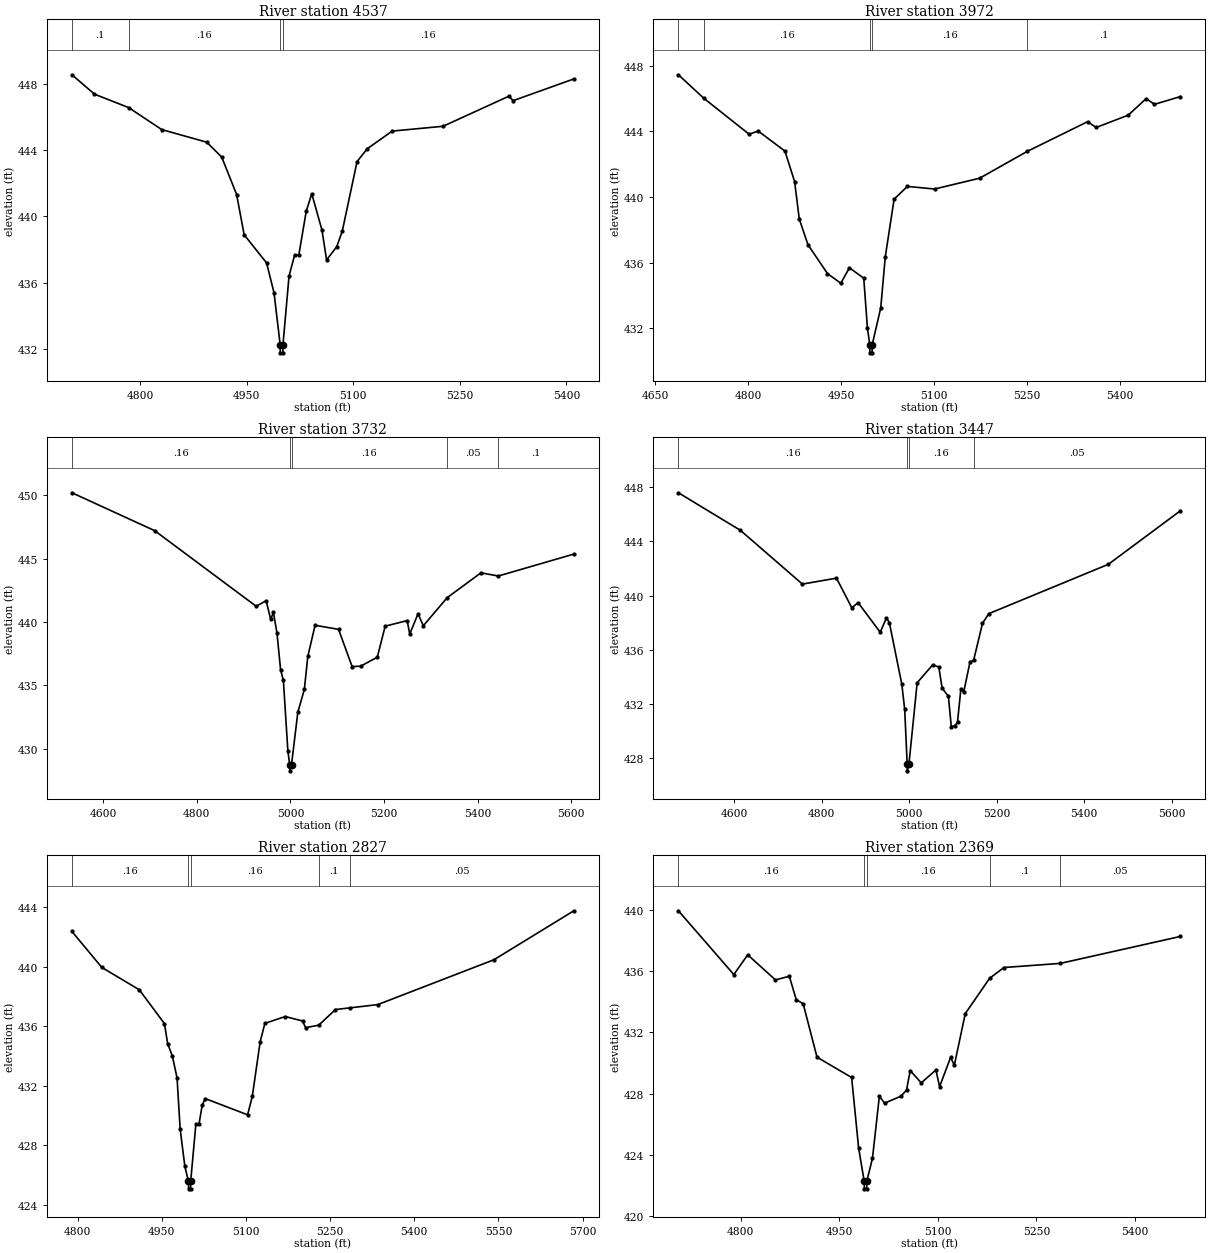
Type RM Length L Ch R = 1,4537,565,565,565
BEGIN DESCRIPTION:
DUCK CREEK TRIB 40 2 20 0
END DESCRIPTION:
XS GIS Cut Line= 3
      3497842.14     10437391.63      3497542.11     10437491.64
      3497292.09     10437791.66
#Sta/Elev= 30
  4703.8  448.55  4735.5  447.38  4783.6  446.57  4830.3  445.24  4893.6  444.48
  4914.7  443.58  4935.7  441.32  4946.3  438.89  4977.9  437.19  4988.4  435.38
  4997.0  432.26  4997.2  431.76  5000.7  431.76  5001.0  432.26  5009.5  436.39
  5017.4  437.67  5023.3  437.67  5033.7  440.30  5041.5  441.37  5055.9  439.17
  5062.4  437.37  5076.7  438.17  5084.5  439.11  5105.3  443.31  5119.6  444.08
  5154.8  445.15  5226.4  445.44  5318.8  447.25  5325.3  446.99  5410.6  448.30
#Mann=4,-1,0
  4703.8     0.1       0  4783.6    0.16       0  4997.0    0.07       0
  5001.0    0.16       0
Bank Sta=4997,5001
Exp/Cntr=0.3,0.1

Type RM Length L Ch R = 1,3972,240,240,240
BEGIN DESCRIPTION:
DUCK CREEK TRIB 40 2 20 1
END DESCRIPTION:
XS GIS Cut Line= 3
      3497600.78     10436923.21      3497273.56     10437113.38
      3497042.45     10437478.16
#Sta/Elev= 30
  4687.7  447.44  4729.0  446.00  4801.8  443.82  4816.6  444.01  4859.7  442.79
  4875.3  440.93  4882.8  438.66  4896.8  437.09  4928.3  435.33  4949.8  434.74
  4963.8  435.68  4986.9  435.05  4992.9  432.00  4996.6  431.00  4996.9  430.50
  5000.4  430.50  5000.6  431.00  5014.4  433.25  5021.6  436.33  5035.9  439.86
  5057.4  440.64  5101.2  440.48  5174.1  441.14  5250.7  442.77  5348.2  444.58
  5362.2  444.23  5413.9  444.98  5442.9  445.99  5456.3  445.64  5498.0  446.11
#Mann=5,-1,0
  4687.7    0.05       0  4729.0    0.16       0  4996.6    0.07       0
  5000.6    0.16       0  5250.7     0.1       0
Bank Sta=4996.6,5000.6
Exp/Cntr=0.3,0.1

Type RM Length L Ch R = 1,3732,285,285,285
BEGIN DESCRIPTION:
DUCK CREEK TRIB 40 2 8 0
END DESCRIPTION:
XS GIS Cut Line= 3
      3497450.16     10436487.54      3497165.86     10436954.14
      3496957.83     10437437.37
#Sta/Elev= 30
  4533.2  450.19  4709.9  447.20  4926.9  441.23  4948.2  441.67  4957.8  440.20
  4963.7  440.74  4971.3  439.12  4979.1  436.20  4985.0  435.38  4994.6  429.81
  4998.4  428.74  4998.7  428.24  5002.4  428.74  5015.9  432.87  5029.8  434.67
  5037.2  437.27  5052.7  439.73  5102.9  439.41  5131.9  436.47  5150.0  436.50
  5185.7  437.21  5202.5  439.66  5249.5  440.10  5255.0  439.04  5272.8  440.64
  5284.0  439.69  5335.0  441.91  5407.1  443.87  5444.3  443.62  5605.7  445.35
#Mann=5,-1,0
  4533.2    0.16       0  4998.4    0.07       0  5002.4    0.16       0
  5335.0    0.05       0  5444.3     0.1       0
Bank Sta=4998.4,5002.4
Exp/Cntr=0.3,0.1

Type RM Length L Ch R = 1,3447,620,620,620
BEGIN DESCRIPTION:
DUCK CREEK TRIB 40 2 9 0
END DESCRIPTION:
XS GIS Cut Line= 3
      3497363.35     10436483.21      3496792.59     10436971.50
      3496669.29     10437347.89
#Sta/Elev= 30
  4472.6  447.58  4614.4  444.81  4756.0  440.85  4833.9  441.29  4869.0  439.10
  4883.3  439.49  4933.8  437.30  4948.0  438.35  4954.7  438.02  4983.2  433.47
  4989.8  431.62  4995.5  427.59  4995.7  427.09  4999.5  427.59  5018.3  433.58
  5053.5  434.89  5067.7  434.75  5075.4  433.18  5089.7  432.58  5096.3  430.34
  5104.0  430.41  5110.5  430.67  5118.2  433.12  5124.8  432.91  5139.1  435.12
  5147.3  435.23  5167.6  437.96  5181.9  438.67  5455.4  442.31  5619.8  446.25
#Mann=4,-1,0
  4472.6    0.16       0  4995.5    0.07       0  4999.5    0.16       0
  5147.3    0.05       0
Bank Sta=4995.5,4999.5
Exp/Cntr=0.3,0.1

Type RM Length L Ch R = 1,2827,458,458,458
BEGIN DESCRIPTION:
DUCK CREEK TRIB 40 2 7 0
END DESCRIPTION:
XS GIS Cut Line= 3
      3496992.09     10436441.65      3496792.11     10436541.64
      3496492.11     10437141.63
#Sta/Elev= 30
  4790.0  442.37  4843.1  439.96  4910.2  438.45  4954.9  436.18  4960.5  434.84
  4968.9  434.01  4977.3  432.54  4982.8  429.11  4991.2  426.60  4997.6  425.59
  4997.9  425.09  5001.4  425.09  5001.6  425.59  5010.8  429.43  5016.4  429.43
  5022.0  430.69  5027.6  431.15  5103.0  430.06  5111.4  431.30  5125.4  434.97
  5133.8  436.20  5170.1  436.66  5200.9  436.36  5206.4  435.91  5229.8  436.08
  5259.6  437.13  5285.1  437.24  5335.0  437.46  5541.9  440.47  5684.4  443.76
#Mann=5,-1,0
  4790.0    0.16       0  4997.6    0.07       0  5001.6    0.16       0
  5229.8     0.1       0  5285.1    0.05       0
Bank Sta=4997.6,5001.6
Exp/Cntr=0.3,0.1

Type RM Length L Ch R = 1,2369,550,550,550
BEGIN DESCRIPTION:
DUCK CREEK TRIB 40 2 7 1
END DESCRIPTION:
XS GIS Cut Line= 3
      3496842.12     10436241.64      3496542.11     10436341.64
      3496342.09     10436741.68
#Sta/Elev= 30
  4705.3  439.95  4789.6  435.78  4810.7  437.07  4852.9  435.43  4874.0  435.67
  4884.5  434.14  4895.1  433.87  4916.1  430.38  4968.8  429.05  4979.4  424.45
  4987.9  422.27  4988.2  421.77  4991.7  421.77  4991.9  422.27  5000.5  423.77
  5011.0  427.83  5018.9  427.37  5043.9  427.83  5052.3  428.23  5057.9  429.50
  5074.7  428.70  5097.0  429.54  5102.6  428.45  5119.4  430.37  5125.0  429.85
  5141.7  433.23  5178.6  435.53  5200.4  436.24  5286.2  436.51  5468.8  438.27
#Mann=5,-1,0
  4705.3    0.16       0  4987.9    0.07       0  4991.9    0.16       0
  5178.6     0.1       0  5286.2    0.05       0
Bank Sta=4987.9,4991.9
Exp/Cntr=0.3,0.1

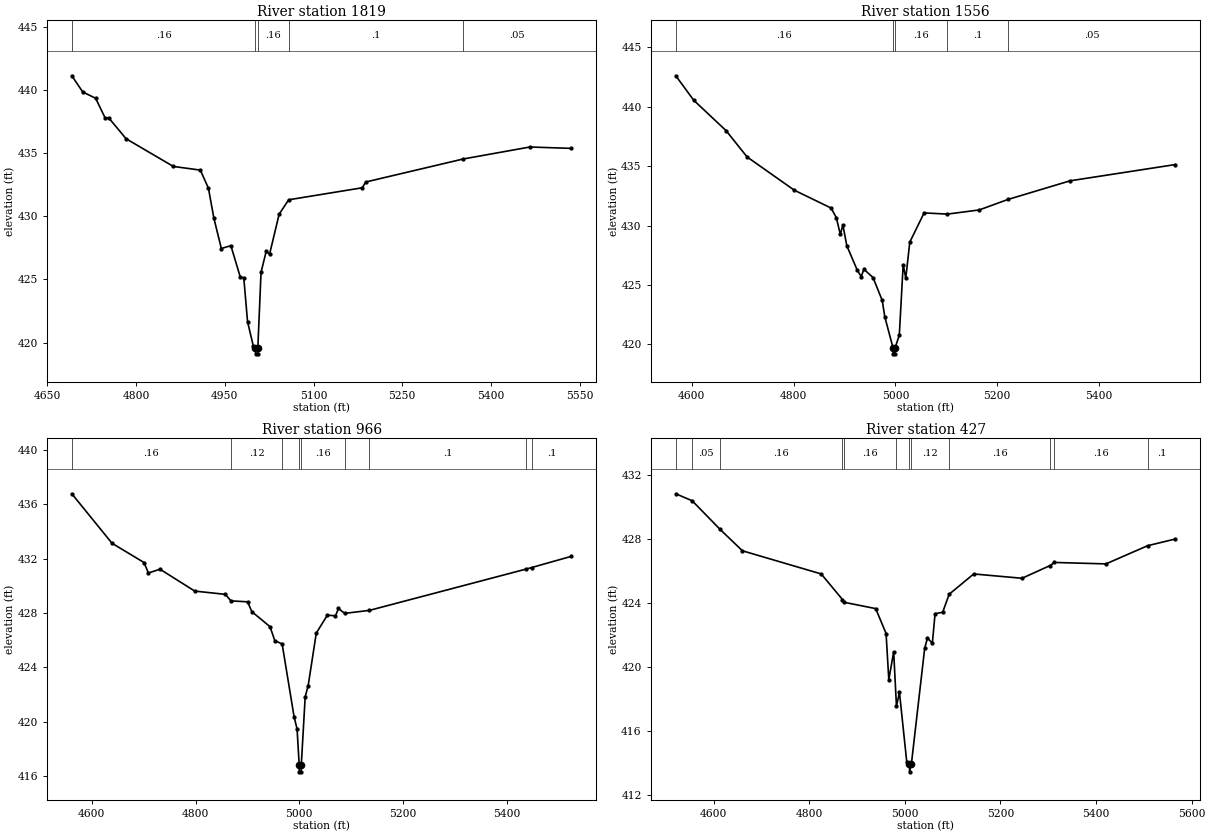
Type RM Length L Ch R = 1,1819,263,263,263
BEGIN DESCRIPTION:
DUCK CREEK TRIB 40 2 6 0
END DESCRIPTION:
XS GIS Cut Line= 3
      3496742.66     10435797.47      3496306.48     10436036.17
      3496130.69     10436335.67
#Sta/Elev= 30
  4691.5  441.13  4709.9  439.85  4731.7  439.35  4747.9  437.78  4753.6  437.81
  4783.3  436.14  4863.1  433.95  4908.7  433.66  4922.4  432.22  4931.5  429.87
  4944.2  427.45  4960.3  427.68  4976.4  425.16  4982.1  425.14  4988.5  421.66
  4998.2  419.73  5001.9  419.61  5002.2  419.11  5005.7  419.11  5005.9  419.61
  5011.3  425.57  5020.0  427.22  5025.7  427.00  5041.9  430.17  5058.0  431.31
  5182.3  432.26  5188.4  432.72  5353.0  434.54  5465.8  435.49  5536.0  435.38
#Mann=5,-1,0
  4691.5    0.16       0  5001.9    0.07       0  5005.9    0.16       0
  5058.0     0.1       0  5353.0    0.05       0
Bank Sta=5001.9,5005.9
Exp/Cntr=0.3,0.1

Type RM Length L Ch R = 1,1556,590,590,590
BEGIN DESCRIPTION:
DUCK CREEK TRIB 40 2 5 0
END DESCRIPTION:
XS GIS Cut Line= 3
      3496757.89     10435617.33      3496230.53     10435749.71
      3496033.06     10436140.31
#Sta/Elev= 30
  4568.7  442.60  4603.7  440.55  4667.5  437.98  4708.7  435.77  4801.5  432.97
  4873.7  431.47  4884.0  430.66  4891.8  429.26  4896.9  430.03  4904.6  428.30
  4925.2  426.23  4932.9  425.70  4938.1  426.32  4956.1  425.62  4974.1  423.70
  4979.3  422.30  4995.4  419.70  4995.6  419.20  4999.1  419.20  4999.4  419.70
  5007.7  420.77  5015.3  426.71  5020.4  425.57  5028.3  428.60  5056.4  431.06
  5102.1  430.96  5164.7  431.31  5221.0  432.19  5343.0  433.76  5550.1  435.13
#Mann=5,-1,0
  4568.7    0.16       0  4995.4    0.07       0  4999.4    0.16       0
  5102.1     0.1       0  5221.0    0.05       0
Bank Sta=4995.4,4999.4
Exp/Cntr=0.3,0.1

Type RM Length L Ch R = 1,966,539,539,539
BEGIN DESCRIPTION:
DUCK CREEK TRIB 40 2 4 0
END DESCRIPTION:
XS GIS Cut Line= 4
      3496537.38     10435151.62      3496304.75     10435207.18
      3496030.44     10435370.37      3495926.69     10435761.18
#Sta/Elev= 30
  4561.6  436.78  4639.0  433.14  4700.7  431.72  4709.1  430.95  4731.5  431.23
  4798.4  429.62  4857.3  429.38  4868.3  428.90  4900.1  428.83  4908.6  428.10
  4943.5  427.00  4952.7  425.97  4966.8  425.73  4989.8  420.38  4995.6  419.47
  4999.7  416.82  4999.9  416.32  5003.4  416.32  5003.7  416.82  5011.2  421.83
  5017.0  422.67  5032.6  426.53  5054.0  427.85  5069.6  427.80  5075.4  428.34
  5087.3  427.98  5134.9  428.20  5437.0  431.24  5447.4  431.35  5524.3  432.18
#Mann=9,-1,0
  4561.6    0.16       0  4868.3    0.12       0  4966.8    0.16       0
  4999.7    0.07       0  5003.7    0.16       0  5087.3    0.12       0
  5134.9     0.1       0  5437.0    0.05       0  5447.4     0.1       0
Bank Sta=4999.7,5003.7
Exp/Cntr=0.3,0.1

Type RM Length L Ch R = 1,427,0,0,0
BEGIN DESCRIPTION:
DUCK CREEK TRIB 40 2 1 0
END DESCRIPTION:
XS GIS Cut Line= 4
      3496210.86     10434786.56      3495900.40     10434755.79
      3495729.80     10435057.83      3495824.89     10435432.59
#Sta/Elev= 30
  4520.6  430.85  4554.9  430.41  4613.3  428.62  4660.0  427.28  4824.9  425.83
  4869.3  424.23  4872.1  424.06  4938.9  423.66  4960.6  422.10  4966.3  419.21
  4976.5  420.95  4982.3  417.56  4988.6  418.41  5003.9  414.05  5009.6  413.94
  5009.8  413.44  5013.6  413.94  5041.4  421.18  5047.2  421.82  5057.4  421.49
  5063.1  423.34  5079.0  423.43  5092.6  424.56  5144.0  425.83  5245.0  425.56
  5303.4  426.35  5312.8  426.55  5420.7  426.46  5508.0  427.60  5566.1  428.02
#Mann=12,-1,0
  4520.6    0.16       0  4554.9    0.05       0  4613.3    0.16       0
  4869.3    0.12       0  4872.1    0.16       0  4982.3    0.12       0
  5009.6    0.07       0  5013.6    0.12       0  5092.6    0.16       0
  5303.4    0.12       0  5312.8    0.16       0  5508.0     0.1       0
Bank Sta=5009.6,5013.6
Exp/Cntr=0.3,0.1

Chan Stop Cuts=-1