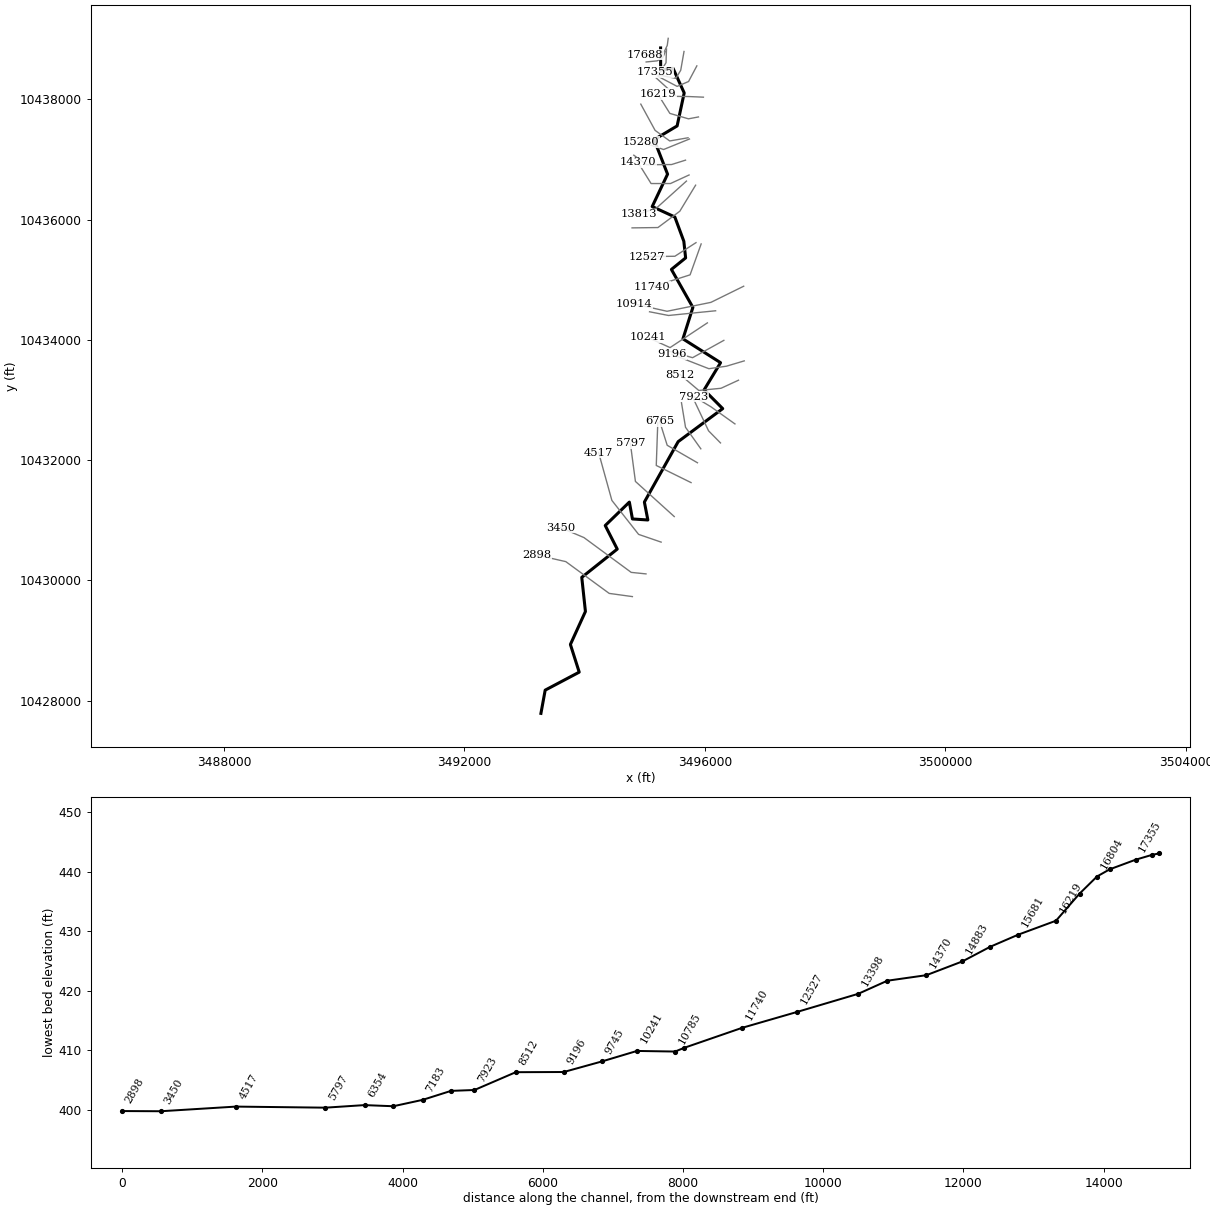
--- DUCK CREEK TRIB 40.prj (project) ---

Proj Title=DUCK CREEK TRIB 40 Base Level Engineering
Current Plan=p01
Default Exp/Contr=0.3,0.1
English Units
Geom File=g01
Flow File=f01
Plan File=p01
Y Axis Title=Elevation
X Axis Title(PF)=Main Channel Distance
X Axis Title(XS)=Station
BEGIN DESCRIPTION:
DUCK CREEK TRIB 40
END DESCRIPTION:
DSS Export Rating Curves= 0
DSS Export Rating Curve Sorted= 0
DSS Export Volume Flow Curves= 0
DXF OffsetX= 0
DXF OffsetY= 0
DXF ScaleX= 1
DXF ScaleY= 10

--- DUCK CREEK TRIB 40.p01 (plan) ---

Plan Title=Multiple Run
Short Identifier=Multiple
Geom File=g01
Flow File=f01
Subcritical Flow
K Sum by GR= 0
Std Step Tol= 0.01
Critical Tol= 0.01
Num of Std Step Trials= 20
Max Error Tol= 0.3
Flow Tol Ratio= 0.001
Split Flow NTrial= 30
Split Flow Tol= 0.02
Split Flow Ratio= 0.02
Log Output Level= 0
Friction Slope Method= 1
Unsteady Friction Slope Method= 2
Unsteady Bridges Friction Slope Method= 1
Parabolic Critical Depth
Global Vel Dist=  1 , 1 , 1
Global Log Level= 0
CheckData=True
Encroach Param= -1, 0, 0, 0
BEGIN DESCRIPTION:
Multiple Run
END DESCRIPTION:

--- DUCK CREEK TRIB 40.f01 (steady flow) ---

Flow Title=Multiple
Program Version=4.10
Number of Profiles= 7
Profile Names=10-year,25-year,50-year,1pct_min,100-year,1pct_plu,500-year
River Rch & RM=DUCK CREEK TRIB,Reach-1         ,17688
     719     969    1171    1032    1396    1888    1979
River Rch & RM=DUCK CREEK TRIB,Reach-1         ,10914
    1474    2053    2534    2276    3078    4163    4535
Boundary for River Rch & Prof#=DUCK CREEK TRIB,Reach-1         , 1
Up Type= 0
Dn Type= 3
Dn Slope=0.005
Boundary for River Rch & Prof#=DUCK CREEK TRIB,Reach-1         , 2
Up Type= 0
Dn Type= 3
Dn Slope=0.005
Boundary for River Rch & Prof#=DUCK CREEK TRIB,Reach-1         , 3
Up Type= 0
Dn Type= 3
Dn Slope=0.005
Boundary for River Rch & Prof#=DUCK CREEK TRIB,Reach-1         , 4
Up Type= 0
Dn Type= 3
Dn Slope=0.005
Boundary for River Rch & Prof#=DUCK CREEK TRIB,Reach-1         , 5
Up Type= 0
Dn Type= 3
Dn Slope=0.005
Boundary for River Rch & Prof#=DUCK CREEK TRIB,Reach-1         , 6
Up Type= 0
Dn Type= 3
Dn Slope=0.005
Boundary for River Rch & Prof#=DUCK CREEK TRIB,Reach-1         , 7
Up Type= 0
Dn Type= 3
Dn Slope=0.005
DSS Import GetInterval= 0
DSS Import GetPeak= 0
DSS Import FillOption= 0

--- DUCK CREEK TRIB 40.g01 (geometry) ---

Geom Title=Existing Conditions
Program Version=4.10

River Reach=DUCK CREEK TRIB ,Reach-1
Reach XY= 30
      3495262.12      10438856.1      3495263.41     10438490.39
      3495469.14     10438517.73      3495654.59     10438108.36
      3495536.86     10437558.99      3495154.32     10437330.48
      3495378.09     10436756.82      3495122.47     10436217.76
      3495498.86     10436044.57      3495648.59     10435640.15
      3495678.31     10435363.95      3495441.97     10435172.15
      3495799.14     10434540.49      3495633.75     10434017.36
      3496259.72     10433621.13      3495985.72     10433168.34
      3496295.17     10432856.98      3495554.29      10432307.5
      3494992.45     10431302.66      3495050.09     10431004.74
      3494793.84     10431021.41      3494742.45     10431301.97
      3494341.06     10430912.38      3494541.06     10430520.02
      3493950.96     10430050.16      3494011.72     10429482.45
      3493761.72     10428933.84      3493908.44     10428473.31
      3493342.46     10428174.14      3493271.53     10427787.68

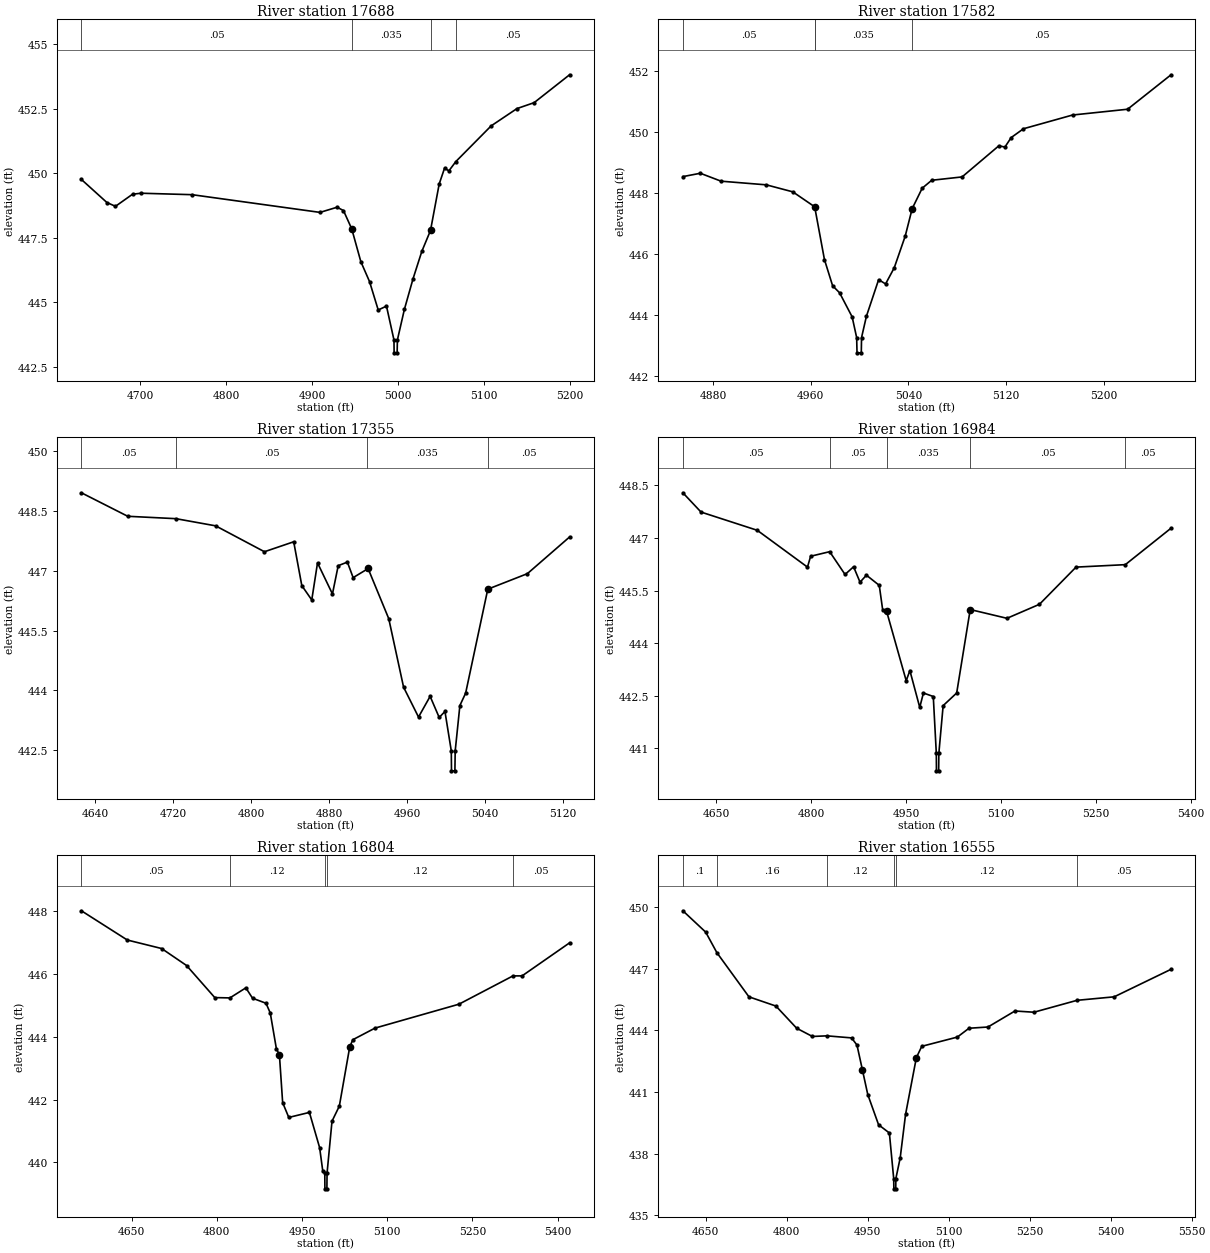
Type RM Length L Ch R = 1 ,17688   ,106,106,106
BEGIN DESCRIPTION:
DUCK CREEK TRIB 40 5 0
END DESCRIPTION:
XS GIS Cut Line= 6
     3495388.716    10439016.122     3495373.099    10438898.993
      3495328.87      10438805.3      3495268.98     10438766.25
      3495120.62     10438742.82      3495000.91     10438742.82
#Sta/Elev= 30
4631.515449.75574661.256448.8605 4671.17448.71544690.998449.18364700.912449.2222
4760.237449.1658    4909  448.48  4928.9  448.68  4936.3  448.55 4945.92  447.84
  4956.5  446.57  4966.6   445.8  4976.7   444.7  4986.3  444.85    4995  443.54
  4995.2  443.04  4998.7  443.04    4999  443.54  5007.1  444.72  5017.2  445.91
  5027.4  446.97  5037.5  447.78  5047.6  449.58  5053.8  450.19  5058.9  450.09
    5067  450.45    5108  451.83    5138   452.5    5158  452.73  5199.2  453.81
#Mann= 4 ,-1 , 0
4631.515     .05       0 4945.92    .035       0  5037.5     .05       0
    5067     .05       0
Bank Sta=4945.92,5037.5
XS Rating Curve= 0 ,0
Exp/Cntr=0.3,0.1

Type RM Length L Ch R = 1 ,17582   ,227,227,227
BEGIN DESCRIPTION:
DUCK CREEK TRIB 40 4 0
END DESCRIPTION:
XS GIS Cut Line= 4
      3495339.27      10438794.9      3495297.62     10438693.37
      3495203.91     10438641.31      3495021.76     10438623.09
#Sta/Elev= 30
  4855.2  448.55  4869.5  448.66  4886.5   448.4  4923.6  448.28  4945.3  448.05
  4963.2  447.56  4971.2  445.83  4977.9  444.97  4983.6  444.74  4993.9  443.95
  4997.6  443.27  4997.9  442.77  5001.4  442.77  5001.6  443.27  5005.6  443.97
  5015.6  445.17  5021.3  445.03  5028.4  445.56  5037.4   446.6  5043.1   447.5
  5051.3  448.17  5059.1  448.43    5084  448.54  5114.1  449.56  5119.1  449.52
  5124.2  449.83  5134.3  450.12  5174.5  450.57  5219.6  450.76  5255.2  451.89
#Mann= 4 ,-1 , 0
  4855.2     .05       0  4963.2     .16       0  4963.2    .035       0
  5043.1     .05       0
Bank Sta=4963.2,5043.1
XS Rating Curve= 0 ,0
Exp/Cntr=0.3,0.1

Type RM Length L Ch R = 1 ,17355   ,371,371,371
BEGIN DESCRIPTION:
DUCK CREEK TRIB 40 31 1
END DESCRIPTION:
XS GIS Cut Line= 4
      3495360.09     10438839.16      3495352.28     10438610.07
      3495245.56     10438440.89       3495176.2      10438456.3
#Sta/Elev= 30
  4626.2  448.96  4673.7  448.37  4723.1  448.31  4763.8  448.13  4813.8  447.48
  4843.8  447.73  4852.1  446.63  4862.3  446.27  4868.2   447.2  4883.5  446.42
  4889.4  447.13  4898.8  447.22  4904.7  446.83  4918.9  447.04    4920  447.06
  4941.2   445.8  4956.4  444.08  4971.7  443.33  4983.6  443.85  4992.9  443.32
  4998.8  443.47  5005.3  442.48  5005.5  441.98    5009  441.98  5009.3  442.48
  5014.1  443.62    5020  443.93  5042.7  446.54  5083.3  446.93  5126.5  447.85
#Mann= 4 ,-1 , 0
  4626.2     .05       0  4723.1     .05       0  4918.9    .035       0
  5042.7     .05       0
Bank Sta=4920,5042.7
XS Rating Curve= 0 ,0
Exp/Cntr=0.3,0.1

Type RM Length L Ch R = 1 ,16984   ,180,180,180
BEGIN DESCRIPTION:
DUCK CREEK TRIB 40 31 0
END DESCRIPTION:
XS GIS Cut Line= 4
      3495651.61      10438797.5      3495596.95     10438485.14
      3495516.26     10438349.79      3495224.72     10438407.05
#Sta/Elev= 30
  4596.9  448.29  4625.6  447.74  4714.5  447.22  4793.9  446.17  4798.9  446.48
    4829  446.61  4853.3  445.96  4866.8  446.18    4877  445.74  4887.1  445.94
  4907.4  445.65  4912.8  444.95    4919  444.91    4950  442.93  4955.8  443.22
  4971.4  442.17  4977.2  442.58  4992.8  442.48  4997.6  440.86  4997.8  440.36
  5001.3  440.36  5001.6  440.86  5008.4  442.22  5029.8  442.58  5051.2  444.96
  5109.3  444.71  5160.7  445.11  5218.5  446.17  5296.4  446.24  5368.7  447.28
#Mann= 5 ,-1 , 0
  4596.9     .05       0    4829     .05       0    4919    .035       0
  5051.2     .05       0  5296.4     .05       0
Bank Sta=4919,5051.2
XS Rating Curve= 0 ,0
Exp/Cntr=0.3,0.1

Type RM Length L Ch R = 1 ,16804   ,249,249,249
BEGIN DESCRIPTION:
DUCK CREEK TRIB 40 32 0
END DESCRIPTION:
XS GIS Cut Line= 4
      3495865.06     10438558.04      3495727.09     10438297.73
      3495537.08     10438217.04      3495219.57      10438383.6
#Sta/Elev= 30
  4561.6     448  4642.5  447.07  4702.9   446.8  4746.8  446.26  4796.5  445.24
  4823.1  445.23  4851.2  445.55    4863  445.22  4886.7  445.06  4894.2  444.75
  4904.9  443.62  4910.3  443.42    4916   441.9  4926.8  441.43  4963.1  441.59
  4981.1  440.47  4986.7  439.72  4990.2  439.66  4990.4  439.16  4993.9  439.16
  4994.2  439.66  5002.9  441.31  5015.8  441.79  5034.1  443.67  5039.5   443.9
  5078.6  444.27  5226.4  445.03  5321.6  445.93  5337.6  445.93  5421.2  446.98
#Mann= 5 ,-1 , 0
  4561.6     .05       0  4823.1     .12       0  4990.2     .07       0
  4994.2     .12       0  5321.6     .05       0
Bank Sta=4910.3,5034.1
XS Rating Curve= 0 ,0
Exp/Cntr=0.3,0.1

Type RM Length L Ch R = 1 ,16555   ,336,336,336
BEGIN DESCRIPTION:
DUCK CREEK TRIB 40 30 1
END DESCRIPTION:
XS GIS Cut Line= 4
       3495974.4     10438037.44       3495732.3     10438047.85
      3495526.67     10438050.45      3495188.85     10438357.09
#Sta/Elev= 30
  4607.6  449.82  4649.9  448.78  4670.6  447.78    4730  445.63    4780  445.18
  4818.4   444.1  4847.5   443.7  4874.5  443.73  4920.1  443.63  4930.1  443.28
  4940.1  442.08  4950.1  440.87  4970.1   439.4  4990.1     439  4998.1  436.78
  4998.4  436.28  5001.9  436.28  5002.1  436.78  5010.1  437.78  5020.1  439.91
  5040.1  442.67  5050.1  443.22    5116  443.67  5137.6   444.1  5172.7  444.16
  5222.7  444.94  5257.9  444.88  5337.7  445.46  5406.5  445.63  5511.8  446.97
#Mann= 6 ,-1 , 0
  4607.6      .1       0  4670.6     .16       0  4874.5     .12       0
  4998.1     .07       0  5002.1     .12       0  5337.7     .05       0
Bank Sta=4940.1,5040.1
XS Rating Curve= 0 ,0
Exp/Cntr=0.3,0.1

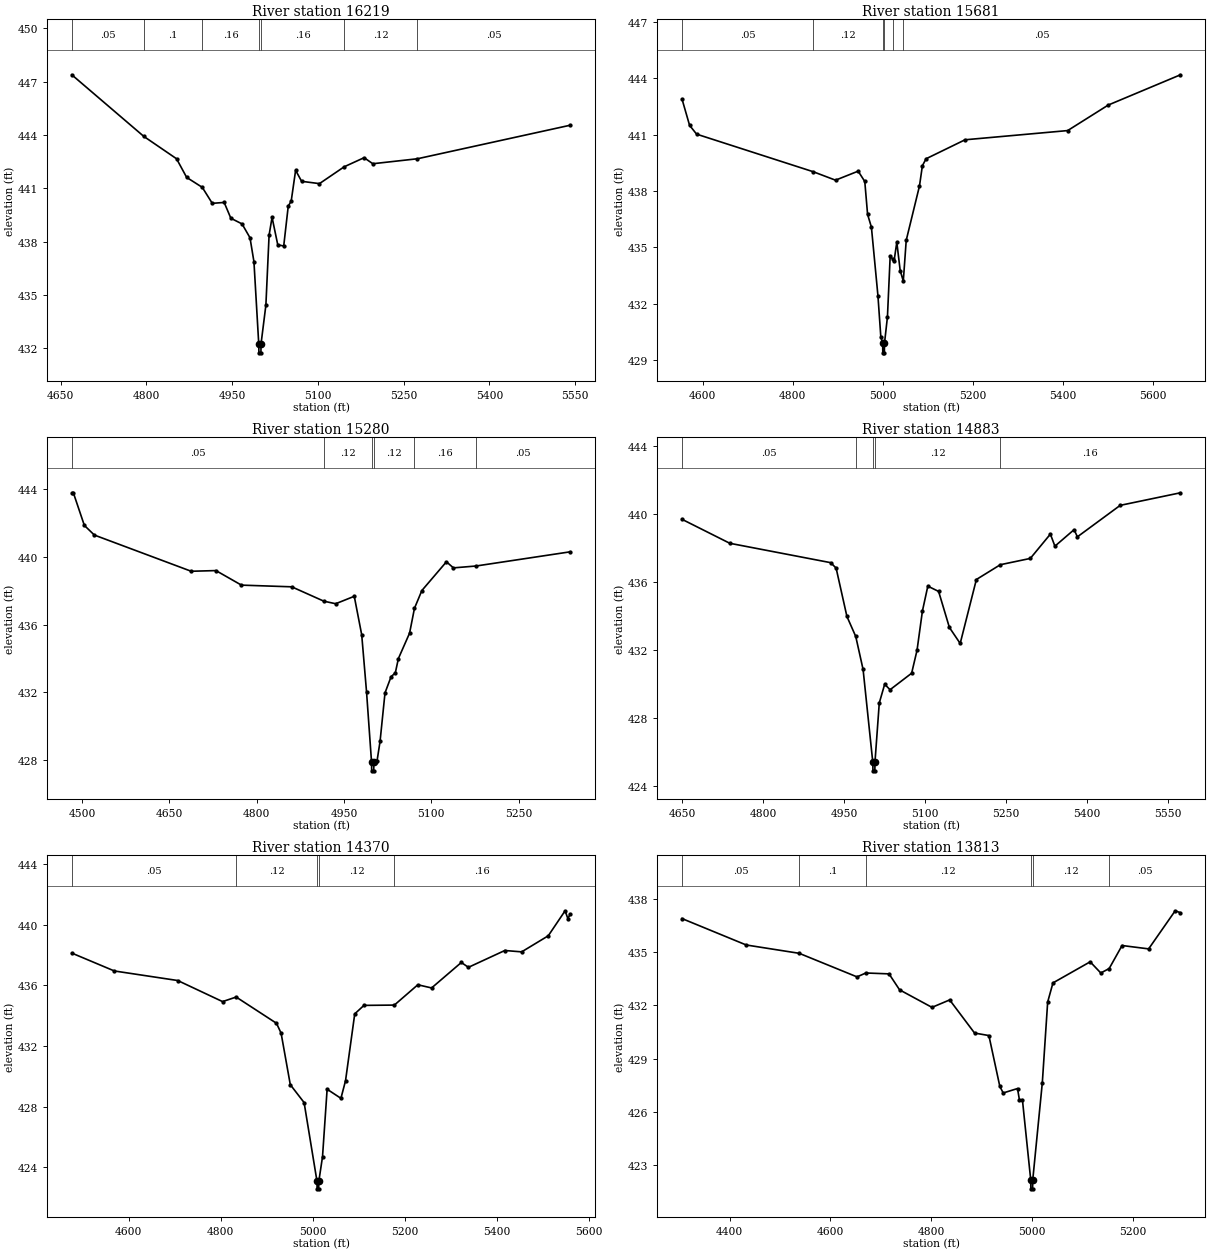
Type RM Length L Ch R = 1 ,16219   ,538,538,538
BEGIN DESCRIPTION:
DUCK CREEK TRIB 40 30 0
END DESCRIPTION:
XS GIS Cut Line= 4
      3495891.93     10437708.52      3495725.23     10437677.26
       3495416.2     10437767.54      3495214.83     10438090.44
#Sta/Elev= 30
  4669.4  447.39  4795.4  443.92  4852.7  442.66  4870.4  441.61  4897.7  441.05
  4915.2  440.15    4936   440.2  4947.7  439.31  4967.3  438.99  4981.2  438.21
  4988.1  436.86  4996.5  432.23  4996.8  431.73  5000.3  431.73  5000.5  432.23
    5009  434.42  5014.6  438.36  5019.8  439.36  5029.8  437.81  5040.2  437.75
  5048.1  439.99  5053.3  440.28    5061  442.01  5071.5  441.39  5102.7  441.26
  5146.1  442.21  5180.8  442.72  5196.1  442.38  5274.1  442.66  5541.5  444.55
#Mann= 7 ,-1 , 0
  4669.4     .05       0  4795.4      .1       0  4897.7     .16       0
  4996.5     .07       0  5000.5     .16       0  5146.1     .12       0
  5274.1     .05       0
Bank Sta=4996.5,5000.5
XS Rating Curve= 0 ,0
Exp/Cntr=0.3,0.1

Type RM Length L Ch R = 1 ,15681   ,401,401,401
BEGIN DESCRIPTION:
DUCK CREEK TRIB 40 29 0
END DESCRIPTION:
XS GIS Cut Line= 4
      3495718.62     10437362.29      3495413.78     10437309.15
      3495170.47     10437485.34      3494932.74     10437921.63
#Sta/Elev= 30
  4553.9   442.9  4570.7   441.5  4586.3  441.03  4845.2  439.03  4894.7  438.58
    4945  439.06  4959.7  438.51  4965.9  436.76  4974.4  436.08  4988.9  432.43
  4995.3  430.24  4999.4  429.89  4999.7  429.39  5003.2  429.39  5003.4  429.89
    5010   431.3  5016.1  434.55  5022.1  434.36  5024.7  434.28  5030.8  435.28
  5038.3  433.77  5045.2  433.21  5051.7  435.38  5081.1  438.27  5087.6  439.35
  5095.8  439.72  5182.3  440.73  5410.1  441.22  5500.3  442.58  5660.6  444.19
#Mann= 6 ,-1 , 0
  4553.9     .05       0  4845.2     .12       0  4999.4     .07       0
  5003.4     .12       0  5022.1     .16       0  5045.2     .05       0
Bank Sta=4999.4,5003.4
XS Rating Curve= 0 ,0
Exp/Cntr=0.3,0.1

Type RM Length L Ch R = 1 ,15280   ,397,397,397
BEGIN DESCRIPTION:
DUCK CREEK TRIB 40 28 0
END DESCRIPTION:
XS GIS Cut Line= 3
      3495742.09     10437341.63      3495312.04     10437166.84
      3494940.51     10437291.84
#Sta/Elev= 30
  4482.5  443.79  4485.2  443.79  4504.1  441.86  4521.3  441.29  4687.6  439.15
  4730.1  439.19  4773.9  438.33  4860.3  438.23  4915.5  437.38  4935.8  437.23
  4967.7  437.67  4980.5  435.39  4988.8  432.01  4997.4  427.85  4997.6  427.35
  5001.1  427.35  5001.4  427.85  5006.7  427.91    5012  429.09  5020.5  431.96
    5031  432.92  5038.2  433.14  5043.5  433.99  5062.7  435.49  5071.1  436.96
  5083.8  438.01    5126  439.71    5138  439.35  5176.8  439.46  5338.7   440.3
#Mann= 6 ,-1 , 0
  4482.5     .05       0  4915.5     .12       0  4997.4     .07       0
  5001.4     .12       0  5071.1     .16       0  5176.8     .05       0
Bank Sta=4997.4,5001.4
XS Rating Curve= 0 ,0
Exp/Cntr=0.3,0.1

Type RM Length L Ch R = 1 ,14883   ,513,513,513
BEGIN DESCRIPTION:
DUCK CREEK TRIB 40 27 0
END DESCRIPTION:
XS GIS Cut Line= 4
      3495676.67     10436989.77      3495443.98     10436916.84
      3495030.79     10436913.37      3494816.32     10437072.49
#Sta/Elev= 30
  4649.1  439.68  4737.7  438.27  4924.8  437.13  4934.8  436.81  4954.8  433.97
  4971.2  432.79  4984.8  430.85  5002.8  425.39  5003.1  424.89  5006.6  424.89
  5006.8  425.39  5014.8  428.88  5024.8  429.98  5034.8  429.66  5074.8  430.63
  5084.8  431.98  5094.8  434.29  5104.8  435.75  5124.8  435.44  5144.8  433.32
  5164.8  432.38  5194.8  436.14  5239.2  437.01  5294.8  437.38    5332  438.81
  5340.4   438.1  5375.9  439.07  5382.1  438.65  5461.4   440.5  5573.2  441.24
#Mann= 5 ,-1 , 0
  4649.1     .05       0  4971.2     .12       0  5002.8     .07       0
  5006.8     .12       0  5239.2     .16       0
Bank Sta=5002.8,5006.8
XS Rating Curve= 0 ,0
Exp/Cntr=0.3,0.1

Type RM Length L Ch R = 1 ,14370   ,557,557,557
BEGIN DESCRIPTION:
DUCK CREEK TRIB 40 26 0
END DESCRIPTION:
XS GIS Cut Line= 4
      3495735.67     10436743.24      3495426.62     10436600.87
       3495103.7     10436600.87      3494882.08     10436957.55
#Sta/Elev= 30
  4476.3  438.13  4568.8  436.95  4706.5  436.32  4803.9  434.93  4833.5  435.23
  4921.1   433.5  4931.1  432.85  4951.1  429.45  4981.1  428.27  5009.1  423.08
  5009.3  422.58  5012.8  422.58  5013.1  423.08  5021.1   424.7  5031.1  429.15
  5061.1  428.55  5071.1  429.71  5091.1  434.12  5111.1  434.68  5177.2   434.7
  5228.2  436.04  5258.1  435.83  5322.7  437.51  5338.1  437.19  5417.2   438.3
  5453.8  438.21  5511.6  439.27  5548.2  440.92  5554.1  440.41  5559.4   440.7
#Mann= 5 ,-1 , 0
  4476.3     .05       0  4833.5     .12       0  5009.1     .07       0
  5013.1     .12       0  5177.2     .16       0
Bank Sta=5009.1,5013.1
XS Rating Curve= 0 ,0
Exp/Cntr=0.3,0.1

Type RM Length L Ch R = 1 ,13813   ,415,415,415
BEGIN DESCRIPTION:
DUCK CREEK TRIB 40 25 0
END DESCRIPTION:
XS GIS Cut Line= 3
      3495692.11     10436641.64      3495192.11     10436191.64
      3494892.12     10436091.65
#Sta/Elev= 30
  4305.6   436.9    4433  435.41  4538.1  434.94  4652.8  433.61  4670.3  433.83
  4716.3  433.78  4737.2  432.88  4801.5  431.89  4836.6  432.31    4886  430.44
  4914.4   430.3  4936.1  427.43  4942.8  427.06  4971.2  427.31  4974.9  426.68
  4980.9  426.68  4997.4  422.15  4997.6  421.65  5001.1  421.65  5001.4  422.15
  5020.4  427.64    5031  432.19  5041.5  433.27  5115.3  434.46  5136.4  433.83
    5153  434.08  5178.6  435.38  5231.3  435.19    5284  437.34  5294.5  437.23
#Mann= 6 ,-1 , 0
  4305.6     .05       0  4538.1      .1       0  4670.3     .12       0
  4997.4     .07       0  5001.4     .12       0    5153     .05       0
Bank Sta=4997.4,5001.4
XS Rating Curve= 0 ,0
Exp/Cntr=0.3,0.1

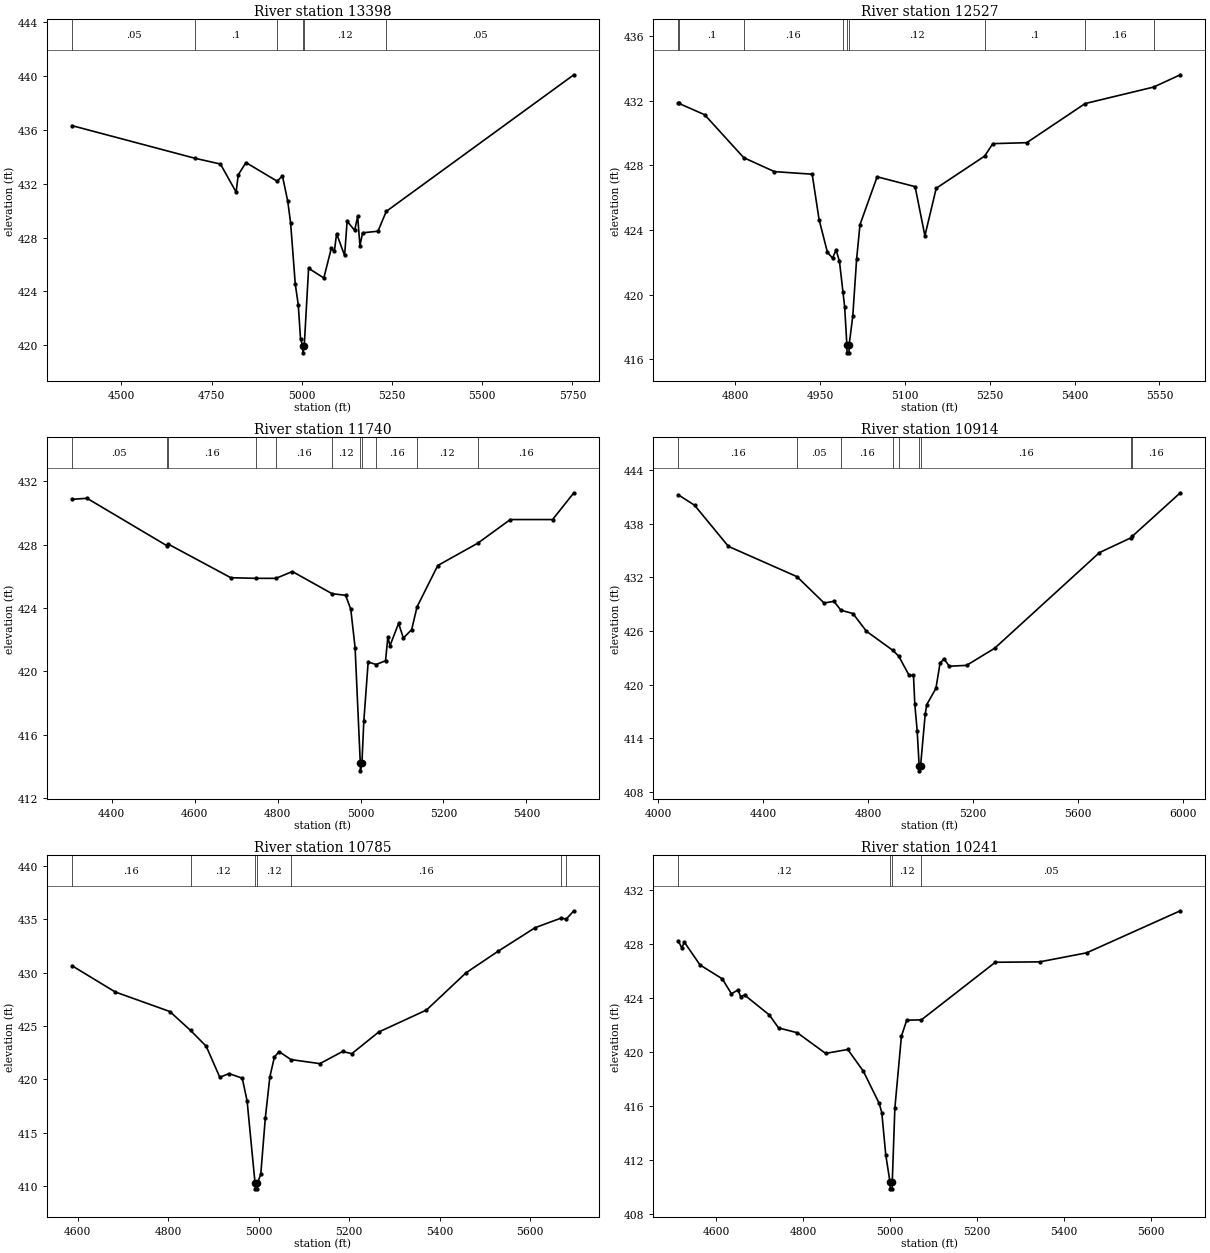
Type RM Length L Ch R = 1 ,13398   ,871,871,871
BEGIN DESCRIPTION:
DUCK CREEK TRIB 40 24 0
END DESCRIPTION:
XS GIS Cut Line= 4
      3495844.44     10436573.59      3495581.58     10436140.14
      3495218.01     10435868.87      3494787.29     10435863.27
#Sta/Elev= 30
  4362.8   436.3  4703.6  433.88  4774.4  433.45  4817.9  431.37  4823.8  432.65
  4845.1  433.56  4931.6  432.18  4946.3  432.57  4960.9   430.7  4968.9   429.1
  4981.8  424.56  4990.1  423.02  4996.4  420.49  5002.7  419.95    5003  419.45
  5006.7  419.95  5018.8  425.72    5061     425  5081.8  427.21  5090.2  426.97
  5096.4  428.29  5118.6  426.67  5125.6  429.21  5146.5  428.53  5154.8  429.57
  5161.1  427.39  5168.5  428.35  5211.1  428.47  5234.1  429.94  5754.1  440.07
#Mann= 6 ,-1 , 0
  4362.8     .05       0  4703.6      .1       0  4931.6     .12       0
  5002.7     .07       0  5006.7     .12       0  5234.1     .05       0
Bank Sta=5002.7,5006.7
XS Rating Curve= 0 ,0
Exp/Cntr=0.3,0.1

Type RM Length L Ch R = 1 ,12527   ,787,787,787
BEGIN DESCRIPTION:
DUCK CREEK TRIB 40 23 0
END DESCRIPTION:
XS GIS Cut Line= 3
      3495851.05     10435617.74      3495499.47     10435391.16
      3495030.76     10435385.96
#Sta/Elev= 30
    4700  431.88  4700.8  431.84  4746.3  431.14  4815.5  428.48  4869.7  427.62
  4936.4  427.46  4948.6  424.65  4963.4  422.62  4972.4  422.27  4978.6  422.78
  4984.6  422.07  4990.8  420.17  4993.8  419.25  4997.7  416.91    4998  416.41
  5001.5  416.41  5001.7  416.91  5008.1  418.66  5014.9   422.2  5020.9  424.34
  5051.2   427.3  5118.3  426.69  5135.6  423.65  5155.6  426.59  5241.2  428.58
  5255.6  429.35  5315.6  429.41  5418.8  431.83  5539.8  432.85    5587  433.61
#Mann= 9 ,-1 , 0
    4700     .05       0  4700.8      .1       0  4815.5     .16       0
  4990.8     .12       0  4997.7     .07       0  5001.7     .12       0
  5241.2      .1       0  5418.8     .16       0  5539.8     .05       0
Bank Sta=4997.7,5001.7
XS Rating Curve= 0 ,0
Exp/Cntr=0.3,0.1

Type RM Length L Ch R = 1 ,11740   ,826,826,826
BEGIN DESCRIPTION:
DUCK CREEK TRIB 40 51 0
END DESCRIPTION:
XS GIS Cut Line= 3
       3495936.7      10435596.1      3495752.66     10435082.18
      3495119.29     10434880.76
#Sta/Elev= 30
  4303.9  430.87  4340.5  430.93  4532.2  427.95  4535.4  428.05    4687  425.92
  4746.9  425.88    4796  425.88  4835.5  426.31  4931.3  424.91  4963.8  424.81
  4976.3  423.94  4986.8  421.51  4999.3  414.23  4999.5  413.73  5003.3  414.23
  5007.8  416.85  5018.3   420.6  5037.7  420.44  5060.2  420.68  5065.8  422.16
    5071  421.63  5091.7  423.04  5103.2  422.11  5123.2  422.64  5136.2  424.08
  5186.2  426.69  5282.8   428.1  5361.1  429.59  5463.1  429.59  5514.4  431.28
#Mann= 11 ,-1 , 0
  4303.9     .05       0  4532.2      .1       0  4535.4     .16       0
  4746.9     .12       0    4796     .16       0  4931.3     .12       0
  4999.3     .07       0  5003.3     .12       0  5037.7     .16       0
  5136.2     .12       0  5282.8     .16       0
Bank Sta=4999.3,5003.3
XS Rating Curve= 0 ,0
Exp/Cntr=0.3,0.1

Type RM Length L Ch R = 1 ,10914   ,129,129,129
BEGIN DESCRIPTION:
DUCK CREEK TRIB 40 52 0
END DESCRIPTION:
XS GIS Cut Line= 4
      3496644.27     10434892.81      3496098.96     10434624.35
      3495369.03     10434476.13      3494820.91     10434599.17
#Sta/Elev= 30
  4076.9  441.21  4138.4  440.06  4267.6  435.46  4529.4  432.07  4632.6  429.13
  4670.1  429.32  4696.3  428.33  4742.7  427.95  4793.7  425.98  4894.7  423.84
  4917.4  423.18    4957  421.03  4973.5  421.05  4978.6  417.82  4987.6  414.84
  4995.3  410.87  4995.7  410.37  5000.4  410.87  5018.2  416.69  5024.1  417.77
  5059.1  419.59  5074.8  422.39  5089.7   422.9  5110.1  422.06  5176.1  422.16
  5283.5  424.08  5682.6  434.76  5804.7  436.44  5807.5  436.57  5991.3  441.45
#Mann= 9 ,-1 , 0
  4076.9     .16       0  4529.4     .05       0  4696.3     .16       0
  4894.7     .12       0  4917.4     .16       0  4995.3     .07       0
  5000.4     .16       0  5804.7     .05       0  5807.5     .16       0
Bank Sta=4995.3,5000.4
XS Rating Curve= 0 ,0
Exp/Cntr=0.3,0.1

Type RM Length L Ch R = 1 ,10785   ,544,544,544
BEGIN DESCRIPTION:
DUCK CREEK TRIB 40 21 0
END DESCRIPTION:
XS GIS Cut Line= 3
      3496177.23     10434484.51       3495394.2     10434406.21
      3495078.17     10434467.74
#Sta/Elev= 30
  4587.6  430.64  4683.2  428.18  4803.8  426.35  4849.6  424.58  4884.2   423.1
  4914.3  420.19  4934.4  420.54  4963.9  420.11  4974.6  417.97  4992.2  410.25
  4992.5  409.75  4996.9  409.75  4997.3  410.25  5004.8  411.13  5014.8  416.37
  5024.9  420.25  5034.9  422.08    5045   422.6  5071.5  421.85  5135.4  421.47
  5185.7  422.61  5205.8   422.4  5265.4  424.43  5370.9  426.49  5458.2  429.97
  5529.1  431.99    5611   434.2  5668.6   435.1  5679.6     435  5696.5  435.78
#Mann= 7 ,-1 , 0
  4587.6     .16       0  4849.6     .12       0  4992.2     .07       0
  4997.3     .12       0  5071.5     .16       0  5668.6     .05       0
  5679.6     .16       0
Bank Sta=4992.2,4997.3
XS Rating Curve= 0 ,0
Exp/Cntr=0.3,0.1

Type RM Length L Ch R = 1 ,10241   ,496,496,496
BEGIN DESCRIPTION:
Mapping XS 628c5268
END DESCRIPTION:
XS GIS Cut Line= 3
       3496040.2     10434283.14      3495419.37     10433872.05
      3495045.85     10434042.08
#Sta/Elev= 30
  4513.4  428.24  4521.1  427.72  4527.1  428.15  4563.2  426.46  4614.4  425.43
  4635.4  424.32  4650.5  424.61  4656.5  424.12  4665.6  424.23  4722.7  422.75
  4743.8  421.79    4787  421.43  4852.1   419.9  4903.2  420.19  4939.3  418.56
  4975.4  416.19  4981.4  415.51  4990.5  412.38  5000.3  410.35  5000.7  409.85
  5005.1  409.85  5005.5  410.35  5011.5  415.84  5026.6  421.18  5038.8  422.36
  5072.7  422.39  5242.7  426.66  5344.9  426.69  5452.8  427.36  5668.4  430.48
#Mann= 4 ,-1 , 0
  4513.4     .12       0  5000.3     .07       0  5005.5     .12       0
  5072.7     .05       0
Bank Sta=5000.3,5005.5
XS Rating Curve= 0 ,0
Exp/Cntr=0.3,0.1

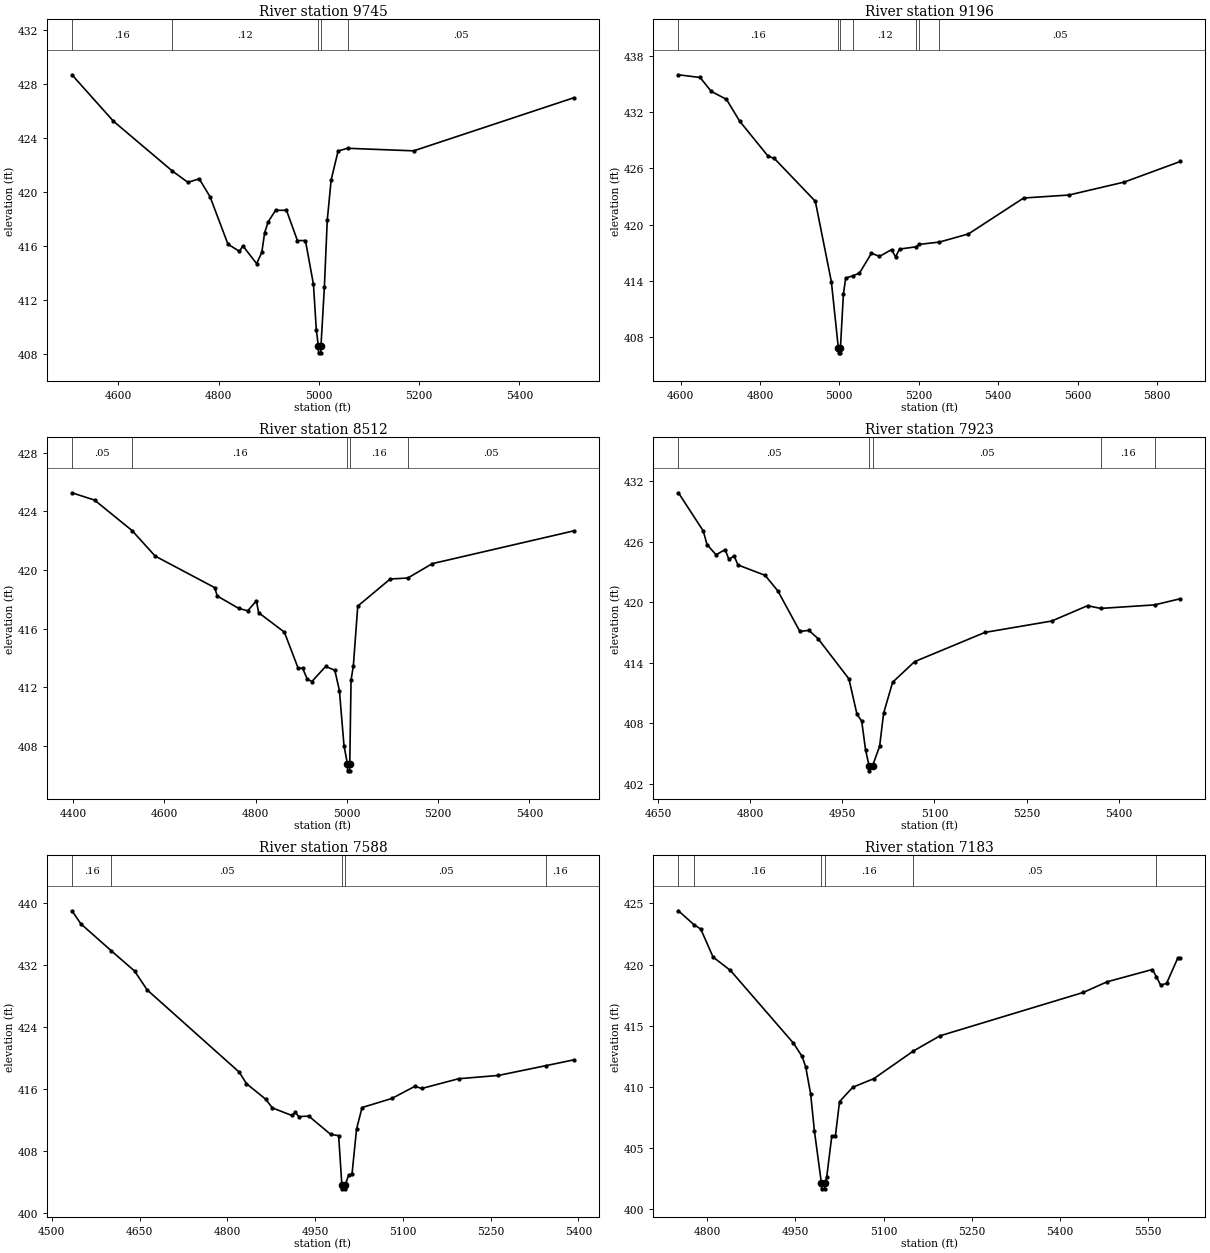
Type RM Length L Ch R = 1 ,9745    ,549,549,549
BEGIN DESCRIPTION:
DUCK CREEK TRIB 40 50
END DESCRIPTION:
XS GIS Cut Line= 3
      3496314.35     10433992.33      3495794.12     10433704.25
      3495402.59     10433813.32
#Sta/Elev= 30
  4507.4  428.68    4590  425.25  4706.9  421.58  4738.6  420.72  4761.3  420.98
    4783  419.64  4818.6  416.14  4841.5  415.61  4848.3  416.02  4875.8   414.7
  4886.1  415.54  4891.8     417  4898.6  417.78  4913.5  418.65  4935.3  418.65
  4957.1  416.41  4973.1  416.41  4989.1  413.17  4994.8   409.8  4998.9   408.6
  4999.3   408.1  5003.7   408.1  5004.1   408.6  5010.9  412.97  5016.6   417.9
  5024.4   420.9  5038.3  423.04  5057.2  423.24    5189  423.05  5508.5  426.98
#Mann= 5 ,-1 , 0
  4507.4     .16       0  4706.9     .12       0  4998.9     .07       0
  5004.1     .12       0  5057.2     .05       0
Bank Sta=4998.9,5004.1
XS Rating Curve= 0 ,0
Exp/Cntr=0.3,0.1

Type RM Length L Ch R = 1 ,9196    ,684,684,684
BEGIN DESCRIPTION:
DUCK CREEK TRIB 40 18 0
END DESCRIPTION:
XS GIS Cut Line= 4
      3496653.62     10433651.06      3496356.76     10433562.52
      3496065.09     10433520.85      3495450.55     10433760.42
#Sta/Elev= 30
  4594.7  435.98  4649.4  435.69  4677.3  434.21  4715.7  433.36  4748.8  431.04
  4820.4   427.3  4836.3  427.05  4939.5  422.48  4979.9   413.9  4997.5  406.81
  4997.9  406.31  5002.3  406.31  5002.7  406.81  5010.2  412.58    5016  414.28
  5035.6  414.56  5050.6  414.81  5080.9  416.94  5101.1   416.6  5131.4  417.32
  5141.5  416.55  5151.6  417.38  5192.5  417.62  5200.8  417.88  5251.9  418.13
  5325.2     419  5464.1  422.83  5578.2  423.15  5717.5  424.53  5858.7  426.73
#Mann= 7 ,-1 , 0
  4594.7     .16       0  4997.5     .07       0  5002.7     .16       0
  5035.6     .12       0  5192.5     .16       0  5200.8     .12       0
  5251.9     .05       0
Bank Sta=4997.5,5002.7
XS Rating Curve= 0 ,0
Exp/Cntr=0.3,0.1

Type RM Length L Ch R = 1 ,8512    ,589,589,589
BEGIN DESCRIPTION:
DUCK CREEK TRIB 40 19 0
END DESCRIPTION:
XS GIS Cut Line= 4
      3496557.62      10433329.5      3496266.76     10433195.25
       3495897.6      10433158.9      3495585.76      10433423.4
#Sta/Elev= 30
  4397.3  425.27  4446.9  424.77  4529.4  422.68  4579.6  420.95  4710.3  418.79
  4715.8  418.22  4762.5  417.38  4782.6  417.21  4801.6  417.89  4806.6  417.08
    4863  415.75  4893.1  413.29  4902.9  413.29  4913.2  412.54  4923.3  412.38
  4953.4  413.41  4973.5  413.15  4983.6  411.76  4993.6  408.01    5001  406.78
  5001.5  406.28  5005.9  406.28  5006.3  406.78  5009.1  412.47  5014.2  413.46
  5023.8  417.53  5094.9  419.38  5133.5  419.45  5187.2  420.43  5497.5  422.67
#Mann= 5 ,-1 , 0
  4397.3     .05       0  4529.4     .16       0    5001     .07       0
  5006.3     .16       0  5133.5     .05       0
Bank Sta=5001,5006.3
XS Rating Curve= 0 ,0
Exp/Cntr=0.3,0.1

Type RM Length L Ch R = 1 ,7923    ,335,335,335
BEGIN DESCRIPTION:
DUCK CREEK TRIB 40 17 0
END DESCRIPTION:
XS GIS Cut Line= 3
      3496498.88     10432602.36      3496098.96     10432887.62
      3495819.27     10433055.43
#Sta/Elev= 30
    4683  430.87  4723.4  427.09  4729.6  425.73  4744.3  424.72  4759.1  425.23
  4765.2  424.28  4773.8   424.6    4780  423.71  4824.2  422.68  4845.1  421.12
  4880.8  417.12  4895.5  417.22  4910.3  416.41  4960.7  412.41  4973.8   408.9
  4981.5  408.23  4987.7   405.4  4993.5  403.79  4993.9  403.29  4999.2  403.79
  5010.7  405.73  5017.2  409.01  5031.9  412.08  5067.6  414.12  5182.2  417.02
    5291  418.15  5349.3  419.67  5370.6   419.4  5458.4  419.75  5500.4  420.36
#Mann= 5 ,-1 , 0
    4683     .05       0  4993.5     .03       0  4999.2     .05       0
  5370.6     .16       0  5458.4     .05       0
Bank Sta=4993.5,4999.2
XS Rating Curve= 0 ,0
Exp/Cntr=0.3,0.1

Type RM Length L Ch R = 1 ,7588    ,405,405,405
BEGIN DESCRIPTION:
DUCK CREEK TRIB 40 16 1
END DESCRIPTION:
XS GIS Cut Line= 3
      3496258.36     10432286.35      3496059.81      10432487.7
      3495813.98      10433007.3
#Sta/Elev= 30
  4534.5  439.01  4549.7  437.33  4601.7  433.85  4641.6  431.23  4662.9  428.81
  4820.4  418.19  4832.7  416.71  4865.4  414.71    4877  413.58  4910.1  412.61
  4916.4     413  4921.9  412.46  4939.2  412.52  4976.5  410.17  4990.2     410
  4995.7  403.64  4996.2  403.14  5001.1  403.14  5001.5  403.64  5007.4  404.95
    5013  405.02  5020.8  410.85  5030.2  413.63  5081.2   414.8  5120.3  416.36
  5132.3  416.09    5195  417.34  5263.2  417.77  5344.3  419.03  5392.1  419.78
#Mann= 5 ,-1 , 0
  4534.5     .16       0  4601.7     .05       0  4995.7     .03       0
  5001.5     .05       0  5344.3     .16       0
Bank Sta=4995.7,5001.5
XS Rating Curve= 0 ,0
Exp/Cntr=0.3,0.1

Type RM Length L Ch R = 1 ,7183    ,418,418,418
BEGIN DESCRIPTION:
DUCK CREEK TRIB 40 16 0
END DESCRIPTION:
XS GIS Cut Line= 3
      3495931.16     10432188.46      3495676.66     10432546.43
      3495609.55     10432954.74
#Sta/Elev= 30
  4751.3   424.4  4777.5  423.27  4789.3   422.9  4810.2  420.61  4839.8  419.51
  4946.8  413.56  4961.5  412.47  4967.7  411.61  4976.1  409.37  4982.4  406.38
  4994.2  402.13  4994.7  401.63  4999.6  401.63  5000.1  402.13  5003.3  402.58
  5011.9  405.92  5018.1  405.96  5025.1  408.77  5047.6  409.95  5083.3  410.65
  5150.8  412.92  5195.8  414.16  5439.2  417.71  5479.6  418.58  5556.6  419.59
  5563.8  418.99  5570.8  418.31  5580.9  418.45  5600.2  420.55  5604.3  420.55
#Mann= 6 ,-1 , 0
  4751.3     .05       0  4777.5     .16       0  4994.2     .07       0
  5000.1     .16       0  5150.8     .05       0  5563.8     .16       0
Bank Sta=4994.2,5000.1
XS Rating Curve= 0 ,0
Exp/Cntr=0.3,0.1

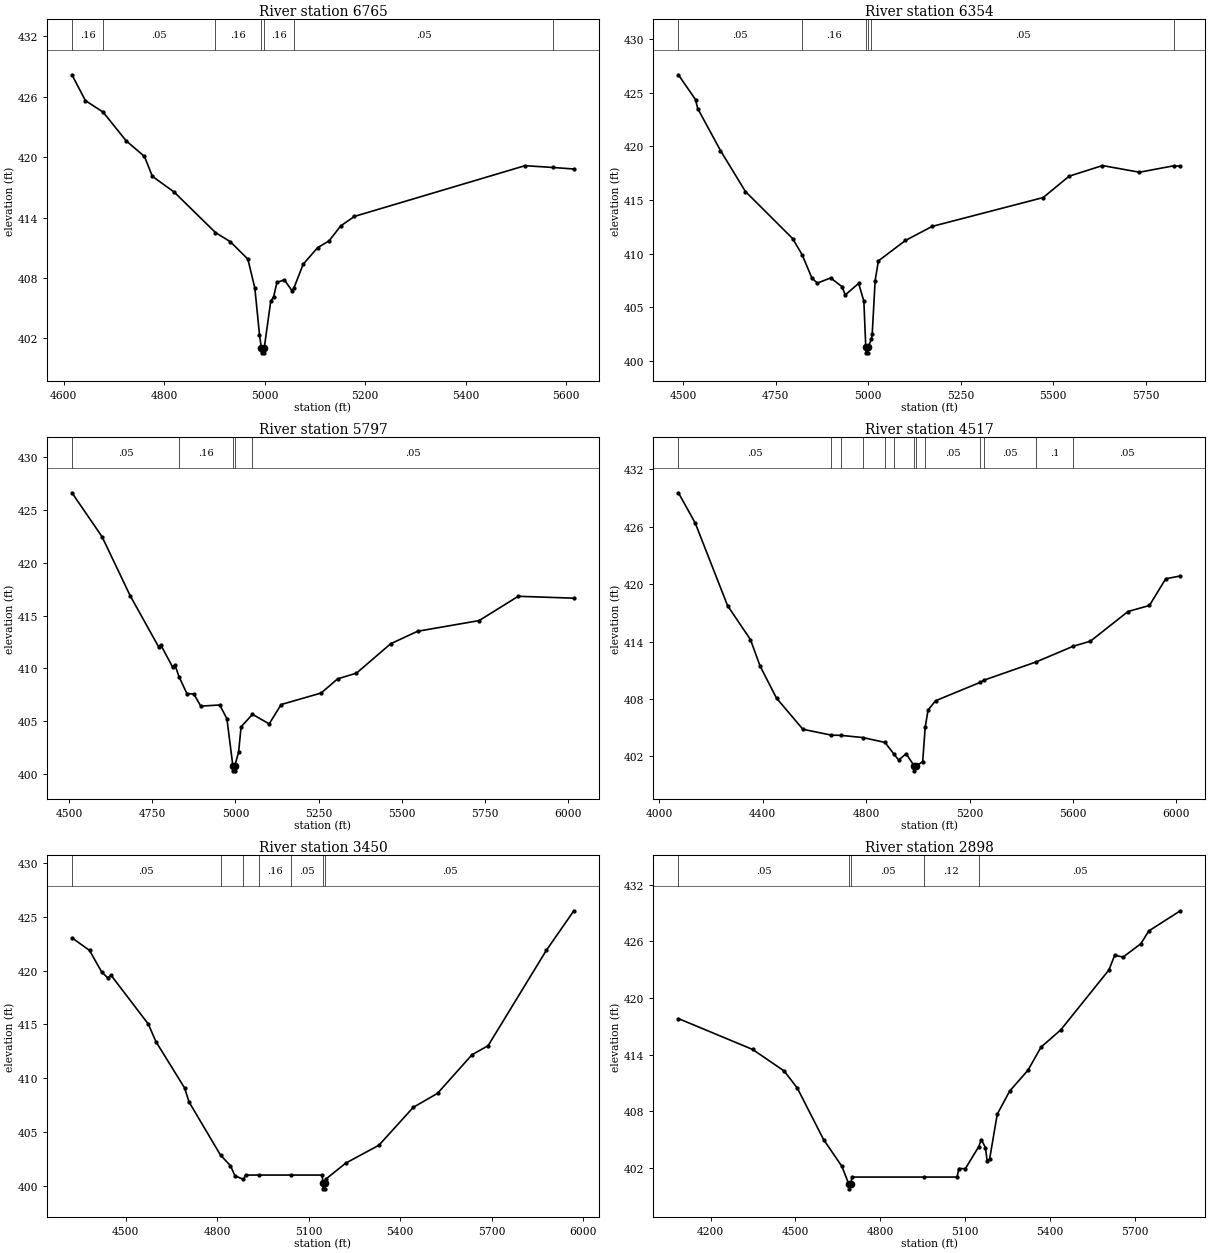
Type RM Length L Ch R = 1 ,6765    ,411,411,411
BEGIN DESCRIPTION:
DUCK CREEK TRIB 40 15 0
END DESCRIPTION:
XS GIS Cut Line= 3
      3495875.19     10431956.35      3495371.83     10432247.18
      3495246.61     10432645.11
#Sta/Elev= 30
  4616.7  428.18  4643.4  425.62  4678.7  424.47  4724.2  421.64  4760.9  420.07
  4776.7  418.09  4819.8  416.54  4902.2  412.51  4931.7   411.6  4966.7  409.87
  4980.6  406.98  4989.8  402.36  4993.4  401.06  4993.8  400.56  4998.8  400.56
  4999.3  401.06  5012.1  405.67  5017.9  406.12  5024.5  407.56  5039.4  407.81
  5055.2  406.67  5058.1  406.98  5076.7  409.36  5105.3     411  5128.4  411.69
  5151.4  413.17  5178.7  414.11    5518  419.15  5574.4  418.97  5615.2  418.82
#Mann= 7 ,-1 , 0
  4616.7     .16       0  4678.7     .05       0  4902.2     .16       0
  4993.4     .07       0  4999.3     .16       0  5058.1     .05       0
  5574.4      .1       0
Bank Sta=4993.4,4999.3
XS Rating Curve= 0 ,0
Exp/Cntr=0.3,0.1

Type RM Length L Ch R = 1 ,6354    ,557,557,557
BEGIN DESCRIPTION:
DUCK CREEK TRIB 40 14 0
END DESCRIPTION:
XS GIS Cut Line= 3
      3495768.96     10431626.32      3495190.04     10431911.58
      3495215.21     10432621.95
#Sta/Elev= 30
  4487.4  426.66  4533.7  424.34  4539.6  423.51  4601.1   419.6  4668.5  415.78
    4796   411.4  4821.7  409.89  4848.2  407.71  4862.9  407.25  4898.7  407.73
  4929.8  406.91    4938  406.14  4974.4  407.22  4988.5  405.56  4993.7  401.25
  4994.2  400.75  4999.2  400.75  4999.7  401.25  5008.7  402.01    5011  402.48
    5019  407.49  5027.8  409.32  5100.8  411.22  5172.9  412.53  5473.1  415.22
  5543.1  417.21  5633.2   418.2  5733.2  417.58    5826  418.18  5843.6  418.14
#Mann= 6 ,-1 , 0
  4487.4     .05       0  4821.7     .16       0  4993.7     .07       0
  4999.7     .16       0  5008.7     .05       0    5826      .1       0
Bank Sta=4993.7,4999.7
XS Rating Curve= 0 ,0
Exp/Cntr=0.3,0.1

Type RM Length L Ch R = 1 ,5797    ,1280,1280,1280
BEGIN DESCRIPTION:
DUCK CREEK TRIB 40 13 0
END DESCRIPTION:
XS GIS Cut Line= 3
      3495489.26     10431061.42      3494843.26      10431645.9
      3494759.45     10432277.29
#Sta/Elev= 30
  4508.9  426.62  4599.4  422.46  4683.9  416.88  4769.1  412.06  4775.8  412.23
  4811.6  410.12  4818.4  410.34  4830.4  409.24  4854.2  407.63  4875.2  407.58
  4896.1  406.44  4952.9  406.55  4974.5  405.25  4992.3  400.82  4992.8  400.32
  4998.1  400.32  4998.6  400.82  5009.7  402.11  5017.1  404.48  5051.3  405.67
  5101.6  404.76  5137.4  406.59  5257.7  407.68  5307.1  409.02  5363.8  409.56
  5466.6  412.34  5547.3  413.52  5732.3  414.53  5849.9  416.83    6017  416.65
#Mann= 5 ,-1 , 0
  4508.9     .05       0  4830.4     .16       0  4992.3     .07       0
  4998.6     .16       0  5051.3     .05       0
Bank Sta=4992.3,4998.6
XS Rating Curve= 0 ,0
Exp/Cntr=0.3,0.1

Type RM Length L Ch R = 1 ,4517    ,1067,1067,1067
BEGIN DESCRIPTION:
DUCK CREEK TRIB 40 20
END DESCRIPTION:
XS GIS Cut Line= 4
      3495271.13     10430636.31      3494896.39     10430764.95
      3494451.72     10431329.88      3494230.83     10432126.79
#Sta/Elev= 30
  4073.6  429.54  4138.8  426.37  4263.8  417.75  4352.3  414.21  4389.8  411.43
  4453.2  408.09  4555.3  404.84  4665.1  404.23  4704.6   404.2  4786.2  403.98
  4872.9  403.47  4907.4  402.25  4925.7  401.63  4954.6  402.28  4986.6     401
  4987.1   400.5  4993.2     401  5018.8  401.46  5028.5  405.06  5039.6  406.85
  5068.5  407.82  5242.1  409.75  5256.9  409.98  5458.4  411.88    5601  413.51
  5667.9  414.04  5813.2  417.14  5896.2  417.77  5959.2  420.56  6015.7  420.85
#Mann= 13 ,-1 , 0
  4073.6     .05       0  4665.1     .16       0  4704.6     .05       0
  4786.2     .16       0  4872.9     .12       0  4907.4     .16       0
  4986.6     .07       0  4993.2     .16       0  5028.5     .05       0
  5242.1     .16       0  5256.9     .05       0  5458.4      .1       0
    5601     .05       0
Bank Sta=4986.6,4993.2
XS Rating Curve= 0 ,0
Exp/Cntr=0.3,0.1

Type RM Length L Ch R = 1 ,3450    ,552,552,552
BEGIN DESCRIPTION:
DUCK CREEK TRIB 40 10
END DESCRIPTION:
XS GIS Cut Line= 4
      3495019.42     10430107.74      3494773.34      10430132.9
      3493987.48     10430711.81      3493598.96     10430876.72
#Sta/Elev= 30
    4324  423.04  4381.6  421.87  4421.8  419.85  4441.9  419.31    4452  419.57
  4574.5  415.02  4599.2   413.4  4693.3  409.09  4707.9  407.79  4811.1  402.85
  4843.7  401.87  4858.3  400.94  4885.8   400.6  4893.8     401  4937.6     401
  5042.8     401  5144.2     401  5147.2  400.22  5147.7  399.72  5153.6  399.72
  5154.1  400.22  5156.9  400.64  5221.7  402.11  5330.4  403.77    5443  407.29
  5522.5  408.59  5635.7  412.18  5688.4  413.02  5879.2  421.87  5969.5  425.55
#Mann= 7 ,-1 , 0
    4324     .05       0  4811.1     .16       0  4885.8     .12       0
  4937.6     .16       0  5042.8     .05       0  5147.2     .07       0
  5154.1     .05       0
Bank Sta=5147.2,5154.1
XS Rating Curve= 0 ,0
Exp/Cntr=0.3,0.1

Type RM Length L Ch R = 1 ,2898    ,470,470,470
BEGIN DESCRIPTION:
DUCK CREEK TRIB 40 8 0
END DESCRIPTION:
XS GIS Cut Line= 4
      3494792.97     10429730.18      3494406.98     10429783.32
      3493685.44     10430311.89      3493205.77     10430420.65
#Sta/Elev= 30
  4086.2  417.82    4349  414.54  4460.6  412.25  4506.7  410.45  4599.8  404.98
  4664.6  402.14  4689.1  400.25  4689.6  399.75  4696.1  400.25  4700.1     401
  4955.7     401  5072.2     401  5078.4   401.9  5101.5  401.89  5148.7  404.22
  5157.9  404.98  5172.5  404.13  5178.7  402.67  5187.2  402.88  5214.3  407.67
  5258.2  410.12  5323.1  412.34  5369.2  414.79  5438.7  416.61  5609.5  422.98
    5630  424.55  5659.4  424.34  5722.3  425.76  5750.7  427.12  5862.1  429.26
#Mann= 5 ,-1 , 0
  4086.2     .05       0  4689.1     .07       0  4696.1     .05       0
  4955.7     .12       0  5148.7     .05       0
Bank Sta=4689.1,4696.1
XS Rating Curve= 0 ,0
Exp/Cntr=0.3,0.1