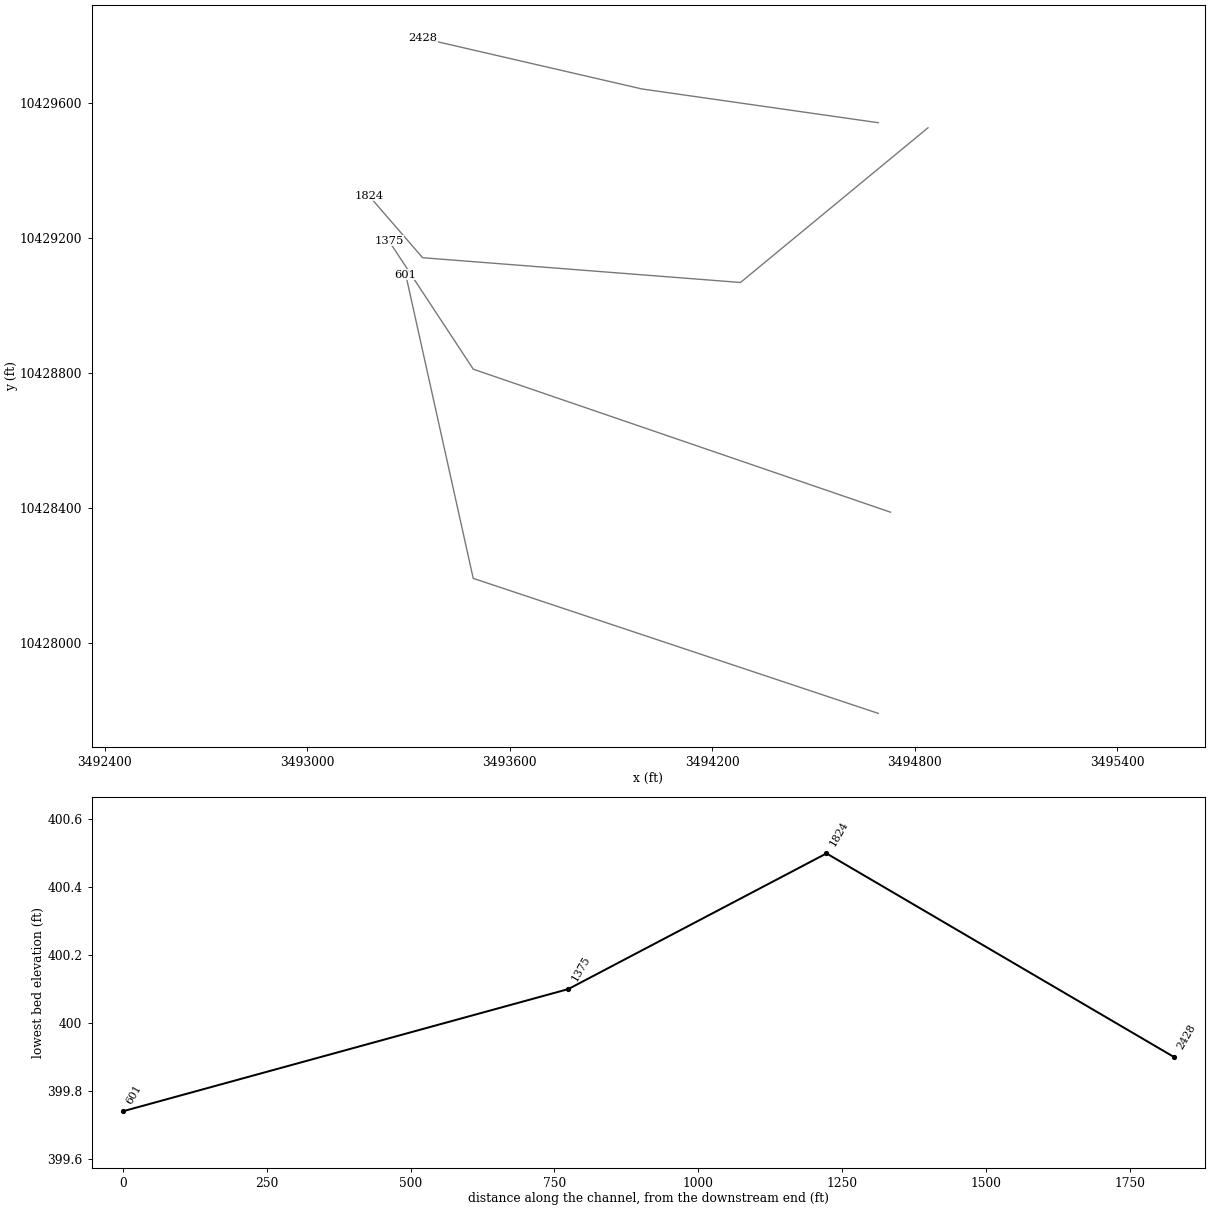
HEC-RAS study DUCK CREEK TRIB 40.prj: DUCK CREEK TRIB 40 Base Level Engineering

--- DUCK CREEK TRIB 40.g01 (geometry) --- (continued)

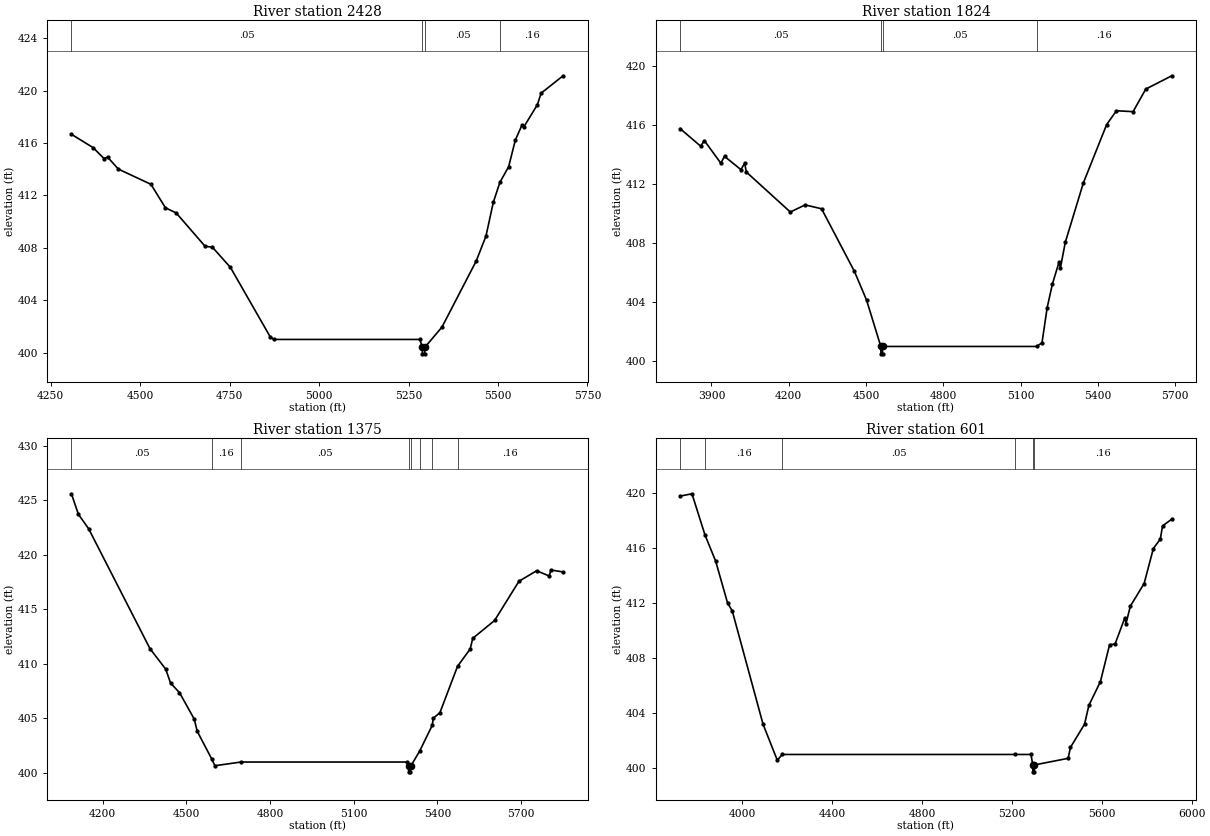
Type RM Length L Ch R = 1 ,2428    ,604,604,604
BEGIN DESCRIPTION:
DUCK CREEK TRIB 40 7 0
END DESCRIPTION:
XS GIS Cut Line= 3
      3494692.06     10429541.65      3493992.11     10429641.64
      3493342.15     10429791.63
#Sta/Elev= 30
  4307.9  416.67  4368.5  415.65  4398.8  414.82  4408.9  414.93  4439.2  414.01
  4530.1  412.85  4570.5  411.06  4600.8  410.66  4681.6  408.11  4701.8  408.05
  4752.3   406.5  4863.4   401.2  4873.5     401  5281.8     401  5288.5   400.4
    5289   399.9  5295.1   399.9  5295.6   400.4  5343.4  401.94  5439.2  406.99
  5466.5   408.9    5487  411.48  5505.7  413.02  5529.8  414.19  5548.6  416.24
  5567.4  417.39  5572.6  417.25  5610.2  418.93  5620.5  419.81    5682  421.14
#Mann= 4 ,-1 , 0
  4307.9     .05       0  5288.5    .033       0  5295.6     .05       0
  5505.7     .16       0
Bank Sta=5288.5,5295.6
XS Rating Curve= 0 ,0
Exp/Cntr=0.3,0.1

Type RM Length L Ch R = 1 ,1824    ,449,449,449
BEGIN DESCRIPTION:
DUCK CREEK TRIB 40 6 0
END DESCRIPTION:
XS GIS Cut Line= 4
      3494839.43     10429526.59      3494283.91     10429068.29
      3493342.11     10429141.64      3493183.24     10429325.21
#Sta/Elev= 30
  3778.6  415.76  3858.2  414.57  3872.6  414.95  3936.4  413.42  3950.8  413.88
  4014.6  412.98  4028.9  413.42  4035.4  412.82  4206.1  410.11  4263.5  410.59
  4327.3  410.33    4455  406.08  4502.2  404.13  4557.2     401  4557.7   400.5
  4563.8   400.5  4564.3     401  5161.7     401  5182.6  401.25  5202.7  403.63
  5222.8  405.22    5249  406.73  5254.1  406.32  5272.9  408.05  5343.1  412.08
  5433.4  416.03  5471.4  416.97    5536  416.91  5585.4  418.44  5686.2  419.34
#Mann= 4 ,-1 , 0
  3778.6     .05       0  4557.2    .033       0  4564.3     .05       0
  5161.7     .16       0
Bank Sta=4557.2,4564.3
XS Rating Curve= 0 ,0
Exp/Cntr=0.3,0.1

Type RM Length L Ch R = 1 ,1375    ,774,774,774
BEGIN DESCRIPTION:
DUCK CREEK TRIB 40 22 0
END DESCRIPTION:
XS GIS Cut Line= 3
      3494728.33     10428387.74      3493492.25     10428811.35
      3493242.13     10429191.61
#Sta/Elev= 30
  4088.3   425.6  4113.2  423.72  4149.8   422.4  4369.7   411.4    4426  409.52
  4443.7  408.23  4475.4  407.37  4528.3  404.94  4538.9  403.83  4590.2  401.32
  4602.3  400.66  4696.1     401  5291.3     401  5296.4   400.6  5296.9   400.1
  5303.1   400.1  5303.6   400.6  5336.1     402  5380.9  404.35  5385.1  405.02
  5408.8  405.53  5471.9  409.78  5517.2  411.37  5526.3  412.34  5604.6  413.98
    5692  417.58  5755.2  418.54  5800.5  418.06  5806.4  418.61  5850.1  418.43
#Mann= 8 ,-1 , 0
  4088.3     .05       0  4590.2     .16       0  4696.1     .05       0
  5296.4    .033       0  5303.6     .05       0  5336.1     .16       0
  5380.9     .12       0  5471.9     .16       0
Bank Sta=5296.4,5303.6
XS Rating Curve= 0 ,0
Exp/Cntr=0.3,0.1

Type RM Length L Ch R = 1 ,601     ,0,0,0
BEGIN DESCRIPTION:
DUCK CREEK TRIB 40 1 0
END DESCRIPTION:
XS GIS Cut Line= 3
      3494692.11     10427791.64      3493492.11     10428191.64
       3493292.1     10429091.67
#Sta/Elev= 30
  3724.7  419.74  3777.4  419.91  3835.1  416.93  3882.8  415.02  3935.5     412
  3956.6  411.41  4093.6  403.19  4156.9  400.58  4178.9     401  5214.5     401
  5285.4     401  5293.1  400.24  5293.6  399.74  5300.2  399.74  5300.7  400.24
  5450.6  400.72  5460.8  401.51  5523.6   403.2  5542.8  404.56    5594  406.28
    5635  408.96  5659.3  409.01  5702.9  410.92    5708  410.49  5727.2  411.76
  5788.6   413.4  5829.6  415.94  5860.4  416.62  5870.6  417.58  5911.6  418.07
#Mann= 6 ,-1 , 0
  3724.7     .05       0  3835.1     .16       0  4178.9     .05       0
  5214.5     .16       0  5293.1    .033       0  5300.7     .16       0
Bank Sta=5293.1,5300.7
XS Rating Curve= 0 ,0
Exp/Cntr=0.3,0.1

Chan Stop Cuts=-1
Use User Specified Reach Order=0
Composite Channel Slope=5