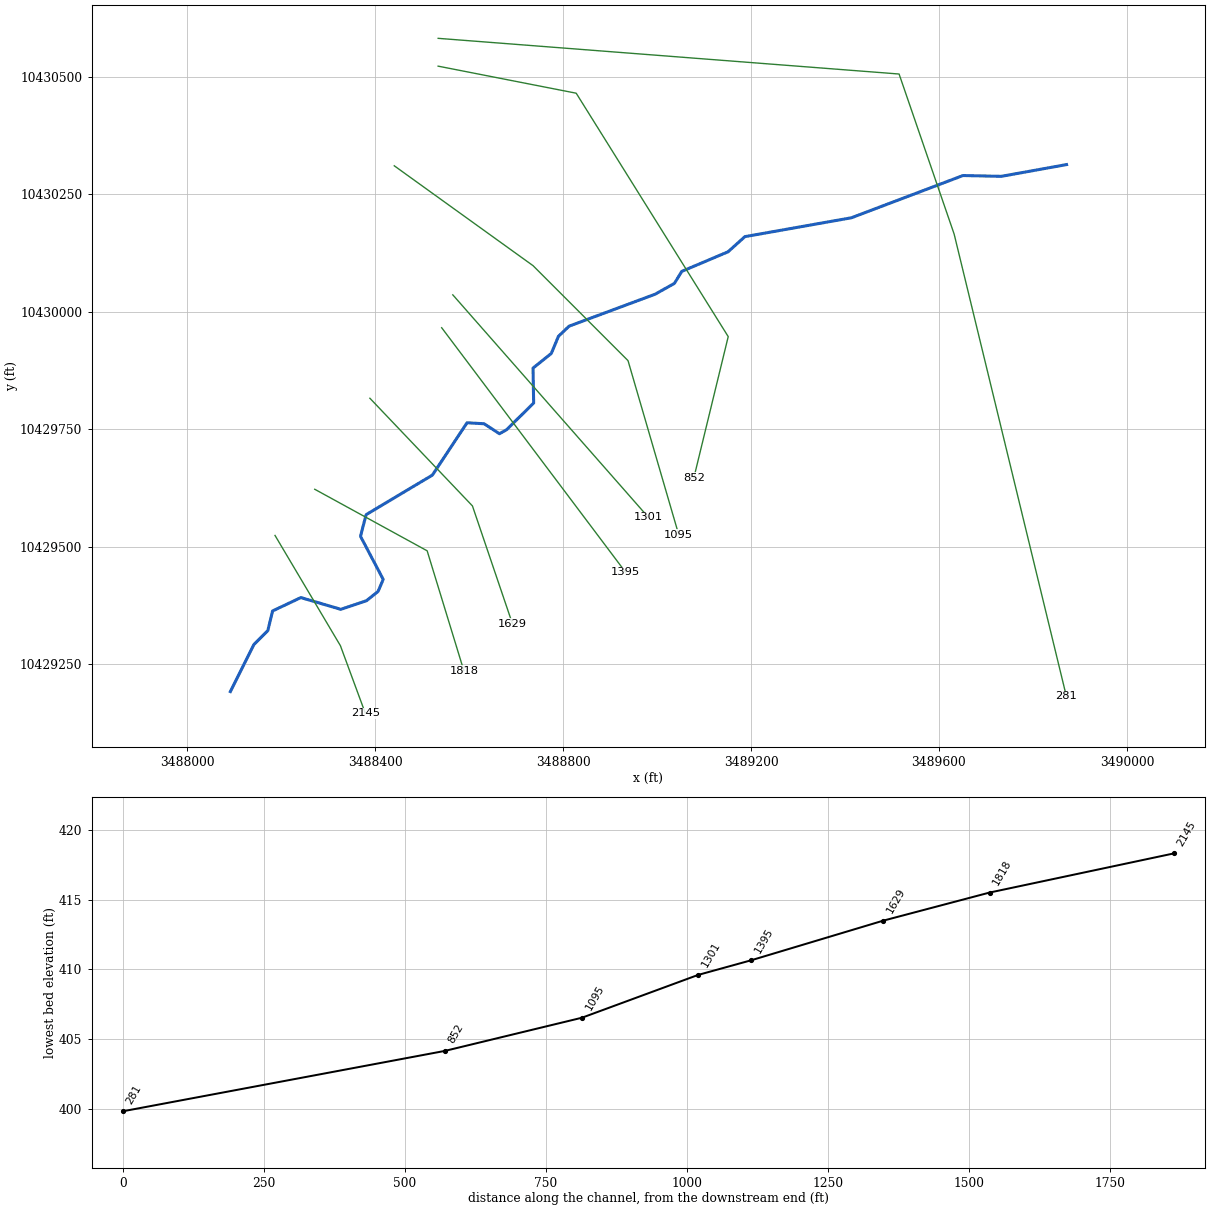
--- DUCK CREEK TRIB 42.prj (project) ---

Proj Title=DUCK CREEK TRIB 42 Base Level Engineering
Current Plan=p01
Default Exp/Contr=0.3,0.1
English Units
Geom File=g01
Flow File=f01
Plan File=p01
BEGIN DESCRIPTION:
DUCK CREEK TRIB 42
END DESCRIPTION:

--- DUCK CREEK TRIB 42.p01 (plan) ---

Plan Title=Multiple Run
Short Identifier=Multiple
Geom File=g01
Flow File=f01
Subcritical Flow
K Sum by GR= 0
Std Step Tol= 0.01
Critical Tol= 0.01
Num of Std Step Trials= 20
Max Error Tol= 0.3
Flow Tol Ratio= 0.001
Split Flow NTrial= 30
Split Flow Tol= 0.02
Split Flow Ratio= 0.02
Log Output Level= 0
Friction Slope Method= 1
Unsteady Friction Slope Method= 2
Unsteady Bridges Friction Slope Method= 1
Parabolic Critical Depth
Global Vel Dist=  1 , 1 , 1
Global Log Level= 0
CheckData=True
Encroach Param= -1, 0, 0, 0
BEGIN DESCRIPTION:
Multiple Run
END DESCRIPTION:

--- DUCK CREEK TRIB 42.f01 (steady flow) ---

Flow Title=Multiple
Number of Profiles=7
Profile Names=10-year,25-year,50-year,1pct_min,100-year,1pct_plu,500-year
River Rch & RM= DUCK CREEK TRIB ,Reach-1,2145
     440     581     694     607     821    1110    1144
Boundary for River Rch & Prof#=DUCK CREEK TRIB ,Reach-1,1
Up Type=0
Dn Type=3
Dn Slope=0.005
Boundary for River Rch & Prof#=DUCK CREEK TRIB ,Reach-1,2
Up Type=0
Dn Type=3
Dn Slope=0.005
Boundary for River Rch & Prof#=DUCK CREEK TRIB ,Reach-1,3
Up Type=0
Dn Type=3
Dn Slope=0.005
Boundary for River Rch & Prof#=DUCK CREEK TRIB ,Reach-1,4
Up Type=0
Dn Type=3
Dn Slope=0.005
Boundary for River Rch & Prof#=DUCK CREEK TRIB ,Reach-1,5
Up Type=0
Dn Type=3
Dn Slope=0.005
Boundary for River Rch & Prof#=DUCK CREEK TRIB ,Reach-1,6
Up Type=0
Dn Type=3
Dn Slope=0.005
Boundary for River Rch & Prof#=DUCK CREEK TRIB ,Reach-1,7
Up Type=0
Dn Type=3
Dn Slope=0.005

--- DUCK CREEK TRIB 42.g01 (geometry) ---

Geom Title=Existing Conditions

River Reach=DUCK CREEK TRIB ,Reach-1
Reach XY= 30
      3488092.11     10429191.64      3488142.11     10429291.64
      3488171.77     10429321.31      3488181.93     10429363.24
      3488242.11     10429391.64      3488327.11     10429366.64
      3488381.60     10429384.93      3488406.40     10429404.73
      3488417.29     10429430.38      3488368.95     10429522.08
      3488380.99     10429568.15      3488521.89     10429652.21
      3488595.75     10429763.64      3488631.95     10429761.55
      3488664.71     10429740.29      3488680.01     10429748.97
      3488737.47     10429805.62      3488736.10     10429879.95
      3488775.05     10429911.20      3488790.30     10429947.73
      3488812.89     10429969.20      3488996.04     10430037.24
      3489037.00     10430060.25      3489052.62     10430085.77
      3489151.06     10430127.44      3489187.00     10430159.73
      3489413.56     10430199.83      3489651.06     10430289.76
      3489732.66     10430288.03      3489871.49     10430313.05

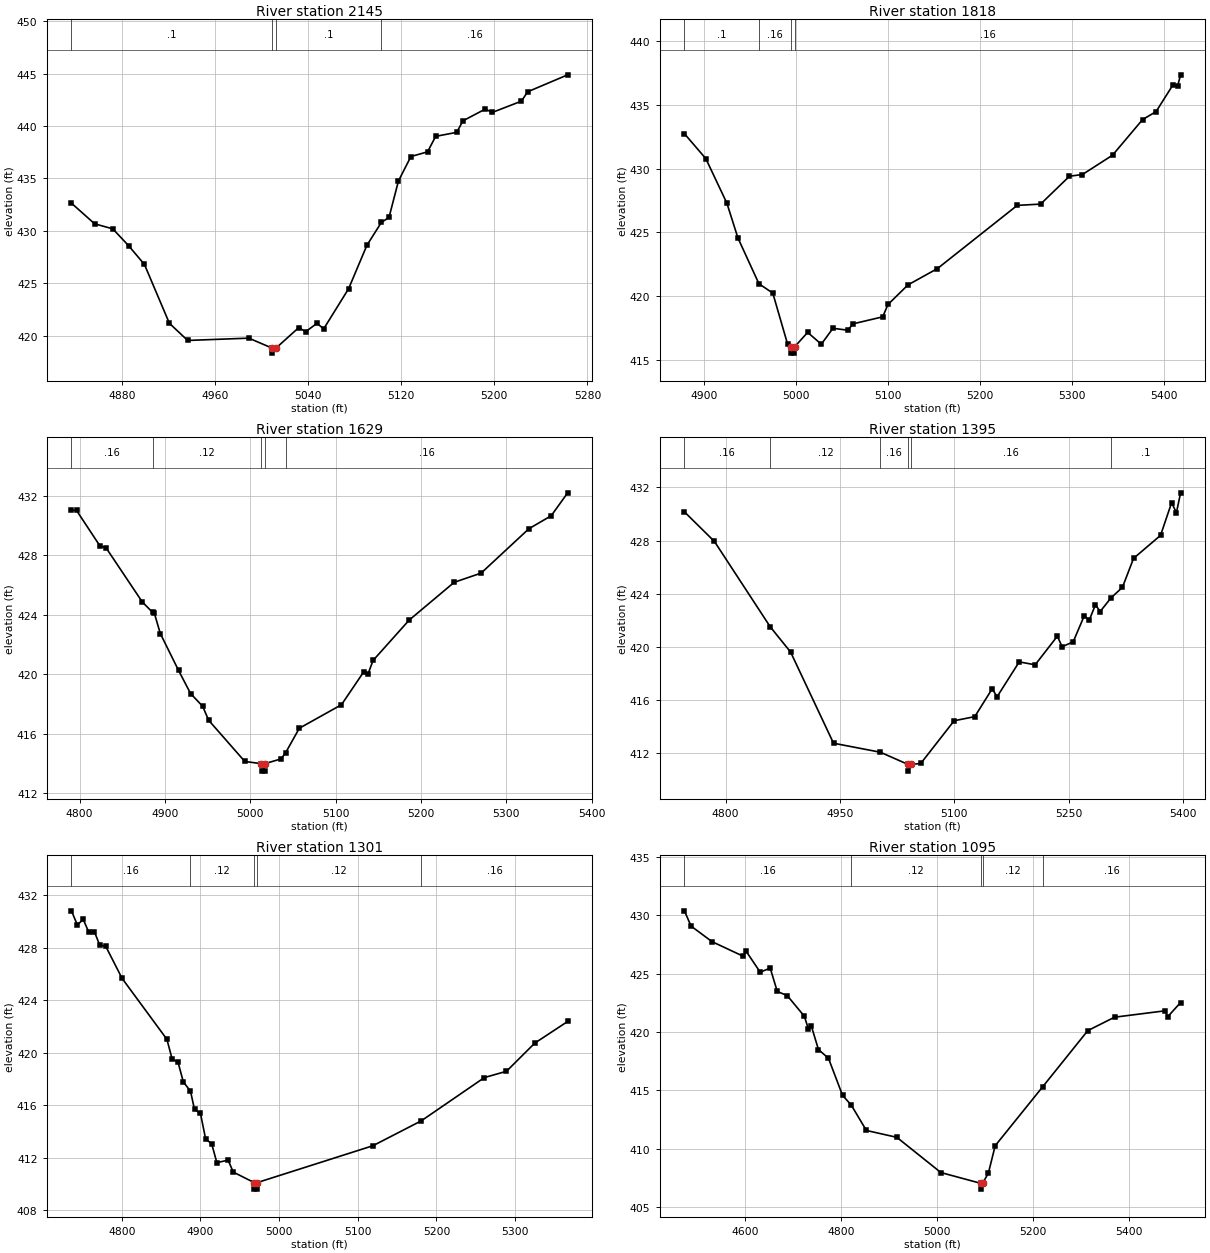
Type RM Length L Ch R = 1,2145,327,327,327
BEGIN DESCRIPTION:
DUCK CREEK TRIB 42 10
END DESCRIPTION:
XS GIS Cut Line= 3
      3488187.07     10429523.89      3488326.21     10429289.27
      3488379.33     10429145.23
#Sta/Elev= 30
  4836.7  432.63  4856.6  430.66  4872.2  430.18  4885.8  428.57  4899.4  426.78
  4920.8  421.17  4936.5  419.53  4989.1  419.75  5008.6  418.82  5008.8  418.32
  5012.6  418.82  5032.0  420.76  5037.8  420.36  5047.6  421.16  5053.4  420.64
  5074.8  424.47  5090.5  428.61  5102.9  430.79  5109.5  431.27  5117.6  434.75
  5128.3  437.08  5142.6  437.53  5149.6  439.01  5167.7  439.39  5173.0  440.49
  5192.2  441.61  5198.2  441.29  5223.3  442.37  5228.6  443.26  5263.0  444.88
#Mann=4,-1,0
  4836.7     0.1       0  5008.6    0.07       0  5012.6     0.1       0
  5102.9    0.16       0
Bank Sta=5008.6,5012.6
Exp/Cntr=0.3,0.1

Type RM Length L Ch R = 1,1818,189,189,189
BEGIN DESCRIPTION:
DUCK CREEK TRIB 42 5 2
END DESCRIPTION:
XS GIS Cut Line= 3
      3488271.63     10429622.13      3488510.82     10429491.16
      3488588.87     10429236.14
#Sta/Elev= 30
  4878.3  432.74  4901.6  430.78  4924.5  427.28  4936.5  424.55  4959.3  420.96
  4974.4  420.22  4990.5  416.21  4994.2  416.01  4994.4  415.51  4997.9  415.51
  4998.2  416.01  5012.3  417.14  5027.1  416.21  5039.8  417.46  5055.9  417.31
  5061.6  417.81  5093.9  418.36  5099.6  419.33  5121.4  420.87  5153.4  422.15
  5240.1  427.11  5265.5  427.21  5296.9  429.40  5310.9  429.53  5343.7  431.05
  5376.4  433.85  5391.0  434.47  5409.2  436.55  5414.4  436.47  5417.7  437.36
#Mann=4,-1,0
  4878.3     0.1       0  4959.3    0.16       0  4994.2    0.07       0
  4998.2    0.16       0
Bank Sta=4994.2,4998.2
Exp/Cntr=0.3,0.1

Type RM Length L Ch R = 1,1629,234,234,234
BEGIN DESCRIPTION:
DUCK CREEK TRIB 42 3 0
END DESCRIPTION:
XS GIS Cut Line= 3
      3488388.97     10429815.80      3488607.21     10429586.65
      3488692.39     10429335.66
#Sta/Elev= 30
  4790.4  431.00  4796.3  431.00  4823.8  428.61  4830.9  428.49  4873.4  424.85
  4885.5  424.15  4887.6  424.08  4894.5  422.73  4915.9  420.25  4930.0  418.70
  4944.2  417.84  4951.1  416.91  4993.5  414.14  5012.9  413.99  5013.2  413.49
  5016.7  413.49  5016.9  413.99  5036.0  414.31  5041.5  414.74  5057.4  416.37
  5106.8  417.95  5132.8  420.15  5138.1  420.04  5143.8  420.92  5186.1  423.63
  5238.9  426.17  5270.5  426.79  5326.5  429.77  5352.6  430.64  5371.9  432.18
#Mann=5,-1,0
  4790.4    0.16       0  4885.5    0.12       0  5012.9    0.07       0
  5016.9    0.12       0  5041.5    0.16       0
Bank Sta=5012.9,5016.9
Exp/Cntr=0.3,0.1

Type RM Length L Ch R = 1,1395,94,94,94
BEGIN DESCRIPTION:
DUCK CREEK TRIB 42 5 1
END DESCRIPTION:
XS GIS Cut Line= 2
      3488541.74     10429965.87      3488933.00     10429445.70
#Sta/Elev= 30
  4746.0  430.16  4785.4  427.93  4858.7  421.50  4885.3  419.61  4941.6  412.75
  5003.2  412.07  5039.5  411.15  5039.8  410.65  5043.5  411.15  5056.1  411.23
  5099.8  414.44  5126.9  414.75  5149.8  416.85  5156.1  416.24  5185.2  418.87
  5206.1  418.65  5235.2  420.80  5241.5  420.01  5256.0  420.38  5270.6  422.35
  5276.9  421.99  5285.2  423.17  5291.4  422.66  5305.5  423.68  5320.6  424.48
  5335.2  426.66  5370.6  428.39  5385.1  430.85  5391.4  430.09  5396.9  431.59
#Mann=6,-1,0
  4746.0    0.16       0  4858.7    0.12       0  5003.2    0.16       0
  5039.5    0.07       0  5043.5    0.16       0  5305.5     0.1       0
Bank Sta=5039.5,5043.5
Exp/Cntr=0.3,0.1

Type RM Length L Ch R = 1,1301,206,206,206
BEGIN DESCRIPTION:
DUCK CREEK TRIB 42 3 1
END DESCRIPTION:
XS GIS Cut Line= 2
      3488565.41     10430035.86      3488981.88     10429562.10
#Sta/Elev= 30
  4736.0  430.83  4743.4  429.76  4751.0  430.17  4757.7  429.24  4765.2  429.23
  4771.9  428.21  4779.5  428.13  4800.3  425.68  4857.3  421.03  4863.9  419.54
  4871.5  419.27  4878.2  417.78  4887.3  417.07  4892.4  415.68  4900.0  415.37
  4906.6  413.41  4914.2  413.07  4920.8  411.62  4935.1  411.81  4941.7  410.90
  4968.2  410.10  4968.4  409.60  4971.9  409.60  4972.2  410.10  5119.2  412.91
  5180.7  414.81  5260.9  418.11  5289.0  418.59  5325.0  420.74  5366.8  422.39
#Mann=5,-1,0
  4736.0    0.16       0  4887.3    0.12       0  4968.2    0.07       0
  4972.2    0.12       0  5180.7    0.16       0
Bank Sta=4968.2,4972.2
Exp/Cntr=0.3,0.1

Type RM Length L Ch R = 1,1095,243,243,243
BEGIN DESCRIPTION:
DUCK CREEK TRIB 42 4 0
END DESCRIPTION:
XS GIS Cut Line= 4
      3488440.83     10430310.48      3488736.17     10430097.93
      3488938.29     10429895.81      3489046.07     10429525.79
#Sta/Elev= 30
  4473.4  430.39  4487.3  429.08  4530.9  427.75  4595.9  426.50  4602.1  426.93
  4631.5  425.13  4652.4  425.48  4667.1  423.48  4688.0  423.12  4723.6  421.35
  4732.1  420.26  4738.3  420.50  4753.0  418.50  4773.9  417.75  4803.3  414.57
  4821.4  413.74  4853.0  411.56  4916.6  410.97  5008.5  407.95  5091.4  407.03
  5091.6  406.53  5095.4  407.03  5107.5  407.90  5121.7  410.25  5220.9  415.31
  5314.9  420.12  5370.7  421.27  5476.4  421.82  5481.6  421.31  5508.5  422.53
#Mann=5,-1,0
  4473.4    0.16       0  4821.4    0.12       0  5091.4    0.07       0
  5095.4    0.12       0  5220.9    0.16       0
Bank Sta=5091.4,5095.4
Exp/Cntr=0.3,0.1

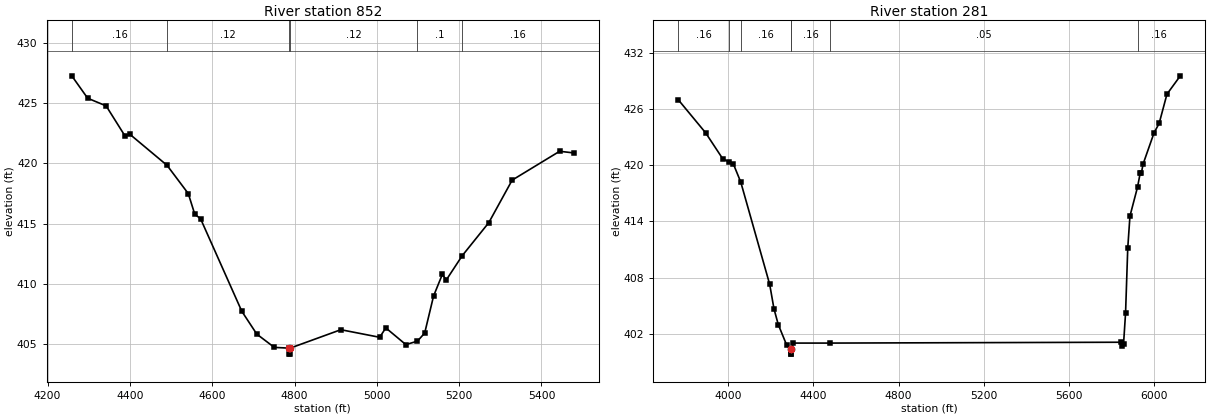
Type RM Length L Ch R = 1,852,571,571,571
BEGIN DESCRIPTION:
DUCK CREEK TRIB 42 4 1
END DESCRIPTION:
XS GIS Cut Line= 4
      3488534.25     10430522.51      3488828.00     10430464.95
      3489151.49     10429946.97      3489078.23     10429646.00
#Sta/Elev= 30
  4258.8  427.28  4297.4  425.42  4342.3  424.78  4388.7  422.25  4399.3  422.44
  4490.3  419.84  4541.9  417.49  4557.7  415.77  4571.6  415.41  4671.9  407.71
  4708.4  405.81  4750.9  404.71  4785.5  404.65  4785.7  404.15  4789.2  404.15
  4789.5  404.65  4912.5  406.18  5006.8  405.55  5021.8  406.33  5070.5  404.94
  5098.6  405.23  5116.2  405.90  5137.8  408.98  5159.0  410.77  5168.8  410.32
  5207.4  412.33  5272.0  415.08  5328.7  418.61  5444.1  421.01  5478.6  420.87
#Mann=6,-1,0
  4258.8    0.16       0  4490.3    0.12       0  4785.5    0.07       0
  4789.5    0.12       0  5098.6     0.1       0  5207.4    0.16       0
Bank Sta=4785.5,4789.5
Exp/Cntr=0.3,0.1

Type RM Length L Ch R = 1,281,0,0,0
BEGIN DESCRIPTION:
DUCK CREEK TRIB 42 1 0
END DESCRIPTION:
XS GIS Cut Line= 4
      3488534.24     10430581.71      3489515.09     10430505.76
      3489632.28     10430165.05      3489870.99     10429182.01
#Sta/Elev= 30
  3766.5  426.99  3894.8  423.46  3975.0  420.69  4003.1  420.36  4025.1  420.13
  4059.9  418.19  4195.6  407.27  4215.7  404.66  4235.8  402.98  4275.9  400.75
  4293.9  400.32  4294.2  399.82  4297.7  399.82  4297.9  400.32  4306.0  401.00
  4479.8  401.00  5844.7  401.09  5850.7  400.68  5855.8  400.88  5865.3  404.20
  5875.6  411.15  5885.9  414.56  5921.4  417.65  5934.2  419.18  5939.4  419.15
  5947.6  420.12  5999.1  423.46  6022.9  424.46  6059.5  427.58  6122.2  429.54
#Mann=7,-1,0
  3766.5    0.16       0  4003.1    0.12       0  4059.9    0.16       0
  4293.9   0.033       0  4297.9    0.16       0  4479.8    0.05       0
  5921.4    0.16       0
Bank Sta=4293.9,4297.9
Exp/Cntr=0.3,0.1

Chan Stop Cuts=-1