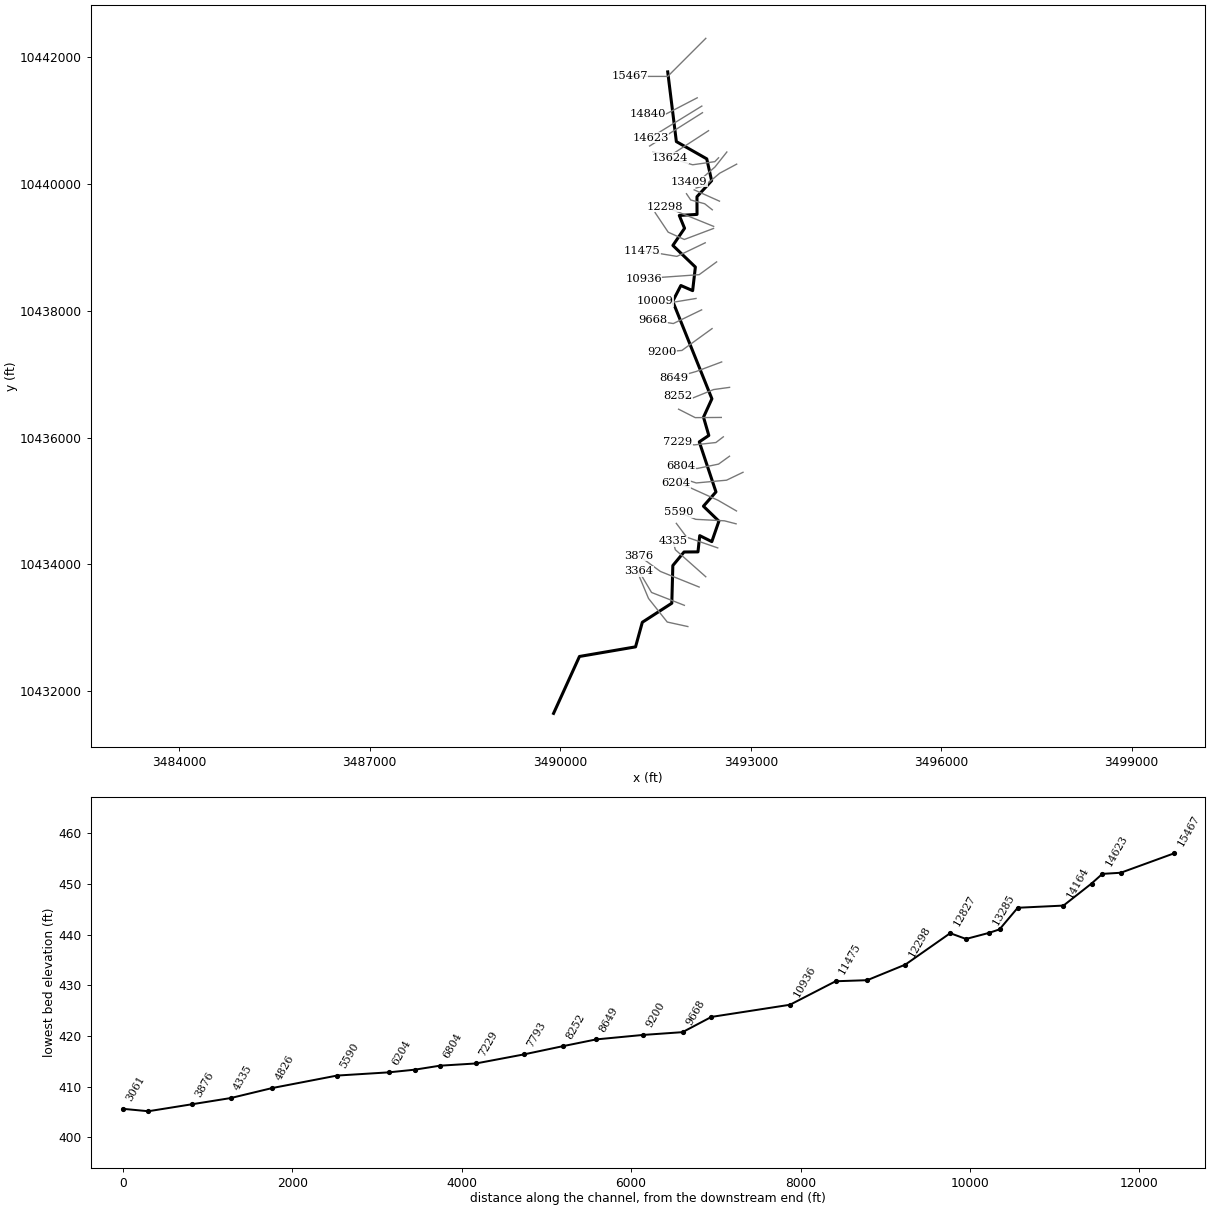
--- DUCK CREEK TRIB 43.prj (project) ---

Proj Title=DUCK CREEK TRIB 43 Base Level Engineering
Current Plan=p01
Default Exp/Contr=0.3,0.1
English Units
Geom File=g01
Flow File=f01
Plan File=p01
BEGIN DESCRIPTION:
DUCK CREEK TRIB 43
END DESCRIPTION:

--- DUCK CREEK TRIB 43.p01 (plan) ---

Plan Title=Multiple Run
Short Identifier=Multiple
Geom File=g01
Flow File=f01
Subcritical Flow
K Sum by GR= 0
Std Step Tol= 0.01
Critical Tol= 0.01
Num of Std Step Trials= 20
Max Error Tol= 0.3
Flow Tol Ratio= 0.001
Split Flow NTrial= 30
Split Flow Tol= 0.02
Split Flow Ratio= 0.02
Log Output Level= 0
Friction Slope Method= 1
Unsteady Friction Slope Method= 2
Unsteady Bridges Friction Slope Method= 1
Parabolic Critical Depth
Global Vel Dist=  1 , 1 , 1
Global Log Level= 0
CheckData=True
Encroach Param= -1, 0, 0, 0
BEGIN DESCRIPTION:
Multiple Run
END DESCRIPTION:

--- DUCK CREEK TRIB 43.f01 (steady flow) ---

Flow Title=Multiple
Number of Profiles=7
Profile Names=10-year,25-year,50-year,1pct_min,100-year,1pct_plu,500-year
River Rch & RM= DUCK CREEK TRIB ,Reach-1,15467
     604     809     973     856    1157    1565    1631
River Rch & RM= DUCK CREEK TRIB ,Reach-1,11475
     887    1215    1485    1324    1791    2421    2597
River Rch & RM= DUCK CREEK TRIB ,Reach-1,8649
    1104    1522    1867    1668    2256    3051    3289
Boundary for River Rch & Prof#=DUCK CREEK TRIB ,Reach-1,1
Up Type=0
Dn Type=3
Dn Slope=0.005
Boundary for River Rch & Prof#=DUCK CREEK TRIB ,Reach-1,2
Up Type=0
Dn Type=3
Dn Slope=0.005
Boundary for River Rch & Prof#=DUCK CREEK TRIB ,Reach-1,3
Up Type=0
Dn Type=3
Dn Slope=0.005
Boundary for River Rch & Prof#=DUCK CREEK TRIB ,Reach-1,4
Up Type=0
Dn Type=3
Dn Slope=0.005
Boundary for River Rch & Prof#=DUCK CREEK TRIB ,Reach-1,5
Up Type=0
Dn Type=3
Dn Slope=0.005
Boundary for River Rch & Prof#=DUCK CREEK TRIB ,Reach-1,6
Up Type=0
Dn Type=3
Dn Slope=0.005
Boundary for River Rch & Prof#=DUCK CREEK TRIB ,Reach-1,7
Up Type=0
Dn Type=3
Dn Slope=0.005

--- DUCK CREEK TRIB 43.g01 (geometry) ---

Geom Title=Existing Conditions

River Reach=DUCK CREEK TRIB ,Reach-1
Reach XY= 30
      3491692.47     10441762.83      3491828.40     10440664.42
      3492307.22     10440392.19      3492383.87     10440047.75
      3492153.04     10439795.88      3492153.98     10439516.67
      3491874.60     10439500.09      3491957.58     10439298.11
      3491773.67     10439027.70      3492127.75     10438687.08
      3492084.88     10438315.34      3491899.30     10438395.96
      3491771.31     10438147.11      3492388.16     10436610.88
      3492256.06     10436320.96      3492339.66     10436032.66
      3492189.54     10435932.11      3492452.18     10435143.02
      3492254.66     10434917.96      3492498.40     10434682.28
      3492386.79     10434359.54      3492196.46     10434454.09
      3492168.84     10434197.90      3491949.46     10434196.27
      3491772.85     10433982.73      3491756.79     10433388.98
      3491292.38     10433088.64      3491185.78     10432701.14
      3490302.45     10432549.75      3489894.64     10431652.87

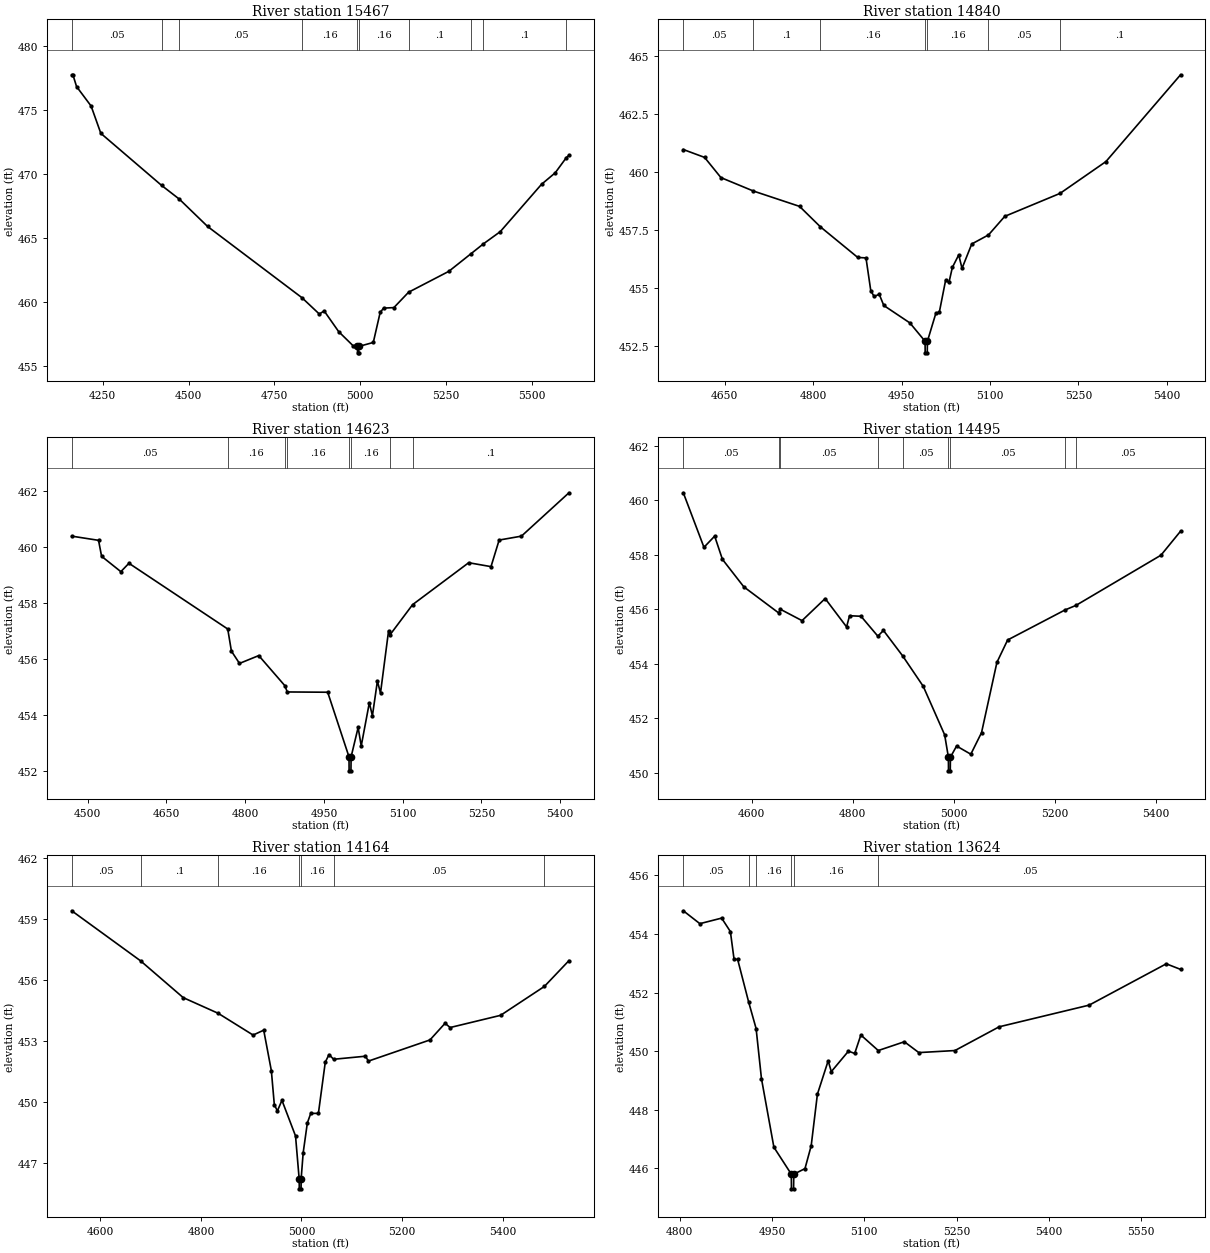
Type RM Length L Ch R = 1,15467,627,627,627
BEGIN DESCRIPTION:
DUCK CREEK TRIB 43 5 0
END DESCRIPTION:
XS GIS Cut Line= 3
      3492292.08     10442291.61      3491692.11     10441691.64
      3491092.09     10441691.64
#Sta/Elev= 30
  4159.7  477.73  4163.2  477.73  4173.8  476.81  4216.2  475.29  4244.5  473.16
  4421.8  469.09  4473.4  468.02  4555.6  465.89  4830.5  460.33  4880.9  459.06
  4895.1  459.30  4937.5  457.68  4979.9  456.57  4992.0  456.53  4992.3  456.03
  4995.8  456.03  4996.0  456.53  5038.2  456.84  5058.2  459.18  5068.2  459.52
  5098.2  459.56  5141.0  460.76  5258.2  462.39  5323.5  463.78  5358.7  464.53
  5408.2  465.49  5528.2  469.18  5568.2  470.08  5600.7  471.27  5608.2  471.44
#Mann=10,-1,0
  4159.7    0.05       0  4421.8     0.1       0  4473.4    0.05       0
  4830.5    0.16       0  4992.0    0.07       0  4996.0    0.16       0
  5141.0     0.1       0  5323.5    0.05       0  5358.7     0.1       0
  5600.7    0.05       0
Bank Sta=4992,4996
Exp/Cntr=0.3,0.1

Type RM Length L Ch R = 1,14840,217,217,217
BEGIN DESCRIPTION:
DUCK CREEK TRIB 43 4 0
END DESCRIPTION:
XS GIS Cut Line= 3
      3492157.11     10441354.32      3491669.17     10441100.94
      3491375.48     10441099.50
#Sta/Elev= 30
  4579.8  460.97  4615.9  460.63  4643.6  459.76  4698.8  459.18  4777.0  458.52
  4812.3  457.64  4875.7  456.32  4889.7  456.30  4897.8  454.89  4903.4  454.64
  4912.2  454.73  4919.9  454.25  4964.1  453.50  4989.9  452.71  4990.1  452.21
  4993.6  452.21  4993.9  452.71  5008.4  453.93  5014.0  453.95  5024.8  455.34
  5030.5  455.25  5036.2  455.89  5047.0  456.43  5052.6  455.85  5069.1  456.90
  5097.5  457.29  5125.1  458.09  5218.9  459.08  5296.7  460.45  5423.3  464.19
#Mann=7,-1,0
  4579.8    0.05       0  4698.8     0.1       0  4812.3    0.16       0
  4989.9    0.07       0  4993.9    0.16       0  5097.5    0.05       0
  5218.9     0.1       0
Bank Sta=4989.9,4993.9
Exp/Cntr=0.3,0.1

Type RM Length L Ch R = 1,14623,128,128,128
BEGIN DESCRIPTION:
DUCK CREEK TRIB 43 31 0
END DESCRIPTION:
XS GIS Cut Line= 2
      3492229.57     10441224.04      3491423.02     10440727.37
#Sta/Elev= 30
  4469.6  460.38  4520.7  460.23  4526.5  459.66  4563.2  459.11  4578.6  459.41
  4766.8  457.06  4773.8  456.27  4789.2  455.83  4825.9  456.11  4875.8  455.03
  4880.1  454.81  4957.2  454.80  4997.8  452.49  4998.0  451.99  5001.5  451.99
  5001.8  452.49  5015.2  453.54  5021.1  452.88  5036.5  454.42  5042.4  453.96
  5051.9  455.20  5057.8  454.77  5073.2  457.00  5075.8  456.85  5118.9  457.93
  5225.8  459.43  5268.3  459.29  5283.8  460.24  5326.3  460.38  5416.8  461.93
#Mann=8,-1,0
  4469.6    0.05       0  4766.8    0.16       0  4875.8    0.05       0
  4880.1    0.16       0  4997.8    0.07       0  5001.8    0.16       0
  5075.8    0.05       0  5118.9     0.1       0
Bank Sta=4997.8,5001.8
Exp/Cntr=0.3,0.1

Type RM Length L Ch R = 1,14495,331,331,331
BEGIN DESCRIPTION:
DUCK CREEK TRIB 43 3 0
END DESCRIPTION:
XS GIS Cut Line= 2
      3492239.68     10441119.77      3491407.11     10440594.16
#Sta/Elev= 30
  4464.9  460.28  4505.8  458.28  4527.0  458.69  4542.3  457.84  4584.7  456.83
  4653.9  455.87  4656.8  456.01  4700.0  455.59  4745.8  456.40  4788.2  455.36
  4794.1  455.77  4816.8  455.75  4850.1  455.02  4861.2  455.23  4899.1  454.30
  4940.0  453.18  4982.4  451.40  4989.8  450.58  4990.0  450.08  4993.5  450.08
  4993.8  450.58  5006.0  450.99  5034.2  450.69  5055.4  451.48  5085.9  454.06
  5107.1  454.88  5220.6  455.98  5242.5  456.15  5410.7  457.99  5449.5  458.87
#Mann=9,-1,0
  4464.9    0.05       0  4653.9    0.16       0  4656.8    0.05       0
  4850.1    0.16       0  4899.1    0.05       0  4989.8    0.04       0
  4993.8    0.05       0  5220.6     0.1       0  5242.5    0.05       0
Bank Sta=4989.8,4993.8
Exp/Cntr=0.3,0.1

Type RM Length L Ch R = 1,14164,540,540,540
BEGIN DESCRIPTION:
DUCK CREEK TRIB 43 29 0
END DESCRIPTION:
XS GIS Cut Line= 3
      3492335.25     10440835.97      3491766.19     10440466.73
      3491456.67     10440494.21
#Sta/Elev= 30
  4543.0  459.40  4679.9  456.94  4764.8  455.13  4834.3  454.36  4903.8  453.29
  4924.9  453.53  4940.1  451.54  4946.0  449.87  4952.1  449.56  4961.2  450.08
  4988.2  448.33  4995.4  446.23  4995.7  445.73  4999.2  445.73  4999.4  446.23
  5003.4  447.50  5011.7  448.97  5018.5  449.44  5033.7  449.44  5047.4  451.96
  5054.8  452.33  5064.0  452.10  5127.3  452.25  5133.2  452.01  5255.6  453.05
  5285.7  453.87  5295.7  453.66  5396.1  454.26  5483.2  455.68  5532.1  456.95
#Mann=7,-1,0
  4543.0    0.05       0  4679.9     0.1       0  4834.3    0.16       0
  4995.4    0.07       0  4999.4    0.16       0  5064.0    0.05       0
  5483.2     0.1       0
Bank Sta=4995.4,4999.4
Exp/Cntr=0.3,0.1

Type RM Length L Ch R = 1,13624,215,215,215
BEGIN DESCRIPTION:
DUCK CREEK TRIB 43 29 1
END DESCRIPTION:
XS GIS Cut Line= 4
      3492493.05     10440408.79      3492433.70     10440348.00
      3492084.74     10440298.77      3491729.94     10440405.93
#Sta/Elev= 30
  4805.9  454.79  4832.8  454.35  4868.2  454.54  4882.4  454.08  4888.4  453.13
  4894.2  453.13  4911.9  451.69  4924.2  450.77  4932.9  449.06  4953.1  446.72
  4981.4  445.80  4981.6  445.30  4985.1  445.30  4985.4  445.80  5003.6  445.99
  5013.7  446.77  5023.8  448.53  5041.3  449.67  5046.4  449.30  5074.3  450.00
  5084.4  449.92  5094.4  450.55  5122.7  450.02  5165.1  450.32  5188.6  449.95
  5247.3  450.02  5319.1  450.83  5465.4  451.57  5590.7  452.98  5613.9  452.79
#Mann=6,-1,0
  4805.9    0.05       0  4911.9     0.1       0  4924.2    0.16       0
  4981.4    0.07       0  4985.4    0.16       0  5122.7    0.05       0
Bank Sta=4981.4,4985.4
Exp/Cntr=0.3,0.1

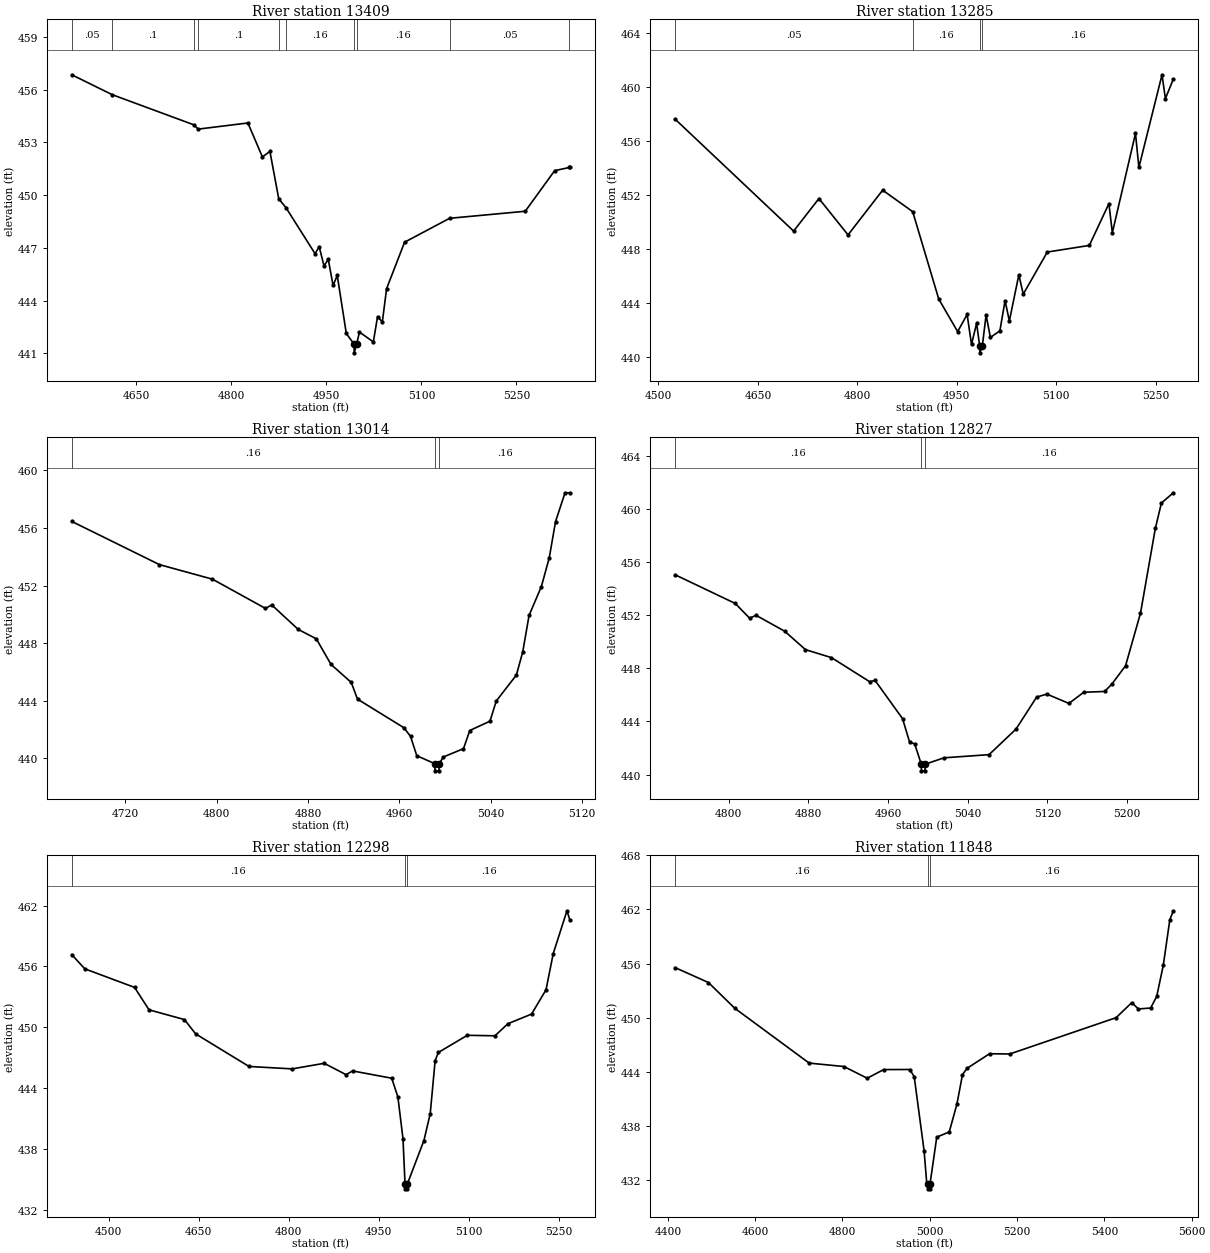
Type RM Length L Ch R = 1,13409,124,124,124
BEGIN DESCRIPTION:
DUCK CREEK TRIB 43 27 0
END DESCRIPTION:
XS GIS Cut Line= 4
      3492623.39     10440500.05      3492436.59     10440264.01
      3492207.82     10440064.20      3492028.30     10440035.24
#Sta/Elev= 30
  4547.9  456.84  4611.7  455.71  4741.0  453.99  4747.5  453.75  4826.0  454.10
  4848.9  452.17  4860.8  452.48  4874.7  449.79  4886.2  449.28  4932.0  446.67
  4938.6  447.06  4946.2  445.97  4952.9  446.35  4960.5  444.86  4967.1  445.43
  4981.4  442.13  4993.6  441.53  4993.9  441.03  4997.6  441.53  5002.2  442.21
  5024.1  441.65  5030.7  443.09  5038.3  442.79  5045.0  444.68  5073.4  447.32
  5144.5  448.68  5263.9  449.08  5310.4  451.39  5333.7  451.57  5334.5  451.57
#Mann=10,-1,0
  4547.9    0.05       0  4611.7     0.1       0  4741.0    0.05       0
  4747.5     0.1       0  4874.7    0.05       0  4886.2    0.16       0
  4993.6    0.07       0  4997.6    0.16       0  5144.5    0.05       0
  5333.7    0.16       0
Bank Sta=4993.6,4997.6
Exp/Cntr=0.3,0.1

Type RM Length L Ch R = 1,13285,271,271,271
BEGIN DESCRIPTION:
DUCK CREEK TRIB 43 28 0
END DESCRIPTION:
XS GIS Cut Line= 4
      3492778.35     10440308.92      3492510.44     10440165.55
      3492280.21     10439970.08      3492139.75     10439932.43
#Sta/Elev= 30
  4525.2  457.63  4703.8  449.35  4742.0  451.76  4785.9  449.07  4838.1  452.38
  4883.4  450.79  4922.7  444.32  4951.2  441.91  4965.5  443.18  4972.1  440.96
  4979.8  442.53  4984.4  440.84  4984.6  440.34  4988.4  440.84  4994.1  443.14
  5000.6  441.48  5014.9  441.97  5022.7  444.20  5029.2  442.70  5043.5  446.12
  5050.1  444.68  5086.4  447.80  5149.8  448.29  5179.3  451.38  5184.5  449.23
  5219.4  456.58  5224.5  454.06  5259.4  460.92  5264.5  459.16  5276.5  460.60
#Mann=4,-1,0
  4525.2    0.05       0  4883.4    0.16       0  4984.4    0.07       0
  4988.4    0.16       0
Bank Sta=4984.4,4988.4
Exp/Cntr=0.3,0.1

Type RM Length L Ch R = 1,13014,187,187,187
BEGIN DESCRIPTION:
DUCK CREEK TRIB 43 27 1
END DESCRIPTION:
XS GIS Cut Line= 2
      3492507.51     10439725.39      3492109.32     10439903.49
#Sta/Elev= 30
  4673.1  456.46  4749.9  453.46  4796.3  452.45  4842.7  450.42  4848.2  450.66
  4871.4  448.96  4887.2  448.31  4900.1  446.53  4917.8  445.28  4923.3  444.12
  4963.8  442.14  4969.7  441.54  4975.2  440.19  4990.9  439.64  4991.1  439.14
  4994.6  439.14  4994.9  439.64  4998.4  440.10  5016.1  440.68  5021.6  441.94
  5039.3  442.59  5044.8  443.99  5062.4  445.79  5068.0  447.41  5073.5  449.93
  5084.3  451.94  5091.2  453.94  5096.7  456.45  5105.0  458.45  5109.3  458.45
#Mann=3,-1,0
  4673.1    0.16       0  4990.9    0.07       0  4994.9    0.16       0
Bank Sta=4990.9,4994.9
Exp/Cntr=0.3,0.1

Type RM Length L Ch R = 1,12827,529,529,529
BEGIN DESCRIPTION:
DUCK CREEK TRIB 43 26 1
END DESCRIPTION:
XS GIS Cut Line= 4
      3492394.60     10439589.27      3492274.42     10439684.83
      3492054.33     10439744.19      3491987.71     10439842.68
#Sta/Elev= 30
  4746.1  455.05  4806.5  452.89  4820.9  451.78  4827.3  452.00  4856.1  450.80
  4877.0  449.41  4903.1  448.81  4941.6  446.99  4946.8  447.10  4974.5  444.21
  4981.6  442.44  4986.7  442.31  4993.3  440.78  4993.5  440.28  4997.0  440.28
  4997.3  440.78  5016.0  441.26  5061.4  441.50  5088.5  443.43  5109.2  445.84
  5119.5  446.06  5141.6  445.36  5156.5  446.20  5177.5  446.26  5184.9  446.83
  5198.5  448.20  5213.5  452.16  5228.4  458.54  5234.5  460.46  5246.5  461.23
#Mann=3,-1,0
  4746.1    0.16       0  4993.3    0.07       0  4997.3    0.16       0
Bank Sta=4993.3,4997.3
Exp/Cntr=0.3,0.1

Type RM Length L Ch R = 1,12298,450,450,450
BEGIN DESCRIPTION:
DUCK CREEK TRIB 43 26 0
END DESCRIPTION:
XS GIS Cut Line= 2
      3492415.80     10439327.94      3491646.30     10439640.07
#Sta/Elev= 30
  4438.3  457.16  4460.0  455.76  4543.0  453.93  4567.1  451.72  4626.1  450.76
  4644.8  449.35  4733.7  446.14  4805.6  445.90  4859.1  446.45  4895.5  445.33
  4906.3  445.70  4971.7  444.98  4981.9  443.13  4990.4  439.03  4993.8  434.58
  4994.0  434.08  4997.5  434.08  4997.8  434.58  5025.3  438.84  5035.8  441.48
  5044.0  446.72  5049.4  447.52  5097.6  449.21  5143.7  449.16  5165.3  450.35
  5204.7  451.30  5228.8  453.69  5240.9  457.27  5263.7  461.48  5268.7  460.55
#Mann=3,-1,0
  4438.3    0.16       0  4993.8    0.07       0  4997.8    0.16       0
Bank Sta=4993.8,4997.8
Exp/Cntr=0.3,0.1

Type RM Length L Ch R = 1,11848,373,373,373
BEGIN DESCRIPTION:
DUCK CREEK TRIB 43 25 0
END DESCRIPTION:
XS GIS Cut Line= 4
      3492413.78     10439295.26      3491953.70     10439121.64
      3491699.79     10439236.66      3491493.61     10439544.86
#Sta/Elev= 30
  4416.8  455.54  4493.0  453.89  4553.4  451.03  4723.8  444.95  4803.4  444.57
  4856.8  443.27  4894.3  444.23  4954.2  444.24  4964.4  443.45  4987.1  435.21
  4993.0  431.70  4996.5  431.50  4996.7  431.00  5000.2  431.00  5000.5  431.50
  5016.1  436.74  5044.7  437.31  5062.3  440.41  5075.0  443.67  5085.4  444.37
  5137.1  445.99  5183.3  445.96  5426.9  449.99  5462.9  451.66  5477.9  450.96
  5506.1  451.06  5520.0  452.35  5535.0  455.79  5550.0  460.85  5558.1  461.85
#Mann=3,-1,0
  4416.8    0.16       0  4996.5    0.07       0  5000.5    0.16       0
Bank Sta=4996.5,5000.5
Exp/Cntr=0.3,0.1

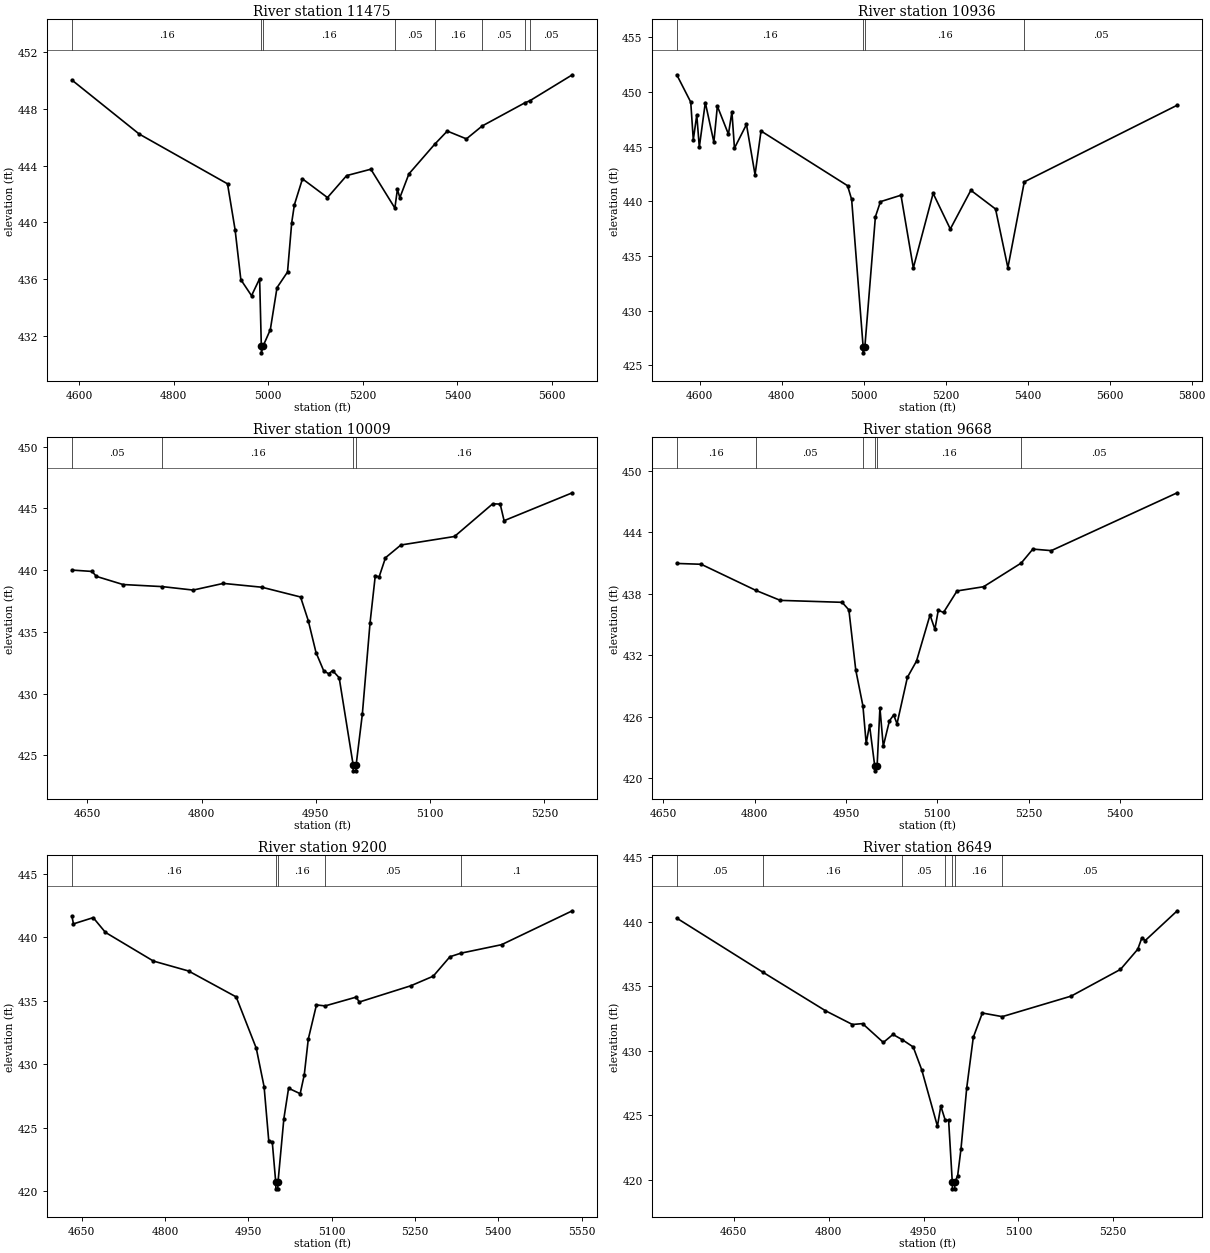
Type RM Length L Ch R = 1,11475,539,539,539
BEGIN DESCRIPTION:
DUCK CREEK TRIB 43 24 0
END DESCRIPTION:
XS GIS Cut Line= 3
      3492283.14     10439069.45      3491837.14     10438855.14
      3491281.09     10438946.37
#Sta/Elev= 30
  4584.7  450.03  4727.1  446.22  4913.8  442.71  4929.8  439.48  4942.0  435.95
  4964.6  434.82  4981.7  436.02  4985.3  431.29  4985.5  430.79  4989.3  431.29
  5004.3  432.42  5018.5  435.39  5040.7  436.49  5049.6  439.98  5055.2  441.23
  5072.3  443.06  5125.2  441.74  5165.7  443.29  5216.9  443.74  5267.7  441.00
  5273.1  442.32  5278.2  441.73  5297.4  443.41  5351.6  445.49  5378.5  446.43
  5419.0  445.88  5452.4  446.79  5541.9  448.41  5553.2  448.57  5643.0  450.40
#Mann=8,-1,0
  4584.7    0.16       0  4985.3    0.07       0  4989.3    0.16       0
  5267.7    0.05       0  5351.6    0.16       0  5452.4    0.05       0
  5541.9    0.16       0  5553.2    0.05       0
Bank Sta=4985.3,4989.3
Exp/Cntr=0.3,0.1

Type RM Length L Ch R = 1,10936,927,927,927
BEGIN DESCRIPTION:
DUCK CREEK TRIB 43 23 0
END DESCRIPTION:
XS GIS Cut Line= 3
      3492462.64     10438768.25      3492187.54     10438567.00
      3491310.10     10438504.74
#Sta/Elev= 30
  4544.4  451.57  4578.5  449.07  4584.7  445.62  4593.2  447.90  4599.4  444.95
  4614.0  449.03  4634.9  445.41  4643.4  448.70  4670.4  446.14  4678.9  448.19
  4685.1  444.86  4714.4  447.03  4735.3  442.43  4749.9  446.43  4960.9  441.43
  4970.9  440.17  4999.0  426.65  4999.2  426.15  5003.0  426.65  5028.8  438.59
  5041.1  439.97  5091.2  440.56  5121.3  433.91  5169.6  440.73  5211.5  437.47
  5261.6  441.01  5321.8  439.30  5351.9  433.93  5391.9  441.78  5764.9  448.79
#Mann=4,-1,0
  4544.4    0.16       0  4999.0    0.07       0  5003.0    0.16       0
  5391.9    0.05       0
Bank Sta=4999,5003
Exp/Cntr=0.3,0.1

Type RM Length L Ch R = 1,10009,341,341,341
BEGIN DESCRIPTION:
DUCK CREEK TRIB 43 22 0
END DESCRIPTION:
XS GIS Cut Line= 3
      3492138.29     10438191.97      3491718.40     10438122.47
      3491488.16     10438145.64
#Sta/Elev= 30
  4629.7  440.01  4656.2  439.90  4661.8  439.50  4696.8  438.84  4748.5  438.67
  4788.9  438.39  4828.5  438.93  4879.2  438.62  4929.9  437.83  4940.0  435.92
  4950.2  433.33  4960.3  431.85  4966.9  431.61  4972.0  431.87  4980.6  431.29
  4998.9  424.25  4999.1  423.75  5002.6  423.75  5002.9  424.25  5011.0  428.33
  5021.1  435.72  5028.0  439.56  5033.0  439.45  5041.4  441.01  5061.6  442.04
  5132.0  442.73  5182.2  445.38  5192.0  445.35  5197.1  444.01  5286.7  446.27
#Mann=4,-1,0
  4629.7    0.05       0  4748.5    0.16       0  4998.9    0.07       0
  5002.9    0.16       0
Bank Sta=4998.9,5002.9
Exp/Cntr=0.3,0.1

Type RM Length L Ch R = 1,9668,468,468,468
BEGIN DESCRIPTION:
DUCK CREEK TRIB 43 20 0
END DESCRIPTION:
XS GIS Cut Line= 3
      3492226.65     10438012.43      3491780.67     10437796.68
      3491457.75     10437847.36
#Sta/Elev= 30
  4672.0  440.96  4712.1  440.88  4802.1  438.33  4842.1  437.36  4943.7  437.17
  4954.8  436.43  4966.1  430.57  4977.9  427.06  4983.2  423.41  4988.7  425.20
  4997.2  421.24  4997.4  420.74  5001.2  421.24  5005.8  426.88  5011.3  423.14
  5021.4  425.61  5028.4  426.19  5033.9  425.33  5050.9  429.85  5065.9  431.44
  5088.1  435.93  5096.1  434.55  5101.7  436.40  5110.3  436.18  5132.5  438.28
  5176.1  438.69  5238.0  441.00  5257.1  442.36  5287.4  442.21  5494.3  447.85
#Mann=6,-1,0
  4672.0    0.16       0  4802.1    0.05       0  4977.9    0.16       0
  4997.2    0.07       0  5001.2    0.16       0  5238.0    0.05       0
Bank Sta=4997.2,5001.2
Exp/Cntr=0.3,0.1

Type RM Length L Ch R = 1,9200,551,551,551
BEGIN DESCRIPTION:
DUCK CREEK TRIB 43 2 0
END DESCRIPTION:
XS GIS Cut Line= 3
      3492391.03     10437717.18      3491915.81     10437372.82
      3491602.49     10437345.27
#Sta/Elev= 30
  4632.1  441.66  4635.0  441.05  4670.5  441.54  4692.5  440.38  4779.0  438.12
  4842.2  437.34  4928.0  435.30  4964.2  431.26  4978.3  428.23  4986.8  423.92
  4993.0  423.89  4999.3  420.69  4999.5  420.19  5003.0  420.19  5003.3  420.69
  5013.9  425.71  5022.4  428.11  5043.3  427.68  5050.7  429.18  5057.9  431.98
  5072.6  434.67  5088.2  434.59  5143.8  435.28  5150.0  434.90  5242.8  436.18
  5282.9  436.93  5313.0  438.46  5332.6  438.74  5406.0  439.41  5533.5  442.08
#Mann=5,-1,0
  4632.1    0.16       0  4999.3    0.07       0  5003.3    0.16       0
  5088.2    0.05       0  5332.6     0.1       0
Bank Sta=4999.3,5003.3
Exp/Cntr=0.3,0.1

Type RM Length L Ch R = 1,8649,397,397,397
BEGIN DESCRIPTION:
DUCK CREEK TRIB 43 19 0
END DESCRIPTION:
XS GIS Cut Line= 3
      3492542.12     10437191.65      3492142.11     10437041.64
      3491792.12     10436941.65
#Sta/Elev= 30
  4559.9  440.28  4696.1  436.09  4794.9  433.11  4837.6  432.04  4853.6  432.11
  4886.5  430.65  4901.7  431.27  4916.5  430.86  4933.7  430.30  4947.1  428.54
  4972.0  424.16  4977.3  425.73  4984.1  424.66  4989.7  424.61  4995.5  419.81
  4995.8  419.31  4999.3  419.31  4999.5  419.81  5004.0  420.34  5009.2  422.39
  5018.3  427.13  5028.7  431.05  5043.0  432.93  5074.5  432.65  5183.4  434.24
  5261.4  436.31  5288.7  437.87  5295.2  438.76  5300.4  438.54  5351.1  440.85
#Mann=7,-1,0
  4559.9    0.05       0  4696.1    0.16       0  4916.5    0.05       0
  4984.1    0.16       0  4995.5    0.07       0  4999.5    0.16       0
  5074.5    0.05       0
Bank Sta=4995.5,4999.5
Exp/Cntr=0.3,0.1

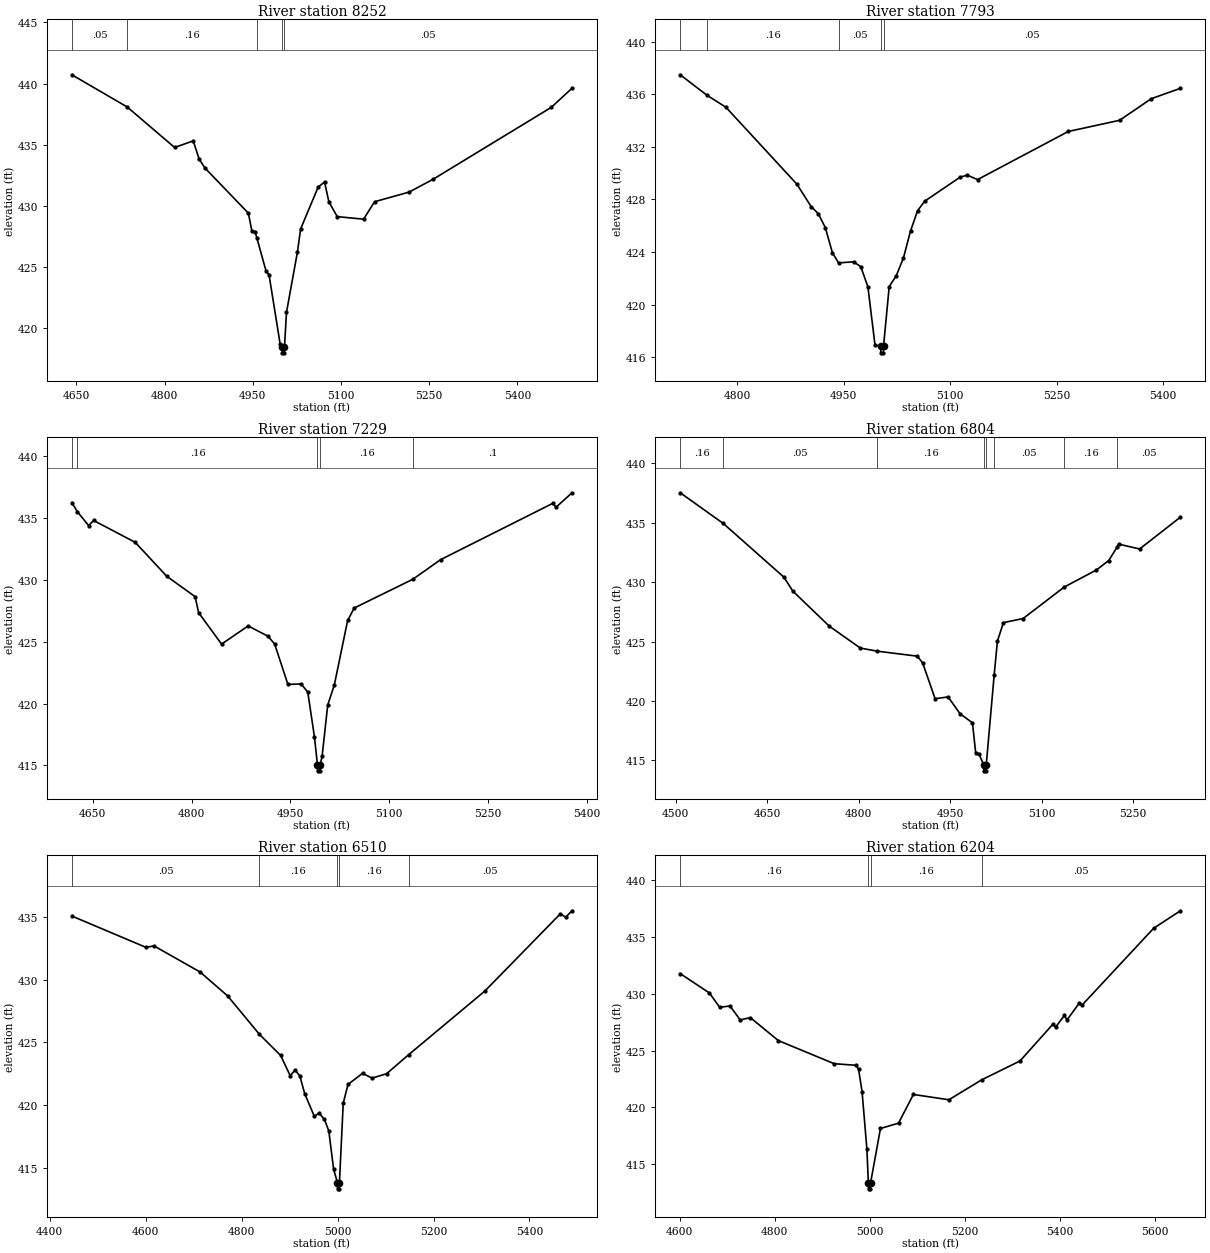
Type RM Length L Ch R = 1,8252,459,459,459
BEGIN DESCRIPTION:
DUCK CREEK TRIB 43 18 0
END DESCRIPTION:
XS GIS Cut Line= 4
      3492666.56     10436790.86      3492415.13     10436756.42
      3492084.55     10436622.12      3491847.03     10436656.54
#Sta/Elev= 30
  4642.2  440.72  4736.4  438.08  4816.9  434.77  4848.6  435.31  4858.7  433.81
  4868.7  433.08  4942.4  429.39  4948.2  427.96  4953.6  427.88  4956.8  427.37
  4972.2  424.69  4977.6  424.32  4996.3  418.71  4999.7  418.46  5000.0  417.96
  5003.5  417.96  5003.8  418.46  5007.2  421.28  5025.8  426.21  5031.2  428.10
  5061.1  431.53  5071.9  431.94  5079.3  430.32  5093.5  429.11  5138.3  428.90
  5157.0  430.33  5215.9  431.12  5256.6  432.17  5457.4  438.05  5492.8  439.62
#Mann=5,-1,0
  4642.2    0.05       0  4736.4    0.16       0  4956.8    0.05       0
  4999.7    0.03       0  5003.8    0.05       0
Bank Sta=4999.7,5003.8
Exp/Cntr=0.3,0.1

Type RM Length L Ch R = 1,7793,564,564,564
BEGIN DESCRIPTION:
DUCK CREEK TRIB 43 17 0
END DESCRIPTION:
XS GIS Cut Line= 3
      3492536.48     10436316.86      3492125.28     10436313.96
      3491863.74     10436446.90
#Sta/Elev= 30
  4719.8  437.48  4757.8  435.91  4784.2  435.01  4884.2  429.16  4904.2  427.46
  4914.2  426.93  4924.2  425.86  4934.2  423.94  4942.9  423.18  4964.2  423.26
  4974.2  422.89  4984.2  421.35  4994.2  416.92  5002.1  416.84  5002.4  416.34
  5006.0  416.34  5006.2  416.84  5014.2  421.38  5024.2  422.21  5034.2  423.55
  5044.2  425.60  5054.2  427.15  5064.2  427.87  5114.2  429.70  5124.2  429.85
  5138.6  429.51  5266.5  433.17  5338.8  434.02  5383.3  435.66  5424.4  436.45
#Mann=5,-1,0
  4719.8    0.05       0  4757.8    0.16       0  4942.9    0.05       0
  5002.1    0.03       0  5006.2    0.05       0
Bank Sta=5002.1,5006.2
Exp/Cntr=0.3,0.1

Type RM Length L Ch R = 1,7229,425,425,425
BEGIN DESCRIPTION:
DUCK CREEK TRIB 43 16 0
END DESCRIPTION:
XS GIS Cut Line= 4
      3492568.34     10436011.32      3492451.07     10435921.56
      3492107.91     10435883.91      3491846.42     10435931.59
#Sta/Elev= 30
  4618.4  436.25  4626.9  435.51  4643.8  434.40  4651.4  434.81  4714.5  433.04
  4762.3  430.30  4805.3  428.65  4810.7  427.35  4845.5  424.81  4885.8  426.28
  4915.9  425.45  4926.0  424.82  4946.1  421.55  4966.2  421.59  4976.3  420.92
  4986.4  417.29  4990.9  415.06  4991.1  414.56  4994.8  414.56  4995.1  415.06
  4998.0  415.75  5006.5  419.88  5016.5  421.50  5036.7  426.72  5046.7  427.73
  5135.8  430.06  5177.7  431.64  5347.7  436.19  5352.8  435.88  5377.1  437.05
#Mann=5,-1,0
  4618.4    0.05       0  4626.9    0.16       0  4990.9    0.07       0
  4995.1    0.16       0  5135.8     0.1       0
Bank Sta=4990.9,4995.1
Exp/Cntr=0.3,0.1

Type RM Length L Ch R = 1,6804,294,294,294
BEGIN DESCRIPTION:
Mapping XS 3e50473d
END DESCRIPTION:
XS GIS Cut Line= 4
      3492665.34     10435705.79      3492493.06     10435581.29
      3492154.24     10435511.79      3491896.11     10435552.16
#Sta/Elev= 30
  4507.6  437.52  4578.1  434.94  4677.5  430.42  4692.2  429.24  4751.8  426.30
  4802.8  424.45  4830.5  424.19  4896.2  423.77  4904.9  423.20  4925.3  420.19
  4946.6  420.34  4966.1  418.93  4986.5  418.16  4991.9  415.59  4997.0  415.56
  5004.9  414.62  5005.1  414.12  5008.8  414.12  5009.1  414.62  5022.1  422.19
  5027.4  425.03  5037.2  426.59  5069.6  426.94  5137.0  429.59  5189.6  431.02
  5209.9  431.82  5223.2  432.92  5226.0  433.20  5260.5  432.79  5327.3  435.47
#Mann=8,-1,0
  4507.6    0.16       0  4578.1    0.05       0  4830.5    0.16       0
  5004.9    0.07       0  5009.1    0.16       0  5022.1    0.05       0
  5137.0    0.16       0  5223.2    0.05       0
Bank Sta=5004.9,5009.1
Exp/Cntr=0.3,0.1

Type RM Length L Ch R = 1,6510,306,306,306
BEGIN DESCRIPTION:
DUCK CREEK TRIB 43 15 0
END DESCRIPTION:
XS GIS Cut Line= 4
      3492878.19     10435452.41      3492619.04     10435327.89
      3492141.21     10435284.46      3491879.15     10435368.43
#Sta/Elev= 30
  4446.2  435.07  4600.4  432.58  4617.5  432.69  4713.6  430.61  4770.8  428.71
  4837.1  425.65  4881.3  423.97  4901.3  422.35  4911.4  422.80  4921.4  422.33
  4931.5  420.92  4951.5  419.12  4961.6  419.37  4972.6  418.87  4981.7  417.96
  4991.7  414.92  4999.6  413.84  4999.9  413.34  5003.6  413.34  5003.9  413.84
  5011.8  420.16  5021.8  421.66  5052.0  422.54  5072.0  422.16  5102.2  422.51
  5148.0  424.02  5307.1  429.10  5464.6  435.26  5475.1  434.97  5488.7  435.49
#Mann=5,-1,0
  4446.2    0.05       0  4837.1    0.16       0  4999.6    0.07       0
  5003.9    0.16       0  5148.0    0.05       0
Bank Sta=4999.6,5003.9
Exp/Cntr=0.3,0.1

Type RM Length L Ch R = 1,6204,614,614,614
BEGIN DESCRIPTION:
DUCK CREEK TRIB 43 14 0
END DESCRIPTION:
XS GIS Cut Line= 4
      3492775.42     10434842.83      3492485.83     10435010.79
      3492060.12     10435203.37      3491822.69     10435284.44
#Sta/Elev= 30
  4600.8  431.78  4662.4  430.07  4683.9  428.81  4705.5  428.93  4727.0  427.70
  4748.5  427.90  4807.3  425.88  4924.9  423.84  4970.6  423.70  4976.1  423.38
  4983.6  421.38  4993.7  416.33  4996.9  413.31  4997.3  412.81  5001.1  412.81
  5001.4  413.31  5022.3  418.13  5060.4  418.60  5091.6  421.13  5166.4  420.66
  5235.4  422.42  5316.0  424.08  5385.3  427.32  5390.8  427.06  5409.5  428.09
  5414.8  427.69  5440.8  429.18  5446.1  428.98  5597.4  435.78  5653.7  437.32
#Mann=4,-1,0
  4600.8    0.16       0  4996.9    0.07       0  5001.4    0.16       0
  5235.4    0.05       0
Bank Sta=4996.9,5001.4
Exp/Cntr=0.3,0.1

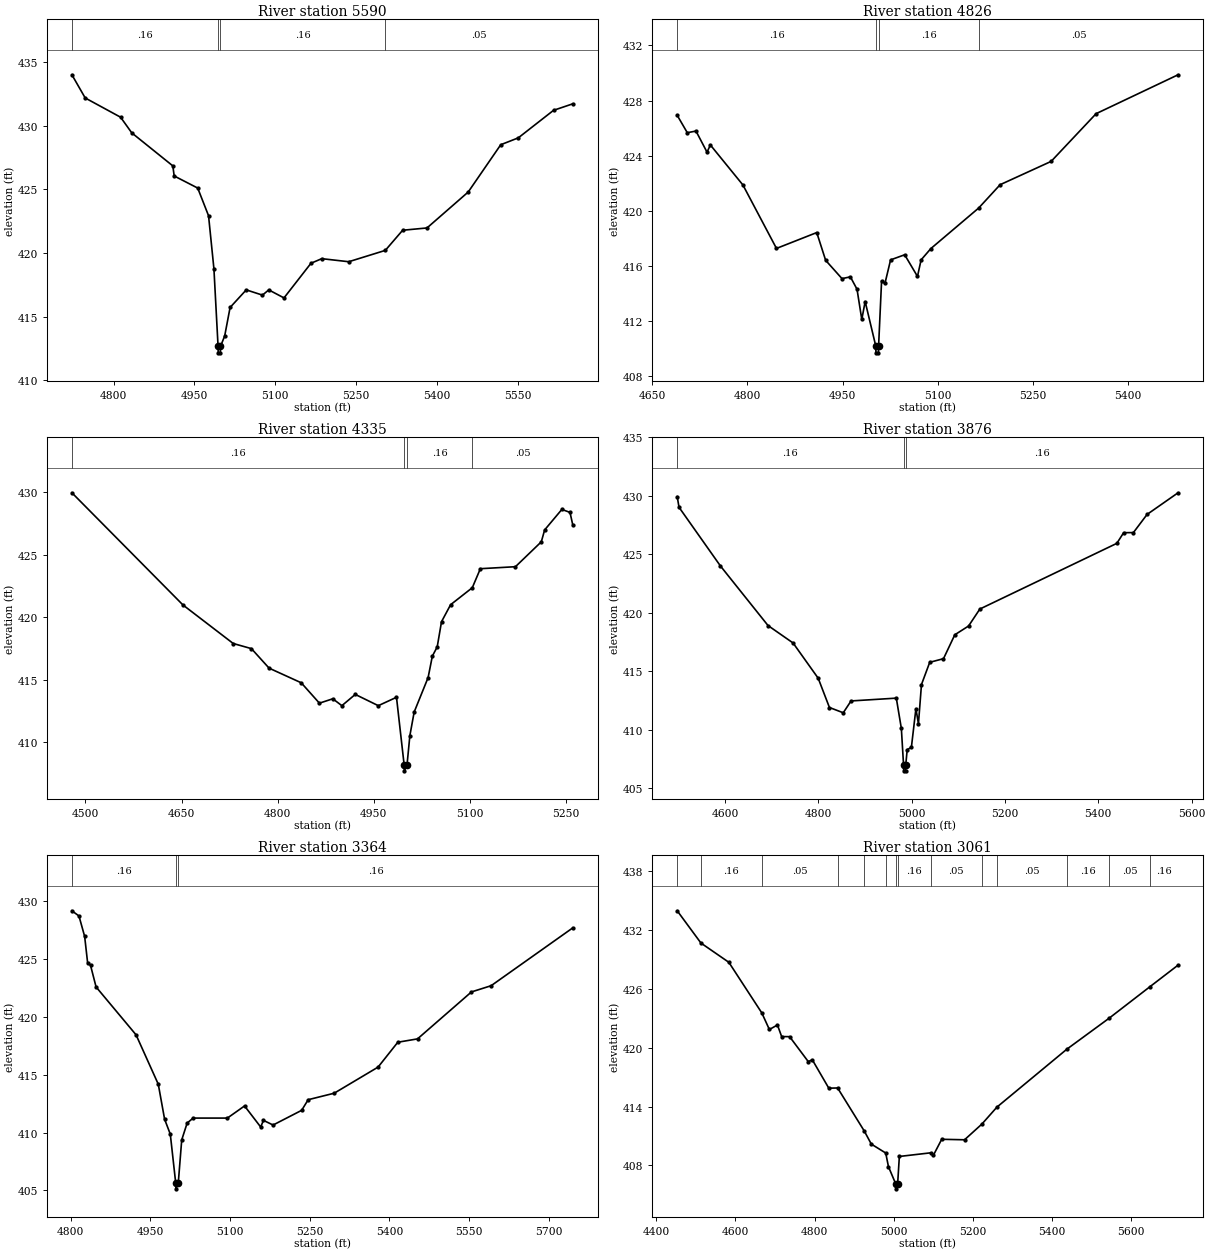
Type RM Length L Ch R = 1,5590,764,764,764
BEGIN DESCRIPTION:
DUCK CREEK TRIB 43 13 0
END DESCRIPTION:
XS GIS Cut Line= 4
      3492769.62     10434640.11      3492584.29     10434687.89
      3492132.52     10434711.06      3491868.98     10434822.56
#Sta/Elev= 30
  4722.5  433.99  4747.2  432.17  4812.9  430.66  4833.7  429.43  4909.9  426.84
  4912.4  426.05  4956.1  425.10  4976.2  422.93  4986.2  418.76  4993.9  412.67
  4994.2  412.17  4998.1  412.17  4998.4  412.67  5006.2  413.50  5016.2  415.73
  5046.2  417.11  5076.3  416.70  5088.0  417.11  5116.3  416.48  5166.4  419.20
  5186.4  419.56  5236.5  419.32  5304.4  420.21  5336.6  421.79  5381.8  421.97
  5458.3  424.79  5518.7  428.50  5551.3  429.04  5616.7  431.20  5652.4  431.71
#Mann=4,-1,0
  4722.5    0.16       0  4993.9    0.07       0  4998.4    0.16       0
  5304.4    0.05       0
Bank Sta=4993.9,4998.4
Exp/Cntr=0.3,0.1

Type RM Length L Ch R = 1,4826,491,491,491
BEGIN DESCRIPTION:
DUCK CREEK TRIB 43 12 0
END DESCRIPTION:
XS GIS Cut Line= 3
      3492480.04     10434260.74      3491990.62     10434430.16
      3491827.84     10434647.68
#Sta/Elev= 30
  4689.4  426.93  4705.3  425.67  4719.0  425.79  4736.4  424.26  4741.7  424.78
  4793.0  421.88  4845.9  417.28  4909.4  418.43  4923.4  416.42  4949.2  415.09
  4962.4  415.22  4972.9  414.32  4980.4  412.13  4985.7  413.43  5002.4  410.21
  5002.7  409.71  5006.6  409.71  5006.9  410.21  5011.6  414.93  5016.9  414.74
  5025.8  416.45  5048.0  416.82  5068.2  415.25  5073.9  416.45  5089.3  417.27
  5164.7  420.21  5198.5  421.90  5278.9  423.59  5349.8  427.05  5479.0  429.87
#Mann=4,-1,0
  4689.4    0.16       0  5002.4    0.07       0  5006.9    0.16       0
  5164.7    0.05       0
Bank Sta=5002.4,5006.9
Exp/Cntr=0.3,0.1

Type RM Length L Ch R = 1,4335,459,459,459
BEGIN DESCRIPTION:
DUCK CREEK TRIB 43 42 0
END DESCRIPTION:
XS GIS Cut Line= 3
      3492291.82     10433806.07      3491812.52     10434231.78
      3491775.24     10434368.01
#Sta/Elev= 30
  4478.8  429.96  4652.3  420.99  4730.8  417.91  4759.2  417.50  4786.8  415.94
  4837.0  414.77  4865.4  413.14  4886.3  413.49  4900.5  412.94  4921.4  413.84
  4957.4  412.94  4985.8  413.61  4997.7  408.23  4998.1  407.73  5002.3  408.23
  5006.7  410.55  5013.4  412.43  5035.2  415.19  5041.8  416.90  5049.4  417.64
  5056.1  419.65  5070.3  421.01  5104.2  422.37  5116.8  423.89  5171.6  424.05
  5212.0  426.04  5217.2  426.99  5244.1  428.63  5256.8  428.39  5261.1  427.40
#Mann=4,-1,0
  4478.8    0.16       0  4997.7    0.07       0  5002.3    0.16       0
  5104.2    0.05       0
Bank Sta=4997.7,5002.3
Exp/Cntr=0.3,0.1

Type RM Length L Ch R = 1,3876,512,512,512
BEGIN DESCRIPTION:
DUCK CREEK TRIB 43 41 0
END DESCRIPTION:
XS GIS Cut Line= 3
      3492187.58     10433643.89      3491576.50     10433890.06
      3491242.05     10434134.75
#Sta/Elev= 30
  4497.7  429.92  4501.6  429.01  4590.3  424.00  4692.3  418.91  4746.0  417.42
  4799.8  414.41  4823.9  411.91  4853.5  411.46  4870.2  412.47  4967.2  412.71
  4978.0  410.12  4982.7  407.00  4983.0  406.50  4987.1  406.50  4987.4  407.00
  4990.5  408.31  4999.5  408.51  5009.2  411.81  5014.6  410.52  5021.1  413.87
  5038.8  415.77  5068.3  416.08  5092.5  418.12  5122.0  418.87  5146.2  420.32
  5439.7  425.93  5454.3  426.84  5475.2  426.85  5504.5  428.40  5570.9  430.25
#Mann=3,-1,0
  4497.7    0.16       0  4982.7    0.07       0  4987.4    0.16       0
Bank Sta=4982.7,4987.4
Exp/Cntr=0.3,0.1

Type RM Length L Ch R = 1,3364,303,303,303
BEGIN DESCRIPTION:
DUCK CREEK TRIB 43 9 0
END DESCRIPTION:
XS GIS Cut Line= 3
      3491954.45     10433355.75      3491437.50     10433558.48
      3491240.56     10433891.53
#Sta/Elev= 30
  4802.6  429.18  4815.9  428.73  4826.6  426.96  4832.2  424.67  4837.6  424.47
  4848.1  422.59  4923.3  418.45  4965.1  414.18  4977.0  411.15  4987.7  409.86
  4997.9  405.63  4998.3  405.13  5002.7  405.63  5009.2  409.36  5019.4  410.82
  5030.7  411.25  5095.1  411.25  5127.4  412.30  5157.7  410.48  5163.0  411.05
  5181.1  410.65  5234.8  411.92  5247.1  412.84  5296.0  413.40  5378.6  415.66
  5415.7  417.81  5452.8  418.10  5554.2  422.16  5591.3  422.70  5744.8  427.70
#Mann=3,-1,0
  4802.6    0.16       0  4997.9    0.07       0  5002.7    0.16       0
Bank Sta=4997.9,5002.7
Exp/Cntr=0.3,0.1

Type RM Length L Ch R = 1,3061,152,152,152
BEGIN DESCRIPTION:
DUCK CREEK TRIB 43 8 0
END DESCRIPTION:
XS GIS Cut Line= 4
      3492009.49     10433021.27      3491685.10     10433092.23
      3491389.71     10433464.36      3491213.18     10433886.89
#Sta/Elev= 30
  4452.9  433.95  4512.9  430.66  4583.3  428.70  4666.6  423.54  4685.7  421.85
  4706.1  422.31  4716.7  421.13  4736.8  421.12  4783.9  418.58  4794.2  418.76
  4835.8  415.87  4858.1  415.89  4925.6  411.49  4943.2  410.17  4979.6  409.26
  4986.5  407.87  5004.9  406.11  5005.2  405.61  5009.7  406.11  5014.0  408.91
  5093.0  409.28  5100.2  409.05  5121.0  410.66  5178.7  410.61  5222.5  412.21
  5260.5  413.94  5437.0  419.84  5543.9  423.00  5646.3  426.19  5718.0  428.41
#Mann=14,-1,0
  4452.9    0.05       0  4512.9    0.16       0  4666.6    0.05       0
  4858.1    0.16       0  4925.6    0.05       0  4979.6    0.16       0
  5004.9    0.07       0  5009.7    0.16       0  5093.0    0.05       0
  5222.5    0.16       0  5260.5    0.05       0  5437.0    0.16       0
  5543.9    0.05       0  5646.3    0.16       0
Bank Sta=5004.9,5009.7
Exp/Cntr=0.3,0.1