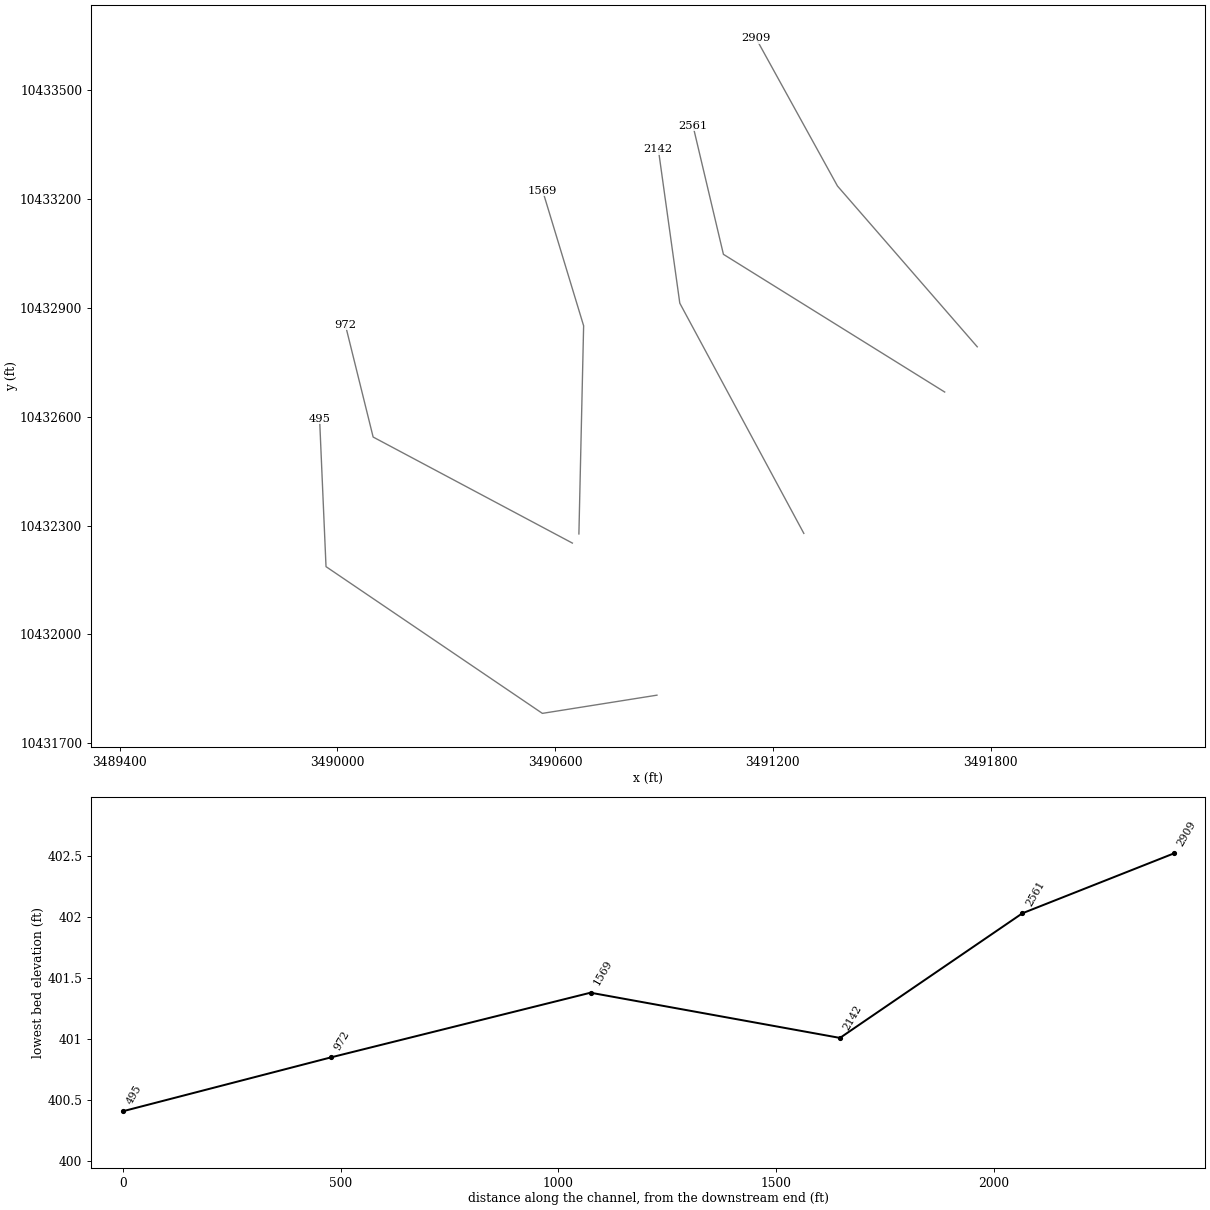
HEC-RAS study DUCK CREEK TRIB 43.prj: DUCK CREEK TRIB 43 Base Level Engineering

--- DUCK CREEK TRIB 43.g01 (geometry) --- (continued)

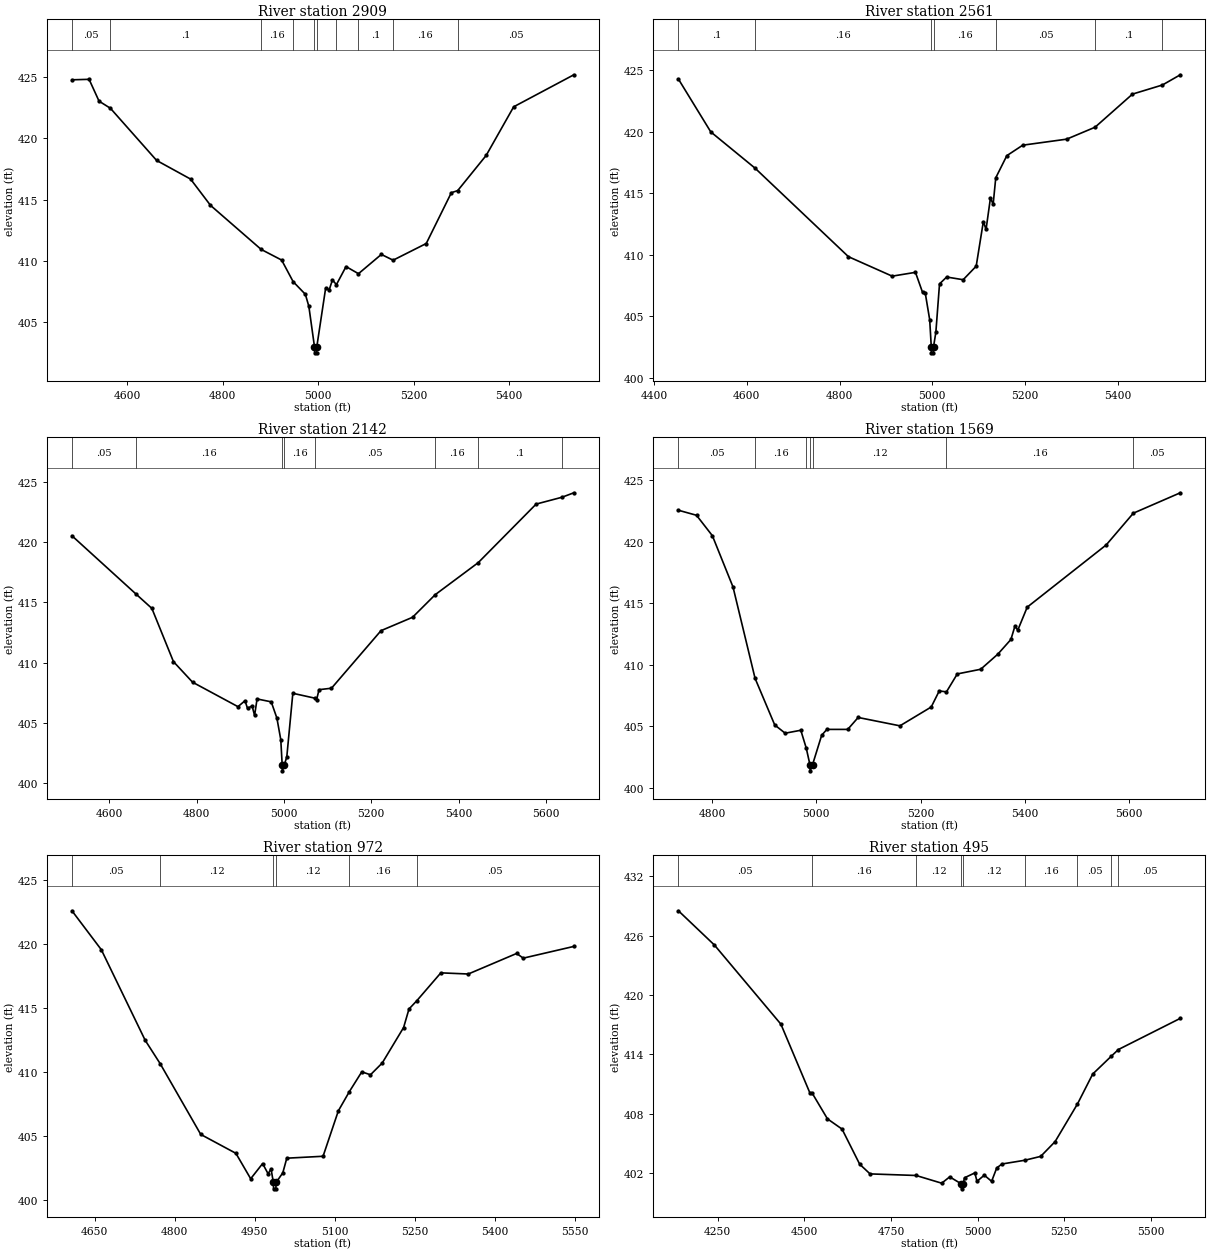
Type RM Length L Ch R = 1,2909,348,348,348
BEGIN DESCRIPTION:
DUCK CREEK TRIB 43 6 2
END DESCRIPTION:
XS GIS Cut Line= 3
      3491763.26     10432792.54      3491378.13     10433235.58
      3491153.70     10433642.45
#Sta/Elev= 30
  4484.0  424.77  4519.9  424.81  4540.8  423.03  4564.6  422.45  4661.4  418.20
  4732.6  416.68  4774.3  414.54  4880.4  410.95  4923.4  410.08  4947.5  408.32
  4973.1  407.29  4980.4  406.31  4992.2  403.02  4992.6  402.52  4996.8  402.52
  4997.1  403.02  5015.5  407.77  5023.2  407.67  5029.8  408.46  5038.2  408.08
  5058.3  409.55  5084.4  408.97  5132.3  410.54  5157.0  410.07  5226.4  411.43
  5279.0  415.57  5292.3  415.74  5352.0  418.61  5409.6  422.57  5535.7  425.18
#Mann=10,-1,0
  4484.0    0.05       0  4564.6     0.1       0  4880.4    0.16       0
  4947.5     0.1       0  4992.2    0.07       0  4997.1     0.1       0
  5038.2    0.16       0  5084.4     0.1       0  5157.0    0.16       0
  5292.3    0.05       0
Bank Sta=4992.2,4997.1
Exp/Cntr=0.3,0.1

Type RM Length L Ch R = 1,2561,419,419,419
BEGIN DESCRIPTION:
DUCK CREEK TRIB 43 6 1
END DESCRIPTION:
XS GIS Cut Line= 3
      3491673.55     10432667.96      3491063.92     10433047.35
      3490979.94     10433402.10
#Sta/Elev= 30
  4452.4  424.27  4522.2  419.98  4617.5  417.04  4819.2  409.84  4913.5  408.26
  4963.7  408.57  4979.0  406.94  4984.9  406.87  4994.4  404.72  4997.8  402.53
  4998.2  402.03  5002.4  402.03  5002.7  402.53  5007.7  403.70  5015.6  407.63
  5031.0  408.19  5066.6  407.97  5094.7  409.07  5110.1  412.69  5116.0  412.06
  5125.4  414.60  5131.3  414.11  5136.9  416.25  5160.8  418.05  5195.1  418.90
  5289.9  419.39  5351.1  420.36  5431.8  423.05  5496.4  423.79  5535.0  424.62
#Mann=7,-1,0
  4452.4     0.1       0  4617.5    0.16       0  4997.8    0.07       0
  5002.7    0.16       0  5136.9    0.05       0  5351.1     0.1       0
  5496.4    0.05       0
Bank Sta=4997.8,5002.7
Exp/Cntr=0.3,0.1

Type RM Length L Ch R = 1,2142,573,573,573
BEGIN DESCRIPTION:
DUCK CREEK TRIB 43 6 0
END DESCRIPTION:
XS GIS Cut Line= 3
      3491285.45     10432278.49      3490943.74     10432912.69
      3490884.50     10433337.47
#Sta/Elev= 30
  4514.5  420.53  4662.1  415.66  4697.5  414.50  4746.9  410.08  4790.7  408.37
  4894.6  406.34  4910.8  406.83  4916.5  406.20  4927.0  406.40  4932.7  405.61
  4938.4  406.98  4970.8  406.74  4983.8  405.39  4992.7  403.60  4995.9  401.51
  4996.3  401.01  5000.9  401.51  5006.5  402.18  5020.3  407.45  5070.0  407.05
  5074.6  406.90  5080.3  407.75  5108.8  407.87  5222.2  412.65  5294.4  413.76
  5346.4  415.64  5444.9  418.30  5577.4  423.16  5636.7  423.73  5663.8  424.10
#Mann=8,-1,0
  4514.5    0.05       0  4662.1    0.16       0  4995.9    0.07       0
  5000.9    0.16       0  5070.0    0.05       0  5346.4    0.16       0
  5444.9     0.1       0  5636.7    0.05       0
Bank Sta=4995.9,5000.9
Exp/Cntr=0.3,0.1

Type RM Length L Ch R = 1,1569,597,597,597
BEGIN DESCRIPTION:
DUCK CREEK TRIB 43 30 1
END DESCRIPTION:
XS GIS Cut Line= 3
      3490665.73     10432276.99      3490678.76     10432850.42
      3490565.81     10433222.58
#Sta/Elev= 30
  4735.7  422.57  4770.4  422.16  4800.8  420.50  4840.4  416.33  4882.7  408.90
  4920.4  405.11  4940.4  404.44  4970.4  404.68  4980.9  403.22  4987.9  401.88
  4988.3  401.38  4992.9  401.88  5010.4  404.27  5020.4  404.75  5060.4  404.75
  5080.4  405.72  5160.5  405.04  5220.5  406.57  5235.9  407.88  5249.7  407.80
  5270.5  409.26  5315.4  409.64  5348.3  410.87  5373.3  412.06  5381.2  413.17
  5386.4  412.81  5404.6  414.69  5556.1  419.75  5608.1  422.33  5698.2  423.99
#Mann=7,-1,0
  4735.7    0.05       0  4882.7    0.16       0  4980.9    0.12       0
  4987.9    0.07       0  4992.9    0.12       0  5249.7    0.16       0
  5608.1    0.05       0
Bank Sta=4987.9,4992.9
Exp/Cntr=0.3,0.1

Type RM Length L Ch R = 1,972,477,477,477
BEGIN DESCRIPTION:
DUCK CREEK TRIB 43 21 0
END DESCRIPTION:
XS GIS Cut Line= 3
      3490647.71     10432251.78      3490098.82     10432543.93
      3490022.10     10432853.77
#Sta/Elev= 30
  4607.2  422.62  4662.3  419.57  4744.5  412.48  4772.6  410.65  4848.7  405.11
  4914.6  403.63  4942.3  401.64  4964.7  402.83  4974.9  402.03  4980.5  402.41
  4984.8  401.35  4985.2  400.85  4989.5  400.85  4989.9  401.35  5002.5  402.10
  5010.0  403.25  5078.0  403.40  5106.7  406.96  5127.3  408.46  5150.6  410.01
  5166.9  409.78  5188.9  410.70  5229.0  413.48  5239.1  414.93  5253.8  415.58
  5298.8  417.76  5350.3  417.67  5441.0  419.28  5453.3  418.91  5548.2  419.83
#Mann=6,-1,0
  4607.2    0.05       0  4772.6    0.12       0  4984.8    0.07       0
  4989.9    0.12       0  5127.3    0.16       0  5253.8    0.05       0
Bank Sta=4984.8,4989.9
Exp/Cntr=0.3,0.1

Type RM Length L Ch R = 1,495,0,0,0
BEGIN DESCRIPTION:
DUCK CREEK TRIB 43 1 0
END DESCRIPTION:
XS GIS Cut Line= 4
      3490880.81     10431832.74      3490565.08     10431782.57
      3489968.98     10432186.86      3489951.27     10432594.11
#Sta/Elev= 30
  4137.2  428.51  4241.0  425.05  4432.8  417.05  4516.2  410.12  4523.0  410.08
  4567.1  407.48  4609.1  406.45  4660.0  402.90  4689.9  401.92  4822.7  401.76
  4896.6  400.98  4919.6  401.62  4953.3  400.91  4953.7  400.41  4958.4  400.91
  4962.5  401.53  4992.1  402.02  4998.4  401.17  5019.4  401.79  5040.5  401.17
  5055.3  402.52  5070.3  402.92  5136.4  403.30  5182.1  403.69  5223.6  405.18
  5288.2  408.99  5332.1  412.01  5386.2  413.83  5406.3  414.49  5584.8  417.64
#Mann=9,-1,0
  4137.2    0.05       0  4523.0    0.16       0  4822.7    0.12       0
  4953.3    0.07       0  4958.4    0.12       0  5136.4    0.16       0
  5288.2    0.05       0  5386.2    0.16       0  5406.3    0.05       0
Bank Sta=4953.3,4958.4
Exp/Cntr=0.3,0.1

Chan Stop Cuts=-1