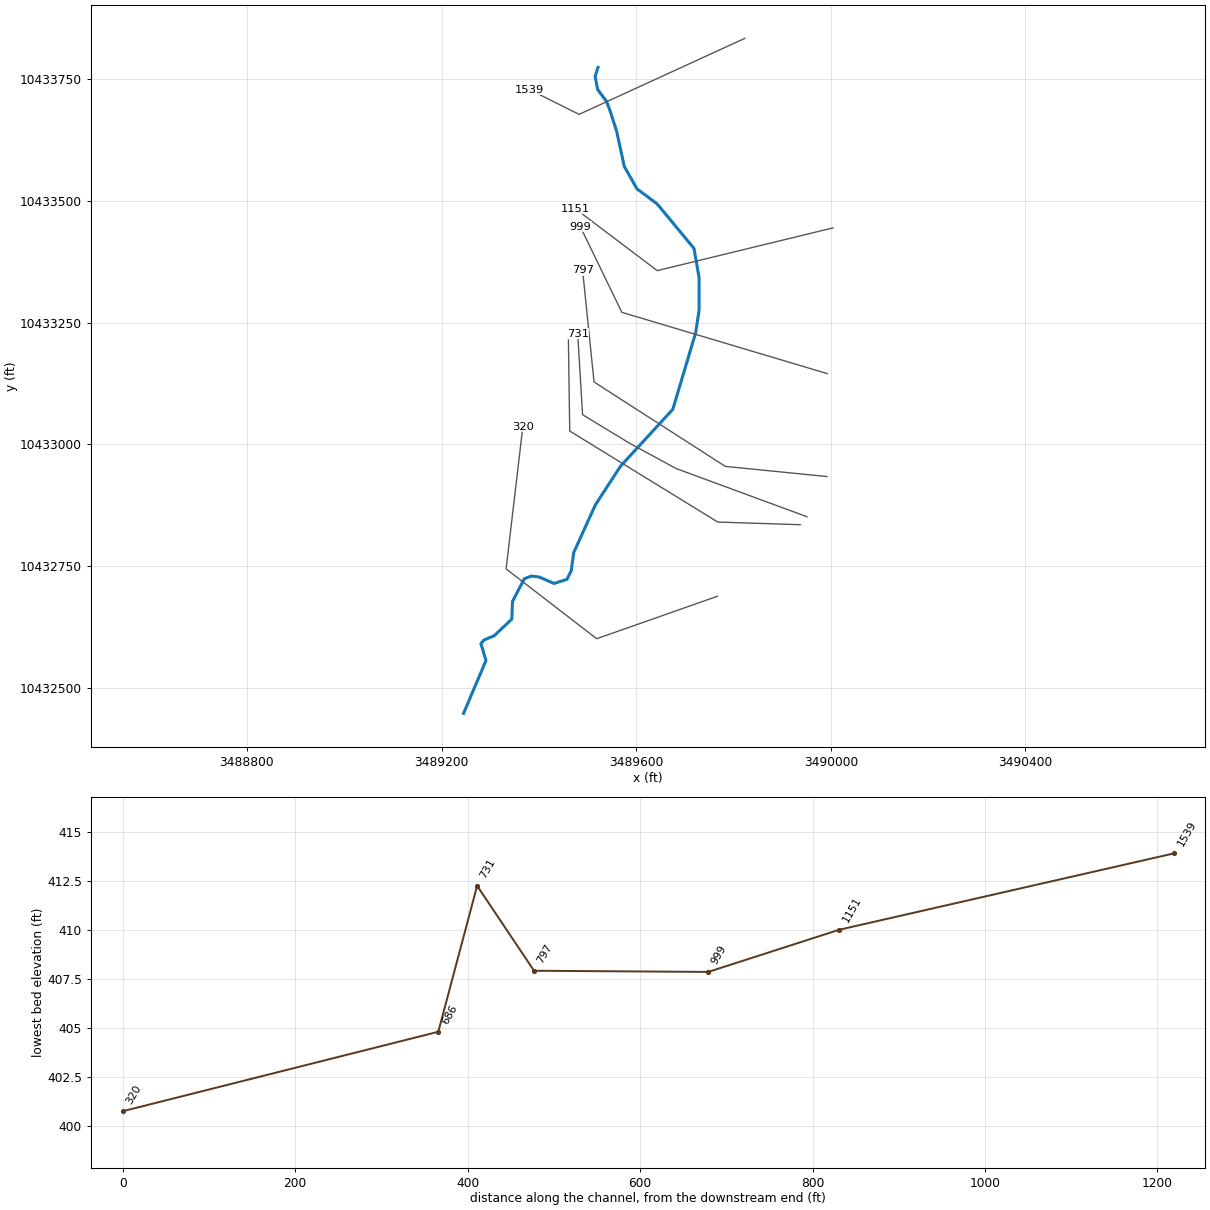
--- DUCK CREEK TRIB 44.prj (project) ---

Proj Title=DUCK CREEK TRIB 44 Base Level Engineering
Current Plan=p01
Default Exp/Contr=0.3,0.1
English Units
Geom File=g01
Flow File=f01
Plan File=p01
BEGIN DESCRIPTION:
DUCK CREEK TRIB 44
END DESCRIPTION:

--- DUCK CREEK TRIB 44.p01 (plan) ---

Plan Title=Multiple Run
Short Identifier=Multiple
Geom File=g01
Flow File=f01
Subcritical Flow
K Sum by GR= 0
Std Step Tol= 0.01
Critical Tol= 0.01
Num of Std Step Trials= 20
Max Error Tol= 0.3
Flow Tol Ratio= 0.001
Split Flow NTrial= 30
Split Flow Tol= 0.02
Split Flow Ratio= 0.02
Log Output Level= 0
Friction Slope Method= 1
Unsteady Friction Slope Method= 2
Unsteady Bridges Friction Slope Method= 1
Parabolic Critical Depth
Global Vel Dist=  1 , 1 , 1
Global Log Level= 0
CheckData=True
Encroach Param= -1, 0, 0, 0
BEGIN DESCRIPTION:
Multiple Run
END DESCRIPTION:

--- DUCK CREEK TRIB 44.f01 (steady flow) ---

Flow Title=Multiple
Number of Profiles=7
Profile Names=10-year,25-year,50-year,1pct_min,100-year,1pct_plu,500-year
River Rch & RM= DUCK CREEK TRIB ,Reach-1,1539
     173     213     241     202     273     369     345
Boundary for River Rch & Prof#=DUCK CREEK TRIB ,Reach-1,1
Up Type=0
Dn Type=3
Dn Slope=0.005
Boundary for River Rch & Prof#=DUCK CREEK TRIB ,Reach-1,2
Up Type=0
Dn Type=3
Dn Slope=0.005
Boundary for River Rch & Prof#=DUCK CREEK TRIB ,Reach-1,3
Up Type=0
Dn Type=3
Dn Slope=0.005
Boundary for River Rch & Prof#=DUCK CREEK TRIB ,Reach-1,4
Up Type=0
Dn Type=3
Dn Slope=0.005
Boundary for River Rch & Prof#=DUCK CREEK TRIB ,Reach-1,5
Up Type=0
Dn Type=3
Dn Slope=0.005
Boundary for River Rch & Prof#=DUCK CREEK TRIB ,Reach-1,6
Up Type=0
Dn Type=3
Dn Slope=0.005
Boundary for River Rch & Prof#=DUCK CREEK TRIB ,Reach-1,7
Up Type=0
Dn Type=3
Dn Slope=0.005

--- DUCK CREEK TRIB 44.g01 (geometry) ---

Geom Title=Existing Conditions

River Reach=DUCK CREEK TRIB ,Reach-1
Reach XY= 30
      3489521.57     10433774.71      3489515.68     10433756.22
      3489520.89     10433729.31      3489539.12     10433705.01
      3489546.93     10433684.17      3489559.95     10433643.37
      3489575.58     10433571.33      3489601.62     10433525.32
      3489643.29     10433494.07      3489718.81     10433402.92
      3489729.22     10433343.90      3489729.22     10433274.45
      3489722.28     10433229.31      3489675.40     10433072.19
      3489567.76     10432955.01      3489516.03     10432875.32
      3489471.58     10432777.40      3489466.72     10432740.60
      3489457.70     10432722.54      3489431.31     10432714.21
      3489400.75     10432727.40      3489384.78     10432729.49
      3489370.20     10432723.93      3489345.89     10432677.40
      3489344.50     10432640.94      3489308.04     10432606.57
      3489287.56     10432598.24      3489280.96     10432590.60
      3489291.38     10432555.87      3489245.28     10432447.19

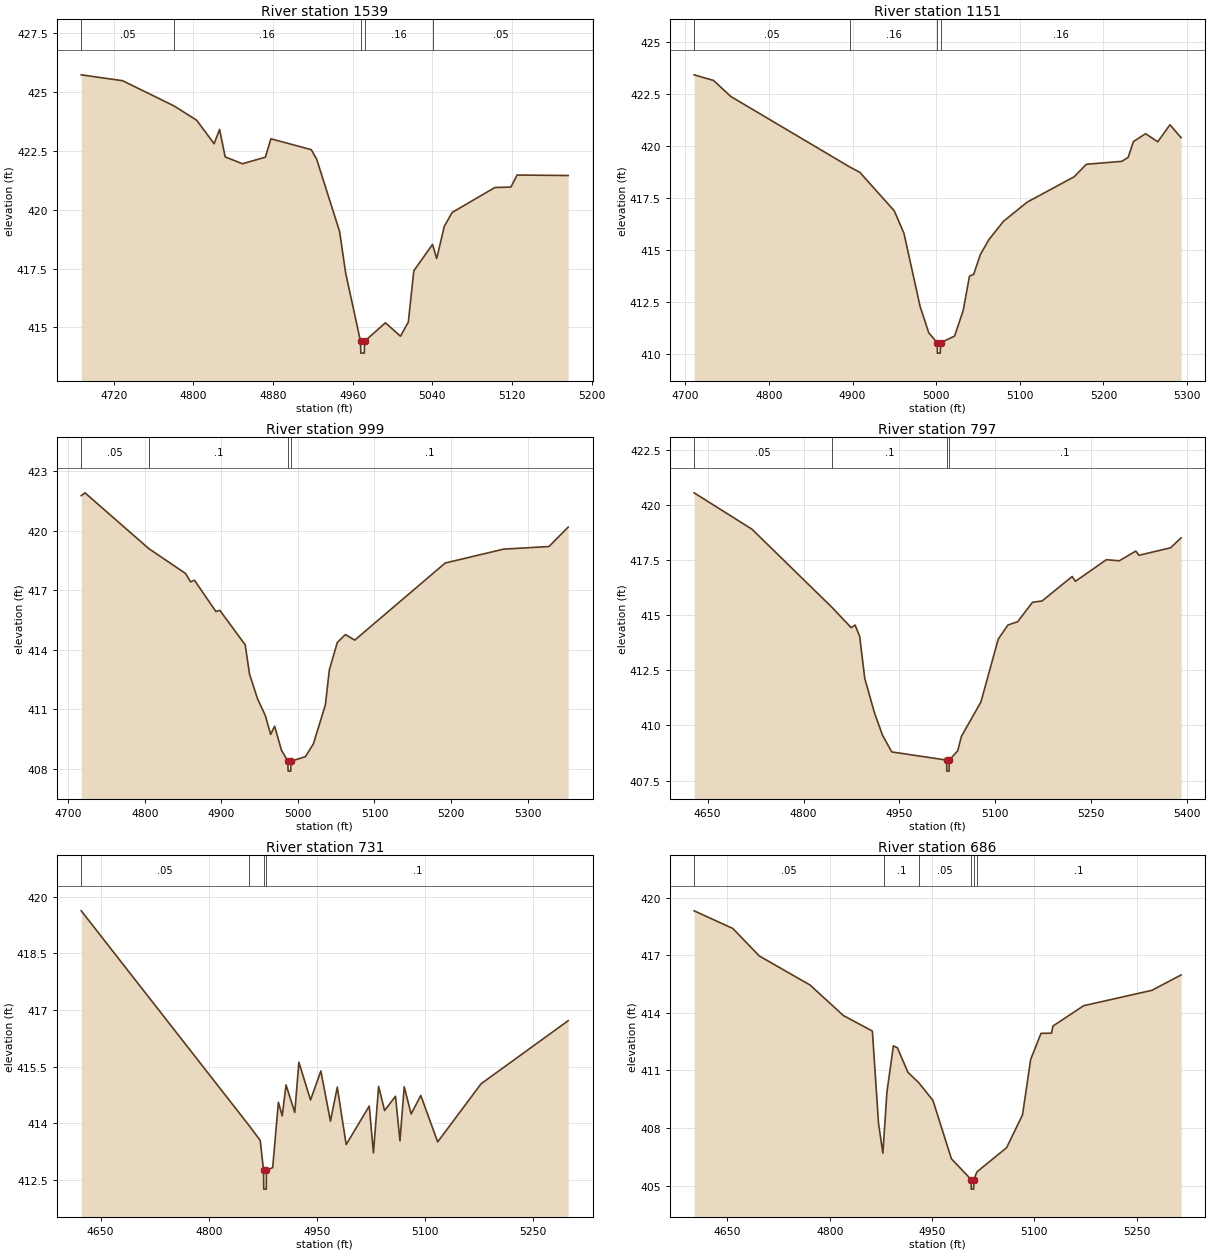
Type RM Length L Ch R = 1,1539,388,388,388
BEGIN DESCRIPTION:
DUCK CREEK TRIB 44 7 0
END DESCRIPTION:
XS GIS Cut Line= 3
      3489823.45     10433834.53      3489482.74     10433678.28
      3489380.71     10433729.29
#Sta/Elev= 30
  4687.5  425.74  4729.0  425.49  4780.6  424.42  4803.4  423.81  4820.9  422.81
  4826.4  423.42  4832.0  422.25  4849.4  421.96  4872.4  422.24  4877.9  423.02
  4918.4  422.56  4923.9  422.15  4946.9  419.08  4953.0  417.31  4967.9  414.41
  4968.2  413.91  4971.7  413.91  4971.9  414.41  4992.9  415.20  5008.0  414.63
  5015.9  415.23  5021.4  417.41  5040.2  418.53  5044.4  417.93  5052.0  419.30
  5059.9  419.89  5102.8  420.95  5118.9  420.97  5125.1  421.48  5176.4  421.46
#Mann=5,-1,0
  4687.5    0.05       0  4780.6    0.16       0  4967.9    0.07       0
  4971.9    0.16       0  5040.2    0.05       0
Bank Sta=4967.9,4971.9
Exp/Cntr=0.3,0.1

Type RM Length L Ch R = 1,1151,152,152,152
BEGIN DESCRIPTION:
DUCK CREEK TRIB 44 6 0
END DESCRIPTION:
XS GIS Cut Line= 3
      3490004.65     10433444.99      3489643.33     10433357.10
      3489475.57     10433483.99
#Sta/Elev= 30
  4710.6  423.40  4733.8  423.13  4754.4  422.36  4897.5  418.95  4908.8  418.71
  4949.9  416.86  4961.4  415.79  4980.8  412.26  4991.1  411.00  5001.2  410.52
  5001.4  410.02  5004.9  410.02  5005.2  410.52  5022.0  410.84  5032.3  412.07
  5039.8  413.72  5044.9  413.81  5052.8  414.76  5063.1  415.48  5080.5  416.36
  5108.8  417.28  5165.0  418.50  5179.6  419.10  5221.9  419.24  5229.5  419.43
  5235.8  420.19  5250.4  420.57  5264.9  420.18  5279.5  421.00  5292.8  420.38
#Mann=4,-1,0
  4710.6    0.05       0  4897.5    0.16       0  5001.2    0.07       0
  5005.2    0.16       0
Bank Sta=5001.2,5005.2
Exp/Cntr=0.3,0.1

Type RM Length L Ch R = 1,999,202,202,202
BEGIN DESCRIPTION:
Mapping XS 6eee5a5f
END DESCRIPTION:
XS GIS Cut Line= 3
      3489992.70     10433145.52      3489570.63     10433271.38
      3489485.29     10433447.45
#Sta/Elev= 30
  4717.0  421.77  4721.9  421.91  4805.1  419.10  4853.3  417.84  4859.7  417.42
  4864.9  417.50  4892.9  415.92  4898.1  415.98  4931.2  414.24  4936.8  412.77
  4947.2  411.53  4957.6  410.66  4964.4  409.72  4969.6  410.14  4978.5  408.93
  4986.9  408.37  4987.2  407.87  4990.7  407.87  4990.9  408.37  5009.8  408.60
  5020.2  409.24  5035.9  411.21  5041.1  412.98  5051.5  414.36  5062.0  414.76
  5074.3  414.48  5192.5  418.37  5268.9  419.07  5328.0  419.20  5353.1  420.18
#Mann=4,-1,0
  4717.0    0.05       0  4805.1     0.1       0  4986.9    0.07       0
  4990.9     0.1       0
Bank Sta=4986.9,4990.9
Exp/Cntr=0.3,0.1

Type RM Length L Ch R = 1,797,66,66,66
BEGIN DESCRIPTION:
DUCK CREEK TRIB 44 4 0
END DESCRIPTION:
XS GIS Cut Line= 4
      3489992.11     10432933.93      3489783.20     10432954.82
      3489513.47     10433128.28      3489489.97     10433357.84
#Sta/Elev= 30
  4628.9  420.54  4719.4  418.89  4844.8  415.34  4874.5  414.43  4880.5  414.55
  4887.7  414.04  4895.7  412.13  4910.9  410.57  4923.4  409.56  4937.9  408.80
  5023.8  408.43  5024.0  407.93  5027.5  407.93  5027.8  408.43  5041.0  408.85
  5046.9  409.51  5077.3  411.06  5104.4  413.91  5119.5  414.55  5134.7  414.70
  5158.0  415.58  5173.0  415.64  5220.1  416.75  5225.1  416.53  5273.5  417.51
  5293.6  417.46  5319.5  417.90  5324.5  417.71  5374.0  418.05  5390.3  418.50
#Mann=4,-1,0
  4628.9    0.05       0  4844.8     0.1       0  5023.8    0.07       0
  5027.8     0.1       0
Bank Sta=5023.8,5027.8
Exp/Cntr=0.3,0.1

Type RM Length L Ch R = 1,731,45,45,45
BEGIN DESCRIPTION:
DUCK CREEK TRIB 44 8 0
END DESCRIPTION:
XS GIS Cut Line= 5
      3489951.22     10432851.29      3489682.39     10432950.28
      3489587.03     10433002.05      3489489.86     10433061.08
      3489479.91     10433227.40
#Sta/Elev= 30
  4623.2  419.63  4855.7  413.95  4871.4  413.55  4876.0  412.76  4876.3  412.26
  4879.8  412.26  4880.0  412.76  4888.7  412.83  4896.6  414.56  4901.9  414.20
  4907.2  415.02  4919.3  414.29  4925.0  415.62  4941.2  414.62  4955.5  415.39
  4968.8  414.06  4978.3  414.96  4990.6  413.44  5022.6  414.46  5028.4  413.22
  5035.6  414.98  5043.9  414.34  5059.0  414.72  5065.2  413.54  5071.1  414.97
  5080.7  414.25  5094.1  414.74  5117.5  413.51  5177.7  415.05  5298.5  416.72
#Mann=4,-1,0
  4623.2    0.05       0  4855.7     0.1       0  4876.0    0.07       0
  4880.0     0.1       0
Bank Sta=4876,4880
Exp/Cntr=0.3,0.1

Type RM Length L Ch R = 1,686,366,366,366
BEGIN DESCRIPTION:
DUCK CREEK TRIB 44 5 0
END DESCRIPTION:
XS GIS Cut Line= 4
      3489937.55     10432834.94      3489767.76     10432840.39
      3489463.52     10433027.48      3489460.79     10433214.51
#Sta/Elev= 30
  4601.1  419.31  4657.9  418.39  4696.6  416.96  4771.0  415.45  4819.9  413.86
  4862.5  413.05  4871.5  408.24  4877.9  406.69  4880.0  407.82  4883.8  409.86
  4893.3  412.28  4899.2  412.18  4914.6  410.90  4930.3  410.37  4951.3  409.44
  4978.4  406.40  5007.3  405.32  5007.5  404.82  5011.0  404.82  5011.3  405.32
  5015.9  405.72  5059.4  406.98  5082.7  408.69  5094.6  411.57  5109.8  412.93
  5125.2  412.94  5127.3  413.31  5172.3  414.37  5272.3  415.17  5315.2  415.97
#Mann=6,-1,0
  4601.1    0.05       0  4880.0     0.1       0  4930.3    0.05       0
  5007.3    0.03       0  5011.3    0.05       0  5015.9     0.1       0
Bank Sta=5007.3,5011.3
Exp/Cntr=0.3,0.1

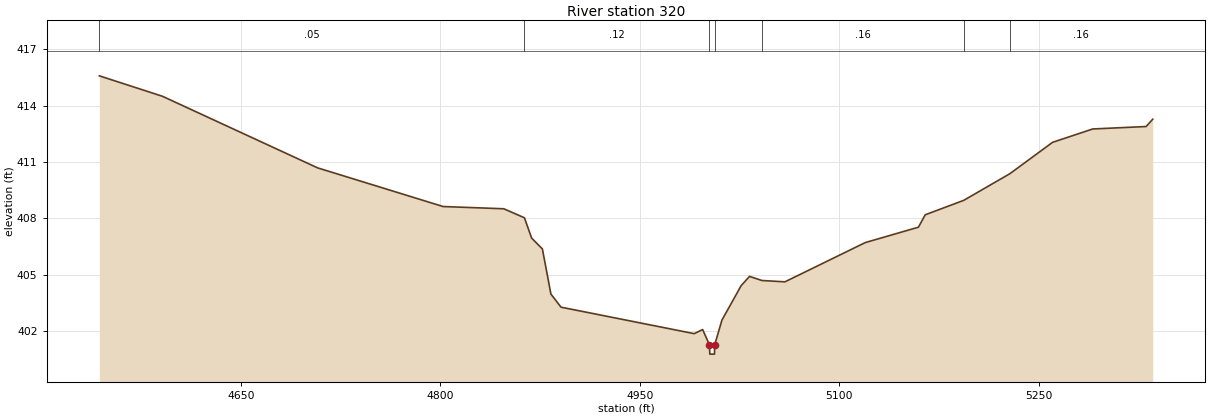
Type RM Length L Ch R = 1,320,0,0,0
BEGIN DESCRIPTION:
DUCK CREEK TRIB 44 1 0
END DESCRIPTION:
XS GIS Cut Line= 4
      3489766.89     10432687.83      3489518.92     10432600.63
      3489332.74     10432744.12      3489367.13     10433036.40
#Sta/Elev= 30
  4543.6  415.59  4591.1  414.50  4707.7  410.69  4802.1  408.63  4847.8  408.51
  4863.3  408.03  4868.7  406.95  4876.8  406.37  4883.2  403.97  4890.8  403.27
  4991.0  401.86  4997.3  402.08  5002.4  401.27  5002.7  400.77  5006.2  400.77
  5006.4  401.27  5011.8  402.58  5026.3  404.42  5032.6  404.91  5041.9  404.69
  5059.2  404.62  5119.6  406.71  5159.6  407.53  5164.7  408.19  5193.7  408.96
  5228.4  410.38  5260.5  412.05  5290.7  412.76  5330.8  412.89  5335.8  413.28
#Mann=7,-1,0
  4543.6    0.05       0  4863.3    0.12       0  5002.4    0.07       0
  5006.4    0.12       0  5041.9    0.16       0  5193.7    0.12       0
  5228.4    0.16       0
Bank Sta=5002.4,5006.4
Exp/Cntr=0.3,0.1

Chan Stop Cuts=-1