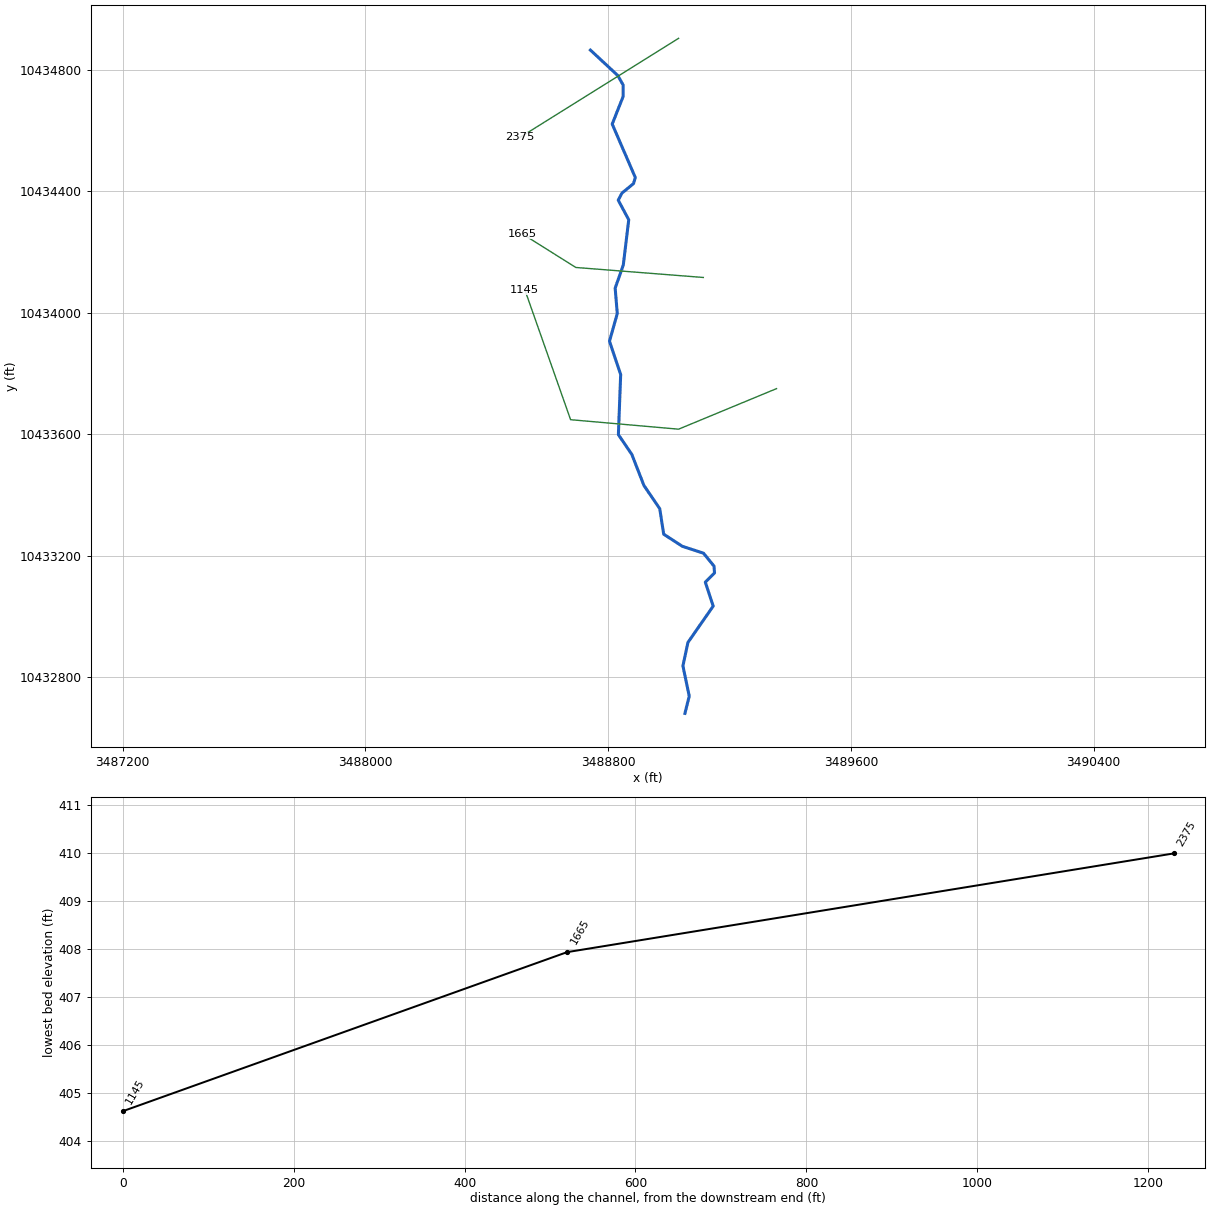
--- DUCK CREEK TRIB 45.prj (project) ---

Proj Title=DUCK CREEK TRIB 45 Base Level Engineering
Current Plan=p01
Default Exp/Contr=0.3,0.1
English Units
Geom File=g01
Flow File=f01
Plan File=p01
BEGIN DESCRIPTION:
DUCK CREEK TRIB 45
END DESCRIPTION:

--- DUCK CREEK TRIB 45.p01 (plan) ---

Plan Title=Multiple Run
Short Identifier=Multiple
Geom File=g01
Flow File=f01
Subcritical Flow
K Sum by GR= 0
Std Step Tol= 0.01
Critical Tol= 0.01
Num of Std Step Trials= 20
Max Error Tol= 0.3
Flow Tol Ratio= 0.001
Split Flow NTrial= 30
Split Flow Tol= 0.02
Split Flow Ratio= 0.02
Log Output Level= 0
Friction Slope Method= 1
Unsteady Friction Slope Method= 2
Unsteady Bridges Friction Slope Method= 1
Parabolic Critical Depth
Global Vel Dist=  1 , 1 , 1
Global Log Level= 0
CheckData=True
Encroach Param= -1, 0, 0, 0
BEGIN DESCRIPTION:
Multiple Run
END DESCRIPTION:

--- DUCK CREEK TRIB 45.f01 (steady flow) ---

Flow Title=Multiple
Number of Profiles=7
Profile Names=10-year,25-year,50-year,1pct_min,100-year,1pct_plu,500-year
River Rch & RM= DUCK CREEK TRIB ,Reach-1,2375
     347     449     527     454     615     831     829
Boundary for River Rch & Prof#=DUCK CREEK TRIB ,Reach-1,1
Up Type=0
Dn Type=3
Dn Slope=0.005
Boundary for River Rch & Prof#=DUCK CREEK TRIB ,Reach-1,2
Up Type=0
Dn Type=3
Dn Slope=0.005
Boundary for River Rch & Prof#=DUCK CREEK TRIB ,Reach-1,3
Up Type=0
Dn Type=3
Dn Slope=0.005
Boundary for River Rch & Prof#=DUCK CREEK TRIB ,Reach-1,4
Up Type=0
Dn Type=3
Dn Slope=0.005
Boundary for River Rch & Prof#=DUCK CREEK TRIB ,Reach-1,5
Up Type=0
Dn Type=3
Dn Slope=0.005
Boundary for River Rch & Prof#=DUCK CREEK TRIB ,Reach-1,6
Up Type=0
Dn Type=3
Dn Slope=0.005
Boundary for River Rch & Prof#=DUCK CREEK TRIB ,Reach-1,7
Up Type=0
Dn Type=3
Dn Slope=0.005

--- DUCK CREEK TRIB 45.g01 (geometry) ---

Geom Title=Existing Conditions

River Reach=DUCK CREEK TRIB ,Reach-1
Reach XY= 30
      3488741.80     10434865.92      3488832.09     10434782.03
      3488849.66     10434750.69      3488849.69     10434713.02
      3488813.61     10434622.07      3488889.71     10434445.95
      3488883.95     10434426.02      3488845.64     10434394.41
      3488833.48     10434371.25      3488868.08     10434306.64
      3488850.13     10434157.45      3488823.38     10434081.16
      3488830.27     10433997.48      3488804.68     10433906.19
      3488841.50     10433796.40      3488833.99     10433598.36
      3488878.26     10433533.26      3488918.19     10433430.83
      3488970.28     10433354.44      3488983.30     10433270.24
      3489044.93     10433230.31      3489114.37     10433207.74
      3489149.10     10433165.20      3489150.83     10433142.63
      3489120.45     10433112.25      3489146.49     10433033.26
      3489063.16     10432913.47      3489046.67     10432836.21
      3489067.50     10432736.38      3489053.29     10432679.72

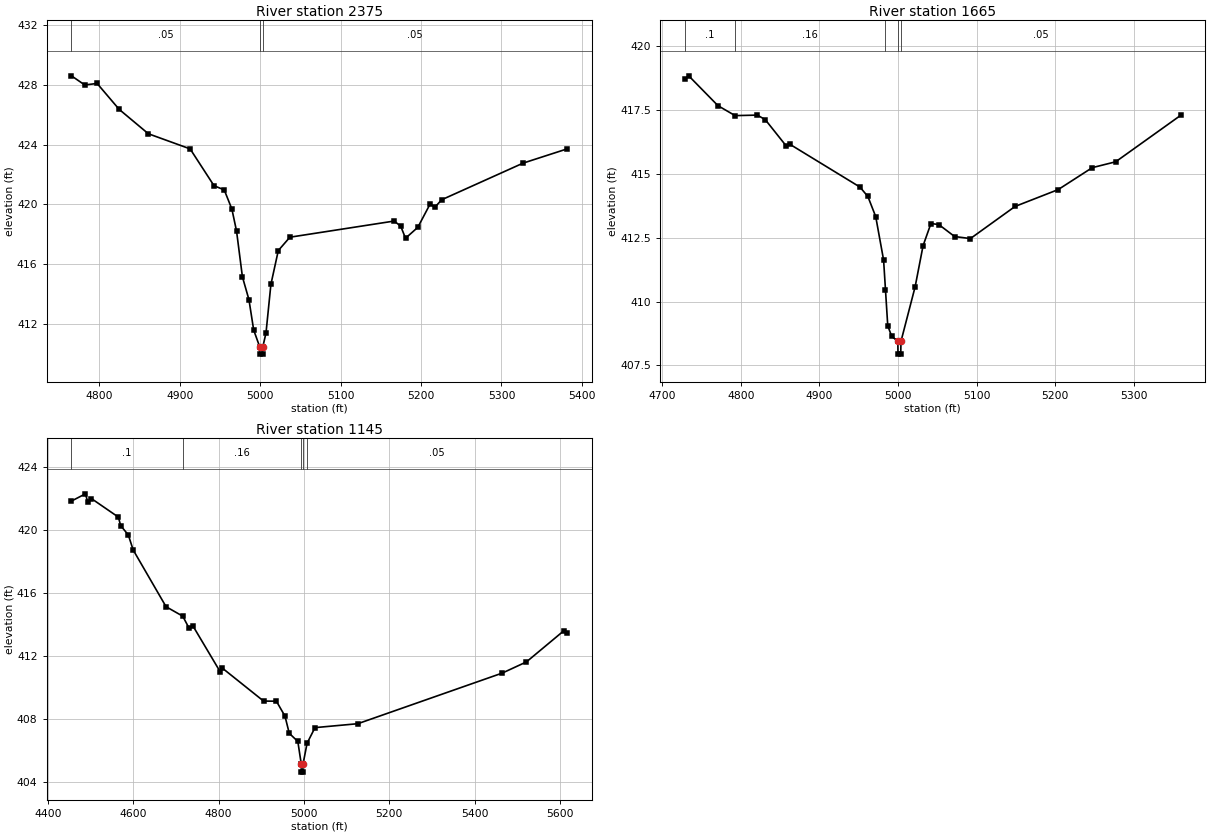
Type RM Length L Ch R = 1,2375,710,710,710
BEGIN DESCRIPTION:
DUCK CREEK TRIB 45 5 0
END DESCRIPTION:
XS GIS Cut Line= 2
      3489032.37     10434904.63      3488509.82     10434578.26
#Sta/Elev= 30
  4765.5  428.59  4782.0  427.98  4797.4  428.08  4824.8  426.35  4861.1  424.72
  4913.0  423.71  4942.7  421.25  4955.4  420.97  4964.9  419.69  4970.7  418.22
  4978.0  415.16  4986.1  413.64  4992.0  411.61  4999.4  410.50  4999.7  410.00
  5003.2  410.00  5003.4  410.50  5007.3  411.41  5013.4  414.66  5022.6  416.92
  5037.0  417.81  5166.7  418.89  5174.8  418.54  5180.7  417.74  5196.0  418.47
  5211.4  420.04  5217.2  419.81  5225.6  420.31  5326.9  422.76  5381.6  423.71
#Mann=3,-1,0
  4765.5    0.05       0  4999.4   0.035       0  5003.4    0.05       0
Bank Sta=4999.4,5003.4
Exp/Cntr=0.3,0.1

Type RM Length L Ch R = 1,1665,520,520,520
BEGIN DESCRIPTION:
DUCK CREEK TRIB 45 2 2
END DESCRIPTION:
XS GIS Cut Line= 3
      3489113.95     10434116.43      3488693.82     10434149.42
      3488516.88     10434260.44
#Sta/Elev= 30
  4729.0  418.73  4733.8  418.85  4771.0  417.68  4792.8  417.29  4821.1  417.31
  4831.2  417.13  4857.8  416.10  4862.8  416.16  4951.5  414.49  4961.6  414.12
  4971.6  413.33  4981.6  411.63  4984.0  410.46  4986.9  409.05  4991.9  408.64
  4999.7  408.44  4999.9  407.94  5003.4  407.94  5003.7  408.44  5021.7  410.58
  5031.8  412.19  5041.8  413.06  5051.8  413.02  5071.9  412.55  5092.0  412.47
  5148.8  413.73  5203.6  414.39  5246.9  415.25  5276.7  415.48  5359.3  417.30
#Mann=5,-1,0
  4729.0     0.1       0  4792.8    0.16       0  4984.0    0.05       0
  4999.7    0.03       0  5003.7    0.05       0
Bank Sta=4999.7,5003.7
Exp/Cntr=0.3,0.1

Type RM Length L Ch R = 1,1145,0,0,0
BEGIN DESCRIPTION:
DUCK CREEK TRIB 45 3 0
END DESCRIPTION:
XS GIS Cut Line= 4
      3489355.25     10433750.10      3489032.36     10433616.43
      3488676.46     10433647.68      3488525.41     10434076.52
#Sta/Elev= 30
  4455.2  421.86  4488.0  422.32  4493.4  421.79  4501.9  422.02  4565.1  420.84
  4570.5  420.30  4588.5  419.70  4599.8  418.75  4676.9  415.14  4715.9  414.54
  4730.1  413.81  4740.0  413.91  4804.4  410.97  4808.5  411.24  4905.3  409.14
  4935.4  409.13  4955.5  408.18  4965.5  407.09  4985.6  406.57  4993.7  405.12
  4993.9  404.62  4997.4  404.62  4997.7  405.12  5007.3  406.46  5025.8  407.45
  5126.2  407.70  5464.6  410.92  5521.2  411.63  5608.8  413.61  5616.6  413.47
#Mann=5,-1,0
  4455.2     0.1       0  4715.9    0.16       0  4993.7    0.07       0
  4997.7    0.16       0  5007.3    0.05       0
Bank Sta=4993.7,4997.7
Exp/Cntr=0.3,0.1

Chan Stop Cuts=-1