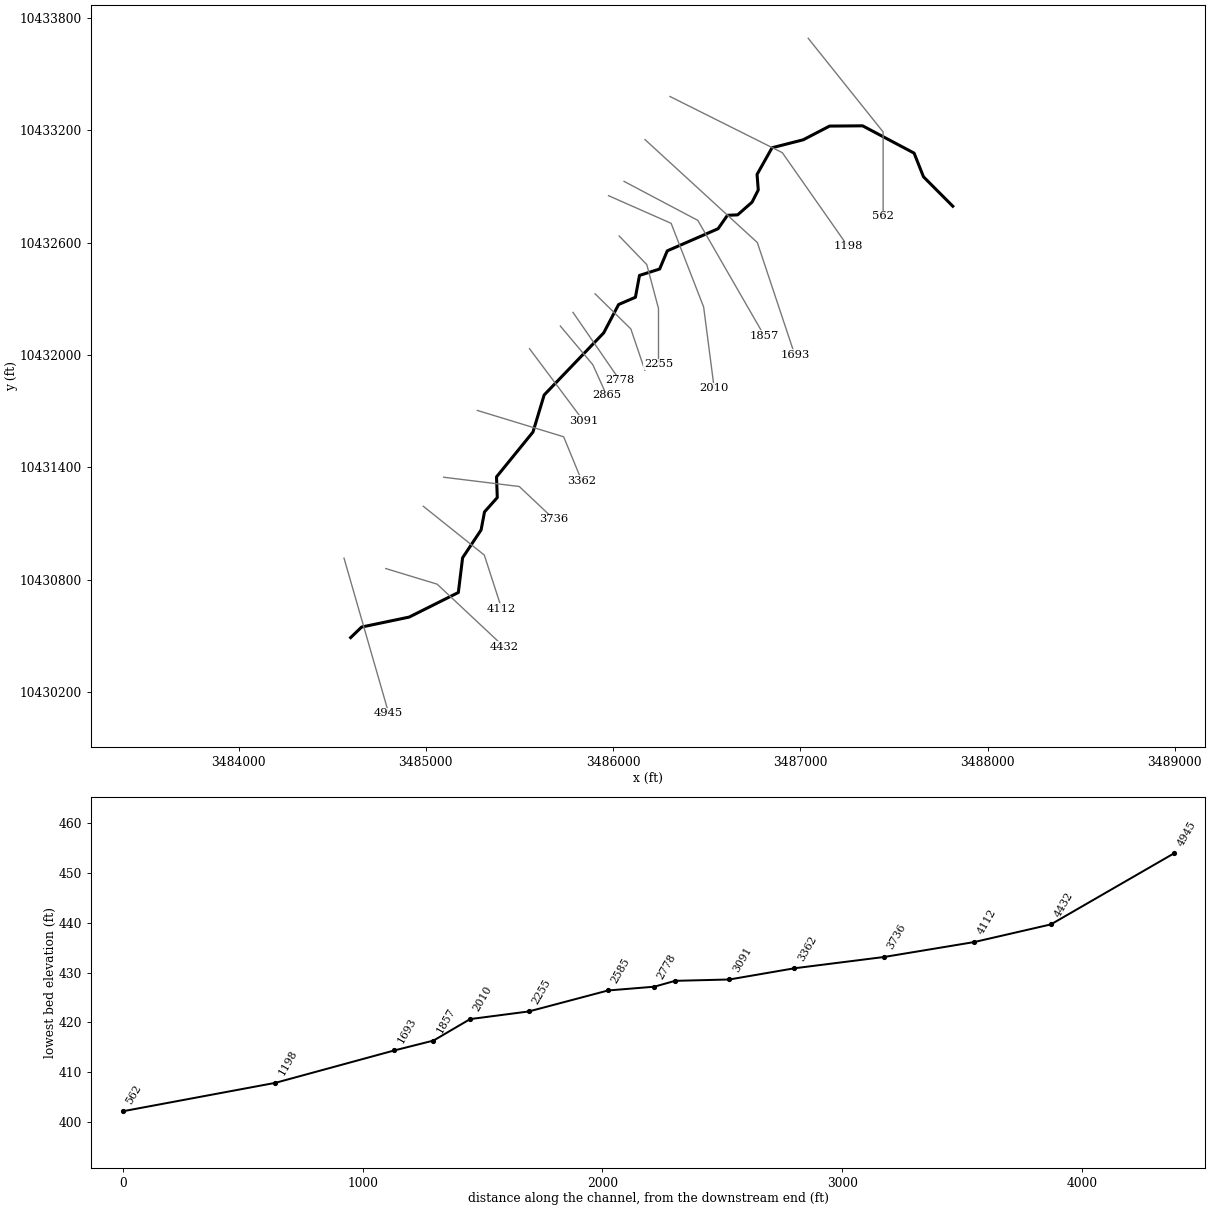
--- DUCK CREEK TRIB 46.prj (project) ---

Proj Title=DUCK CREEK TRIB 46 Base Level Engineering
Current Plan=p01
Default Exp/Contr=0.3,0.1
English Units
Geom File=g01
Flow File=f01
Plan File=p01
Y Axis Title=Elevation
X Axis Title(PF)=Main Channel Distance
X Axis Title(XS)=Station
BEGIN DESCRIPTION:
DUCK CREEK TRIB 46
END DESCRIPTION:
DSS Export Rating Curves= 0
DSS Export Rating Curve Sorted= 0
DSS Export Volume Flow Curves= 0
DXF OffsetX= 0
DXF OffsetY= 0
DXF ScaleX= 1
DXF ScaleY= 10

--- DUCK CREEK TRIB 46.p01 (plan) ---

Plan Title=Multiple Run
Short Identifier=Multiple
Geom File=g01
Flow File=f01
Subcritical Flow
K Sum by GR= 0
Std Step Tol= 0.01
Critical Tol= 0.01
Num of Std Step Trials= 20
Max Error Tol= 0.3
Flow Tol Ratio= 0.001
Split Flow NTrial= 30
Split Flow Tol= 0.02
Split Flow Ratio= 0.02
Log Output Level= 0
Friction Slope Method= 1
Unsteady Friction Slope Method= 2
Unsteady Bridges Friction Slope Method= 1
Parabolic Critical Depth
Global Vel Dist=  1 , 1 , 1
Global Log Level= 0
CheckData=True
Encroach Param= -1, 0, 0, 0
BEGIN DESCRIPTION:
Multiple Run
END DESCRIPTION:

--- DUCK CREEK TRIB 46.f01 (steady flow) ---

Flow Title=Multiple
Program Version=4.10
Number of Profiles= 7
Profile Names=10-year,25-year,50-year,1pct_min,100-year,1pct_plu,500-year
River Rch & RM=DUCK CREEK TRIB,Reach-1         ,4945
     380     496     587     509     689     931     942
Boundary for River Rch & Prof#=DUCK CREEK TRIB,Reach-1         , 1
Up Type= 0
Dn Type= 3
Dn Slope=0.011
Boundary for River Rch & Prof#=DUCK CREEK TRIB,Reach-1         , 2
Up Type= 0
Dn Type= 3
Dn Slope=0.011
Boundary for River Rch & Prof#=DUCK CREEK TRIB,Reach-1         , 3
Up Type= 0
Dn Type= 3
Dn Slope=0.011
Boundary for River Rch & Prof#=DUCK CREEK TRIB,Reach-1         , 4
Up Type= 0
Dn Type= 3
Dn Slope=0.011
Boundary for River Rch & Prof#=DUCK CREEK TRIB,Reach-1         , 5
Up Type= 0
Dn Type= 3
Dn Slope=0.011
Boundary for River Rch & Prof#=DUCK CREEK TRIB,Reach-1         , 6
Up Type= 0
Dn Type= 3
Dn Slope=0.011
Boundary for River Rch & Prof#=DUCK CREEK TRIB,Reach-1         , 7
Up Type= 0
Dn Type= 3
Dn Slope=0.011
DSS Import GetInterval= 0
DSS Import GetPeak= 0
DSS Import FillOption= 0

--- DUCK CREEK TRIB 46.g01 (geometry) ---

Geom Title=Existing Conditions
Program Version=4.10

River Reach=DUCK CREEK TRIB ,Reach-1
Reach XY= 30
      3484598.42     10430491.18      3484657.02      10430547.6
      3484910.92     10430600.77      3485173.51     10430732.06
       3485196.3     10430917.61      3485295.08     10431066.21
      3485313.31     10431162.56      3485381.53     10431239.12
      3485377.37     10431349.54      3485572.16     10431589.12
      3485631.81     10431786.85      3485949.65     10432118.42
      3486029.34     10432269.98      3486119.18     10432308.79
      3486140.96     10432425.41       3486248.6     10432459.67
       3486289.3     10432556.65      3486560.78     10432674.88
      3486610.59     10432746.53      3486665.17     10432748.88
      3486742.15      10432816.7       3486775.3     10432881.89
      3486768.83     10432964.81      3486848.88     10433107.24
      3487015.22     10433149.74      3487156.21     10433222.99
       3487332.6     10433224.38       3487607.6     10433078.54
       3487657.6     10432952.15      3487814.27     10432794.96

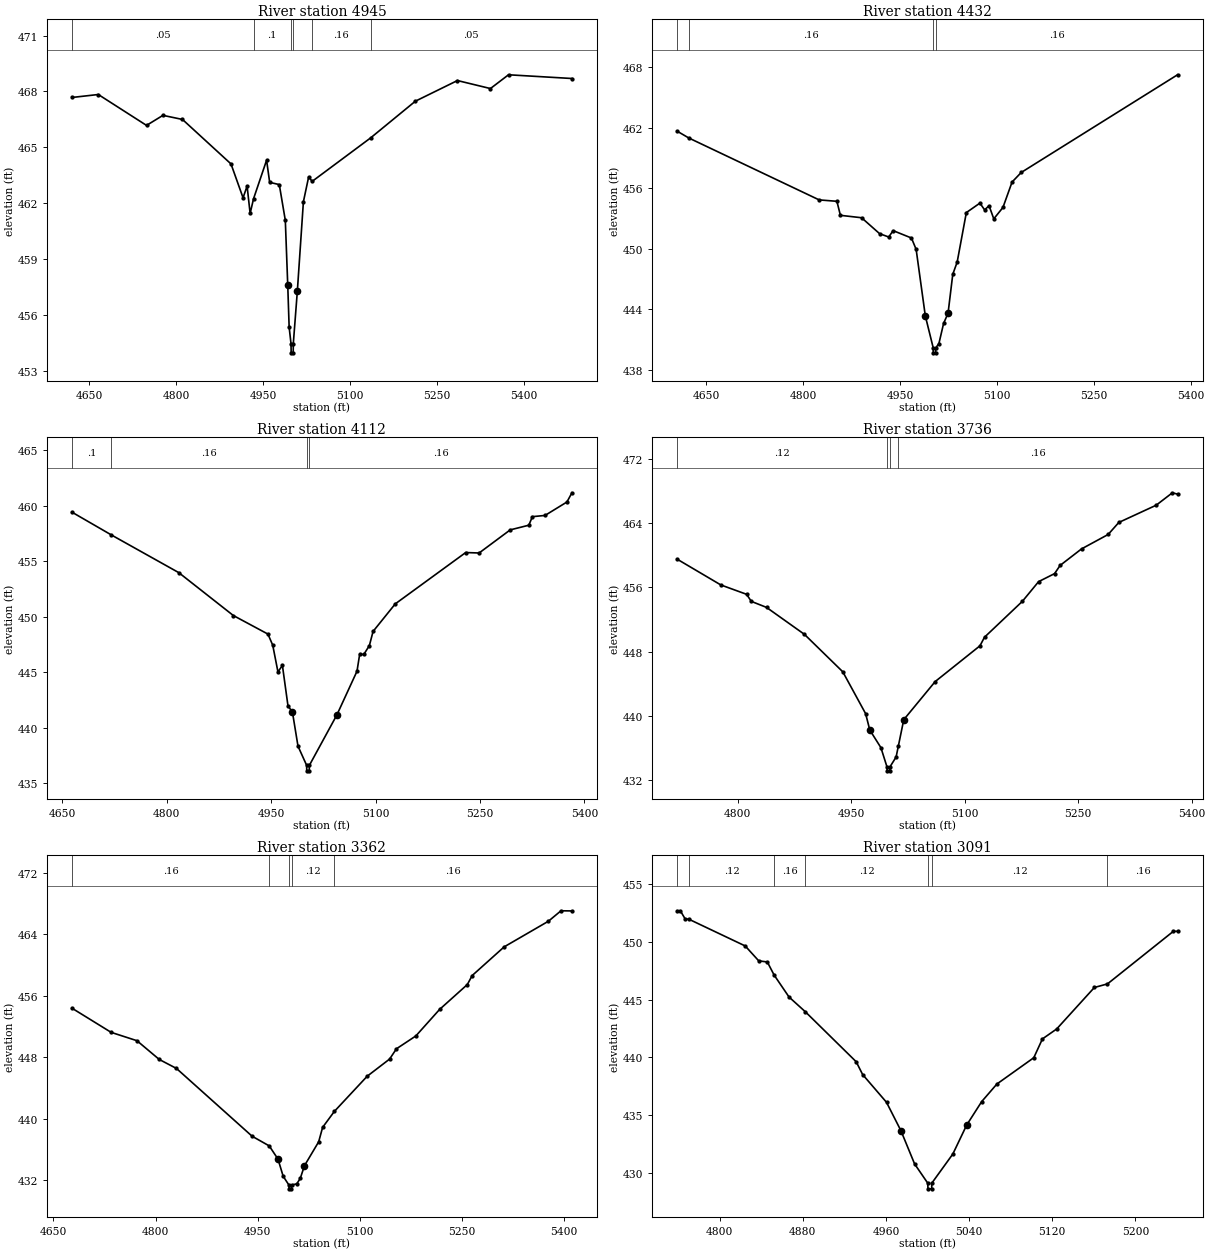
Type RM Length L Ch R = 1 ,4945    ,513,513,513
BEGIN DESCRIPTION:
DUCK CREEK TRIB 46 3 0
END DESCRIPTION:
XS GIS Cut Line= 2
      3484562.99     10430915.45      3484801.68     10430086.53
#Sta/Elev= 30
  4619.7  467.67  4665.3  467.83  4748.5  466.17  4776.8  466.71  4810.5  466.49
  4894.2   464.1    4915  462.28    4922  462.91  4927.2  461.44  4933.1  462.23
  4955.6   464.3  4960.9  463.11  4977.5  462.99  4987.9  461.07  4992.1  457.57
  4994.5  455.33  4997.7  454.45    4998  453.95  5001.5  453.95  5001.7  454.45
  5008.7  457.29  5019.1  462.07  5028.2  463.41  5034.1  463.16  5135.1   465.5
  5212.2  467.47  5284.8  468.58  5341.7  468.15  5372.9  468.89  5482.3  468.69
#Mann= 6 ,-1 , 0
  4619.7     .05       0  4933.1      .1       0  4997.7     .07       0
  5001.7      .1       0  5034.1     .16       0  5135.1     .05       0
Bank Sta=4992.1,5008.7
XS Rating Curve= 0 ,0
Exp/Cntr=0.3,0.1

Type RM Length L Ch R = 1 ,4432    ,320,320,320
BEGIN DESCRIPTION:
DUCK CREEK TRIB 46 12 0
END DESCRIPTION:
XS GIS Cut Line= 3
      3484785.83     10430860.01      3485060.14     10430776.68
      3485416.03     10430443.35
#Sta/Elev= 30
  4605.1  461.65  4622.7  460.99  4824.5  454.85    4852  454.71  4857.4  453.32
  4890.2  453.08  4918.1   451.5  4932.2  451.17  4939.1   451.8  4967.4  451.07
  4974.7  449.94  4988.9  443.34  5001.1  440.18  5001.3  439.68  5004.8  439.68
  5005.1  440.18  5009.9  440.59  5017.2   442.6  5024.1  443.61  5031.4  447.47
  5038.2  448.68  5052.4  453.59  5073.4  454.53  5080.7  453.86  5087.6  454.27
  5094.9  452.97  5109.1   454.1  5123.2  456.62  5137.4  457.57  5379.4  467.26
#Mann= 4 ,-1 , 0
  4605.1     .05       0  4622.7     .16       0  5001.1     .07       0
  5005.1     .16       0
Bank Sta=4988.9,5024.1
XS Rating Curve= 0 ,0
Exp/Cntr=0.3,0.1

Type RM Length L Ch R = 1 ,4112    ,376,376,376
BEGIN DESCRIPTION:
DUCK CREEK TRIB 46 11 0
END DESCRIPTION:
XS GIS Cut Line= 3
      3484986.68     10431192.33      3485312.18     10430931.93
      3485405.31      10430644.8
#Sta/Elev= 30
  4663.5  459.42  4720.4  457.36  4817.2  453.97  4895.6  450.11  4945.3  448.44
  4952.2  447.44  4959.7  445.03  4966.1  445.62  4974.1  441.98  4980.5  441.42
  4988.5  438.35  5000.9  436.63  5001.1  436.13  5004.6  436.13  5004.9  436.63
  5044.5  441.18  5073.3   445.1  5077.1  446.61  5083.1  446.61  5091.1  447.41
  5096.4  448.68  5128.3  451.16  5229.5  455.78  5248.8  455.74  5293.5  457.82
  5320.2  458.24  5325.4  459.01  5343.5  459.12    5375  460.33  5382.2  461.16
#Mann= 4 ,-1 , 0
  4663.5      .1       0  4720.4     .16       0  5000.9     .07       0
  5004.9     .16       0
Bank Sta=4980.5,5044.5
XS Rating Curve= 0 ,0
Exp/Cntr=0.3,0.1

Type RM Length L Ch R = 1 ,3736    ,374,374,374
BEGIN DESCRIPTION:
DUCK CREEK TRIB 46 10 0
END DESCRIPTION:
XS GIS Cut Line= 3
      3485095.24     10431347.62      3485498.92     10431298.14
       3485683.8     10431123.68
#Sta/Elev= 30
  4720.4   459.5  4777.7  456.31  4811.8  455.14    4818  454.26  4838.1  453.51
  4888.2  450.15  4938.9  445.48  4969.1  440.26  4974.6  438.22  4989.3  436.02
  4997.3  433.63  4997.6  433.13  5001.1  433.13  5001.3  433.63  5009.4  434.86
  5012.3   436.2  5019.5  439.51    5061  444.26  5120.2  448.72  5126.2  449.79
  5176.3  454.27  5197.7  456.72  5218.8  457.72  5226.1  458.74  5254.4   460.8
  5289.6   462.6  5303.7   464.1  5353.1  466.25  5374.5   467.8  5381.3  467.63
#Mann= 4 ,-1 , 0
  4720.4     .12       0  4997.3     .07       0  5001.3     .12       0
  5012.3     .16       0
Bank Sta=4974.6,5019.5
XS Rating Curve= 0 ,0
Exp/Cntr=0.3,0.1

Type RM Length L Ch R = 1 ,3362    ,271,271,271
BEGIN DESCRIPTION:
DUCK CREEK TRIB 46 9 0
END DESCRIPTION:
XS GIS Cut Line= 3
      3485274.96     10431704.39       3485735.9     10431563.77
      3485832.25     10431329.41
#Sta/Elev= 30
    4677  454.38  4734.7  451.23  4772.7  450.14  4805.5   447.7  4830.8  446.53
    4942  437.71  4967.2  436.45  4980.1  434.73  4987.7   432.5  4996.1  431.36
  4996.4  430.86  4999.9  430.86  5000.1  431.36  5007.7  431.51  5012.9  432.23
    5019  433.87  5039.9  436.98  5045.7  438.86  5062.9  440.93  5111.3  445.52
  5144.2  447.75  5154.3  449.09  5182.8  450.76  5217.7  454.21  5258.5  457.45
  5265.6  458.62  5312.6  462.35  5377.7  465.69  5396.2  467.05  5412.3  467.03
#Mann= 5 ,-1 , 0
    4677     .16       0  4967.2     .12       0  4996.1     .07       0
  5000.1     .12       0  5062.9     .16       0
Bank Sta=4980.1,5019
XS Rating Curve= 0 ,0
Exp/Cntr=0.3,0.1

Type RM Length L Ch R = 1 ,3091    ,226,226,226
BEGIN DESCRIPTION:
DUCK CREEK TRIB 46 8 0
END DESCRIPTION:
XS GIS Cut Line= 2
      3485553.77      10432033.9      3485841.94     10431648.52
#Sta/Elev= 30
  4759.4  452.72  4762.2  452.72  4766.7  452.03  4770.6  451.98  4824.6  449.67
  4837.6  448.38  4845.9  448.28  4852.4  447.15  4866.8  445.24  4882.4  443.97
  4931.4  439.63  4937.6  438.52  4960.6  436.11  4974.5  433.64  4987.6  430.77
  5000.2  429.11  5000.5  428.61    5004  428.61  5004.2  429.11  5024.4  431.63
  5037.7  434.14  5052.2  436.18  5066.8   437.7  5102.3  439.98  5110.6  441.61
  5124.3  442.47  5160.6  446.07  5173.2  446.38  5236.6  450.94  5240.6  450.94
#Mann= 7 ,-1 , 0
  4759.4     .16       0  4770.6     .12       0  4852.4     .16       0
  4882.4     .12       0  5000.2     .07       0  5004.2     .12       0
  5173.2     .16       0
Bank Sta=4974.5,5037.7
XS Rating Curve= 0 ,0
Exp/Cntr=0.3,0.1

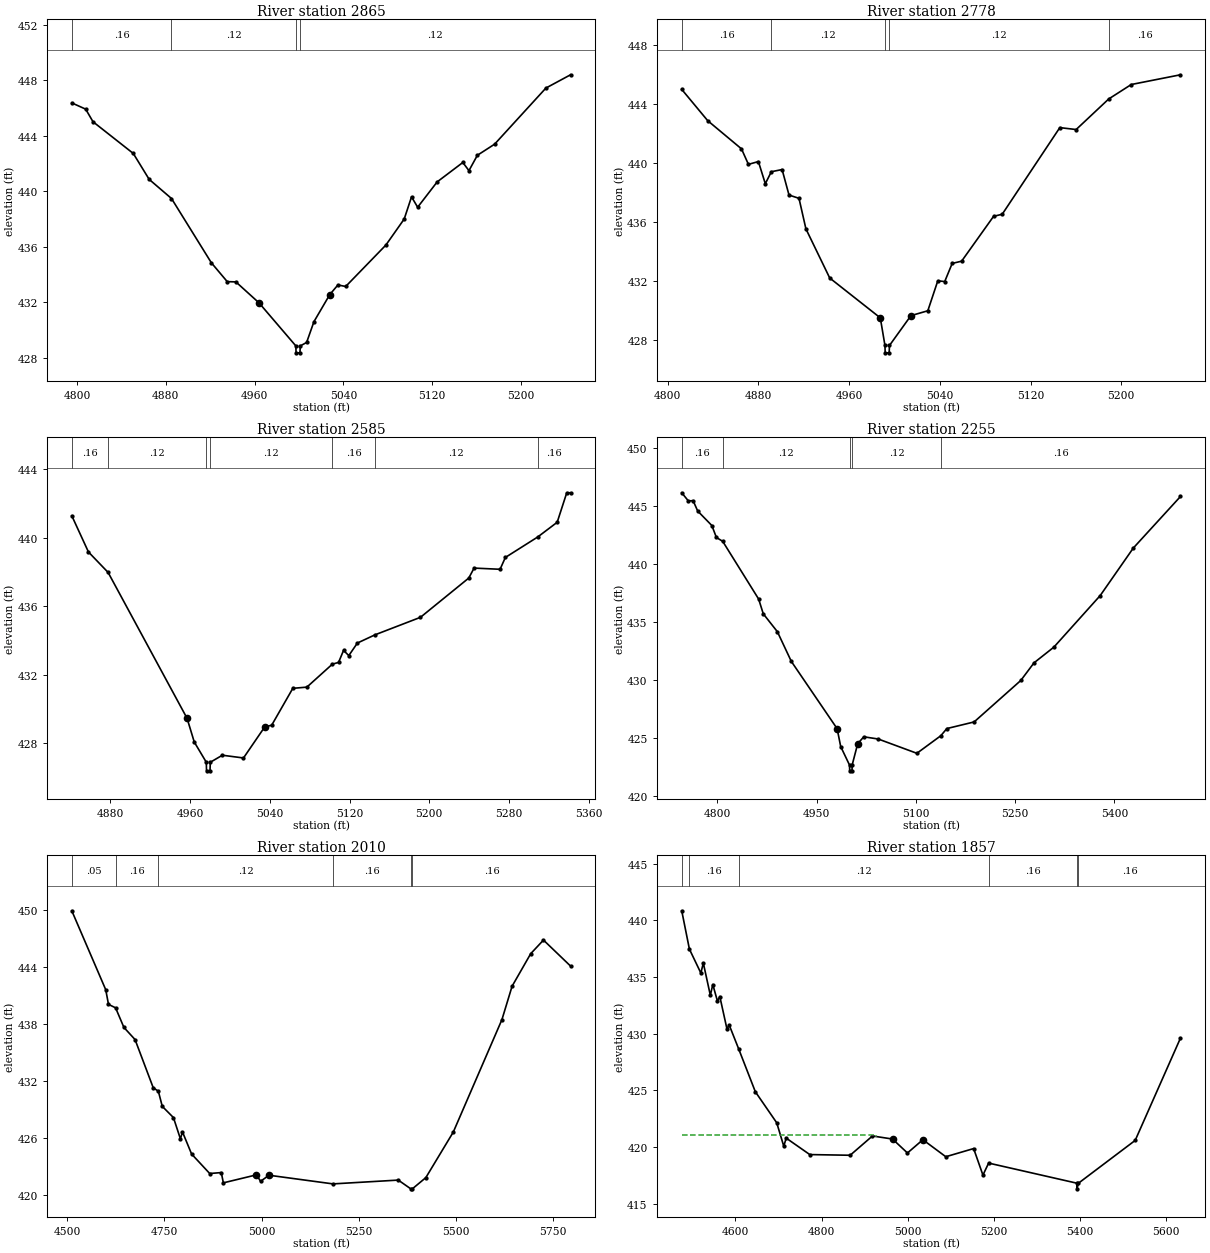
Type RM Length L Ch R = 1 ,2865    ,87,87,87
BEGIN DESCRIPTION:
DUCK CREEK TRIB 46 6 1
END DESCRIPTION:
XS GIS Cut Line= 3
      3485718.12     10432155.15      3485891.73     10431948.55
      3485965.69     10431785.17
#Sta/Elev= 30
  4795.4  446.38  4807.9  445.93  4814.5  445.02  4850.8  442.73  4865.1  440.86
  4885.2  439.48  4921.1  434.84  4935.4  433.48  4943.2  433.46    4964  431.95
  4997.2  428.84  4997.4  428.34  5000.9  428.34  5001.2  428.84  5006.9  429.09
  5013.5  430.59  5027.8  432.55  5035.1  433.24  5042.1  433.13  5078.3  436.12
  5094.8     438  5101.4   439.6  5106.9  438.85  5124.5  440.68  5147.6  442.08
  5153.1  441.49  5160.7   442.6  5176.2   443.4  5222.4  447.45  5244.6  448.41
#Mann= 4 ,-1 , 0
  4795.4     .16       0  4885.2     .12       0  4997.2     .07       0
  5001.2     .12       0
Bank Sta=4964,5027.8
XS Rating Curve= 0 ,0
Exp/Cntr=0.3,0.1

Type RM Length L Ch R = 1 ,2778    ,193,193,193
BEGIN DESCRIPTION:
DUCK CREEK TRIB 46 6 0
END DESCRIPTION:
XS GIS Cut Line= 2
      3485785.84     10432228.05      3486035.37     10431865.89
#Sta/Elev= 30
  4812.4  445.01  4835.3  442.89  4865.1  440.98  4871.2  439.93    4880  440.12
  4886.1  438.62  4891.4  439.43  4900.9  439.58    4907  437.85  4915.8  437.63
  4921.9  435.56  4942.9  432.23  4987.5  429.53  4991.6  427.66  4991.8  427.16
  4995.3  427.16  4995.6  427.66  5014.5  429.68  5029.4  430.01  5038.2  432.04
  5044.3  431.99  5050.9  433.22  5059.2  433.37  5087.4  436.41    5095  436.55
  5145.8  442.42  5160.2  442.29  5188.9  444.36  5208.8  445.34  5252.2     446
#Mann= 5 ,-1 , 0
  4812.4     .16       0  4891.4     .12       0  4991.6     .07       0
  4995.6     .12       0  5188.9     .16       0
Bank Sta=4987.5,5014.5
XS Rating Curve= 0 ,0
Exp/Cntr=0.3,0.1

Type RM Length L Ch R = 1 ,2585    ,330,330,330
BEGIN DESCRIPTION:
DUCK CREEK TRIB 46 7 0
END DESCRIPTION:
XS GIS Cut Line= 3
      3485903.86     10432327.05      3486094.86     10432139.52
      3486169.53     10431918.99
#Sta/Elev= 30
  4841.3  441.27    4858  439.16  4877.7  437.97    4957  429.46  4964.2  428.08
  4976.3   426.9  4976.5   426.4    4980   426.4  4980.3   426.9  4992.4  427.31
  5013.6  427.15  5034.9  428.96  5041.9  429.06  5063.1  431.21  5077.2  431.28
  5102.8  432.62    5109  432.72    5114  433.42  5119.3  433.12  5127.9  433.85
  5145.6  434.33  5191.2  435.35  5239.7  437.64    5245  438.22  5271.1  438.15
  5276.4  438.84  5308.8  440.03  5328.4  440.89    5338  442.61  5341.8  442.61
#Mann= 7 ,-1 , 0
  4841.3     .16       0  4877.7     .12       0  4976.3     .07       0
  4980.3     .12       0  5102.8     .16       0  5145.6     .12       0
  5308.8     .16       0
Bank Sta=4957,5034.9
XS Rating Curve= 0 ,0
Exp/Cntr=0.3,0.1

Type RM Length L Ch R = 1 ,2255    ,245,245,245
BEGIN DESCRIPTION:
DUCK CREEK TRIB 46 5 1
END DESCRIPTION:
XS GIS Cut Line= 4
      3486032.33     10432636.08      3486179.93     10432483.27
      3486242.43      10432248.9      3486242.43     10431950.31
#Sta/Elev= 30
  4746.1  446.13  4756.1  445.43  4763.3  445.45  4770.2  444.56  4791.6  443.31
  4798.5  442.28    4808  441.95  4862.3  436.98  4869.3  435.71  4890.6  434.17
  4911.7  431.61  4980.9  425.82  4986.3  424.28  4999.6  422.69  4999.9  422.19
  5003.4  422.19  5003.6  422.69    5012  424.53  5021.2  425.12    5043  424.93
  5101.4   423.7  5137.5  425.21  5146.7  425.83  5187.9   426.4  5258.4  429.97
  5278.4  431.49  5308.4  432.84  5378.4  437.28  5428.4  441.37  5499.7  445.81
#Mann= 5 ,-1 , 0
  4746.1     .16       0    4808     .12       0  4999.6     .07       0
  5003.6     .12       0  5137.5     .16       0
Bank Sta=4980.9,5012
XS Rating Curve= 0 ,0
Exp/Cntr=0.3,0.1

Type RM Length L Ch R = 1 ,2010    ,153,153,153
BEGIN DESCRIPTION:
DUCK CREEK TRIB 46 5 2
END DESCRIPTION:
XS GIS Cut Line= 4
      3485975.71     10432851.26      3486309.94     10432703.68
      3486483.55     10432256.63      3486539.97     10431822.62
#Sta/Elev= 30
  4511.9  449.88  4599.2  441.58  4606.3  440.04  4624.5  439.68  4645.9  437.62
  4674.6  436.34  4721.3  431.28  4734.5  430.91  4744.6  429.32  4773.3  428.14
  4791.2  425.91  4796.6  426.63    4820  424.31  4866.6  422.26  4896.3  422.36
  4901.7  421.28  4986.7  422.12  4997.5  421.44  5018.9  422.08  5183.6  421.17
  5351.5  421.57  5383.7  420.65  5387.7  420.65  5422.4  421.83    5493  426.62
  5618.1  438.44  5644.2  441.95  5692.1  445.37  5724.9   446.8  5794.5  444.07
#Mann= 6 ,-1 , 0
  4511.9     .05       0  4624.5     .16       0  4734.5     .12       0
  5183.6     .16       0  5383.7     .07       0  5387.7     .16       0
#Block Obstruct= 2 , 0
         5013.93  421.46 5021.87          421.46
Bank Sta=4986.7,5018.9
XS Rating Curve= 0 ,0
Exp/Cntr=0.3,0.1

Type RM Length L Ch R = 1 ,1857    ,164,164,164
BEGIN DESCRIPTION:
Mapping XS b45f6008
END DESCRIPTION:
XS GIS Cut Line= 3
      3486058.44      10432927.7       3486452.5     10432719.38
      3486807.73     10432102.49
#Sta/Elev= 30
  4475.5  440.84  4493.3  437.46  4519.9  435.35  4525.6  436.23  4541.9  433.39
  4547.6  434.34  4558.3  432.89  4563.9  433.28  4580.3  430.45  4585.9  430.75
  4607.5  428.68  4646.3  424.89    4696  422.15  4712.3  420.09    4718   420.8
  4772.7  419.35  4866.4  419.29  4918.2  420.99  4964.8  420.72  4999.4  419.49
  5035.2  420.66  5088.4  419.16    5153  419.88  5174.6  417.54  5187.8   418.6
  5392.4  416.83  5392.7  416.33  5396.4  416.83    5528   420.6  5633.1  429.62
#Mann= 6 ,-1 , 0
  4475.5     .05       0  4493.3     .16       0  4607.5     .12       0
  5187.8     .16       0  5392.4     .07       0  5396.4     .16       0
#XS Ineff= 2 , 0
         4926.74  421.08
Permanent Ineff=
       F       F
#Block Obstruct= 2 , 0
         4920.19  419.35 5040.61          419.31
Bank Sta=4964.8,5035.2
XS Rating Curve= 0 ,0
Exp/Cntr=0.3,0.1

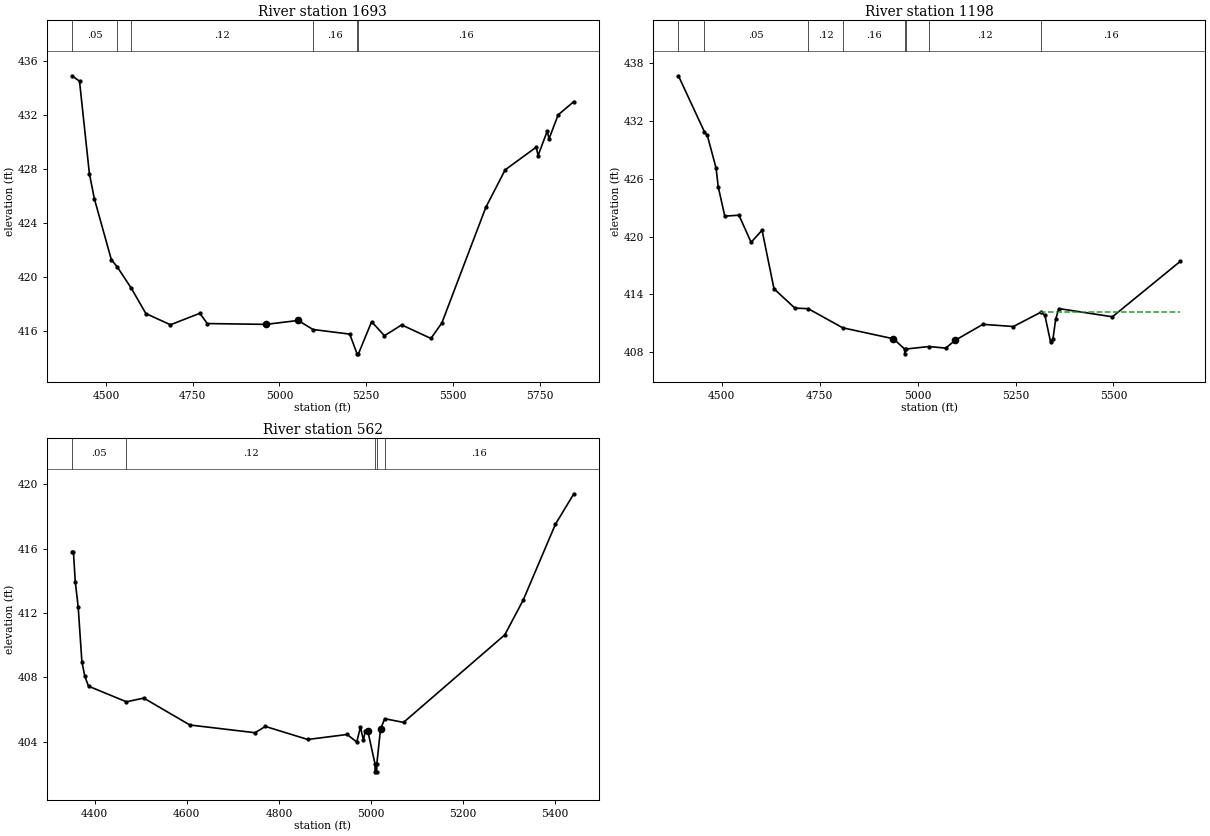
Type RM Length L Ch R = 1 ,1693    ,495,495,495
BEGIN DESCRIPTION:
DUCK CREEK TRIB 46 5 0
END DESCRIPTION:
XS GIS Cut Line= 3
       3486170.4     10433150.85       3486770.4     10432600.84
       3486970.4     10432000.84
#Sta/Elev= 30
  4402.2  434.91    4424  434.51  4452.4  427.68  4466.6  425.83  4515.9  421.29
    4532   420.8  4573.1   419.2  4615.2  417.32  4686.1  416.49  4770.8  417.34
  4792.2  416.58  4961.7  416.52  5054.2  416.81  5096.8  416.14  5202.8   415.8
  5223.8  414.34  5227.8  414.34  5265.8  416.72  5302.7  415.68  5352.3  416.48
  5436.7  415.48  5468.3  416.63  5594.8  425.17  5650.6  427.95  5740.2  429.63
  5745.5  429.01  5771.8  430.81  5777.1  430.25  5803.4  432.02  5848.6     433
#Mann= 6 ,-1 , 0
  4402.2     .05       0    4532     .16       0  4573.1     .12       0
  5096.8     .16       0  5223.8     .07       0  5227.8     .16       0
#Block Obstruct= 2 , 0
         4944.68  416.17 5067.94          416.17
Bank Sta=4961.7,5054.2
XS Rating Curve= 0 ,0
Exp/Cntr=0.3,0.1

Type RM Length L Ch R = 1 ,1198    ,636,636,636
BEGIN DESCRIPTION:
DUCK CREEK TRIB 46 4 0
END DESCRIPTION:
XS GIS Cut Line= 3
      3486303.84     10433380.95      3486903.85     10433080.94
      3487253.87     10432580.91
#Sta/Elev= 30
  4389.5  436.66  4455.7  430.87  4463.2  430.49  4485.6   427.1  4491.2  425.14
  4507.9  422.11  4544.1  422.21    4575   419.4    4603  420.65  4633.5  414.58
  4686.8  412.58  4720.8  412.52  4808.8  410.54  4938.4   409.4  4966.9  408.34
  4967.2  407.84  4970.9  408.34  5029.3   408.6  5071.9  408.43  5095.4  409.23
  5166.9   410.9  5244.5  410.67    5314  412.14  5324.8  411.87  5339.6  409.05
  5345.7   409.4  5352.4   411.4  5360.5  412.53  5497.4  411.68  5670.7  417.43
#Mann= 8 ,-1 , 0
  4389.5     .16       0  4455.7     .05       0  4720.8     .12       0
  4808.8     .16       0  4966.9     .07       0  4970.9     .16       0
  5029.3     .12       0    5314     .16       0
#XS Ineff= 2 , 0
                         5316.33          412.18
Permanent Ineff=
       F       F
Bank Sta=4938.4,5095.4
XS Rating Curve= 0 ,0
Exp/Cntr=0.3,0.1

Type RM Length L Ch R = 1 ,562     ,0,0,0
BEGIN DESCRIPTION:
DUCK CREEK TRIB 46 1 0
END DESCRIPTION:
XS GIS Cut Line= 3
      3487042.13     10433691.61      3487442.11     10433191.64
      3487442.11     10432741.61
#Sta/Elev= 30
  4350.4  415.81  4353.6  415.81  4357.6  413.95    4364  412.35    4372  408.97
  4378.4  408.06  4386.4  407.45  4468.8  406.48  4506.4  406.71  4606.5  405.04
  4748.1  404.56  4770.6  404.95  4862.6  404.14  4948.2  404.45  4969.1  403.98
  4977.1  404.91  4983.5  404.09  4987.5  404.65  4993.2  404.65  5008.7  402.63
  5008.9  402.13  5012.4  402.13  5012.7  402.63  5020.7  404.78  5029.8  405.43
  5070.7   405.2  5290.7  410.64  5330.7   412.8  5400.7  417.51  5440.7   419.4
#Mann= 5 ,-1 , 0
  4350.4     .05       0  4468.8     .12       0  5008.7     .07       0
  5012.7     .12       0  5029.8     .16       0
Bank Sta=4993.2,5020.7
XS Rating Curve= 0 ,0
Exp/Cntr=0.3,0.1

Chan Stop Cuts=-1
Use User Specified Reach Order=0
Composite Channel Slope=5