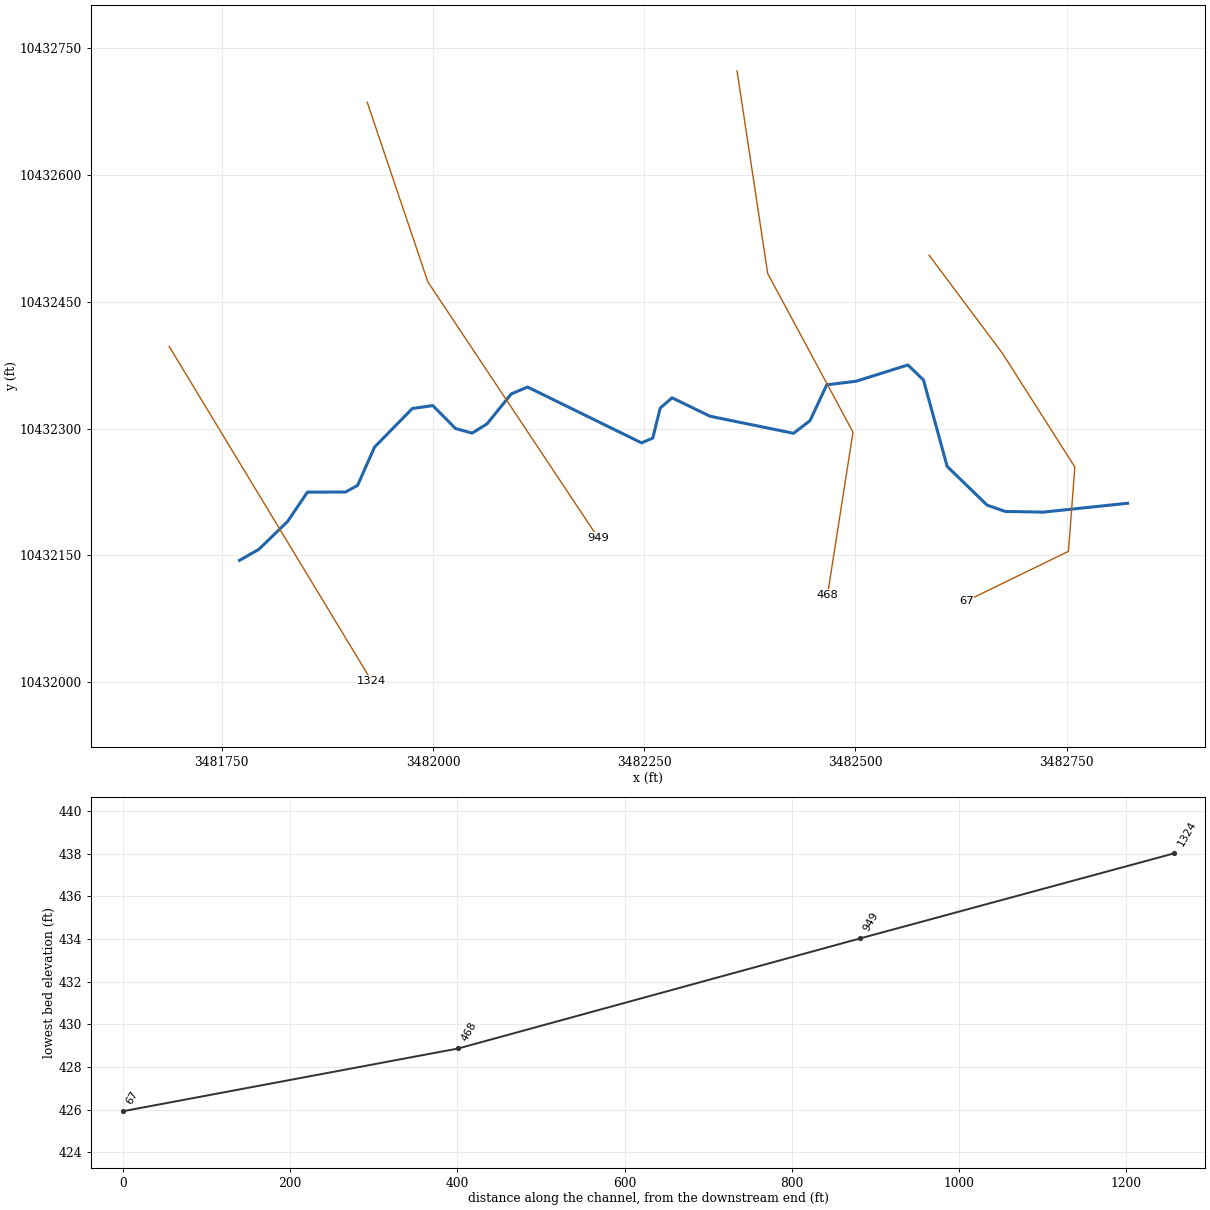
--- DUCK CREEK TRIB 47 1.prj (project) ---

Proj Title=DUCK CREEK TRIB 47 1 Base Level Engineering
Current Plan=p01
Default Exp/Contr=0.3,0.1
English Units
Geom File=g01
Flow File=f01
Plan File=p01
Y Axis Title=Elevation
X Axis Title(PF)=Main Channel Distance
X Axis Title(XS)=Station
BEGIN DESCRIPTION:
DUCK CREEK TRIB 47 1
END DESCRIPTION:
DSS Export Rating Curves= 0
DSS Export Rating Curve Sorted= 0
DSS Export Volume Flow Curves= 0
DXF OffsetX= 0
DXF OffsetY= 0
DXF ScaleX= 1
DXF ScaleY= 10

--- DUCK CREEK TRIB 47 1.p01 (plan) ---

Plan Title=Multiple Run
Short Identifier=Multiple
Geom File=g01
Flow File=f01
Subcritical Flow
K Sum by GR= 0
Std Step Tol= 0.01
Critical Tol= 0.01
Num of Std Step Trials= 20
Max Error Tol= 0.3
Flow Tol Ratio= 0.001
Split Flow NTrial= 30
Split Flow Tol= 0.02
Split Flow Ratio= 0.02
Log Output Level= 0
Friction Slope Method= 1
Unsteady Friction Slope Method= 2
Unsteady Bridges Friction Slope Method= 1
Parabolic Critical Depth
Global Vel Dist=  1 , 1 , 1
Global Log Level= 0
CheckData=True
Encroach Param= -1, 0, 0, 0
BEGIN DESCRIPTION:
Multiple Run
END DESCRIPTION:

--- DUCK CREEK TRIB 47 1.f01 (steady flow) ---

Flow Title=Multiple
Program Version=4.10
Number of Profiles= 7
Profile Names=10-year,25-year,50-year,1pct_min,100-year,1pct_plu,500-year
River Rch & RM=DUCK CREEK TRIB,Reach-1         ,1324
     311     401     470     405     547     740     737
Boundary for River Rch & Prof#=DUCK CREEK TRIB,Reach-1         , 1
Up Type= 0
Dn Type= 3
Dn Slope=0.0085
Boundary for River Rch & Prof#=DUCK CREEK TRIB,Reach-1         , 2
Up Type= 0
Dn Type= 3
Dn Slope=0.0085
Boundary for River Rch & Prof#=DUCK CREEK TRIB,Reach-1         , 3
Up Type= 0
Dn Type= 3
Dn Slope=0.0085
Boundary for River Rch & Prof#=DUCK CREEK TRIB,Reach-1         , 4
Up Type= 0
Dn Type= 3
Dn Slope=0.0085
Boundary for River Rch & Prof#=DUCK CREEK TRIB,Reach-1         , 5
Up Type= 0
Dn Type= 3
Dn Slope=0.0085
Boundary for River Rch & Prof#=DUCK CREEK TRIB,Reach-1         , 6
Up Type= 0
Dn Type= 3
Dn Slope=0.0085
Boundary for River Rch & Prof#=DUCK CREEK TRIB,Reach-1         , 7
Up Type= 0
Dn Type= 3
Dn Slope=0.0085
DSS Import GetInterval= 0
DSS Import GetPeak= 0
DSS Import FillOption= 0

--- DUCK CREEK TRIB 47 1.g01 (geometry) ---

Geom Title=Existing Conditions
Program Version=4.10

River Reach=DUCK CREEK TRIB ,Reach-1
Reach XY= 30
      3481771.04     10432144.07      3481793.72       10432157.
      3481827.75     10432189.91      3481851.37     10432224.81
      3481896.41     10432224.93      3481910.73     10432232.81
      3481930.75     10432278.07      3481975.57     10432323.81
      3481999.79     10432327.21      3482026.68     10432300.05
      3482046.34     10432294.65      3482063.94     10432305.59
      3482092.61     10432341.08      3482111.93     10432349.18
       3482246.8     10432283.09      3482260.07     10432288.74
      3482268.86     10432324.28       3482282.9     10432336.43
      3482327.94     10432314.61      3482426.66     10432294.41
      3482446.12     10432309.35      3482466.02     10432351.79
      3482500.73     10432356.05        3482562.     10432375.31
      3482580.47     10432357.54      3482608.46      10432255.3
      3482655.73     10432209.42       3482677.2     10432201.95
      3482721.98     10432201.12      3482822.11     10432211.64

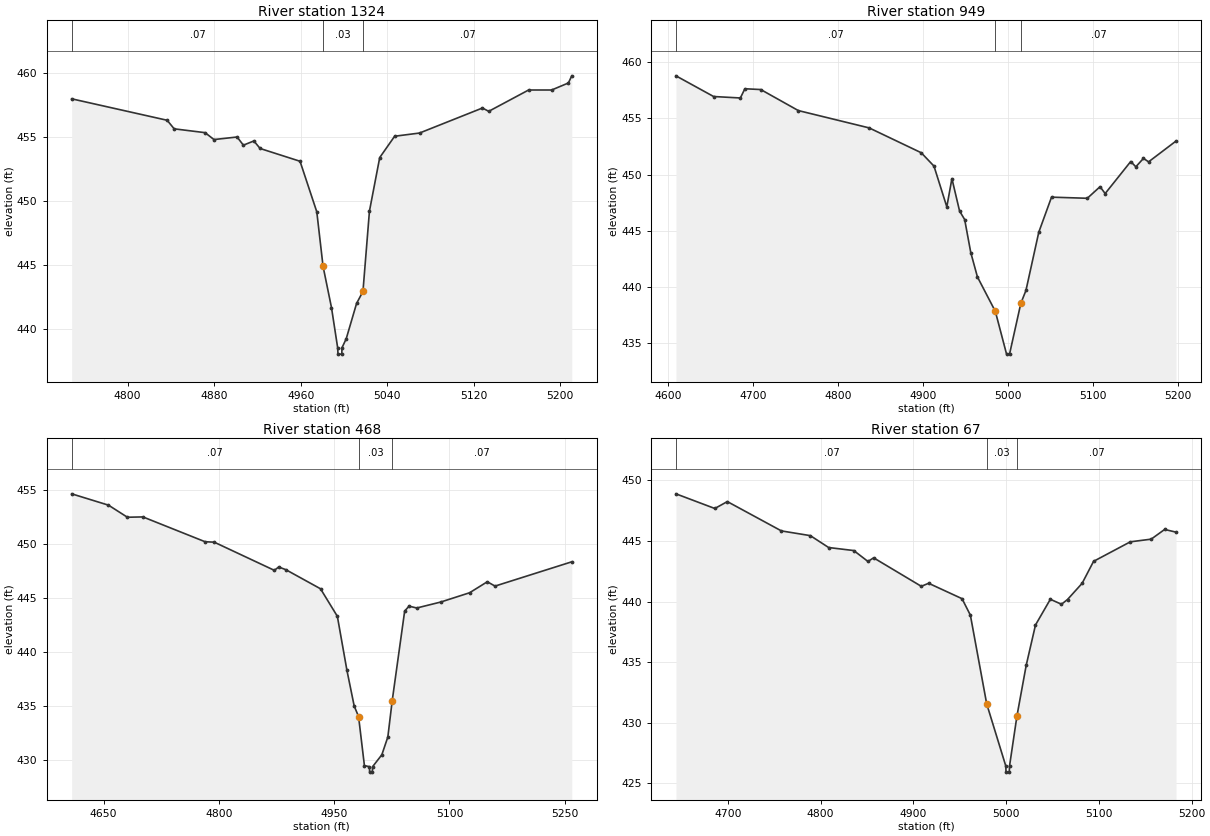
Type RM Length L Ch R = 1 ,1324    ,375,375,375
BEGIN DESCRIPTION:
DUCK CREEK TRIB 47 1 3 0
END DESCRIPTION:
XS GIS Cut Line= 2
      3481687.72     10432397.22       3481927.2     10432001.55
#Sta/Elev= 30
  4748.2     458  4836.5  456.32    4843  455.65  4871.6  455.35  4879.8  454.81
  4901.2  455.01    4907  454.37  4916.7   454.7  4922.5  454.11  4959.4  453.11
  4974.9  449.15  4980.7  444.88  4988.5  441.65  4994.2  438.51  4994.5  438.01
    4998  438.01  4998.2  438.51  5002.1  439.21  5011.7  441.98  5017.6  442.92
  5023.6  449.21  5033.1   453.4  5046.9  455.07  5069.9  455.32  5128.1  457.28
  5133.9  457.02  5170.8  458.69  5192.1  458.69  5207.6  459.24  5210.7   459.8
#Mann= 3 , 0 , 0
  4748.2     .07       0  4980.7     .03       0  5017.6     .07       0
Bank Sta=4980.7,5017.6
XS Rating Curve= 0 ,0
Exp/Cntr=0.3,0.1

Type RM Length L Ch R = 1 ,949     ,481,481,481
BEGIN DESCRIPTION:
DUCK CREEK TRIB 47 1 4 0
END DESCRIPTION:
XS GIS Cut Line= 3
      3481922.12     10432686.23      3481993.89     10432473.63
      3482195.56      10432170.6
#Sta/Elev= 30
  4609.1  458.78  4653.4  456.94  4684.9  456.81  4690.2  457.63  4708.9  457.56
  4753.1  455.69  4836.4  454.15  4897.7  451.94  4912.7  450.75  4927.8  447.13
  4933.8  449.64  4942.8  446.76  4948.8     446    4956  443.06  4963.8   440.9
  4984.9  437.83  4998.1  434.03  5001.6  434.03  5014.9  438.55  5020.9  439.69
    5036  444.87    5051  447.99  5093.1  447.89  5108.1  448.92  5114.1  448.31
  5144.2  451.16  5150.2  450.69  5159.2  451.44  5165.2  451.13  5197.5  452.98
#Mann= 3 , 0 , 0
  4609.1     .07       0  4984.9     .03       0  5014.9     .07       0
Bank Sta=4984.9,5014.9
XS Rating Curve= 0 ,0
Exp/Cntr=0.3,0.1

Type RM Length L Ch R = 1 ,468     ,401,401,401
BEGIN DESCRIPTION:
DUCK CREEK TRIB 47 1 2 1
END DESCRIPTION:
XS GIS Cut Line= 4
      3482359.82     10432723.29      3482396.12     10432483.51
      3482497.03     10432295.79      3482466.88     10432103.07
#Sta/Elev= 30
  4608.4  454.66  4656.3  453.61  4680.9  452.49  4701.1  452.52    4782  450.22
  4793.9  450.18  4872.1  447.57  4877.8  447.88  4887.1  447.63  4932.2  445.86
  4954.1  443.31  4966.6  438.29    4976     435  4981.7  434.02  4989.3  429.48
  4995.9  429.37  4996.1  428.87  4999.6  428.87  4999.9  429.37    5012  430.48
  5019.8  432.13  5025.5   435.5  5041.7   443.8  5047.4  444.25  5057.4  444.08
  5088.5  444.63  5126.1  445.49  5149.2  446.51  5159.3  446.11  5259.1  448.36
#Mann= 3 , 0 , 0
  4608.4     .07       0  4981.7     .03       0  5025.5     .07       0
Bank Sta=4981.7,5025.5
XS Rating Curve= 0 ,0
Exp/Cntr=0.3,0.1

Type RM Length L Ch R = 1 ,67      ,0,0,0
BEGIN DESCRIPTION:
DUCK CREEK TRIB 47 1 1 0
END DESCRIPTION:
XS GIS Cut Line= 5
       3482587.1     10432505.19       3482673.9     10432389.11
      3482759.62     10432254.56      3482752.02     10432154.73
      3482631.08     10432095.87
#Sta/Elev= 30
    4644  448.89  4685.9  447.68  4699.4  448.25  4757.7  445.83  4788.9  445.44
  4808.6  444.46  4835.7  444.21    4851  443.31  4857.1  443.61  4908.5  441.26
  4916.4  441.51  4952.4  440.24  4961.4  438.88    4979  431.56  4999.6  426.43
  4999.8  425.93  5003.3  425.93  5003.6  426.43  5011.6  430.56  5021.6  434.75
  5031.6  438.07  5047.6  440.19  5059.6  439.78  5066.1  440.17  5081.9  441.51
  5094.2  443.32  5133.8  444.93  5156.3  445.15  5170.8  445.95  5183.1  445.73
#Mann= 3 , 0 , 0
    4644     .07       0    4979     .03       0  5011.6     .07       0
Bank Sta=4979,5011.6
XS Rating Curve= 0 ,0
Exp/Cntr=0.3,0.1

Chan Stop Cuts=-1
Use User Specified Reach Order=0
Composite Channel Slope=5