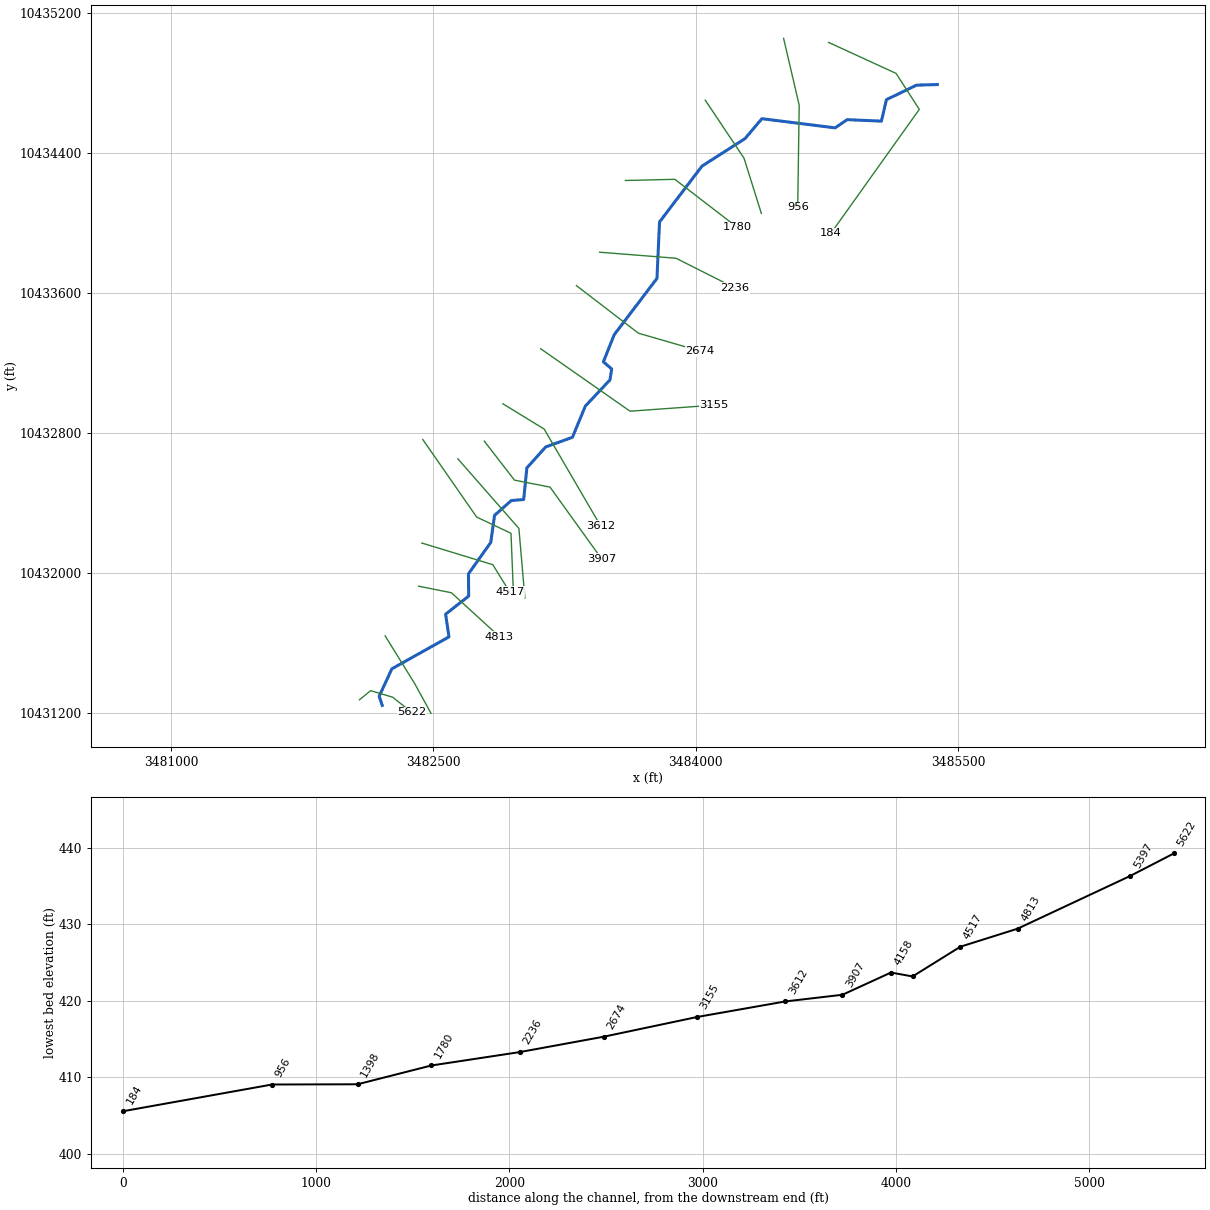
--- DUCK CREEK TRIB 47.prj (project) ---

Proj Title=DUCK CREEK TRIB 47 Base Level Engineering
Current Plan=p01
Default Exp/Contr=0.3,0.1
English Units
Geom File=g01
Flow File=f01
Plan File=p01
Y Axis Title=Elevation
X Axis Title(PF)=Main Channel Distance
X Axis Title(XS)=Station
BEGIN DESCRIPTION:
DUCK CREEK TRIB 47
END DESCRIPTION:
DSS Export Rating Curves= 0
DSS Export Rating Curve Sorted= 0
DSS Export Volume Flow Curves= 0
DXF OffsetX= 0
DXF OffsetY= 0
DXF ScaleX= 1
DXF ScaleY= 10

--- DUCK CREEK TRIB 47.p01 (plan) ---

Plan Title=Multiple Run
Short Identifier=Multiple
Geom File=g01
Flow File=f01
Subcritical Flow
K Sum by GR= 0
Std Step Tol= 0.01
Critical Tol= 0.01
Num of Std Step Trials= 20
Max Error Tol= 0.3
Flow Tol Ratio= 0.001
Split Flow NTrial= 30
Split Flow Tol= 0.02
Split Flow Ratio= 0.02
Log Output Level= 0
Friction Slope Method= 1
Unsteady Friction Slope Method= 2
Unsteady Bridges Friction Slope Method= 1
Parabolic Critical Depth
Global Vel Dist=  1 , 1 , 1
Global Log Level= 0
CheckData=True
Encroach Param= -1, 0, 0, 0
BEGIN DESCRIPTION:
Multiple Run
END DESCRIPTION:

--- DUCK CREEK TRIB 47.f01 (steady flow) ---

Flow Title=Multiple
Program Version=4.10
Number of Profiles= 7
Profile Names=10-year,25-year,50-year,1pct_min,100-year,1pct_plu,500-year
River Rch & RM=DUCK CREEK TRIB,Reach-1         ,5622
     271     347     405     348     470     636     629
River Rch & RM=DUCK CREEK TRIB,Reach-1         ,4270
     485     644     771     677     915    1237    1282
River Rch & RM=DUCK CREEK TRIB,Reach-1         ,3907
     757    1031    1256    1118    1512    2044    2183
Boundary for River Rch & Prof#=DUCK CREEK TRIB,Reach-1         , 1
Up Type= 0
Dn Type= 3
Dn Slope=0.005
Boundary for River Rch & Prof#=DUCK CREEK TRIB,Reach-1         , 2
Up Type= 0
Dn Type= 3
Dn Slope=0.005
Boundary for River Rch & Prof#=DUCK CREEK TRIB,Reach-1         , 3
Up Type= 0
Dn Type= 3
Dn Slope=0.005
Boundary for River Rch & Prof#=DUCK CREEK TRIB,Reach-1         , 4
Up Type= 0
Dn Type= 3
Dn Slope=0.005
Boundary for River Rch & Prof#=DUCK CREEK TRIB,Reach-1         , 5
Up Type= 0
Dn Type= 3
Dn Slope=0.005
Boundary for River Rch & Prof#=DUCK CREEK TRIB,Reach-1         , 6
Up Type= 0
Dn Type= 3
Dn Slope=0.005
Boundary for River Rch & Prof#=DUCK CREEK TRIB,Reach-1         , 7
Up Type= 0
Dn Type= 3
Dn Slope=0.005
DSS Import GetInterval= 0
DSS Import GetPeak= 0
DSS Import FillOption= 0

--- DUCK CREEK TRIB 47.g01 (geometry) ---

Geom Title=Existing Conditions
Program Version=4.10

River Reach=DUCK CREEK TRIB ,Reach-1
Reach XY= 30
      3482207.52     10431241.48      3482190.25     10431293.89
      3482262.98     10431450.77      3482589.47     10431633.42
      3482570.12     10431763.03      3482701.99     10431866.69
      3482700.85     10431993.99      3482828.36     10432173.33
      3482849.91     10432327.94      3482945.53     10432412.76
      3483016.53     10432418.88      3483034.88     10432599.67
       3483142.8     10432719.58      3483295.49     10432774.59
      3483369.11     10432952.96      3483509.91     10433102.86
      3483519.81     10433165.41      3483472.52      10433205.9
      3483533.96     10433360.88      3483778.67     10433683.06
      3483793.45     10434006.19      3484036.28     10434325.37
        3484282.     10434482.33      3484378.75     10434596.56
      3484797.56     10434544.06      3484866.58     10434591.05
      3485062.17     10434582.45      3485090.97     10434705.36
      3485263.13     10434788.35      3485382.11     10434791.64

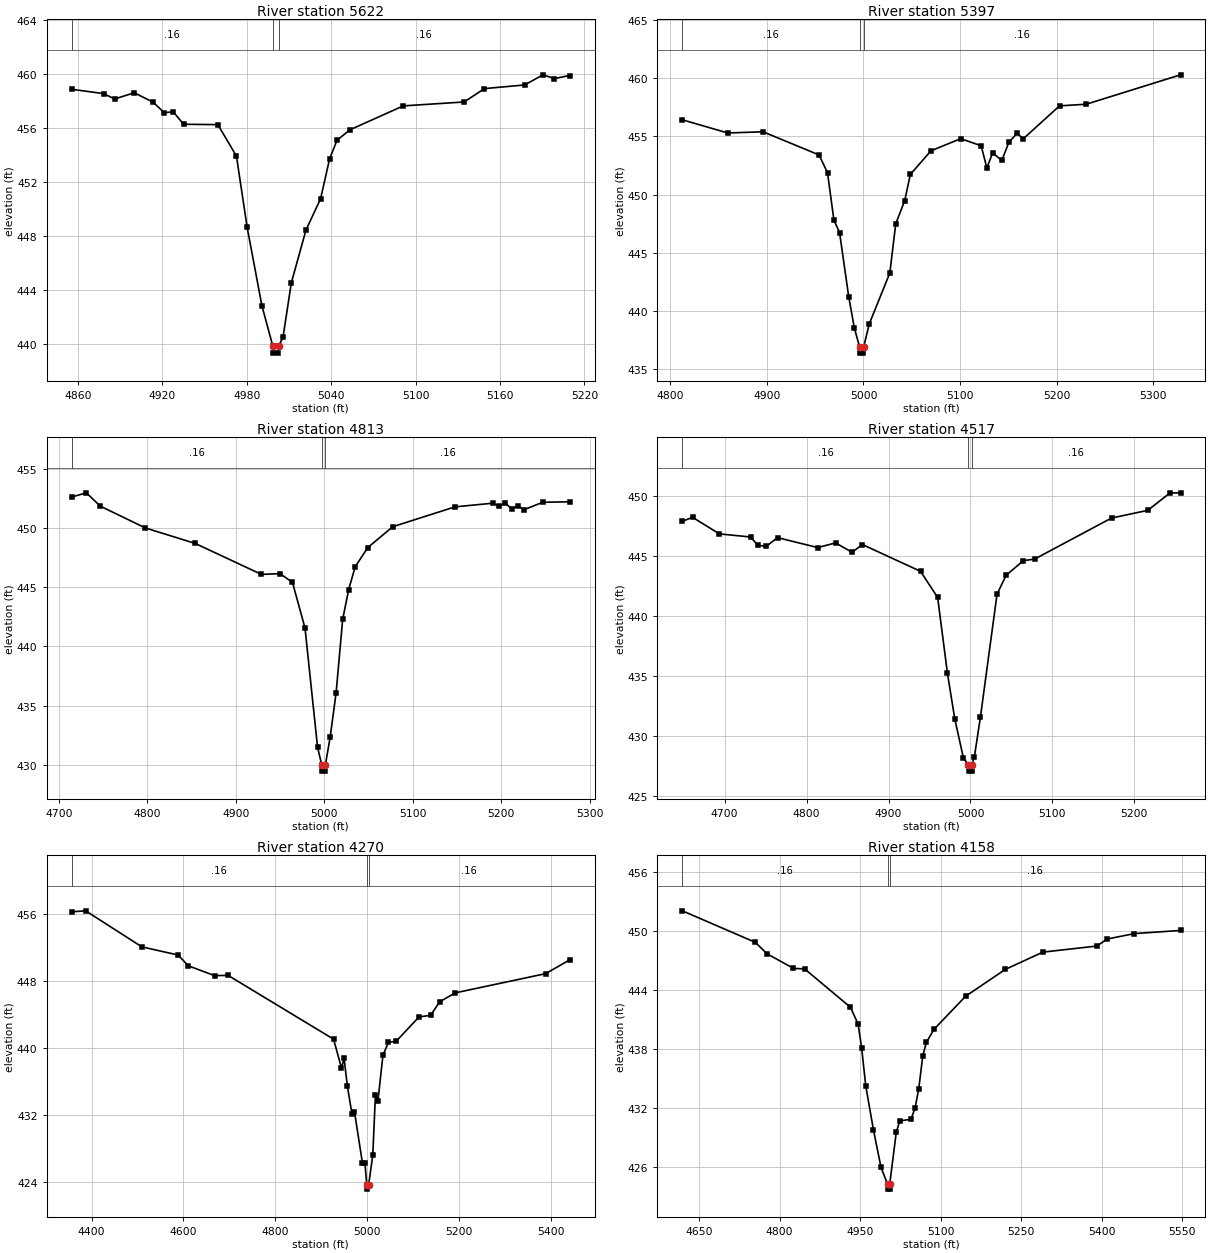
Type RM Length L Ch R = 1 ,5622    ,225,225,225
BEGIN DESCRIPTION:
DUCK CREEK TRIB 47 3 0
END DESCRIPTION:
XS GIS Cut Line= 4
      3482077.61     10431273.81      3482141.44     10431325.92
      3482267.75     10431288.16      3482377.09     10431200.94
#Sta/Elev= 30
  4855.5  458.84  4878.2  458.52  4886.1  458.12    4900  458.58  4913.4  457.89
  4921.3  457.11  4927.8  457.17  4935.1  456.25  4959.5  456.22  4972.7  453.89
  4980.3  448.62  4990.8  442.81  4998.6   439.8  4998.9   439.3  5002.4   439.3
  5002.6   439.8  5005.8  440.48  5011.7   444.5  5022.1  448.41  5032.5  450.73
  5038.9  453.68  5044.2  455.07  5053.4  455.84  5091.3  457.61  5134.6   457.9
    5149  458.89  5177.6  459.16  5190.6  459.91  5198.6  459.63  5209.6  459.86
#Mann= 3 ,-1 , 0
  4855.5     .16       0  4998.6     .07       0  5002.6     .16       0
Bank Sta=4998.6,5002.6
XS Rating Curve= 0 ,0
Exp/Cntr=0.3,0.1

Type RM Length L Ch R = 1 ,5397    ,584,584,584
BEGIN DESCRIPTION:
DUCK CREEK TRIB 47 3 0
END DESCRIPTION:
XS GIS Cut Line= 3
      3482224.21     10431639.35      3482393.47     10431365.93
      3482486.73     10431195.89
#Sta/Elev= 30
  4812.6  456.43  4859.5   455.3  4896.1   455.4    4954  453.41  4962.8  451.88
  4969.4  447.82  4975.3  446.72  4984.8  441.18  4990.6  438.52  4996.1  436.86
  4996.3  436.36  4999.8  436.36  5000.1  436.86    5006  438.87  5027.3  443.26
  5033.4  447.48  5042.7  449.48  5048.5  451.73  5069.8  453.76  5100.6  454.81
  5121.8   454.2  5127.7  452.29  5133.7  453.58  5143.2  452.94  5150.5   454.5
  5159.3  455.29    5165  454.77  5202.9  457.63  5230.5  457.77  5328.1   460.3
#Mann= 3 ,-1 , 0
  4812.6     .16       0  4996.1     .07       0  5000.1     .16       0
Bank Sta=4996.1,5000.1
XS Rating Curve= 0 ,0
Exp/Cntr=0.3,0.1

Type RM Length L Ch R = 1 ,4813    ,296,296,296
BEGIN DESCRIPTION:
DUCK CREEK TRIB 47 2 0
END DESCRIPTION:
XS GIS Cut Line= 3
      3482415.77     10431923.08      3482602.93     10431885.91
      3482878.02     10431634.62
#Sta/Elev= 30
  4714.2  452.66  4730.9  453.02  4746.7  451.89  4797.8  450.04  4854.1  448.73
  4928.9  446.11  4949.9  446.17    4964  445.44  4978.2  441.57  4992.4  431.47
  4997.2  429.94  4997.4  429.44  5000.9  429.44  5001.2  429.94  5006.6  432.29
  5013.4  436.08  5020.8  442.29  5027.6  444.82    5035  446.76  5049.2  448.38
  5077.5  450.15  5147.8  451.83  5190.4  452.14  5197.8  451.87  5204.6  452.15
    5212  451.67  5218.7  451.92  5226.2   451.6  5247.1  452.22  5277.6  452.26
#Mann= 3 ,-1 , 0
  4714.2     .16       0  4997.2     .07       0  5001.2     .16       0
Bank Sta=4997.2,5001.2
XS Rating Curve= 0 ,0
Exp/Cntr=0.3,0.1

Type RM Length L Ch R = 1 ,4517    ,247,247,247
BEGIN DESCRIPTION:
DUCK CREEK TRIB 47 10 0
END DESCRIPTION:
XS GIS Cut Line= 3
      3482434.13     10432169.91      3482839.91     10432046.23
      3482936.48     10431889.98
#Sta/Elev= 30
  4648.4  447.89  4660.8  448.22  4693.6  446.84  4731.7  446.58  4740.4  445.89
  4750.8   445.8  4764.5  446.53  4813.6   445.7  4835.4  446.09  4855.4  445.31
  4868.2  445.95  4939.1  443.72  4959.9  441.55  4971.9  435.22  4980.8  431.44
  4991.3   428.2  4997.5  427.58  4997.8  427.08  5001.3  427.08  5001.5  427.58
  5004.8  428.29  5012.2  431.61  5032.4  441.82  5043.5  443.39  5064.5  444.61
  5078.2  444.74  5172.1  448.16  5216.3   448.8  5243.5  450.25  5256.3  450.26
#Mann= 3 ,-1 , 0
  4648.4     .16       0  4997.5     .07       0  5001.5     .16       0
Bank Sta=4997.5,5001.5
XS Rating Curve= 0 ,0
Exp/Cntr=0.3,0.1

Type RM Length L Ch R = 1 ,4270    ,112,112,112
BEGIN DESCRIPTION:
DUCK CREEK TRIB 48 10 0
END DESCRIPTION:
XS GIS Cut Line= 4
      3482439.65     10432761.94       3482747.6      10432318.6
      3482944.03     10432225.69      3482957.31     10431899.16
#Sta/Elev= 30
  4356.5   456.2  4387.2  456.32  4509.4  452.03  4588.2  451.06  4610.7  449.77
  4667.5  448.61  4697.2  448.63  4926.6  441.04  4943.8   437.6  4949.4  438.77
  4956.6  435.45  4966.6  432.14  4972.1   432.4  4989.3  426.32  4994.9  426.27
  4998.8  423.69  4999.1  423.19  5002.8  423.69  5011.9  427.21  5017.6  434.37
  5023.2  433.74    5034  439.12  5045.9  440.65  5063.1  440.81  5112.5  443.69
  5137.7  443.88  5157.7   445.5    5191  446.55  5387.9  448.84  5440.4  450.48
#Mann= 3 ,-1 , 0
  4356.5     .16       0  4998.8     .07       0  5002.8     .16       0
Bank Sta=4998.8,5002.8
XS Rating Curve= 0 ,0
Exp/Cntr=0.3,0.1

Type RM Length L Ch R = 1 ,4158    ,251,251,251
BEGIN DESCRIPTION:
DUCK CREEK TRIB 47 9 0
END DESCRIPTION:
XS GIS Cut Line= 3
      3482640.09     10432651.75      3482989.16     10432253.56
      3483023.62     10431855.99
#Sta/Elev= 30
  4618.6  452.07  4754.5  448.86  4776.3   447.7  4825.7   446.2  4846.5  446.15
  4931.9  442.24  4946.2  440.52  4952.8  438.08  4960.4  434.24  4974.7  429.77
  4988.9  425.92  5001.1   424.2  5001.4   423.7  5004.9   423.7  5005.1   424.2
  5017.4  429.52    5024  430.66  5044.9  430.82  5052.5  432.01  5059.1  433.86
  5066.7  437.27  5073.4  438.65  5087.6  439.99  5146.6  443.36  5220.3  446.09
  5290.6  447.86    5391  448.48    5411   449.2  5461.2  449.75  5547.2  450.07
#Mann= 3 ,-1 , 0
  4618.6     .16       0  5001.1     .07       0  5005.1     .16       0
Bank Sta=5001.1,5005.1
XS Rating Curve= 0 ,0
Exp/Cntr=0.3,0.1

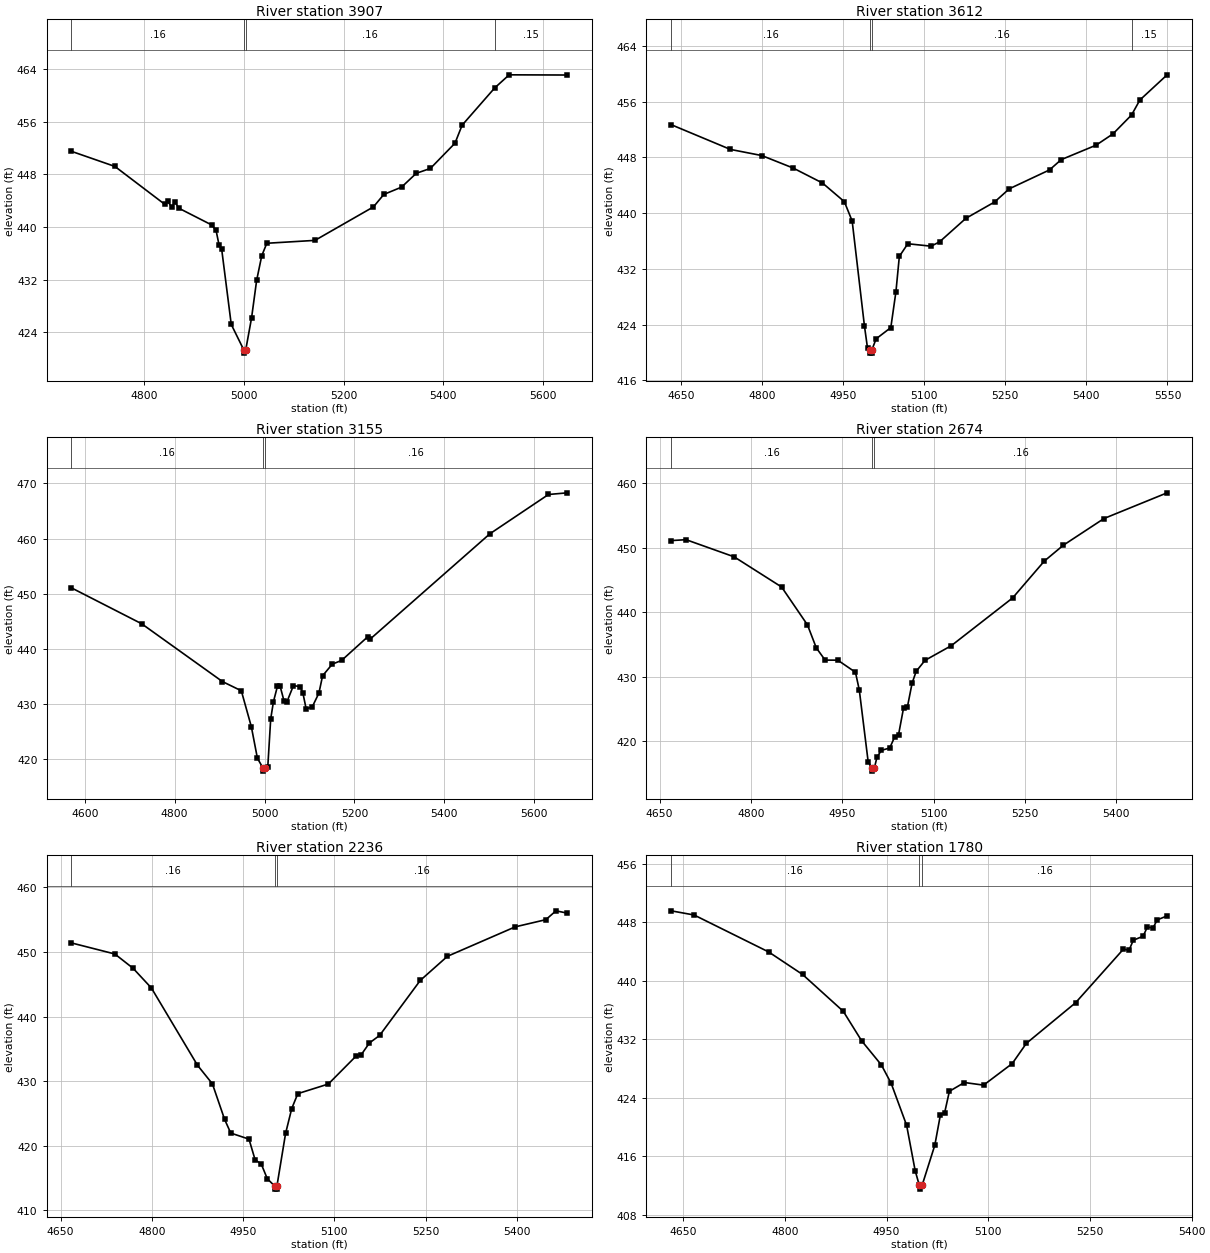
Type RM Length L Ch R = 1 ,3907    ,295,295,295
BEGIN DESCRIPTION:
DUCK CREEK TRIB 47 8 5
END DESCRIPTION:
XS GIS Cut Line= 4
      3482791.39     10432752.63      3482963.94     10432529.64
      3483167.01     10432489.82      3483462.97     10432078.41
#Sta/Elev= 30
  4653.5  451.52  4740.7  449.22  4840.3  443.48  4846.7   443.9  4854.8  443.05
  4861.2   443.8  4869.3  442.85  4935.5  440.29  4943.8  439.48  4949.9  437.23
    4955  436.67  4974.3  425.16  4999.4  421.29  4999.7  420.79  5003.4  421.29
  5015.1  426.16  5025.3  431.88  5035.5  435.61  5045.7  437.52  5142.4  437.96
  5259.8  443.06  5280.7  444.96  5316.3  446.07  5345.7  448.17  5374.2  448.92
  5423.5  452.76  5437.8   455.5  5503.3  461.18  5532.3  463.17  5649.2  463.14
#Mann= 4 ,-1 , 0
  4653.5     .16       0  4999.4     .07       0  5003.4     .16       0
  5503.3     .15       0
Bank Sta=4999.4,5003.4
XS Rating Curve= 0 ,0
Exp/Cntr=0.3,0.1

Type RM Length L Ch R = 1 ,3612    ,457,457,457
BEGIN DESCRIPTION:
DUCK CREEK TRIB 47 8 2
END DESCRIPTION:
XS GIS Cut Line= 3
      3482897.55     10432966.33      3483133.83     10432821.63
      3483456.38     10432268.12
#Sta/Elev= 30
  4631.7  452.69  4741.3  449.14  4799.4  448.26  4857.4  446.47  4911.7  444.32
  4952.1  441.65  4966.6  438.87  4989.3  423.83  4995.1  420.59  4999.3  420.42
  4999.6  419.92  5003.1  419.92  5003.3  420.42  5010.9  421.97  5038.1  423.58
  5047.6  428.73  5053.9   433.8  5069.6  435.61  5112.6  435.26  5128.3  435.88
  5177.1  439.26    5230  441.59  5257.3  443.49  5331.8   446.2  5353.3  447.67
    5418  449.75  5449.2  451.37  5483.6  454.08    5499  456.23  5549.4  459.84
#Mann= 4 ,-1 , 0
  4631.7     .16       0  4999.3     .07       0  5003.3     .16       0
  5483.6     .15       0
Bank Sta=4999.3,5003.3
XS Rating Curve= 0 ,0
Exp/Cntr=0.3,0.1

Type RM Length L Ch R = 1 ,3155    ,481,481,481
BEGIN DESCRIPTION:
DUCK CREEK TRIB 47 8 3
END DESCRIPTION:
XS GIS Cut Line= 3
      3483113.96     10433280.85      3483624.92     10432923.83
      3484104.05     10432958.34
#Sta/Elev= 30
  4570.3  451.06  4726.6  444.56  4906.4  434.09  4948.3  432.43  4970.6  425.93
  4984.1  420.22  4996.9  418.38  4997.1  417.88  5000.9  418.38  5007.2  418.65
  5013.7  427.33  5019.8  430.45  5028.6  433.21  5034.7  433.24  5043.4  430.57
  5049.5  430.37  5064.3  433.37  5079.1  433.18  5085.2  432.08  5092.6  429.15
  5106.2  429.52    5121  432.01  5129.2  435.15  5150.7  437.25  5171.6  437.93
  5229.3  442.18  5234.3  441.73  5501.6  460.86  5631.9  467.97    5674  468.27
#Mann= 3 ,-1 , 0
  4570.3     .16       0  4996.9     .07       0  5000.9     .16       0
Bank Sta=4996.9,5000.9
XS Rating Curve= 0 ,0
Exp/Cntr=0.3,0.1

Type RM Length L Ch R = 1 ,2674    ,438,438,438
BEGIN DESCRIPTION:
DUCK CREEK TRIB 47 8 4
END DESCRIPTION:
XS GIS Cut Line= 3
       3483318.3      10433641.9       3483672.7      10433369.8
      3484025.79     10433267.59
#Sta/Elev= 30
    4669  451.13  4693.4  451.27  4772.3  448.61  4850.3  443.92  4892.8  438.03
  4907.3  434.46  4921.8  432.56  4942.6  432.55  4971.6  430.67  4977.9  427.92
  4992.5  416.74  4998.7  415.81  4998.9  415.31  5002.7  415.81    5007  417.49
  5014.2  418.54  5027.8   418.9    5036  420.61  5042.3  420.93  5050.5  425.08
  5056.8  425.23  5064.6  428.97  5071.3  430.81  5085.8  432.52    5129   434.8
  5229.7  442.22  5281.8  447.95    5313  450.41  5379.8  454.56  5483.4  458.55
#Mann= 3 ,-1 , 0
    4669     .16       0  4998.7     .07       0  5002.7     .16       0
Bank Sta=4998.7,5002.7
XS Rating Curve= 0 ,0
Exp/Cntr=0.3,0.1

Type RM Length L Ch R = 1 ,2236    ,456,456,456
BEGIN DESCRIPTION:
DUCK CREEK TRIB 47 9 1
END DESCRIPTION:
XS GIS Cut Line= 3
      3483451.07     10433833.01      3483887.72      10433798.5
      3484224.82     10433628.63
#Sta/Elev= 30
  4667.8  451.39  4739.1  449.68  4769.2  447.46  4799.2  444.42    4875  432.46
  4899.6  429.57  4919.6  424.08  4929.7  421.96  4959.7  421.02  4969.8  417.81
  4979.8  417.19  4989.8  414.89  5001.7  413.78  5001.9  413.28  5005.4  413.28
  5005.7  413.78  5019.9  421.91    5030  425.75    5040  428.06  5090.2  429.55
  5135.4  433.84  5144.3  434.09  5157.8  435.91  5174.5  437.07  5241.4  445.59
    5286  449.32  5397.5  453.88  5447.8  454.99  5464.5  456.36  5483.3     456
#Mann= 3 ,-1 , 0
  4667.8     .16       0  5001.7     .07       0  5005.7     .16       0
Bank Sta=5001.7,5005.7
XS Rating Curve= 0 ,0
Exp/Cntr=0.3,0.1

Type RM Length L Ch R = 1 ,1780    ,382,382,382
BEGIN DESCRIPTION:
DUCK CREEK TRIB 47 8 1
END DESCRIPTION:
XS GIS Cut Line= 3
      3483598.36     10434243.14      3483881.08     10434249.77
       3484236.6      10433976.2
#Sta/Elev= 30
  4632.4  449.56  4666.2  448.99  4776.2  443.94  4826.2  440.86  4886.2  435.83
  4913.2  431.81  4942.4   428.5  4956.9  425.97  4979.6  420.26  4992.2  414.06
  4998.4  412.03  4998.7  411.53  5002.4  412.03  5021.2  417.53  5029.4  421.66
  5035.7  421.98  5042.7   424.9  5064.8   426.1  5093.1  425.74  5135.4  428.69
  5156.2  431.45  5228.8     437  5299.4  444.33  5307.6  444.17  5313.9  445.54
  5328.4  446.09  5334.7  447.36  5342.9  447.21  5349.2  448.32  5363.8  448.87
#Mann= 3 ,-1 , 0
  4632.4     .16       0  4998.4     .07       0  5002.4     .16       0
Bank Sta=4998.4,5002.4
XS Rating Curve= 0 ,0
Exp/Cntr=0.3,0.1

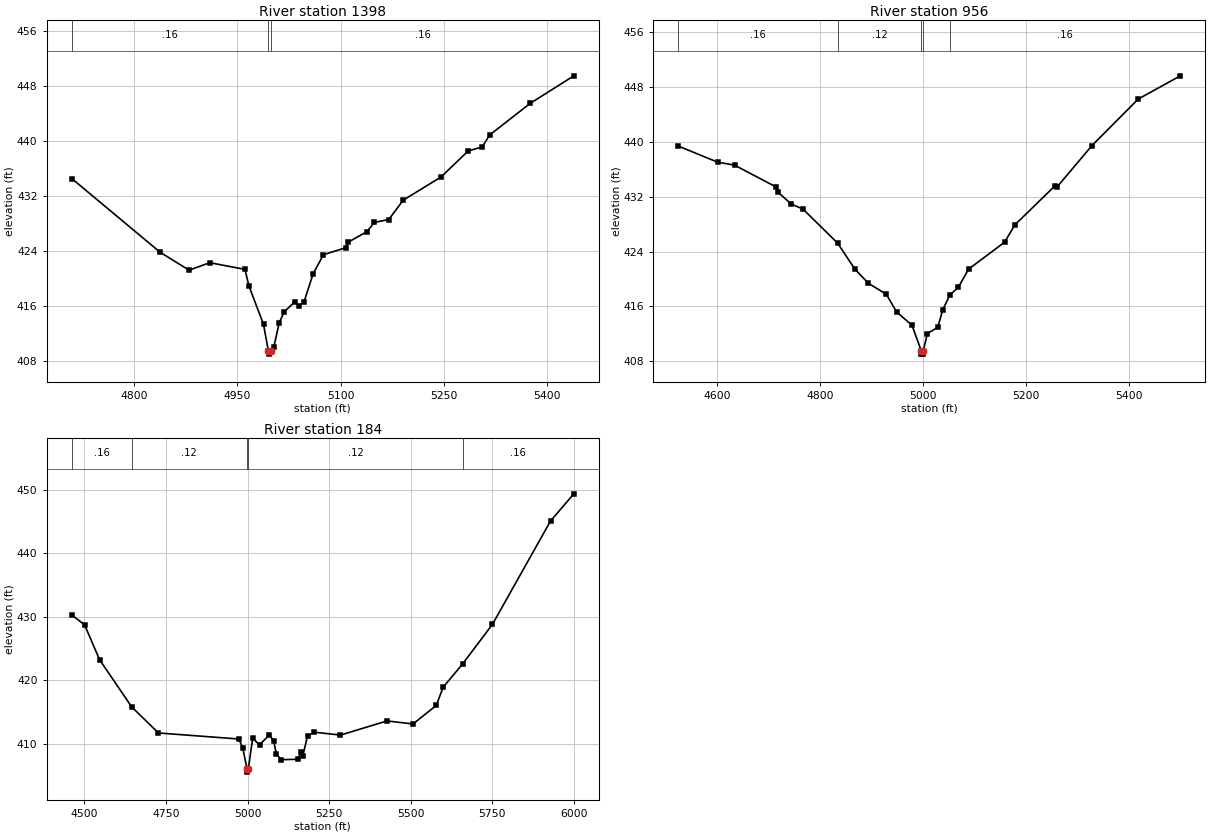
Type RM Length L Ch R = 1 ,1398    ,442,442,442
BEGIN DESCRIPTION:
DUCK CREEK TRIB 47 8 0
END DESCRIPTION:
XS GIS Cut Line= 3
      3484054.95     10434702.39      3484276.61     10434370.56
      3484375.64     10434054.99
#Sta/Elev= 30
  4709.3  434.57  4837.8  423.86  4879.9  421.26  4909.9  422.35    4961  421.38
    4967  418.92    4988  413.39    4995  409.57  4995.3  409.07    4999  409.57
    5003   410.1  5010.8  413.61    5018   415.2  5033.1  416.65  5039.1  416.08
  5046.9  416.65  5060.1  420.74  5075.1  423.51  5108.4  424.55  5111.2  425.33
  5138.4  426.87  5149.1   428.2  5170.1  428.62  5191.1  431.43  5246.2  434.81
  5285.4  438.57  5305.8  439.16  5316.8   440.9  5375.8   445.5  5439.1  449.49
#Mann= 3 ,-1 , 0
  4709.3     .16       0    4995     .07       0    4999     .16       0
Bank Sta=4995,4999
XS Rating Curve= 0 ,0
Exp/Cntr=0.3,0.1

Type RM Length L Ch R = 1 ,956     ,772,772,772
BEGIN DESCRIPTION:
DUCK CREEK TRIB 47 4 0
END DESCRIPTION:
XS GIS Cut Line= 3
      3484502.85     10435056.01      3484592.11     10434673.22
      3484583.57     10434089.84
#Sta/Elev= 30
  4524.1  439.42  4600.5  437.07  4633.7  436.63  4713.4  433.48  4718.8  432.64
  4744.2  430.93  4766.5  430.23  4834.3  425.23  4867.4  421.47  4894.1  419.37
  4928.7   417.8  4948.7   415.2  4978.7  413.26  4996.7  409.54    4997  409.04
  5000.5  409.04  5000.7  409.54  5008.7  412.05  5028.8  412.95  5038.8  415.55
  5052.5   417.7  5068.8  418.78  5088.8  421.45  5158.8  425.38  5178.8  427.91
  5256.4  433.58  5261.4  433.49  5328.8  439.49  5418.8  446.28  5500.6  449.67
#Mann= 5 ,-1 , 0
  4524.1     .16       0  4834.3     .12       0  4996.7     .07       0
  5000.7     .12       0  5052.5     .16       0
Bank Sta=4996.7,5000.7
XS Rating Curve= 0 ,0
Exp/Cntr=0.3,0.1

Type RM Length L Ch R = 1 ,184     ,0,0,0
BEGIN DESCRIPTION:
DUCK CREEK TRIB 47 1 0
END DESCRIPTION:
XS GIS Cut Line= 4
      3484760.63      10435032.6      3485146.07     10434855.51
      3485278.89     10434649.78      3484773.67     10433941.44
#Sta/Elev= 30
  4461.2  430.26  4500.4  428.72  4546.3  423.24  4644.6  415.82  4726.9   411.7
  4973.3  410.75  4985.3  409.35  4998.5  406.04  4998.7  405.54  5002.5  406.04
  5015.7  410.86  5036.8  409.83  5067.1  411.41  5080.4  410.41  5088.2   408.4
  5103.4   407.5  5154.6  407.56  5163.2  408.73  5169.4  408.11  5184.1  411.25
    5205  411.82  5284.9  411.37  5427.5  413.59  5507.4  413.12  5578.7  416.04
  5599.6   418.9  5659.2  422.55  5750.8  428.79    5929  445.06  6000.3  449.32
#Mann= 5 ,-1 , 0
  4461.2     .16       0  4644.6     .12       0  4998.5     .07       0
  5002.5     .12       0  5659.2     .16       0
Bank Sta=4998.5,5002.5
XS Rating Curve= 0 ,0
Exp/Cntr=0.3,0.1

Chan Stop Cuts=-1
Use User Specified Reach Order=0
Composite Channel Slope=5