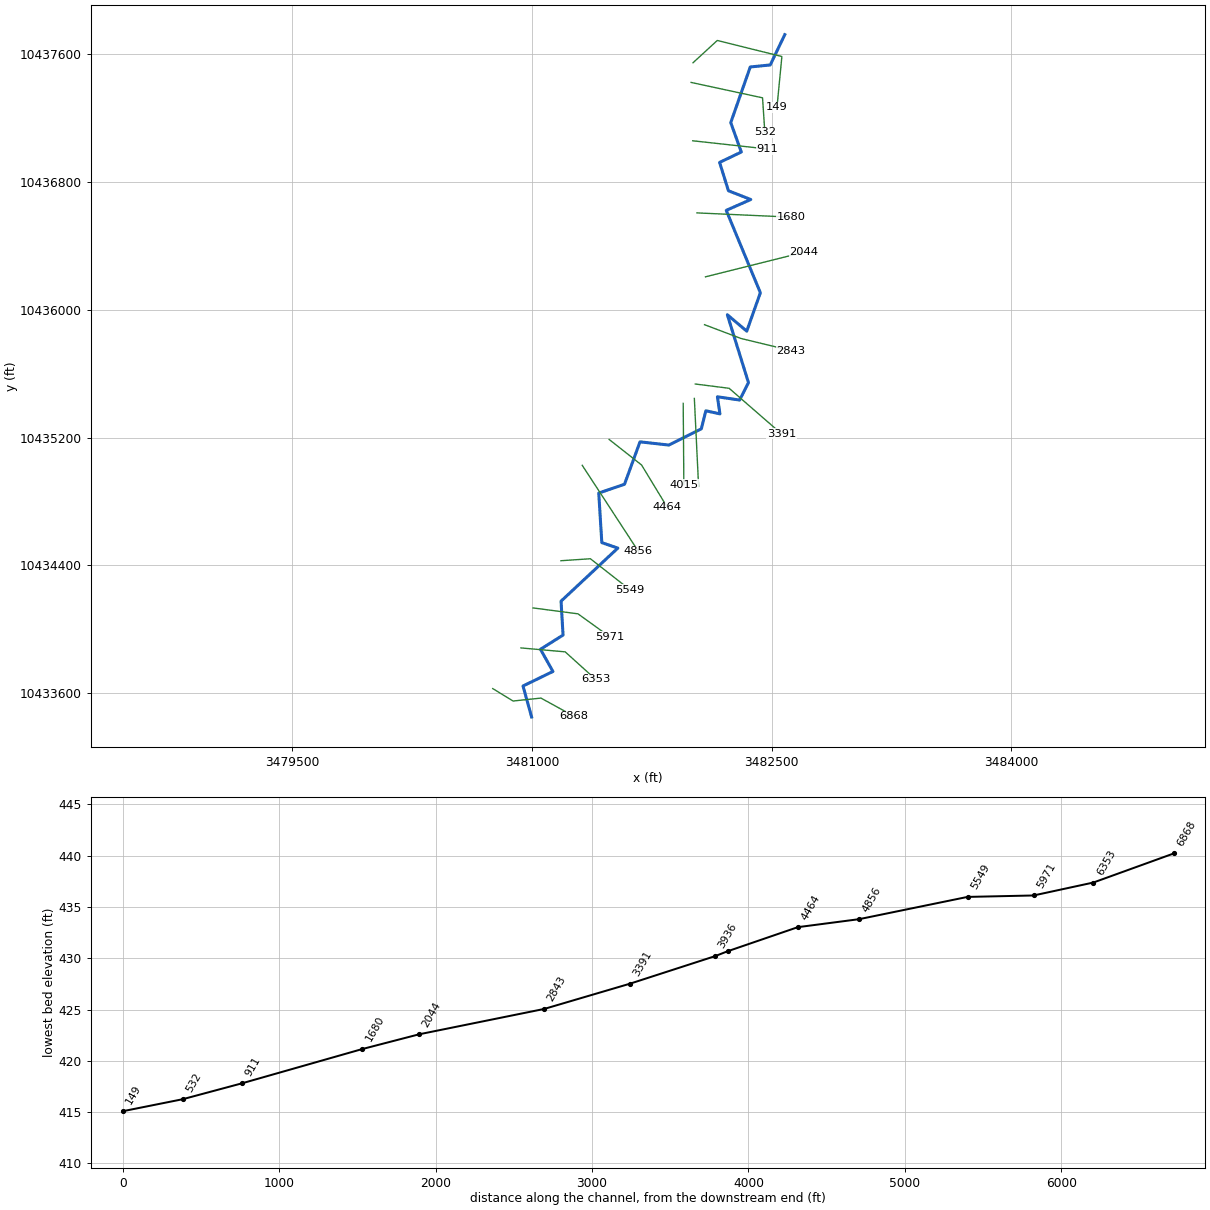
--- DUCK CREEK TRIB 48.prj (project) ---

Proj Title=DUCK CREEK TRIB 48 Base Level Engineering
Current Plan=p01
Default Exp/Contr=0.3,0.1
English Units
Geom File=g01
Flow File=f01
Plan File=p01
BEGIN DESCRIPTION:
DUCK CREEK TRIB 48
END DESCRIPTION:

--- DUCK CREEK TRIB 48.p01 (plan) ---

Plan Title=Multiple Run
Short Identifier=Multiple
Geom File=g01
Flow File=f01
Subcritical Flow
K Sum by GR= 0
Std Step Tol= 0.01
Critical Tol= 0.01
Num of Std Step Trials= 20
Max Error Tol= 0.3
Flow Tol Ratio= 0.001
Split Flow NTrial= 30
Split Flow Tol= 0.02
Split Flow Ratio= 0.02
Log Output Level= 0
Friction Slope Method= 1
Unsteady Friction Slope Method= 2
Unsteady Bridges Friction Slope Method= 1
Parabolic Critical Depth
Global Vel Dist=  1 , 1 , 1
Global Log Level= 0
CheckData=True
Encroach Param= -1, 0, 0, 0
BEGIN DESCRIPTION:
Multiple Run
END DESCRIPTION:

--- DUCK CREEK TRIB 48.f01 (steady flow) ---

Flow Title=Multiple
Number of Profiles=7
Profile Names=10-year,25-year,50-year,1pct_min,100-year,1pct_plu,500-year
River Rch & RM= DUCK CREEK TRIB ,Reach-1,6868
     647     866    1042     915    1238    1674    1742
Boundary for River Rch & Prof#=DUCK CREEK TRIB ,Reach-1,1
Up Type=0
Dn Type=3
Dn Slope=0.005
Boundary for River Rch & Prof#=DUCK CREEK TRIB ,Reach-1,2
Up Type=0
Dn Type=3
Dn Slope=0.005
Boundary for River Rch & Prof#=DUCK CREEK TRIB ,Reach-1,3
Up Type=0
Dn Type=3
Dn Slope=0.005
Boundary for River Rch & Prof#=DUCK CREEK TRIB ,Reach-1,4
Up Type=0
Dn Type=3
Dn Slope=0.005
Boundary for River Rch & Prof#=DUCK CREEK TRIB ,Reach-1,5
Up Type=0
Dn Type=3
Dn Slope=0.005
Boundary for River Rch & Prof#=DUCK CREEK TRIB ,Reach-1,6
Up Type=0
Dn Type=3
Dn Slope=0.005
Boundary for River Rch & Prof#=DUCK CREEK TRIB ,Reach-1,7
Up Type=0
Dn Type=3
Dn Slope=0.005

--- DUCK CREEK TRIB 48.g01 (geometry) ---

Geom Title=Existing Conditions

River Reach=DUCK CREEK TRIB ,Reach-1
Reach XY= 30
      3480997.89     10433451.71      3480944.09     10433645.74
      3481131.26     10433736.73      3481053.48     10433875.63
      3481194.60     10433964.51      3481182.12     10434176.70
      3481537.50     10434508.90      3481437.22     10434542.92
      3481418.06     10434853.28      3481579.21     10434908.26
      3481676.14     10435173.74      3481856.39     10435153.63
      3482060.13     10435255.52      3482088.21     10435368.16
      3482176.50     10435348.65      3482160.64     10435455.75
      3482299.76     10435435.26      3482354.90     10435544.52
      3482222.83     10435968.85      3482344.28     10435866.40
      3482429.46     10436106.80      3482215.82     10436622.39
      3482369.50     10436690.13      3482229.62     10436745.03
      3482174.31     10436922.41      3482310.18     10436987.28
      3482244.13     10437171.43      3482366.16     10437519.66
      3482491.24     10437532.28      3482582.11     10437721.64

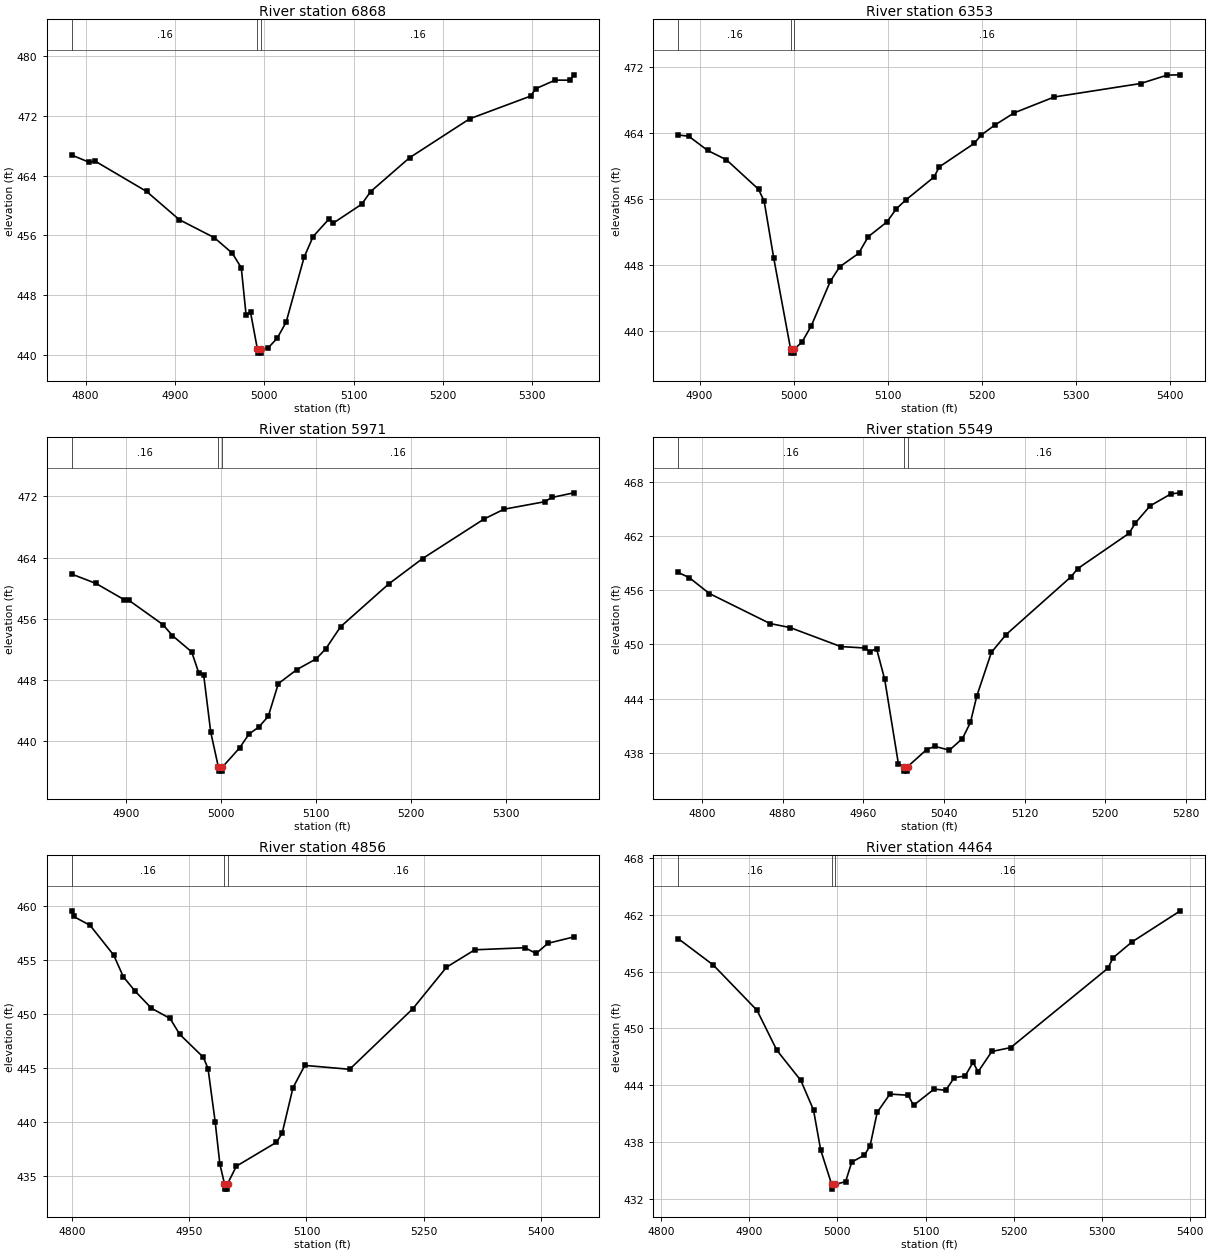
Type RM Length L Ch R = 1,6868,515,515,515
BEGIN DESCRIPTION:
DUCK CREEK TRIB 48 3 0
END DESCRIPTION:
XS GIS Cut Line= 4
      3480754.65     10433629.71      3480881.81     10433551.77
      3481056.19     10433570.23      3481264.29     10433455.98
#Sta/Elev= 30
  4784.6  466.75  4804.4  465.77  4810.3  465.97  4868.3  461.88  4905.0  458.09
  4944.1  455.69  4964.2  453.61  4974.3  451.66  4979.7  445.31  4984.7  445.67
  4992.4  440.72  4992.6  440.22  4996.1  440.22  4996.4  440.72  5004.4  440.92
  5014.5  442.22  5024.5  444.37  5044.7  453.09  5054.7  455.84  5072.4  458.18
  5077.4  457.65  5109.1  460.17  5119.1  461.86  5162.6  466.39  5229.9  471.61
  5298.1  474.65  5303.8  475.64  5325.6  476.79  5341.7  476.78  5346.5  477.50
#Mann=3,-1,0
  4784.6    0.16       0  4992.4    0.07       0  4996.4    0.16       0
Bank Sta=4992.4,4996.4
Exp/Cntr=0.3,0.1

Type RM Length L Ch R = 1,6353,382,382,382
BEGIN DESCRIPTION:
DUCK CREEK TRIB 48 2 0
END DESCRIPTION:
XS GIS Cut Line= 3
      3480931.04     10433884.11      3481208.00     10433859.50
      3481397.94     10433687.94
#Sta/Elev= 30
  4877.3  463.76  4888.4  463.62  4908.5  461.90  4928.6  460.76  4962.7  457.20
  4968.7  455.75  4978.8  448.92  4996.8  437.88  4997.1  437.38  5000.6  437.38
  5000.8  437.88  5008.9  438.71  5018.9  440.70  5039.0  446.06  5049.0  447.82
  5069.1  449.44  5079.4  451.46  5099.2  453.24  5109.3  454.84  5119.3  455.90
  5149.4  458.68  5154.9  459.90  5192.0  462.74  5199.5  463.75  5213.7  464.94
  5234.6  466.44  5277.2  468.36  5369.1  469.99  5397.5  471.01  5411.3  471.04
#Mann=3,-1,0
  4877.3    0.16       0  4996.8    0.07       0  5000.8    0.16       0
Bank Sta=4996.8,5000.8
Exp/Cntr=0.3,0.1

Type RM Length L Ch R = 1,5971,422,422,422
BEGIN DESCRIPTION:
DUCK CREEK TRIB 48 13 0
END DESCRIPTION:
XS GIS Cut Line= 3
      3481006.91     10434134.41      3481288.01     10434097.47
      3481486.99     10433953.88
#Sta/Elev= 30
  4843.0  461.85  4868.4  460.64  4898.1  458.52  4903.2  458.43  4939.0  455.26
  4949.1  453.81  4969.3  451.70  4976.8  448.94  4981.9  448.73  4989.4  441.20
  4997.5  436.62  4997.8  436.12  5001.3  436.12  5001.5  436.62  5019.7  439.14
  5029.8  440.98  5039.9  441.86  5050.0  443.28  5060.6  447.55  5080.2  449.39
  5100.4  450.78  5110.5  452.08  5126.1  454.97  5177.0  460.58  5212.6  463.89
  5277.6  469.07  5298.4  470.33  5341.2  471.31  5348.7  471.86  5371.9  472.47
#Mann=3,-1,0
  4843.0    0.16       0  4997.5    0.07       0  5001.5    0.16       0
Bank Sta=4997.5,5001.5
Exp/Cntr=0.3,0.1

Type RM Length L Ch R = 1,5549,693,693,693
BEGIN DESCRIPTION:
DUCK CREEK TRIB 48 12 0
END DESCRIPTION:
XS GIS Cut Line= 3
      3481181.32     10434429.82      3481365.97     10434442.13
      3481612.17     10434249.27
#Sta/Elev= 30
  4776.6  457.97  4787.4  457.41  4807.5  455.64  4867.6  452.32  4887.6  451.87
  4937.7  449.77  4961.7  449.61  4966.8  449.20  4973.2  449.55  4981.3  446.14
  4994.9  436.78  5000.1  436.48  5000.3  435.98  5003.8  435.98  5004.1  436.48
  5022.9  438.37  5031.0  438.72  5045.5  438.30  5058.4  439.59  5066.3  441.37
  5072.6  444.29  5087.1  449.13  5101.6  451.09  5165.7  457.46  5172.7  458.40
  5223.5  462.30  5229.9  463.46  5244.4  465.34  5265.2  466.68  5274.4  466.79
#Mann=3,-1,0
  4776.6    0.16       0  5000.1    0.07       0  5004.1    0.16       0
Bank Sta=5000.1,5004.1
Exp/Cntr=0.3,0.1

Type RM Length L Ch R = 1,4856,392,392,392
BEGIN DESCRIPTION:
DUCK CREEK TRIB 48 10
END DESCRIPTION:
XS GIS Cut Line= 2
      3481314.70     10435026.79      3481665.48     10434489.33
#Sta/Elev= 30
  4800.0  459.52  4802.3  459.00  4823.4  458.18  4853.6  455.43  4865.9  453.43
  4880.7  452.12  4901.8  450.52  4925.6  449.58  4938.0  448.11  4968.2  445.99
  4974.2  444.94  4983.3  440.03  4989.3  436.13  4995.2  434.31  4995.5  433.81
  4999.0  433.81  4999.2  434.31  5010.4  435.93  5061.7  438.14  5068.9  438.97
  5082.8  443.18  5097.9  445.24  5155.2  444.88  5236.0  450.48  5279.0  454.31
  5315.2  455.92  5379.3  456.11  5393.6  455.58  5408.7  456.52  5441.8  457.11
#Mann=3,-1,0
  4800.0    0.16       0  4995.2    0.07       0  4999.2    0.16       0
Bank Sta=4995.2,4999.2
Exp/Cntr=0.3,0.1

Type RM Length L Ch R = 1,4464,449,449,449
BEGIN DESCRIPTION:
DUCK CREEK TRIB 48 11 0
END DESCRIPTION:
XS GIS Cut Line= 3
      3481482.94     10435188.85      3481686.01     10435028.86
      3481847.61     10434762.93
#Sta/Elev= 30
  4819.4  459.49  4859.1  456.71  4908.8  451.92  4931.3  447.70  4958.5  444.51
  4972.9  441.39  4981.0  437.18  4993.5  433.53  4993.7  433.03  4997.5  433.53
  5009.3  433.82  5016.3  435.89  5030.7  436.62  5037.1  437.61  5045.2  441.15
  5059.6  443.07  5080.3  442.95  5086.4  441.88  5109.8  443.60  5122.9  443.47
  5132.6  444.80  5144.9  444.98  5153.9  446.42  5159.7  445.43  5175.2  447.57
  5196.6  447.98  5307.0  456.37  5312.8  457.47  5334.2  459.14  5389.1  462.43
#Mann=3,-1,0
  4819.4    0.16       0  4993.5    0.07       0  4997.5    0.16       0
Bank Sta=4993.5,4997.5
Exp/Cntr=0.3,0.1

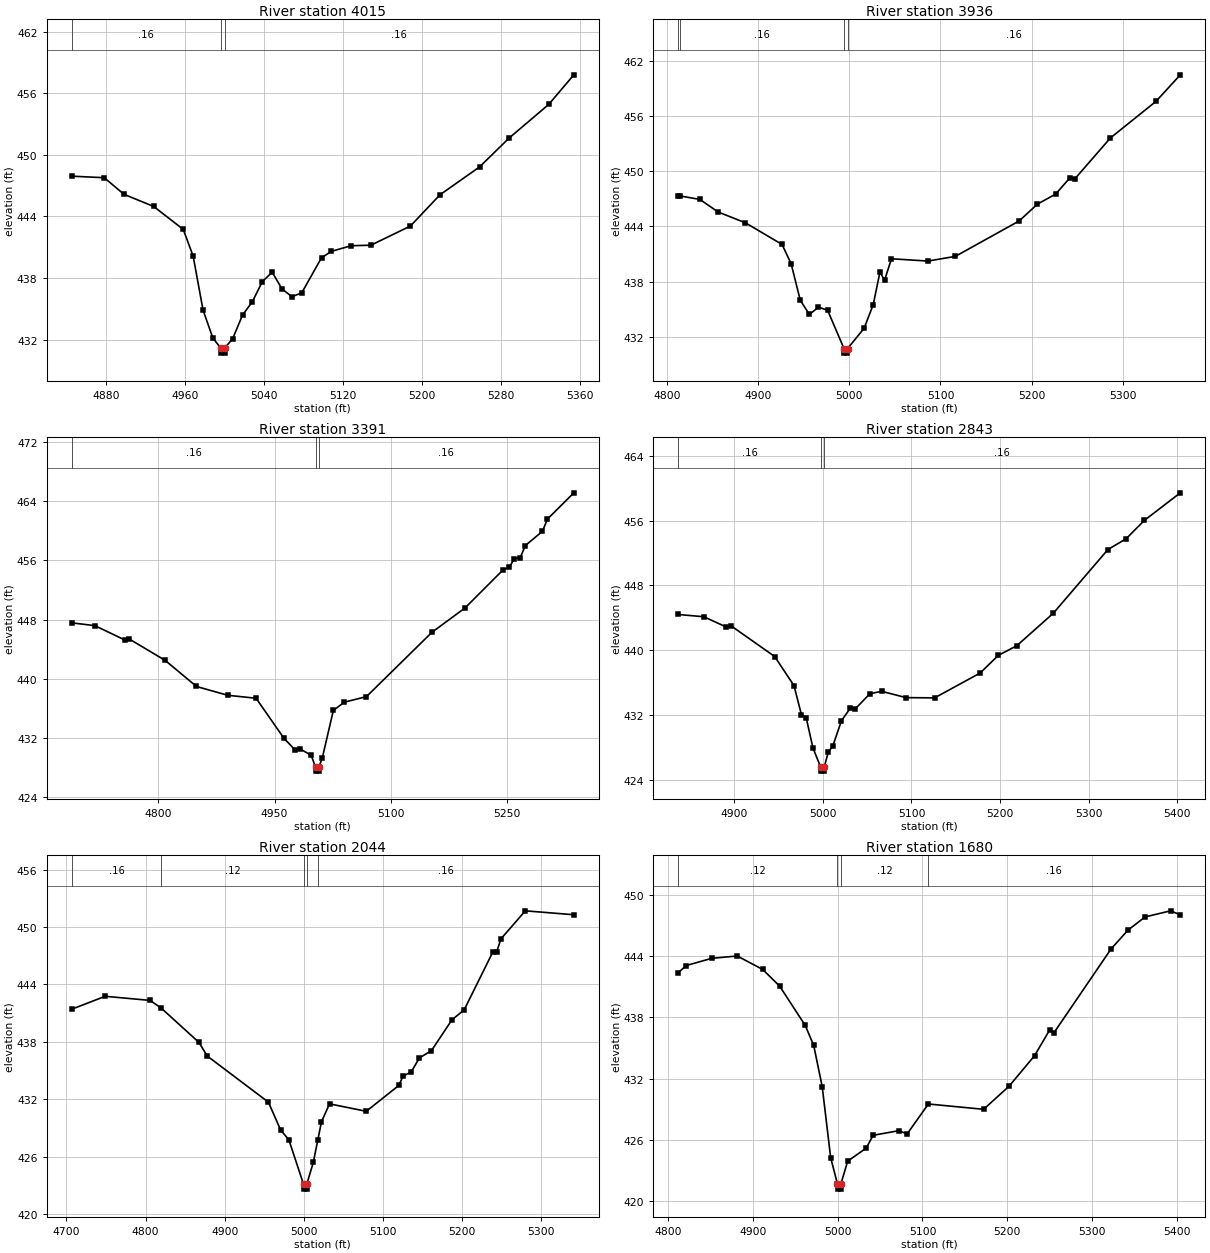
Type RM Length L Ch R = 1,4015,79,79,79
BEGIN DESCRIPTION:
Mapping XS b38c9e48
END DESCRIPTION:
XS GIS Cut Line= 2
      3481946.55     10435414.56      3481950.65     10434906.17
#Sta/Elev= 30
  4845.6  447.93  4878.5  447.78  4898.5  446.16  4928.5  444.98  4958.5  442.74
  4968.5  440.14  4978.5  434.89  4988.5  432.14  4996.5  431.18  4996.8  430.68
  5000.3  430.68  5000.5  431.18  5008.5  432.08  5018.5  434.39  5028.5  435.70
  5038.5  437.64  5048.5  438.57  5058.5  436.94  5068.5  436.18  5078.5  436.56
  5098.5  439.98  5108.5  440.60  5128.5  441.15  5148.5  441.20  5188.5  443.07
  5218.5  446.12  5258.5  448.83  5288.5  451.65  5328.5  454.92  5354.0  457.81
#Mann=3,-1,0
  4845.6    0.16       0  4996.5    0.07       0  5000.5    0.16       0
Bank Sta=4996.5,5000.5
Exp/Cntr=0.3,0.1

Type RM Length L Ch R = 1,3936,545,545,545
BEGIN DESCRIPTION:
DUCK CREEK TRIB 48 9 0
END DESCRIPTION:
XS GIS Cut Line= 2
      3482016.30     10435445.36      3482042.90     10434895.01
#Sta/Elev= 30
  4812.2  447.32  4814.0  447.32  4835.9  446.94  4856.0  445.57  4886.0  444.39
  4926.1  442.04  4936.1  439.94  4946.1  435.97  4956.1  434.42  4966.1  435.21
  4976.1  434.88  4994.1  430.71  4994.4  430.21  4997.9  430.21  4998.1  430.71
  5016.2  432.92  5026.2  435.49  5033.6  439.05  5038.6  438.13  5046.2  440.48
  5086.2  440.23  5116.3  440.74  5186.4  444.60  5206.4  446.43  5226.4  447.52
  5242.3  449.32  5247.3  449.16  5286.5  453.63  5336.5  457.61  5363.2  460.50
#Mann=4,-1,0
  4812.2    0.12       0  4814.0    0.16       0  4994.1    0.07       0
  4998.1    0.16       0
Bank Sta=4994.1,4998.1
Exp/Cntr=0.3,0.1

Type RM Length L Ch R = 1,3391,548,548,548
BEGIN DESCRIPTION:
DUCK CREEK TRIB 48 8 0
END DESCRIPTION:
XS GIS Cut Line= 3
      3482022.49     10435535.58      3482233.76     10435508.92
      3482562.04     10435223.73
#Sta/Elev= 30
  4688.4  447.56  4718.2  447.18  4756.7  445.25  4761.7  445.43  4809.0  442.48
  4849.3  438.96  4889.6  437.77  4926.2  437.37  4962.3  431.94  4976.5  430.39
  4983.2  430.51  4997.4  429.65  5003.0  428.02  5003.3  427.52  5006.8  427.52
  5007.0  428.02  5011.6  429.28  5025.9  435.73  5040.1  436.84  5068.6  437.59
  5153.1  446.28  5195.9  449.58  5245.2  454.75  5252.9  455.08  5259.5  456.23
  5267.1  456.39  5273.7  458.01  5295.6  459.92  5302.2  461.59  5336.2  465.13
#Mann=3,-1,0
  4688.4    0.16       0  5003.0    0.07       0  5007.0    0.16       0
Bank Sta=5003,5007
Exp/Cntr=0.3,0.1

Type RM Length L Ch R = 1,2843,799,799,799
BEGIN DESCRIPTION:
DUCK CREEK TRIB 48 7 0
END DESCRIPTION:
XS GIS Cut Line= 3
      3482079.93     10435906.90      3482307.62     10435820.75
      3482621.53     10435744.83
#Sta/Elev= 30
  4836.9  444.41  4865.9  444.13  4890.7  442.88  4896.1  443.04  4945.7  439.22
  4967.5  435.62  4975.9  432.02  4981.2  431.68  4988.9  427.91  4997.6  425.56
  4997.9  425.06  5001.4  425.06  5001.6  425.56  5006.1  427.39  5011.4  428.20
  5021.0  431.28  5030.9  432.82  5036.2  432.70  5053.1  434.62  5066.4  434.92
  5093.9  434.14  5126.1  434.11  5177.5  437.18  5198.1  439.37  5218.7  440.54
  5259.9  444.55  5321.6  452.43  5342.2  453.77  5362.7  456.03  5403.3  459.44
#Mann=3,-1,0
  4836.9    0.16       0  4997.6    0.07       0  5001.6    0.16       0
Bank Sta=4997.6,5001.6
Exp/Cntr=0.3,0.1

Type RM Length L Ch R = 1,2044,364,364,364
BEGIN DESCRIPTION:
DUCK CREEK TRIB 48 6 0
END DESCRIPTION:
XS GIS Cut Line= 2
      3482086.03     10436206.43      3482701.49     10436360.29
#Sta/Elev= 30
  4706.7  441.41  4748.9  442.76  4805.7  442.33  4819.8  441.52  4867.5  437.93
  4877.9  436.51  4955.1  431.69  4970.7  428.76  4981.0  427.75  4999.6  423.09
  4999.8  422.59  5003.3  422.59  5003.6  423.09  5011.9  425.39  5017.7  427.78
  5022.2  429.63  5032.4  431.51  5078.8  430.73  5120.0  433.44  5125.3  434.42
  5135.6  434.84  5145.9  436.31  5161.2  437.08  5187.1  440.30  5202.5  441.34
  5238.6  447.37  5243.7  447.44  5249.0  448.77  5279.8  451.70  5341.1  451.29
#Mann=5,-1,0
  4706.7    0.16       0  4819.8    0.12       0  4999.6    0.07       0
  5003.6    0.12       0  5017.7    0.16       0
Bank Sta=4999.6,5003.6
Exp/Cntr=0.3,0.1

Type RM Length L Ch R = 1,1680,769,769,769
BEGIN DESCRIPTION:
DUCK CREEK TRIB 48 5 0
END DESCRIPTION:
XS GIS Cut Line= 2
      3482032.70     10436606.48      3482623.60     10436579.81
#Sta/Elev= 30
  4812.3  442.38  4821.7  443.08  4851.7  443.79  4881.8  444.02  4911.8  442.70
  4931.8  441.06  4961.9  437.21  4971.9  435.25  4981.9  431.21  4991.9  424.23
  4999.9  421.65  5000.1  421.15  5003.6  421.15  5003.9  421.65  5011.9  423.89
  5033.7  425.17  5041.9  426.43  5072.0  426.88  5082.0  426.57  5107.0  429.50
  5172.1  428.98  5202.1  431.25  5232.1  434.24  5249.7  436.74  5254.7  436.46
  5322.2  444.71  5342.2  446.56  5362.3  447.85  5392.3  448.45  5403.8  448.06
#Mann=4,-1,0
  4812.3    0.12       0  4999.9    0.07       0  5003.9    0.12       0
  5107.0    0.16       0
Bank Sta=4999.9,5003.9
Exp/Cntr=0.3,0.1

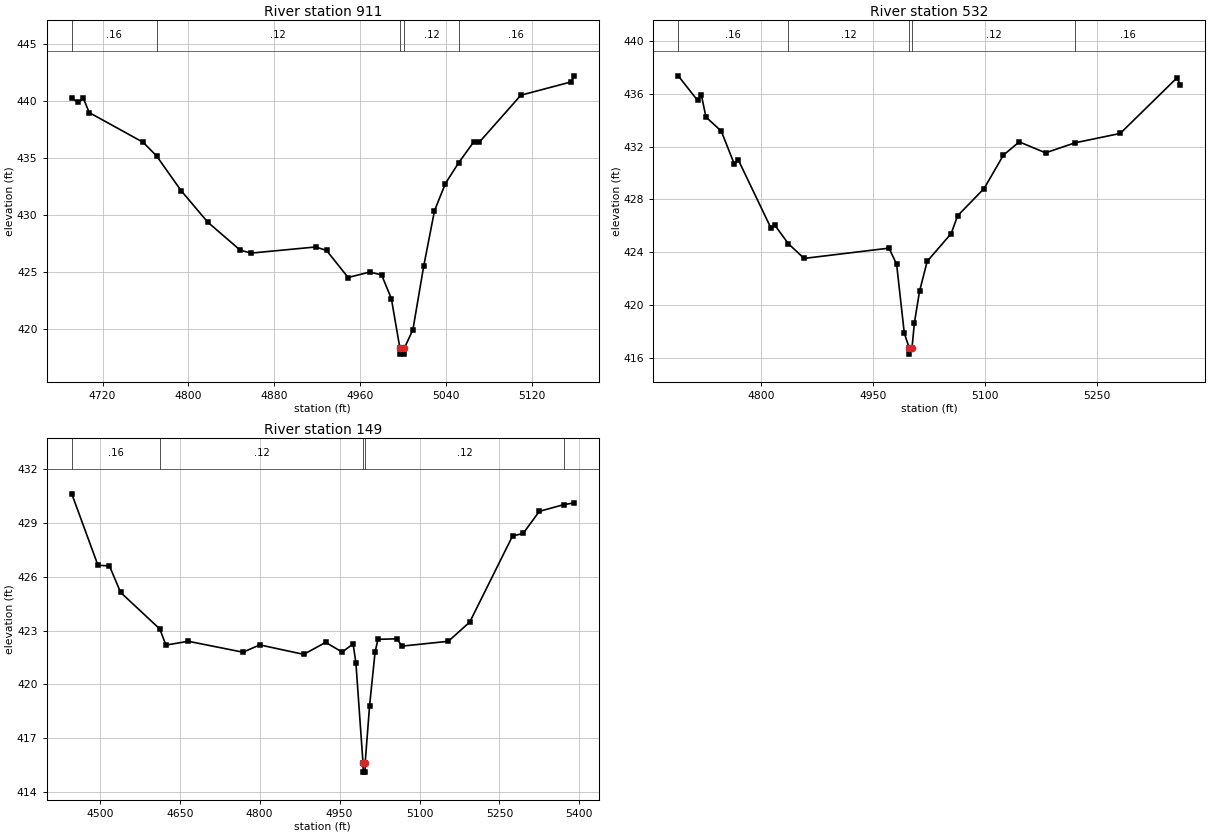
Type RM Length L Ch R = 1,911,379,379,379
BEGIN DESCRIPTION:
DUCK CREEK TRIB 48 4 0
END DESCRIPTION:
XS GIS Cut Line= 2
      3482006.03     10437057.81      3482471.22     10437006.58
#Sta/Elev= 30
  4691.3  440.26  4697.2  439.89  4702.2  440.24  4707.5  439.00  4757.8  436.39
  4770.3  435.20  4793.2  432.15  4818.1  429.38  4848.3  426.93  4858.4  426.67
  4918.7  427.21  4928.8  426.90  4948.9  424.53  4969.0  425.01  4980.1  424.76
  4989.2  422.68  4997.2  418.31  4997.5  417.81  5001.0  417.81  5001.2  418.31
  5009.3  419.96  5019.3  425.50  5029.4  430.38  5039.5  432.76  5051.9  434.59
  5066.0  436.43  5071.0  436.38  5109.9  440.52  5156.9  441.69  5159.3  442.22
#Mann=5,-1,0
  4691.3    0.16       0  4770.3    0.12       0  4997.2    0.07       0
  5001.2    0.12       0  5051.9    0.16       0
Bank Sta=4997.2,5001.2
Exp/Cntr=0.3,0.1

Type RM Length L Ch R = 1,532,383,383,383
BEGIN DESCRIPTION:
Mapping XS d6bcf72f
END DESCRIPTION:
XS GIS Cut Line= 3
      3481995.74     10437422.99      3482443.02     10437326.56
      3482457.38     10437111.19
#Sta/Elev= 30
  4688.8  437.37  4714.8  435.50  4719.9  435.89  4726.0  434.24  4746.5  433.18
  4764.1  430.66  4769.2  431.01  4813.4  425.79  4818.5  426.03  4836.6  424.63
  4857.6  423.52  4971.5  424.30  4981.7  423.08  4992.0  417.85  4998.4  416.76
  4998.6  416.26  5002.4  416.76  5005.5  418.61  5012.4  421.02  5022.7  423.30
  5054.8  425.40  5063.6  426.76  5099.0  428.82  5125.0  431.36  5146.2  432.36
  5181.4  431.53  5221.1  432.29  5281.6  433.00  5357.4  437.20  5362.2  436.71
#Mann=5,-1,0
  4688.8    0.16       0  4836.6    0.12       0  4998.4    0.07       0
  5002.4    0.12       0  5221.1    0.16       0
Bank Sta=4998.4,5002.4
Exp/Cntr=0.3,0.1

Type RM Length L Ch R = 1,149,0,0,0
BEGIN DESCRIPTION:
DUCK CREEK TRIB 48 1 0
END DESCRIPTION:
XS GIS Cut Line= 4
      3482008.07     10437546.05      3482159.91     10437685.58
      3482564.06     10437585.05      3482533.29     10437267.11
#Sta/Elev= 30
  4447.5  430.64  4496.6  426.65  4518.2  426.61  4539.2  425.13  4612.6  423.09
  4624.2  422.19  4666.3  422.40  4768.9  421.79  4800.2  422.20  4882.7  421.67
  4923.9  422.34  4954.8  421.80  4975.4  422.25  4980.6  421.21  4994.0  415.59
  4994.3  415.09  4997.8  415.09  4998.0  415.59  5006.3  418.80  5016.6  421.79
  5022.0  422.51  5057.9  422.54  5066.9  422.13  5154.0  422.40  5194.2  423.47
  5274.5  428.28  5294.6  428.43  5324.8  429.66  5371.1  430.04  5389.6  430.13
#Mann=5,-1,0
  4447.5    0.16       0  4612.6    0.12       0  4994.0    0.07       0
  4998.0    0.12       0  5371.1    0.16       0
Bank Sta=4994,4998
Exp/Cntr=0.3,0.1

Chan Stop Cuts=-1