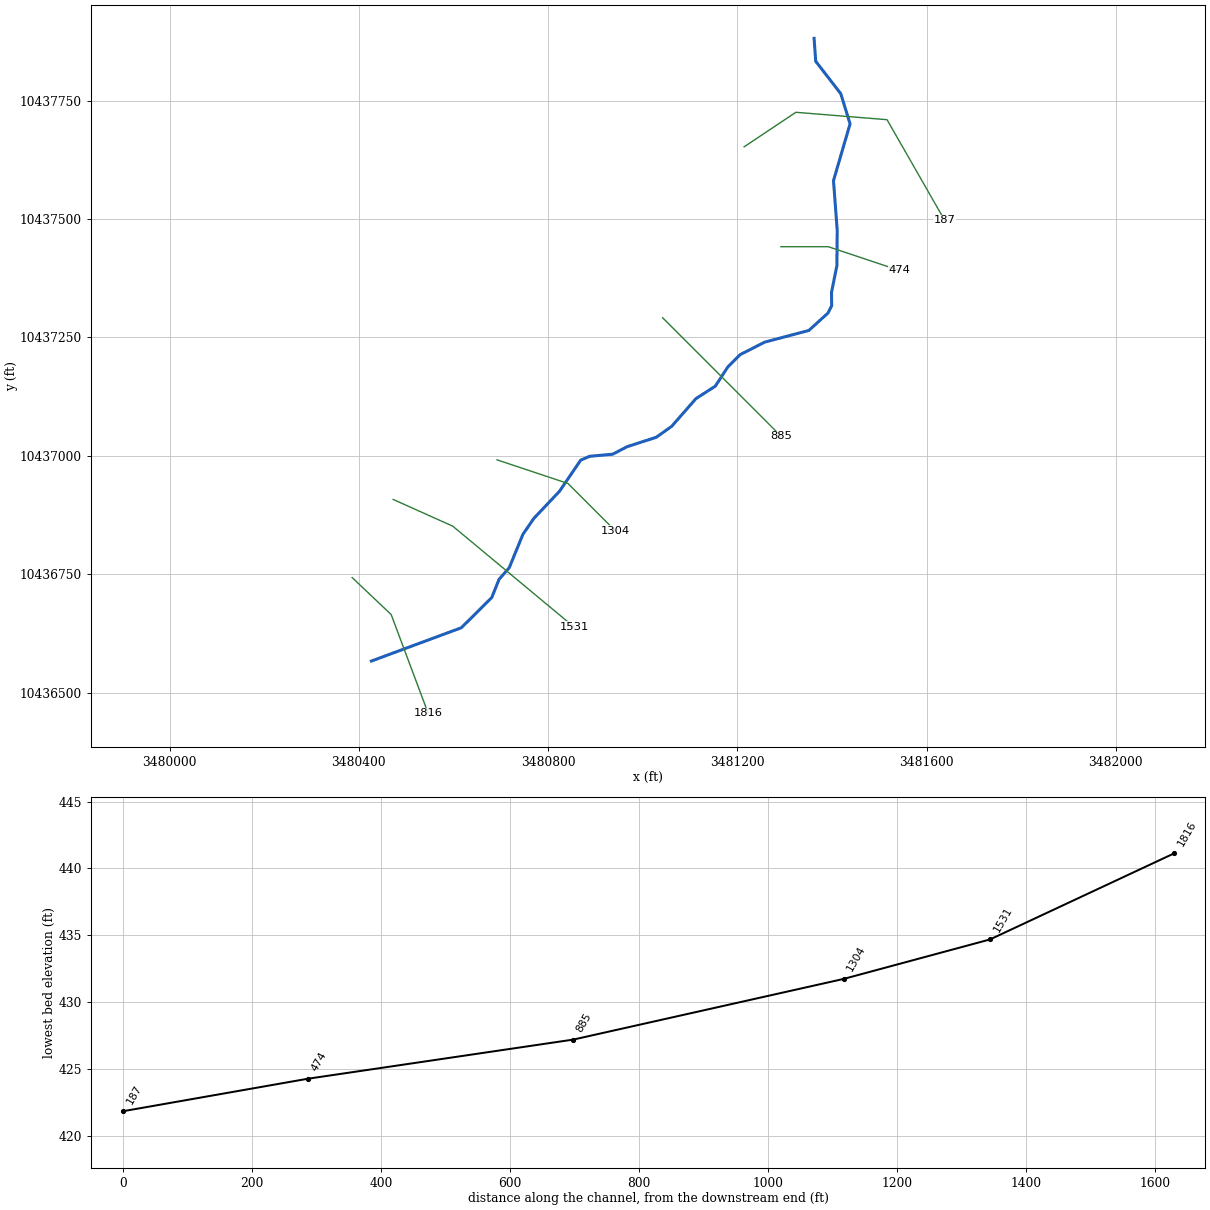
--- DUCK CREEK TRIB 49.prj (project) ---

Proj Title=DUCK CREEK TRIB 49 Base Level Engineering
Current Plan=p01
Default Exp/Contr=0.3,0.1
English Units
Geom File=g01
Flow File=f01
Plan File=p01
Y Axis Title=Elevation
X Axis Title(PF)=Main Channel Distance
X Axis Title(XS)=Station
BEGIN DESCRIPTION:
DUCK CREEK TRIB 49
END DESCRIPTION:
DSS Export Rating Curves= 0
DSS Export Rating Curve Sorted= 0
DSS Export Volume Flow Curves= 0
DXF OffsetX= 0
DXF OffsetY= 0
DXF ScaleX= 1
DXF ScaleY= 10

--- DUCK CREEK TRIB 49.p01 (plan) ---

Plan Title=Multiple Run
Short Identifier=Multiple
Geom File=g01
Flow File=f01
Subcritical Flow
K Sum by GR= 0
Std Step Tol= 0.01
Critical Tol= 0.01
Num of Std Step Trials= 20
Max Error Tol= 0.3
Flow Tol Ratio= 0.001
Split Flow NTrial= 30
Split Flow Tol= 0.02
Split Flow Ratio= 0.02
Log Output Level= 0
Friction Slope Method= 1
Unsteady Friction Slope Method= 2
Unsteady Bridges Friction Slope Method= 1
Parabolic Critical Depth
Global Vel Dist=  1 , 1 , 1
Global Log Level= 0
CheckData=True
Encroach Param= -1, 0, 0, 0
BEGIN DESCRIPTION:
Multiple Run
END DESCRIPTION:

--- DUCK CREEK TRIB 49.f01 (steady flow) ---

Flow Title=Multiple
Program Version=4.10
Number of Profiles= 7
Profile Names=10-year,25-year,50-year,1pct_min,100-year,1pct_plu,500-year
River Rch & RM=DUCK CREEK TRIB,Reach-1         ,1816
     254     322     373     318     430     582     568
Boundary for River Rch & Prof#=DUCK CREEK TRIB,Reach-1         , 1
Up Type= 0
Dn Type= 3
Dn Slope=0.005
Boundary for River Rch & Prof#=DUCK CREEK TRIB,Reach-1         , 2
Up Type= 0
Dn Type= 3
Dn Slope=0.005
Boundary for River Rch & Prof#=DUCK CREEK TRIB,Reach-1         , 3
Up Type= 0
Dn Type= 3
Dn Slope=0.005
Boundary for River Rch & Prof#=DUCK CREEK TRIB,Reach-1         , 4
Up Type= 0
Dn Type= 3
Dn Slope=0.005
Boundary for River Rch & Prof#=DUCK CREEK TRIB,Reach-1         , 5
Up Type= 0
Dn Type= 3
Dn Slope=0.005
Boundary for River Rch & Prof#=DUCK CREEK TRIB,Reach-1         , 6
Up Type= 0
Dn Type= 3
Dn Slope=0.005
Boundary for River Rch & Prof#=DUCK CREEK TRIB,Reach-1         , 7
Up Type= 0
Dn Type= 3
Dn Slope=0.005
DSS Import GetInterval= 0
DSS Import GetPeak= 0
DSS Import FillOption= 0

--- DUCK CREEK TRIB 49.g01 (geometry) ---

Geom Title=Existing Conditions
Program Version=4.10

River Reach=DUCK CREEK TRIB ,Reach-1
Reach XY= 30
      3480426.45     10436566.77      3480616.55     10436637.09
       3480680.8      10436700.8      3480696.25     10436739.32
      3480717.85     10436763.92      3480746.74     10436834.41
      3480770.03     10436868.26      3480823.98     10436925.21
      3480868.76     10436990.85      3480887.48     10436999.08
      3480936.35     10437003.51      3480966.95     10437019.37
      3481028.47     10437039.23      3481061.18     10437062.41
      3481112.45     10437120.89       3481153.5     10437147.32
      3481179.88     10437187.94      3481205.83     10437213.71
      3481257.71     10437240.15      3481351.03      10437264.8
       3481391.6     10437301.65      3481399.31     10437317.02
      3481398.98     10437345.26      3481410.37     10437401.94
        3481411.     10437476.33      3481403.15     10437581.15
       3481438.2       10437701.      3481418.53     10437764.79
      3481365.59     10437833.08      3481362.11     10437881.64

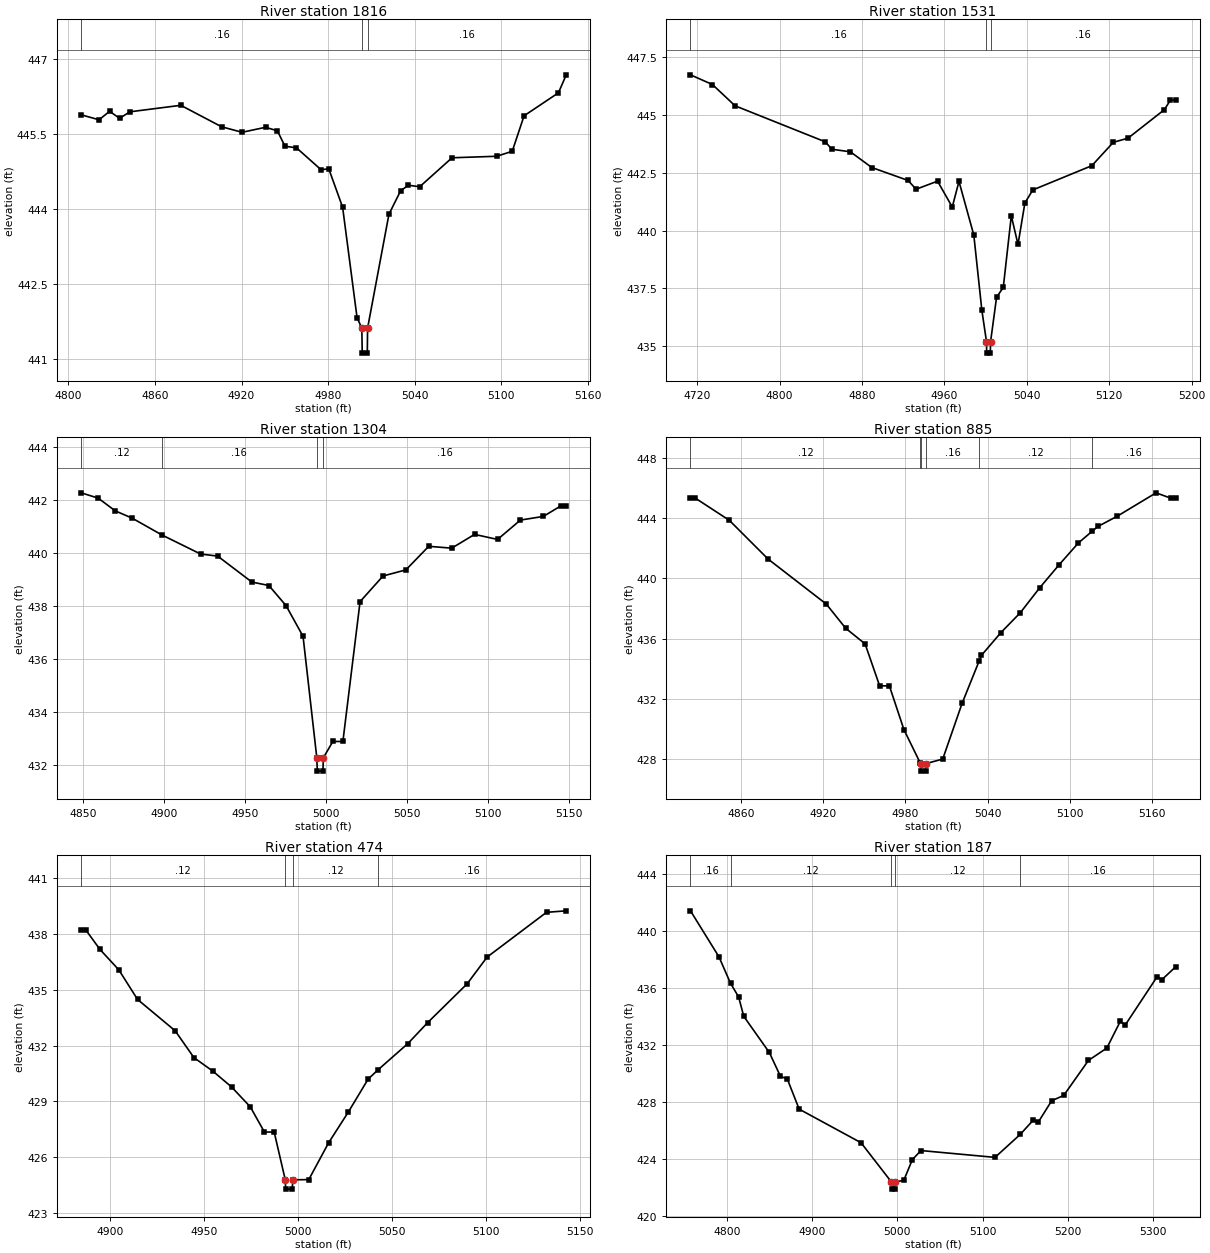
Type RM Length L Ch R = 1 ,1816    ,285,285,285
BEGIN DESCRIPTION:
DUCK CREEK TRIB 49 4 0
END DESCRIPTION:
XS GIS Cut Line= 3
      3480385.83     10436743.01      3480468.26     10436664.92
      3480546.37     10436456.63
#Sta/Elev= 30
  4808.9  445.89  4821.3  445.79  4828.6  445.96  4835.5  445.82  4842.7  445.95
  4877.9  446.08  4906.2  445.65  4920.4  445.54  4936.6  445.64  4944.8  445.57
  4950.1  445.26    4958  445.23  4975.1  444.79  4980.4  444.81    4990  444.04
    5000  441.83  5003.3  441.62  5003.6  441.12  5007.1  441.12  5007.3  441.62
  5022.1   443.9  5030.2  444.37  5035.6  444.48  5043.4  444.45  5065.8  445.03
  5096.8  445.06  5107.5  445.16  5115.7  445.87  5139.5  446.33  5144.9  446.69
#Mann= 3 ,-1 , 0
  4808.9     .16       0  5003.3     .07       0  5007.3     .16       0
Bank Sta=5003.3,5007.3
XS Rating Curve= 0 ,0
Exp/Cntr=0.3,0.1

Type RM Length L Ch R = 1 ,1531    ,227,227,227
BEGIN DESCRIPTION:
Mapping XS 42b6a4a8
END DESCRIPTION:
XS GIS Cut Line= 3
      3480472.63     10436907.96      3480598.47     10436851.55
      3480854.56     10436638.86
#Sta/Elev= 30
  4713.5  446.74  4734.8  446.32  4756.8   445.4  4844.4  443.84  4850.7  443.52
  4868.7  443.41  4889.5  442.73  4924.7  442.17  4932.5  441.79  4953.3  442.14
  4967.6  441.02  4974.1  442.13  4988.5  439.81  4996.3  436.56  5000.8   435.2
    5001   434.7  5004.5   434.7  5004.8   435.2  5010.6  437.12  5017.1  437.54
  5024.9  440.64  5031.4   439.4  5038.1   441.2  5045.8  441.76  5103.1  442.81
  5123.9  443.82  5138.2     444  5173.4  445.23  5179.4  445.65  5184.3  445.65
#Mann= 3 ,-1 , 0
  4713.5     .16       0  5000.8     .07       0  5004.8     .16       0
Bank Sta=5000.8,5004.8
XS Rating Curve= 0 ,0
Exp/Cntr=0.3,0.1

Type RM Length L Ch R = 1 ,1304    ,419,419,419
BEGIN DESCRIPTION:
DUCK CREEK TRIB 49 4 0
END DESCRIPTION:
XS GIS Cut Line= 3
      3480692.14     10436991.63      3480842.11     10436941.64
      3480942.11     10436841.64
#Sta/Elev= 28
    4849  442.26  4859.5  442.06    4870  441.58  4880.6   441.3  4898.8  440.67
  4922.7  439.95  4933.3  439.87  4954.4  438.89  4964.9  438.76  4975.5     438
    4986  436.84  4994.5  432.25  4994.8  431.75  4998.3  431.75  4998.5  432.25
  5004.4  432.87  5010.6  432.87  5021.2  438.15  5035.4  439.12  5049.5  439.35
  5063.6  440.24  5077.8  440.17  5091.9  440.69  5106.1   440.5  5120.2  441.23
  5134.4  441.37    5145  441.76  5148.5  441.76
#Mann= 4 ,-1 , 0
    4849     .12       0  4898.8     .16       0  4994.5     .07       0
  4998.5     .16       0
Bank Sta=4994.5,4998.5
XS Rating Curve= 0 ,0
Exp/Cntr=0.3,0.1

Type RM Length L Ch R = 1 ,885     ,411,411,411
BEGIN DESCRIPTION:
DUCK CREEK TRIB 49 2 0
END DESCRIPTION:
XS GIS Cut Line= 3
       3481042.1     10437291.65      3481142.11     10437191.64
      3481292.13     10437041.61
#Sta/Elev= 30
  4823.3  445.31  4826.8  445.31  4851.6  443.84  4879.9  441.27  4922.3  438.29
  4936.4  436.69  4950.6  435.65  4961.2  432.87  4968.3  432.87  4978.9  429.97
  4990.9  427.74    4991  427.72  4991.3  427.22  4994.8  427.22    4995  427.72
  5007.2  428.02  5021.3  431.71  5033.7  434.51  5035.4  434.89  5049.6   436.4
  5063.7  437.71  5077.9  439.37    5092  440.89  5106.1  442.34  5116.2  443.12
  5120.3  443.43  5134.4  444.11  5162.7  445.66  5173.3  445.31  5176.9  445.31
#Mann= 6 ,-1 , 0
  4823.3     .12       0  4990.9     .16       0    4991     .07       0
    4995     .16       0  5033.7     .12       0  5116.2     .16       0
Bank Sta=4991,4995
XS Rating Curve= 0 ,0
Exp/Cntr=0.3,0.1

Type RM Length L Ch R = 1 ,474     ,287,287,287
BEGIN DESCRIPTION:
DUCK CREEK TRIB 49 3 0
END DESCRIPTION:
XS GIS Cut Line= 3
      3481292.07     10437441.64      3481392.11     10437441.64
      3481542.06     10437391.66
#Sta/Elev= 27
  4884.8  438.19  4887.3  438.19  4894.8  437.15  4904.8  436.06  4914.8  434.47
  4934.8  432.79  4944.8  431.35  4954.8  430.63  4964.8  429.78  4974.8  428.71
  4982.3  427.36  4987.5  427.36  4993.4   424.8  4993.6   424.3  4997.1   424.3
  4997.4   424.8  5005.9  424.81  5016.5  426.79    5027  428.44  5037.5   430.2
  5042.8   430.7  5058.6   432.1  5069.2  433.23  5090.2  435.31  5100.8  436.74
  5132.4  439.14  5142.9  439.22
#Mann= 4 ,-1 , 0
  4884.8     .12       0  4993.4     .07       0  4997.4     .12       0
  5042.8     .16       0
Bank Sta=4993.4,4997.4
XS Rating Curve= 0 ,0
Exp/Cntr=0.3,0.1

Type RM Length L Ch R = 1 ,187     ,0,0,0
BEGIN DESCRIPTION:
DUCK CREEK TRIB 49 1 0
END DESCRIPTION:
XS GIS Cut Line= 4
      3481214.28     10437652.54      3481323.64     10437725.45
      3481516.35     10437709.83      3481637.84     10437497.85
#Sta/Elev= 30
  4757.2  441.42  4790.6  438.19  4804.2  436.33  4813.7  435.37  4819.7  434.01
  4849.7  431.47  4862.8  429.79  4870.8  429.61  4884.7  427.49  4957.3  425.13
    4993  422.37  4993.3  421.87  4996.8  421.87    4997  422.37  5007.5  422.49
  5017.5  423.94  5027.6  424.58  5114.5   424.1  5144.2  425.72  5159.4  426.72
  5165.1  426.56    5181  428.08  5195.1  428.45  5224.1  430.91  5245.7  431.78
  5261.5  433.66  5267.3   433.4  5304.7  436.79  5310.4  436.59  5326.3  437.48
#Mann= 5 ,-1 , 0
  4757.2     .16       0  4804.2     .12       0    4993     .07       0
    4997     .12       0  5144.2     .16       0
Bank Sta=4993,4997
XS Rating Curve= 0 ,0
Exp/Cntr=0.3,0.1

Chan Stop Cuts=-1
Use User Specified Reach Order=0
Composite Channel Slope=5