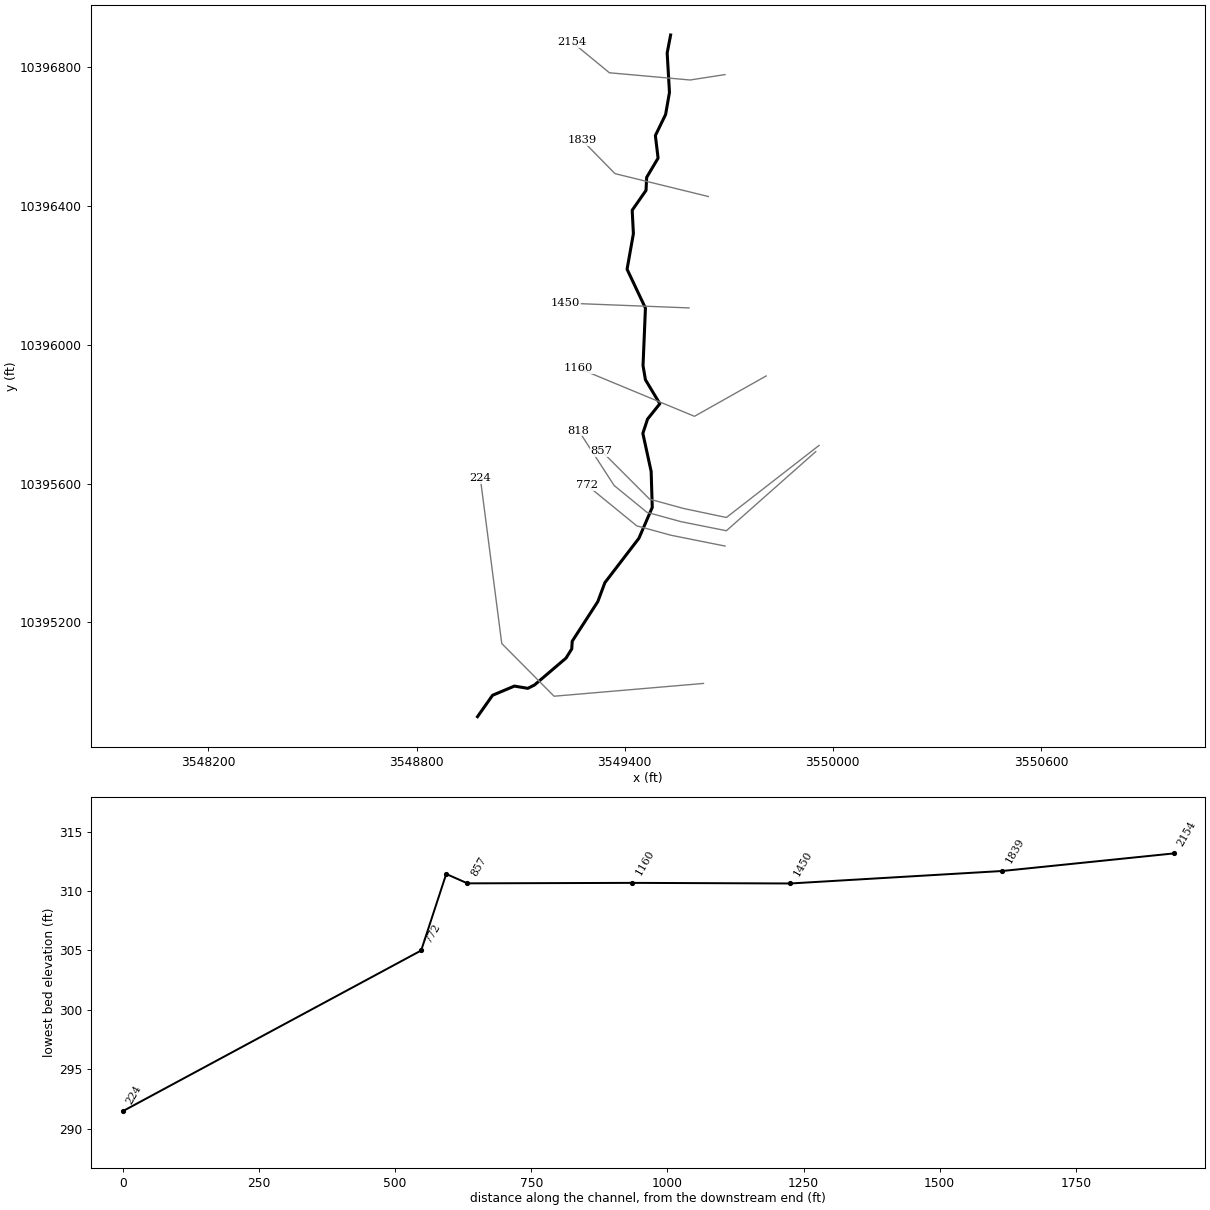
--- DUCK CREEK TRIB 8.prj (project) ---

Proj Title=DUCK CREEK TRIB 8 Base Level Engineering
Current Plan=p01
Default Exp/Contr=0.3,0.1
English Units
Geom File=g01
Flow File=f01
Plan File=p01
Y Axis Title=Elevation
X Axis Title(PF)=Main Channel Distance
X Axis Title(XS)=Station
BEGIN DESCRIPTION:
DUCK CREEK TRIB 8
END DESCRIPTION:
DSS Export Rating Curves= 0
DSS Export Rating Curve Sorted= 0
DSS Export Volume Flow Curves= 0
DXF OffsetX= 0
DXF OffsetY= 0
DXF ScaleX= 1
DXF ScaleY= 10

--- DUCK CREEK TRIB 8.p01 (plan) ---

Plan Title=Multiple Run
Short Identifier=Multiple
Geom File=g01
Flow File=f01
Subcritical Flow
K Sum by GR= 0
Std Step Tol= 0.01
Critical Tol= 0.01
Num of Std Step Trials= 20
Max Error Tol= 0.3
Flow Tol Ratio= 0.001
Split Flow NTrial= 30
Split Flow Tol= 0.02
Split Flow Ratio= 0.02
Log Output Level= 0
Friction Slope Method= 1
Unsteady Friction Slope Method= 2
Unsteady Bridges Friction Slope Method= 1
Parabolic Critical Depth
Global Vel Dist=  1 , 1 , 1
Global Log Level= 0
CheckData=True
Encroach Param= -1, 0, 0, 0
BEGIN DESCRIPTION:
Multiple Run
END DESCRIPTION:

--- DUCK CREEK TRIB 8.f01 (steady flow) ---

Flow Title=Multiple
Program Version=4.10
Number of Profiles= 7
Profile Names=10-year,25-year,50-year,1pct_min,100-year,1pct_plu,500-year
River Rch & RM=DUCK CREEK TRIB,Reach-1         ,2154
     362     470     555     481     650     880     888
Boundary for River Rch & Prof#=DUCK CREEK TRIB,Reach-1         , 1
Up Type= 0
Dn Type= 3
Dn Slope=0.024
Boundary for River Rch & Prof#=DUCK CREEK TRIB,Reach-1         , 2
Up Type= 0
Dn Type= 3
Dn Slope=0.024
Boundary for River Rch & Prof#=DUCK CREEK TRIB,Reach-1         , 3
Up Type= 0
Dn Type= 3
Dn Slope=0.024
Boundary for River Rch & Prof#=DUCK CREEK TRIB,Reach-1         , 4
Up Type= 0
Dn Type= 3
Dn Slope=0.024
Boundary for River Rch & Prof#=DUCK CREEK TRIB,Reach-1         , 5
Up Type= 0
Dn Type= 3
Dn Slope=0.024
Boundary for River Rch & Prof#=DUCK CREEK TRIB,Reach-1         , 6
Up Type= 0
Dn Type= 3
Dn Slope=0.024
Boundary for River Rch & Prof#=DUCK CREEK TRIB,Reach-1         , 7
Up Type= 0
Dn Type= 3
Dn Slope=0.024
DSS Import GetInterval= 0
DSS Import GetPeak= 0
DSS Import FillOption= 0

--- DUCK CREEK TRIB 8.g01 (geometry) ---

Geom Title=Existing Conditions
Program Version=4.10

River Reach=DUCK CREEK TRIB ,Reach-1
Reach XY= 30
      3549532.33     10396893.53      3549522.43     10396841.77
      3549529.03     10396728.13      3549517.91      10396664.5
       3549488.4     10396603.74      3549496.21     10396538.64
      3549463.23     10396483.08      3549461.49     10396445.75
      3549421.56     10396388.46      3549425.03     10396320.75
       3549406.8     10396218.32      3549459.75     10396106.34
      3549452.81     10395940.54      3549459.75     10395899.75
      3549501.26      10395830.6      3549465.84     10395786.33
       3549452.3     10395745.19      3549476.26     10395635.29
      3549479.38     10395531.64      3549440.84     10395442.58
      3549342.84      10395314.8      3549322.44     10395260.12
      3549248.65     10395145.97      3549247.35     10395123.83
      3549230.86     10395097.36      3549139.71     10395019.66
      3549120.62     10395010.12      3549081.99     10395016.63
      3549019.05     10394990.15      3548975.61     10394928.42

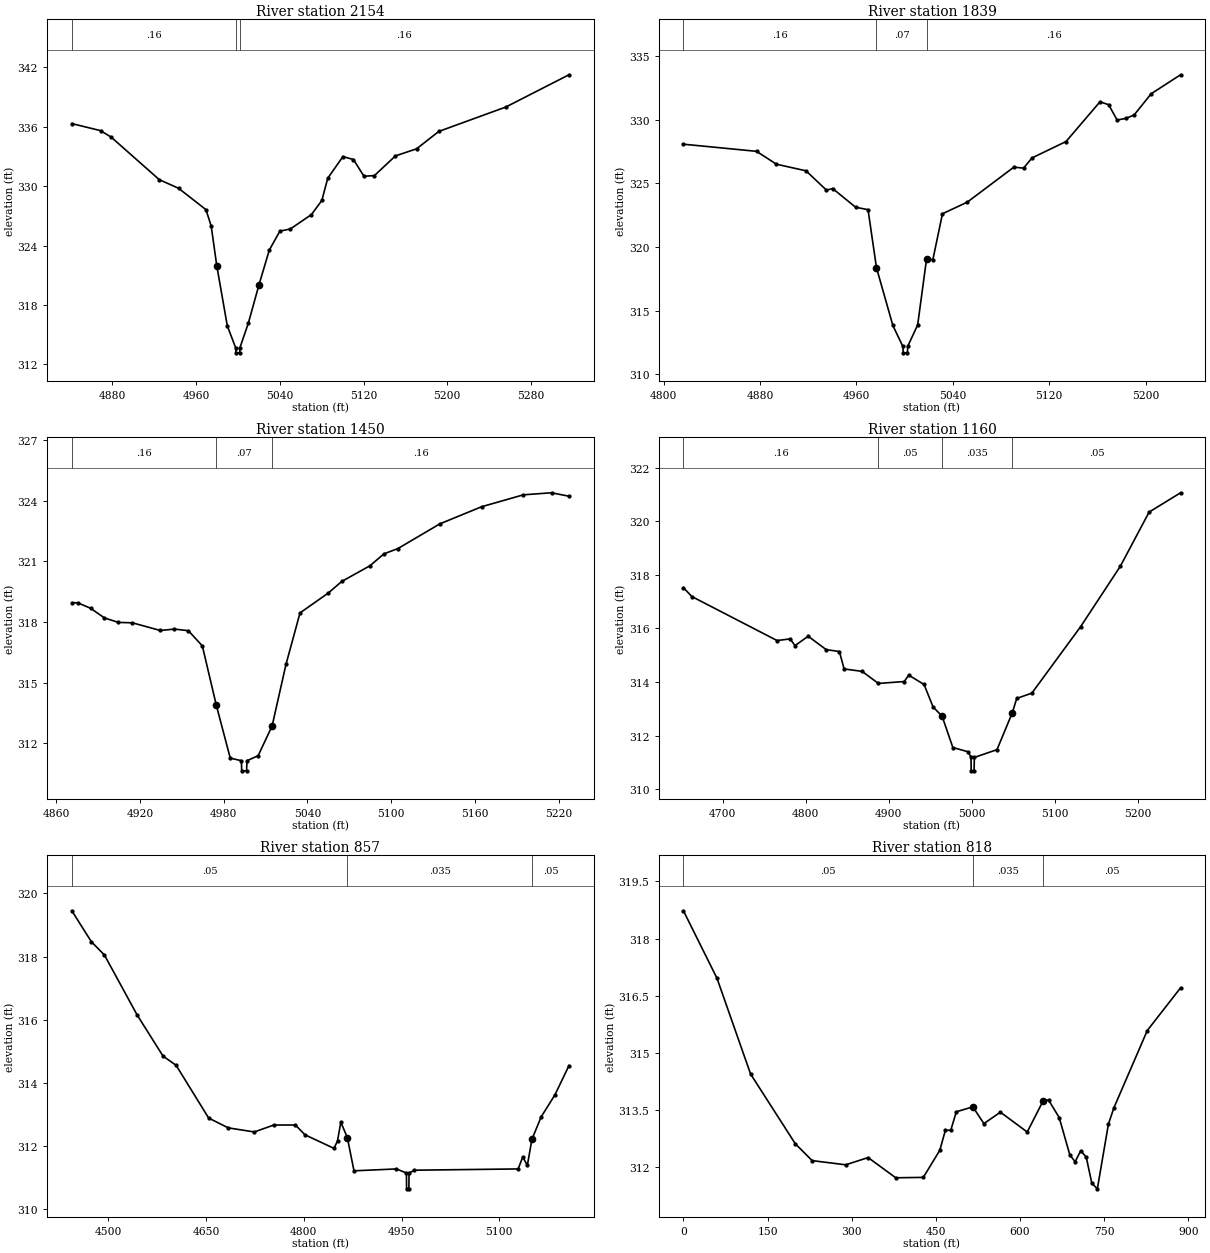
Type RM Length L Ch R = 1 ,2154    ,315,315,315
XS GIS Cut Line= 4
       3549689.2     10396779.51      3549588.52     10396763.88
      3549355.88     10396784.72      3549248.27     10396873.23
#Sta/Elev= 30
  4841.4  336.32  4868.8  335.61  4878.9  334.96  4924.9  330.66  4943.3  329.79
  4969.5  327.63  4974.5  325.98  4979.8  321.98  4989.9  315.89  4997.9  313.67
  4998.2  313.17  5001.7  313.17  5001.9  313.67    5010  316.18    5020  319.99
    5030  323.55  5040.1  325.46  5050.1  325.68  5070.2  327.13  5080.2  328.56
  5085.8   330.8  5100.3  332.99  5110.4  332.69  5120.4     331  5130.4  331.07
  5150.5  333.06  5170.6  333.77  5191.9  335.53  5255.8  337.99  5316.2  341.25
#Mann= 3 ,-1 , 0
  4841.4     .16       0  4997.9     .07       0  5001.9     .16       0
Bank Sta=4979.8,5020
XS Rating Curve= 0 ,0
Exp/Cntr=0.3,0.1

Type RM Length L Ch R = 1 ,1839    ,389,389,389
BEGIN DESCRIPTION:
DUCK CREEK TRIB 8 2 0
END DESCRIPTION:
XS GIS Cut Line= 3
      3549641.01     10396428.01      3549371.93     10396493.98
      3549276.81     10396590.83
#Sta/Elev= 30
  4816.3  328.07    4877  327.51  4893.5   326.5  4918.1  325.98  4935.1  324.46
  4940.2  324.59  4959.3  323.12  4969.6  322.93  4976.6  318.37  4990.2  313.84
  4998.5  312.19  4998.8  311.69  5002.3  311.69  5002.5  312.19  5010.8  313.88
  5018.2  319.07  5023.4     319  5031.4  322.61    5052  323.52  5090.7  326.27
  5098.7  326.19  5105.7  326.99    5134  328.28  5162.2   331.4  5169.4  331.17
  5176.4  329.97  5183.5  330.09  5190.5  330.36  5204.7  332.03  5229.1  333.52
#Mann= 3 , 0 , 0
  4816.3     .16       0  4976.6     .07       0  5018.2     .16       0
Bank Sta=4976.6,5018.2
XS Rating Curve= 0 ,0
Exp/Cntr=0.3,0.1

Type RM Length L Ch R = 1 ,1450    ,290,290,290
BEGIN DESCRIPTION:
Mapping XS ff1e0022
END DESCRIPTION:
XS GIS Cut Line= 2
      3549585.51     10396106.83      3549229.58     10396120.72
#Sta/Elev= 30
  4871.2  318.95  4875.4  318.95  4884.6  318.68  4894.6   318.2  4904.6  317.98
  4914.6  317.96  4934.6  317.58  4944.7  317.65  4954.7  317.57  4964.7  316.82
  4974.7  313.89  4984.7  311.27  4992.7  311.14  4992.9  310.64  4996.4  310.64
  4996.7  311.14  5004.7  311.39  5014.7  312.86  5024.7  315.92  5034.7  318.45
  5054.7  319.42  5064.7  320.01  5084.8  320.78  5094.8  321.37  5104.8  321.63
  5134.8  322.85  5164.8   323.7  5194.8  324.29  5214.9  324.39  5227.4  324.22
#Mann= 3 , 0 , 0
  4871.2     .16       0  4974.7     .07       0  5014.7     .16       0
Bank Sta=4974.7,5014.7
XS Rating Curve= 0 ,0
Exp/Cntr=0.3,0.1

Type RM Length L Ch R = 1 ,1160    ,303,303,303
BEGIN DESCRIPTION:
DUCK CREEK TRIB 8 3 0
END DESCRIPTION:
XS GIS Cut Line= 3
      3549807.73     10395910.67       3549601.1     10395794.33
      3549266.54     10395933.01
#Sta/Elev= 30
  4652.5  317.52  4662.7  317.19  4765.3  315.55  4781.2  315.61    4787  315.36
  4802.9  315.71  4824.6  315.21  4840.5  315.14  4846.2  314.49  4867.9   314.4
  4887.5  313.95  4918.7  314.02  4924.1  314.26  4942.6  313.91  4953.5  313.07
  4964.3  312.73  4977.3  311.56  4995.8   311.4  4999.2  311.19  4999.4  310.69
  5002.9  310.69  5003.2  311.19  5030.5  311.48  5048.9  312.85  5054.3  313.39
  5072.6  313.59  5131.4  316.07  5179.2  318.32  5213.9  320.34  5251.8  321.06
#Mann= 4 ,-1 , 0
  4652.5     .16       0  4887.5     .05       0  4964.3    .035       0
  5048.9     .05       0
Bank Sta=4964.3,5048.9
XS Rating Curve= 0 ,0
Exp/Cntr=0.3,0.1

Type RM Length L Ch R = 1 ,857     ,39,39,39
BEGIN DESCRIPTION:
DUCK CREEK TRIB 8 6 0
END DESCRIPTION:
XS GIS Cut Line= 5
     3549960.358    10395710.467      3549693.12     10395502.66
      3549569.89     10395528.61      3549471.79     10395555.52
      3549333.77     10395693.61
#Sta/Elev= 30
 4444.01  319.45 4474.01  318.47 4494.01  318.05 4544.01  316.16    4584  314.85
    4604  314.56    4654  312.89    4684  312.58    4724  312.45    4754  312.67
  4787.1  312.67  4801.8  312.36  4846.4  311.93  4851.7  312.17  4856.8  312.76
  4866.8  312.27    4877  311.22  4942.1  311.28  4957.5  311.15  4957.7  310.65
  4961.2  310.65  4961.5  311.15  4969.8  311.24  5128.9  311.28    5136  311.66
    5143  311.39  5150.1  312.22  5164.3  312.93  5185.5  313.63  5206.9  314.55
#Mann= 3 , 0 , 0
 4444.01     .05       0  4866.8    .035       0  5150.1     .05       0
Bank Sta=4866.8,5150.1
XS Rating Curve= 0 ,0
Exp/Cntr=0.3,0.1

Type RM Length L Ch R = 1 ,818     ,46,46,46
BEGIN DESCRIPTION:
DUCK CREEK TRIB 8 4 0
END DESCRIPTION:
XS GIS Cut Line= 6
     3549950.702    10395692.534       3549693.1     10395464.47
      3549562.29     10395490.63      3549464.19     10395517.54
      3549369.58      10395594.8      3549267.11     10395753.05
#Sta/Elev= 30
       0  318.73   59.86  316.96  119.73  314.45  199.55  312.62  229.48  312.18
  289.35  312.07  329.26  312.26  378.51  311.73  427.61  311.74  457.07  312.45
  466.89  312.97  476.71  312.98  486.53  313.46  515.99  313.59  535.63  313.15
  565.09  313.45   612.9  312.93  641.39  313.75  650.89  313.77  669.88  313.31
  688.88  312.33  698.37  312.15  708.26  312.44  718.15  312.27  728.04  311.59
  737.93  311.44  757.71  313.14   767.6  313.57  826.94  315.59  886.28  316.71
#Mann= 3 , 0 , 0
       0     .05       0  515.99    .035       0  641.39     .05       0
#XS Ineff= 2 , 0
       0   508.2  313.55   651.5       0  313.72
Permanent Ineff=
       T       T
Bank Sta=515.99,641.39
XS Rating Curve= 0 ,0
Exp/Cntr=0.3,0.1

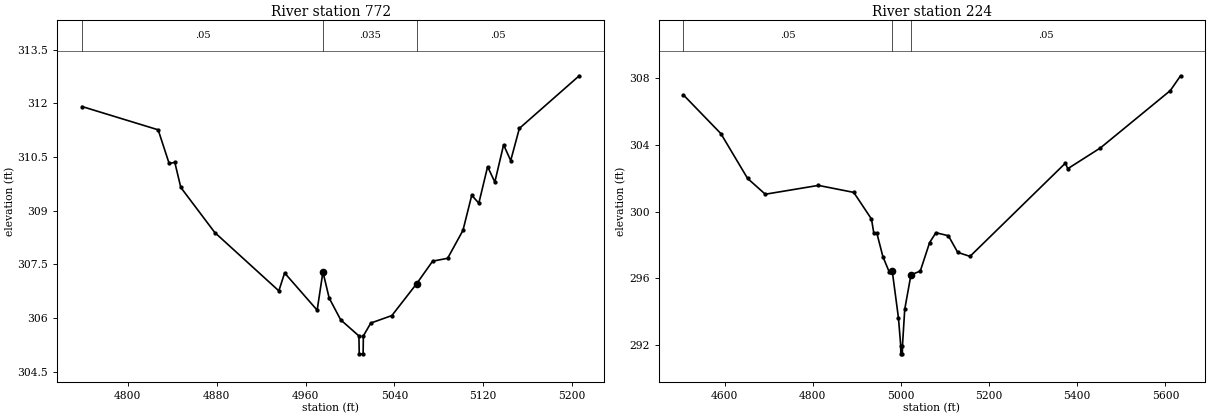
Type RM Length L Ch R = 1 ,772     ,548,548,548
BEGIN DESCRIPTION:
DUCK CREEK TRIB 8 5 0
END DESCRIPTION:
XS GIS Cut Line= 4
      3549689.29     10395420.31      3549532.99     10395451.57
      3549434.89     10395478.48      3549290.32     10395596.43
#Sta/Elev= 30
  4758.8  311.91  4827.3  311.26  4837.2  310.32  4842.3  310.35  4847.7  309.65
  4878.3  308.39    4936  306.76  4941.2  307.26  4970.5  306.22  4975.7  307.29
  4981.3  306.56  4991.7  305.95  5008.1   305.5  5008.4     305  5011.9     305
  5012.1   305.5  5018.8  305.86  5037.8  306.07  5060.1  306.96  5074.5  307.59
    5088  307.67  5101.8  308.45  5109.7  309.43  5116.1  309.21    5124  310.23
  5130.5   309.8  5138.4  310.84  5144.8   310.4  5152.6   311.3  5206.5  312.77
#Mann= 3 , 0 , 0
  4758.8     .05       0  4975.7    .035       0  5060.1     .05       0
Bank Sta=4975.7,5060.1
XS Rating Curve= 0 ,0
Exp/Cntr=0.3,0.1

Type RM Length L Ch R = 1 ,224     ,0,0,0
BEGIN DESCRIPTION:
DUCK CREEK TRIB 8 1 0
END DESCRIPTION:
XS GIS Cut Line= 4
      3549627.11     10395024.29      3549196.37      10394987.4
      3549045.55     10395139.31      3548983.71     10395616.64
#Sta/Elev= 30
  4506.7  307.01  4591.6  304.69  4652.2     302  4692.4  301.05  4812.8  301.58
  4893.1  301.16  4933.3  299.56  4938.6  298.71  4945.5  298.71  4959.1  297.31
  4973.3   296.4  4980.4  296.44  4994.5  293.62  4999.6  291.97  4999.8  291.47
  5003.3  291.47  5003.6  291.97  5008.7  294.14  5022.8  296.21    5044  296.44
  5065.2  298.15  5079.4  298.74  5107.7  298.56  5128.9  297.56  5156.8  297.32
  5373.3  302.92  5378.4  302.58  5452.6  303.83  5611.1  307.27  5634.4  308.16
#Mann= 3 , 0 , 0
  4506.7     .05       0  4980.4    .035       0  5022.8     .05       0
#XS Ineff= 2 , 0
                         5086.48          298.68
Permanent Ineff=
       F       F
Bank Sta=4980.4,5022.8
XS Rating Curve= 0 ,0
Exp/Cntr=0.3,0.1

Chan Stop Cuts=-1
Use User Specified Reach Order=0
Composite Channel Slope=5