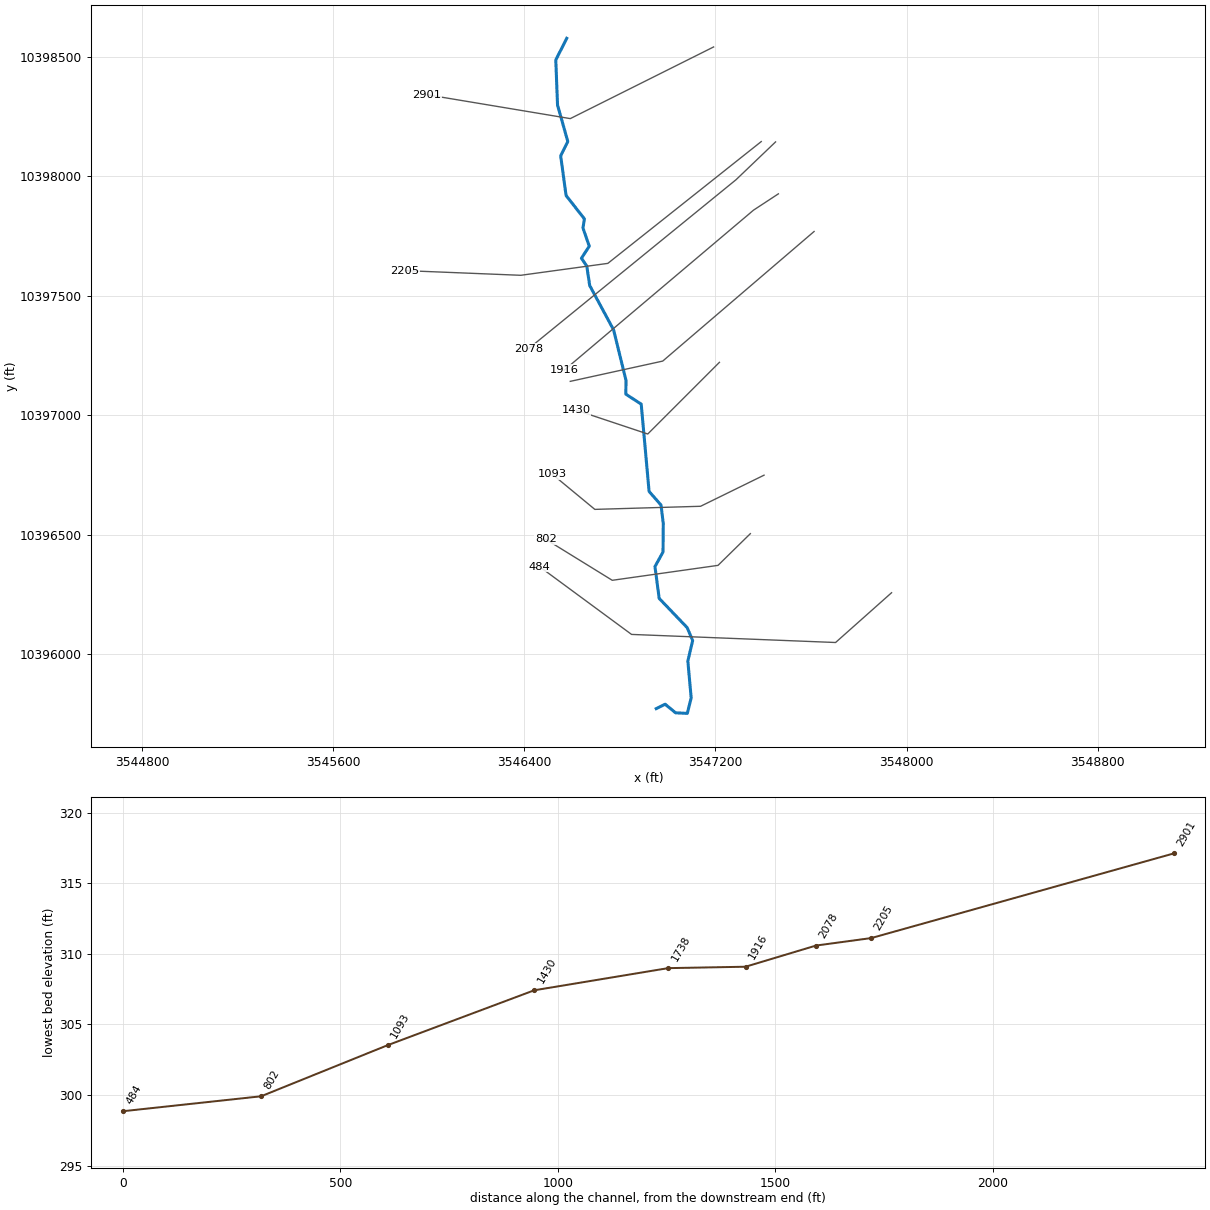
--- DUCK CREEK TRIB 9.prj (project) ---

Proj Title=DUCK CREEK TRIB 9 Base Level Engineering
Current Plan=p01
Default Exp/Contr=0.3,0.1
English Units
Geom File=g01
Flow File=f01
Plan File=p01
BEGIN DESCRIPTION:
DUCK CREEK TRIB 9
END DESCRIPTION:

--- DUCK CREEK TRIB 9.p01 (plan) ---

Plan Title=Multiple Run
Short Identifier=Multiple
Geom File=g01
Flow File=f01
Subcritical Flow
K Sum by GR= 0
Std Step Tol= 0.01
Critical Tol= 0.01
Num of Std Step Trials= 20
Max Error Tol= 0.3
Flow Tol Ratio= 0.001
Split Flow NTrial= 30
Split Flow Tol= 0.02
Split Flow Ratio= 0.02
Log Output Level= 0
Friction Slope Method= 1
Unsteady Friction Slope Method= 2
Unsteady Bridges Friction Slope Method= 1
Parabolic Critical Depth
Global Vel Dist=  1 , 1 , 1
Global Log Level= 0
CheckData=True
Encroach Param= -1, 0, 0, 0
BEGIN DESCRIPTION:
Multiple Run
END DESCRIPTION:

--- DUCK CREEK TRIB 9.f01 (steady flow) ---

Flow Title=Multiple
Number of Profiles=7
Profile Names=10-year,25-year,50-year,1pct_min,100-year,1pct_plu,500-year
River Rch & RM= DUCK CREEK TRIB ,Reach-1,2901
     578     773     929     818    1106    1496    1561
Boundary for River Rch & Prof#=DUCK CREEK TRIB ,Reach-1,1
Up Type=0
Dn Type=3
Dn Slope=0.005
Boundary for River Rch & Prof#=DUCK CREEK TRIB ,Reach-1,2
Up Type=0
Dn Type=3
Dn Slope=0.005
Boundary for River Rch & Prof#=DUCK CREEK TRIB ,Reach-1,3
Up Type=0
Dn Type=3
Dn Slope=0.005
Boundary for River Rch & Prof#=DUCK CREEK TRIB ,Reach-1,4
Up Type=0
Dn Type=3
Dn Slope=0.005
Boundary for River Rch & Prof#=DUCK CREEK TRIB ,Reach-1,5
Up Type=0
Dn Type=3
Dn Slope=0.005
Boundary for River Rch & Prof#=DUCK CREEK TRIB ,Reach-1,6
Up Type=0
Dn Type=3
Dn Slope=0.005
Boundary for River Rch & Prof#=DUCK CREEK TRIB ,Reach-1,7
Up Type=0
Dn Type=3
Dn Slope=0.005

--- DUCK CREEK TRIB 9.g01 (geometry) ---

Geom Title=Existing Conditions

River Reach=DUCK CREEK TRIB ,Reach-1
Reach XY= 30
      3546577.21     10398577.69      3546531.36     10398486.87
      3546538.79     10398297.97      3546581.71     10398145.90
      3546551.85     10398086.18      3546574.42     10397919.86
      3546651.15     10397821.94      3546645.25     10397783.40
      3546671.64     10397707.36      3546638.65     10397657.01
      3546661.22     10397624.37      3546673.37     10397542.77
      3546773.37     10397357.36      3546825.46     10397145.23
      3546824.53     10397088.03      3546889.03     10397046.24
      3546922.00     10396680.76      3546971.93     10396623.83
      3546981.42     10396546.34      3546980.35     10396427.23
      3546946.65     10396366.01      3546964.25     10396233.01
      3547081.44     10396110.61      3547104.44     10396056.36
      3547084.28     10395970.92      3547098.22     10395816.84
      3547082.11     10395751.64      3547032.91     10395753.91
      3546989.41     10395789.88      3546952.11     10395771.64

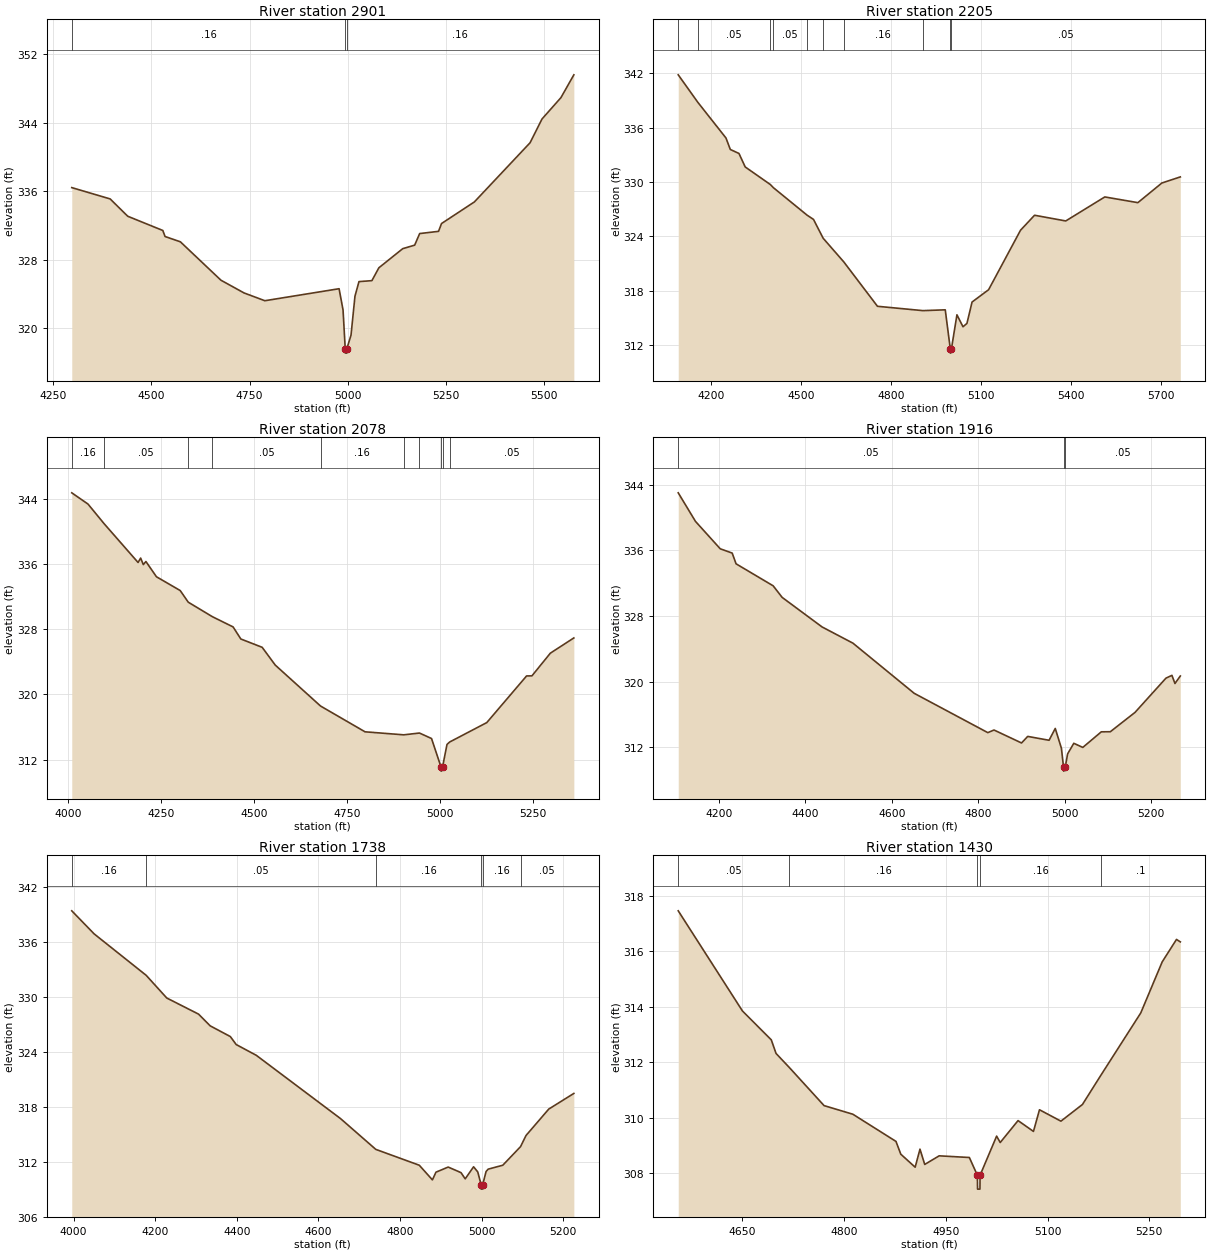
Type RM Length L Ch R = 1,2901,696,696,696
BEGIN DESCRIPTION:
DUCK CREEK TRIB 9 8 0
END DESCRIPTION:
XS GIS Cut Line= 3
      3547192.12     10398541.65      3546592.11     10398241.64
      3545992.11     10398341.64
#Sta/Elev= 30
  4297.2  336.42  4395.0  335.10  4439.8  333.08  4529.2  331.42  4534.8  330.72
  4573.9  330.10  4677.3  325.62  4736.0  324.14  4789.1  323.23  4978.2  324.63
  4988.3  322.16  4993.9  317.62  4994.2  317.12  4997.7  317.12  4997.9  317.62
  5008.6  319.21  5018.7  323.76  5028.9  325.46  5061.8  325.57  5079.6  327.07
  5140.4  329.30  5170.8  329.71  5183.5  331.06  5231.6  331.32  5239.2  332.23
  5322.9  334.75  5464.8  341.65  5495.2  344.42  5543.4  346.91  5576.3  349.57
#Mann=3,-1,0
  4297.2    0.16       0  4993.9    0.07       0  4997.9    0.16       0
Bank Sta=4993.9,4997.9
Exp/Cntr=0.3,0.1

Type RM Length L Ch R = 1,2205,127,127,127
BEGIN DESCRIPTION:
DUCK CREEK TRIB 9 7 0
END DESCRIPTION:
XS GIS Cut Line= 4
      3547391.66     10398145.55      3546749.31     10397635.57
      3546384.72     10397585.66      3545900.78     10397605.19
#Sta/Elev= 30
  4090.9  341.84  4156.3  338.80  4249.9  334.87  4264.4  333.60  4293.2  333.16
  4314.0  331.67  4397.8  329.73  4407.6  329.39  4520.1  326.35  4541.5  325.88
  4573.7  323.80  4642.4  321.19  4754.6  316.29  4906.0  315.81  4980.4  315.90
  4997.1  311.62  4997.3  311.12  5001.1  311.62  5019.3  315.35  5039.5  314.03
  5052.6  314.40  5069.7  316.76  5124.8  318.12  5231.2  324.69  5277.9  326.34
  5381.8  325.71  5511.9  328.36  5622.0  327.73  5702.0  329.90  5763.4  330.57
#Mann=10,-1,0
  4090.9    0.16       0  4156.3    0.05       0  4397.8    0.16       0
  4407.6    0.05       0  4520.1    0.16       0  4573.7    0.05       0
  4642.4    0.16       0  4906.0    0.05       0  4997.1    0.03       0
  5001.1    0.05       0
Bank Sta=4997.1,5001.1
Exp/Cntr=0.3,0.1

Type RM Length L Ch R = 1,2078,162,162,162
BEGIN DESCRIPTION:
DUCK CREEK TRIB 9 5 0
END DESCRIPTION:
XS GIS Cut Line= 3
      3547451.54     10398144.08      3547286.06     10397985.84
      3546416.72     10397277.88
#Sta/Elev= 30
  4008.9  344.71  4052.6  343.33  4096.0  340.92  4187.2  336.17  4194.1  336.71
  4201.3  335.91  4208.3  336.29  4236.6  334.42  4300.5  332.73  4322.2  331.30
  4387.2  329.52  4442.7  328.27  4463.5  326.79  4520.9  325.77  4556.1  323.59
  4677.9  318.57  4797.5  315.41  4901.6  315.04  4943.9  315.26  4976.3  314.59
  5001.9  311.09  5002.1  310.59  5005.9  311.09  5017.9  313.86  5025.1  314.16
  5124.9  316.54  5231.9  322.26  5246.3  322.27  5295.8  325.05  5359.0  326.92
#Mann=10,-1,0
  4008.9    0.16       0  4096.0    0.05       0  4322.2    0.16       0
  4387.2    0.05       0  4677.9    0.16       0  4901.6    0.05       0
  4943.9    0.16       0  5001.9    0.07       0  5005.9    0.16       0
  5025.1    0.05       0
Bank Sta=5001.9,5005.9
Exp/Cntr=0.3,0.1

Type RM Length L Ch R = 1,1916,178,178,178
BEGIN DESCRIPTION:
DUCK CREEK TRIB 9 6 0
END DESCRIPTION:
XS GIS Cut Line= 3
      3547463.33     10397926.69      3547358.98     10397858.24
      3546567.28     10397188.94
#Sta/Elev= 30
  4105.7  343.00  4145.6  339.52  4202.9  336.18  4230.5  335.66  4239.5  334.35
  4325.3  331.67  4346.1  330.26  4438.4  326.66  4509.9  324.68  4651.6  318.57
  4821.9  313.78  4836.2  314.10  4899.9  312.52  4914.2  313.32  4963.6  312.85
  4977.9  314.29  4992.2  311.87  4997.0  309.59  4997.2  309.09  5001.0  309.59
  5006.5  311.19  5020.8  312.48  5041.6  311.98  5084.5  313.88  5105.3  313.89
  5162.5  316.25  5234.0  320.42  5247.8  320.76  5254.8  319.77  5267.2  320.68
#Mann=3,-1,0
  4105.7    0.05       0  4997.0    0.04       0  5001.0    0.05       0
Bank Sta=4997,5001
Exp/Cntr=0.3,0.1

Type RM Length L Ch R = 1,1738,308,308,308
BEGIN DESCRIPTION:
DUCK CREEK TRIB 9 4 0
END DESCRIPTION:
XS GIS Cut Line= 3
      3547612.75     10397769.03      3546979.09     10397226.51
      3546592.07     10397141.63
#Sta/Elev= 30
  3995.4  339.38  4050.3  336.86  4177.7  332.34  4228.2  329.86  4306.1  328.10
  4334.6  326.82  4384.0  325.65  4398.3  324.78  4447.7  323.60  4654.1  316.69
  4740.5  313.33  4847.0  311.60  4879.2  310.00  4887.9  310.84  4917.9  311.40
  4949.3  310.79  4959.6  310.11  4980.1  311.43  4990.3  310.87  4998.5  309.49
  4998.8  308.99  5002.3  308.99  5002.5  309.49  5010.7  310.91  5015.8  311.17
  5051.7  311.60  5095.2  313.63  5108.5  314.84  5164.3  317.73  5225.8  319.44
#Mann=6,-1,0
  3995.4    0.16       0  4177.7    0.05       0  4740.5    0.16       0
  4998.5    0.07       0  5002.5    0.16       0  5095.2    0.05       0
Bank Sta=4998.5,5002.5
Exp/Cntr=0.3,0.1

Type RM Length L Ch R = 1,1430,337,337,337
BEGIN DESCRIPTION:
DUCK CREEK TRIB 9 2 0
END DESCRIPTION:
XS GIS Cut Line= 3
      3547216.46     10397221.28      3546916.43     10396921.25
      3546616.75     10397021.14
#Sta/Elev= 30
  4555.6  317.45  4650.3  313.84  4692.8  312.80  4699.8  312.31  4719.5  311.80
  4770.6  310.43  4813.0  310.12  4876.6  309.14  4883.7  308.68  4904.9  308.21
  4912.0  308.86  4919.0  308.31  4940.3  308.62  4984.8  308.56  4996.6  307.92
  4996.9  307.42  5000.4  307.42  5000.6  307.92  5025.0  309.33  5030.3  309.10
  5056.6  309.89  5079.3  309.50  5088.2  310.28  5119.8  309.87  5151.5  310.47
  5178.6  311.52  5237.5  313.77  5269.1  315.61  5290.2  316.42  5295.8  316.33
#Mann=5,-1,0
  4555.6    0.05       0  4719.5    0.16       0  4996.6    0.07       0
  5000.6    0.16       0  5178.6     0.1       0
Bank Sta=4996.6,5000.6
Exp/Cntr=0.3,0.1

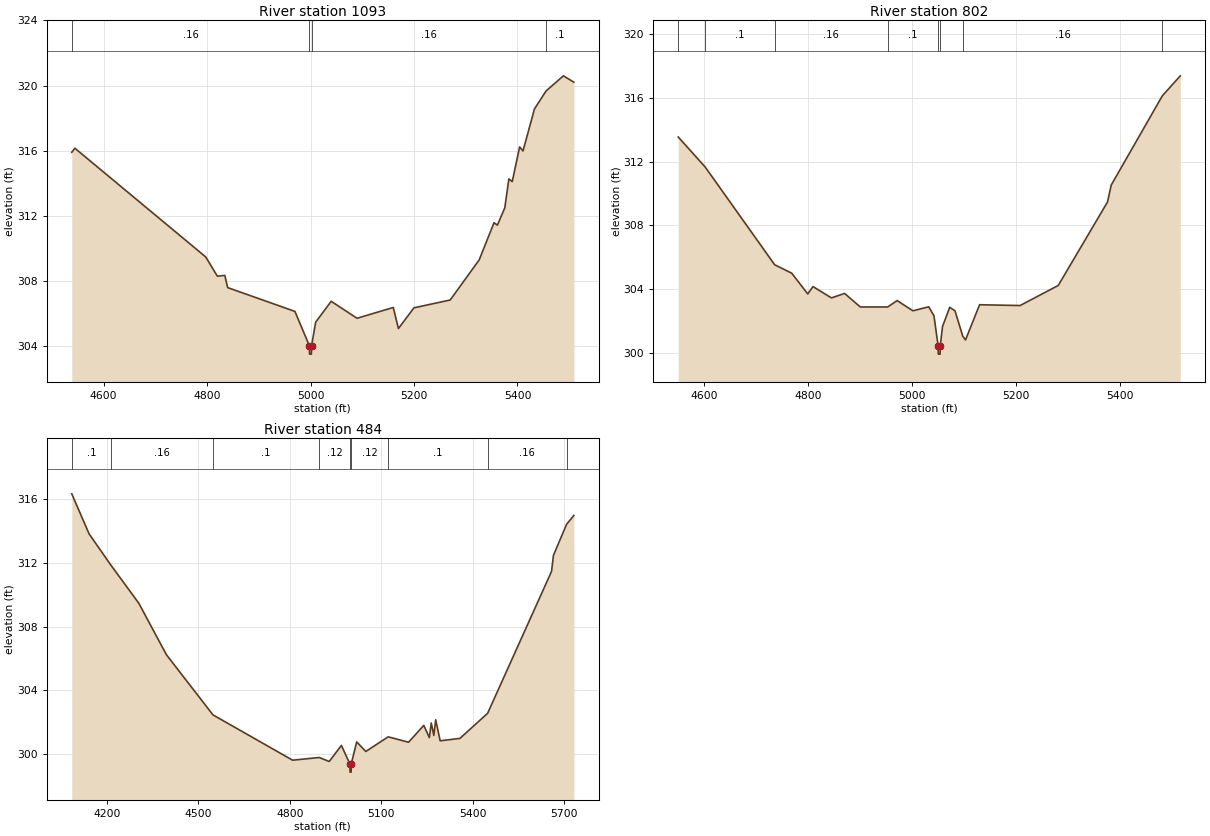
Type RM Length L Ch R = 1,1093,291,291,291
BEGIN DESCRIPTION:
DUCK CREEK TRIB 9 3 0
END DESCRIPTION:
XS GIS Cut Line= 4
      3547403.29     10396748.88      3547137.62     10396618.66
      3546694.91     10396605.64      3546516.18     10396753.29
#Sta/Elev= 30
  4538.4  315.91  4544.4  316.16  4797.4  309.49  4819.9  308.31  4834.3  308.36
  4839.8  307.61  4969.8  306.15  4997.9  304.03  4998.1  303.53  5001.6  303.53
  5001.9  304.03  5009.9  305.49  5039.9  306.77  5089.9  305.73  5159.9  306.39
  5169.9  305.10  5199.9  306.37  5270.0  306.85  5326.0  309.31  5354.7  311.59
  5361.2  311.44  5375.5  312.50  5383.4  314.28  5389.9  314.11  5404.2  316.24
  5410.7  315.99  5432.9  318.57  5455.3  319.67  5488.8  320.60  5509.0  320.21
#Mann=4,-1,0
  4538.4    0.16       0  4997.9    0.07       0  5001.9    0.16       0
  5455.3     0.1       0
Bank Sta=4997.9,5001.9
Exp/Cntr=0.3,0.1

Type RM Length L Ch R = 1,802,318,318,318
BEGIN DESCRIPTION:
DUCK CREEK TRIB 9 9 0
END DESCRIPTION:
XS GIS Cut Line= 4
      3547345.96     10396504.08      3547210.54     10396371.26
      3546767.83     10396308.76      3546489.16     10396480.65
#Sta/Elev= 30
  4550.9  313.54  4602.8  311.65  4736.1  305.52  4768.9  304.99  4799.6  303.69
  4809.7  304.15  4845.1  303.44  4870.3  303.72  4900.6  302.87  4953.2  302.87
  4971.3  303.27  5001.6  302.63  5031.9  302.88  5042.0  302.32  5050.1  300.41
  5050.3  299.91  5053.8  299.91  5054.1  300.41  5058.4  301.64  5072.3  302.85
  5082.4  302.63  5097.3  301.04  5102.6  300.80  5129.6  303.01  5207.4  302.96
  5280.7  304.22  5375.3  309.46  5382.4  310.52  5480.5  316.12  5515.1  317.38
#Mann=8,-1,0
  4550.9    0.05       0  4602.8     0.1       0  4736.1    0.16       0
  4953.2     0.1       0  5050.1    0.07       0  5054.1     0.1       0
  5097.3    0.16       0  5480.5    0.05       0
Bank Sta=5050.1,5054.1
Exp/Cntr=0.3,0.1

Type RM Length L Ch R = 1,484,0,0,0
BEGIN DESCRIPTION:
DUCK CREEK TRIB 9 1 0
END DESCRIPTION:
XS GIS Cut Line= 4
      3547937.10     10396256.68      3547702.73     10396048.34
      3546848.56     10396082.20      3546463.13     10396366.06
#Sta/Elev= 30
  4084.5  316.35  4141.4  313.83  4213.1  311.86  4304.4  309.47  4395.1  306.23
  4547.7  302.45  4809.0  299.60  4896.3  299.77  4929.1  299.52  4969.1  300.53
  4997.2  299.35  4997.4  298.85  5000.9  298.85  5001.2  299.35  5019.2  300.75
  5049.2  300.15  5122.6  301.07  5189.3  300.73  5239.4  301.79  5257.6  301.02
  5263.8  301.94  5272.2  301.16  5278.4  302.14  5293.1  300.82  5357.8  300.97
  5448.8  302.55  5658.4  311.47  5664.8  312.49  5707.7  314.43  5731.6  314.99
#Mann=9,-1,0
  4084.5     0.1       0  4213.1    0.16       0  4547.7     0.1       0
  4896.3    0.12       0  4997.2    0.07       0  5001.2    0.12       0
  5122.6     0.1       0  5448.8    0.16       0  5707.7    0.05       0
Bank Sta=4997.2,5001.2
Exp/Cntr=0.3,0.1

Chan Stop Cuts=-1