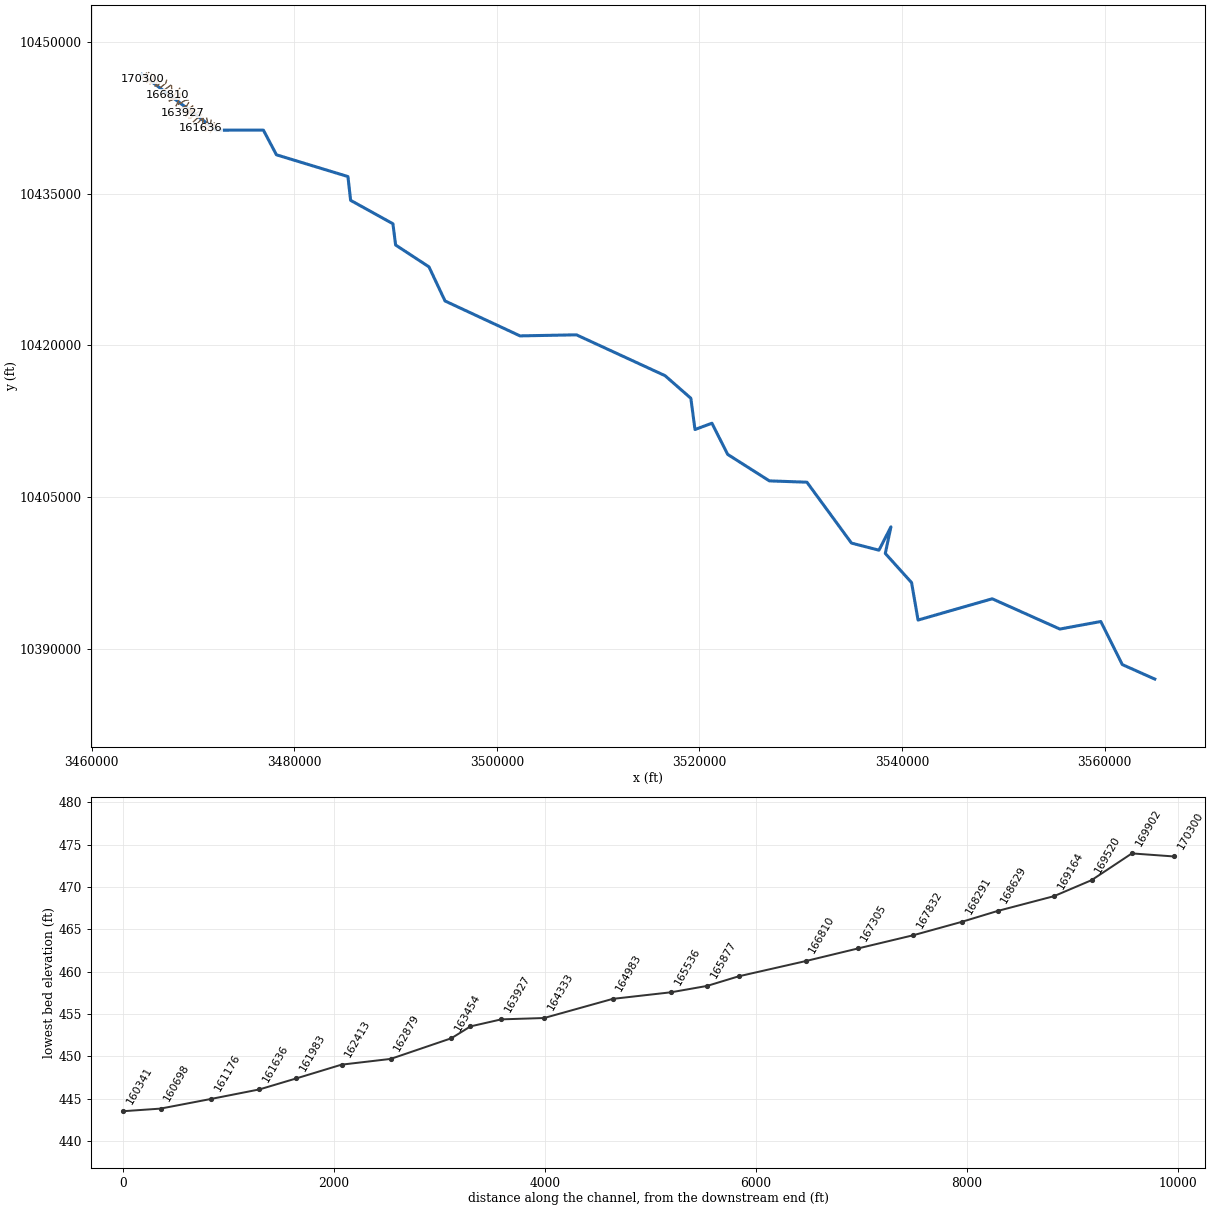
--- DUCK CREEK.prj (project) ---

Proj Title=DUCK CREEK Base Level Engineering
Current Plan=p01
Default Exp/Contr=0.3,0.1
English Units
Geom File=g01
Flow File=f01
Plan File=p01
Y Axis Title=Elevation
X Axis Title(PF)=Main Channel Distance
X Axis Title(XS)=Station
BEGIN DESCRIPTION:
DUCK CREEK
END DESCRIPTION:
DSS Export Rating Curves= 0
DSS Export Rating Curve Sorted= 0
DSS Export Volume Flow Curves= 0
DXF OffsetX= 0
DXF OffsetY= 0
DXF ScaleX= 1
DXF ScaleY= 10

--- DUCK CREEK.p01 (plan) ---

Plan Title=Multiple Run
Short Identifier=Multiple
Geom File=g01
Flow File=f01
Subcritical Flow
K Sum by GR= 0
Std Step Tol= 0.01
Critical Tol= 0.01
Num of Std Step Trials= 20
Max Error Tol= 0.3
Flow Tol Ratio= 0.001
Split Flow NTrial= 30
Split Flow Tol= 0.02
Split Flow Ratio= 0.02
Log Output Level= 0
Friction Slope Method= 1
Unsteady Friction Slope Method= 2
Unsteady Bridges Friction Slope Method= 1
Parabolic Critical Depth
Global Vel Dist=  1 , 1 , 1
Global Log Level= 0
CheckData=True
Encroach Param= -1, 0, 0, 0
BEGIN DESCRIPTION:
Multiple Run
END DESCRIPTION:

--- DUCK CREEK.f01 (steady flow) ---

Flow Title=Multiple
Program Version=4.10
Number of Profiles= 7
Profile Names=10-year,25-year,50-year,1pct_min,100-year,1pct_plu,500-year
River Rch & RM=DUCK CREEK,Reach-1         ,170300
    1234    1729    2144    1939    2622    3546    3914
River Rch & RM=DUCK CREEK,Reach-1         ,166175
    2239    3227    4079    3751    5073    6861    7838
River Rch & RM=DUCK CREEK,Reach-1         ,162879
    2502    3617    4579    4216    5701    7710    8828
River Rch & RM=DUCK CREEK,Reach-1         ,159367
    2884    4195    5332    4927    6663    9011   10394
River Rch & RM=DUCK CREEK,Reach-1         ,158096
    2898    4208    5343    4931    6668    9018   10375
River Rch & RM=DUCK CREEK,Reach-1         ,155599
    3219    4692    5972    5523    7470   10102   11672
River Rch & RM=DUCK CREEK,Reach-1         ,154857
    4146    6104    7824    7282    9848   13318   15583
River Rch & RM=DUCK CREEK,Reach-1         ,154382
    4204    6189    7932    7381    9981   13499   15787
River Rch & RM=DUCK CREEK,Reach-1         ,152082
    4306    6334    8113    7543   10202   13796   16110
River Rch & RM=DUCK CREEK,Reach-1         ,149993
    4373    6428    8230    7647   10341   13985   16311
River Rch & RM=DUCK CREEK,Reach-1         ,147234
    4488    6599    8452    7854   10622   14365   16760
River Rch & RM=DUCK CREEK,Reach-1         ,145629
    4738    6978    8945    8320   11252   15217   17783
River Rch & RM=DUCK CREEK,Reach-1         ,143476
    4677    6873    8796    8167   11045   14937   17396
River Rch & RM=DUCK CREEK,Reach-1         ,139769
    4847    7125    9122    8471   11456   15493   18050
River Rch & RM=DUCK CREEK,Reach-1         ,137867
    5730    8463   10870   10124   13691   18515   21689
River Rch & RM=DUCK CREEK,Reach-1         ,135307
    5792    8552   10981   10223   13825   18697   21886
River Rch & RM=DUCK CREEK,Reach-1         ,134681
    5853    8645   11102   10338   13980   18907   22139
River Rch & RM=DUCK CREEK,Reach-1         ,134257
    5834    8610   11051   10284   13908   18808   21998
River Rch & RM=DUCK CREEK,Reach-1         ,133128
    6150    9085   11669   10864   14692   19870   23262
River Rch & RM=DUCK CREEK,Reach-1         ,131707
    6081    8955   11476   10660   14416   19497   22717
River Rch & RM=DUCK CREEK,Reach-1         ,127226
    6622    9776   12551   11676   15791   21355   24959
River Rch & RM=DUCK CREEK,Reach-1         ,126029
    7325   10816   13889   12919   17472   23629   27605
River Rch & RM=DUCK CREEK,Reach-1         ,120919
    7364   10861   13935   12950   17513   23684   27618
River Rch & RM=DUCK CREEK,Reach-1         ,117636
    7712   11371   14587   13550   18325   24783   28874
River Rch & RM=DUCK CREEK,Reach-1         ,115189
    9327   13808   17764   16543   22373   30257   35422
River Rch & RM=DUCK CREEK,Reach-1         ,113478
    9327   13808   17764   16543   22373   30257   35422
River Rch & RM=DUCK CREEK,Reach-1         ,110983
    9403   13884   17830   16571   22411   30308   35339
River Rch & RM=DUCK CREEK,Reach-1         ,110423
   10343   15425   19946   18671   25251   34149   40391
River Rch & RM=DUCK CREEK,Reach-1         ,108051
   10550   15751   20384   19097   25827   34928   41380
River Rch & RM=DUCK CREEK,Reach-1         ,106077
   10550   15751   20384   19097   25827   34928   41380
River Rch & RM=DUCK CREEK,Reach-1         ,105445
   10902   16267   21042   19703   26646   36036   42643
River Rch & RM=DUCK CREEK,Reach-1         ,104860
   10902   16267   21042   19703   26646   36036   42643
River Rch & RM=DUCK CREEK,Reach-1         ,102078
   11315   16902   21882   20505   27731   37503   44447
River Rch & RM=DUCK CREEK,Reach-1         ,100946
   11176   16662   21542   20158   27261   36867   43568
River Rch & RM=DUCK CREEK,Reach-1         ,99909
   11176   16662   21542   20158   27261   36867   43568
River Rch & RM=DUCK CREEK,Reach-1         ,99151
   11238   16755   21664   20272   27416   37077   43818
River Rch & RM=DUCK CREEK,Reach-1         ,98068
   11431   17021   21987   20555   27798   37593   44337
River Rch & RM=DUCK CREEK,Reach-1         ,97595
   11431   17021   21987   20555   27798   37593   44337
River Rch & RM=DUCK CREEK,Reach-1         ,92840
   11431   17021   21987   20555   27798   37593   44337
River Rch & RM=DUCK CREEK,Reach-1         ,91013
   11895   17737   22935   21463   29026   39254   46386
River Rch & RM=DUCK CREEK,Reach-1         ,88989
   11895   17737   22935   21463   29026   39254   46386
River Rch & RM=DUCK CREEK,Reach-1         ,85966
   12111   18038   23306   21789   29467   39850   47000
River Rch & RM=DUCK CREEK,Reach-1         ,82243
   12462   18578   24021   22473   30392   41101   48541
River Rch & RM=DUCK CREEK,Reach-1         ,79917
   12981   19317   24947   23307   31521   42628   50202
River Rch & RM=DUCK CREEK,Reach-1         ,77166
   12981   19317   24947   23307   31521   42628   50202
River Rch & RM=DUCK CREEK,Reach-1         ,72389
   12981   19317   24947   23307   31521   42628   50202
River Rch & RM=DUCK CREEK,Reach-1         ,70465
   12981   19317   24947   23307   31521   42628   50202
River Rch & RM=DUCK CREEK,Reach-1         ,69848
   12981   19317   24947   23307   31521   42628   50202
River Rch & RM=DUCK CREEK,Reach-1         ,67911
   12913   19186   24750   23097   31236   42243   49633
River Rch & RM=DUCK CREEK,Reach-1         ,65905
   12913   19186   24750   23097   31236   42243   49633
River Rch & RM=DUCK CREEK,Reach-1         ,61122
   18871   28258   36663   34396   46517   62909   74664
River Rch & RM=DUCK CREEK,Reach-1         ,55486
   19208   28776   37346   35047   47398   64100   76120
River Rch & RM=DUCK CREEK,Reach-1         ,54805
   19095   28581   37072   34769   47020   63590   75421
River Rch & RM=DUCK CREEK,Reach-1         ,49319
   18934   28299   36669   34355   46461   62833   74368
River Rch & RM=DUCK CREEK,Reach-1         ,41920
   18979   28359   36740   34415   46542   62943   74466
River Rch & RM=DUCK CREEK,Reach-1         ,40007
   19522   29186   37827   35448   47939   64832   76760
River Rch & RM=DUCK CREEK,Reach-1         ,39611
   19522   29186   37827   35448   47939   64832   76760
River Rch & RM=DUCK CREEK,Reach-1         ,38064
   19278   28778   37260   34878   47169   63790   75363
River Rch & RM=DUCK CREEK,Reach-1         ,34974
   19593   29244   37860   35436   47923   64810   76547
River Rch & RM=DUCK CREEK,Reach-1         ,29885
   19593   29244   37860   35436   47923   64810   76547
River Rch & RM=DUCK CREEK,Reach-1         ,24724
   19263   28689   37086   34657   46870   63386   74633
River Rch & RM=DUCK CREEK,Reach-1         ,18030
   19630   29230   37781   35302   47742   64565   75996
River Rch & RM=DUCK CREEK,Reach-1         ,13596
   19630   29230   37781   35302   47742   64565   75996
Boundary for River Rch & Prof#=DUCK CREEK,Reach-1         , 1
Up Type= 0
Dn Type= 3
Dn Slope=0.001
Boundary for River Rch & Prof#=DUCK CREEK,Reach-1         , 2
Up Type= 0
Dn Type= 3
Dn Slope=0.001
Boundary for River Rch & Prof#=DUCK CREEK,Reach-1         , 3
Up Type= 0
Dn Type= 3
Dn Slope=0.001
Boundary for River Rch & Prof#=DUCK CREEK,Reach-1         , 4
Up Type= 0
Dn Type= 3
Dn Slope=0.001
Boundary for River Rch & Prof#=DUCK CREEK,Reach-1         , 5
Up Type= 0
Dn Type= 3
Dn Slope=0.001
Boundary for River Rch & Prof#=DUCK CREEK,Reach-1         , 6
Up Type= 0
Dn Type= 3
Dn Slope=0.001
Boundary for River Rch & Prof#=DUCK CREEK,Reach-1         , 7
Up Type= 0
Dn Type= 3
Dn Slope=0.001
DSS Import GetInterval= 0
DSS Import GetPeak= 0
DSS Import FillOption= 0

--- DUCK CREEK.g01 (geometry) ---

Geom Title=Existing Conditions
Program Version=4.10

River Reach=DUCK CREEK      ,Reach-1
Reach XY= 30
      3464972.11     10446781.64      3472309.51     10441267.05
      3476962.11     10441271.64      3478248.93     10438835.36
      3485308.66     10436683.59      3485572.54     10434331.58
      3489749.29     10432018.48      3490014.47     10429918.46
      3493306.14     10427758.96      3494895.84      10424384.5
      3502297.41     10420935.66       3507866.3      10421039.7
      3516613.48     10417002.87      3519159.74      10414770.7
      3519568.33     10411679.79      3521240.09     10412305.14
      3522795.37     10409222.05      3526912.91     10406603.59
      3530618.09     10406472.92      3535016.77     10400454.66
       3537730.8     10399753.66      3538912.66     10402062.07
      3538354.83     10399432.78        3540949.     10396551.14
      3541589.38     10392846.99      3548909.78     10394952.42
      3555587.23     10391959.13       3559629.6     10392704.52
      3561750.27     10388447.91       3564957.6     10387016.61

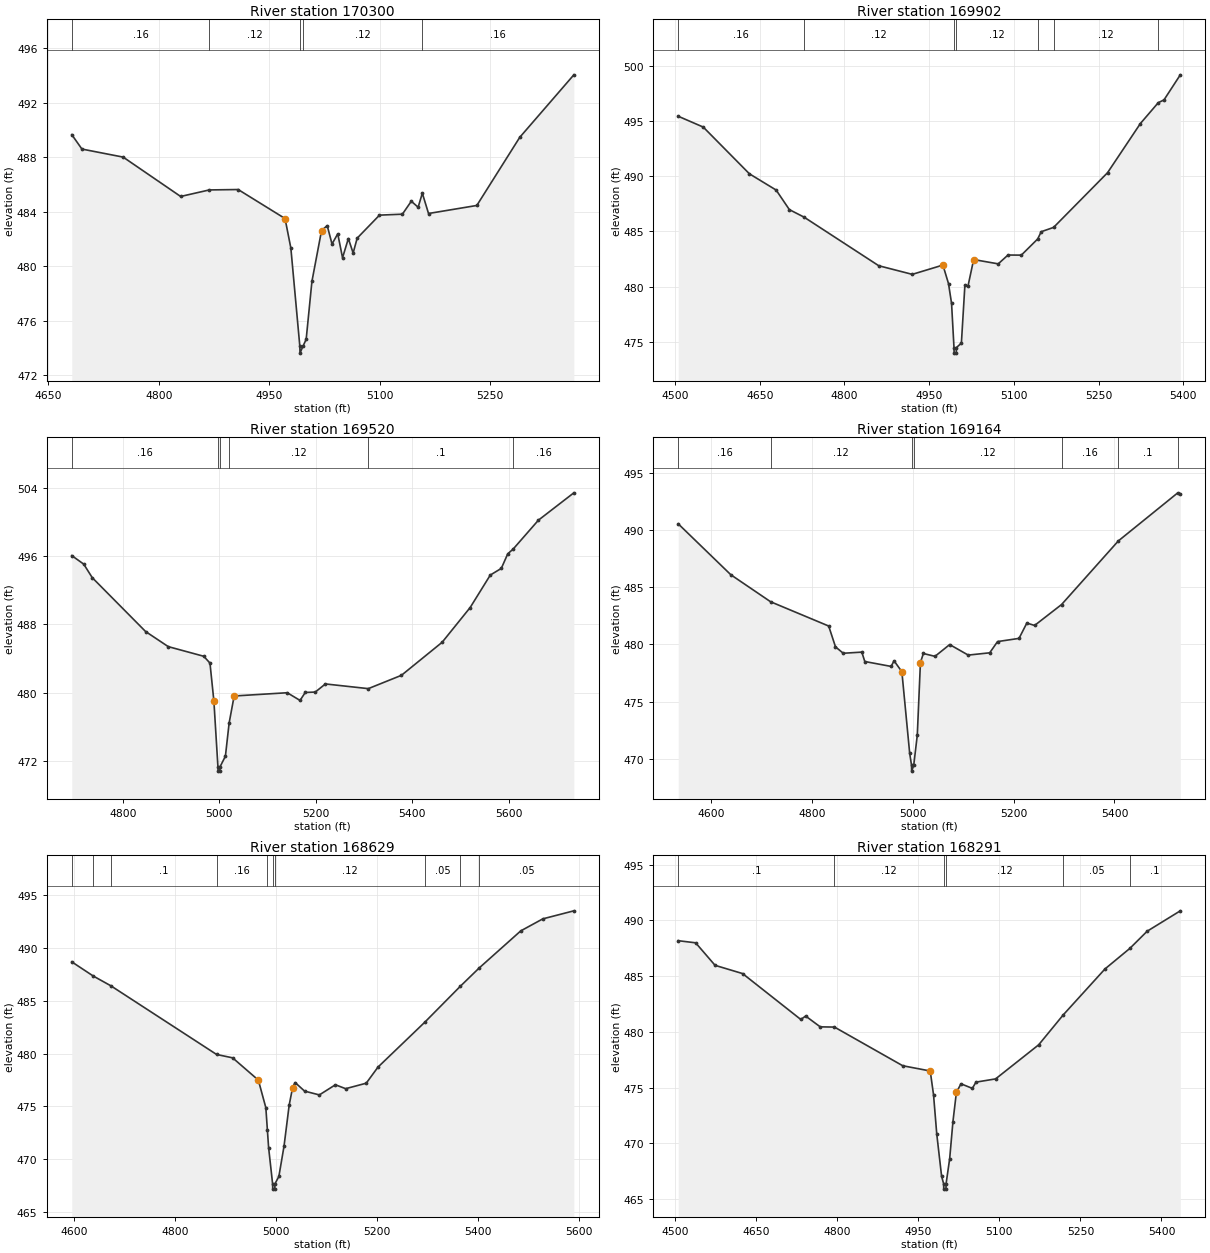
Type RM Length L Ch R = 1 ,170300  ,398,398,398
BEGIN DESCRIPTION:
DUCK CREEK 18 0
END DESCRIPTION:
XS GIS Cut Line= 3
      3465420.05     10446912.29      3465170.06      10446612.3
      3465020.08     10446362.34
#Sta/Elev= 30
  4681.7  489.65  4695.5  488.59  4751.5     488  4829.6  485.11  4868.5  485.59
  4907.7  485.62  4971.4  483.49  4979.3  481.32  4991.5  474.11  4991.7  473.61
  4995.7  474.11  5000.1  474.62  5007.9  478.87    5021  482.61  5028.7  482.97
  5035.2  481.62    5043  482.37  5049.5  480.61  5057.4  482.02  5063.9  480.96
  5069.4  482.05  5099.7  483.74  5130.8  483.81  5142.9  484.76  5152.2  484.32
  5157.9  485.35  5166.3  483.86  5231.9  484.45  5290.2  489.45  5363.7  494.04
#Mann= 5 ,-1 , 0
  4681.7     .16       0  4868.5     .12       0  4991.5     .07       0
  4995.7     .12       0  5157.9     .16       0
Bank Sta=4971.4,5021
XS Rating Curve= 0 ,0
Exp/Cntr=0.3,0.1

Type RM Length L Ch R = 1 ,169902  ,382,382,382
BEGIN DESCRIPTION:
DUCK CREEK 17 0
END DESCRIPTION:
XS GIS Cut Line= 2
      3465646.55      10446952.6      3465297.82     10446135.18
#Sta/Elev= 30
  4505.8  495.41  4550.1  494.43  4631.8   490.2  4679.1  488.73  4702.5  486.96
  4728.5  486.28  4860.7  481.88    4920   481.1  4974.3  481.94  4984.2  480.26
  4989.6  478.47  4993.9  474.47  4994.2  473.97  4997.9  473.97  4998.2  474.47
    5007  474.88  5013.2  480.11  5018.7  480.04  5028.7  482.44  5072.2  482.05
  5089.5  482.85  5113.1  482.84    5142   484.3  5148.3  484.96  5170.2  485.35
  5265.7   490.3  5323.8  494.75  5355.5  496.64  5365.6  496.89  5394.5  499.16
#Mann= 7 ,-1 , 0
  4505.8     .16       0  4728.5     .12       0  4993.9     .07       0
  4998.2     .12       0    5142      .1       0  5170.2     .12       0
  5355.5     .16       0
Bank Sta=4974.3,5028.7
XS Rating Curve= 0 ,0
Exp/Cntr=0.3,0.1

Type RM Length L Ch R = 1 ,169520  ,356,356,356
BEGIN DESCRIPTION:
DUCK CREEK 168 0
END DESCRIPTION:
XS GIS Cut Line= 3
      3465914.17     10446842.03       3465689.8     10446146.47
        3465443.     10445958.97
#Sta/Elev= 30
  4694.2  496.05    4719  495.05  4736.6  493.47  4847.2  487.16  4894.2  485.39
  4967.8  484.26  4980.7  483.46  4988.8  479.02  4997.2  471.31  4997.5  470.81
  5001.2  470.81  5001.5  471.31  5012.7  472.56  5020.4  476.44  5030.8  479.61
  5140.9  479.99  5167.4  479.09  5178.2  480.02    5199  480.07    5220  481.02
  5308.9  480.47  5377.6  482.03    5462   485.9  5520.1  489.97  5561.8  493.77
  5584.6  494.55    5598  496.26  5609.3  496.82  5661.6   500.2    5735   503.4
#Mann= 6 ,-1 , 0
  4694.2     .16       0  4997.2     .07       0  5001.5     .16       0
  5020.4     .12       0  5308.9      .1       0  5609.3     .16       0
Bank Sta=4988.8,5030.8
XS Rating Curve= 0 ,0
Exp/Cntr=0.3,0.1

Type RM Length L Ch R = 1 ,169164  ,535,535,535
BEGIN DESCRIPTION:
DUCK CREEK 167 0
END DESCRIPTION:
XS GIS Cut Line= 3
      3466149.74     10446745.79      3466135.32      10446473.4
      3465758.78     10445856.51
#Sta/Elev= 30
    4535  490.53  4639.3  486.08  4718.2  483.72  4833.3   481.6  4846.8  479.78
  4862.2  479.22    4899  479.32  4904.9   478.5  4957.1  478.07  4962.9  478.56
  4978.4  477.61  4993.9  470.48  4997.6  469.42  4997.8  468.92  5001.9  469.42
    5009  472.07  5015.2   478.4    5021   479.2  5044.1  478.95  5073.2  479.98
    5110  479.06  5152.6  479.26  5168.1  480.24  5210.7  480.52  5226.2  481.86
  5241.6  481.65  5295.1  483.48  5407.7  489.04  5525.5  493.24  5530.5  493.16
#Mann= 7 ,-1 , 0
    4535     .16       0  4718.2     .12       0  4997.6     .07       0
  5001.9     .12       0  5295.1     .16       0  5407.7      .1       0
  5525.5     .16       0
Bank Sta=4978.4,5015.2
XS Rating Curve= 0 ,0
Exp/Cntr=0.3,0.1

Type RM Length L Ch R = 1 ,168629  ,338,338,338
BEGIN DESCRIPTION:
DUCK CREEK 166 0
END DESCRIPTION:
XS GIS Cut Line= 3
      3466556.79     10446564.76       3466436.6      10445914.1
      3466277.94     10445622.43
#Sta/Elev= 30
  4595.6  488.69    4638  487.35    4673  486.42  4882.2  479.92    4914   479.6
  4964.9  477.49  4979.7  474.88  4982.7  472.81  4985.2  471.09  4993.1  467.67
  4993.4  467.17  4997.4  467.17  4997.7  467.67  5005.5  468.37  5015.7  471.24
  5025.9  475.13  5032.6  476.77  5037.7  477.26  5056.4  476.45  5085.6  476.09
  5117.4  477.05  5137.7  476.68  5178.4   477.2  5201.6  478.72  5294.2  482.97
  5364.9  486.39  5402.2  488.12  5484.2  491.62  5527.9  492.76  5589.3  493.52
#Mann= 10 ,-1 , 0
  4595.6      .1       0    4638     .16       0    4673      .1       0
  4882.2     .16       0  4982.7     .12       0  4993.1     .07       0
  4997.7     .12       0  5294.2     .05       0  5364.9      .1       0
  5402.2     .05       0
Bank Sta=4964.9,5032.6
XS Rating Curve= 0 ,0
Exp/Cntr=0.3,0.1

Type RM Length L Ch R = 1 ,168291  ,459,459,459
BEGIN DESCRIPTION:
DUCK CREEK 165 0
END DESCRIPTION:
XS GIS Cut Line= 2
      3467032.75     10446386.86      3466510.34     10445619.26
#Sta/Elev= 30
  4506.3  488.18  4538.5  487.99  4574.4  485.97  4625.3  485.23    4733  481.11
  4741.9  481.42  4768.9  480.45  4795.2  480.43  4921.5  476.96  4972.3  476.49
  4978.4  474.37  4984.4  470.83  4993.3  467.06    4997  466.39  4997.4  465.89
  5001.4  465.89  5001.7  466.39  5008.3  468.63  5014.3  471.94  5020.7  474.57
  5029.2  475.34  5050.2  474.93  5056.9  475.49  5093.2  475.78  5172.9  478.84
  5218.6  481.54  5295.6  485.65  5341.5  487.49  5373.5  489.03  5434.8  490.86
#Mann= 6 ,-1 , 0
  4506.3      .1       0  4795.2     .12       0    4997     .07       0
  5001.7     .12       0  5218.6     .05       0  5341.5      .1       0
Bank Sta=4972.3,5020.7
XS Rating Curve= 0 ,0
Exp/Cntr=0.3,0.1

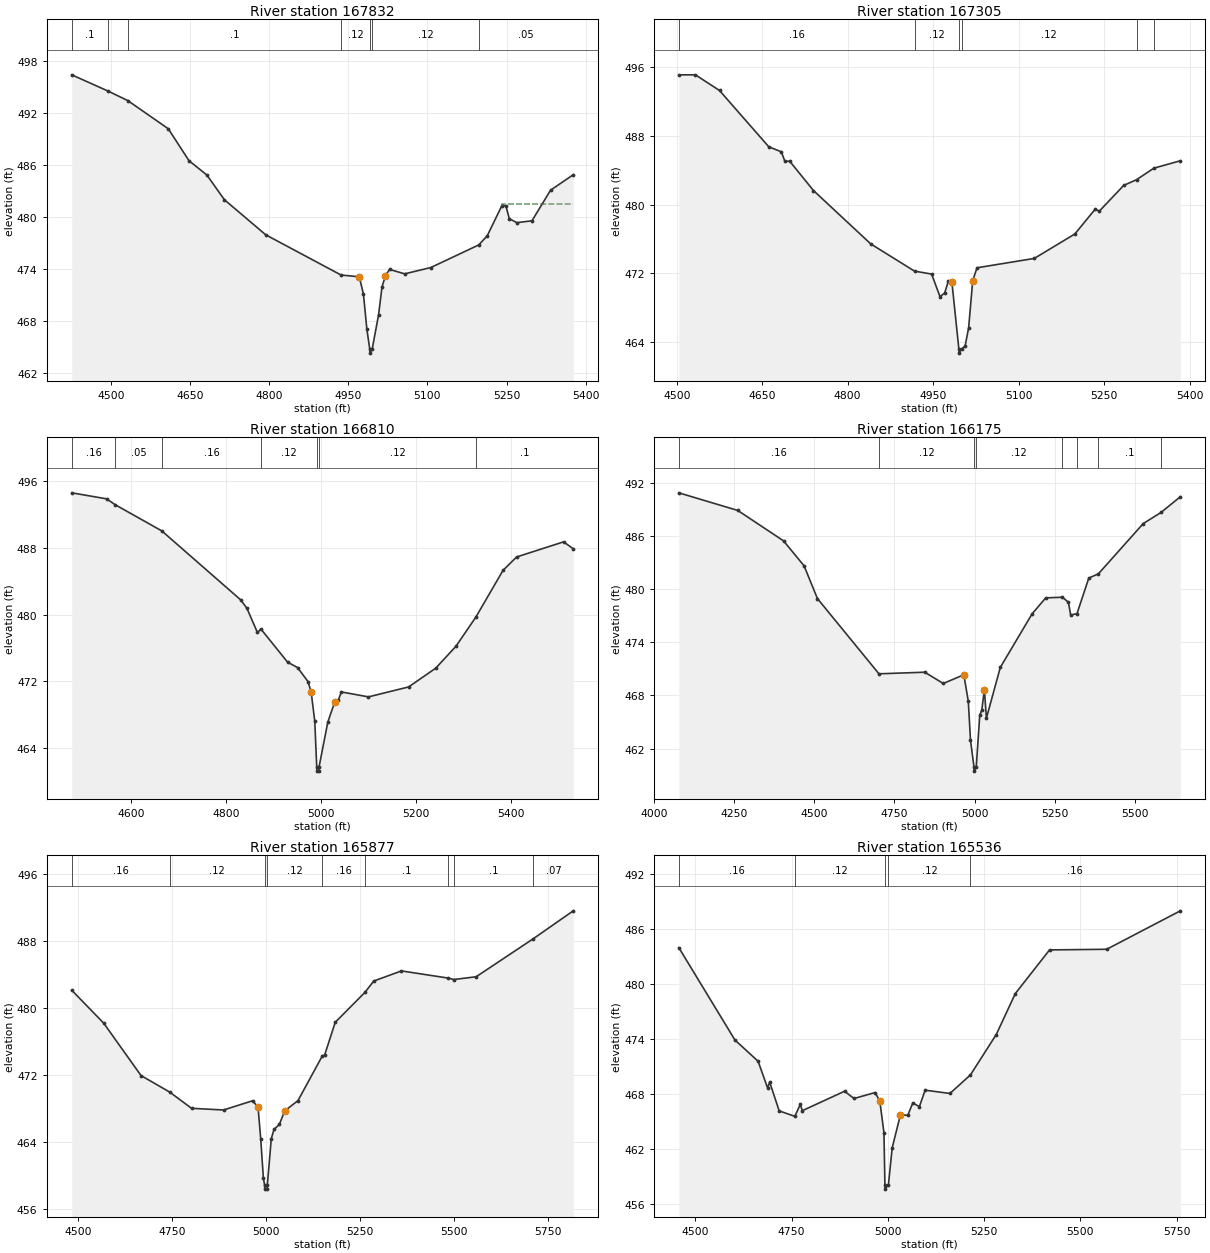
Type RM Length L Ch R = 1 ,167832  ,527,527,527
BEGIN DESCRIPTION:
DUCK CREEK 164 0
END DESCRIPTION:
XS GIS Cut Line= 3
      3467406.15     10446194.52      3467327.63      10445915.7
      3466817.26     10445496.53
#Sta/Elev= 30
  4426.2  496.46  4494.8  494.59  4532.2  493.49  4609.1  490.23  4648.3  486.54
  4682.3  484.88  4715.4  482.03  4793.7  477.98  4936.5  473.33  4970.9  473.13
  4978.8  471.13  4985.3  467.08  4990.7  464.81  4991.1  464.31  4995.5  464.81
  5007.5  468.74    5014  471.96  5020.6  473.27  5028.3  473.98    5057  473.47
  5106.5   474.2  5197.3  476.81  5213.4  477.87  5240.7   481.3  5248.6  481.34
  5255.1  479.85  5269.4  479.38  5298.1   479.6  5333.3  483.13  5376.3  484.92
#Mann= 7 ,-1 , 0
  4426.2      .1       0  4494.8     .05       0  4532.2      .1       0
  4936.5     .12       0  4990.7     .07       0  4995.5     .12       0
  5197.3     .05       0
#XS Ineff= 2 , 0
                         5240.84          481.49
Permanent Ineff=
       F       F
Bank Sta=4970.9,5020.6
XS Rating Curve= 0 ,0
Exp/Cntr=0.3,0.1

Type RM Length L Ch R = 1 ,167305  ,495,495,495
BEGIN DESCRIPTION:
DUCK CREEK 163 0
END DESCRIPTION:
XS GIS Cut Line= 2
      3467809.99     10445704.15      3467096.97     10445188.22
#Sta/Elev= 30
  4503.7  495.09  4532.8  495.09  4575.1  493.27  4661.5  486.73  4683.6  486.14
  4689.8  485.04  4698.3  485.05    4740  481.64  4840.6  475.43  4917.4  472.27
  4947.3  471.93    4962  469.31  4970.1  469.71  4976.7   471.1  4982.9  471.01
  4995.1  463.24  4995.5  462.74    5000  463.24  5006.1  463.56  5012.3   465.7
  5019.5  471.18    5027  472.66  5127.5  473.75  5198.7  476.59  5234.2  479.46
  5241.7  479.25  5284.5  482.24    5307   482.9  5337.3  484.24  5383.8   485.1
#Mann= 6 ,-1 , 0
  4503.7     .16       0  4917.4     .12       0  4995.1     .07       0
    5000     .12       0    5307     .16       0  5337.3     .12       0
Bank Sta=4982.9,5019.5
XS Rating Curve= 0 ,0
Exp/Cntr=0.3,0.1

Type RM Length L Ch R = 1 ,166810  ,635,635,635
BEGIN DESCRIPTION:
DUCK CREEK 162 0
END DESCRIPTION:
XS GIS Cut Line= 3
      3467894.94     10445644.91      3467915.77     10445295.51
      3467459.57     10444756.07
#Sta/Elev= 30
  4474.5  494.57  4547.9  493.85  4566.2  493.14  4664.3  490.01  4830.3  481.76
  4843.6  480.74  4865.6  477.85  4873.2  478.25  4929.3  474.29  4950.2  473.65
  4972.2  471.97  4978.8  470.74  4986.5   467.2  4990.6  461.75  4990.9  461.25
  4995.1  461.25  4995.5  461.75  5013.9  467.11  5028.2  469.47  5035.9  469.72
  5042.5  470.73  5099.6  470.14  5184.2  471.33  5241.4  473.58  5284.2  476.22
    5326  479.71  5383.1  485.29  5411.7  486.89  5510.6   488.7    5531  487.87
#Mann= 7 ,-1 , 0
  4474.5     .16       0  4566.2     .05       0  4664.3     .16       0
  4873.2     .12       0  4990.6     .07       0  4995.5     .12       0
    5326      .1       0
Bank Sta=4978.8,5028.2
XS Rating Curve= 0 ,0
Exp/Cntr=0.3,0.1

Type RM Length L Ch R = 1 ,166175  ,298,298,298
BEGIN DESCRIPTION:
DUCK CREEK 160 0
END DESCRIPTION:
XS GIS Cut Line= 3
      3468702.66     10445409.32      3468003.91     10444527.88
      3467699.41     10444210.55
#Sta/Elev= 30
  4077.4  490.85  4261.4  488.86  4404.1  485.43  4468.2  482.61  4509.8  478.92
  4701.7  470.43  4844.7  470.61  4902.4  469.34  4966.5  470.32  4980.5  467.33
  4987.3  462.95  4998.1  459.95  4998.6  459.45  5005.4  459.95  5016.2  465.76
  5022.6  466.33  5030.6  468.65    5037  465.42  5080.3  471.15  5179.6   477.2
  5222.1     479  5274.2  479.07  5292.9   478.5  5299.8  477.07  5319.5  477.21
  5356.4  481.23  5386.6  481.72  5526.2  487.38  5581.9  488.64    5642  490.41
#Mann= 8 ,-1 , 0
  4077.4     .16       0  4701.7     .12       0  4998.1     .07       0
  5005.4     .12       0  5274.2      .1       0  5319.5     .12       0
  5386.6      .1       0  5581.9     .07       0
Bank Sta=4966.5,5030.6
XS Rating Curve= 0 ,0
Exp/Cntr=0.3,0.1

Type RM Length L Ch R = 1 ,165877  ,341,341,341
BEGIN DESCRIPTION:
DUCK CREEK 16 0
END DESCRIPTION:
XS GIS Cut Line= 3
      3468734.68     10444909.28      3468229.87     10444367.62
      3467677.03     10444152.89
#Sta/Elev= 30
  4482.8  482.12  4567.8  478.18    4667  471.91    4743  469.94  4801.4  467.99
  4886.4  467.79  4964.1   468.9  4978.2  468.11  4985.3  464.33  4992.4  459.61
  4995.6  458.82  4996.1  458.32  5002.4  458.32  5002.9  458.82  5013.4  464.36
  5020.7  465.47  5034.9  466.06  5049.1  467.69  5084.2   468.9  5149.5  474.29
  5155.1  474.34  5183.4  478.28  5262.1  481.85  5285.9  483.22  5359.5  484.43
  5484.1  483.57  5498.6   483.4  5558.1  483.73  5710.3  488.29  5816.3  491.62
#Mann= 9 ,-1 , 0
  4482.8     .16       0    4743     .12       0  4995.6     .07       0
  5002.9     .12       0  5149.5     .16       0  5262.1      .1       0
  5484.1     .16       0  5498.6      .1       0  5710.3     .07       0
Bank Sta=4978.2,5049.1
XS Rating Curve= 0 ,0
Exp/Cntr=0.3,0.1

Type RM Length L Ch R = 1 ,165536  ,553,553,553
BEGIN DESCRIPTION:
DUCK CREEK 159 0
END DESCRIPTION:
XS GIS Cut Line= 3
      3468840.46     10444869.23      3468510.32     10444005.44
      3468338.87     10443668.93
#Sta/Elev= 30
  4457.1  483.95  4602.8  473.86  4662.9  471.54  4687.6  468.63    4693  469.26
  4717.7  466.12  4758.4  465.52  4772.5  466.83  4777.8  466.14  4887.4  468.26
  4912.1  467.47  4966.9  468.12  4979.1  467.18  4989.8  463.73  4992.3  458.07
  4992.8  457.57  5001.5  458.07  5011.2  462.09  5032.6  465.68  5051.7  465.64
  5064.7  466.98  5081.8  466.58  5096.8  468.38  5161.1  468.02  5214.3  470.04
  5281.5  474.46  5330.9  478.93  5419.8   483.7  5568.2  483.77  5759.5  487.97
#Mann= 5 ,-1 , 0
  4457.1     .16       0  4758.4     .12       0  4992.3     .07       0
  5001.5     .12       0  5214.3     .16       0
Bank Sta=4979.1,5032.6
XS Rating Curve= 0 ,0
Exp/Cntr=0.3,0.1

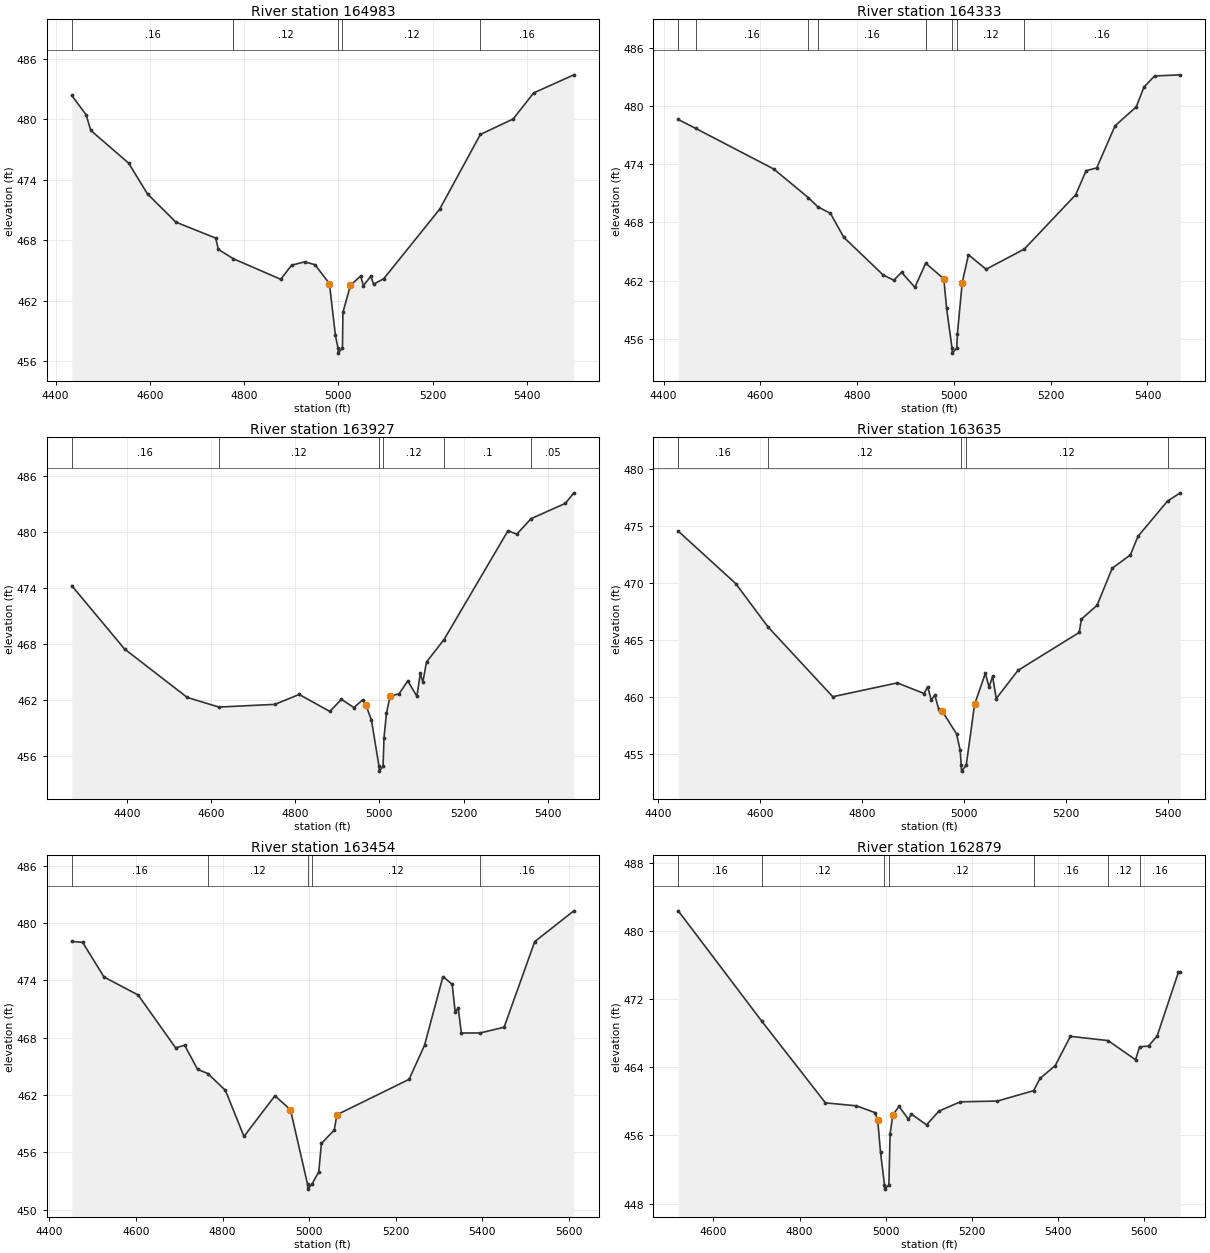
Type RM Length L Ch R = 1 ,164983  ,650,650,650
BEGIN DESCRIPTION:
DUCK CREEK 157 0
END DESCRIPTION:
XS GIS Cut Line= 3
      3469542.37     10444247.42      3469273.15     10444226.59
      3468580.22     10443836.12
#Sta/Elev= 30
  4434.2  482.36  4464.6  480.45  4474.6  478.89  4554.8  475.65  4594.9  472.59
  4655.1  469.79  4739.5  468.21  4745.2  467.09  4776.9  466.16  4877.6  464.12
  4900.6  465.51  4928.7  465.85  4950.4  465.56  4980.9   463.7  4993.7  458.54
  4999.1  457.29  4999.6  456.79  5008.6  457.29  5009.6  460.84  5025.6  463.52
  5047.2  464.44    5053  463.48  5068.9  464.44  5074.6  463.63  5096.3  464.18
  5214.8  471.07  5301.2  478.49  5370.9  480.03  5414.2  482.61  5499.6  484.41
#Mann= 5 ,-1 , 0
  4434.2     .16       0  4776.9     .12       0  4999.1     .07       0
  5008.6     .12       0  5301.2     .16       0
Bank Sta=4980.9,5025.6
XS Rating Curve= 0 ,0
Exp/Cntr=0.3,0.1

Type RM Length L Ch R = 1 ,164333  ,406,406,406
BEGIN DESCRIPTION:
DUCK CREEK 156 0
END DESCRIPTION:
XS GIS Cut Line= 3
      3469580.87     10443981.44       3469431.8      10443729.8
      3468777.97     10443372.43
#Sta/Elev= 30
  4430.3  478.59  4466.1  477.68  4627.7  473.49  4699.2  470.54  4719.1  469.59
  4744.9  468.92  4772.4  466.46    4854  462.57  4875.8  462.04  4891.9  462.85
  4919.4  461.31  4941.7  463.79  4979.2  462.18  4984.9  459.14  4996.2  455.03
  4996.7  454.53  5005.8  455.03  5007.3  456.55  5017.2   461.8  5030.1  464.66
  5066.5  463.17  5145.4  465.24  5251.5  470.83  5273.3  473.32  5295.1   473.6
  5333.1  477.95  5376.7  479.88  5392.8  481.93  5414.7  483.07  5467.9  483.19
#Mann= 8 ,-1 , 0
  4430.3      .1       0  4466.1     .16       0  4699.2     .12       0
  4719.1     .16       0  4941.7     .12       0  4996.2     .07       0
  5005.8     .12       0  5145.4     .16       0
Bank Sta=4979.2,5017.2
XS Rating Curve= 0 ,0
Exp/Cntr=0.3,0.1

Type RM Length L Ch R = 1 ,163927  ,292,292,292
BEGIN DESCRIPTION:
DUCK CREEK 153 1
END DESCRIPTION:
XS GIS Cut Line= 2
      3469986.32      10443660.9       3469005.5     10442979.29
#Sta/Elev= 30
  4268.1  474.23  4393.6  467.45  4542.8  462.26  4618.1  461.23  4751.5  461.52
    4809  462.58  4882.1  460.76  4909.5  462.06  4939.2  461.18  4960.1     462
  4967.4   461.5  4981.1  459.83    4999  454.87  4999.5  454.37  5008.7  454.87
  5010.8  457.91  5016.8   460.6  5025.6  462.42  5046.5  462.64  5067.5  464.03
  5089.1  462.38  5097.2  464.84  5103.3   463.9    5112  466.06  5153.4  468.44
  5305.8  480.11  5326.8  479.74  5360.6   481.4  5442.3  483.04  5462.5  484.17
#Mann= 6 ,-1 , 0
  4268.1     .16       0  4618.1     .12       0    4999     .07       0
  5008.7     .12       0  5153.4      .1       0  5360.6     .05       0
Bank Sta=4967.4,5025.6
XS Rating Curve= 0 ,0
Exp/Cntr=0.3,0.1

Type RM Length L Ch R = 1 ,163635  ,181,181,181
BEGIN DESCRIPTION:
DUCK CREEK 155 0
END DESCRIPTION:
XS GIS Cut Line= 4
      3470120.55     10443352.75      3469701.67     10443162.84
      3469465.12     10442930.64      3469307.75     10442819.93
#Sta/Elev= 30
  4440.2  474.54  4552.8  469.95  4616.3  466.15    4743  460.05  4869.4  461.26
  4921.9  460.33  4928.9  460.93    4936  459.75    4943   460.2  4950.2  459.01
  4957.2  458.81  4985.5   456.8  4992.6  455.38  4994.8  454.04  4995.3  453.54
  5004.5  454.04  5020.9  459.38    5042   462.1  5049.2   460.9  5056.2  461.83
  5063.3  459.89  5105.8  462.35  5225.9  465.67  5230.2  466.84  5260.9  468.05
  5290.5  471.29  5326.2  472.46    5341  474.08  5398.9  477.17    5424  477.89
#Mann= 5 ,-1 , 0
  4440.2     .16       0  4616.3     .12       0  4994.8     .07       0
  5004.5     .12       0  5398.9     .16       0
Bank Sta=4957.2,5020.9
XS Rating Curve= 0 ,0
Exp/Cntr=0.3,0.1

Type RM Length L Ch R = 1 ,163454  ,575,575,575
BEGIN DESCRIPTION:
DUCK CREEK 154 0
END DESCRIPTION:
XS GIS Cut Line= 3
       3470233.1     10443324.35      3469537.57     10442838.77
      3469319.91      10442616.3
#Sta/Elev= 30
  4451.8  478.09    4477  477.98  4526.2  474.36  4605.2  472.47  4691.6  466.94
  4712.5  467.21  4742.2  464.69    4766  464.25  4806.7  462.48  4849.5  457.66
    4921  461.92  4956.8  460.46  4996.4  452.64  4996.9  452.14  5006.2  452.64
  5022.2  453.95  5028.3  456.92    5058  458.33  5064.1  459.93  5230.7  463.64
  5266.4   467.2    5309  474.41  5330.2   473.6  5337.3  470.71  5344.3  471.09
  5351.5  468.49  5395.2   468.5  5450.3   469.1    5521  478.07  5611.3  481.29
#Mann= 5 ,-1 , 0
  4451.8     .16       0    4766     .12       0  4996.4     .07       0
  5006.2     .12       0  5395.2     .16       0
#XS Ineff= 2 , 0
                         5311.76          474.24
Permanent Ineff=
       F       F
Bank Sta=4956.8,5064.1
XS Rating Curve= 0 ,0
Exp/Cntr=0.3,0.1

Type RM Length L Ch R = 1 ,162879  ,466,466,466
BEGIN DESCRIPTION:
DUCK CREEK 152 1
END DESCRIPTION:
XS GIS Cut Line= 3
      3470555.23       10443100.      3469845.27     10442518.25
      3469598.45     10442502.22
#Sta/Elev= 30
  4518.2  482.34  4711.9  469.41  4859.8  459.82  4931.6  459.47  4974.7  458.68
  4981.1  457.78  4987.7     454  4996.8   450.2  4997.3   449.7  5007.1   450.2
  5009.8  456.14  5016.3  458.41  5030.6  459.41  5052.3   457.9  5059.4   458.5
  5094.5  457.24  5123.2  458.85  5172.8  459.94  5258.9  460.03  5342.9  461.25
  5357.9  462.69  5393.1  464.19  5428.3  467.62  5515.9  467.12  5579.5  464.87
  5588.9  466.39  5609.6  466.48  5629.6  467.66  5679.1  475.15  5683.4  475.15
#Mann= 7 ,-1 , 0
  4518.2     .16       0  4711.9     .12       0  4996.8     .07       0
  5007.1     .12       0  5342.9     .16       0  5515.9     .12       0
  5588.9     .16       0
Bank Sta=4981.1,5016.3
XS Rating Curve= 0 ,0
Exp/Cntr=0.3,0.1

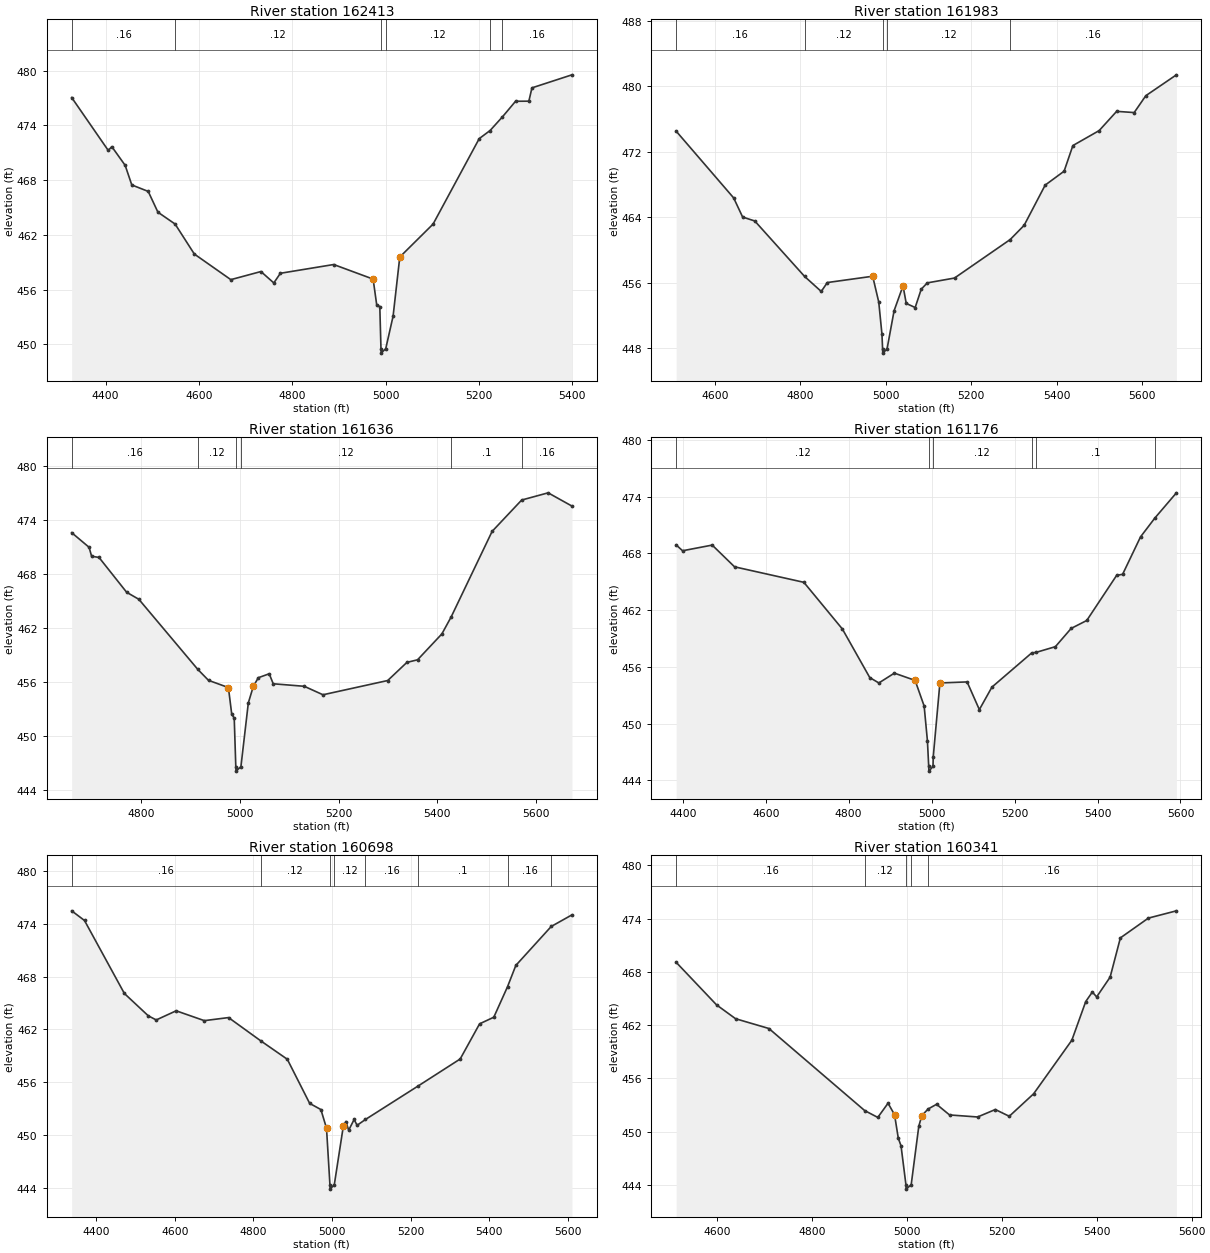
Type RM Length L Ch R = 1 ,162413  ,430,430,430
BEGIN DESCRIPTION:
DUCK CREEK 152 0
END DESCRIPTION:
XS GIS Cut Line= 2
      3470861.32     10442803.53      3470046.46     10442107.14
#Sta/Elev= 30
  4327.3  477.06  4405.6  471.26  4413.3  471.67  4441.9  469.62  4456.1  467.47
  4491.3  466.76  4512.1  464.48  4548.9  463.18  4590.1  459.89  4668.3  457.08
  4732.8  457.97  4760.4  456.72  4774.5  457.78  4888.7  458.74  4973.2  457.14
  4980.9  454.31  4987.5  454.13    4990  449.52  4990.5  449.02  5000.3  449.52
    5016  453.08  5030.3  459.56  5101.7  463.18  5200.5  472.55  5223.8  473.44
  5250.3  474.94  5278.4  476.65  5306.9  476.66  5313.5  478.12  5399.2  479.55
#Mann= 6 ,-1 , 0
  4327.3     .16       0  4548.9     .12       0    4990     .07       0
  5000.3     .12       0  5223.8      .1       0  5250.3     .16       0
Bank Sta=4973.2,5030.3
XS Rating Curve= 0 ,0
Exp/Cntr=0.3,0.1

Type RM Length L Ch R = 1 ,161983  ,347,347,347
BEGIN DESCRIPTION:
DUCK CREEK 15 1
END DESCRIPTION:
XS GIS Cut Line= 3
       3471000.7     10442532.65      3470420.59     10441886.84
      3470125.65     10441821.47
#Sta/Elev= 30
  4509.6   474.5  4644.2  466.34  4665.1  464.01  4693.5  463.53    4810  456.76
    4849  454.92  4863.2  456.01  4969.3  456.78  4983.5  453.63    4991  449.71
  4992.5  447.89    4993  447.39  5002.9  447.89  5019.4  452.57  5040.3  455.61
  5047.8  453.46  5068.7  452.96  5082.9   455.2  5097.1  455.97  5160.7  456.56
  5290.9  461.26  5323.6     463  5372.8  467.91  5417.1  469.61  5437.6  472.74
  5499.1  474.57    5540  476.92    5581  476.77  5608.2  478.83  5679.8  481.38
#Mann= 5 ,-1 , 0
  4509.6     .16       0    4810     .12       0  4992.5     .07       0
  5002.9     .12       0  5290.9     .16       0
Bank Sta=4969.3,5040.3
XS Rating Curve= 0 ,0
Exp/Cntr=0.3,0.1

Type RM Length L Ch R = 1 ,161636  ,460,460,460
BEGIN DESCRIPTION:
DUCK CREEK 15 0
END DESCRIPTION:
XS GIS Cut Line= 3
      3471032.78     10442436.56       3470925.4      10441676.9
      3470806.97     10441459.24
#Sta/Elev= 30
  4658.5  472.55  4693.8  470.93  4698.9  469.94    4714   469.8    4770  465.94
  4794.8  465.16  4914.3  457.39  4936.1  456.17  4976.5  455.37  4983.2  452.43
  4988.3  451.97  4991.5   446.6    4992   446.1  5001.9   446.6  5016.9  453.67
    5027  455.49  5037.1  456.46  5059.3   456.9  5067.4  455.79  5130.4  455.51
  5168.4  454.57  5299.7  456.15  5338.6  458.16  5360.3  458.45  5409.6  461.32
  5428.4   463.2  5511.5  472.69  5571.5  476.17  5625.2  476.97  5673.5   475.5
#Mann= 6 ,-1 , 0
  4658.5     .16       0  4914.3     .12       0  4991.5     .07       0
  5001.9     .12       0  5428.4      .1       0  5571.5     .16       0
Bank Sta=4976.5,5027
XS Rating Curve= 0 ,0
Exp/Cntr=0.3,0.1

Type RM Length L Ch R = 1 ,161176  ,478,478,478
BEGIN DESCRIPTION:
DUCK CREEK 149 0
END DESCRIPTION:
XS GIS Cut Line= 4
      3471364.51     10442446.12      3471446.23      10442109.6
      3471156.17     10441575.94      3470936.82     10441451.06
#Sta/Elev= 30
  4384.1  468.91  4399.6  468.29    4471  468.89  4524.9  466.59    4692  464.95
    4785     460  4850.9  454.87  4872.8   454.3  4910.2  455.34  4960.2  454.57
    4982  451.86  4989.9  448.18    4993  445.47  4993.5  444.97  5003.4  445.47
  5003.9  446.47    5020   454.3  5085.6  454.41  5115.1  451.48  5145.4  453.86
  5241.1  457.47  5252.2  457.54  5298.4  458.14  5336.4  460.07    5374  460.91
    5446  465.68  5460.5   465.8  5503.7  469.76  5538.2  471.75  5590.2  474.42
#Mann= 6 ,-1 , 0
  4384.1     .12       0    4993     .07       0  5003.4     .12       0
  5241.1     .16       0  5252.2      .1       0  5538.2     .16       0
Bank Sta=4960.2,5020
XS Rating Curve= 0 ,0
Exp/Cntr=0.3,0.1

Type RM Length L Ch R = 1 ,160698  ,357,357,357
BEGIN DESCRIPTION:
DUCK CREEK 148 0
END DESCRIPTION:
XS GIS Cut Line= 4
      3471797.19      10442253.8      3471749.12     10441963.76
      3471793.99     10441774.66      3471279.59     10441183.34
#Sta/Elev= 30
    4338  475.48  4370.6  474.38    4472  466.08  4532.8  463.54    4553  463.07
  4603.7  464.11  4675.3  462.99  4736.9  463.34  4818.3  460.71  4886.3   458.6
  4943.2  453.58  4971.7  452.88    4986  450.76  4994.7  444.33  4995.2  443.83
  5005.8  444.33  5028.7  450.97  5035.3  451.52  5042.4  450.53  5056.2  451.75
  5063.8  451.09    5085  451.75  5219.7  455.58  5325.9  458.63  5375.3  462.63
  5411.4  463.38  5446.4  466.86  5467.4  469.27  5557.4   473.7  5610.1  475.02
#Mann= 8 ,-1 , 0
    4338     .16       0  4818.3     .12       0  4994.7     .07       0
  5005.8     .12       0    5085     .16       0  5219.7      .1       0
  5446.4     .16       0  5557.4     .05       0
Bank Sta=4986,5028.7
XS Rating Curve= 0 ,0
Exp/Cntr=0.3,0.1

Type RM Length L Ch R = 1 ,160341  ,464,464,464
BEGIN DESCRIPTION:
DUCK CREEK 147 0
END DESCRIPTION:
XS GIS Cut Line= 3
      3472124.12     10441976.63      3472104.89     10441704.15
      3471717.63     10441025.64
#Sta/Elev= 30
  4513.5  469.08  4598.7  464.28  4638.8  462.72    4709  461.62  4910.9  452.37
  4938.5   451.6  4960.1   453.2  4973.8  451.91  4981.7  449.26  4987.5  448.39
  4997.8  444.02  4998.3  443.52  5008.9  444.02  5024.9   450.6  5031.3  451.81
  5044.6  452.55  5062.4  453.08  5089.7  451.88  5148.8  451.65  5186.2  452.49
  5215.6  451.73  5266.9  454.26  5347.5   460.3  5376.8  464.66  5390.7  465.73
  5399.8  465.18  5428.2  467.41  5449.8  471.83  5508.8  474.06  5567.9  474.88
#Mann= 5 ,-1 , 0
  4513.5     .16       0  4910.9     .12       0  4997.8     .07       0
  5008.9     .12       0  5044.6     .16       0
Bank Sta=4973.8,5031.3
XS Rating Curve= 0 ,0
Exp/Cntr=0.3,0.1