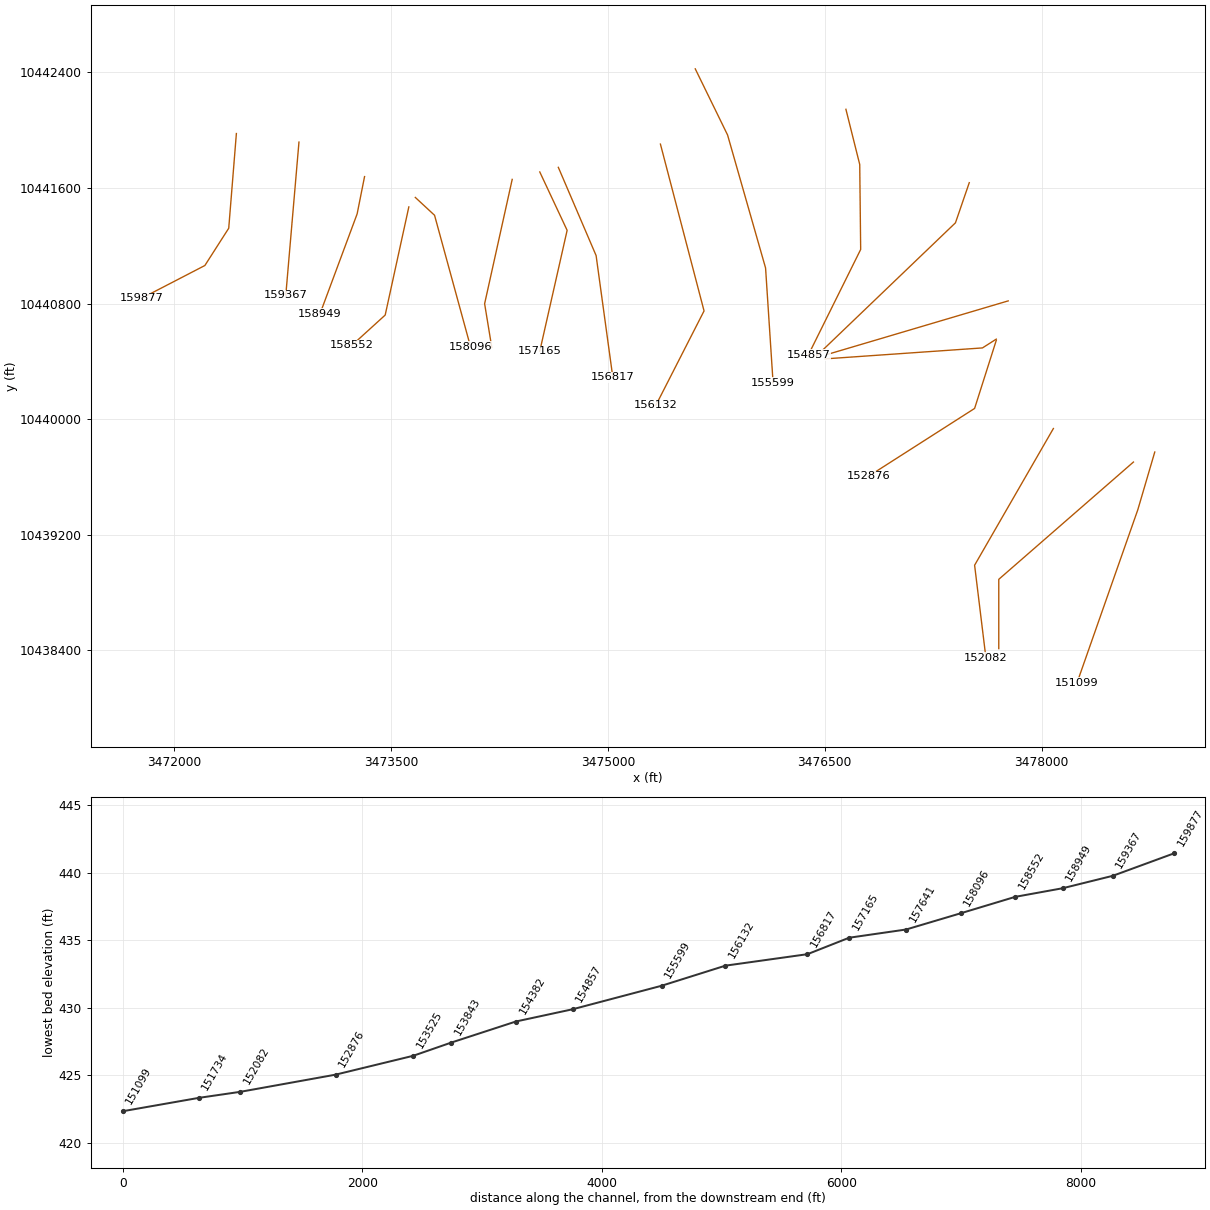
HEC-RAS study DUCK CREEK.prj: DUCK CREEK Base Level Engineering

--- DUCK CREEK.g01 (geometry) --- (continued)

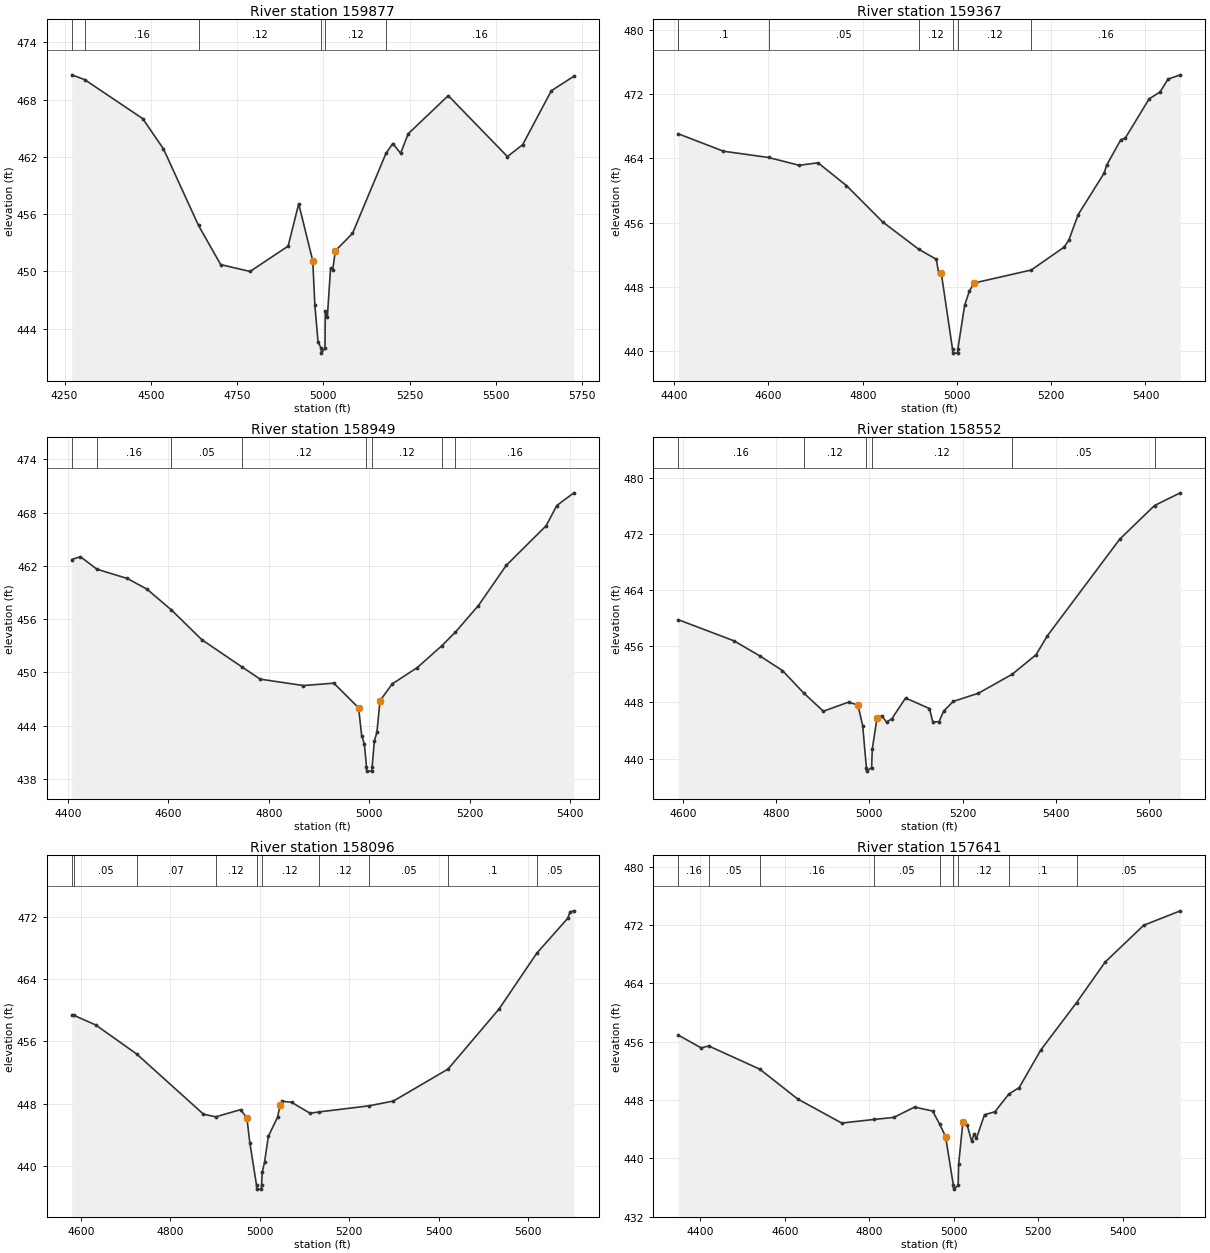
Type RM Length L Ch R = 1 ,159877  ,510,510,510
BEGIN DESCRIPTION:
DUCK CREEK 146 0
END DESCRIPTION:
XS GIS Cut Line= 4
      3472431.82     10441976.62      3472378.93     10441321.13
      3472213.87     10441063.12      3471777.97     10440837.16
#Sta/Elev= 30
    4271  470.61  4308.6   470.1  4476.6  466.02  4536.8  462.84  4638.3  454.82
  4702.5  450.72  4787.7     450    4898  452.66  4928.6  457.09  4969.3  451.12
  4975.5  446.44  4984.6  442.62  4993.7  441.94  4994.2  441.44  5004.8  441.94
  5005.7  445.87  5011.6   445.2  5020.9  450.35  5026.9  450.11  5034.9  452.17
  5084.4  453.98  5181.4  462.37  5201.1  463.41  5223.9  462.39  5245.8  464.43
    5362  468.43  5533.4  462.04  5577.7  463.29  5660.6  468.94  5725.9  470.46
#Mann= 6 ,-1 , 0
    4271      .1       0  4308.6     .16       0  4638.3     .12       0
  4993.7     .07       0  5004.8     .12       0  5181.4     .16       0
Bank Sta=4969.3,5034.9
XS Rating Curve= 0 ,0
Exp/Cntr=0.3,0.1

Type RM Length L Ch R = 1 ,159367  ,418,418,418
BEGIN DESCRIPTION:
DUCK CREEK 145 0
END DESCRIPTION:
XS GIS Cut Line= 2
      3472864.51     10441917.28      3472773.24      10440855.7
#Sta/Elev= 30
  4408.5  467.06  4504.5  464.89  4600.1  464.11  4665.1  463.14  4705.2  463.45
  4765.4  460.62  4842.9  456.07  4919.1  452.69  4956.2  451.45  4961.5  449.61
  4966.6  449.78  4990.6  440.28  4991.1  439.78  5001.4  439.78  5001.9  440.28
  5016.4  445.76  5026.4   447.5  5036.4   448.5  5157.8  450.12  5227.1  452.95
  5237.2   453.8  5257.3  457.02  5312.3  462.16  5317.5  463.13  5347.6  466.31
  5357.6  466.56  5407.8   471.4  5430.9  472.25    5448  473.86    5474  474.39
#Mann= 6 ,-1 , 0
  4408.5      .1       0  4600.1     .05       0  4919.1     .12       0
  4990.6     .07       0  5001.9     .12       0  5157.8     .16       0
Bank Sta=4966.6,5036.4
XS Rating Curve= 0 ,0
Exp/Cntr=0.3,0.1

Type RM Length L Ch R = 1 ,158949  ,397,397,397
BEGIN DESCRIPTION:
DUCK CREEK 144 0
END DESCRIPTION:
XS GIS Cut Line= 3
      3473318.04     10441678.51      3473266.75     10441420.49
      3473010.36     10440729.82
#Sta/Elev= 30
  4407.4  462.72  4424.6  463.04  4457.4  461.63  4518.1  460.58  4557.1  459.38
  4605.9  457.03  4666.4  453.68  4746.3  450.61  4782.8  449.23  4868.6  448.51
  4929.3  448.78  4978.6  445.99  4984.7  442.86  4990.1   441.9  4994.3  439.36
  4994.8  438.86  5005.1  438.86  5005.6  439.36  5009.8  442.22  5015.1  443.26
  5021.2   446.8  5045.5  448.69  5095.5  450.54  5144.1  452.99  5171.3  454.53
    5217  457.52  5272.4  462.05  5351.9  466.52  5373.3  468.81  5407.2  470.24
#Mann= 8 ,-1 , 0
  4407.4      .1       0  4457.4     .16       0  4605.9     .05       0
  4746.3     .12       0  4994.3     .07       0  5005.6     .12       0
  5144.1     .05       0  5171.3     .16       0
Bank Sta=4978.6,5021.2
XS Rating Curve= 0 ,0
Exp/Cntr=0.3,0.1

Type RM Length L Ch R = 1 ,158552  ,456,456,456
BEGIN DESCRIPTION:
DUCK CREEK 143 0
END DESCRIPTION:
XS GIS Cut Line= 3
      3473624.14     10441468.61      3473460.67     10440720.17
      3473229.87     10440510.21
#Sta/Elev= 30
  4589.6  459.78  4709.3  456.77  4764.4  454.64  4813.4  452.54  4858.6  449.37
  4901.2  446.75  4955.4  448.04  4975.5  447.63  4985.7  444.68  4993.6  438.72
  4994.1  438.22  5004.9  438.72  5006.2  441.33  5016.4  445.77  5026.6   446.1
  5036.9   445.2  5048.3  445.68  5077.8  448.63    5129  447.13  5136.1  445.24
  5149.5  445.25  5159.7  446.78    5180  448.14  5234.1  449.31  5306.7  452.01
  5358.1   454.8  5381.7  457.44  5537.7  471.25  5612.3  476.03  5667.7  477.84
#Mann= 6 ,-1 , 0
  4589.6     .16       0  4858.6     .12       0  4993.6     .07       0
  5004.9     .12       0  5306.7     .05       0  5612.3      .1       0
Bank Sta=4975.5,5016.4
XS Rating Curve= 0 ,0
Exp/Cntr=0.3,0.1

Type RM Length L Ch R = 1 ,158096  ,455,455,455
BEGIN DESCRIPTION:
DUCK CREEK 142 0
END DESCRIPTION:
XS GIS Cut Line= 3
      3473668.99     10441534.28      3473802.01     10441410.88
       3474050.4     10440502.26
#Sta/Elev= 30
  4579.2  459.34  4584.4  459.34  4632.9  458.11  4724.4  454.38  4873.9  446.64
  4901.4   446.3  4956.8  447.22    4971  446.18  4977.6  442.98  4992.6   437.5
  4993.1     437  5003.4     437  5003.9   437.5  5005.5  439.17  5010.7  440.53
    5019  443.78  5039.8  446.27  5045.2  447.77  5050.4   448.3  5070.9  448.17
  5112.3  446.76  5131.5  446.92    5244  447.71  5298.9  448.33  5421.1  452.44
  5535.3  460.17  5619.5  467.33  5688.9  471.83  5694.1  472.65  5702.6  472.79
#Mann= 10 ,-1 , 0
  4579.2     .16       0  4584.4     .05       0  4724.4     .07       0
  4901.4     .12       0  4992.6     .07       0  5003.9     .12       0
  5131.5     .12       0    5244     .05       0  5421.1      .1       0
  5619.5     .05       0
Bank Sta=4971,5045.2
XS Rating Curve= 0 ,0
Exp/Cntr=0.3,0.1

Type RM Length L Ch R = 1 ,157641  ,476,476,476
BEGIN DESCRIPTION:
DUCK CREEK 14 1
END DESCRIPTION:
XS GIS Cut Line= 3
      3474338.88     10441659.29      3474148.17     10440798.69
      3474197.78     10440496.21
#Sta/Elev= 30
  4347.9  456.92  4402.1  455.17  4420.1  455.43  4540.8  452.25  4630.3  448.17
  4734.7  444.86  4810.2  445.35  4857.6  445.63  4907.2  447.05  4949.8  446.51
  4966.5  444.71  4980.5     443    4999   436.3  4999.5   435.8  5010.3   436.3
  5011.3  439.18  5021.5  445.03  5031.7  444.57    5042   442.4  5048.3  443.33
  5053.4  442.77  5072.7  446.01    5097   446.4    5130  448.83  5154.7  449.73
  5205.9  454.89  5290.6  461.39  5358.1  466.94  5449.3  471.98  5535.9  473.96
#Mann= 9 ,-1 , 0
  4347.9     .16       0  4420.1     .05       0  4540.8     .16       0
  4810.2     .05       0  4966.5     .12       0    4999     .07       0
  5010.3     .12       0    5130      .1       0  5290.6     .05       0
Bank Sta=4980.5,5021.5
XS Rating Curve= 0 ,0
Exp/Cntr=0.3,0.1

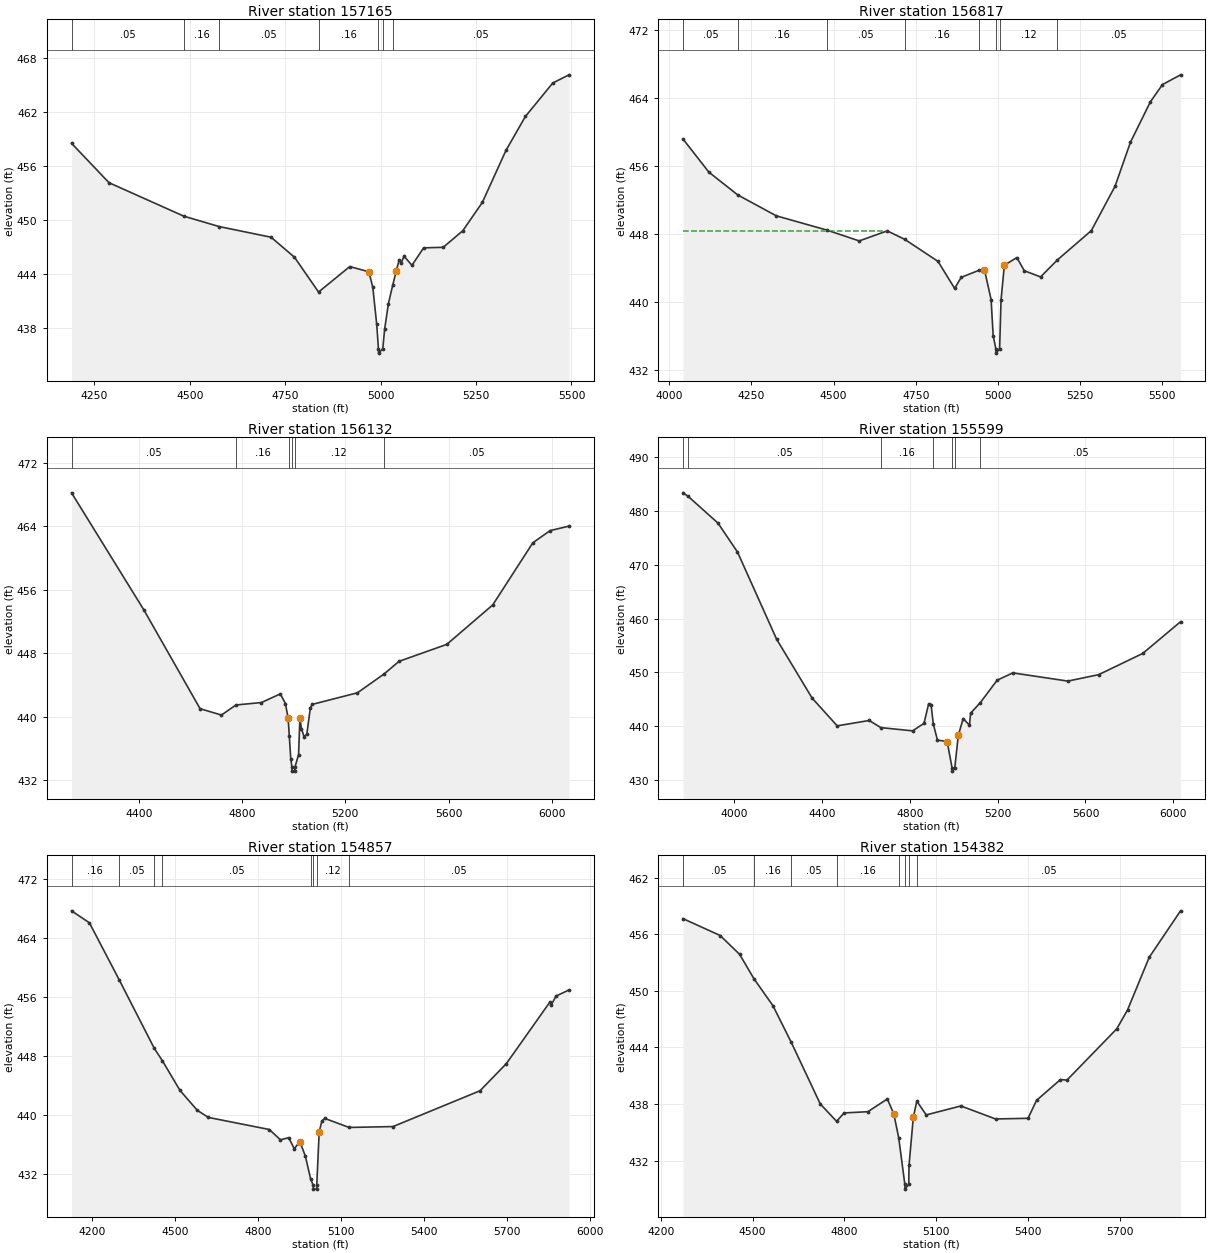
Type RM Length L Ch R = 1 ,157165  ,348,348,348
BEGIN DESCRIPTION:
DUCK CREEK 14 0
END DESCRIPTION:
XS GIS Cut Line= 3
      3474529.59     10441710.54      3474718.68     10441306.71
      3474529.57     10440470.13
#Sta/Elev= 30
  4189.9  458.51  4288.1  454.13  4484.2  450.41  4576.4  449.26  4712.8  448.07
  4774.1  445.85  4837.2  441.98    4919  444.81  4969.1  444.23  4979.3  442.51
  4989.6   438.4  4994.1  435.69  4994.6  435.19  5005.5  435.69  5010.5   437.9
  5020.3   440.7  5031.4  442.72  5040.8  444.31  5048.6  445.58  5053.7  445.22
  5061.3  445.96  5081.9  444.95  5112.6  446.89  5163.9  446.95  5215.1  448.79
  5266.4  451.94  5328.2  457.71  5379.2  461.49  5450.9  465.21  5493.5  466.12
#Mann= 7 ,-1 , 0
  4189.9     .05       0  4484.2     .16       0  4576.4     .05       0
  4837.2     .16       0  4994.1     .07       0  5005.5     .16       0
  5031.4     .05       0
Bank Sta=4969.1,5040.8
XS Rating Curve= 0 ,0
Exp/Cntr=0.3,0.1

Type RM Length L Ch R = 1 ,156817  ,685,685,685
BEGIN DESCRIPTION:
DUCK CREEK 139 0
END DESCRIPTION:
XS GIS Cut Line= 3
      3474657.79      10441742.6      3474919.01     10441132.03
      3475034.39     10440290.71
#Sta/Elev= 30
  4042.3  459.16  4120.9  455.27  4208.6  452.59  4326.1  450.13    4480  448.45
  4578.1  447.18  4663.3  448.36  4716.7  447.36  4817.8  444.77  4868.3  441.59
  4888.5  442.89  4942.4  443.72  4959.1  443.78  4979.3  440.28  4985.6  436.04
  4993.8  434.47  4994.3  433.97  5005.2  434.47  5009.6  440.26  5019.7  444.32
  5057.7  445.22  5080.3  443.67  5129.8  442.94  5180.9  444.94  5284.2  448.39
  5356.3  453.61  5403.3   458.8  5463.8  463.55  5500.6  465.58  5555.6  466.73
#Mann= 8 ,-1 , 0
  4042.3     .05       0  4208.6     .16       0    4480     .05       0
  4716.7     .16       0  4942.4     .12       0  4993.8     .07       0
  5005.2     .12       0  5180.9     .05       0
#XS Ineff= 2 , 0
         4662.84  448.39
Permanent Ineff=
       F       F
Bank Sta=4959.1,5019.7
XS Rating Curve= 0 ,0
Exp/Cntr=0.3,0.1

Type RM Length L Ch R = 1 ,156132  ,533,533,533
BEGIN DESCRIPTION:
DUCK CREEK 138 0
END DESCRIPTION:
XS GIS Cut Line= 3
      3475363.68     10441903.46      3475665.34     10440748.89
      3475331.96     10440095.11
#Sta/Elev= 30
  4139.2  468.25  4420.1  453.43  4637.2     441  4719.9   440.2  4776.2  441.47
  4874.9  441.78  4948.2  442.87  4967.9  441.64  4978.3  439.79  4982.8  437.58
  4988.6  434.65  4993.2  433.62  4993.7  433.12  5004.1  433.12  5004.6  433.62
  5018.7  435.21  5023.9  439.81  5029.9  438.48  5040.3  437.45  5050.6  437.77
  5064.4   441.1  5071.3  441.54    5247  443.01    5349  445.36    5408  446.98
    5593  449.12  5770.9   454.1  5926.5  461.95  5993.2  463.48  6066.4  464.05
#Mann= 6 ,-1 , 0
  4139.2     .05       0  4776.2     .16       0  4982.8     .12       0
  4993.2     .07       0  5004.6     .12       0    5349     .05       0
Bank Sta=4978.3,5023.9
XS Rating Curve= 0 ,0
Exp/Cntr=0.3,0.1

Type RM Length L Ch R = 1 ,155599  ,742,742,742
BEGIN DESCRIPTION:
DUCK CREEK 137 0
END DESCRIPTION:
XS GIS Cut Line= 4
      3475604.59     10442424.22       3475828.1     10441966.34
      3476090.69      10441046.2      3476142.77      10440249.8
#Sta/Elev= 30
  3768.3  483.38  3791.7  482.71    3927  477.76    4016  472.37    4194  456.17
  4355.5  445.22  4469.9  440.05  4615.5  441.05  4668.6  439.72  4813.1  439.12
  4865.1  440.52  4885.9  444.11  4897.6  443.85  4907.2  440.43  4926.2   437.4
  4970.4  437.13  4993.2  432.13  4993.7  431.63  5004.8  432.13  5021.1  438.26
  5043.2   441.4  5071.9  440.18  5077.1   442.4  5121.6  444.38  5197.8  448.53
  5269.3   449.9  5519.9  448.37  5660.2  449.57  5860.6  453.51  6032.8  459.41
#Mann= 7 ,-1 , 0
  3768.3      .1       0  3791.7     .05       0  4668.6     .16       0
  4907.2     .12       0  4993.2     .07       0  5004.8     .12       0
  5121.6     .05       0
Bank Sta=4970.4,5021.1
XS Rating Curve= 0 ,0
Exp/Cntr=0.3,0.1

Type RM Length L Ch R = 1 ,154857  ,475,475,475
BEGIN DESCRIPTION:
DUCK CREEK 135 1
END DESCRIPTION:
XS GIS Cut Line= 4
      3476646.25     10442144.29      3476741.73     10441762.35
      3476748.24     10441174.24      3476386.47      10440444.2
#Sta/Elev= 30
  4126.6   467.7  4191.2  466.07  4298.7  458.33  4425.5  449.01  4454.4  447.35
  4518.1  443.31    4581  440.59    4621  439.63    4841  437.99    4881  436.59
    4911  436.88    4931  435.37    4951  436.36    4971  434.38    4990  431.29
  4999.6  430.39  5000.1  429.89  5011.7  429.89  5012.2  430.39    5021  437.69
    5031  439.16    5041   439.5    5129  438.27  5287.7  438.39  5601.6  443.25
  5696.9  446.94  5853.9  455.29  5859.4  454.93  5876.3  456.12  5923.2  456.95
#Mann= 8 ,-1 , 0
  4126.6     .16       0  4298.7     .05       0  4425.5     .16       0
  4454.4     .05       0    4990     .12       0  4999.6     .07       0
  5012.2     .12       0    5129     .05       0
Bank Sta=4951,5021
XS Rating Curve= 0 ,0
Exp/Cntr=0.3,0.1

Type RM Length L Ch R = 1 ,154382  ,539,539,539
BEGIN DESCRIPTION:
DUCK CREEK 134 1
END DESCRIPTION:
XS GIS Cut Line= 3
       3477499.1     10441636.45      3477403.62      10441358.7
      3476442.36      10440436.5
#Sta/Elev= 30
  4272.6  457.66    4394  455.87  4457.5  453.87  4503.8  451.31  4566.3  448.43
  4626.4  444.53  4720.8  438.02  4774.3  436.17  4798.7  437.06  4876.4  437.19
  4940.2  438.54  4961.3  436.95  4977.2  434.45  4997.4  429.48  4997.9  428.98
  5010.1  429.48    5011   431.5  5025.1  436.61  5036.5  438.31  5067.3  436.85
  5180.5   437.8  5293.7  436.42  5399.9  436.49    5428   438.4    5506   440.6
  5527.1  440.54    5690  445.98  5725.2  447.98    5796  453.56  5898.4  458.49
#Mann= 8 ,-1 , 0
  4272.6     .05       0  4503.8     .16       0  4626.4     .05       0
  4774.3     .16       0  4977.2     .12       0  4997.4     .07       0
  5010.1     .12       0  5036.5     .05       0
Bank Sta=4961.3,5025.1
XS Rating Curve= 0 ,0
Exp/Cntr=0.3,0.1

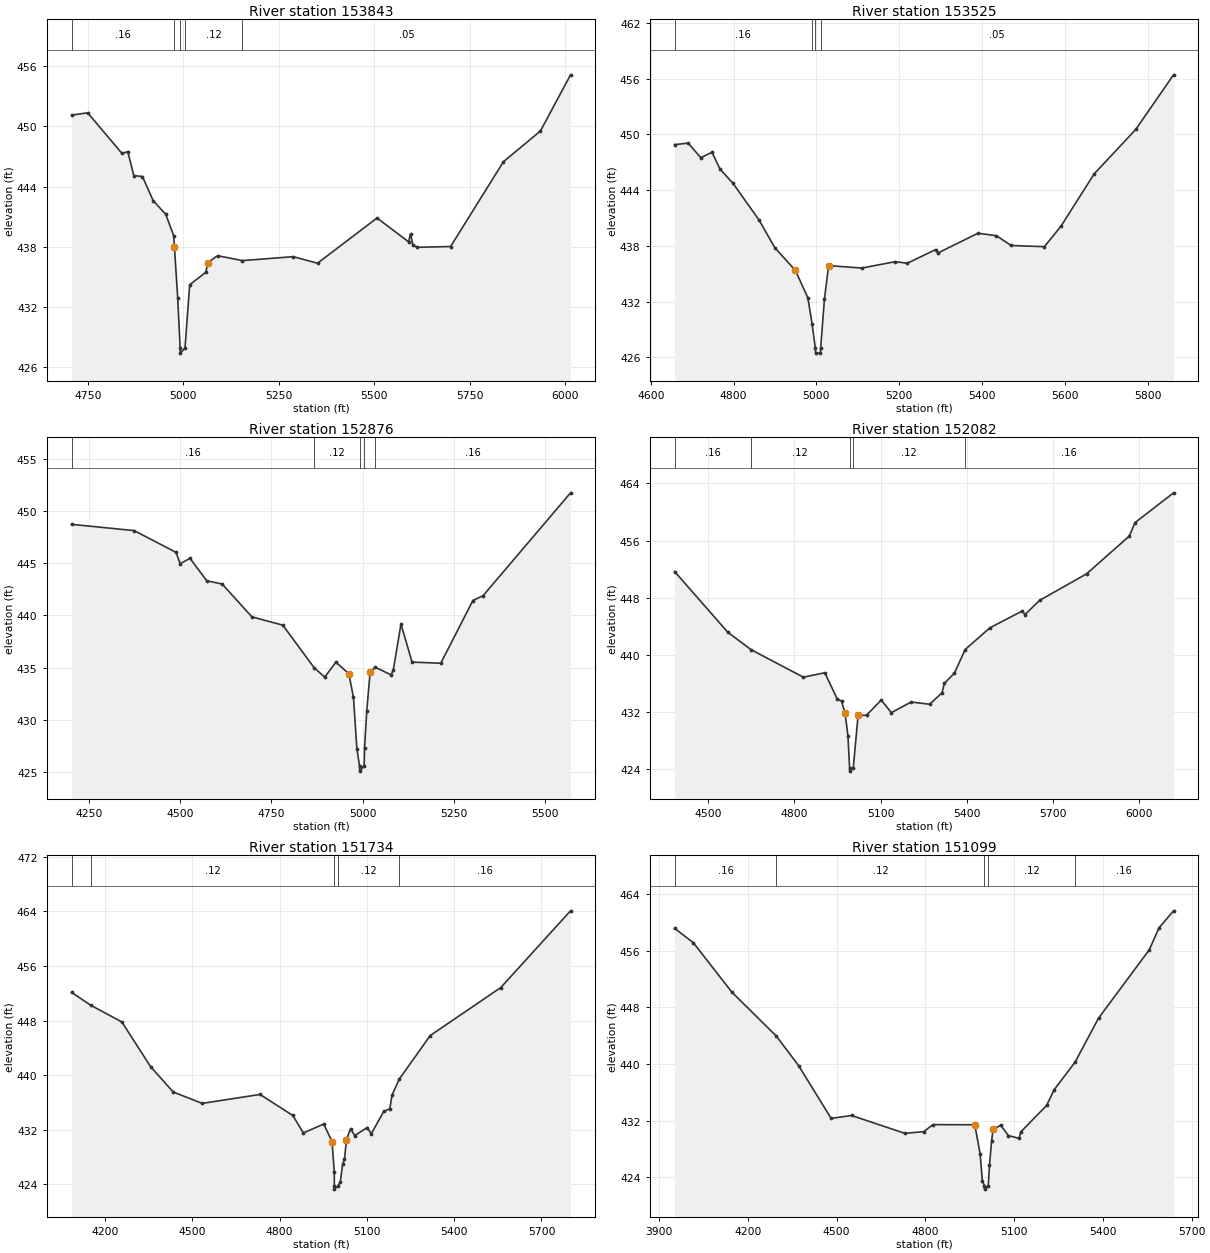
Type RM Length L Ch R = 1 ,153843  ,318,318,318
BEGIN DESCRIPTION:
DUCK CREEK 135 0
END DESCRIPTION:
XS GIS Cut Line= 2
      3477768.23     10440818.35      3476516.54     10440447.39
#Sta/Elev= 30
  4707.8  451.11  4749.8  451.34  4839.3  447.31  4854.8  447.47  4870.6  445.09
  4893.2     445  4921.3  442.59  4954.1  441.24  4974.9  439.11  4976.8  437.99
  4985.4  432.92  4991.8  427.92  4992.3  427.42  5004.5  427.92  5016.7  434.22
  5058.4  435.45  5064.7  436.44  5089.7  437.12  5154.6  436.63  5287.8  437.02
  5351.4  436.37  5506.9  440.87  5589.4   438.5  5594.6  439.28  5600.7  438.22
  5611.2  437.95  5699.5  438.03  5837.7  446.47  5934.5  449.53  6013.3  455.12
#Mann= 5 ,-1 , 0
  4707.8     .16       0  4976.8     .12       0  4991.8     .07       0
  5004.5     .12       0  5154.6     .05       0
Bank Sta=4976.8,5064.7
XS Rating Curve= 0 ,0
Exp/Cntr=0.3,0.1

Type RM Length L Ch R = 1 ,153525  ,649,649,649
BEGIN DESCRIPTION:
DUCK CREEK 134 0
END DESCRIPTION:
XS GIS Cut Line= 3
      3477685.75     10440553.59      3477590.26     10440492.82
      3476500.89     10440416.87
#Sta/Elev= 30
  4657.7  448.91  4690.5  449.07  4720.9   447.5    4748  448.09  4767.3  446.28
  4799.1  444.72    4862  440.76  4899.4  437.82  4949.5  435.35  4979.5  432.41
  4989.8   429.6  4997.7  426.94  4998.2  426.44  5009.9  426.44  5010.4  426.94
  5019.6  432.27  5029.7  435.87  5109.9  435.61  5190.1  436.29  5220.1  436.13
  5288.2   437.6  5293.2  437.22  5390.5  439.36  5435.2  439.09  5470.7  438.04
  5550.9  437.91    5591  440.12  5671.2  445.76  5771.5  450.54  5862.9  456.43
#Mann= 4 ,-1 , 0
  4657.7     .16       0  4989.8     .05       0  4997.7    .035       0
  5010.4     .05       0
Bank Sta=4949.5,5029.7
XS Rating Curve= 0 ,0
Exp/Cntr=0.3,0.1

Type RM Length L Ch R = 1 ,152876  ,794,794,794
BEGIN DESCRIPTION:
DUCK CREEK 133 0
END DESCRIPTION:
XS GIS Cut Line= 3
      3477685.73     10440544.86        3477536.     10440073.98
      3476800.32     10439603.06
#Sta/Elev= 30
  4202.5  448.76  4373.8  448.16  4489.2  446.06  4499.9  444.97  4526.9   445.5
  4573.1  443.33  4615.1  443.03  4696.6  439.87  4781.4  439.07    4868  434.95
  4896.4  434.08  4926.8  435.51  4962.4  434.41  4975.1  432.12  4984.4  427.21
  4991.7  425.54  4992.2  425.04  5004.4  425.54  5005.5  427.29  5011.4  430.79
  5020.7  434.54  5034.7  435.03  5078.2  434.29  5084.2  434.75  5105.3  439.18
  5135.7  435.52  5214.4  435.41  5302.3  441.43  5330.5  441.91  5570.1  451.79
#Mann= 5 ,-1 , 0
  4202.5     .16       0    4868     .12       0  4991.7     .07       0
  5004.4     .12       0  5034.7     .16       0
Bank Sta=4962.4,5020.7
XS Rating Curve= 0 ,0
Exp/Cntr=0.3,0.1

Type RM Length L Ch R = 1 ,152082  ,348,348,348
BEGIN DESCRIPTION:
DUCK CREEK 132 0
END DESCRIPTION:
XS GIS Cut Line= 3
      3478080.69     10439935.06        3477536.     10438988.91
      3477614.13     10438348.69
#Sta/Elev= 30
  4382.9  451.67  4568.1  443.18  4649.3  440.74  4831.1   436.9  4905.8  437.52
  4948.9  433.85  4963.8  433.56  4976.2  431.87  4986.2  428.73  4991.9  424.27
  4992.4  423.77  5004.9  424.27  5021.5  431.57  5050.9  431.59  5102.2  433.71
  5137.2  431.94  5206.1  433.43  5270.8  433.12  5313.9  434.73  5321.5  436.02
    5357  437.48  5394.3  440.77  5480.3   443.8  5592.8  446.15  5602.8  445.66
  5653.5  447.64  5816.7  451.34  5965.5  456.62  5985.7  458.51  6119.6  462.67
#Mann= 5 ,-1 , 0
  4382.9     .16       0  4649.3     .12       0  4991.9     .07       0
  5004.9     .12       0  5394.3     .16       0
Bank Sta=4976.2,5021.5
XS Rating Curve= 0 ,0
Exp/Cntr=0.3,0.1

Type RM Length L Ch R = 1 ,151734  ,635,635,635
BEGIN DESCRIPTION:
DUCK CREEK 130 0
END DESCRIPTION:
XS GIS Cut Line= 3
      3478634.09     10439702.89       3477703.1     10438891.26
       3477703.1     10438411.66
#Sta/Elev= 30
  4085.3  452.12  4151.8  450.22    4258  447.79  4356.7  441.25  4434.5  437.54
  4534.2  435.87  4732.7  437.18  4845.6   434.1  4881.7  431.54  4951.9  432.85
  4980.4  430.27    4988  425.86  4988.2  423.82  4988.7  423.32  5001.2  423.82
  5008.9  424.41  5016.5  426.95  5023.1  427.67  5029.9  430.58    5044  432.14
  5058.3  431.16    5101  432.33  5115.2  431.42    5158  434.69  5178.8  435.08
  5186.4  437.06  5211.1  439.41  5317.7   445.8    5560  452.82    5800  464.06
#Mann= 5 ,-1 , 0
  4085.3     .16       0  4151.8     .12       0  4988.2     .07       0
  5001.2     .12       0  5211.1     .16       0
Bank Sta=4980.4,5029.9
XS Rating Curve= 0 ,0
Exp/Cntr=0.3,0.1

Type RM Length L Ch R = 1 ,151099  ,548,548,548
BEGIN DESCRIPTION:
DUCK CREEK 13 0
END DESCRIPTION:
XS GIS Cut Line= 3
      3478781.66     10439772.32      3478664.47     10439373.03
       3478244.1     10438174.75
#Sta/Elev= 30
  3952.8  459.16    4016  457.13  4146.4  450.14    4297  443.92  4372.3  439.74
  4481.7  432.32  4550.6  432.73  4730.7  430.21  4794.3  430.44  4826.1  431.44
  4967.2  431.42  4985.1  427.33  4992.9  423.45  4999.7  422.83  5000.2  422.33
  5012.7  422.83  5016.8  425.67  5023.9  429.12  5029.2  430.78  5054.9  431.35
  5080.4   429.9  5116.9   429.5  5122.8  430.42  5209.9  434.15  5235.6  436.38
  5305.8  440.25  5385.3  446.47  5557.3  456.16  5589.1   459.2  5638.8  461.63
#Mann= 5 ,-1 , 0
  3952.8     .16       0    4297     .12       0  4999.7     .07       0
  5012.7     .12       0  5305.8     .16       0
Bank Sta=4967.2,5029.2
XS Rating Curve= 0 ,0
Exp/Cntr=0.3,0.1