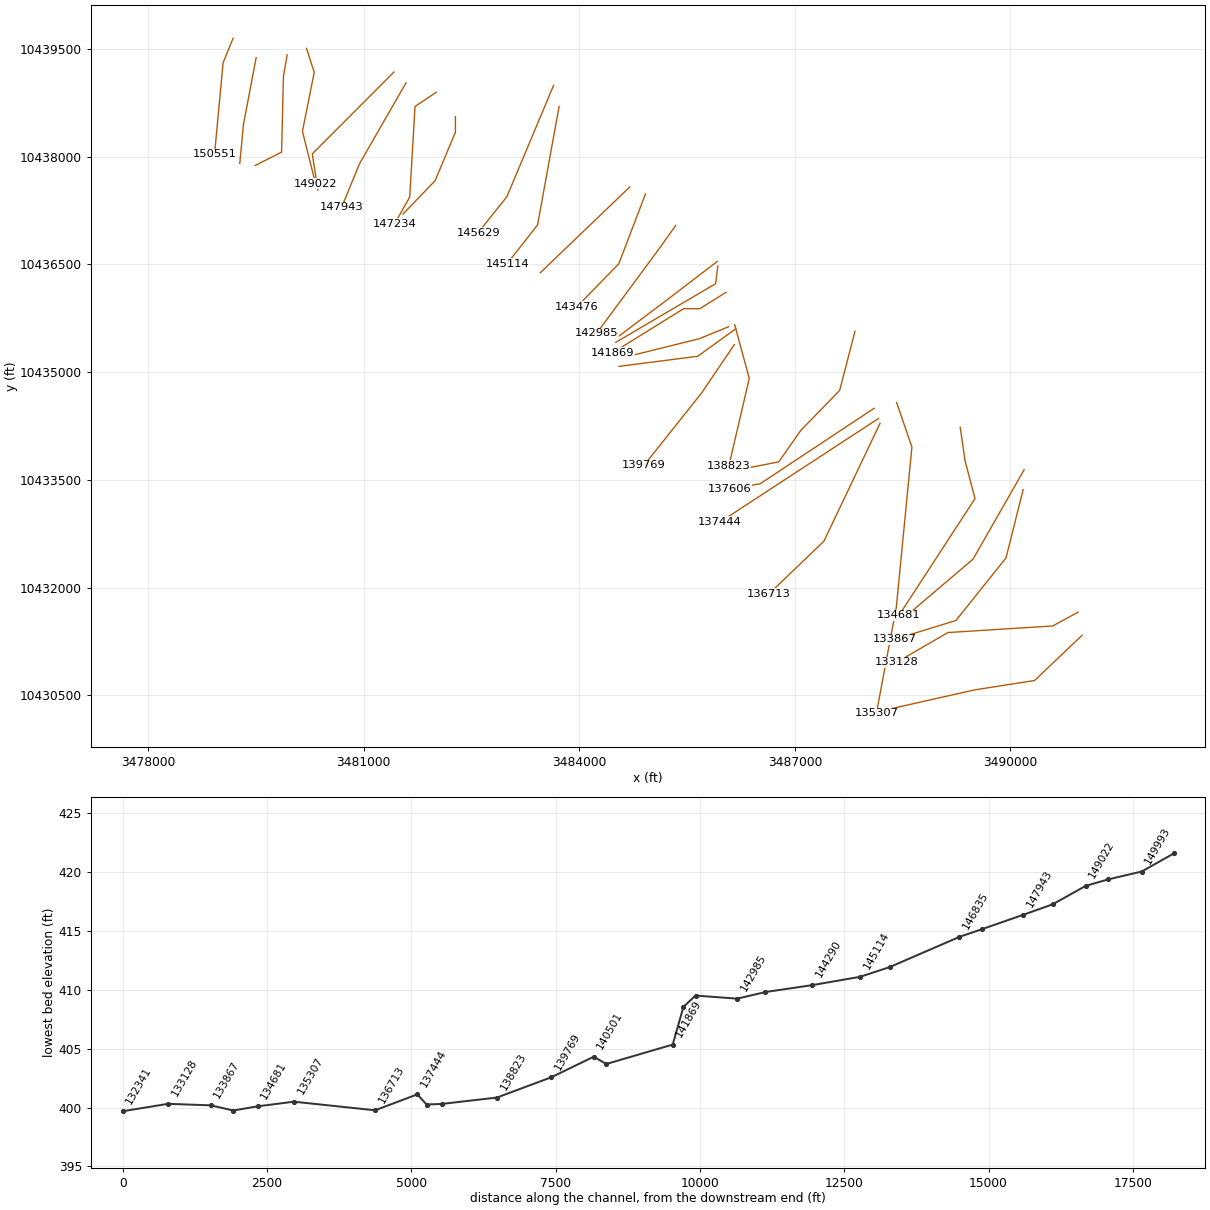
HEC-RAS study DUCK CREEK.prj: DUCK CREEK Base Level Engineering

--- DUCK CREEK.g01 (geometry) --- (continued)

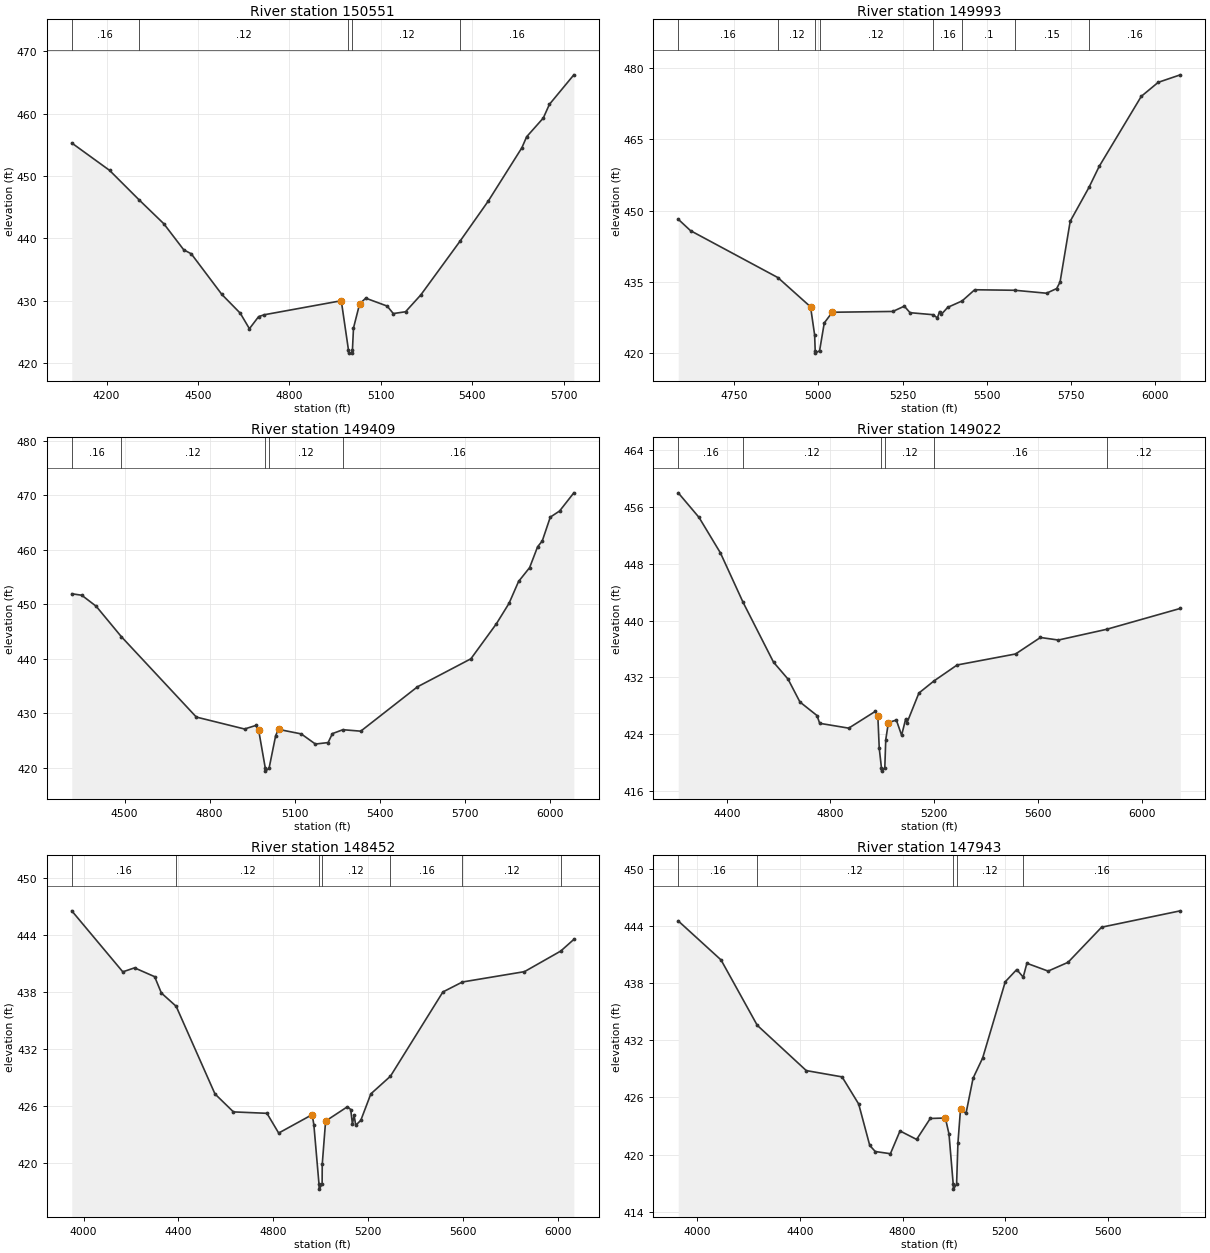
Type RM Length L Ch R = 1 ,150551  ,558,558,558
BEGIN DESCRIPTION:
DUCK CREEK 129 0
END DESCRIPTION:
XS GIS Cut Line= 3
      3479180.95     10439646.43      3479042.08     10439305.75
      3478922.72     10438031.83
#Sta/Elev= 30
  4085.8   455.3  4209.8  450.91  4306.2   446.2  4387.7  442.35  4453.2  438.16
  4477.9  437.52  4578.4  430.99  4638.6  427.99  4668.7   425.5  4698.9  427.44
  4717.7  427.74  4970.1  429.99  4993.7  422.08  4994.2  421.58  5006.2  421.58
  5006.7  422.08  5010.2  425.61  5030.3  429.49  5050.4   430.4  5120.7  429.13
  5140.8  427.93    5181  428.22  5231.2  430.93  5360.7  439.61  5452.2  445.97
  5562.6  454.53  5578.3   456.3    5633  459.31    5653   461.5  5733.2  466.24
#Mann= 5 ,-1 , 0
  4085.8     .16       0  4306.2     .12       0  4993.7     .07       0
  5006.7     .12       0  5360.7     .16       0
Bank Sta=4970.1,5030.3
XS Rating Curve= 0 ,0
Exp/Cntr=0.3,0.1

Type RM Length L Ch R = 1 ,149993  ,584,584,584
BEGIN DESCRIPTION:
DUCK CREEK 128 0
END DESCRIPTION:
XS GIS Cut Line= 3
      3479502.15     10439377.39      3479326.37     10438452.89
      3479274.31     10437906.33
#Sta/Elev= 30
  4584.1  448.18  4620.5  445.78    4880  435.91  4976.8  429.77  4988.9  423.87
  4990.6  420.54  4991.1  420.04  5003.6  420.54  5017.5  426.38  5041.2  428.63
  5221.1   428.8  5255.1  429.91    5272  428.54  5339.7  428.12  5353.4  427.45
  5359.5  428.77  5364.6  428.16  5383.9  429.66  5426.6  431.01    5464  433.36
  5583.3  433.25  5677.1  432.63  5707.2  433.61  5717.3  434.97  5747.4  447.75
  5803.1  454.87  5833.3  459.27  5958.4  474.01  6008.6  476.95  6074.2  478.53
#Mann= 8 ,-1 , 0
  4584.1     .16       0    4880     .12       0  4990.6     .07       0
  5003.6     .12       0  5339.7     .16       0  5426.6      .1       0
  5583.3     .15       0  5803.1     .16       0
Bank Sta=4976.8,5041.2
XS Rating Curve= 0 ,0
Exp/Cntr=0.3,0.1

Type RM Length L Ch R = 1 ,149409  ,387,387,387
BEGIN DESCRIPTION:
DUCK CREEK 127 0
END DESCRIPTION:
XS GIS Cut Line= 4
      3479934.01     10439416.46      3479881.92     10439116.95
      3479855.88     10438062.26      3479487.99     10437876.16
#Sta/Elev= 30
  4313.5  451.91  4348.8  451.64  4399.6  449.62  4487.9  444.07  4752.9  429.29
  4922.9   427.1  4962.9  427.75  4972.9  426.86  4996.4  419.87  4996.9  419.37
  5009.5  419.87  5032.9   425.9  5042.9  427.03    5123   426.2    5173  424.34
  5217.9  424.61    5233  426.25    5270  426.97    5333   426.7  5533.1  434.84
  5721.6  439.98  5811.2  446.38  5856.1  450.15  5889.8  454.17  5928.8  456.71
  5956.9  460.53  5973.3  461.59  6001.7  465.97  6034.6   467.1  6084.8  470.43
#Mann= 5 ,-1 , 0
  4313.5     .16       0  4487.9     .12       0  4996.4     .07       0
  5009.5     .12       0    5270     .16       0
Bank Sta=4972.9,5042.9
XS Rating Curve= 0 ,0
Exp/Cntr=0.3,0.1

Type RM Length L Ch R = 1 ,149022  ,570,570,570
BEGIN DESCRIPTION:
DUCK CREEK 126 0
END DESCRIPTION:
XS GIS Cut Line= 4
      3480203.84     10439506.72      3480310.62     10439173.37
      3480146.55     10438353.06      3480328.51     10437625.24
#Sta/Elev= 30
  4212.7  457.99  4292.9  454.53  4375.5  449.53  4462.4  442.61  4580.2  434.16
  4636.3  431.77  4682.2  428.55  4748.1  426.64  4758.3  425.55  4870.4  424.87
  4972.4  427.22  4982.6  426.64  4988.1  422.04  4996.5  419.32    4997  418.82
  5009.6  419.32  5013.2  423.24  5023.4  425.65    5054  426.01  5074.4  423.87
  5090.1  426.17  5095.2  425.63  5141.1  429.81  5199.1  431.51  5288.6  433.76
  5514.1  435.31  5609.9  437.63  5679.1  437.27  5865.2  438.78  6149.5  441.72
#Mann= 6 ,-1 , 0
  4212.7     .16       0  4462.4     .12       0  4996.5     .07       0
  5009.6     .12       0  5199.1     .16       0  5865.2     .12       0
Bank Sta=4982.6,5023.4
XS Rating Curve= 0 ,0
Exp/Cntr=0.3,0.1

Type RM Length L Ch R = 1 ,148452  ,509,509,509
BEGIN DESCRIPTION:
DUCK CREEK 125 0
END DESCRIPTION:
XS GIS Cut Line= 3
      3481420.58     10439177.75       3480283.4     10438038.39
      3480361.39     10437535.77
#Sta/Elev= 30
  3950.4  446.59  4165.8  440.16  4215.3  440.58  4300.1  439.65  4328.4  437.93
  4390.8  436.53  4554.7  427.29  4632.5   425.4  4773.9  425.25  4823.4  423.17
  4964.8  425.11  4971.9  424.03  4993.6  417.76  4994.1  417.26  5006.7  417.76
  5007.2  419.87  5021.4  424.43  5113.3  425.94  5127.4  425.65  5134.5  424.12
  5141.6  425.03  5148.6  423.99  5169.9  424.51  5212.3   427.3    5295  429.16
  5516.3  438.04  5598.6  439.09  5860.5  440.18  6013.5  442.35  6068.8  443.58
#Mann= 7 ,-1 , 0
  3950.4     .16       0  4390.8     .12       0  4993.6     .07       0
  5006.7     .12       0    5295     .16       0  5598.6     .12       0
  6013.5     .16       0
Bank Sta=4964.8,5021.4
XS Rating Curve= 0 ,0
Exp/Cntr=0.3,0.1

Type RM Length L Ch R = 1 ,147943  ,709,709,709
BEGIN DESCRIPTION:
DUCK CREEK 124 0
END DESCRIPTION:
XS GIS Cut Line= 3
      3481587.66     10439025.83      3480940.95     10437901.67
      3480691.39     10437291.87
#Sta/Elev= 30
  3926.1  444.54  4092.9  440.44  4233.8  433.58  4424.9  428.82  4564.3  428.16
    4629  425.31  4672.1  420.96  4693.7  420.32  4752.6  420.09    4790  422.48
  4854.7  421.59  4907.8  423.79  4966.7  423.84  4980.8  422.16  4997.3  416.87
  4997.8  416.37  5010.4  416.87  5015.6   421.2  5025.7  424.78  5047.2  424.34
  5074.6  428.02  5111.9  430.14    5200  438.15  5244.6  439.43    5270  438.64
  5284.2  440.09    5367  439.27  5444.5  440.19  5575.3  443.88  5881.9   445.6
#Mann= 5 ,-1 , 0
  3926.1     .16       0  4233.8     .12       0  4997.3     .07       0
  5010.4     .12       0    5270     .16       0
Bank Sta=4966.7,5025.7
XS Rating Curve= 0 ,0
Exp/Cntr=0.3,0.1

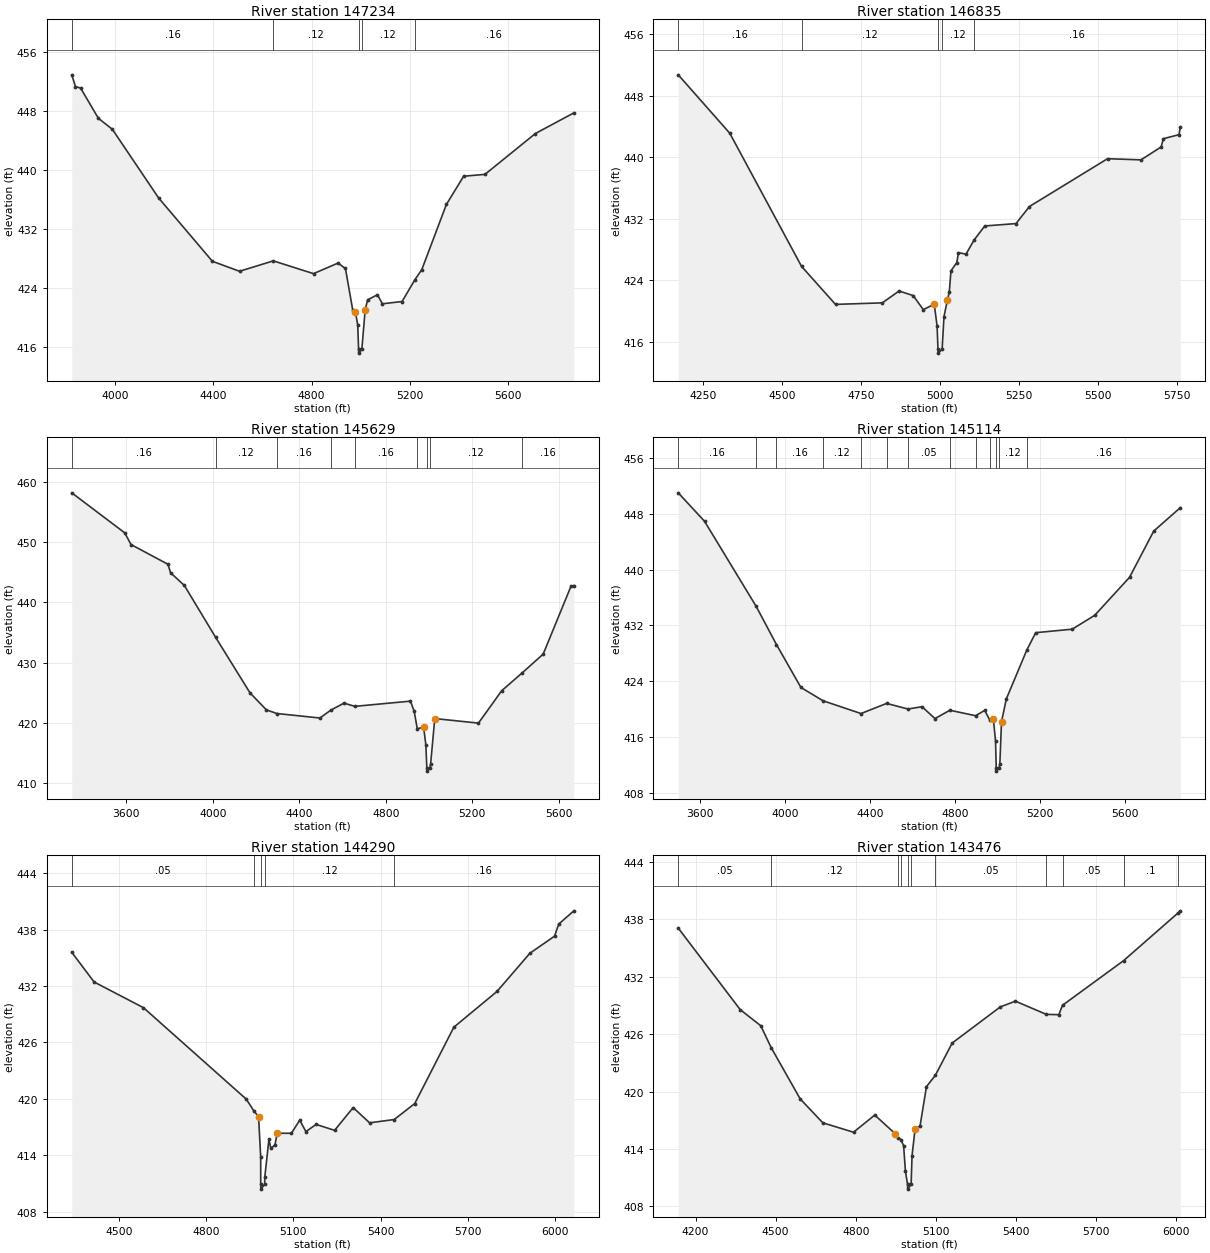
Type RM Length L Ch R = 1 ,147234  ,399,399,399
BEGIN DESCRIPTION:
DUCK CREEK 123 0
END DESCRIPTION:
XS GIS Cut Line= 4
      3482008.67      10438895.6      3481713.52     10438698.11
      3481639.73     10437437.26      3481431.41     10437068.35
#Sta/Elev= 30
  3824.6   452.9  3839.6  451.31  3860.6   451.1  3932.7  447.01  3989.7  445.51
  4177.6  436.21  4396.6  427.61  4506.8  426.26  4644.2  427.67  4807.7  425.94
  4907.4  427.37  4937.5  426.64  4967.5  420.95  4978.4  420.69  4987.6  418.95
    4991  415.66  4991.5  415.16  5004.2  415.66  5017.6  420.97  5027.6  422.38
  5067.7  423.08  5087.7  421.85  5167.9  422.16  5219.5  425.09    5248  426.48
  5348.2  435.33  5418.3  439.15    5505   439.4    5710  444.94  5866.4  447.74
#Mann= 5 ,-1 , 0
  3824.6     .16       0  4644.2     .12       0    4991     .07       0
  5004.2     .12       0  5219.5     .16       0
Bank Sta=4978.4,5017.6
XS Rating Curve= 0 ,0
Exp/Cntr=0.3,0.1

Type RM Length L Ch R = 1 ,146835  ,1206,1206,1206
BEGIN DESCRIPTION:
DUCK CREEK 122 0
END DESCRIPTION:
XS GIS Cut Line= 4
      3482275.59      10438554.9      3482275.59     10438340.04
      3481993.47     10437665.13      3481546.75     10437201.06
#Sta/Elev= 30
  4170.1  450.69  4333.4  443.09  4560.8  425.77  4668.3  420.83  4816.6  421.03
  4869.6  422.57  4914.3  421.98  4946.4  420.15  4981.1  420.85  4990.2  417.99
  4992.9  414.99  4993.4  414.49  5006.1  414.99  5011.9  419.22  5022.7  421.39
  5028.7  422.42  5034.1   425.2  5052.5  426.26  5057.9  427.56  5081.7  427.36
  5107.1  429.19  5141.1  431.03  5240.1  431.34  5282.6  433.56  5530.1  439.78
  5636.1  439.63  5699.9  441.31  5706.8  442.38  5756.5  442.91  5760.6  443.92
#Mann= 5 ,-1 , 0
  4170.1     .16       0  4560.8     .12       0  4992.9     .07       0
  5006.1     .12       0  5107.1     .16       0
Bank Sta=4981.1,5022.7
XS Rating Curve= 0 ,0
Exp/Cntr=0.3,0.1

Type RM Length L Ch R = 1 ,145629  ,515,515,515
BEGIN DESCRIPTION:
DUCK CREEK 120 0
END DESCRIPTION:
XS GIS Cut Line= 3
      3483642.11     10438991.64      3482992.11     10437441.64
       3482592.1     10436941.63
#Sta/Elev= 30
  3348.1  458.25  3592.9  451.59  3622.1  449.64  3792.7  446.36  3804.8  444.95
  3868.6  442.83  4012.8  434.22  4172.2  424.95  4248.1  422.12  4296.3  421.52
  4495.4  420.77  4545.6  422.08  4606.8  423.25  4656.5  422.71  4913.8  423.58
  4931.3  421.87  4945.4  418.97  4974.7  419.26  4985.1  416.29  4989.6  412.43
  4990.1  411.93    5003  412.43  5007.2  413.17  5026.2  420.68  5228.2  419.92
  5335.4   425.3  5431.2  428.31  5527.5  431.41  5655.6  442.67  5669.2  442.82
#Mann= 9 ,-1 , 0
  3348.1     .16       0  4012.8     .12       0  4296.3     .16       0
  4545.6     .12       0  4656.5     .16       0  4945.4     .12       0
  4989.6     .07       0    5003     .12       0  5431.2     .16       0
Bank Sta=4974.7,5026.2
XS Rating Curve= 0 ,0
Exp/Cntr=0.3,0.1

Type RM Length L Ch R = 1 ,145114  ,824,824,824
BEGIN DESCRIPTION:
DUCK CREEK 12 0
END DESCRIPTION:
XS GIS Cut Line= 3
      3483719.06     10438699.03      3483419.54      10437049.6
      3482997.02     10436512.22
#Sta/Elev= 30
  3499.6  451.02  3623.2  446.94  3865.8  434.74  3961.4  429.25  4076.3   423.1
  4180.4  421.19  4358.7  419.36  4479.1  420.81  4579.6  420.01  4645.4  420.34
  4706.4  418.64  4776.6  419.83  4897.4  419.05  4940.2  419.81  4964.7  418.38
  4980.8  418.64    4991  415.42  4994.4   411.6  4994.9   411.1  5007.8   411.6
  5011.3  412.09  5019.1  418.17  5041.8  421.46  5138.5   428.5  5179.9  430.96
  5351.5  431.46  5457.3  433.45  5620.9   438.9  5734.8  445.54  5859.6  448.89
#Mann= 13 ,-1 , 0
  3499.6     .16       0  3865.8     .12       0  3961.4     .16       0
  4180.4     .12       0  4358.7     .16       0  4479.1     .12       0
  4579.6     .05       0  4776.6     .12       0  4897.4     .16       0
  4964.7     .12       0  4994.4     .07       0  5007.8     .12       0
  5138.5     .16       0
Bank Sta=4980.8,5019.1
XS Rating Curve= 0 ,0
Exp/Cntr=0.3,0.1

Type RM Length L Ch R = 1 ,144290  ,814,814,814
BEGIN DESCRIPTION:
DUCK CREEK 118 0
END DESCRIPTION:
XS GIS Cut Line= 2
      3484703.76     10437578.87      3483456.79     10436383.17
#Sta/Elev= 30
  4337.3  435.58  4414.3  432.42  4584.1  429.69  4937.6  419.97  4964.8  418.67
    4980  418.12  4987.3  413.85  4987.5   410.9    4988   410.4  5000.9   410.9
  5001.4  411.66  5015.6  415.68  5022.5  414.72  5036.6  415.12  5043.9  416.34
  5093.2  416.34  5121.6  417.73  5142.9  416.52  5178.2  417.28  5241.7  416.65
  5305.5  419.07  5362.1  417.45  5446.8   417.8  5517.5   419.5  5652.1  427.62
  5800.5  431.42  5913.7  435.48  5998.6   437.3  6012.8  438.58  6064.9  439.99
#Mann= 5 ,-1 , 0
  4337.3     .05       0  4964.8     .12       0  4987.5     .07       0
  5000.9     .12       0  5446.8     .16       0
Bank Sta=4980,5043.9
XS Rating Curve= 0 ,0
Exp/Cntr=0.3,0.1

Type RM Length L Ch R = 1 ,143476  ,491,491,491
BEGIN DESCRIPTION:
DUCK CREEK 117 0
END DESCRIPTION:
XS GIS Cut Line= 3
      3484921.24     10437480.39      3484549.93       10436508.
      3483963.23     10435906.94
#Sta/Elev= 30
  4135.1  437.06  4367.4  428.54  4444.2  426.87    4483  424.59  4591.9  419.23
  4676.8  416.73  4791.7  415.75  4871.3  417.54  4947.3  415.61  4957.5  415.15
  4969.3  414.98  4979.4  414.34  4986.2  411.68  4994.1  410.31  4994.6  409.81
  5007.5  410.31  5010.9  413.29  5022.2  416.06    5041  416.42    5065  420.51
    5098  421.68  5161.4  425.06  5341.5  428.83  5398.1  429.43  5514.2  428.05
  5560.9  428.02  5574.6     429  5803.4  433.66  6005.5  438.59  6015.9  438.86
#Mann= 11 ,-1 , 0
  4135.1     .05       0    4483     .12       0  4957.5     .16       0
  4969.3     .12       0  4994.1     .07       0  5007.5     .12       0
    5098     .05       0  5514.2     .16       0  5574.6     .05       0
  5803.4      .1       0  6005.5     .05       0
Bank Sta=4947.3,5022.2
XS Rating Curve= 0 ,0
Exp/Cntr=0.3,0.1

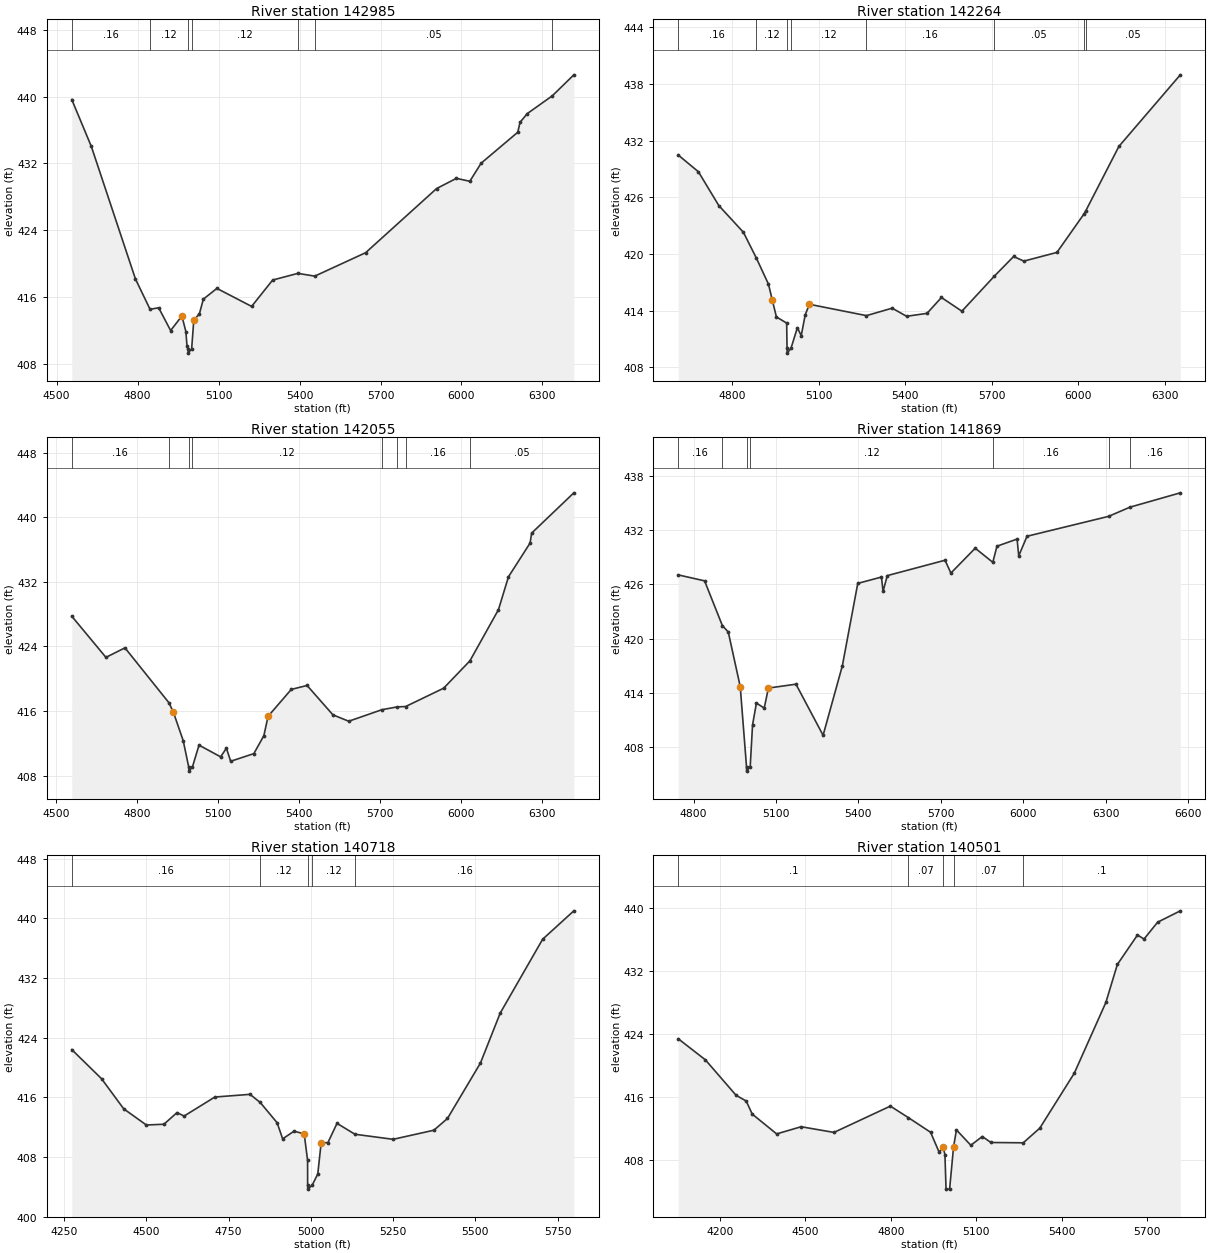
Type RM Length L Ch R = 1 ,142985  ,721,721,721
BEGIN DESCRIPTION:
DUCK CREEK 116 0
END DESCRIPTION:
XS GIS Cut Line= 3
      3485342.08     10437041.61      3485092.11     10436691.64
      3484242.11     10435541.65
#Sta/Elev= 30
  4556.2  439.65  4628.7  434.02  4792.1  418.14  4846.3   414.5  4878.1  414.69
  4922.4  411.96  4964.2   413.7  4978.9  411.84  4983.2  410.07  4986.9  409.75
  4987.4  409.25  5000.3  409.75  5008.2  413.18  5029.1  413.97  5043.7  415.72
  5093.8  417.01  5222.5  414.85  5300.4  418.01  5393.9  418.81  5456.5  418.48
    5645  421.29  5907.9  428.98  5981.1   430.2  6030.8  429.85  6072.9  432.02
  6208.6  435.73    6217  436.92  6244.1  437.97  6336.7   440.1  6416.3  442.61
#Mann= 7 ,-1 , 0
  4556.2     .16       0  4846.3     .12       0  4986.9     .07       0
  5000.3     .12       0  5393.9     .16       0  5456.5     .05       0
  6336.7      .1       0
Bank Sta=4964.2,5008.2
XS Rating Curve= 0 ,0
Exp/Cntr=0.3,0.1

Type RM Length L Ch R = 1 ,142264  ,209,209,209
BEGIN DESCRIPTION:
DUCK CREEK 113 3
END DESCRIPTION:
XS GIS Cut Line= 3
       3485920.2     10436540.82      3485198.82     10435988.72
      3484535.92     10435489.59
#Sta/Elev= 30
  4614.4  430.48  4684.2  428.71  4754.9  425.13  4840.1   422.3  4884.9  419.57
  4926.8  416.81  4939.8  415.16  4954.3  413.34  4989.8  412.69  4991.1  410.01
  4991.6  409.51  5004.6  410.01  5026.9   412.2  5040.2  411.36  5054.1  413.58
  5068.6  414.68    5266  413.48    5355  414.27    5405  413.41  5475.7  413.72
  5525.6   415.4  5596.4  413.95  5708.5  417.65  5775.5  419.74  5810.9  419.25
  5925.4  420.17  6019.3  424.25  6025.2  424.57  6139.9  431.39  6352.6  438.97
#Mann= 8 ,-1 , 0
  4614.4     .16       0  4884.9     .12       0  4991.1     .07       0
  5004.6     .12       0    5266     .16       0  5708.5     .05       0
  6019.3     .16       0  6025.2     .05       0
Bank Sta=4939.8,5068.6
XS Rating Curve= 0 ,0
Exp/Cntr=0.3,0.1

Type RM Length L Ch R = 1 ,142055  ,186,186,186
BEGIN DESCRIPTION:
DUCK CREEK 113 2
END DESCRIPTION:
XS GIS Cut Line= 3
      3485928.55     10436477.24      3485897.77     10436231.05
        3484507.     10435414.64
#Sta/Elev= 30
  4557.1  427.74  4683.7  422.64  4754.2  423.82  4916.7  417.04    4933  415.91
  4970.1  412.33  4990.6  409.05  4991.1  408.55  5004.1  409.05  5028.7  411.77
  5108.8  410.32  5130.3  411.39    5146  409.77  5231.9  410.72    5269  412.94
  5284.7  415.34  5370.6  418.67  5429.2  419.16    5525  415.52  5583.6  414.73
  5706.7  416.16  5764.1  416.51  5794.4  416.55  5935.3  418.82  6032.7  422.21
  6138.4  428.54  6175.6  432.62  6255.7   436.8  6261.5  438.03  6417.9  443.02
#Mann= 8 ,-1 , 0
  4557.1     .16       0  4916.7     .12       0  4990.6     .07       0
  5004.1     .12       0  5706.7     .16       0  5764.1     .05       0
  5794.4     .16       0  6032.7     .05       0
Bank Sta=4933,5284.7
XS Rating Curve= 0 ,0
Exp/Cntr=0.3,0.1

Type RM Length L Ch R = 1 ,141869  ,1151,1151,1151
BEGIN DESCRIPTION:
DUCK CREEK 115 0
END DESCRIPTION:
XS GIS Cut Line= 4
      3486043.41     10436112.05      3485676.21     10435882.29
      3485454.65     10435884.34      3484457.87     10435266.22
#Sta/Elev= 30
  4744.2  427.04  4840.1  426.38  4904.9  421.43  4926.3  420.73  4969.9  414.69
  4992.7  405.85  4993.2  405.35  5006.2  405.85  5014.7  410.46  5028.8  412.87
  5057.2  412.32  5072.5  414.53  5172.7  414.96  5271.5  409.31  5341.5  416.98
  5397.7   426.1  5483.9   426.8  5489.8  425.22  5505.2  426.96  5715.4  428.66
  5736.7  427.24  5825.3  429.99  5889.2  428.43  5904.4  430.21  5977.7     431
  5983.6  429.14  6013.8  431.31  6310.9  433.51    6388  434.52  6571.8  436.11
#Mann= 7 ,-1 , 0
  4744.2     .16       0  4904.9     .12       0  4992.7     .07       0
  5006.2     .12       0  5889.2     .16       0  6310.9     .05       0
    6388     .16       0
Bank Sta=4969.9,5072.5
XS Rating Curve= 0 ,0
Exp/Cntr=0.3,0.1

Type RM Length L Ch R = 1 ,140718  ,217,217,217
BEGIN DESCRIPTION:
DUCK CREEK 114 0
END DESCRIPTION:
XS GIS Cut Line= 3
      3486078.27     10435631.99      3485672.11     10435465.83
      3484616.37     10435203.44
#Sta/Elev= 30
  4272.9  422.41  4363.4  418.51  4430.8  414.47  4499.7   412.3  4553.1   412.4
  4592.9  413.96  4614.5   413.5    4708  416.05  4814.8  416.41    4846  415.32
  4897.2  412.61  4914.2  410.44  4948.7  411.47  4979.7  411.11    4990  407.54
  4990.1   404.2  4990.6   403.7  5003.6   404.2  5020.9  405.72  5031.2   409.9
  5051.8  409.94  5079.5  412.52  5133.9  411.06    5250  410.38    5374   411.6
  5415.4  413.18  5515.5   420.6  5575.6   427.3  5704.7  437.21  5799.6  441.02
#Mann= 5 ,-1 , 0
  4272.9     .16       0    4846     .12       0  4990.1     .07       0
  5003.6     .12       0  5133.9     .16       0
Bank Sta=4979.7,5031.2
XS Rating Curve= 0 ,0
Exp/Cntr=0.3,0.1

Type RM Length L Ch R = 1 ,140501  ,732,732,732
BEGIN DESCRIPTION:
DUCK CREEK 113 4
END DESCRIPTION:
XS GIS Cut Line= 4
3486181.3170479210435605.7431683      3486039.53     10435503.34
      3485648.88      10435221.2      3484553.01     10435080.15
#Sta/Elev= 30
    4054  423.41 4149.34  420.73    4257  416.23  4292.6   415.5  4313.5  413.85
  4399.3  411.33  4485.2  412.24  4600.5  411.52  4798.3  414.86  4861.3   413.4
  4939.4  411.54  4969.7  408.99  4983.2  409.73  4989.8  408.69  4993.7  404.32
  5006.2  404.32  5020.1  409.69  5030.2  411.84  5080.6  409.89  5120.9     411
  5151.2  410.24  5264.5   410.2  5322.6  412.06  5443.6  419.03  5554.5  428.02
  5594.8  432.84  5665.4  436.58  5688.5  436.07  5735.9   438.2  5815.7  439.65
#Mann= 5 ,-1 , 0
    4054      .1       0  4861.3     .07       0  4983.2     .03       0
  5020.1     .07       0  5264.5      .1       0
Bank Sta=4983.2,5020.1
XS Rating Curve= 0 ,0
Exp/Cntr=0.3,0.1

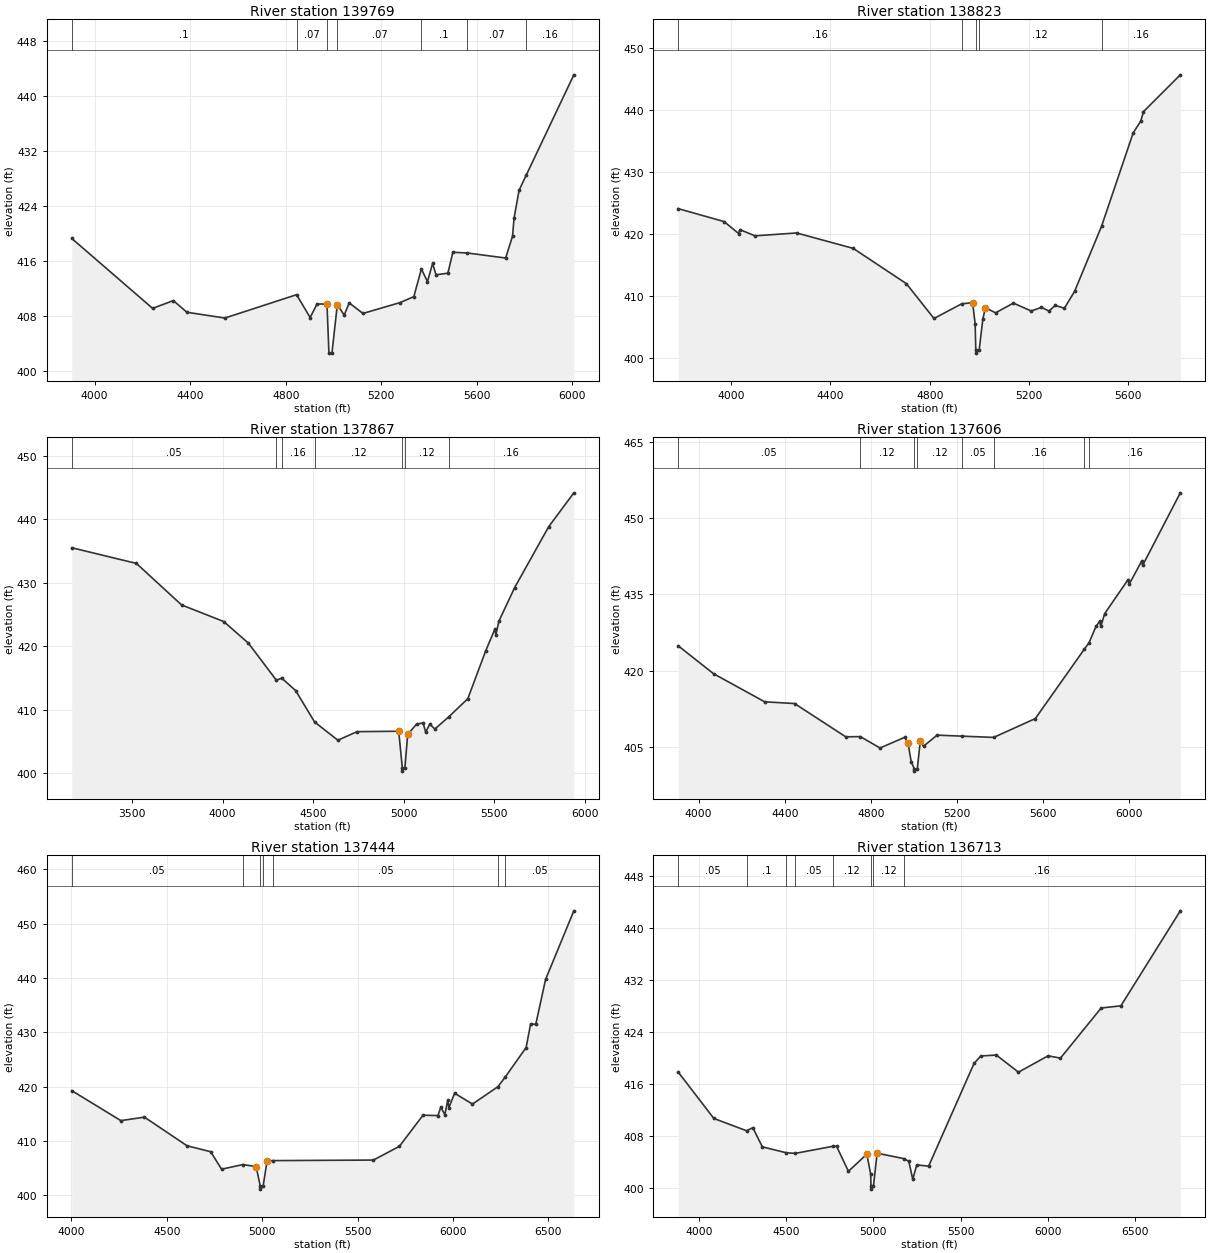
Type RM Length L Ch R = 1 ,139769  ,946,946,946
BEGIN DESCRIPTION:
DUCK CREEK 113 1
END DESCRIPTION:
XS GIS Cut Line= 3
      3486158.85     10435383.94      3485703.13     10434711.22
       3484900.2     10433702.14
#Sta/Elev= 30
  3904.1  419.28  4242.5   409.1  4329.4  410.23  4386.3  408.53    4545  407.69
  4845.3  411.09  4902.2  407.76    4931  409.75  4972.7  409.71  4980.8  402.58
  4993.4  402.58  5015.9  409.63  5044.8  408.12  5065.6   409.9  5123.3  408.36
  5278.6  409.94  5336.3  410.81    5368  414.84  5393.4  412.99  5414.8  415.65
  5429.2  413.99  5478.8  414.22  5499.6  417.27  5558.8  417.17  5720.7  416.43
  5749.5  419.61  5755.9  422.23  5776.8  426.29  5807.7  428.56  6006.2  443.11
#Mann= 7 ,-1 , 0
  3904.1      .1       0  4845.3     .07       0  4972.7     .05       0
  5015.9     .07       0    5368      .1       0  5558.8     .07       0
  5807.7     .16       0
Bank Sta=4972.7,5015.9
XS Rating Curve= 0 ,0
Exp/Cntr=0.3,0.1

Type RM Length L Ch R = 1 ,138823  ,956,956,956
BEGIN DESCRIPTION:
DUCK CREEK 113 0
END DESCRIPTION:
XS GIS Cut Line= 3
      3486162.97     10435660.17      3486366.11     10434912.72
      3486082.25     10433696.57
#Sta/Elev= 30
  3786.6  424.16  3971.6  422.07  4029.9  420.15    4035  420.78    4096  419.77
  4263.4  420.24  4491.8  417.75    4706  412.06  4817.3  406.44  4929.5  408.82
    4973  408.98  4983.3  405.54  4985.8  401.35  4986.3  400.85  4999.4  401.35
  5014.1  406.33  5024.4  408.19  5065.4  407.35  5137.3  408.92  5209.2  407.65
  5250.3  408.23  5281.1  407.64  5305.7  408.55  5342.7  408.09  5383.8   410.8
  5492.5  421.31    5620  436.38  5650.8   438.3  5661.4  439.81    5810  445.75
#Mann= 5 ,-1 , 0
  3786.6     .16       0  4929.5     .12       0  4985.8     .07       0
  4999.4     .12       0  5492.5     .16       0
Bank Sta=4973,5024.4
XS Rating Curve= 0 ,0
Exp/Cntr=0.3,0.1

Type RM Length L Ch R = 1 ,137867  ,261,261,261
BEGIN DESCRIPTION:
DUCK CREEK 111 0
END DESCRIPTION:
XS GIS Cut Line= 5
      3487837.47     10435568.98      3487624.12     10434744.89
      3487085.51     10434192.12      3486776.17     10433751.12
      3486175.42     10433633.96
#Sta/Elev= 30
  3167.1   435.5  3524.2  433.03  3773.8  426.49  4006.3  423.88  4142.3  420.49
    4297  414.65  4327.6  414.95  4403.9     413  4508.6  408.05  4637.2  405.18
  4743.4  406.53  4973.4  406.59  4993.2  400.81  4993.7  400.31  5007.6  400.81
  5022.8  406.09  5071.9  407.71  5108.3  407.92  5122.4  406.43    5145  407.72
    5173  406.94  5249.4  408.85  5355.3  411.73  5453.4  419.22    5505  422.71
  5510.1  421.78  5526.5  423.91  5613.3  429.19  5801.6   438.8  5940.9  444.15
#Mann= 7 ,-1 , 0
  3167.1     .05       0    4297      .1       0  4327.6     .16       0
  4508.6     .12       0  4993.2     .07       0  5007.6     .12       0
  5249.4     .16       0
Bank Sta=4973.4,5022.8
XS Rating Curve= 0 ,0
Exp/Cntr=0.3,0.1

Type RM Length L Ch R = 1 ,137606  ,162,162,162
BEGIN DESCRIPTION:
DUCK CREEK 110 2
END DESCRIPTION:
XS GIS Cut Line= 3
      3488103.91     10434496.83      3486515.35     10433444.73
      3486095.29     10433379.91
#Sta/Elev= 30
  3905.7  424.87  4069.4   419.4  4307.1  413.87  4445.5  413.54  4683.1     407
  4750.9  407.04  4842.6   404.8  4956.9  406.91    4972  405.79    4987  402.13
  5000.9  400.76  5001.4  400.26  5015.3  400.76  5029.1  406.08  5044.2  405.15
  5107.3  407.33  5223.1  407.13  5369.6  406.88  5563.1  410.58    5791  424.24
  5812.7   425.5  5844.7  428.68    5862  429.67  5867.1  428.68  5885.2   431.2
  5993.3  437.86  5998.4  436.94  6056.5  441.49  6061.5   440.7  6236.1  454.92
#Mann= 8 ,-1 , 0
  3905.7     .05       0  4750.9     .12       0  5000.9     .07       0
  5015.3     .12       0  5223.1     .05       0  5369.6     .16       0
    5791     .05       0  5812.7     .16       0
Bank Sta=4972,5029.1
XS Rating Curve= 0 ,0
Exp/Cntr=0.3,0.1

Type RM Length L Ch R = 1 ,137444  ,731,731,731
BEGIN DESCRIPTION:
DUCK CREEK 109 1
END DESCRIPTION:
XS GIS Cut Line= 4
      3488165.56     10434355.41      3487135.05     10433682.01
      3486061.42     10432980.43      3485959.41     10432921.03
#Sta/Elev= 30
    4002  419.25  4259.3  413.73    4383  414.37  4606.2   409.1  4729.9  408.01
  4787.2  404.79  4898.5  405.64  4968.2  405.28  4990.4  401.62  4990.9  401.12
  5004.8  401.62  5025.5   406.3  5055.4  406.37    5583  406.47  5719.2     409
    5843  414.73  5921.3  414.66  5936.4  416.22  5957.5  414.82  5972.6  417.49
  5978.6  416.13  6008.8  418.77  6102.3  416.78  6235.8  419.98  6273.4  421.73
  6383.3  427.17    6407  431.52  6434.1  431.47  6485.4  439.72  6633.6  452.35
#Mann= 7 ,-1 , 0
    4002     .05       0  4898.5     .12       0  4990.4     .07       0
  5004.8     .12       0  5055.4     .05       0  6235.8     .16       0
  6273.4     .05       0
Bank Sta=4968.2,5025.5
XS Rating Curve= 0 ,0
Exp/Cntr=0.3,0.1

Type RM Length L Ch R = 1 ,136713  ,1406,1406,1406
BEGIN DESCRIPTION:
DUCK CREEK 11 0
END DESCRIPTION:
XS GIS Cut Line= 3
      3488186.44     10434287.76      3487405.17      10432647.1
      3486639.53     10431912.71
#Sta/Elev= 30
  3881.7  417.77  4085.9  410.64  4273.4  408.75  4309.4  409.22  4363.9  406.27
  4501.8  405.36  4552.8  405.27  4766.5  406.35  4789.2  406.37  4857.3  402.51
  4962.8  405.15    4985  402.05  4986.4  400.27  4986.9  399.77  5000.8  400.27
  5021.8   405.3  5177.3  404.45  5203.5  404.03  5226.2  401.27  5248.9   403.5
    5317   403.3  5577.8  419.13  5616.3  420.25  5704.8   420.4  5832.2  417.76
    6002  420.28  6072.7  419.92  6306.1  427.63  6419.3  427.97  6759.8  442.58
#Mann= 8 ,-1 , 0
  3881.7     .05       0  4273.4      .1       0  4501.8     .12       0
  4552.8     .05       0  4766.5     .12       0  4986.4     .07       0
  5000.8     .12       0  5177.3     .16       0
Bank Sta=4962.8,5021.8
XS Rating Curve= 0 ,0
Exp/Cntr=0.3,0.1

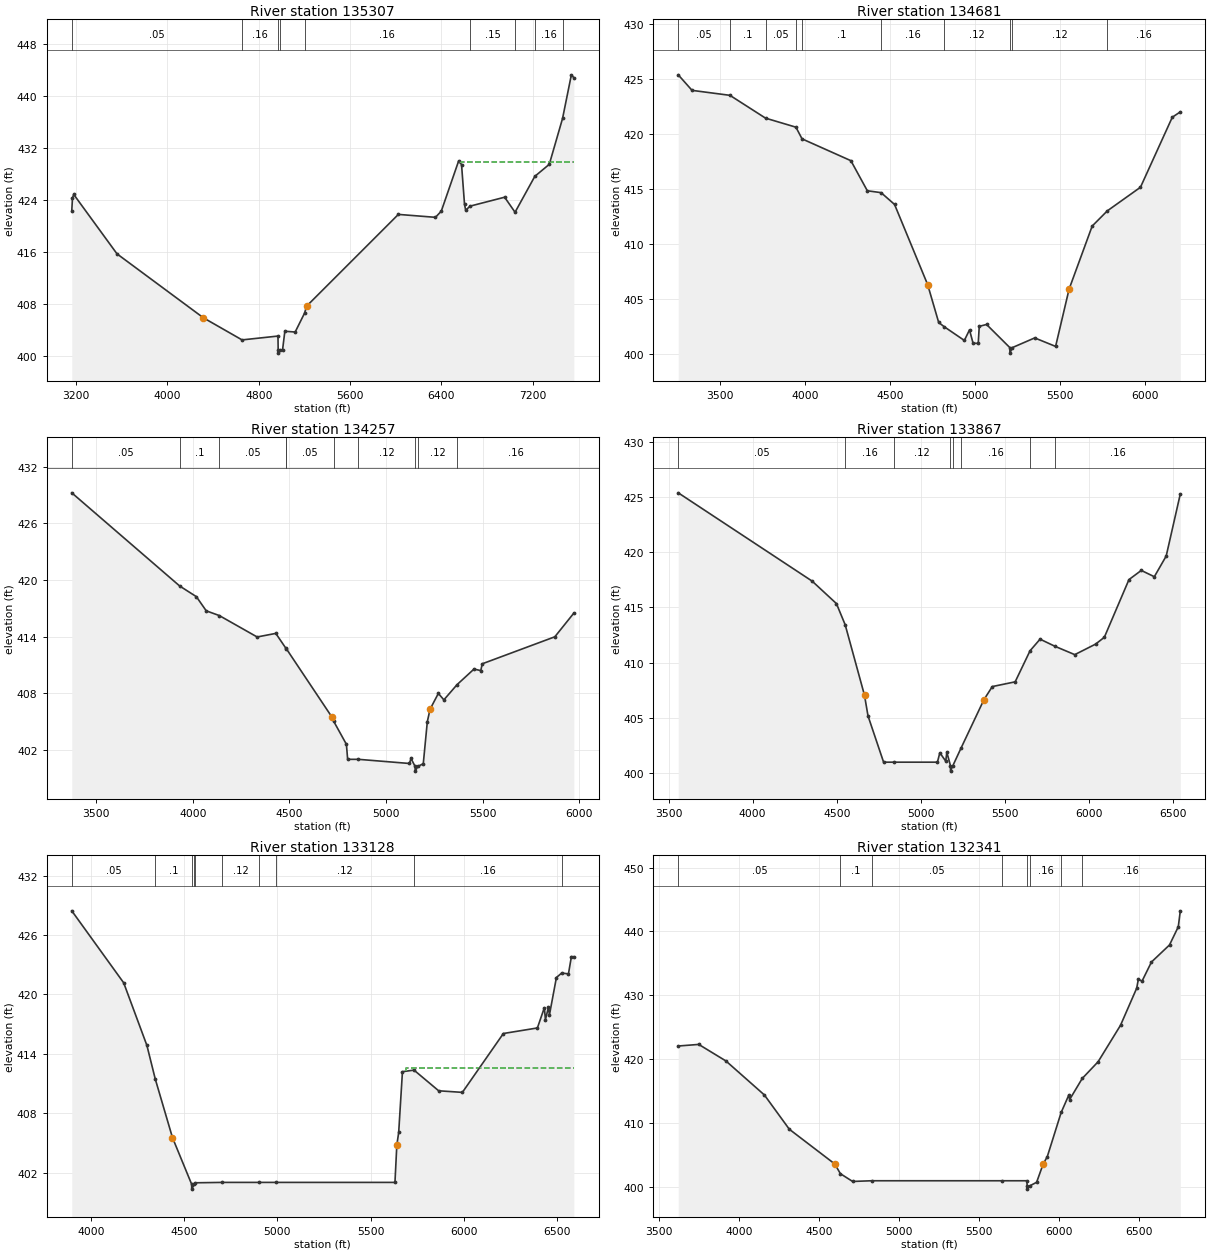
Type RM Length L Ch R = 1 ,135307  ,626,626,626
BEGIN DESCRIPTION:
DUCK CREEK 109 2
END DESCRIPTION:
XS GIS Cut Line= 4
      3488417.12      10434577.5      3488629.78     10433956.89
      3488412.77     10431725.98      3488134.99     10430250.27
#Sta/Elev= 30
  3161.4  422.36  3167.6   424.3  3178.2  424.87  3557.9  415.74    4315  405.92
  4653.4  402.53  4968.1  403.12  4969.9     401  4970.4   400.5  4984.4     401
  5008.3     401  5028.4  403.86  5118.8  403.74  5200.8  406.63  5219.3  407.72
    6023   421.8  6348.2  421.35  6399.1   422.3  6551.7  430.04  6576.6  429.44
  6602.6  423.35  6612.8  422.44  6651.4  423.07    6954  424.44  7045.3  422.13
  7218.5  427.64  7345.4  429.49  7461.7  436.54  7538.8  443.23  7560.5  442.79
#Mann= 9 ,-1 , 0
  3161.4     .05       0  4653.4     .16       0  4969.9     .07       0
  4984.4     .16       0  5200.8     .16       0  6651.4     .15       0
  7045.3     .12       0  7218.5     .16       0  7461.7     .12       0
#XS Ineff= 2 , 0
                         6563.49          429.81
Permanent Ineff=
       F       F
Bank Sta=4315,5219.3
XS Rating Curve= 0 ,0
Exp/Cntr=0.3,0.1

Type RM Length L Ch R = 1 ,134681  ,424,424,424
BEGIN DESCRIPTION:
Mapping XS 3ea73d8d
END DESCRIPTION:
XS GIS Cut Line= 4
      3489302.71     10434232.01      3489370.41      10433763.3
      3489508.43     10433239.86      3488451.14     10431617.47
#Sta/Elev= 30
  3256.2  425.36  3337.4  423.95  3560.1   423.5  3769.4  421.43    3948  420.61
    3984  419.55  4271.1  417.57  4367.8  414.84  4448.6  414.67  4527.8   413.6
  4722.5  406.32  4787.3  402.89  4819.3  402.51  4938.1  401.26  4968.4  402.22
  4989.5     401  5019.7     401  5025.7  402.54  5068.7  402.71  5205.5  400.61
    5206  400.11    5220  400.61  5351.7  401.49  5474.5  400.72  5553.9  405.92
  5689.6  411.64  5778.7  413.02  5973.4  415.16  6160.4  421.51  6207.6     422
#Mann= 10 ,-1 , 0
  3256.2     .05       0  3560.1      .1       0  3769.4     .05       0
    3948     .16       0    3984      .1       0  4448.6     .16       0
  4819.3     .12       0  5205.5     .07       0    5220     .12       0
  5778.7     .16       0
Bank Sta=4722.5,5553.9
XS Rating Curve= 0 ,0
Exp/Cntr=0.3,0.1

Type RM Length L Ch R = 1 ,134257  ,390,390,390
BEGIN DESCRIPTION:
DUCK CREEK 109 0
END DESCRIPTION:
XS GIS Cut Line= 3
      3490192.13     10433641.68      3489480.77     10432396.81
      3488592.89     10431642.23
#Sta/Elev= 30
  3373.4  429.23    3932  419.36  4018.4  418.23  4069.5  416.73    4137  416.23
    4333  413.96  4429.5  414.34  4482.6  412.74  4483.9  412.72    4721  405.45
  4729.2  405.03  4795.1  402.59  4801.5     401  4857.4     401  5121.6  400.56
  5129.3   401.1  5150.6  400.25  5151.1  399.75  5165.2  400.25    5193  400.54
  5213.9  404.99  5228.2  406.31    5271  407.98  5299.6   407.3  5368.3  408.92
  5455.5  410.56  5490.6   410.4  5498.4  411.12    5874  413.98  5972.4  416.49
#Mann= 10 ,-1 , 0
  3373.4     .05       0    3932      .1       0    4137     .05       0
  4482.6      .1       0  4483.9     .05       0  4729.2     .16       0
  4857.4     .12       0  5150.6     .07       0  5165.2     .12       0
  5368.3     .16       0
Bank Sta=4721,5228.2
XS Rating Curve= 0 ,0
Exp/Cntr=0.3,0.1

Type RM Length L Ch R = 1 ,133867  ,739,739,739
BEGIN DESCRIPTION:
DUCK CREEK 107 0
END DESCRIPTION:
XS GIS Cut Line= 4
      3490178.51     10433364.34      3489939.47     10432414.08
      3489243.04     10431543.54      3488390.16     10431280.89
#Sta/Elev= 30
  3557.1  425.37  4353.9  417.38  4498.2  415.35  4550.4  413.43  4665.3  407.05
  4686.1  405.19  4778.9     401  4842.2     401  5099.1     401  5113.5  401.85
  5148.7  401.09  5155.1   401.9  5176.6  400.69  5177.1  400.19  5191.2  400.69
  5238.9  402.25    5376  406.66  5425.6  407.84  5561.7  408.27  5650.2  411.08
  5709.8  412.13  5799.1  411.48  5916.3  410.73  6039.9  411.68  6092.2   412.3
  6238.7  417.52    6312  418.35  6389.6  417.78  6460.2  419.65  6544.2  425.27
#Mann= 8 ,-1 , 0
  3557.1     .05       0  4550.4     .16       0  4842.2     .12       0
  5176.6     .07       0  5191.2     .12       0  5238.9     .16       0
  5650.2     .12       0  5799.1     .16       0
#XS Ineff= 2 , 0
                         5709.77          411.98
Permanent Ineff=
       F       F
Bank Sta=4665.3,5376
XS Rating Curve= 0 ,0
Exp/Cntr=0.3,0.1

Type RM Length L Ch R = 1 ,133128  ,787,787,787
BEGIN DESCRIPTION:
DUCK CREEK 106 0
END DESCRIPTION:
XS GIS Cut Line= 4
      3490942.78     10431658.62      3490588.69     10431466.82
       3489130.9     10431375.34      3488415.48     10430960.21
#Sta/Elev= 30
  3897.9  428.45  4176.2  421.17  4300.6  414.84    4345  411.47  4437.5  405.53
  4540.2  400.82  4540.7  400.32  4555.1  400.82  4557.1  400.96  4704.9     401
  4902.4     401  4991.4     401  5629.8     401  5639.8  404.77  5649.8  406.05
  5669.9  412.19  5731.9  412.35    5864  410.26  5991.1   410.1  6210.8  416.05
  6393.1  416.61  6430.4  418.66  6436.2  417.44  6451.9  418.69  6457.7  417.94
    6495  421.71  6523.2  422.16  6559.5  422.08  6575.3  423.82  6588.4  423.81
#Mann= 10 ,-1 , 0
  3897.9     .05       0    4345      .1       0  4540.2     .07       0
  4555.1      .1       0  4557.1     .16       0  4704.9     .12       0
  4902.4     .16       0  4991.4     .12       0  5731.9     .16       0
  6523.2     .15       0
#XS Ineff= 2 , 0
                         5691.34          412.59
Permanent Ineff=
       F       F
Bank Sta=4437.5,5639.8
XS Rating Curve= 0 ,0
Exp/Cntr=0.3,0.1

Type RM Length L Ch R = 1 ,132341  ,634,634,634
BEGIN DESCRIPTION:
DUCK CREEK 105 0
END DESCRIPTION:
XS GIS Cut Line= 4
      3490998.28     10431336.66      3490336.38     10430707.31
      3489500.87      10430577.1      3488156.26     10430273.48
#Sta/Elev= 30
  3621.8  422.08    3750  422.33  3919.9  419.74  4160.2  414.42  4315.9  409.06
  4599.8  403.63  4635.3   402.1  4711.5  400.89  4829.8     401  5646.4     401
  5799.8     401  5802.6  400.19  5803.1  399.69  5817.5  400.19  5861.3  400.76
  5902.3  403.63  5927.8  404.76  6014.6  411.68  6062.5  414.41  6067.7  413.71
  6146.2     417  6245.6  419.62  6385.5  425.32  6486.7  431.13  6496.9  432.51
  6520.2  432.24  6578.9  435.22  6691.7  437.89  6746.5  440.73  6759.2  443.23
#Mann= 8 ,-1 , 0
  3621.8     .05       0  4635.3      .1       0  4829.8     .05       0
  5646.4     .16       0  5802.6    .033       0  5817.5     .16       0
  6014.6     .12       0  6146.2     .16       0
Bank Sta=4599.8,5902.3
XS Rating Curve= 0 ,0
Exp/Cntr=0.3,0.1