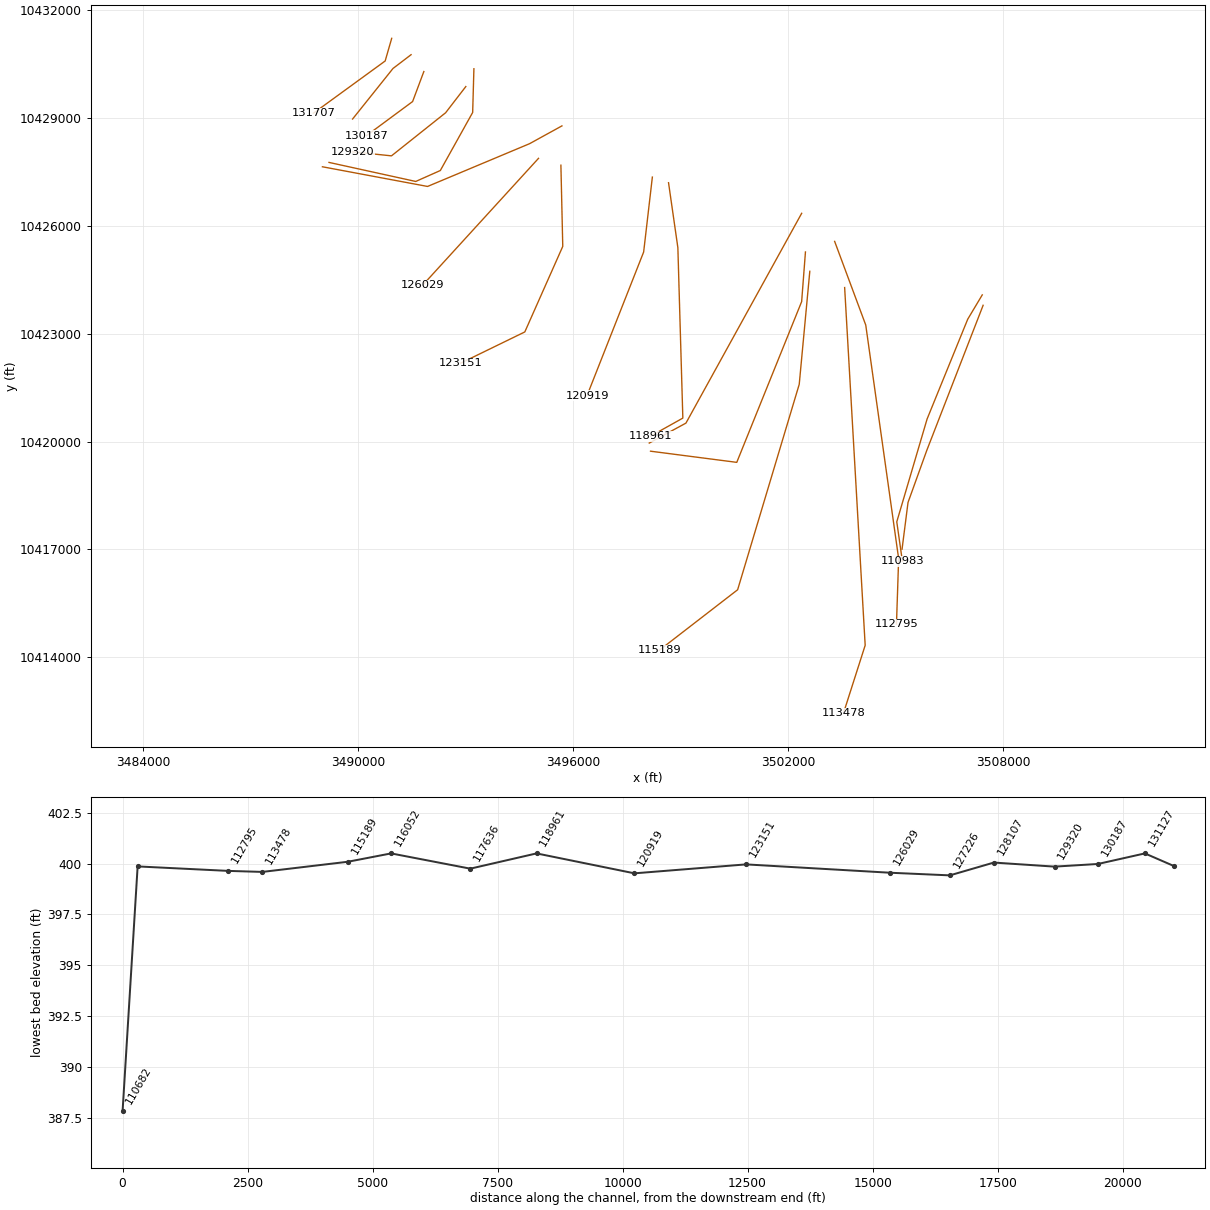
HEC-RAS study DUCK CREEK.prj: DUCK CREEK Base Level Engineering

--- DUCK CREEK.g01 (geometry) --- (continued)

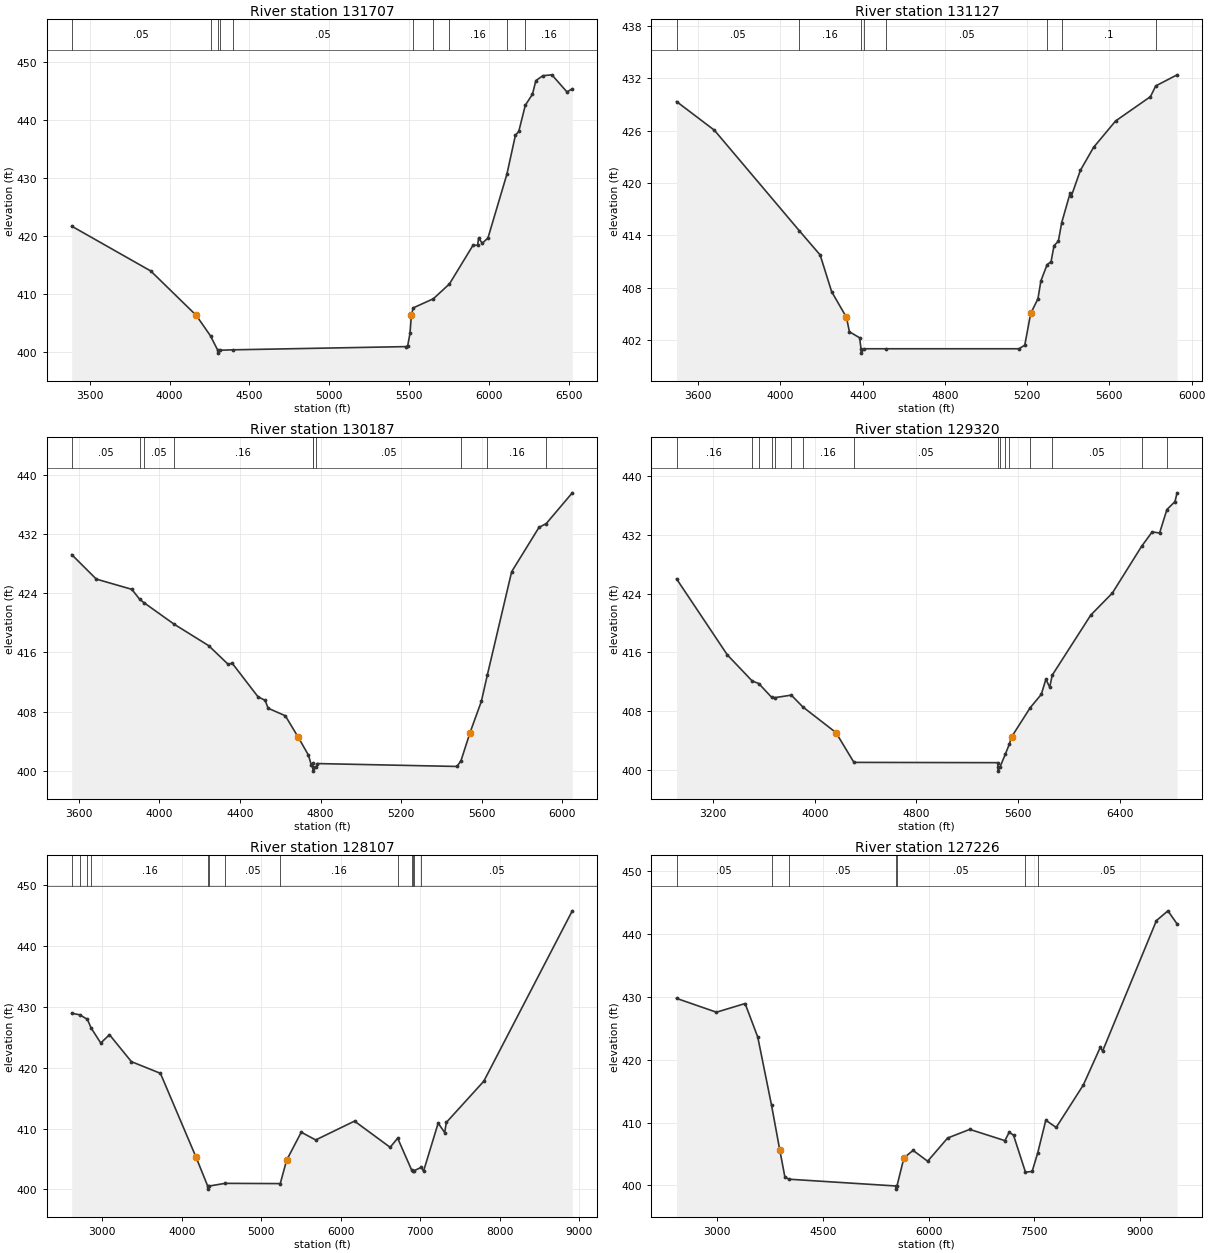
Type RM Length L Ch R = 1 ,131707  ,580,580,580
BEGIN DESCRIPTION:
DUCK CREEK 104 0
END DESCRIPTION:
XS GIS Cut Line= 3
      3490934.39     10431212.23      3490751.88     10430582.07
      3488747.74     10429128.89
#Sta/Elev= 30
  3388.1  421.73  3882.4  414.02  4166.9  406.39  4256.6  402.84  4301.7  400.38
  4302.2  399.88  4316.7  400.38  4398.4  400.45  5476.7     401  5489.8  401.12
  5504.5  403.27    5513  406.36  5524.1  407.66    5651  409.24  5751.3  411.79
    5898  418.41  5927.4  418.47  5933.8  419.69  5956.8  418.78  5992.4  419.71
  6110.6  430.67    6164  437.38  6184.9  438.03  6225.9  442.54  6270.7  444.44
    6292  446.78  6335.7  447.62  6392.1  447.77  6486.4  444.83  6519.7  445.36
#Mann= 10 ,-1 , 0
  3388.1     .05       0  4256.6      .1       0  4301.7    .033       0
  4316.7      .1       0  4398.4     .05       0  5524.1     .16       0
    5651      .1       0  5751.3     .16       0  6110.6      .1       0
  6225.9     .16       0
Bank Sta=4166.9,5513
XS Rating Curve= 0 ,0
Exp/Cntr=0.3,0.1

Type RM Length L Ch R = 1 ,131127  ,940,940,940
BEGIN DESCRIPTION:
DUCK CREEK 103 0
END DESCRIPTION:
XS GIS Cut Line= 3
      3491475.05     10430757.14       3490971.6     10430375.21
      3489843.11     10428968.94
#Sta/Elev= 30
  3494.3  429.33  3678.6  426.04  4091.1  414.54  4192.9  411.75  4248.9  407.54
  4320.9   404.6  4335.3  402.95  4384.9  402.26  4391.8     401  4392.3   400.5
  4406.8     401  4513.4     401  5159.5     401  5188.3  401.41  5217.1  405.05
  5252.3  406.72  5266.7  408.78  5296.8  410.63  5316.3  410.99  5330.7  412.83
  5351.5  413.31    5368  415.46  5409.1  418.85  5415.5  418.54  5458.7  421.44
  5522.7  424.07  5629.9   427.1  5799.6  429.89  5825.4  431.12  5929.3  432.39
#Mann= 8 ,-1 , 0
  3494.3     .05       0  4091.1     .16       0  4391.8    .033       0
  4406.8     .16       0  4513.4     .05       0  5296.8     .16       0
    5368      .1       0  5825.4     .16       0
Bank Sta=4320.9,5217.1
XS Rating Curve= 0 ,0
Exp/Cntr=0.3,0.1

Type RM Length L Ch R = 1 ,130187  ,867,867,867
BEGIN DESCRIPTION:
DUCK CREEK 171 0
END DESCRIPTION:
XS GIS Cut Line= 3
      3491830.99     10430288.45      3491518.48     10429455.08
      3490233.75     10428508.89
#Sta/Elev= 30
  3564.1   429.2  3686.3  425.89  3862.5  424.51  3902.3  423.15  3922.3  422.72
    4072  419.82  4244.2  416.91  4339.6  414.43  4361.7  414.52  4489.2  410.01
  4524.7  409.53  4539.3  408.47  4624.9  407.45  4689.7  404.52  4739.8  402.13
  4754.5  400.74    4760  401.04  4761.6  400.48  4762.1  399.98  4776.6  400.48
  4783.8     401  5477.2  400.61  5497.1  401.39    5542  405.18  5598.3   409.4
  5627.9  412.95  5748.7  426.89  5884.5  432.87  5920.4  433.38  6049.7  437.53
#Mann= 10 ,-1 , 0
  3564.1     .05       0  3902.3      .1       0  3922.3     .05       0
    4072     .16       0    4760     .05       0  4761.6    .033       0
  4776.6     .05       0  5497.1     .12       0  5627.9     .16       0
  5920.4      .1       0
Bank Sta=4689.7,5542
XS Rating Curve= 0 ,0
Exp/Cntr=0.3,0.1

Type RM Length L Ch R = 1 ,129320  ,1213,1213,1213
BEGIN DESCRIPTION:
DUCK CREEK 99 0
END DESCRIPTION:
XS GIS Cut Line= 4
      3493002.86     10429871.75      3492438.62     10429142.58
       3490928.2     10427944.66      3489845.12      10428057.3
#Sta/Elev= 30
  2912.8  426.01  3312.8  415.66  3508.3  412.11  3559.8  411.77  3661.9  409.88
  3687.9  409.85  3815.9  410.19  3906.4  408.59  4167.4  405.09  4308.6  401.04
  5441.2     401  5441.8  400.35  5442.3  399.85  5456.8  400.35  5499.7  402.15
  5531.4  403.52  5548.6  404.49  5694.9  408.46  5782.8  410.29    5819  412.35
  5849.1  411.27  5869.1  412.91  6172.2  421.08  6341.8  424.07  6571.7  430.42
  6655.1  432.39  6713.8  432.25  6771.3  435.44  6834.4  436.51  6851.5  437.71
#Mann= 16 ,-1 , 0
  2912.8     .16       0  3508.3     .05       0  3559.8     .16       0
  3661.9     .05       0  3687.9     .16       0  3815.9     .05       0
  3906.4     .16       0  4308.6     .05       0  5441.8    .033       0
  5456.8     .05       0  5499.7     .16       0  5531.4     .12       0
  5694.9     .16       0  5869.1     .05       0  6571.7     .16       0
  6771.3     .05       0
Bank Sta=4167.4,5548.6
XS Rating Curve= 0 ,0
Exp/Cntr=0.3,0.1

Type RM Length L Ch R = 1 ,128107  ,881,881,881
BEGIN DESCRIPTION:
DUCK CREEK 100 0
END DESCRIPTION:
XS GIS Cut Line= 5
      3493228.55     10430366.56      3493193.83     10429151.26
      3492291.05     10427536.67      3491605.28     10427232.85
      3489185.24     10427761.97
#Sta/Elev= 30
  2616.5  428.97  2715.1  428.74  2813.4  427.99  2861.4  426.54  2981.6  424.09
  3091.6  425.45    3367  421.02  3731.9   419.1  4177.6  405.37  4326.5  400.55
    4327  400.05  4341.5  400.55  4544.3     401  5238.3  400.96  5318.5  404.82
  5502.3  409.41  5684.3  408.14  6171.8  411.24  6619.7  406.93  6714.2  408.43
  6891.6  403.14  6910.3  402.96  6924.8   403.1  7011.2  403.64  7039.4     403
  7223.6  410.91  7305.5  409.35    7326  411.02  7796.9   417.8  8909.4  445.83
#Mann= 13 ,-1 , 0
  2616.5     .05       0  2715.1     .16       0  2813.4     .05       0
  2861.4     .16       0  4326.5    .033       0  4341.5     .16       0
  4544.3     .05       0  5238.3     .16       0  6714.2     .12       0
  6891.6     .16       0  6910.3     .12       0  6924.8     .16       0
  7011.2     .05       0
Bank Sta=4177.6,5318.5
XS Rating Curve= 0 ,0
Exp/Cntr=0.3,0.1

Type RM Length L Ch R = 1 ,127226  ,1197,1197,1197
BEGIN DESCRIPTION:
DUCK CREEK 97 0
END DESCRIPTION:
XS GIS Cut Line= 4
      3495685.13     10428777.98      3494782.37      10428283.2
      3491935.14     10427093.96      3489001.14     10427640.84
#Sta/Elev= 30
  2425.7  429.75  2991.9  427.55  3398.4  428.93    3578  423.59  3773.1  412.77
  3890.8   405.6  3962.3  401.37    4018     401  5537.2  399.92  5537.7  399.42
  5552.2  399.92  5650.8  404.39  5780.7  405.58  5987.4  403.86    6271  407.55
  6584.5  408.92    7083  407.13    7144  408.47    7205     408  7374.8  402.12
  7469.5  402.23  7549.1  405.21  7662.8  410.37  7810.4  409.23  8194.7  415.97
  8435.9  421.97  8468.5  421.37    9232  442.12  9395.2  443.67  9525.3  441.58
#Mann= 7 ,-1 , 0
  2425.7     .05       0  3773.1     .16       0    4018     .05       0
  5537.2    .033       0  5552.2     .05       0  7374.8     .12       0
  7549.1     .05       0
Bank Sta=3890.8,5650.8
XS Rating Curve= 0 ,0
Exp/Cntr=0.3,0.1

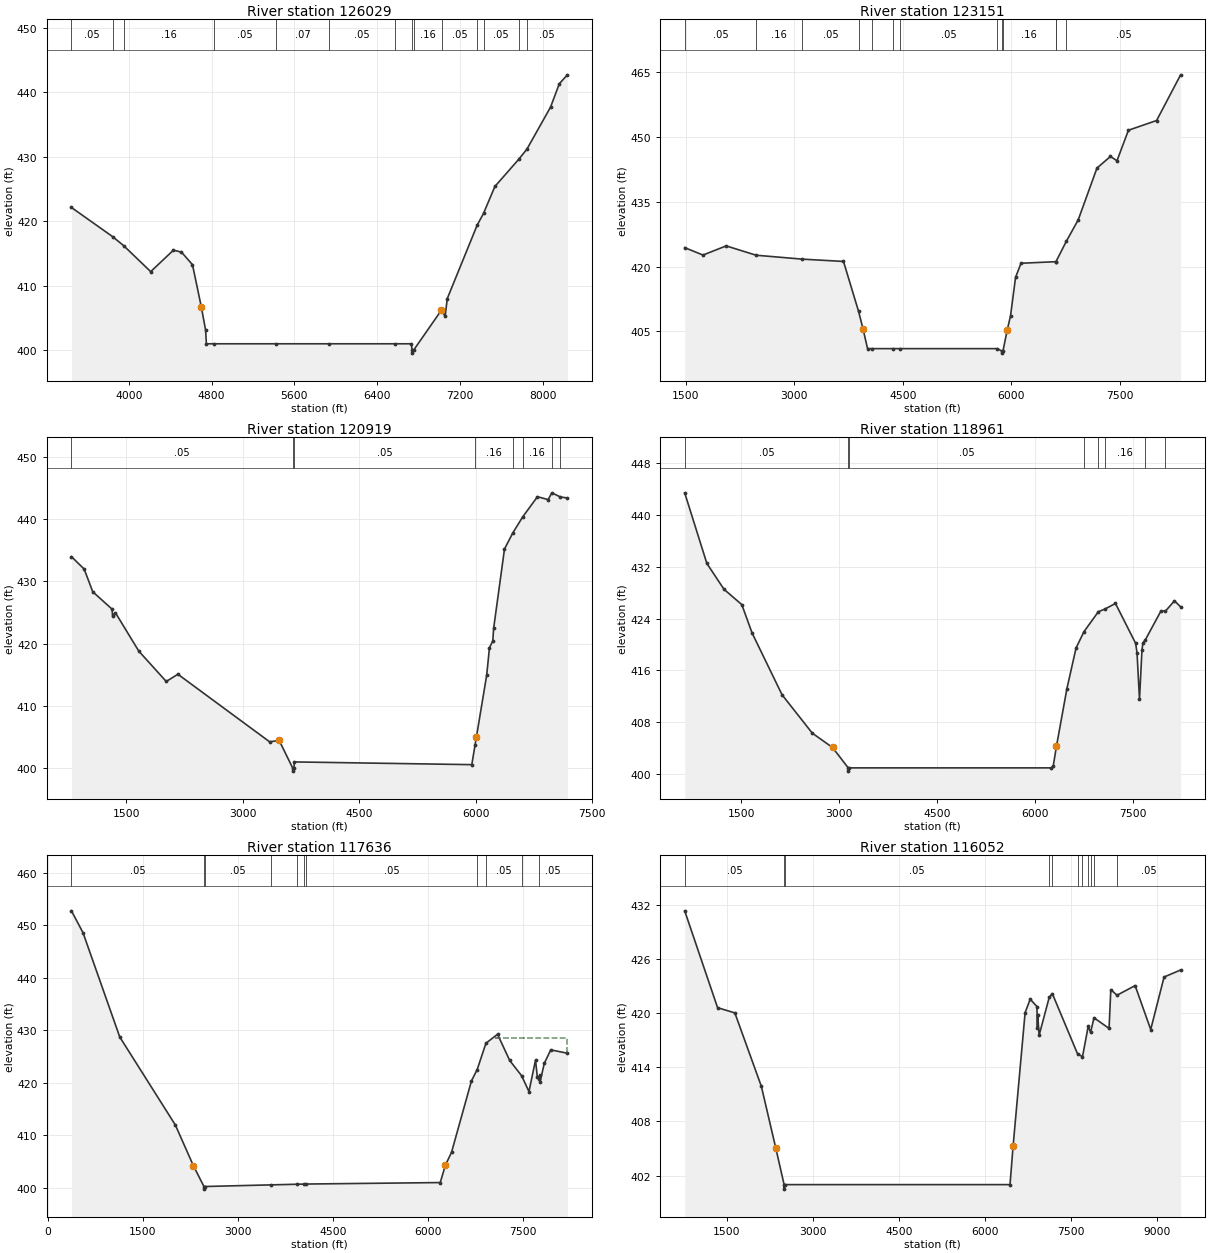
Type RM Length L Ch R = 1 ,126029  ,2878,2878,2878
BEGIN DESCRIPTION:
DUCK CREEK 96 1
END DESCRIPTION:
XS GIS Cut Line= 2
      3495031.06     10427875.14      3491792.09     10424341.63
#Sta/Elev= 30
  3446.3  422.14  3845.8   417.6  3950.2  416.23  4212.2  412.19  4431.7  415.52
  4509.4  415.22  4616.1  413.27  4700.6  406.78  4743.1   403.1  4750.5     401
  4827.4     401  5420.4     401  5937.6     401  6573.7     401  6732.3     401
    6738  400.05  6738.5  399.55    6755  400.05  7022.2  406.21  7023.9  406.16
  7057.9  405.26  7078.9  408.02  7367.4  419.39  7429.3  421.23  7538.9   425.4
  7771.8  429.66  7848.8   431.2  8076.9  437.71  8161.7  441.34  8239.7  442.72
#Mann= 14 ,-1 , 0
  3446.3     .05       0  3845.8     .12       0  3950.2     .16       0
  4827.4     .05       0  5420.4     .07       0  5937.6     .05       0
  6573.7     .16       0    6738    .033       0    6755     .16       0
  7023.9     .05       0  7367.4     .16       0  7429.3     .05       0
  7771.8      .1       0  7848.8     .05       0
Bank Sta=4700.6,7022.2
XS Rating Curve= 0 ,0
Exp/Cntr=0.3,0.1

Type RM Length L Ch R = 1 ,123151  ,2232,2232,2232
BEGIN DESCRIPTION:
DUCK CREEK 96 0
END DESCRIPTION:
XS GIS Cut Line= 4
      3495656.07     10427684.18      3495708.16     10425427.24
      3494649.13     10423048.77      3492860.92      10422180.7
#Sta/Elev= 30
  1488.4  424.39    1741  422.67  2061.1  424.79  2475.1  422.63  3115.1  421.72
  3681.5  421.19  3889.8  409.62  3949.9  405.66  4014.1     401  4071.8     401
  4365.4     401  4455.2     401  5805.9     401  5867.1  400.46  5867.6  399.96
  5884.2  400.46  5941.7  405.24  5988.2  408.58  6057.9  417.51  6133.1  420.77
    6610  421.13  6613.5  421.06  6757.8  425.82  6922.8  430.81  7182.1  442.81
  7368.9  445.51  7458.5   444.5  7616.4  451.57  8005.6  453.82  8337.3   464.4
#Mann= 13 ,-1 , 0
  1488.4     .05       0  2475.1     .16       0  3115.1     .05       0
  3889.8      .1       0  4071.8     .05       0  4365.4     .07       0
  4455.2     .05       0  5805.9     .16       0  5867.1    .033       0
  5884.2     .16       0    6610     .05       0  6613.5     .16       0
  6757.8     .05       0
Bank Sta=3949.9,5941.7
XS Rating Curve= 0 ,0
Exp/Cntr=0.3,0.1

Type RM Length L Ch R = 1 ,120919  ,1958,1958,1958
BEGIN DESCRIPTION:
DUCK CREEK 92 0
END DESCRIPTION:
XS GIS Cut Line= 3
      3498208.15      10427354.3       3497965.1     10425270.99
      3496385.23     10421277.91
#Sta/Elev= 30
   791.6  433.97   955.4  431.97  1066.1  428.33  1315.6  425.53  1320.6  424.49
  1358.1  424.96  1659.3   418.8  2013.2  413.92  2163.5  415.08  3345.5  404.23
  3469.1  404.44  3642.7  400.02  3643.2  399.52  3661.1  400.02  3662.6     401
  5951.5  400.56  5992.2  403.64  6010.9     405  6143.4  414.95  6179.1  419.35
  6221.8  420.43  6232.9  422.46  6372.7   435.2  6479.6  437.78  6607.7  440.36
  6797.6   443.6  6935.4  443.13  6982.8  444.22  7092.3  443.56  7183.3  443.39
#Mann= 8 ,-1 , 0
   791.6     .05       0  3642.7    .033       0  3661.1     .05       0
  5992.2     .16       0  6479.6     .05       0  6607.7     .16       0
  6982.8     .05       0  7092.3      .1       0
Bank Sta=3469.1,6010.9
XS Rating Curve= 0 ,0
Exp/Cntr=0.3,0.1

Type RM Length L Ch R = 1 ,118961  ,1325,1325,1325
BEGIN DESCRIPTION:
DUCK CREEK 85 0
END DESCRIPTION:
XS GIS Cut Line= 4
      3498659.55     10427198.05      3498919.96     10425392.52
      3499058.85     10420652.93      3498156.61     10420149.76
#Sta/Elev= 30
   634.8  443.36   974.7  432.48  1237.4   428.5  1510.2  426.14  1667.6  421.77
  2126.5  412.26  2589.9  406.35  2900.1  404.14  3140.8     401  3141.3   400.5
  3159.5     401  6251.5     401  6281.5  401.26  6331.6  404.34  6491.6  413.21
  6631.7  419.47    6753  421.98  6973.3  425.05  7071.3  425.45  7235.5  426.32
  7544.1  420.19  7565.8  418.73  7603.5  411.54  7641.2  419.09  7654.9  420.24
  7692.6  420.71  7933.8  425.19  7999.5  425.12  8139.5  426.73  8233.7   425.8
#Mann= 8 ,-1 , 0
   634.8     .05       0  3140.8    .033       0  3159.5     .05       0
    6753      .1       0  6973.3     .05       0  7071.3     .16       0
  7692.6      .1       0  7999.5     .05       0
#XS Ineff= 2 , 0
                         7045.06          424.71
Permanent Ineff=
       F       F
Bank Sta=2900.1,6331.6
XS Rating Curve= 0 ,0
Exp/Cntr=0.3,0.1

Type RM Length L Ch R = 1 ,117636  ,1584,1584,1584
BEGIN DESCRIPTION:
DUCK CREEK 8 0
END DESCRIPTION:
XS GIS Cut Line= 3
      3502374.82     10426347.37      3499145.66     10420514.05
      3498121.38      10419958.5
#Sta/Elev= 30
   370.6  452.75     553  448.58  1133.5  428.72  2011.6  411.96  2297.4  404.18
  2463.2  400.25  2463.7  399.75  2483.2  400.25    3521  400.56  3925.7  400.68
  4042.5  400.71  4082.2  400.72    6195     401  6275.9  404.28  6373.3  406.76
  6688.1  420.36  6778.8  422.53  6917.2  427.54  7100.1  429.24  7292.4  424.25
    7480  421.35  7596.4  418.33    7700  424.32  7727.6  421.18    7756  420.67
  7765.6  421.43  7771.3  420.13  7838.4  423.71  7940.8  426.27  8203.3  425.63
#Mann= 11 ,-1 , 0
   370.6     .05       0  2463.2    .033       0  2483.2     .05       0
    3521     .07       0  3925.7     .05       0  4042.5     .07       0
  4082.2     .05       0  6778.8      .1       0  6917.2     .05       0
    7480     .16       0    7756     .05       0
#XS Ineff= 2 , 0
                         7062.61          428.62
Permanent Ineff=
       F       F
Bank Sta=2297.4,6275.9
XS Rating Curve= 0 ,0
Exp/Cntr=0.3,0.1

Type RM Length L Ch R = 1 ,116052  ,863,863,863
BEGIN DESCRIPTION:
DUCK CREEK 78 0
END DESCRIPTION:
XS GIS Cut Line= 4
      3502480.26     10425272.44      3502374.13     10423891.35
      3500563.63      10419422.2       3498156.6     10419732.73
#Sta/Elev= 30
   770.6  431.36  1343.1  420.62    1644  420.04  2105.3   411.9    2358  405.01
  2501.5     401    2502   400.5  2521.5     401  6434.6     401  6488.2  405.28
  6697.3  420.07  6785.8  421.56  6902.8  420.75  6911.7  418.42  6917.1  419.79
  6941.2  417.56  7116.4  421.75  7171.2  422.18  7609.4  415.51  7696.4  415.18
  7796.5  418.57  7837.2  417.88  7896.7   419.5    8159  418.32  8189.5  422.62
  8297.3     422  8612.7  423.07    8884   418.2  9116.8  424.02  9404.7   424.8
#Mann= 11 ,-1 , 0
   770.6     .05       0  2501.5    .033       0  2521.5     .05       0
  7116.4      .1       0  7171.2     .05       0  7609.4      .1       0
  7696.4     .05       0  7796.5     .15       0  7837.2      .1       0
  7896.7     .15       0  8297.3     .05       0
Bank Sta=2358,6488.2
XS Rating Curve= 0 ,0
Exp/Cntr=0.3,0.1

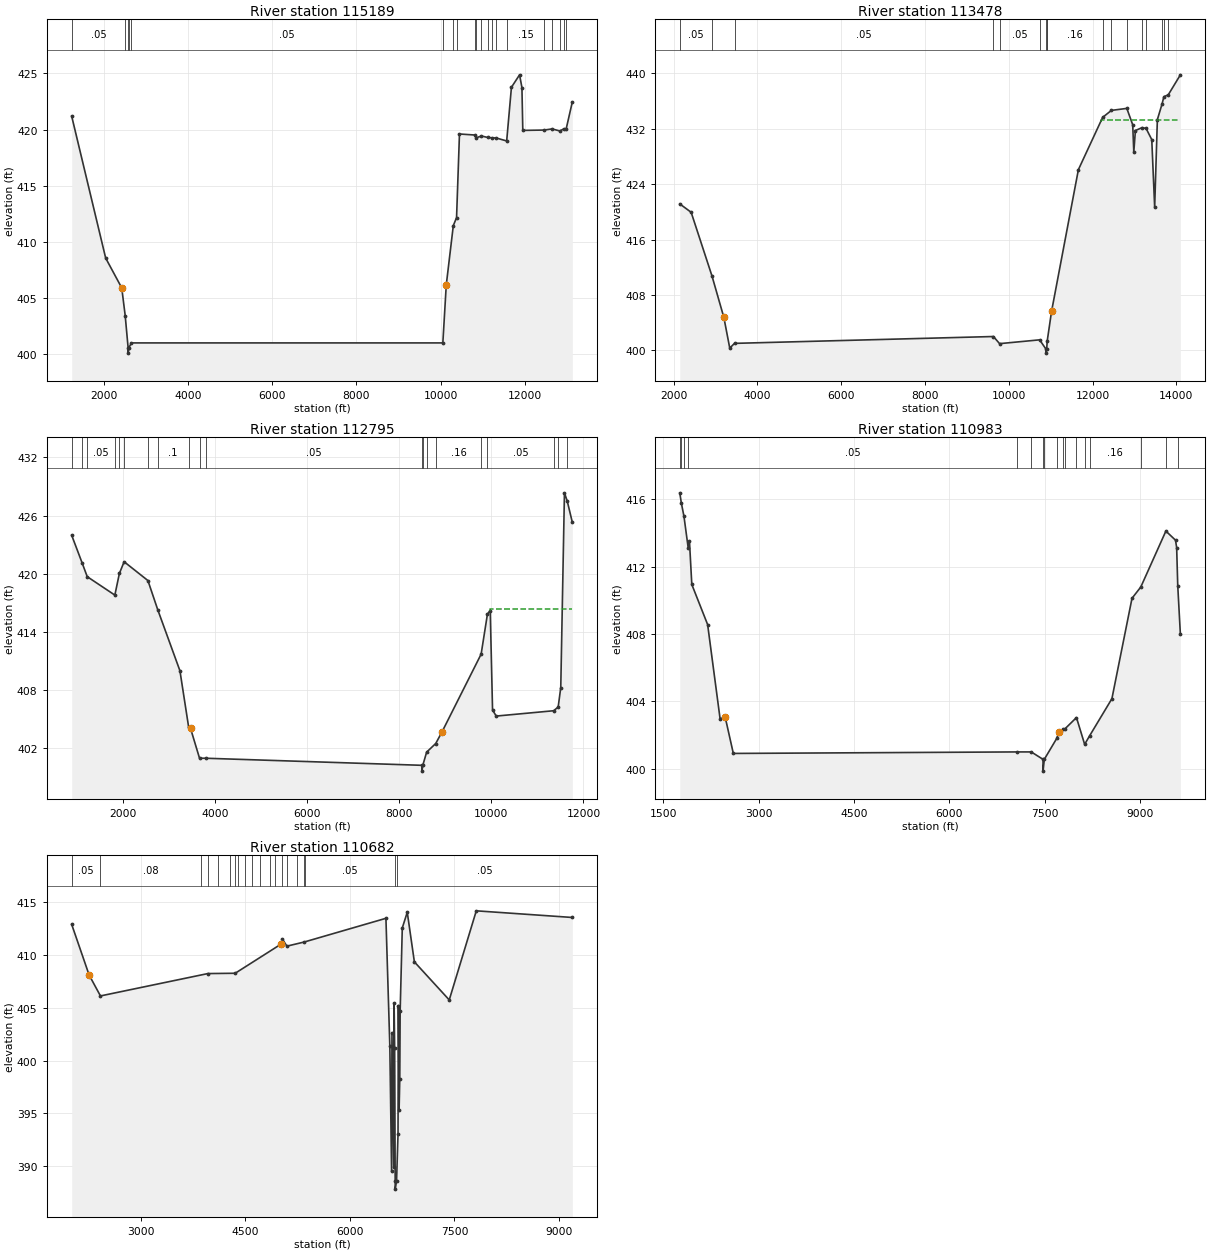
Type RM Length L Ch R = 1 ,115189  ,1711,1711,1711
BEGIN DESCRIPTION:
Mapping XS c6f8a44a
END DESCRIPTION:
XS GIS Cut Line= 4
      3502601.79     10424734.22      3502306.65     10421591.85
       3500587.9     10415880.05      3498400.82     10414196.34
#Sta/Elev= 30
  1241.4  421.19  2047.5  408.56  2429.2   405.9    2511  403.44  2579.9  400.59
  2580.4  400.09  2599.9  400.59  2660.4     401 10049.9     401   10131  406.16
 10298.4  411.45 10375.4  412.16 10444.5  419.61 10802.3  419.52 10838.1  419.27
   10967  419.43 11115.5   419.3   11209  419.27 11320.2  419.25   11565  418.99
 11677.7  423.77 11870.7  424.88 11926.8  423.75 11947.6  419.93 12452.9  419.96
 12642.4  420.06 12829.1  419.88   12926  420.08 12975.5  420.04 13122.5  422.46
#Mann= 20 ,-1 , 0
  1241.4     .05       0    2511      .1       0  2579.9    .033       0
  2599.9      .1       0  2660.4     .05       0 10049.9      .1       0
 10298.4     .05       0 10375.4      .1       0 10802.3     .08       0
 10838.1      .1       0   10967     .08       0 11115.5     .08       0
   11209      .1       0 11320.2      .1       0   11565     .15       0
 12452.9     .15       0 12642.4     .05       0 12829.1     .15       0
   12926     .05       0 12975.5     .15       0
Bank Sta=2429.2,10131
XS Rating Curve= 0 ,0
Exp/Cntr=0.3,0.1

Type RM Length L Ch R = 1 ,113478  ,683,683,683
BEGIN DESCRIPTION:
DUCK CREEK 76 0
END DESCRIPTION:
XS GIS Cut Line= 3
      3503574.01     10424282.83      3504146.93     10414334.91
       3503539.3     10412442.58
#Sta/Elev= 30
  2145.8  421.15  2417.4  419.94  2914.7  410.74  3198.7  404.74    3339  400.32
  3453.3     401  9633.6  401.99  9781.3  400.96 10737.3  401.51 10886.2  400.19
 10886.7  399.59 10906.2  400.19 10917.7  401.31 11021.7  405.61 11662.7   426.1
 12241.7  433.65 12450.5  434.66 12819.2  434.95 12959.6  432.58 12985.4  428.64
 13023.8  431.75 13181.5  432.17 13278.7  432.06 13414.4  430.44 13483.8  420.67
 13548.1  433.33   13660  435.58 13703.7  436.64 13808.1  436.91 14097.7   439.8
#Mann= 17 ,-1 , 0
  2145.8     .05       0  2914.7     .16       0  3453.3     .05       0
  9633.6     .16       0  9781.3     .05       0 10737.3      .1       0
 10886.2    .033       0 10906.2      .1       0 10917.7     .16       0
 12241.7     .05       0 12450.5      .1       0 12819.2     .16       0
 13181.5     .05       0 13278.7     .16       0   13660      .1       0
 13703.7     .16       0 13808.1      .1       0
#XS Ineff= 2 , 0
                        12190.75          433.25
Permanent Ineff=
       F       F
Bank Sta=3198.7,11021.7
XS Rating Curve= 0 ,0
Exp/Cntr=0.3,0.1

Type RM Length L Ch R = 1 ,112795  ,1812,1812,1812
BEGIN DESCRIPTION:
DUCK CREEK 74 0
END DESCRIPTION:
XS GIS Cut Line= 4
      3503294.96     10425566.14      3504163.02     10423239.74
      3505080.96     10416744.05      3505020.19     10414921.17
#Sta/Elev= 30
   892.2  423.97  1119.3  421.11  1229.3   419.7    1829   417.8  1927.2  420.03
  2030.4  421.24  2546.6   419.3  2759.4   416.3  3241.9  409.99  3431.9  404.15
  3472.6  404.04  3667.3  400.97    3799  400.97  8493.8  400.24  8494.3  399.64
  8513.8  400.24  8597.3   401.6  8794.5  402.49    8928  403.66  9780.3  411.71
    9917  415.84  9977.9  416.21   10028  405.94   10108  405.32 11354.1  405.87
 11452.5  406.25 11508.8  408.26 11588.8  428.35 11649.1   427.5 11759.4  425.32
#Mann= 20 ,-1 , 0
   892.2     .05       0  1119.3      .1       0  1229.3     .05       0
    1829     .08       0  1927.2     .05       0  2030.4      .1       0
  2546.6     .05       0  2759.4      .1       0  3431.9     .16       0
  3667.3     .16       0    3799     .05       0  8493.8    .033       0
  8513.8      .1       0  8597.3     .05       0  8794.5     .16       0
  9780.3      .1       0    9917     .05       0 11354.1      .1       0
 11452.5     .16       0 11649.1     .05       0
#XS Ineff= 2 , 0
                         9963.72          416.37
Permanent Ineff=
       F       F
Bank Sta=3472.6,8928
XS Rating Curve= 0 ,0
Exp/Cntr=0.3,0.1

Type RM Length L Ch R = 1 ,110983  ,301,301,301
BEGIN DESCRIPTION:
DUCK CREEK 71 0
END DESCRIPTION:
XS GIS Cut Line= 5
      3507414.44     10424078.91      3507008.86     10423403.25
      3505874.74      10420627.2      3505028.87     10417768.36
      3505184.98     10416675.63
#Sta/Elev= 30
  1760.5  416.38    1785  415.78  1826.6  414.98    1893  413.11  1912.8  413.51
  1949.7  410.94  2198.5  408.56  2394.7  402.96  2474.4  403.07  2602.5  400.91
  7070.4     401  7287.2     401  7472.6  400.56  7473.1  399.86  7492.6  400.56
  7687.8   401.8  7720.6  402.16  7791.4  402.36    7820  402.38  7998.5  403.04
  8127.1  401.45  8205.7  401.96  8555.7  404.16  8871.8  410.12    9010  410.79
  9404.4  414.11  9555.7  413.57  9573.9  413.13  9591.1  410.86  9632.5  407.98
#Mann= 17 ,-1 , 0
  1760.5      .1       0    1785     .05       0  1826.6      .1       0
    1893     .05       0  7070.4      .1       0  7287.2     .05       0
  7472.6    .033       0  7492.6     .05       0  7687.8     .16       0
  7791.4     .05       0    7820     .16       0  7998.5      .1       0
  8127.1     .05       0  8205.7     .16       0    9010     .05       0
  9404.4      .1       0  9591.1     .05       0
Bank Sta=2474.4,7720.6
XS Rating Curve= 0 ,0
Exp/Cntr=0.3,0.1

Type RM Length L Ch R = 1 ,110682  ,259,259,259
BEGIN DESCRIPTION:
DUCK CREEK 68 1
END DESCRIPTION:
XS GIS Cut Line= 4
      3507438.16     10423788.91       3505863.2     10419747.17
      3505342.65     10418307.45      3505175.98      10417008.8
#Sta/Elev= 30
  2011.3  412.92  2261.3  408.12  2423.6  406.14  3963.4  408.26  4355.6  408.29
  5012.2  411.05  5033.4  411.52  5096.7  410.86  5343.7  411.25  6516.9   413.5
  6572.9  401.37  6598.2   389.5  6603.5  402.66  6628.9  389.89  6634.2  405.44
    6642  401.19  6649.5  388.62    6650  387.82  6669.5  388.62  6690.2  393.02
  6695.5  405.23  6705.8  395.36  6715.5  398.28  6720.8  404.68  6751.5  412.59
  6822.8  414.07  6924.8  409.37  7424.7  405.76  7812.6  414.21  9189.3  413.58
#Mann= 20 ,-1 , 0
  2011.3     .05       0  2423.6     .08       0  3861.6     .15       0
  3963.4     .05       0  4108.6     .15       0  4284.4      .1       0
  4355.6     .15       0  4391.4      .1       0  4498.4     .05       0
  4602.6      .1       0  4712.4     .05       0  4849.7      .1       0
  4926.4     .15       0  5033.4     .05       0  5096.7     .15       0
  5247.4     .05       0  5343.7     .15       0  5354.4     .05       0
  6649.5     .07       0  6669.5     .05       0
#Block Obstruct= 2 , 0
                          5169.1          404.66
Bank Sta=2261.3,5012.2
XS Rating Curve= 0 ,0
Exp/Cntr=0.3,0.1