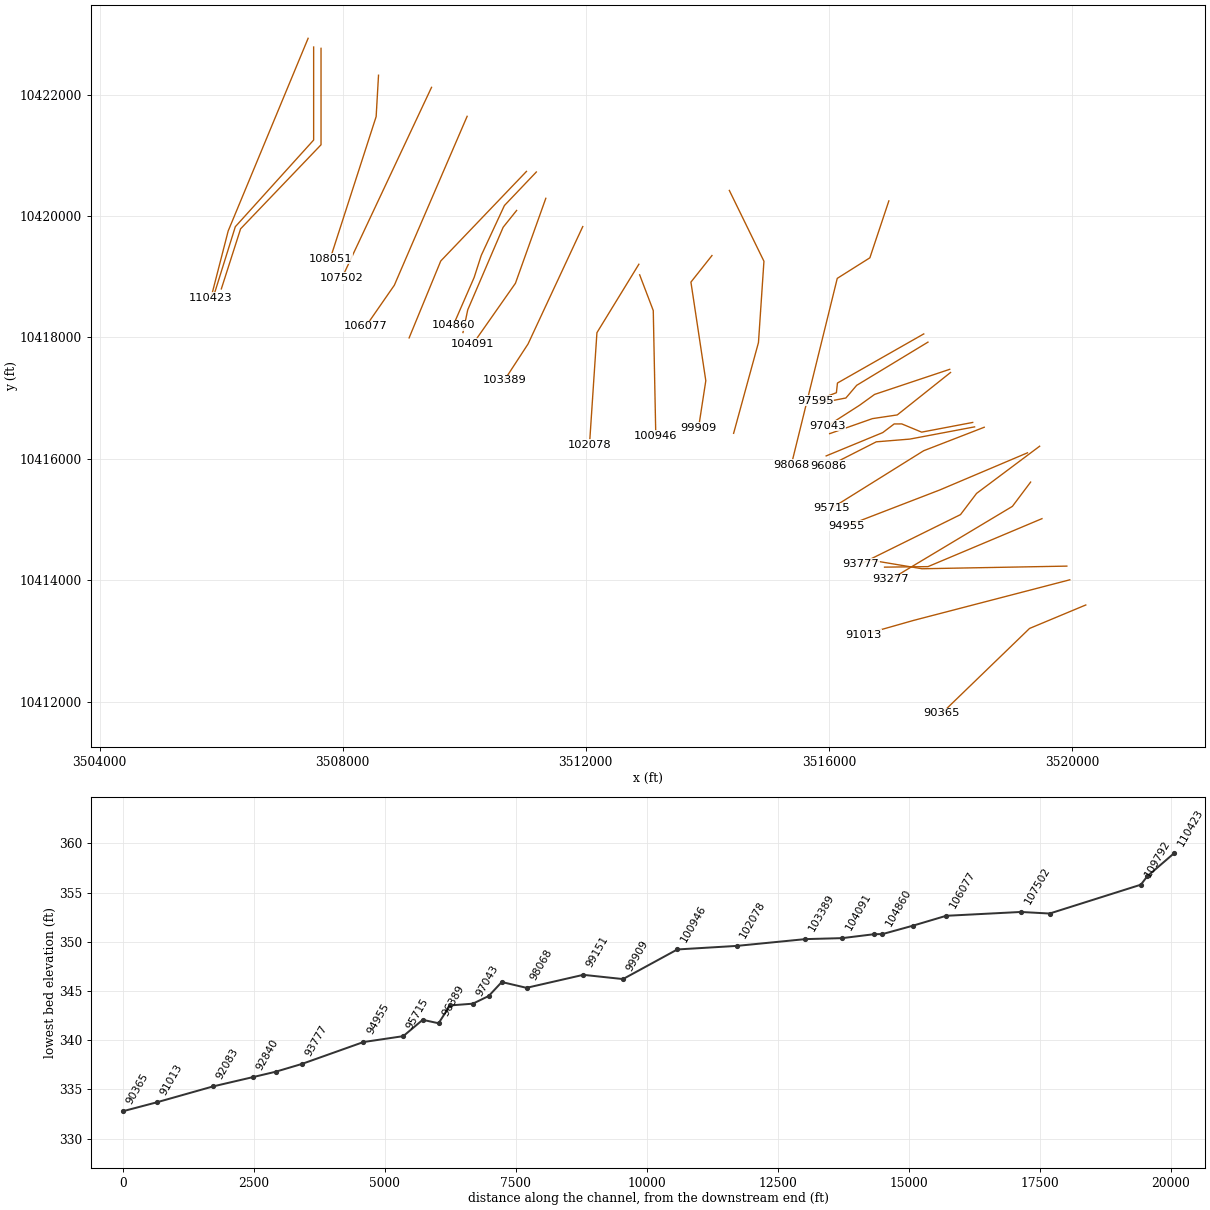
HEC-RAS study DUCK CREEK.prj: DUCK CREEK Base Level Engineering

--- DUCK CREEK.g01 (geometry) --- (continued)

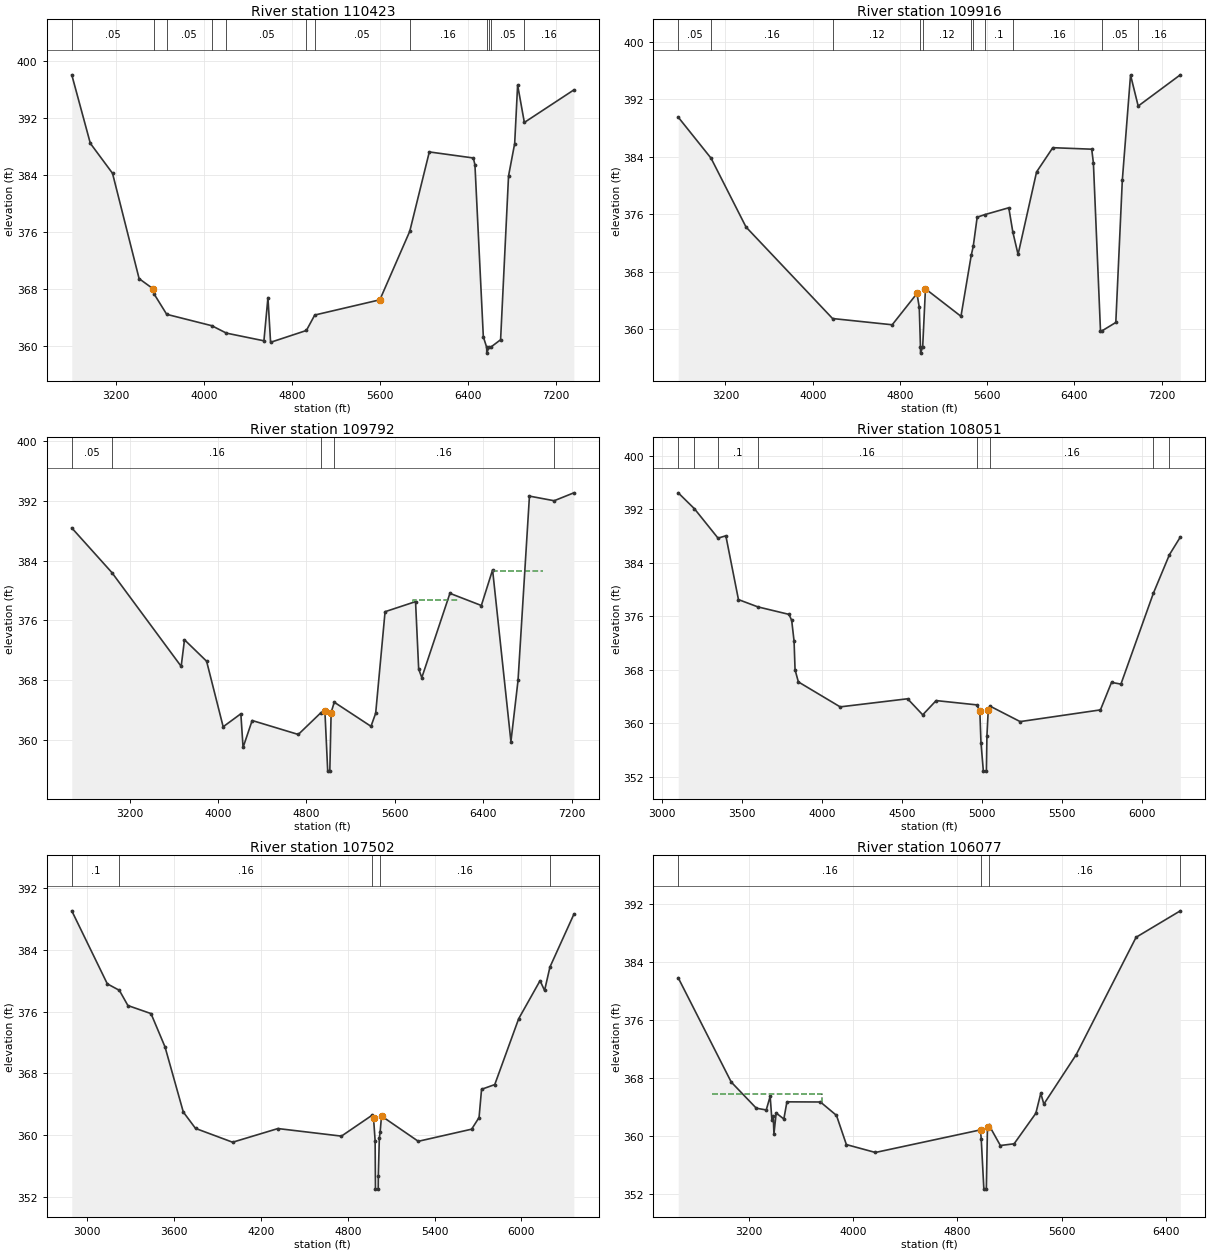
Type RM Length L Ch R = 1 ,110423  ,507,507,507
BEGIN DESCRIPTION:
DUCK CREEK 68 0
END DESCRIPTION:
XS GIS Cut Line= 3
      3507430.04     10422926.64      3506114.92     10419753.86
      3505832.92     10418656.25
#Sta/Elev= 30
  2797.9  398.07  2966.7  388.45  3168.6  384.24  3410.6  369.44  3535.4  368.04
  3547.2  367.28  3661.6  364.43  4071.9  362.83  4204.7  361.79  4546.1  360.71
  4582.7  366.78  4606.6   360.5  4932.3  362.16  5008.5  364.33  5600.8  366.47
  5872.8  376.09  6050.8  387.24  6451.6  386.39  6465.9  385.41  6542.2  361.28
    6573  359.78  6573.5  358.98    6593  359.78  6608.3   359.8  6699.3  360.86
  6771.6  383.87  6827.4  388.42  6854.2  396.64  6915.4  391.38  7365.7  395.95
#Mann= 12 ,-1 , 0
  2797.9     .05       0  3547.2     .16       0  3661.6     .05       0
  4071.9     .16       0  4204.7     .05       0  4932.3     .16       0
  5008.5     .05       0  5872.8     .16       0    6573     .07       0
    6593     .16       0  6608.3     .05       0  6915.4     .16       0
#XS Ineff= 2 , 0
                         6146.28             387
Permanent Ineff=
       F       F
Bank Sta=3535.4,5600.8
XS Rating Curve= 0 ,0
Exp/Cntr=0.3,0.1

Type RM Length L Ch R = 1 ,109916  ,124,124,124
BEGIN DESCRIPTION:
DUCK CREEK 67 0
END DESCRIPTION:
XS GIS Cut Line= 4
      3507521.17     10422783.38      3507521.17     10421251.26
      3506232.11      10419823.3      3505889.44     10418725.91
#Sta/Elev= 30
  2766.5  389.53  3067.8  383.81  3388.2  374.23  4182.1  361.48  4729.2  360.61
  4956.4  364.97  4977.3  363.07  4988.6  357.46  4989.1  356.66  5008.6  357.46
  5034.1  365.62    5360  361.79    5454  370.27  5472.7  371.55  5508.7   375.6
    5582  375.97  5798.6  376.91  5836.1   373.5  5883.8  370.41  6053.5   381.9
  6202.2  385.28  6559.3  385.07  6574.8  383.15  6639.8  359.76  6655.5  359.78
  6780.3  360.93    6840  380.74  6915.5   395.4  6985.6  391.08    7372  395.43
#Mann= 11 ,-1 , 0
  2766.5     .05       0  3067.8     .16       0  4182.1     .12       0
  4988.6     .07       0  5008.6     .12       0    5454      .1       0
  5472.7     .05       0    5582      .1       0  5836.1     .16       0
  6655.5     .05       0  6985.6     .16       0
#XS Ineff= 2 ,-1
 5798.71 5984.79   376.8 6198.95  6929.2  385.13
Permanent Ineff=
       F       F
Bank Sta=4956.4,5034.1
XS Rating Curve= 0 ,0
Exp/Cntr=0.3,0.1

Type RM Length L Ch R = 1 ,109792  ,1741,1741,1741
BEGIN DESCRIPTION:
Mapping XS 31a8d5ba
END DESCRIPTION:
XS GIS Cut Line= 4
       3507642.7     10422761.68       3507642.7     10421173.13
      3506318.91     10419788.58      3506002.07     10418798.98
#Sta/Elev= 30
  2677.3  388.37    3041  382.38  3667.3  369.83  3697.3  373.39  3897.3  370.52
  4047.3  361.74  4207.3  363.48  4227.3  358.97  4309.6  362.58    4727  360.71
    4932  363.63  4967.6   363.9  4993.3   355.8  5012.3   355.8  5024.2  363.65
  5052.5  365.03  5384.9   361.8  5427.4  363.56  5512.3  377.15  5788.1   378.5
  5816.4  369.47  5844.7  368.32  6099.1  379.61  6383.5  377.98  6485.2  382.75
  6651.2  359.75  6715.5  367.95  6818.7  392.63  7042.2  392.01  7220.5  393.07
#Mann= 5 ,-1 , 0
  2677.3     .05       0    3041     .16       0    4932     .12       0
  5052.5     .16       0  7042.2     .16       0
#XS Ineff= 2 ,-1
 5767.12 6181.39  378.68 6486.83 6939.73  382.59
Permanent Ineff=
       F       F
Bank Sta=4967.6,5024.2
XS Rating Curve= 0 ,0
Exp/Cntr=0.3,0.1

Type RM Length L Ch R = 1 ,108051  ,549,549,549
BEGIN DESCRIPTION:
DUCK CREEK 66 0
END DESCRIPTION:
XS GIS Cut Line= 3
      3508588.88     10422318.95      3508549.82     10421637.54
      3507794.61     10419298.15
#Sta/Elev= 30
  3099.1  394.45  3200.5  392.07    3348  387.68  3396.9  388.03  3475.8   378.5
  3597.2  377.41  3791.8  376.29  3808.8   375.4  3823.8  372.27  3829.9     368
  3850.6   366.2  4112.1  362.47  4533.9  363.68  4628.5  361.28  4712.5  363.41
  4966.1  362.77  4985.8  361.88  4992.9  357.14  5007.8  352.87  5026.8  352.87
  5030.2  358.16  5038.3  361.95  5048.8  362.59    5238  360.27  5740.3  362.02
  5809.6  366.13  5868.4  365.87  6071.2  379.44  6171.9  385.21  6239.9  387.84
#Mann= 8 ,-1 , 0
  3099.1     .16       0  3200.5     .05       0    3348      .1       0
  3597.2     .16       0  4966.1     .12       0  5048.8     .16       0
  6071.2      .1       0  6171.9     .05       0
Bank Sta=4985.8,5038.3
XS Rating Curve= 0 ,0
Exp/Cntr=0.3,0.1

Type RM Length L Ch R = 1 ,107502  ,1425,1425,1425
BEGIN DESCRIPTION:
DUCK CREEK 65 4
END DESCRIPTION:
XS GIS Cut Line= 2
      3509461.29     10422119.35      3507986.33     10418978.54
#Sta/Elev= 30
  2892.2  389.05  3137.8   379.6  3221.1  378.76  3280.2  376.79  3439.8  375.75
  3536.6  371.44    3663  363.01  3747.4  360.89  4003.9   359.1    4317  360.87
  4755.9  359.89  4966.7  362.58  4977.7  362.26  4988.7   359.3  4991.1  353.03
  5010.1  353.03  5010.8  354.76  5017.8  359.63  5023.4  360.42  5032.9  362.49
    5287  359.22  5655.8  360.79    5707   362.3  5724.3  365.95  5815.5  366.56
  5980.7  375.08  6128.6  380.01  6159.8  378.74    6197  381.78  6362.1   388.6
#Mann= 5 ,-1 , 0
  2892.2      .1       0  3221.1     .16       0  4966.7     .12       0
  5023.4     .16       0    6197     .16       0
Bank Sta=4977.7,5032.9
XS Rating Curve= 0 ,0
Exp/Cntr=0.3,0.1

Type RM Length L Ch R = 1 ,106077  ,632,632,632
BEGIN DESCRIPTION:
DUCK CREEK 65 0
END DESCRIPTION:
XS GIS Cut Line= 3
      3510047.23     10421641.92       3508849.3     10418859.76
      3508380.55     10418182.69
#Sta/Elev= 30
  2658.9  381.81  3065.6  367.42    3258  363.81  3334.2  363.57  3364.3  365.45
  3377.8  362.15  3387.9  362.69  3393.3  360.26  3410.4  363.15  3469.3  362.32
  3492.9  364.69    3750  364.67  3873.1  362.82  3949.1  358.79  4171.8   357.7
  4978.3  360.82  4984.1   359.5  5004.1  352.64  5023.1  352.64  5031.7  361.26
  5037.1  361.21  5043.6  361.47  5130.7  358.66  5236.3   358.9  5402.9  363.11
  5440.8  365.87  5464.4  364.38  5712.8  371.21  6172.2  387.41  6511.5  391.06
#Mann= 4 ,-1 , 0
  2658.9     .16       0  4984.1     .12       0  5043.6     .16       0
  6511.5     .05       0
#XS Ineff= 1 ,-1
 2917.61 3758.52  365.83
Permanent Ineff=
       T
Bank Sta=4978.3,5037.1
XS Rating Curve= 0 ,0
Exp/Cntr=0.3,0.1

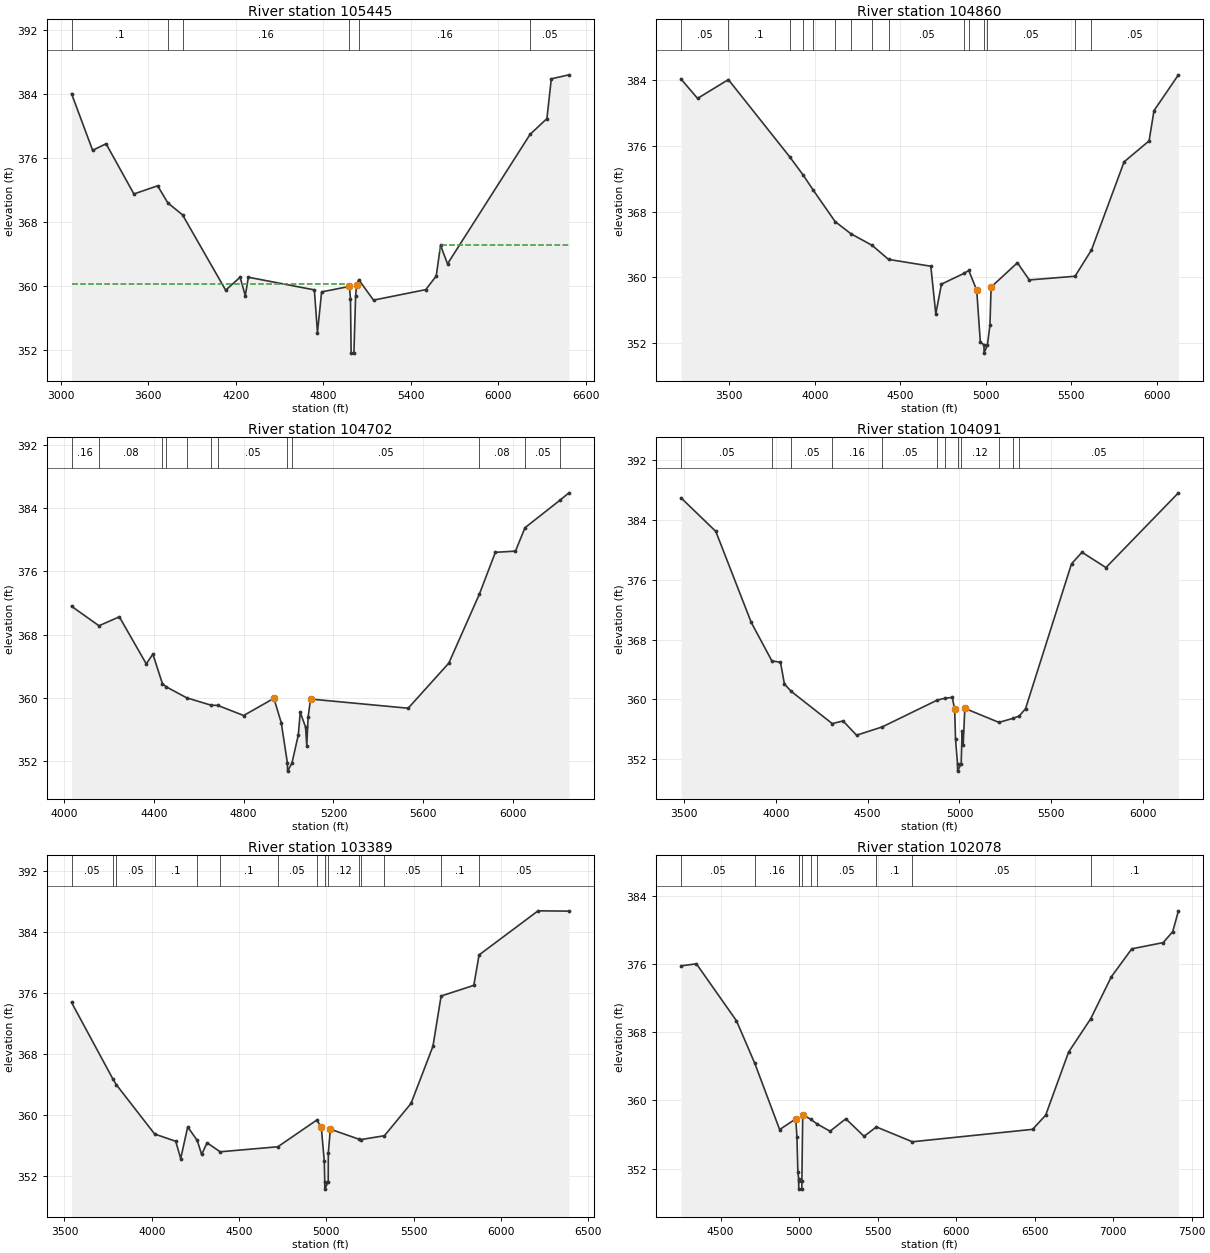
Type RM Length L Ch R = 1 ,105445  ,585,585,585
BEGIN DESCRIPTION:
DUCK CREEK 65 3
END DESCRIPTION:
XS GIS Cut Line= 3
      3511023.77     10420734.76      3509613.18     10419259.07
      3509092.36     10417991.74
#Sta/Elev= 30
  3073.1  384.05  3217.8  376.97    3310  377.79  3500.9  371.52  3663.5  372.54
  3733.8   370.4  3834.5  368.91  4130.2   359.5  4229.3  361.12  4264.8  358.82
  4285.9  361.12  4738.5  359.54  4759.9   354.2  4788.2  359.29  4979.1  359.97
  4986.3   358.4  4990.8  351.64  5009.8  351.64  5021.5  358.82  5028.4  360.11
  5042.6  360.82  5144.2  358.26  5502.6  359.57  5574.5  361.28  5603.9  365.11
  5651.8  362.79  6218.2  378.97  6333.4  380.93  6363.7   385.9  6484.7   386.4
#Mann= 6 ,-1 , 0
  3073.1      .1       0  3733.8     .08       0  3834.5     .16       0
  4979.1     .12       0  5042.6     .16       0  6218.2     .05       0
#XS Ineff= 2 , 0
       0 4964.77  360.31 5597.16       0  365.17
Permanent Ineff=
       T       T
Bank Sta=4979.1,5028.4
XS Rating Curve= 0 ,0
Exp/Cntr=0.3,0.1

Type RM Length L Ch R = 1 ,104860  ,158,158,158
BEGIN DESCRIPTION:
DUCK CREEK 62 3
END DESCRIPTION:
XS GIS Cut Line= 5
       3511185.9      10420724.8      3510660.96     10420172.84
      3510278.76      10419348.9      3510162.88     10418988.16
      3509818.69     10418198.72
#Sta/Elev= 30
  3217.1  384.15    3314  381.79  3494.2  384.08  3852.6  374.69  3930.3   372.5
  3990.2  370.64    4119  366.79  4210.6  365.32  4335.3   363.9  4431.1  362.19
  4678.6  361.36  4707.7  355.56  4740.8  359.18  4873.7   360.5  4900.7  360.84
  4947.2  358.44  4968.2  352.14  4989.8  351.78  4990.3  350.78  5009.8  351.78
  5024.6   354.2  5031.3  358.82  5185.2  361.78  5254.6  359.69  5522.5  360.14
  5618.5  363.34  5809.5  374.07  5955.5  376.62  5984.3   380.3  6127.2  384.66
#Mann= 15 ,-1 , 0
  3217.1     .05       0  3494.2      .1       0  3852.6     .05       0
  3930.3      .1       0  3990.2     .08       0    4119     .16       0
  4210.6     .08       0  4335.3     .16       0  4431.1     .05       0
  4873.7     .12       0  4900.7     .05       0  4989.8     .04       0
  5009.8     .05       0  5522.5     .07       0  5618.5     .05       0
Bank Sta=4947.2,5031.3
XS Rating Curve= 0 ,0
Exp/Cntr=0.3,0.1

Type RM Length L Ch R = 1 ,104702  ,611,611,611
BEGIN DESCRIPTION:
DUCK CREEK 62 0
END DESCRIPTION:
XS GIS Cut Line= 4
      3510861.56     10420091.15      3510640.22     10419815.13
      3510056.89     10418453.15      3509978.75     10418080.71
#Sta/Elev= 30
  4033.4  371.58  4155.6  369.12  4246.3  370.25  4366.3  364.31  4395.8  365.54
    4438  361.83  4454.8  361.42  4546.6  360.02  4655.2  359.09  4684.5  359.07
  4800.2  357.79  4934.9  359.96  4967.6  356.89  4995.2  351.77  4995.7  350.77
  5015.2  351.77  5043.7  355.35  5052.3  358.19  5075.9  356.33  5081.4  353.98
  5087.2  357.55  5098.1  359.87    5533  358.71  5714.3  364.41  5850.1   373.1
  5921.5  378.39  6011.1  378.54  6053.6   381.5  6210.7     385  6249.4   385.9
#Mann= 12 ,-1 , 0
  4033.4     .16       0  4155.6     .08       0    4438     .05       0
  4454.8     .08       0  4546.6     .05       0  4655.2     .16       0
  4684.5     .05       0  4995.2     .04       0  5015.2     .05       0
  5850.1     .08       0  6053.6     .05       0  6210.7     .08       0
Bank Sta=4934.9,5098.1
XS Rating Curve= 0 ,0
Exp/Cntr=0.3,0.1

Type RM Length L Ch R = 1 ,104091  ,702,702,702
BEGIN DESCRIPTION:
DUCK CREEK 63 0
END DESCRIPTION:
XS GIS Cut Line= 3
       3511342.1     10420291.63      3510842.11     10418891.64
      3510142.13     10417891.68
#Sta/Elev= 30
  3484.4  386.98  3673.9  382.48  3866.7  370.29  3978.7  365.15  4025.9  364.94
  4047.2  362.04    4084  361.06  4307.4  356.74  4366.3  357.09  4440.1  355.18
  4579.1  356.29  4879.6  359.89  4923.3  360.15  4960.9  360.24    4974  358.63
  4978.4  354.68  4989.3  351.37  4989.8  350.37  5009.3  351.37  5014.1  355.73
  5020.3   353.9    5029  358.78  5214.7   356.9  5291.6  357.44  5325.2  357.76
  5359.4  358.73  5609.7  378.14  5666.8  379.69  5797.1  377.64  6191.6  387.65
#Mann= 12 ,-1 , 0
  3484.4     .05       0  3978.7      .1       0    4084     .05       0
  4307.4     .16       0  4579.1     .05       0  4879.6     .16       0
  4923.3     .12       0  4989.3     .07       0  5009.3     .12       0
  5214.7     .07       0  5291.6      .1       0  5325.2     .05       0
Bank Sta=4974,5029
XS Rating Curve= 0 ,0
Exp/Cntr=0.3,0.1

Type RM Length L Ch R = 1 ,103389  ,1311,1311,1311
BEGIN DESCRIPTION:
DUCK CREEK 61 2
END DESCRIPTION:
XS GIS Cut Line= 3
      3511950.11     10419825.53      3511049.08     10417890.65
      3510658.43     10417291.67
#Sta/Elev= 30
  3540.4  374.77  3777.9   364.7  3797.8  363.95  4016.5   357.5  4137.3  356.55
  4165.7  354.28  4205.9  358.43  4260.6  356.66  4285.6  354.82  4316.9  356.35
  4391.6  355.17  4722.3  355.83    4945  359.33    4971  358.42  4988.4  353.92
  4990.8  351.27  4991.3  350.27  5010.8  351.27  5011.3  354.99  5022.9  358.14
  5184.6  356.84    5200  356.78  5332.9  357.28  5485.3  361.52  5610.7  369.01
  5657.5  375.61  5844.9  377.01  5874.9     381    6213  386.79  6389.9  386.75
#Mann= 15 ,-1 , 0
  3540.4     .05       0  3777.9     .16       0  3797.8     .05       0
  4016.5      .1       0  4260.6     .05       0  4391.6      .1       0
  4722.3     .05       0    4945     .12       0  4990.8     .07       0
  5010.8     .12       0  5184.6     .07       0    5200     .16       0
  5332.9     .05       0  5657.5      .1       0  5874.9     .05       0
Bank Sta=4971,5022.9
XS Rating Curve= 0 ,0
Exp/Cntr=0.3,0.1

Type RM Length L Ch R = 1 ,102078  ,1132,1132,1132
BEGIN DESCRIPTION:
DUCK CREEK 60 0
END DESCRIPTION:
XS GIS Cut Line= 3
      3512873.37     10419205.32      3512183.26     10418077.71
      3512060.95     10416235.29
#Sta/Elev= 30
  4247.4  375.79  4345.5  376.03  4600.9  369.34  4717.8  364.33  4875.7  356.57
  4978.6  357.83  4985.9   355.7  4991.8  351.62  4996.7  350.81    4997  350.58
  4997.5  349.58  5016.9  349.58  5017.4  350.58  5022.7  358.32  5073.4  357.78
  5114.6  357.23  5196.8  356.38  5297.4  357.84  5413.5  355.78  5491.9  356.88
    5721  355.14  6487.5   356.6  6570.4  358.27  6716.1  365.66  6857.3  369.59
  6988.6  374.51  7118.9  377.79  7318.7  378.52  7379.5   379.8  7415.9  382.25
#Mann= 10 ,-1 , 0
  4247.4     .05       0  4717.8     .16       0  4996.7     .12       0
    4997     .07       0  5017.4     .12       0  5073.4     .07       0
  5114.6     .05       0  5491.9      .1       0    5721     .05       0
  6857.3      .1       0
Bank Sta=4978.6,5022.7
XS Rating Curve= 0 ,0
Exp/Cntr=0.3,0.1

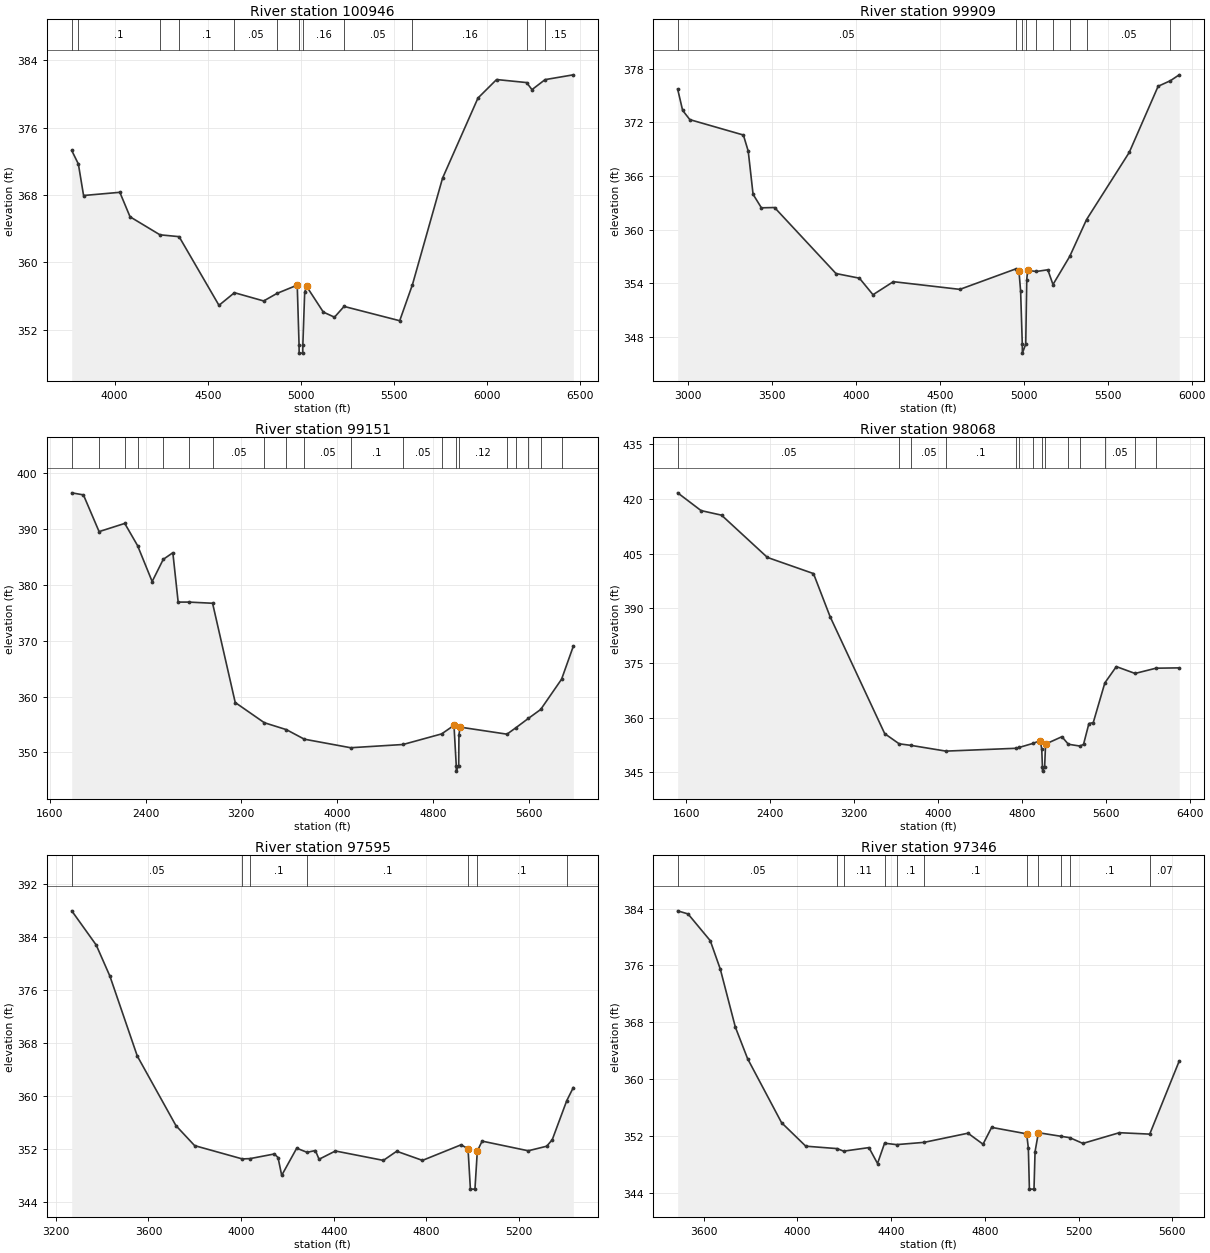
Type RM Length L Ch R = 1 ,100946  ,1037,1037,1037
BEGIN DESCRIPTION:
DUCK CREEK 6 0
END DESCRIPTION:
XS GIS Cut Line= 3
      3512886.39     10419030.83      3513110.34      10418442.3
      3513152.01     10416379.82
#Sta/Elev= 30
  3769.5   373.3  3805.1  371.69    3833  367.95  4027.7  368.33  4082.5  365.42
    4243  363.28  4345.8  363.06  4559.9   354.9  4642.9   356.4  4799.9  355.42
  4871.6  356.32    4980   357.3  4989.8  350.22  4990.3  349.22  5009.7  349.22
  5010.2  350.22    5020  356.44    5030  357.16    5120   354.1    5180  353.49
  5231.5  354.77  5530.1  353.07  5598.7  357.37  5760.1  370.01  5950.2  379.53
  6050.2  381.73  6211.4  381.37  6240.2  380.53  6310.6  381.72  6462.1  382.29
#Mann= 12 ,-1 , 0
  3769.5     .05       0  3805.1      .1       0    4243     .05       0
  4345.8      .1       0  4642.9     .05       0  4871.6     .16       0
  4989.8     .07       0  5010.2     .16       0  5231.5     .05       0
  5598.7     .16       0  6211.4      .1       0  6310.6     .15       0
Bank Sta=4980,5030
XS Rating Curve= 0 ,0
Exp/Cntr=0.3,0.1

Type RM Length L Ch R = 1 ,99909   ,758,758,758
BEGIN DESCRIPTION:
DUCK CREEK 57 2
END DESCRIPTION:
XS GIS Cut Line= 4
      3514076.48     10419348.54      3513730.14     10418911.05
      3513974.93     10417286.05      3513855.14     10416507.43
#Sta/Elev= 30
  2936.9  375.74  2966.5  373.36  3009.5  372.32  3328.6   370.6  3357.5   368.8
  3386.4  363.97    3436  362.46  3514.5  362.49  3880.5  355.11  4020.2  354.59
  4101.1  352.74  4222.4   354.2  4618.8  353.34  4952.3  355.63  4970.8  355.43
  4980.9  353.13  4990.8  347.21  4991.3  346.21  5011.3  347.21  5017.4  354.41
  5022.5  355.46  5074.6  355.34    5143  355.53  5173.7  353.88  5273.6  357.03
  5373.6  361.14  5628.3  368.66  5800.3  376.05  5873.2  376.67    5926  377.33
#Mann= 9 ,-1 , 0
  2936.9     .05       0  4952.3     .16       0  4990.8     .07       0
  5011.3     .16       0  5074.6     .12       0  5173.7     .16       0
  5273.6      .1       0  5373.6     .05       0  5873.2      .1       0
Bank Sta=4970.8,5022.5
XS Rating Curve= 0 ,0
Exp/Cntr=0.3,0.1

Type RM Length L Ch R = 1 ,99151   ,1083,1083,1083
BEGIN DESCRIPTION:
DUCK CREEK 57 1
END DESCRIPTION:
XS GIS Cut Line= 4
      3514362.47     10420420.56      3514931.69     10419254.63
      3514841.62     10417915.39      3514432.74     10416420.11
#Sta/Elev= 30
  1783.8  396.49  1881.4  396.12  2012.3  389.54  2226.6  391.01  2333.8  387.03
  2455.6   380.6  2548.1  384.57  2628.3  385.76  2672.8  376.92  2762.4  376.92
  2960.3  376.71  3149.5  358.93  3392.7  355.31  3576.9  354.07  3727.1  352.36
  4113.9  350.83  4551.3  351.41    4874  353.31  4976.9  354.84  4995.8  347.64
  4996.3  346.64  5016.3  347.64  5018.3  353.17  5028.7  354.52  5419.6  353.26
  5495.2  354.43  5598.1  356.08  5700.9  357.68  5875.6   363.1  5973.7  369.01
#Mann= 20 ,-1 , 0
  1783.8     .16       0  2012.3      .1       0  2226.6     .08       0
  2333.8      .1       0  2548.1     .05       0  2762.4     .15       0
  2960.3     .05       0  3392.7     .12       0  3576.9     .05       0
  3727.1     .05       0  4113.9      .1       0  4551.3     .05       0
    4874     .12       0  4995.8     .07       0  5016.3     .12       0
  5419.6     .16       0  5495.2     .05       0  5598.1     .16       0
  5700.9     .05       0  5875.6      .1       0
Bank Sta=4976.9,5028.7
XS Rating Curve= 0 ,0
Exp/Cntr=0.3,0.1

Type RM Length L Ch R = 1 ,98068   ,473,473,473
BEGIN DESCRIPTION:
DUCK CREEK 59 0
END DESCRIPTION:
XS GIS Cut Line= 4
      3516987.45     10420248.73      3516674.95     10419311.22
      3516138.49     10418972.68      3515383.49     10415905.81
#Sta/Elev= 30
  1515.7  421.65  1738.7  416.78  1934.3  415.52  2371.2  403.93  2810.6   399.5
  2968.5  387.71  3489.5   355.6  3627.2  352.81  3740.6  352.38  4072.7  350.81
  4737.4  351.58    4773  351.83  4905.4  352.95  4972.5  353.71  4986.3  351.34
  4993.1  346.32  4993.6  345.32  5013.7  346.32  5022.7  352.74  5178.5  354.76
    5240  352.69  5349.9   352.2  5384.4  352.64  5435.9  358.38  5477.1  358.61
  5587.8  369.52  5697.2  373.99  5875.7  372.11  6075.2  373.55  6296.7  373.64
#Mann= 14 ,-1 , 0
  1515.7     .05       0  3627.2      .1       0  3740.6     .05       0
  4072.7      .1       0  4737.4     .05       0    4773     .16       0
  4905.4     .12       0  4993.1     .07       0  5013.7     .12       0
    5240     .05       0  5349.9      .1       0  5587.8     .05       0
  5875.7      .1       0  6075.2     .05       0
Bank Sta=4972.5,5022.7
XS Rating Curve= 0 ,0
Exp/Cntr=0.3,0.1

Type RM Length L Ch R = 1 ,97595   ,249,249,249
BEGIN DESCRIPTION:
DUCK CREEK 56 4
END DESCRIPTION:
XS GIS Cut Line= 4
       3517561.7     10418057.48      3516141.57     10417248.46
      3516124.21     10417088.74      3515777.01      10416956.8
#Sta/Elev= 30
  3268.5  387.94  3374.3  382.77  3433.4  378.07  3551.5  366.02  3718.6   355.5
  3799.3  352.48  4005.4  350.47  4038.9  350.52  4143.7  351.22  4159.5  350.68
  4175.4  347.99  4240.2  352.09  4284.9  351.47  4320.9  351.74  4336.8  350.42
  4407.4  351.67  4614.6  350.25  4672.1  351.63  4783.4  350.25    4950   352.6
  4980.2  352.02  4990.5  345.91  5010.1  345.91  5020.4  351.67  5041.2  353.16
  5240.4   351.7    5320  352.39    5344  353.37  5406.9  359.29    5435  361.25
#Mann= 7 ,-1 , 0
  3268.5     .05       0  4005.4     .07       0  4038.9      .1       0
  4284.9      .1       0  4980.2     .05       0  5020.4      .1       0
  5406.9      .1       0
Bank Sta=4980.2,5020.4
XS Rating Curve= 0 ,0
Exp/Cntr=0.3,0.1

Type RM Length L Ch R = 1 ,97346   ,303,303,303
BEGIN DESCRIPTION:
DUCK CREEK 57 0
END DESCRIPTION:
XS GIS Cut Line= 4
      3517631.15     10417922.07      3516457.55     10417210.27
      3516280.46     10417001.93      3515795.71     10416908.44
#Sta/Elev= 30
  3489.4   383.7  3533.8  383.26  3628.6  379.49  3671.5  375.47  3735.5  367.32
  3787.8  362.87  3932.7  353.85    4036  350.54  4169.7   350.2  4197.5  349.84
  4305.4  350.34  4342.1   348.1  4372.2  350.96  4423.2  350.76  4540.9  351.08
    4728  352.37  4792.1  350.82  4828.9  353.19  4978.3  352.28  4985.5  350.27
    4990  344.49  5009.6  344.49  5014.1  349.77  5028.4  352.44  5125.5  351.93
  5162.1  351.74  5218.2  350.93  5373.8  352.44  5503.3  352.24  5629.1  362.54
#Mann= 11 ,-1 , 0
  3489.4     .05       0  4169.7     .07       0  4197.5     .11       0
  4372.2     .07       0  4423.2      .1       0  4540.9      .1       0
  4978.3     .05       0  5028.4      .1       0  5125.5     .07       0
  5162.1      .1       0  5503.3     .07       0
Bank Sta=4978.3,5028.4
XS Rating Curve= 0 ,0
Exp/Cntr=0.3,0.1

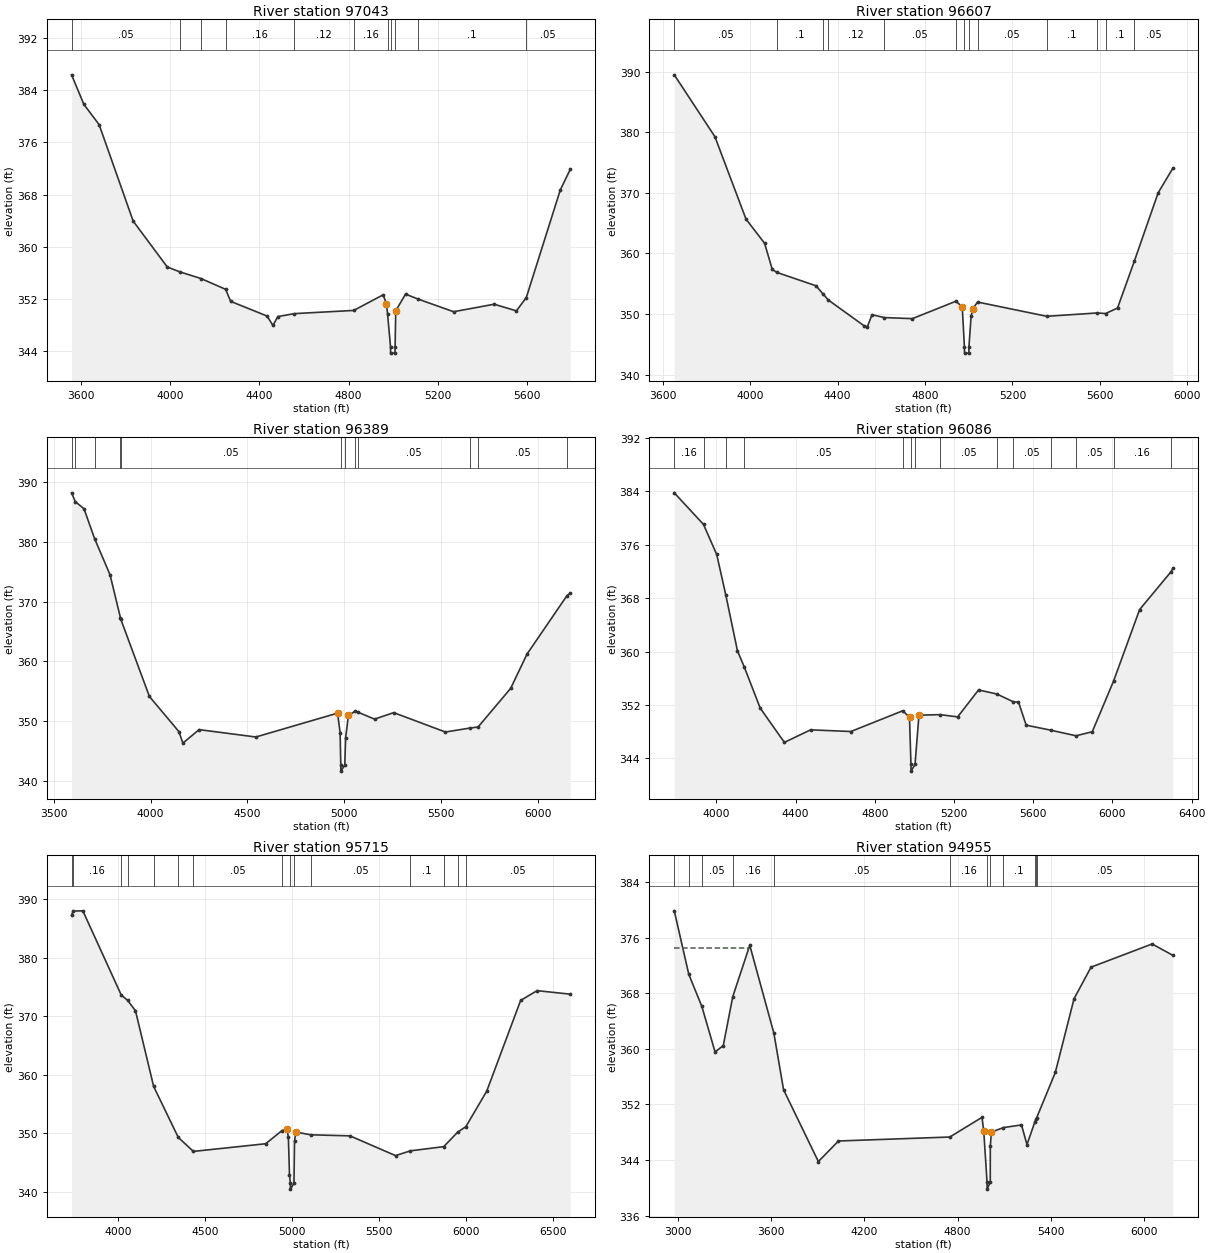
Type RM Length L Ch R = 1 ,97043   ,436,436,436
BEGIN DESCRIPTION:
DUCK CREEK 56 8
END DESCRIPTION:
XS GIS Cut Line= 4
      3517988.78     10417474.15      3516752.68     10417060.96
      3516502.68     10416880.41      3515978.35     10416543.58
#Sta/Elev= 30
  3558.2  386.33  3613.1  381.81  3681.5  378.71  3834.2  363.93  3986.8  356.91
  4042.8  356.16  4138.4  355.13  4248.5  353.48  4271.1  351.64  4434.3  349.39
  4460.6  347.95  4482.6  349.31    4557  349.76  4822.8  350.25  4954.5  352.64
  4969.2  351.29  4974.6  349.63  4987.6  344.71  4988.1  343.71  5007.7  343.71
  5008.2  344.71    5011   350.2  5055.1  352.75  5110.9  351.99  5270.5  350.05
  5452.2   351.2  5551.9  350.18  5596.2  352.22  5748.7  368.71  5793.1  371.84
#Mann= 11 ,-1 , 0
  3558.2     .05       0  4042.8     .16       0  4138.4      .1       0
  4248.5     .16       0    4557     .12       0  4822.8     .16       0
  4974.6     .12       0  4987.6     .07       0  5008.2     .12       0
  5110.9      .1       0  5596.2     .05       0
Bank Sta=4969.2,5011
XS Rating Curve= 0 ,0
Exp/Cntr=0.3,0.1

Type RM Length L Ch R = 1 ,96607   ,218,218,218
BEGIN DESCRIPTION:
DUCK CREEK 56 5
END DESCRIPTION:
XS GIS Cut Line= 4
      3518002.68     10417422.06      3517125.66     10416722.94
      3516717.67     10416662.17      3516013.16     10416414.32
#Sta/Elev= 30
    3653  389.46  3838.7  379.26  3981.2  365.64  4066.1  361.66  4101.3  357.34
  4122.5  356.85  4301.5  354.64    4335  353.23  4357.8  352.29  4522.5  348.01
  4536.1  347.87  4557.7  349.88  4612.5   349.4  4741.9  349.22  4941.2  352.09
  4970.3  351.18  4980.2  344.53  4980.7  343.53  5000.3  343.53  5000.8  344.53
  5010.7  349.58  5018.4  350.88  5040.5  351.96    5357  349.61  5588.1  350.16
  5625.6  350.06  5680.6  350.97  5757.9  358.75  5866.4  369.99  5933.9  374.06
#Mann= 13 ,-1 , 0
    3653     .05       0  4122.5      .1       0    4335     .05       0
  4357.8     .12       0  4612.5     .05       0  4941.2     .12       0
  4980.2     .07       0  5000.8     .12       0  5040.5     .05       0
    5357      .1       0  5588.1     .05       0  5625.6      .1       0
  5757.9     .05       0
Bank Sta=4970.3,5018.4
XS Rating Curve= 0 ,0
Exp/Cntr=0.3,0.1

Type RM Length L Ch R = 1 ,96389   ,303,303,303
BEGIN DESCRIPTION:
DUCK CREEK 56 6
END DESCRIPTION:
XS GIS Cut Line= 6
      3518367.27     10416599.16      3517526.99     10416439.43
       3517200.6     10416574.85      3517075.05     10416574.46
       3516887.3      10416432.3       3515955.6      10416047.7
#Sta/Elev= 30
  3591.3  388.12  3610.4  386.64  3655.4  385.47  3710.2  380.48    3790  374.46
  3843.9  367.28    3846  367.01  3993.5  354.17  4146.2   348.3  4166.6  346.38
  4250.2  348.64  4543.8  347.41  4966.1  351.39  4979.4  348.16  4982.9  342.72
  4983.4  341.72  5003.5  342.72  5007.8  347.24  5022.3     351  5058.6  351.75
  5072.2  351.54  5157.4  350.39  5256.6  351.47  5523.7  348.24  5652.1  348.91
  5692.7  349.08  5860.9  355.51  5945.6  361.23    6152  370.97    6169  371.39
#Mann= 12 ,-1 , 0
  3591.3     .16       0  3610.4      .1       0  3710.2     .05       0
  3843.9      .1       0    3846     .05       0  4982.9     .03       0
  5003.5     .05       0  5058.6     .12       0  5072.2     .05       0
  5652.1      .1       0  5692.7     .05       0    6152     .16       0
Bank Sta=4966.1,5022.3
XS Rating Curve= 0 ,0
Exp/Cntr=0.3,0.1

Type RM Length L Ch R = 1 ,96086   ,371,371,371
BEGIN DESCRIPTION:
DUCK CREEK 56 7
END DESCRIPTION:
XS GIS Cut Line= 4
      3518398.53     10416526.24      3517332.55     10416324.85
      3516780.46     10416279.71       3515996.4     10415880.74
#Sta/Elev= 30
  3786.8   383.8  3934.4  379.06    4001  374.57  4046.6  368.54  4105.8  360.12
    4141  357.64  4220.8  351.52  4342.9  346.38  4475.2  348.26  4678.7  348.01
  4940.9  351.12  4974.9  350.15  4982.2  343.07  4982.7  342.07  5002.8  343.07
  5022.6  350.46  5129.7  350.54    5218   350.2  5323.6  354.24  5415.3  353.64
  5499.8  352.46  5525.4  352.43  5564.3  348.96    5690   348.2  5815.9  347.37
    5898  347.98  6005.4  355.56  6137.1  366.29  6295.8  371.97  6305.3  372.49
#Mann= 14 ,-1 , 0
  3786.8     .16       0  3934.4     .05       0  4046.6      .1       0
    4141     .05       0  4940.9     .16       0  4982.2     .07       0
  5002.8     .16       0  5129.7     .05       0  5415.3      .1       0
  5499.8     .05       0    5690      .1       0  5815.9     .05       0
  6005.4     .16       0  6295.8     .05       0
Bank Sta=4974.9,5022.6
XS Rating Curve= 0 ,0
Exp/Cntr=0.3,0.1

Type RM Length L Ch R = 1 ,95715   ,760,760,760
BEGIN DESCRIPTION:
DUCK CREEK 58 0
END DESCRIPTION:
XS GIS Cut Line= 3
      3518557.31     10416519.96      3517559.69     10416132.66
      3516039.98     10415183.18
#Sta/Elev= 30
  3735.1  387.25  3743.7  387.96  3799.6     388  4020.3  373.59  4056.9  372.69
  4101.8  370.91  4206.1  357.97  4347.5  349.25  4434.2  346.86    4849  348.17
  4942.7  350.42  4970.5  350.64  4979.3  349.38  4985.8  342.86  4990.9  341.41
  4991.4  340.41  5011.5  341.41  5014.7  348.63  5022.4  350.17  5107.8   349.7
    5333  349.52  5594.4  346.14  5679.9  346.96  5870.9  347.67  5951.6  350.17
  5998.2  351.09    6118  357.17  6312.6  372.68  6406.9  374.35  6597.2  373.75
#Mann= 15 ,-1 , 0
  3735.1      .1       0  3743.7     .16       0  4020.3     .05       0
  4056.9      .1       0  4206.1     .05       0  4347.5      .1       0
  4434.2     .05       0  4942.7     .16       0  4990.9     .07       0
  5011.5     .16       0  5107.8     .05       0  5679.9      .1       0
  5870.9     .05       0  5951.6      .1       0  5998.2     .05       0
Bank Sta=4970.5,5022.4
XS Rating Curve= 0 ,0
Exp/Cntr=0.3,0.1

Type RM Length L Ch R = 1 ,94955   ,1178,1178,1178
BEGIN DESCRIPTION:
DUCK CREEK 56 3
END DESCRIPTION:
XS GIS Cut Line= 3
      3519269.07     10416098.94      3517824.82     10415486.57
      3516296.54      10414896.9
#Sta/Elev= 30
  2977.9  379.87  3071.3  370.72  3154.9  366.13  3240.3  359.55  3293.1  360.48
  3354.1  367.52  3463.4  374.91  3618.5  362.25  3680.7  354.12  3904.6  343.78
  4033.8  346.74  4749.7  347.31  4956.8  350.14    4968  348.24  4989.4  340.81
  4989.9  339.81    5010  340.81  5010.4     346  5017.2  348.02  5094.9  348.67
  5210.9  349.05  5246.2  346.22    5297  349.48  5303.6  349.88  5307.5  350.03
  5428.4   356.6  5549.1  367.23  5658.2  371.76    6051   375.1  6184.7  373.46
#Mann= 12 ,-1 , 0
  2977.9     .05       0  3071.3     .16       0  3154.9     .05       0
  3354.1     .16       0  3618.5     .05       0  4749.7     .16       0
  4989.4     .07       0    5010     .16       0  5094.9      .1       0
    5297     .05       0  5303.6      .1       0  5307.5     .05       0
#XS Ineff= 2 , 0
          3452.6  374.47
Permanent Ineff=
       F       F
Bank Sta=4968,5017.2
XS Rating Curve= 0 ,0
Exp/Cntr=0.3,0.1

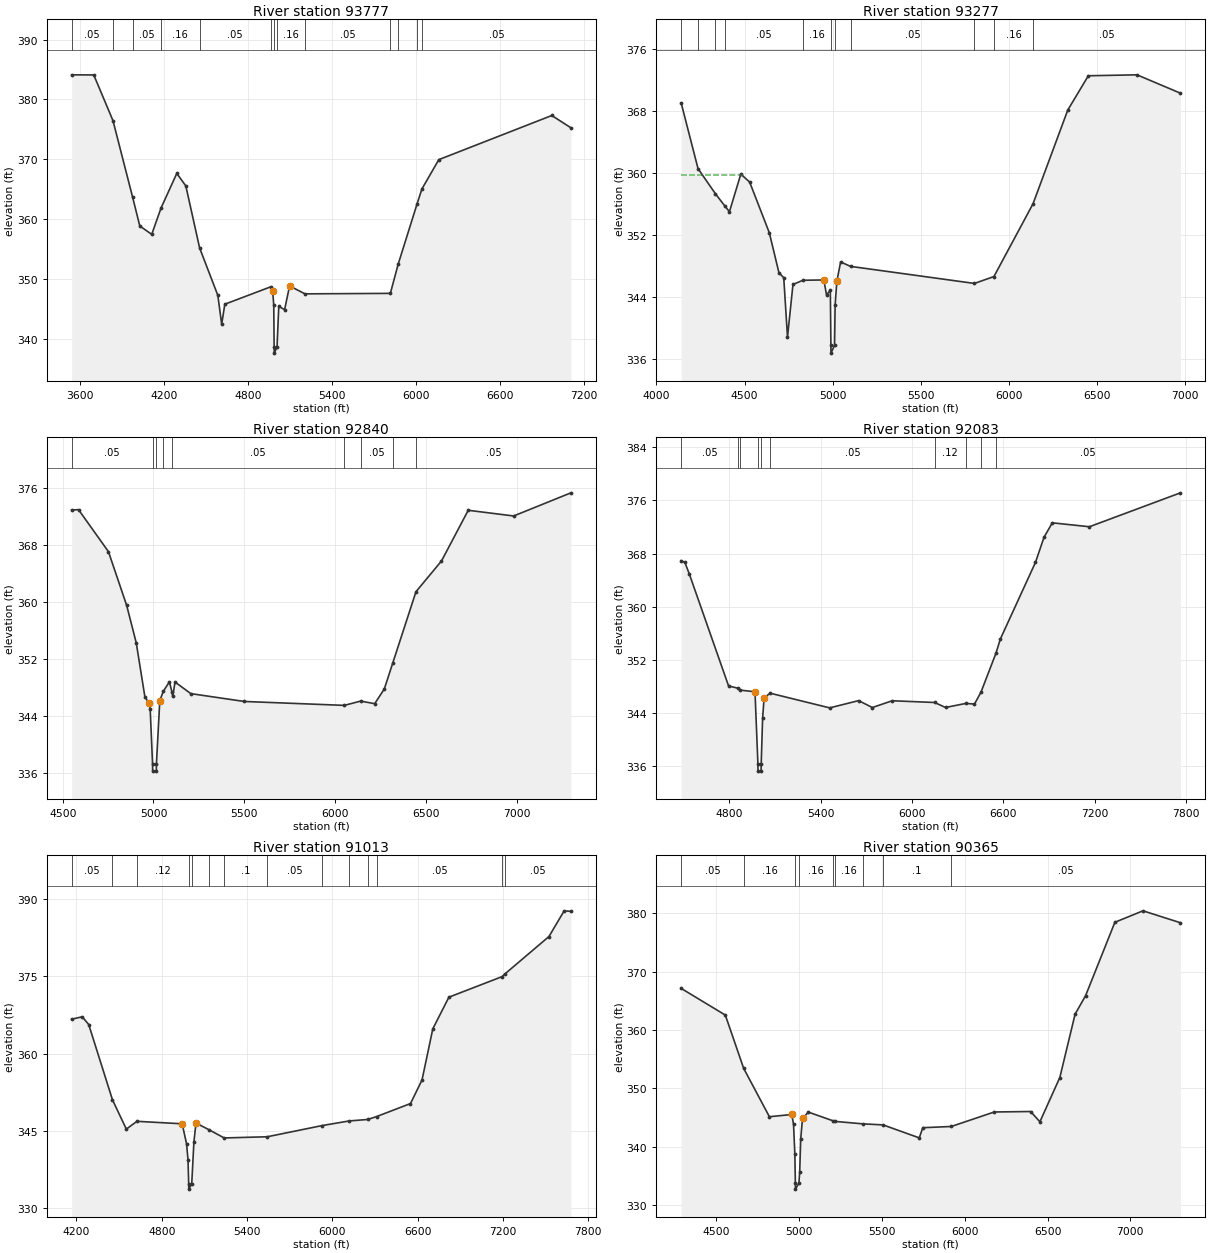
Type RM Length L Ch R = 1 ,93777   ,500,500,500
BEGIN DESCRIPTION:
DUCK CREEK 55 2
END DESCRIPTION:
XS GIS Cut Line= 4
       3519468.8     10416207.49      3518431.44     10415430.55
      3518166.87     10415081.09      3516521.69     10414267.34
#Sta/Elev= 30
  3539.8  384.11  3698.1  384.09  3835.4  376.45  3975.6  363.67  4027.1  358.84
  4112.5  357.44  4179.3  361.86  4291.7  367.63  4356.3  365.53  4454.8  355.17
  4585.1  347.24  4612.6  342.41  4635.1  345.76  4964.7  348.68  4977.1  347.98
    4985  345.55  4987.6  338.58  4988.1  337.58  5008.3  338.58  5020.8   345.4
  5062.5  344.85  5097.9  348.81  5208.3  347.49  5818.6  347.57  5874.7  352.47
  6008.7  362.46  6043.9  365.02  6165.1  369.93  6972.8  377.31  7109.6  375.25
#Mann= 13 ,-1 , 0
  3539.8     .05       0  3835.4     .16       0  3975.6     .05       0
  4179.3     .16       0  4454.8     .05       0  4964.7     .16       0
  4987.6     .07       0  5008.3     .16       0  5208.3     .05       0
  5818.6      .1       0  5874.7     .05       0  6008.7      .1       0
  6043.9     .05       0
#XS Ineff= 2 , 0
         4295.79   366.9
Permanent Ineff=
       F       F
Bank Sta=4977.1,5097.9
XS Rating Curve= 0 ,0
Exp/Cntr=0.3,0.1

Type RM Length L Ch R = 1 ,93277   ,437,437,437
BEGIN DESCRIPTION:
DUCK CREEK 55 5
END DESCRIPTION:
XS GIS Cut Line= 3
       3519320.7     10415616.83      3519020.69      10415216.8
      3517020.69     10414016.81
#Sta/Elev= 30
    4140  369.07  4235.8  360.59  4333.8  357.37  4389.8  355.71  4413.9  355.03
  4478.5  359.88  4528.5  358.86    4640  352.33  4694.8  347.16    4722  346.52
  4743.3  338.86  4774.4  345.65    4831  346.19  4949.4  346.23  4964.9  344.29
  4986.3  344.93  4989.5  337.79    4990  336.79  5010.2  337.79  5013.5  342.99
  5023.2  346.04  5044.6  348.55    5101  347.98  5803.8  345.78  5914.4  346.67
  6136.2  356.06  6333.3  368.15  6449.9  372.57  6725.9  372.69  6972.4  370.32
#Mann= 11 ,-1 , 0
    4140     .16       0  4235.8     .05       0  4333.8     .16       0
  4389.8     .05       0    4831     .16       0  4989.5     .07       0
  5010.2     .16       0    5101     .05       0  5803.8      .1       0
  5914.4     .16       0  6136.2     .05       0
#XS Ineff= 2 , 0
         4493.27  359.77
Permanent Ineff=
       F       F
Bank Sta=4949.4,5023.2
XS Rating Curve= 0 ,0
Exp/Cntr=0.3,0.1

Type RM Length L Ch R = 1 ,92840   ,757,757,757
BEGIN DESCRIPTION:
DUCK CREEK 56 1
END DESCRIPTION:
XS GIS Cut Line= 3
      3519507.04     10415014.11      3517632.07      10414224.2
      3516916.49     10414215.52
#Sta/Elev= 30
  4549.1  372.89    4587  372.95  4751.9  367.05  4852.3   359.5  4905.2  354.23
  4952.6  346.67  4976.3  345.74  4981.8  344.96  4994.9  337.24  4995.4  336.24
  5015.6  336.24  5016.1  337.24  5034.7  346.13    5054  347.44  5087.5  348.77
  5101.6  347.36  5105.8  346.73  5118.7  348.75  5205.5  347.12  5499.8  346.02
  6051.2  345.47  6140.5  346.07  6218.4  345.71  6271.3  347.77  6317.8  351.41
  6445.8  361.43  6586.2  365.74  6733.6  372.86  6983.7  372.06  7299.3  375.31
#Mann= 9 ,-1 , 0
  4549.1     .05       0  4994.9     .03       0  5016.1     .05       0
    5054     .16       0  5101.6     .05       0  6051.2      .1       0
  6140.5     .05       0  6317.8     .16       0  6445.8     .05       0
Bank Sta=4976.3,5034.7
XS Rating Curve= 0 ,0
Exp/Cntr=0.3,0.1

Type RM Length L Ch R = 1 ,92083   ,1070,1070,1070
BEGIN DESCRIPTION:
DUCK CREEK 56 2
END DESCRIPTION:
XS GIS Cut Line= 3
      3519916.61     10414232.34      3517533.84     10414188.94
      3516652.77     10414336.51
#Sta/Elev= 30
  4485.4  366.93  4509.9  366.68  4539.9  364.88  4796.7   348.1  4861.3  347.75
  4872.9  347.48    4970  347.23  4989.3   336.3  4989.8   335.3  5010.1   335.3
  5010.6   336.3    5020  343.26    5030  346.36  5070.5  347.01  5460.1  344.81
  5650.1   345.9  5740.1  344.86  5870.1  345.88  6148.7  345.62  6220.2  344.87
    6354  345.48  6410.2  345.38  6452.8  347.16  6551.6  353.05  6580.2  355.17
  6810.3  366.67  6866.9  370.47    6921  372.63  7164.4  372.04  7761.9  377.14
#Mann= 10 ,-1 , 0
  4485.4     .05       0  4861.3     .16       0  4872.9     .12       0
  4989.3     .07       0  5010.6     .12       0  5070.5     .05       0
  6148.7     .12       0    6354     .05       0  6452.8     .16       0
  6551.6     .05       0
Bank Sta=4970,5030
XS Rating Curve= 0 ,0
Exp/Cntr=0.3,0.1

Type RM Length L Ch R = 1 ,91013   ,648,648,648
BEGIN DESCRIPTION:
DUCK CREEK 55 4
END DESCRIPTION:
XS GIS Cut Line= 3
      3519964.42     10414006.66      3517394.95     10413338.25
       3516570.3     10413103.87
#Sta/Elev= 30
    4166  366.69  4240.5  367.16  4286.2  365.66  4453.2  351.04  4550.7  345.35
  4625.7  346.86  4943.4  346.38  4974.4   342.5  4984.7  339.38  4989.5  334.69
    4990  333.69  5010.8  334.69    5026  342.81  5040.7  346.52  5129.1  345.27
  5239.3  343.63  5542.2  343.86  5929.3  346.04  6117.9  346.93  6249.1  347.22
  6311.1  347.78  6549.7  350.31  6630.8  354.89  6706.6  364.82  6819.9  370.97
  7193.9  374.96    7215  375.51  7523.8  382.75  7630.6  387.74  7678.3  387.64
#Mann= 14 ,-1 , 0
    4166     .05       0  4453.2     .16       0  4625.7     .12       0
  4989.5     .07       0  5010.8     .12       0  5129.1     .05       0
  5239.3      .1       0  5542.2     .05       0  5929.3     .16       0
  6117.9      .1       0  6249.1     .16       0  6311.1     .05       0
  7193.9     .16       0    7215     .05       0
Bank Sta=4943.4,5040.7
XS Rating Curve= 0 ,0
Exp/Cntr=0.3,0.1

Type RM Length L Ch R = 1 ,90365   ,1376,1376,1376
BEGIN DESCRIPTION:
DUCK CREEK 55 3
END DESCRIPTION:
XS GIS Cut Line= 3
      3520228.19     10413592.32      3519302.74     10413205.58
      3517857.59     10411806.56
#Sta/Elev= 30
  4288.2  367.13  4554.9  362.56  4665.7  353.44    4821  345.17  4956.3  345.55
  4966.8  343.85  4974.7  338.75  4977.8  333.78  4978.3  332.78  4999.1  333.78
  5003.9  335.69  5010.1  341.36  5020.9  344.92    5057  345.95  5203.1  344.49
    5217  344.37  5384.7  343.95  5507.2  343.77  5725.8  341.55  5747.1  343.29
  5919.2   343.5  6178.5  345.98  6397.7  346.06  6454.2  344.31  6574.4  351.88
  6666.5  362.71    6730  365.89  6906.7  378.44  7076.5   380.4  7302.6  378.36
#Mann= 9 ,-1 , 0
  4288.2     .05       0  4665.7     .16       0  4977.8     .07       0
  4999.1     .16       0  5203.1     .05       0    5217     .16       0
  5384.7     .05       0  5507.2      .1       0  5919.2     .05       0
Bank Sta=4956.3,5020.9
XS Rating Curve= 0 ,0
Exp/Cntr=0.3,0.1