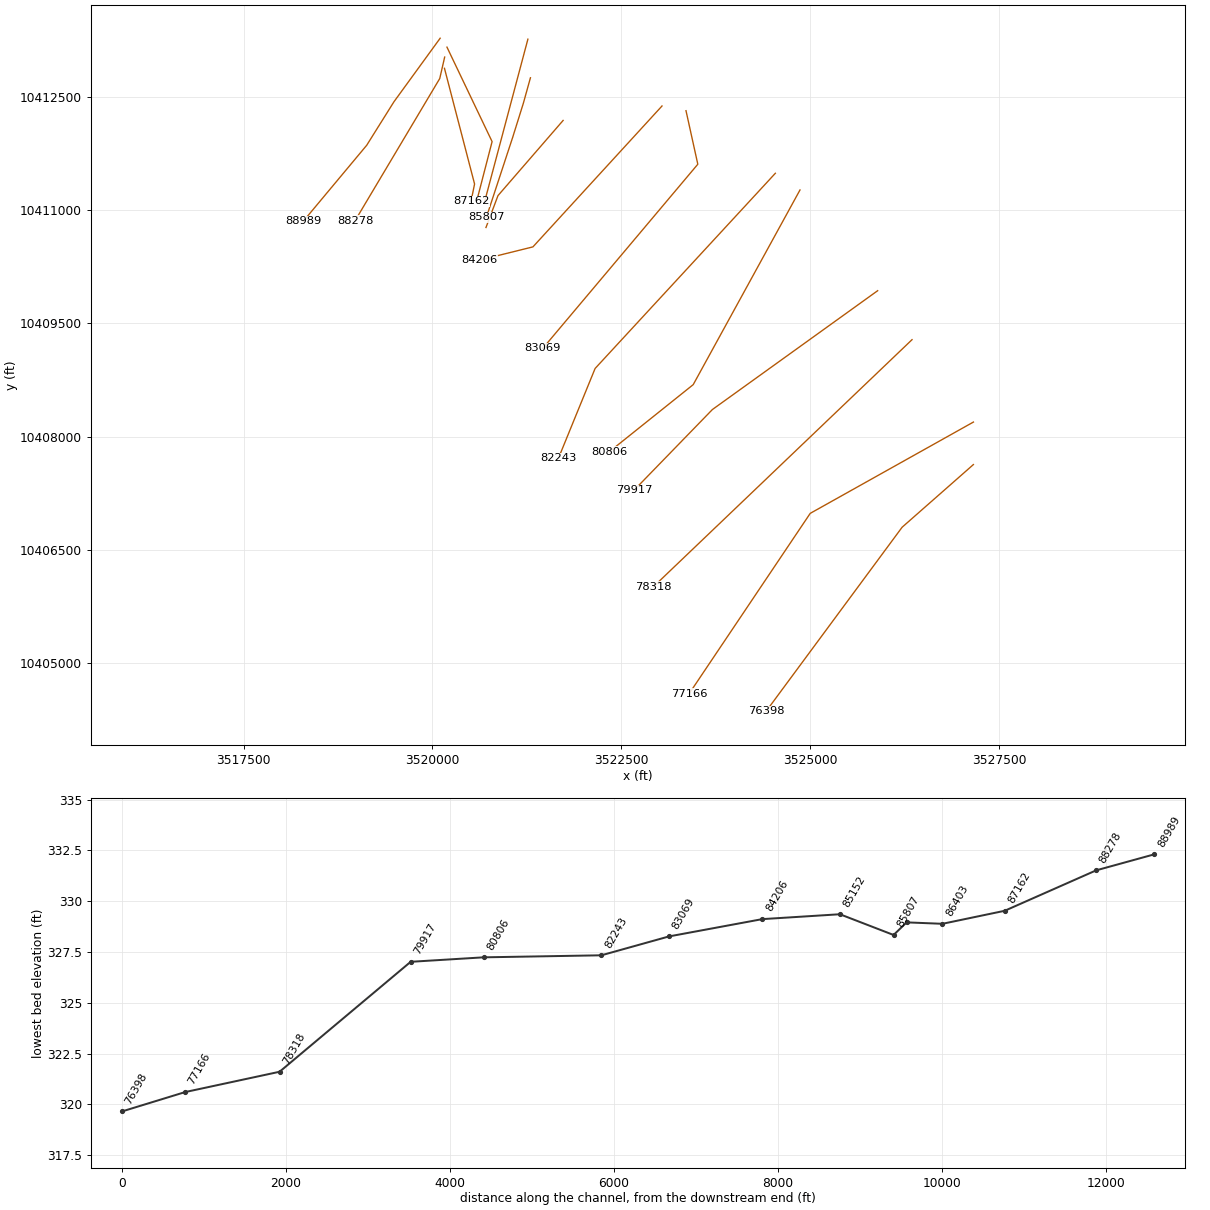
HEC-RAS study DUCK CREEK.prj: DUCK CREEK Base Level Engineering

--- DUCK CREEK.g01 (geometry) --- (continued)

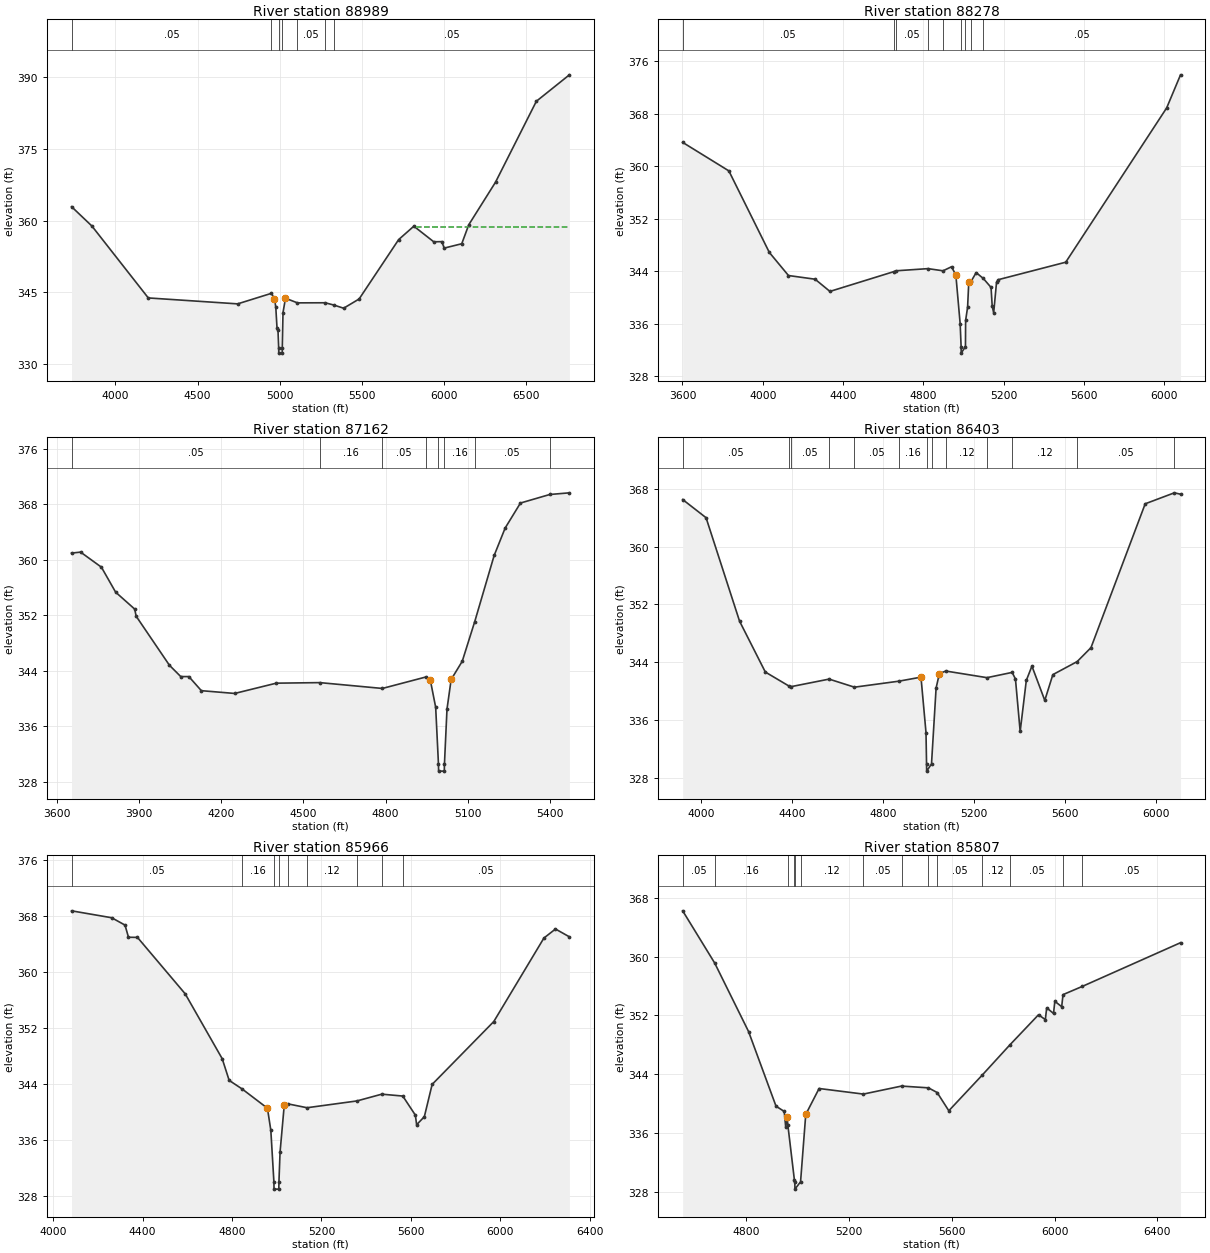
Type RM Length L Ch R = 1 ,88989   ,711,711,711
BEGIN DESCRIPTION:
DUCK CREEK 54 2
END DESCRIPTION:
XS GIS Cut Line= 4
      3520101.36     10413275.04      3519490.24     10412434.74
      3519129.13     10411858.35      3518288.84     10410851.39
#Sta/Elev= 30
  3732.7  362.93  3856.7  358.88  4199.8  343.85  4743.8  342.61    4949  344.81
    4968  343.71    4976  341.92  4983.4  337.57  4989.3  337.18  4993.7  333.31
  4994.2  332.31  5014.9  332.31  5015.4  333.31  5019.9  340.78    5035  343.79
  5107.7  342.82  5276.5  342.84  5330.8  342.35    5389   341.7  5483.2  343.63
    5724  356.05  5816.4  358.85  5937.5  355.59  5986.9  355.62  6001.2  354.27
    6108  355.18  6150.9  359.16  6313.6  368.05  6562.2  384.97  6763.4   390.5
#Mann= 7 ,-1 , 0
  3732.7     .05       0    4949     .16       0  4993.7     .07       0
  5015.4     .16       0  5107.7     .05       0  5276.5      .1       0
  5330.8     .05       0
#XS Ineff= 2 , 0
                         5826.51          358.66
Permanent Ineff=
       F       F
Bank Sta=4968,5035
XS Rating Curve= 0 ,0
Exp/Cntr=0.3,0.1

Type RM Length L Ch R = 1 ,88278   ,1116,1116,1116
BEGIN DESCRIPTION:
DUCK CREEK 55 1
END DESCRIPTION:
XS GIS Cut Line= 3
      3520161.08     10413025.68      3520095.97     10412741.79
      3518976.62     10410862.32
#Sta/Elev= 30
  3601.2  363.62  3831.1  359.28  4032.6  346.86    4128  343.34  4260.4  342.78
  4334.4  340.92  4652.2  343.93  4663.6  344.06  4822.5  344.39  4897.6  344.06
  4939.9  344.68  4961.4   343.4  4982.8  336.01  4987.5  332.52    4988  331.52
  5009.2  332.52    5010   336.5  5019.8   338.5  5025.6  342.29  5037.9  342.49
  5062.6  343.78  5098.1  342.89  5136.6  341.53  5142.4  338.66  5149.7  337.66
  5163.8  342.28  5172.9  342.71  5508.5  345.37    6011  368.87    6080  373.91
#Mann= 9 ,-1 , 0
  3601.2     .05       0  4652.2     .16       0  4663.6     .05       0
  4822.5     .16       0  4897.6     .05       0  4987.5     .03       0
  5009.2     .05       0  5037.9     .16       0  5098.1     .05       0
Bank Sta=4961.4,5025.6
XS Rating Curve= 0 ,0
Exp/Cntr=0.3,0.1

Type RM Length L Ch R = 1 ,87162   ,759,759,759
BEGIN DESCRIPTION:
DUCK CREEK 55 0
END DESCRIPTION:
XS GIS Cut Line= 3
      3520158.46     10412877.24      3520556.91     10411345.95
      3520509.95     10411116.69
#Sta/Elev= 30
  3654.3  360.94  3687.3  361.08  3763.2  358.91  3815.1  355.31  3884.7  352.87
  3889.9  351.85  4011.4  344.78  4052.7  343.15  4082.2  343.15  4127.8  341.12
  4249.4  340.72  4401.2   342.2    4560  342.28  4788.2  341.44  4947.9   343.1
  4963.3  342.62  4982.7  338.73  4992.9  330.53  4993.4  329.53  5014.2  329.53
  5014.7  330.53    5024  338.46  5039.2  342.73  5079.7  345.36  5125.3  351.08
  5196.1   360.6  5236.2  364.55    5292  368.15    5399  369.38  5470.6  369.62
#Mann= 8 ,-1 , 0
  3654.3     .05       0    4560     .16       0  4788.2     .05       0
  4947.9     .16       0  4992.9     .07       0  5014.7     .16       0
  5125.3     .05       0    5399     .08       0
Bank Sta=4963.3,5039.2
XS Rating Curve= 0 ,0
Exp/Cntr=0.3,0.1

Type RM Length L Ch R = 1 ,86403   ,437,437,437
BEGIN DESCRIPTION:
DUCK CREEK 54 3
END DESCRIPTION:
XS GIS Cut Line= 3
      3520191.63     10413156.96      3520788.85     10411906.97
      3520587.45     10411129.15
#Sta/Elev= 30
  3918.2  366.55    4021  364.03  4168.2  349.69  4281.6  342.63  4385.9  340.68
  4395.9  340.61    4562  341.65  4673.4  340.53  4868.3  341.36  4965.9  341.92
    4988  334.24  4990.4  329.89  4990.9  328.89  5012.2  329.89  5032.4  340.41
  5046.7  342.41  5074.9  342.77  5256.1  341.85  5366.8  342.58  5381.3  341.66
    5402  334.39    5429  341.47  5453.7  343.45  5510.2   338.7  5545.7  342.27
  5652.6  344.08  5713.3  346.01  5951.7  365.96  6079.8  367.48    6107  367.29
#Mann= 13 ,-1 , 0
  3918.2     .05       0  4385.9     .16       0  4395.9     .05       0
    4562     .16       0  4673.4     .05       0  4868.3     .16       0
  4990.4     .07       0  5012.2     .16       0  5074.9     .12       0
  5256.1     .16       0  5366.8     .12       0  5652.6     .05       0
  6079.8     .08       0
Bank Sta=4965.9,5046.7
XS Rating Curve= 0 ,0
Exp/Cntr=0.3,0.1

Type RM Length L Ch R = 1 ,85966   ,159,159,159
BEGIN DESCRIPTION:
DUCK CREEK 54 0
END DESCRIPTION:
XS GIS Cut Line= 2
      3521262.62     10413262.58      3520689.72     10411111.57
#Sta/Elev= 30
  4082.6  368.76  4262.1  367.77  4321.6  366.72  4337.1  364.98  4377.3  364.96
  4590.7  356.89  4756.2  347.61  4787.3  344.51    4845  343.29  4958.4  340.53
  4973.6  337.37  4987.4  329.96  4987.9  328.96  5009.3  328.96  5009.8  329.96
  5014.9  334.27  5033.5  340.93  5050.3  341.15  5135.6   340.6  5358.3  341.57
  5469.8  342.54  5563.6  342.27  5619.9  339.54  5625.5  338.17    5660  339.32
  5694.9  343.94  5970.6  352.93  6194.7  364.87  6246.4  366.16  6308.6  365.04
#Mann= 9 ,-1 , 0
  4082.6     .05       0    4845     .16       0  4987.4     .07       0
  5009.8     .16       0  5050.3     .05       0  5135.6     .12       0
  5358.3     .05       0  5469.8     .16       0  5563.6     .05       0
Bank Sta=4958.4,5033.5
XS Rating Curve= 0 ,0
Exp/Cntr=0.3,0.1

Type RM Length L Ch R = 1 ,85807   ,655,655,655
BEGIN DESCRIPTION:
DUCK CREEK 54 1
END DESCRIPTION:
XS GIS Cut Line= 4
      3521296.32     10412751.68      3521202.56     10412414.86
       3521060.2     10411959.99      3520713.34     10410905.53
#Sta/Elev= 30
  4553.7  366.23  4678.1  359.13  4809.9   349.8  4916.8  339.63  4948.6  338.92
  4954.5  336.79  4959.7  338.14  4962.8  337.05  4988.1  329.62  4989.8  329.34
  4990.3  328.34  5012.2  329.34  5032.4  338.51  5084.3  342.04  5256.5  341.28
  5404.8  342.37  5509.5  342.13  5543.5  341.49  5588.8  339.01  5718.9  343.87
  5825.8  347.96  5937.7  352.08  5964.2  351.42  5969.5  353.02    5996  352.26
  6001.2  353.91  6027.8  353.18    6033  354.82    6108  355.94    6490  361.89
#Mann= 14 ,-1 , 0
  4553.7     .05       0  4678.1     .16       0  4962.8     .05       0
  4988.1     .12       0  4989.8     .07       0  5012.2     .12       0
  5256.5     .05       0  5404.8     .12       0  5509.5     .16       0
  5543.5     .05       0  5718.9     .12       0  5825.8     .05       0
    6033     .16       0    6108     .05       0
Bank Sta=4959.7,5032.4
XS Rating Curve= 0 ,0
Exp/Cntr=0.3,0.1

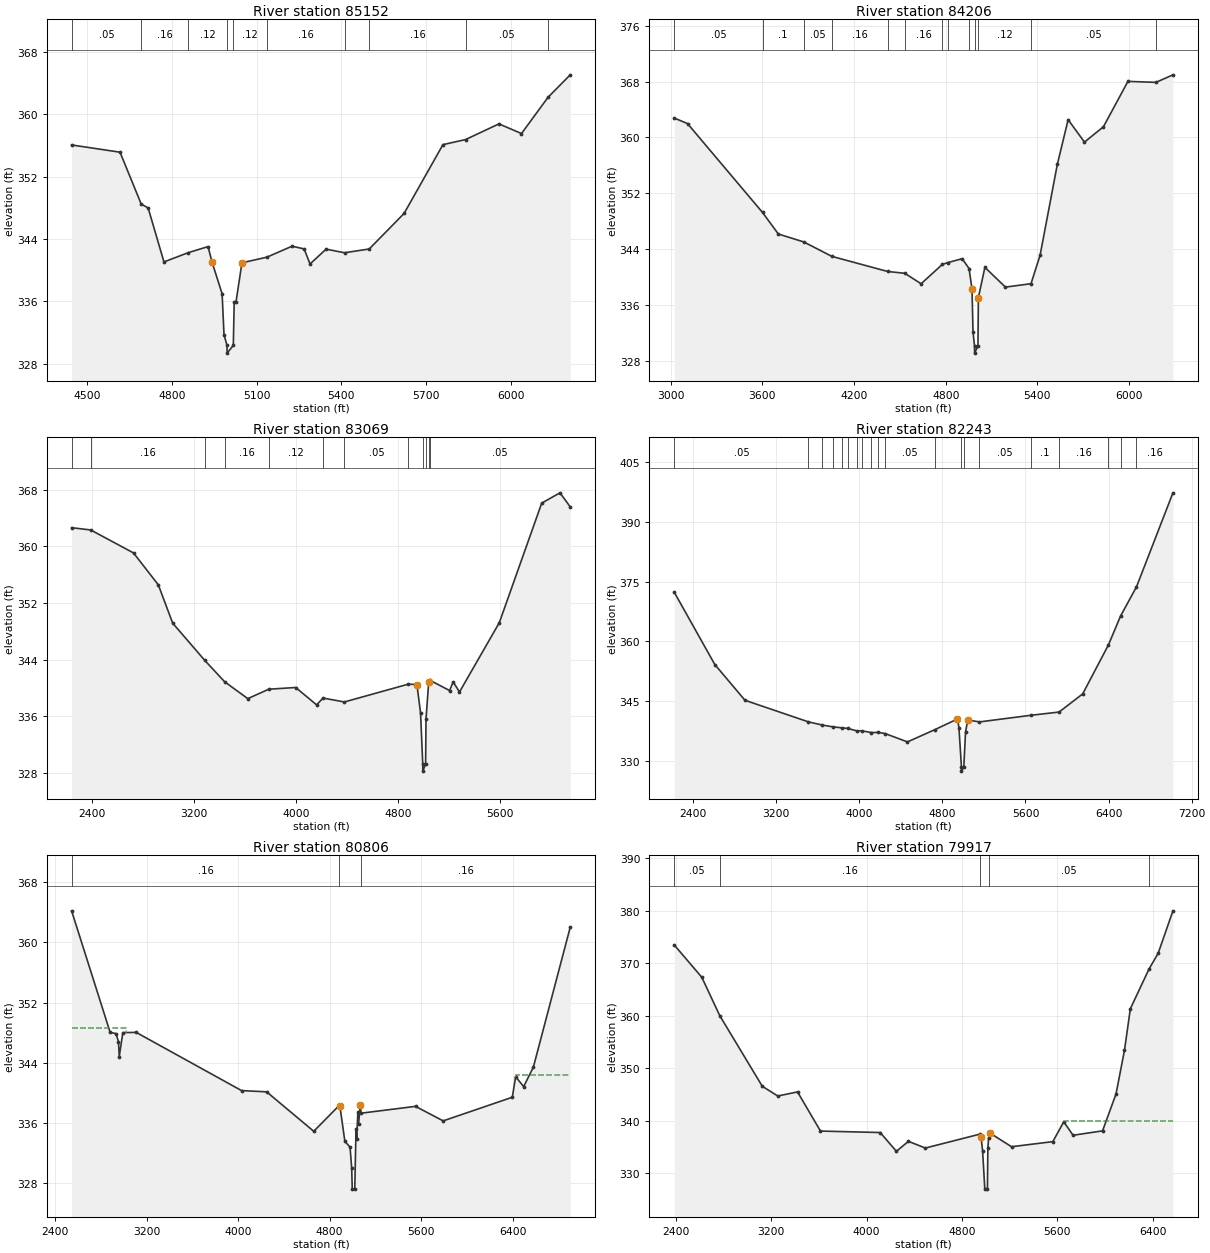
Type RM Length L Ch R = 1 ,85152   ,946,946,946
BEGIN DESCRIPTION:
DUCK CREEK 53 2
END DESCRIPTION:
XS GIS Cut Line= 3
      3521728.77     10412187.09       3520866.8     10411192.31
      3520707.94      10410770.4
#Sta/Elev= 30
  4444.5  356.05  4616.1  355.12  4691.2  348.47  4715.8  347.97  4771.8  341.05
    4857  342.23  4928.1  343.02  4941.8  341.07  4977.9  336.97  4984.6  331.74
  4995.2  330.36  4995.7  329.36  5017.6  330.36  5020.7  335.91  5027.3  335.97
  5048.2  340.94  5136.5  341.66  5225.8  343.07  5268.6  342.72  5289.4  340.79
  5346.4  342.69  5411.8  342.23  5499.2  342.71  5622.8  347.27  5760.5  356.09
  5840.6  356.74  5958.9  358.75  6038.8  357.51  6132.9  362.16  6211.6  365.04
#Mann= 10 ,-1 , 0
  4444.5     .05       0  4691.2     .16       0    4857     .12       0
  4995.2     .07       0  5017.6     .12       0  5136.5     .16       0
  5411.8     .12       0  5499.2     .16       0  5840.6     .05       0
  6132.9     .16       0
Bank Sta=4941.8,5048.2
XS Rating Curve= 0 ,0
Exp/Cntr=0.3,0.1

Type RM Length L Ch R = 1 ,84206   ,1137,1137,1137
BEGIN DESCRIPTION:
DUCK CREEK 53 0
END DESCRIPTION:
XS GIS Cut Line= 3
       3523037.5     10412378.34      3521329.14     10410513.73
      3520616.35     10410336.83
#Sta/Elev= 30
  3023.6  362.77  3110.1  361.98  3600.9  349.26  3704.6  346.17  3870.7  345.04
  4054.6  342.97  4419.6  340.81  4531.8  340.55  4638.8  339.05  4778.2  341.83
  4812.2  342.07  4907.6  342.64  4952.5  341.23  4971.8  338.33  4978.5   332.2
  4988.3  330.12  4988.8  329.12  5010.7  330.12  5013.7  337.07  5056.2   341.4
  5190.7  338.57  5358.1  339.06  5417.6  343.15  5530.4  356.15    5601  362.54
  5707.8  359.33  5831.9  361.52  5992.2  368.02  6175.9  367.88  6286.9  368.96
#Mann= 13 ,-1 , 0
  3023.6     .05       0  3600.9      .1       0  3870.7     .05       0
  4054.6     .16       0  4419.6     .05       0  4531.8     .16       0
  4778.2     .05       0  4812.2     .16       0  4952.5     .12       0
  4988.3     .07       0  5010.7     .12       0  5358.1     .05       0
  6175.9      .1       0
Bank Sta=4971.8,5013.7
XS Rating Curve= 0 ,0
Exp/Cntr=0.3,0.1

Type RM Length L Ch R = 1 ,83069   ,826,826,826
BEGIN DESCRIPTION:
DUCK CREEK 51 1
END DESCRIPTION:
XS GIS Cut Line= 3
      3523355.18     10412315.83      3523511.43     10411607.48
      3521459.33     10409169.96
#Sta/Elev= 30
  2238.1  362.62  2387.9   362.3  2723.7  359.06  2918.3  354.56  3031.1  349.15
  3283.1  343.89  3438.6  340.88  3620.3   338.5  3784.9  339.83  3996.1  340.07
    4160  337.62  4210.7  338.58  4378.2  338.03    4879  340.54  4946.8  340.49
  4975.4  336.51  4992.8  329.27  4993.3  328.27  5015.2  329.27  5018.3   335.6
  5039.2  340.78  5041.9   340.9  5050.6  341.08    5203  339.64  5231.6  340.85
    5281  339.44  5593.2  349.21  5926.1  366.09  6069.1  367.54  6149.8  365.56
#Mann= 12 ,-1 , 0
  2238.1     .05       0  2387.9     .16       0  3283.1     .05       0
  3438.6     .16       0  3784.9     .12       0  4210.7     .16       0
  4378.2     .05       0    4879     .16       0  4992.8     .07       0
  5015.2     .16       0  5041.9     .12       0  5050.6     .05       0
Bank Sta=4946.8,5039.2
XS Rating Curve= 0 ,0
Exp/Cntr=0.3,0.1

Type RM Length L Ch R = 1 ,82243   ,1437,1437,1437
BEGIN DESCRIPTION:
DUCK CREEK 5 1
END DESCRIPTION:
XS GIS Cut Line= 3
      3524537.45     10411487.66      3522152.05     10408904.35
       3521667.1     10407716.63
#Sta/Elev= 30
  2220.2  372.33  2610.1  354.16  2900.5  345.16  3511.3  339.73  3645.4  338.93
  3748.9  338.47  3837.2  338.22  3887.6  338.09  3976.9  337.47  4026.2  337.48
  4116.5  337.04  4183.6  337.08  4249.5  336.79  4464.3  334.69  4727.3  337.77
  4945.8  340.46  4959.9  338.26  4983.7  328.34  4984.2  327.34  5006.4  328.34
  5023.4  337.25    5045  340.22  5156.7  339.72  5652.9  341.39  5923.5   342.2
  6150.7  346.77  6398.5  359.09    6515  366.35  6668.4  373.69  7019.3  397.35
#Mann= 20 ,-1 , 0
  2220.2     .05       0  3511.3     .12       0  3645.4     .05       0
  3748.9     .12       0  3837.2     .05       0  3887.6     .12       0
  3976.9     .05       0  4026.2     .12       0  4116.5     .05       0
  4183.6     .12       0  4249.5     .05       0  4727.3     .12       0
  4983.7     .07       0  5006.4     .12       0  5156.7     .05       0
  5652.9      .1       0  5923.5     .16       0  6398.5     .05       0
    6515     .05       0  6668.4     .16       0
Bank Sta=4945.8,5045
XS Rating Curve= 0 ,0
Exp/Cntr=0.3,0.1

Type RM Length L Ch R = 1 ,80806   ,889,889,889
BEGIN DESCRIPTION:
DUCK CREEK 48 0
END DESCRIPTION:
XS GIS Cut Line= 3
      3524863.84     10411267.09      3523450.62     10408690.66
       3522339.5     10407801.76
#Sta/Elev= 30
    2543  364.19    2880  348.06  2931.3  347.89  2953.1  346.81  2959.8  344.83
    2991  348.02  3108.1  348.05  4029.8  340.32  4248.6  340.16    4661  334.92
  4883.8  338.35  4889.5   338.3  4933.1  333.59  4978.6  332.81  4992.8  330.02
  4997.9  327.24  5019.8  327.24  5030.7  335.24  5036.4  333.94  5046.8  337.43
  5052.5  335.85  5068.6  338.43  5074.3  337.32  5551.1  338.23  5792.8   336.3
  6397.9  339.44  6426.7  342.17  6497.1  340.85    6582  343.44  6904.5  362.02
#Mann= 3 ,-1 , 0
    2543     .16       0  4883.8     .12       0  5074.3     .16       0
#XS Ineff= 2 , 0
       0 3019.89  348.58 6426.14       0  342.37
Permanent Ineff=
       T       T
Bank Sta=4889.5,5068.6
XS Rating Curve= 0 ,0
Exp/Cntr=0.3,0.1

Type RM Length L Ch R = 1 ,79917   ,1599,1599,1599
BEGIN DESCRIPTION:
DUCK CREEK 49 0
END DESCRIPTION:
XS GIS Cut Line= 3
      3525891.61     10409933.73      3523704.09      10408360.8
      3522666.53       10407292.
#Sta/Elev= 30
  2387.1  373.47  2618.1  367.33  2768.3  360.04  3125.5  346.59  3255.3  344.74
    3421  345.52  3613.7  338.07  4114.6  337.79  4250.8  334.22  4351.5  336.11
  4493.9  334.84  4950.1  337.48  4960.7  336.96  4973.9  334.33  4992.4  327.02
  5014.3  327.02  5018.1  334.76  5024.2  336.81  5032.8  337.73  5216.6  335.09
  5563.1  336.06    5655  339.83  5732.9  337.27  5980.4  338.11  6093.5  345.14
  6164.3  353.44  6213.7  361.35  6369.3  368.86    6447   371.9    6571  379.98
#Mann= 5 ,-1 , 0
  2387.1     .05       0  2768.3     .16       0  4950.1     .12       0
  5024.2     .05       0  6369.3     .16       0
#XS Ineff= 2 , 0
       0                 5656.25       0   339.9
Permanent Ineff=
       F       T
Bank Sta=4960.7,5032.8
XS Rating Curve= 0 ,0
Exp/Cntr=0.3,0.1

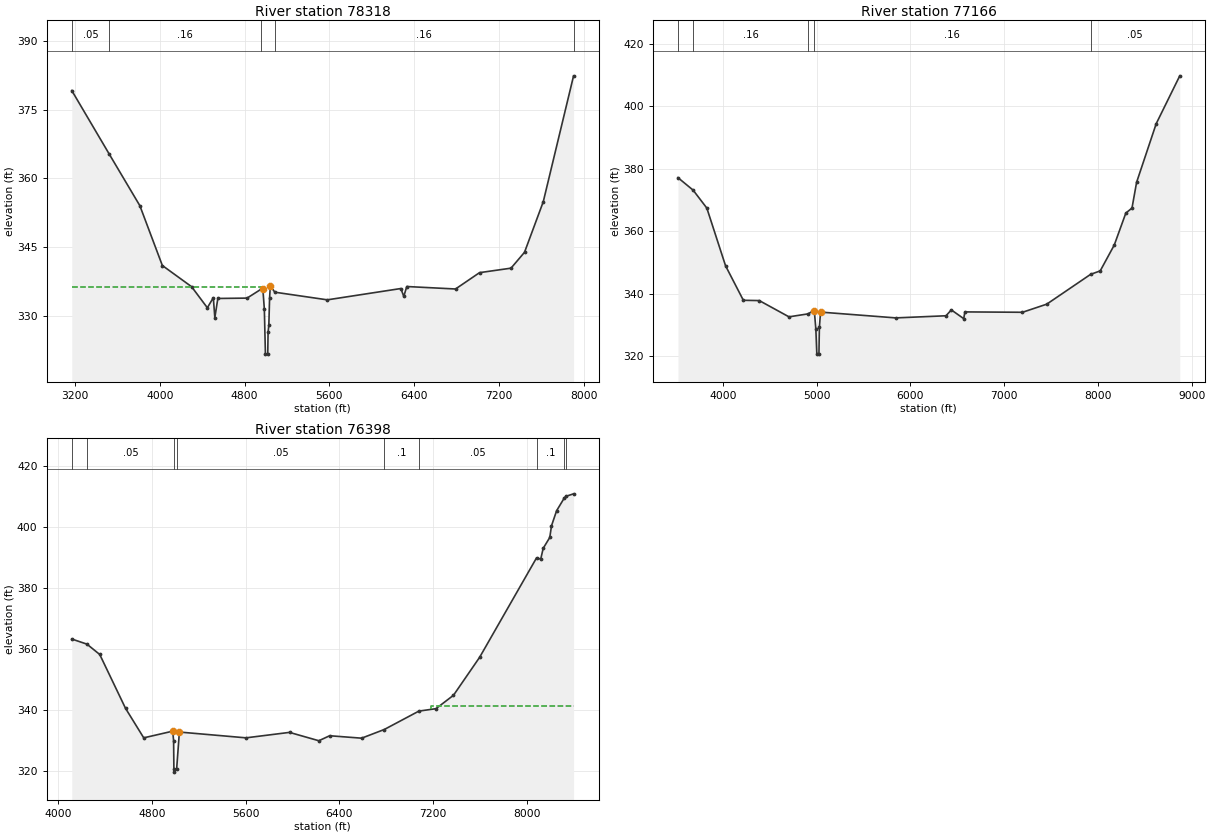
Type RM Length L Ch R = 1 ,78318   ,1152,1152,1152
BEGIN DESCRIPTION:
DUCK CREEK 47 1
END DESCRIPTION:
XS GIS Cut Line= 2
      3526346.48     10409285.59      3522923.82     10406015.67
#Sta/Elev= 30
  3169.9   379.2  3522.2  365.36  3812.2  354.04  4024.5  340.97  4300.3  336.34
  4448.8  331.74  4505.4  333.94  4519.5  329.57  4547.8  333.77  4823.7  333.85
  4958.3  335.83  4972.4   335.9  4986.6  331.44  4996.7  321.61  5018.6  321.61
  5021.8  326.38    5029  327.97    5036  333.86    5043  336.53  5085.3  335.14
  5580.7  333.47  6273.9  335.94  6301.9  334.23  6330.2  336.38    6790  335.84
  7016.4  339.41  7313.3  340.39  7440.7  343.86  7617.5   354.9  7903.5  382.41
#Mann= 5 ,-1 , 0
  3169.9     .05       0  3522.2     .16       0  4958.3     .12       0
  5085.3     .16       0  7903.5     .05       0
#XS Ineff= 2 , 0
       0  4951.7  336.21               0
Permanent Ineff=
       T       F
Bank Sta=4972.4,5043
XS Rating Curve= 0 ,0
Exp/Cntr=0.3,0.1

Type RM Length L Ch R = 1 ,77166   ,768,768,768
BEGIN DESCRIPTION:
DUCK CREEK 46 0
END DESCRIPTION:
XS GIS Cut Line= 3
      3527158.99     10408195.31      3524999.23     10406986.95
      3523396.08     10404599.58
#Sta/Elev= 30
  3522.6  377.16  3684.4  373.16  3830.6  367.41  4030.4  348.91    4220  337.86
  4389.9  337.77  4706.4  332.56    4910  333.51  4971.3  334.61    4977  334.42
    4993   328.6  5003.5  320.61  5025.9  320.61  5030.6  329.16    5043  334.08
  5845.2  332.22  6380.6   332.9  6437.6  334.78  6569.6  331.98    6582  334.14
  7196.3  334.02  7454.7  336.62  7922.8  346.18  8024.8  347.28  8174.9  355.58
  8297.9   365.8  8363.8  367.42  8412.9  375.67  8621.9  394.45  8873.1  409.79
#Mann= 5 ,-1 , 0
  3522.6     .05       0  3684.4     .16       0    4910     .12       0
  4971.3     .16       0  7922.8     .05       0
Bank Sta=4977,5043
XS Rating Curve= 0 ,0
Exp/Cntr=0.3,0.1

Type RM Length L Ch R = 1 ,76398   ,523,523,523
BEGIN DESCRIPTION:
DUCK CREEK 45 1
END DESCRIPTION:
XS GIS Cut Line= 3
      3527158.66     10407632.67      3526215.54     10406803.52
      3524414.28     10404366.02
#Sta/Elev= 30
  4113.7   363.3  4243.4  361.62  4352.7  358.23  4572.8  340.59  4728.5   330.9
  4976.1  333.09  4983.7  329.99  4986.2  320.66  4986.7  319.66  5009.6  320.66
    5033   332.8  5602.1   330.9  5973.7  332.69  6224.3  329.95  6316.8  331.59
  6589.6  330.79  6782.9  333.63  7079.1  339.67  7224.5  340.46  7374.5  344.86
  7597.5  357.29  8083.9   389.9  8119.8  389.52  8140.8  393.04  8197.1   396.6
  8211.7  400.42  8255.6  405.38    8322   409.6  8337.6  410.11  8400.3   410.9
#Mann= 9 ,-1 , 0
  4113.7     .16       0  4243.4     .05       0  4986.2     .03       0
  5009.6     .05       0  6782.9      .1       0  7079.1     .05       0
  8083.9      .1       0    8322     .16       0  8337.6      .1       0
#XS Ineff= 2 , 0
                         7183.22          341.41
Permanent Ineff=
       F       F
Bank Sta=4976.1,5033
XS Rating Curve= 0 ,0
Exp/Cntr=0.3,0.1