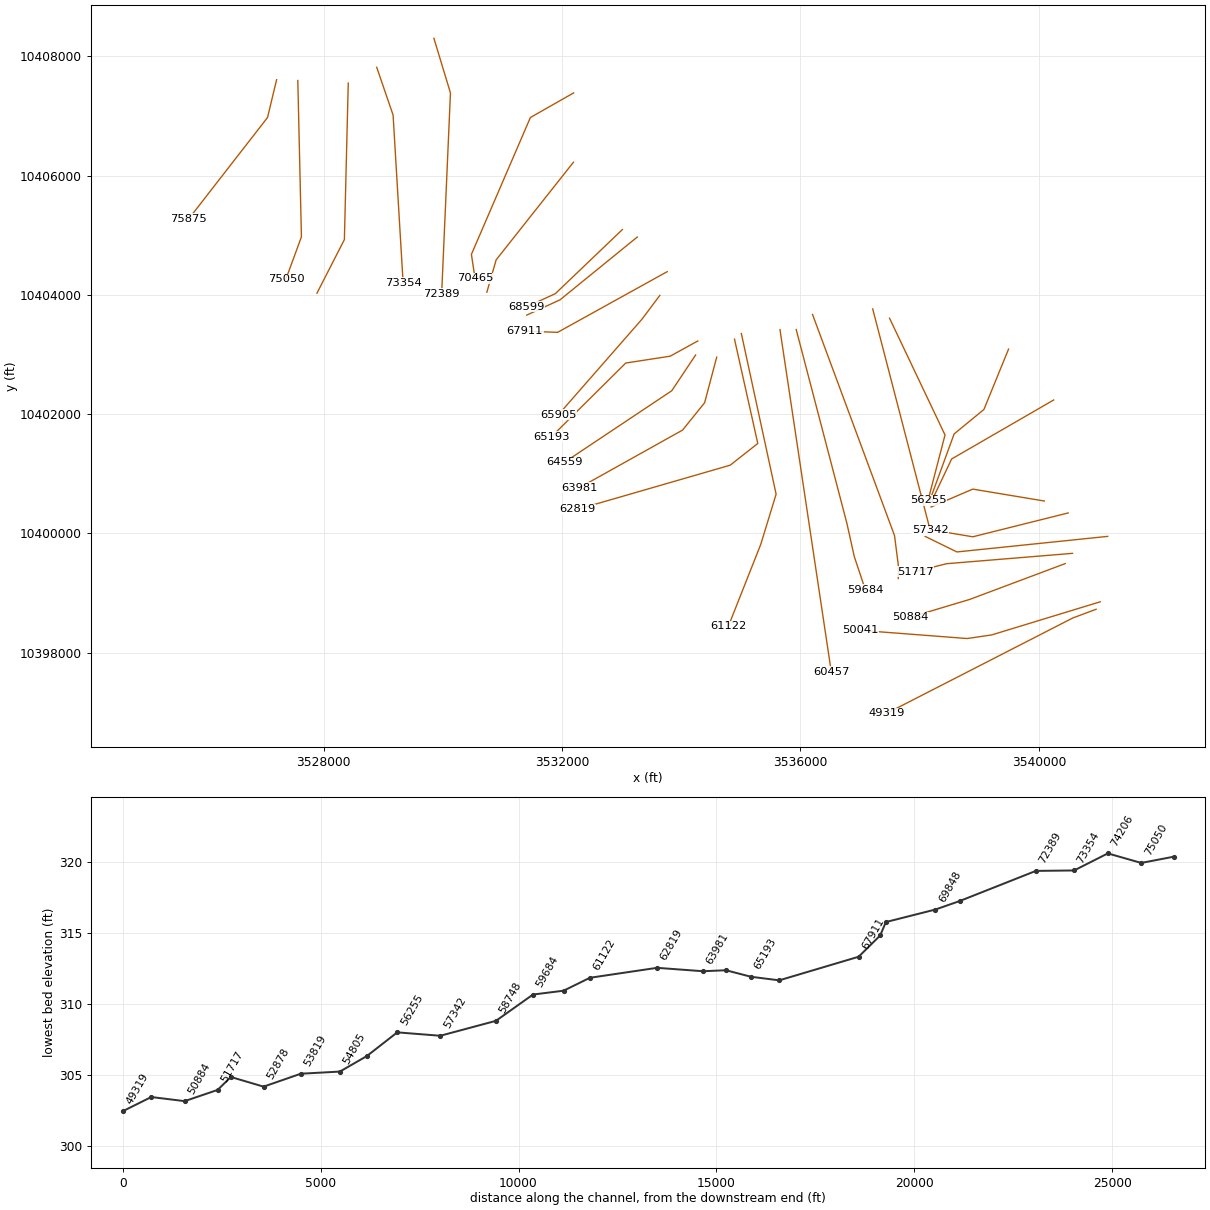
HEC-RAS study DUCK CREEK.prj: DUCK CREEK Base Level Engineering

--- DUCK CREEK.g01 (geometry) --- (continued)

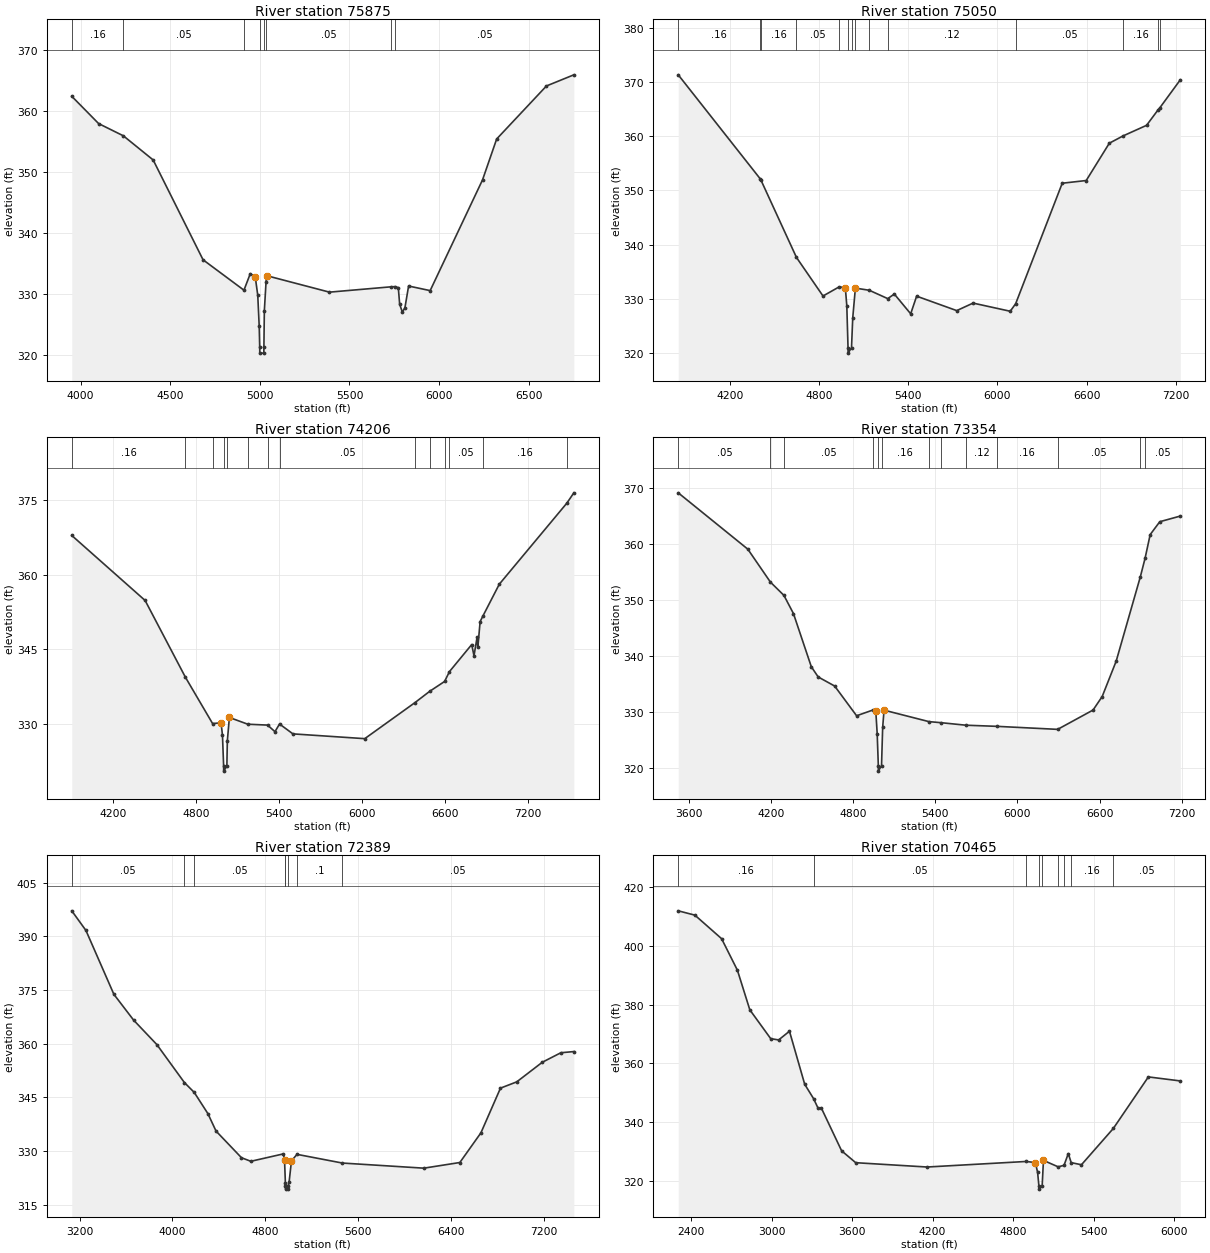
Type RM Length L Ch R = 1 ,75875   ,825,825,825
BEGIN DESCRIPTION:
DUCK CREEK 47 0
END DESCRIPTION:
XS GIS Cut Line= 3
      3527212.78      10407609.2      3527060.87     10406975.51
      3525741.41     10405278.44
#Sta/Elev= 30
  3950.7  362.35  4100.5  357.89  4238.5  355.89  4404.9  351.94  4683.2  335.62
  4911.4  330.65  4946.8  333.36  4974.6  332.78  4988.4  329.83  4996.5  324.75
  4999.3  321.36  4999.8  320.36  5022.2  320.36  5022.7  321.36  5025.2  327.32
  5034.8  332.06  5038.2  333.02  5388.4  330.33  5731.4   331.2  5754.2  331.23
  5772.6  331.06  5780.2  328.35  5794.7   327.1  5809.2  327.72    5830  331.33
  5950.3  330.58  6242.6  348.69  6321.4  355.37  6599.2  364.04    6752  365.86
#Mann= 8 ,-1 , 0
  3950.7     .16       0  4238.5     .05       0  4911.4     .16       0
  4999.3     .07       0  5022.7     .16       0  5034.8     .05       0
  5731.4     .16       0  5754.2     .05       0
Bank Sta=4974.6,5038.2
XS Rating Curve= 0 ,0
Exp/Cntr=0.3,0.1

Type RM Length L Ch R = 1 ,75050   ,844,844,844
BEGIN DESCRIPTION:
DUCK CREEK 45 2
END DESCRIPTION:
XS GIS Cut Line= 3
      3527568.68     10407596.13      3527629.45     10404974.65
      3527369.04     10404262.87
#Sta/Elev= 30
  3851.3  371.37  4405.1  352.08  4407.3  351.96  4647.3  337.61    4826  330.48
  4933.5  332.15  4976.1  332.05  4986.1   328.7  4994.4  320.92  4994.9  319.92
  5017.8  320.92  5026.1  326.43  5043.9  331.94  5137.5  331.54  5261.6     330
  5306.2  330.84  5416.2  327.19  5456.2  330.45  5726.3  327.78  5836.3  329.17
  6086.4  327.66    6123  329.06  6436.5  351.33  6597.9  351.83  6753.5  358.73
  6845.5  360.07    7004  362.03  7081.6  364.89  7094.2   365.3  7231.4  370.45
#Mann= 14 ,-1 , 0
  3851.3     .16       0  4405.1     .05       0  4407.3     .16       0
  4647.3     .05       0  4933.5      .1       0  4994.4     .07       0
  5017.8      .1       0  5043.9     .16       0  5137.5     .05       0
  5261.6     .12       0    6123     .05       0  6845.5     .16       0
  7081.6     .05       0  7094.2     .16       0
Bank Sta=4976.1,5043.9
XS Rating Curve= 0 ,0
Exp/Cntr=0.3,0.1

Type RM Length L Ch R = 1 ,74206   ,852,852,852
BEGIN DESCRIPTION:
DUCK CREEK 44 3
END DESCRIPTION:
XS GIS Cut Line= 3
      3528415.04     10407552.81      3528349.93      10404926.9
      3527889.86     10404028.46
#Sta/Elev= 30
  3898.5  367.85  4429.8  354.81  4721.7  339.41  4918.3  330.13    4980  330.28
    4990  327.74  4998.3  321.59  4998.8  320.59  5021.7  321.59  5025.2  326.69
    5040  331.35    5173     330  5316.5  329.82  5370.1   328.5  5403.1  330.04
  5500.2  328.06  6020.3   327.1    6385  334.35  6490.9   336.6  6598.5  338.57
  6633.8  340.55  6794.9  345.97  6811.5  343.73  6833.7  347.41  6839.3  345.43
  6855.9  350.58  6876.7  351.73  6994.8  358.08  7484.2  374.34  7534.6   376.4
#Mann= 14 ,-1 , 0
  3898.5     .16       0  4721.7      .1       0  4918.3     .16       0
  4998.3     .07       0  5021.7     .16       0    5173     .05       0
  5316.5     .16       0  5403.1     .05       0    6385     .16       0
  6490.9     .05       0  6598.5     .16       0  6633.8     .05       0
  6876.7     .16       0  7484.2      .1       0
Bank Sta=4980,5040
XS Rating Curve= 0 ,0
Exp/Cntr=0.3,0.1

Type RM Length L Ch R = 1 ,73354   ,965,965,965
BEGIN DESCRIPTION:
DUCK CREEK 44 2
END DESCRIPTION:
XS GIS Cut Line= 3
      3528892.46     10407817.55      3529167.11     10407016.64
      3529335.18     10404202.05
#Sta/Elev= 30
  3523.1   369.1  4031.1  359.04  4196.4  353.15    4295  350.78  4364.5  347.53
    4495  338.03  4545.1  336.21  4665.3  334.59  4825.6  329.28    4943  330.29
  4965.8  330.06  4975.9   326.1  4984.2  320.39  4984.7  319.39  5007.6  320.39
  5015.9  327.19    5026  330.28    5354  328.23  5439.1  328.05  5624.5  327.59
  5849.5  327.39  6293.7  326.85  6552.2   330.3  6618.8  332.71  6721.2  339.04
  6897.9  354.13  6932.1  357.41  6969.4  361.64  7039.5  363.94  7189.4  364.95
#Mann= 13 ,-1 , 0
  3523.1     .05       0  4196.4     .16       0    4295     .05       0
    4943     .16       0  4984.2     .07       0  5007.6     .16       0
    5354     .12       0  5439.1     .16       0  5624.5     .12       0
  5849.5     .16       0  6293.7     .05       0  6897.9      .1       0
  6932.1     .05       0
Bank Sta=4965.8,5026
XS Rating Curve= 0 ,0
Exp/Cntr=0.3,0.1

Type RM Length L Ch R = 1 ,72389   ,1924,1924,1924
BEGIN DESCRIPTION:
DUCK CREEK 45 0
END DESCRIPTION:
XS GIS Cut Line= 3
      3529851.67     10408303.64      3530129.45     10407387.84
      3529981.88     10404019.77
#Sta/Elev= 30
  3132.4  397.15  3254.6  391.66  3495.3  373.82  3665.1  366.62    3866  359.76
  4103.4  349.15  4188.1   346.4  4305.8  340.47  4376.1  335.59  4595.4  328.14
  4676.2  327.14  4956.4  329.21  4966.4  327.63    4974  321.05  4974.8  320.36
  4975.3  319.36  4997.7  319.36  4998.2  320.36  5006.5  321.48  5026.5  327.27
  5074.1  329.08  5464.8  326.65  6167.6  325.22  6477.9   326.8  6659.5  335.09
  6828.2  347.59  6968.4  349.34  7188.6  354.82  7348.7  357.48  7460.7  357.81
#Mann= 8 ,-1 , 0
  3132.4     .05       0  4103.4      .1       0  4188.1     .05       0
    4974     .16       0  4974.8     .07       0  4998.2     .16       0
  5074.1      .1       0  5464.8     .05       0
Bank Sta=4966.4,5026.5
XS Rating Curve= 0 ,0
Exp/Cntr=0.3,0.1

Type RM Length L Ch R = 1 ,70465   ,617,617,617
BEGIN DESCRIPTION:
DUCK CREEK 44 1
END DESCRIPTION:
XS GIS Cut Line= 4
       3532195.4     10407387.83      3531470.59     10406975.51
      3530481.01     10404679.51      3530541.72     10404276.22
#Sta/Elev= 30
  2304.3   411.9  2428.5  410.43  2627.4  402.43  2745.3   391.7  2837.8  378.23
  2993.5  368.42  3052.6  367.99  3133.3  370.95  3246.9   352.9  3312.5  348.05
  3346.5  344.76    3370   344.9    3522  330.27    3627  326.23  4159.1  324.76
  4898.2  326.65  4966.2  326.26  4982.7  322.92  4992.5  318.24    4993  317.24
  5016.5  318.24  5026.2  327.01  5135.6  324.83  5179.4  325.33  5211.4  329.33
    5233  326.25  5309.4  325.53  5546.8  337.87  5808.1  355.41  6046.2  354.04
#Mann= 9 ,-1 , 0
  2304.3     .16       0  3312.5     .05       0  4898.2     .12       0
  4992.5     .07       0  5016.5     .12       0  5135.6     .16       0
  5179.4      .1       0    5233     .16       0  5546.8     .05       0
Bank Sta=4966.2,5026.2
XS Rating Curve= 0 ,0
Exp/Cntr=0.3,0.1

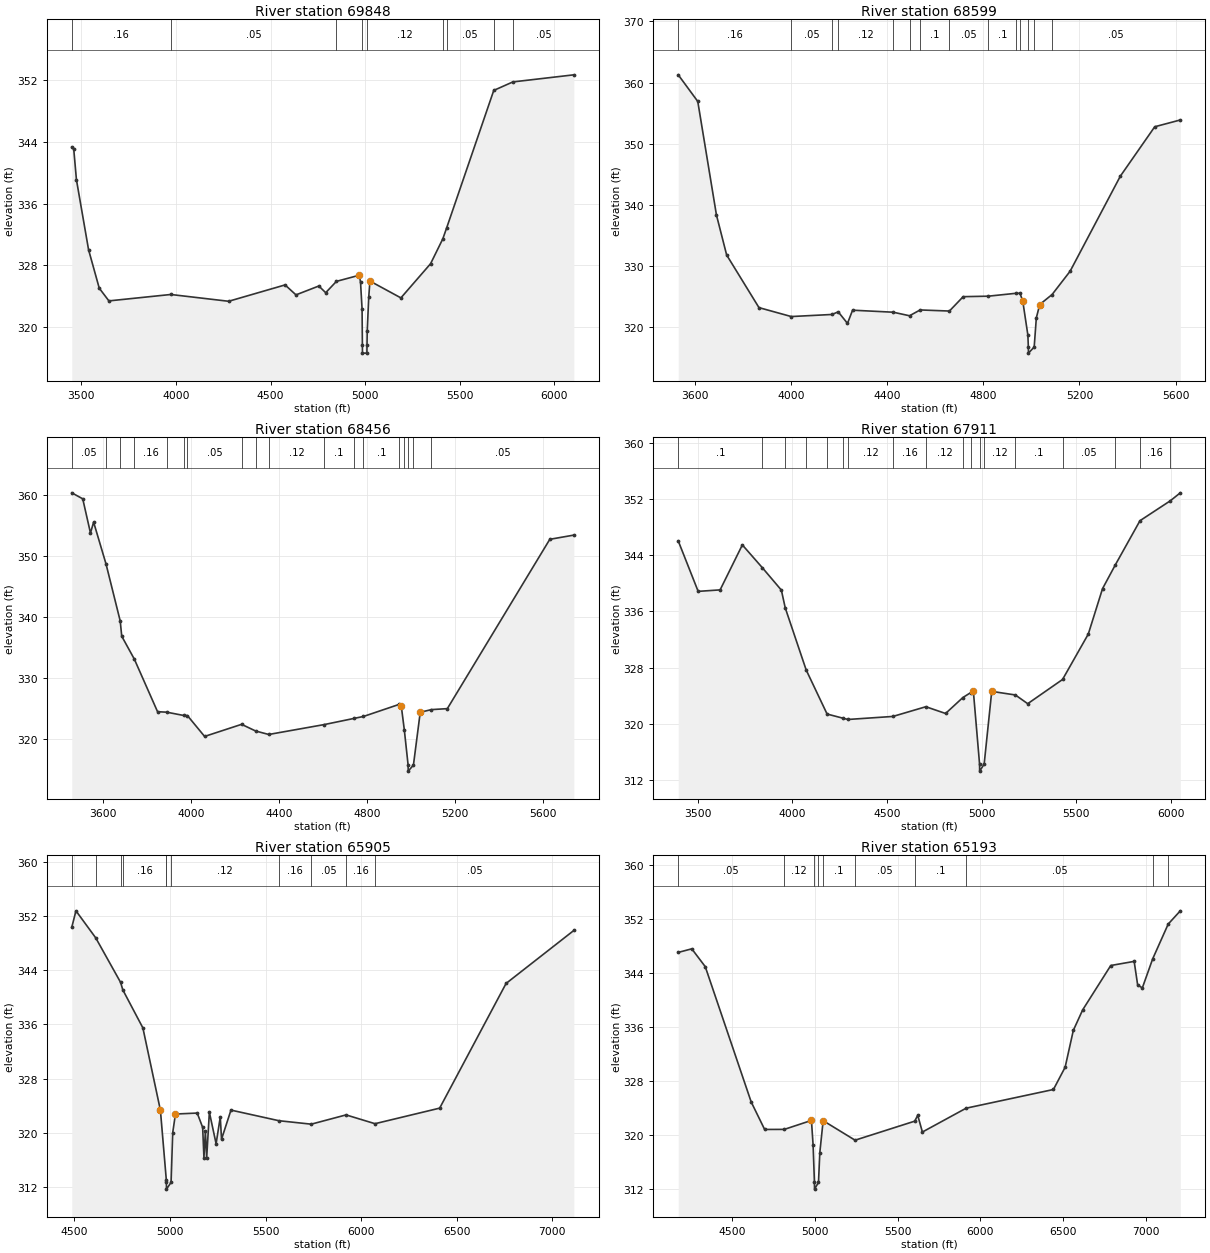
Type RM Length L Ch R = 1 ,69848   ,1249,1249,1249
BEGIN DESCRIPTION:
DUCK CREEK 43 1
END DESCRIPTION:
XS GIS Cut Line= 3
      3532192.81     10406225.51      3530895.94     10404587.49
      3530740.19     10404044.96
#Sta/Elev= 30
  3449.4  343.35  3459.7  343.12  3474.1  339.11  3538.2  330.04  3594.6  325.06
  3645.6  323.41  3972.7  324.24  4278.6  323.36  4576.8  325.48  4634.4  324.19
  4755.3  325.34  4791.5  324.47  4848.2  325.94  4969.4  326.74  4975.7  325.81
  4983.8  322.35  4985.5  317.64    4986  316.64  5009.3  316.64  5009.8  317.64
    5011  319.48    5019   323.9  5025.4  325.98    5189   323.8  5345.9  328.23
  5410.5  331.45  5431.1  332.89  5679.8  350.69  5780.8  351.79  6103.1  352.71
#Mann= 9 ,-1 , 0
  3449.4     .16       0  3972.7     .05       0  4848.2     .12       0
  4985.5     .07       0  5009.8     .12       0  5410.5     .16       0
  5431.1     .05       0  5679.8     .16       0  5780.8     .05       0
Bank Sta=4969.4,5025.4
XS Rating Curve= 0 ,0
Exp/Cntr=0.3,0.1

Type RM Length L Ch R = 1 ,68599   ,143,143,143
BEGIN DESCRIPTION:
DUCK CREEK 43 0
END DESCRIPTION:
XS GIS Cut Line= 3
      3533013.12      10405095.3      3531888.13     10404019.78
      3531405.44      10403799.2
#Sta/Elev= 30
    3532  361.26  3613.2  356.91  3690.9  338.33  3733.3   331.8  3867.6   323.2
  4001.8  321.74  4171.1  322.08    4197  322.51  4235.6  320.62  4256.7  322.78
  4425.5  322.45  4493.4  321.87  4537.6  322.82  4659.2  322.64  4716.5  324.99
  4820.7  325.07  4937.9  325.55  4952.4  325.54    4964  324.32  4985.4  318.72
  4987.4  316.76  4987.9  315.76  5011.7  316.76  5020.6  321.53  5034.8  323.71
  5086.1  325.34    5161  329.15  5369.9   344.7  5512.8  352.77  5619.1  353.88
#Mann= 14 ,-1 , 0
    3532     .16       0  4001.8     .05       0  4171.1     .16       0
    4197     .12       0  4425.5     .05       0  4493.4     .12       0
  4537.6      .1       0  4659.2     .05       0  4820.7      .1       0
  4937.9     .05       0  4952.4     .12       0  4987.4     .07       0
  5011.7     .12       0  5086.1     .05       0
Bank Sta=4964,5034.8
XS Rating Curve= 0 ,0
Exp/Cntr=0.3,0.1

Type RM Length L Ch R = 1 ,68456   ,545,545,545
BEGIN DESCRIPTION:
DUCK CREEK 42 0
END DESCRIPTION:
XS GIS Cut Line= 3
      3533263.12      10404970.3      3531967.11     10403916.64
      3531408.99     10403660.42
#Sta/Elev= 30
  3457.5  360.38  3507.4   359.4  3542.6   353.8  3556.9  355.58  3613.3  348.74
    3678  339.39  3684.8  336.91  3742.2  333.15  3847.8  324.55  3889.6  324.47
  3966.8  323.93  3983.5  323.92  4061.9   320.5  4230.2  322.48    4294  321.39
  4353.6  320.82  4606.1  322.44  4740.4  323.44  4784.7  323.77  4948.2  325.76
  4956.8  325.46  4970.6  321.57  4987.8  315.82  4988.3  314.82  5012.1  315.82
    5043  324.46  5093.9  324.89  5166.3  325.05  5632.5  352.77  5741.9  353.46
#Mann= 18 ,-1 , 0
  3457.5     .05       0  3613.3     .16       0    3678     .05       0
  3742.2     .16       0  3889.6     .05       0  3966.8     .12       0
  3983.5     .05       0  4230.2     .12       0    4294     .05       0
  4353.6     .12       0  4606.1      .1       0  4740.4     .05       0
  4784.7      .1       0  4948.2     .05       0  4970.6      .1       0
  4987.8     .07       0  5012.1      .1       0  5093.9     .05       0
Bank Sta=4956.8,5043
XS Rating Curve= 0 ,0
Exp/Cntr=0.3,0.1

Type RM Length L Ch R = 1 ,67911   ,2006,2006,2006
BEGIN DESCRIPTION:
DUCK CREEK 4 1
END DESCRIPTION:
XS GIS Cut Line= 3
      3533765.71     10404389.57      3531927.19     10403371.35
      3531376.14     10403392.14
#Sta/Elev= 30
  3396.6  346.03  3501.9  338.86  3617.9  339.07  3735.4  345.46  3841.7   342.2
  3941.5  339.04  3962.1  336.51  4072.7  327.69  4183.2  321.43  4268.4  320.83
  4293.8  320.66  4530.9  321.09  4705.1  322.47  4809.3  321.51  4900.9  323.78
  4941.3  324.46  4955.9  324.74  4988.9  314.32  4989.4  313.32  5013.2  314.32
  5053.2  324.65  5178.1  324.14  5243.3   322.9  5427.4  326.34  5563.4  332.79
  5638.6  339.24  5706.6  342.64  5836.6   348.9  5996.4  351.72  6049.7  352.86
#Mann= 18 ,-1 , 0
  3396.6      .1       0  3841.7     .05       0  3962.1     .16       0
  4072.7     .05       0  4183.2      .1       0  4268.4     .05       0
  4293.8     .12       0  4530.9     .16       0  4705.1     .12       0
  4900.9     .05       0  4941.3     .12       0  4988.9     .07       0
  5013.2     .12       0  5178.1      .1       0  5427.4     .05       0
  5706.6      .1       0  5836.6     .16       0  5996.4     .05       0
#XS Ineff= 2 , 0
         3737.27  345.13
Permanent Ineff=
       F       F
Bank Sta=4955.9,5053.2
XS Rating Curve= 0 ,0
Exp/Cntr=0.3,0.1

Type RM Length L Ch R = 1 ,65905   ,712,712,712
BEGIN DESCRIPTION:
DUCK CREEK 4 0
END DESCRIPTION:
XS GIS Cut Line= 3
      3533642.12     10403991.66      3533342.11     10403591.64
      3531942.14     10401991.68
#Sta/Elev= 30
  4486.2  350.35  4508.1  352.79  4611.6  348.79  4741.7  342.21  4753.1  341.11
  4858.1  335.49  4949.8  323.32  4980.9  312.95  4981.1  312.66  4981.6  311.66
  5005.6  312.66  5014.2  320.01  5028.5  322.76  5142.4   322.9  5170.8  320.78
  5177.5  316.32  5185.1  320.25  5191.7  316.24  5205.9  323.03  5241.1  318.37
  5262.9  322.32  5269.5  319.04  5318.9  323.34  5569.8  321.77  5738.7  321.26
  5920.8  322.63  6072.2  321.33  6410.4  323.63  6757.8  342.06  7112.2  349.89
#Mann= 11 ,-1 , 0
  4486.2      .1       0  4611.6     .05       0  4741.7      .1       0
  4753.1     .16       0  4980.9     .12       0  4981.1     .07       0
  5005.6     .12       0  5569.8     .16       0  5738.7     .05       0
  5920.8     .16       0  6072.2     .05       0
Bank Sta=4949.8,5028.5
XS Rating Curve= 0 ,0
Exp/Cntr=0.3,0.1

Type RM Length L Ch R = 1 ,65193   ,634,634,634
BEGIN DESCRIPTION:
DUCK CREEK 39 0
END DESCRIPTION:
XS GIS Cut Line= 4
      3534278.42      10403226.4      3533814.89      10402971.2
       3533070.1     10402856.62      3531826.19     10401623.11
#Sta/Elev= 30
  4174.1  346.98    4256  347.51  4337.4  344.87  4615.1  324.82  4696.3  320.75
  4815.1  320.76  4979.2  322.09  4989.3   318.4  4997.3  312.91  4997.8  311.91
  5021.8  312.91  5029.8  317.32  5049.6  321.97  5050.1  322.05  5242.8  319.16
  5603.5  321.98  5621.5  322.85  5649.8  320.37    5914   323.9  6441.8  326.67
  6512.5  329.97    6562  335.43  6618.6  338.47  6788.3  345.04  6929.7  345.65
  6950.9  342.14  6979.2  341.73  7041.7  346.03  7135.5  351.18  7208.6  353.14
#Mann= 10 ,-1 , 0
  4174.1     .05       0  4815.1     .12       0  4997.3     .07       0
  5021.8     .12       0  5049.6      .1       0  5242.8     .05       0
  5603.5      .1       0    5914     .05       0  7041.7      .1       0
  7135.5     .05       0
Bank Sta=4979.2,5050.1
XS Rating Curve= 0 ,0
Exp/Cntr=0.3,0.1

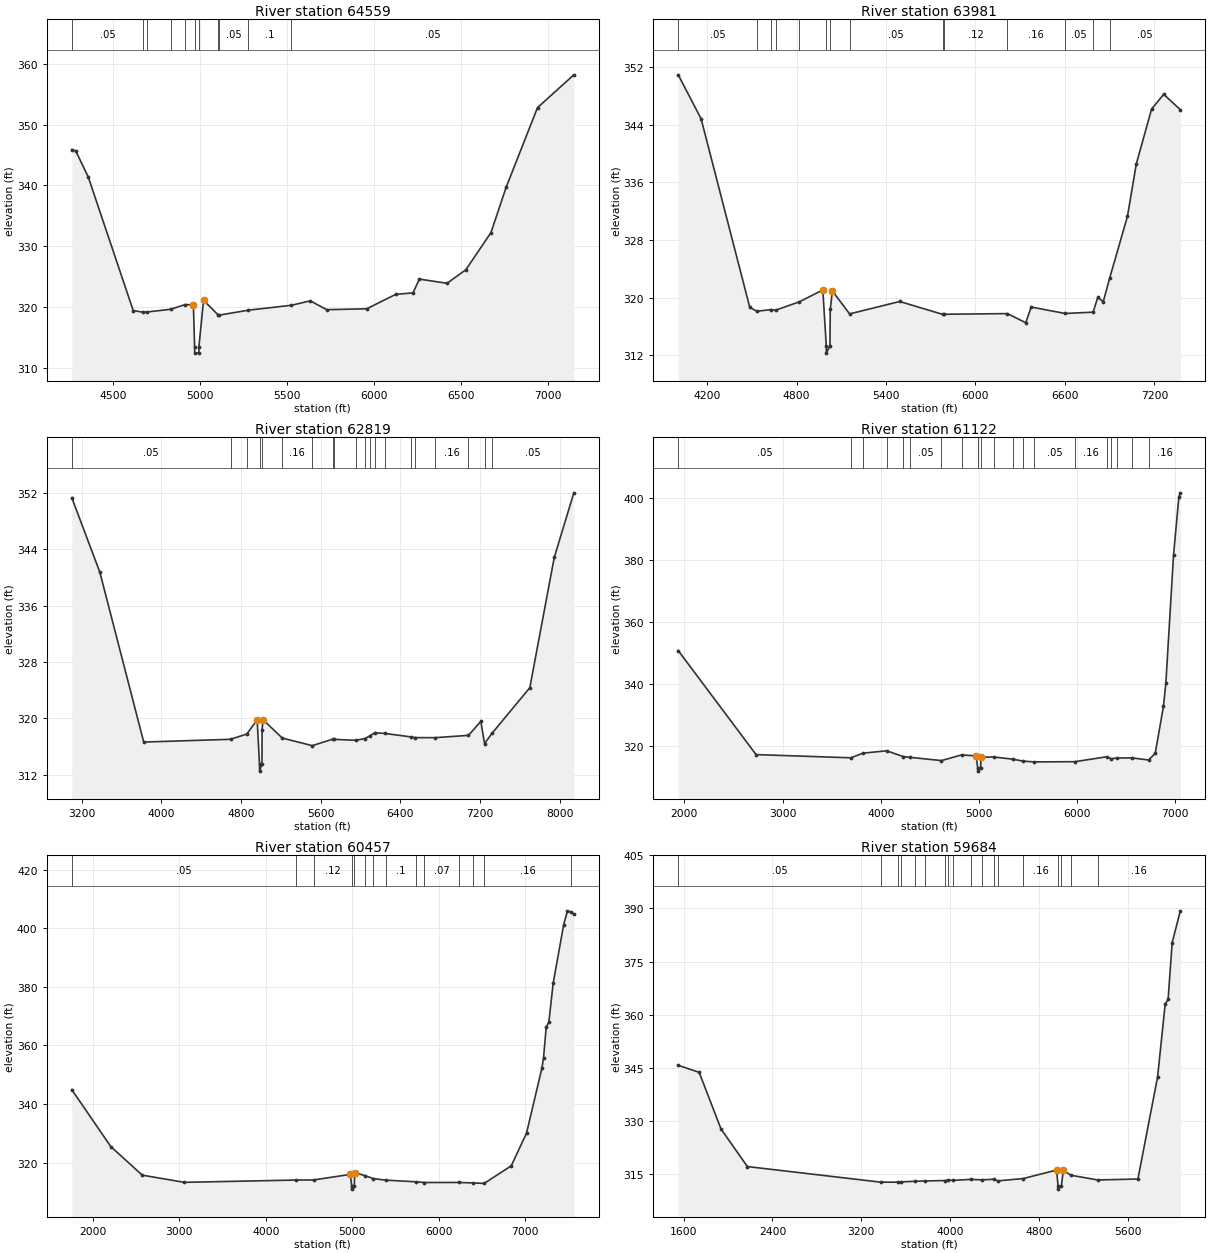
Type RM Length L Ch R = 1 ,64559   ,578,578,578
BEGIN DESCRIPTION:
DUCK CREEK 38 0
END DESCRIPTION:
XS GIS Cut Line= 3
       3534242.1     10402991.63      3533842.11     10402391.64
      3532042.13     10401191.66
#Sta/Elev= 30
  4263.6  345.89  4286.1  345.68  4358.2  341.38  4616.6  319.38  4672.8  319.11
  4695.3  319.14  4831.5  319.59  4914.4  320.36  4962.2  320.33  4969.4  313.37
  4969.9  312.37  4993.4  312.37  4993.9  313.37  5020.7  321.07  5104.7  318.66
  5111.7  318.63  5277.8  319.44  5525.7  320.25  5633.7  320.98  5728.3  319.52
  5958.2  319.67  6124.9  322.05  6224.1  322.29  6260.2  324.56  6419.4  323.87
  6527.6   326.1  6671.8  332.21  6758.9  339.66  6939.2  352.79    7148  358.19
#Mann= 11 ,-1 , 0
  4263.6     .05       0  4672.8     .16       0  4695.3     .05       0
  4831.5     .16       0  4914.4     .12       0  4969.4     .07       0
  4993.9     .12       0  5104.7      .1       0  5111.7     .05       0
  5277.8      .1       0  5525.7     .05       0
Bank Sta=4962.2,5020.7
XS Rating Curve= 0 ,0
Exp/Cntr=0.3,0.1

Type RM Length L Ch R = 1 ,63981   ,1162,1162,1162
BEGIN DESCRIPTION:
DUCK CREEK 37 0
END DESCRIPTION:
XS GIS Cut Line= 4
      3534596.15     10402955.59      3534393.02     10402189.95
      3534023.23     10401731.62      3532288.88     10400762.88
#Sta/Elev= 30
  4006.5  350.89  4159.7   344.8  4486.5  318.63  4534.5  318.11  4627.8  318.33
  4658.9  318.25  4819.4  319.42  4976.3  321.06  4999.5   313.3    5000   312.3
  5024.1   313.3  5026.2  318.38  5040.5  320.91    5156  317.74  5491.9  319.46
  5780.8  317.67  5790.2  317.69  6214.1  317.78  6337.4  316.52  6373.9  318.69
  6601.2   317.8  6789.2  317.98  6820.6  320.04  6857.2  319.41    6900  322.69
  7019.4  331.25  7078.8  338.52  7181.6  346.15  7262.7  348.19  7374.1  346.06
#Mann= 14 ,-1 , 0
  4006.5     .05       0  4534.5      .1       0  4627.8     .05       0
  4658.9     .16       0  4819.4     .12       0  4999.5     .07       0
  5024.1     .12       0    5156     .05       0  5780.8     .16       0
  5790.2     .12       0  6214.1     .16       0  6601.2     .05       0
  6789.2      .1       0    6900     .05       0
Bank Sta=4976.3,5040.5
XS Rating Curve= 0 ,0
Exp/Cntr=0.3,0.1

Type RM Length L Ch R = 1 ,62819   ,1697,1697,1697
BEGIN DESCRIPTION:
DUCK CREEK 36 1
END DESCRIPTION:
XS GIS Cut Line= 4
      3534894.53      10403257.2      3535285.15     10401507.23
      3534821.61     10401142.65      3532264.28     10400403.05
#Sta/Elev= 30
  3099.1   351.3  3381.3  340.72    3822  316.66  4694.1  317.05  4858.1   317.8
  4961.9  319.81  4985.5  313.54    4986  312.54  5010.1  313.54  5011.6  318.35
  5019.7  319.85  5213.5  317.23  5515.1  316.15  5719.1  317.06  5734.1  317.04
  5953.1  316.91  6041.3  317.14  6093.4  317.52    6143  317.98  6244.7  317.88
  6502.7   317.4  6549.9  317.29  6749.6  317.28  7085.1  317.61  7209.4  319.59
    7247  316.44  7321.2  317.89  7701.5  324.36  7947.2  342.82    8144  351.98
#Mann= 20 ,-1 , 0
  3099.1     .05       0  4694.1     .16       0  4858.1     .12       0
  4985.5     .07       0  5010.1     .12       0  5213.5     .16       0
  5515.1     .05       0  5719.1     .12       0  5734.1     .16       0
  5953.1     .05       0  6041.3     .16       0  6093.4     .05       0
    6143     .16       0  6244.7     .05       0  6502.7     .16       0
  6549.9     .05       0  6749.6     .16       0  7085.1     .12       0
    7247     .16       0  7321.2     .05       0
Bank Sta=4961.9,5019.7
XS Rating Curve= 0 ,0
Exp/Cntr=0.3,0.1

Type RM Length L Ch R = 1 ,61122   ,665,665,665
BEGIN DESCRIPTION:
DUCK CREEK 36 0
END DESCRIPTION:
XS GIS Cut Line= 4
      3535009.33     10403351.45      3535592.67     10400656.97
      3535335.73     10399816.69      3534792.11     10398441.64
#Sta/Elev= 30
  1936.9  350.71  2729.7  317.17  3695.6  316.14    3821  317.65  4059.7  318.39
    4231  316.52  4302.5  316.27  4617.8  315.24  4822.3  317.07  4971.3  316.76
  4987.6  312.84  4988.1  311.84  5017.6  312.84  5019.5  316.32  5149.6   316.4
  5341.8  315.71  5445.7  315.09  5560.6  314.81  5977.8  314.89  6299.5  316.46
  6347.7  315.83  6406.8  316.08  6560.4   316.1  6728.5  315.43  6795.6  317.57
  6879.4  332.73  6903.7  340.15  6982.2  381.55  7036.2  400.23  7051.1  401.59
#Mann= 20 ,-1 , 0
  1936.9     .05       0  3695.6     .16       0    3821     .05       0
  4059.7     .05       0    4231     .12       0  4302.5     .05       0
  4617.8     .05       0  4822.3     .16       0  4987.6     .07       0
  5017.6     .12       0  5149.6      .1       0  5341.8     .05       0
  5445.7     .07       0  5560.6     .05       0  5977.8     .16       0
  6299.5     .05       0  6347.7     .16       0  6406.8     .05       0
  6560.4     .12       0  6728.5     .16       0
Bank Sta=4971.3,5019.5
XS Rating Curve= 0 ,0
Exp/Cntr=0.3,0.1

Type RM Length L Ch R = 1 ,60457   ,773,773,773
BEGIN DESCRIPTION:
DUCK CREEK 35 0
END DESCRIPTION:
XS GIS Cut Line= 2
      3535657.34      10403417.6       3536518.3     10397675.59
#Sta/Elev= 30
  1756.3  344.89  2207.2  325.47  2571.3   315.7  3056.6  313.25  4348.2  314.03
  4552.1  314.06  4977.9  315.96  4993.2  311.93  4993.7  310.93  5023.2  311.93
  5028.4  316.54  5144.2  315.58  5242.8  314.53  5384.8     314  5736.2  313.43
  5834.9  313.19  6229.6  313.21  6401.1  313.05  6525.7  312.88  6838.4  318.88
  7015.2  330.03  7192.4  352.13  7212.4  355.82  7242.9  366.26  7273.2  367.88
  7323.8   381.3  7445.1  401.19  7488.8  405.91  7531.5  405.51  7562.5  404.68
#Mann= 14 ,-1 , 0
  1756.3     .05       0  4348.2     .07       0  4552.1     .12       0
  4993.2     .07       0  5023.2     .12       0  5144.2     .05       0
  5242.8     .16       0  5384.8      .1       0  5736.2     .16       0
  5834.9     .07       0  6229.6     .12       0  6401.1     .07       0
  6525.7     .16       0  7531.5     .05       0
Bank Sta=4977.9,5028.4
XS Rating Curve= 0 ,0
Exp/Cntr=0.3,0.1

Type RM Length L Ch R = 1 ,59684   ,936,936,936
BEGIN DESCRIPTION:
DUCK CREEK 33 5
END DESCRIPTION:
XS GIS Cut Line= 4
      3535929.47     10403419.16      3536779.81     10400168.46
      3536904.07     10399609.23      3537090.93     10399049.33
#Sta/Elev= 30
  1551.2  345.66  1739.6  343.69  1936.6  327.67    2174  317.04  3375.7  312.63
    3534  312.62    3555   312.7  3684.2  312.88  3776.6  312.98  3951.3  313.08
  3985.5  313.22  4024.5  313.15  4186.4   313.4  4286.8  313.29  4392.8  313.44
  4429.8  312.99  4658.7  313.65  4959.2  316.05  4972.9  311.66  4973.4  310.66
  5002.9  311.66  5020.7  315.96  5088.9  314.58  5331.8  313.25  5692.4  313.52
  5869.6  342.33  5938.1  362.99  5964.4  364.31  6001.3  380.38  6074.4  389.34
#Mann= 18 ,-1 , 0
  1551.2     .05       0  3375.7      .1       0    3534     .05       0
    3555      .1       0  3684.2     .05       0  3776.6      .1       0
  3951.3     .05       0  3985.5     .07       0  4024.5      .1       0
  4186.4     .07       0  4286.8     .05       0  4392.8     .07       0
  4429.8     .05       0  4658.7     .16       0  4972.9     .04       0
  5002.9     .16       0  5088.9     .07       0  5331.8     .16       0
Bank Sta=4959.2,5020.7
XS Rating Curve= 0 ,0
Exp/Cntr=0.3,0.1

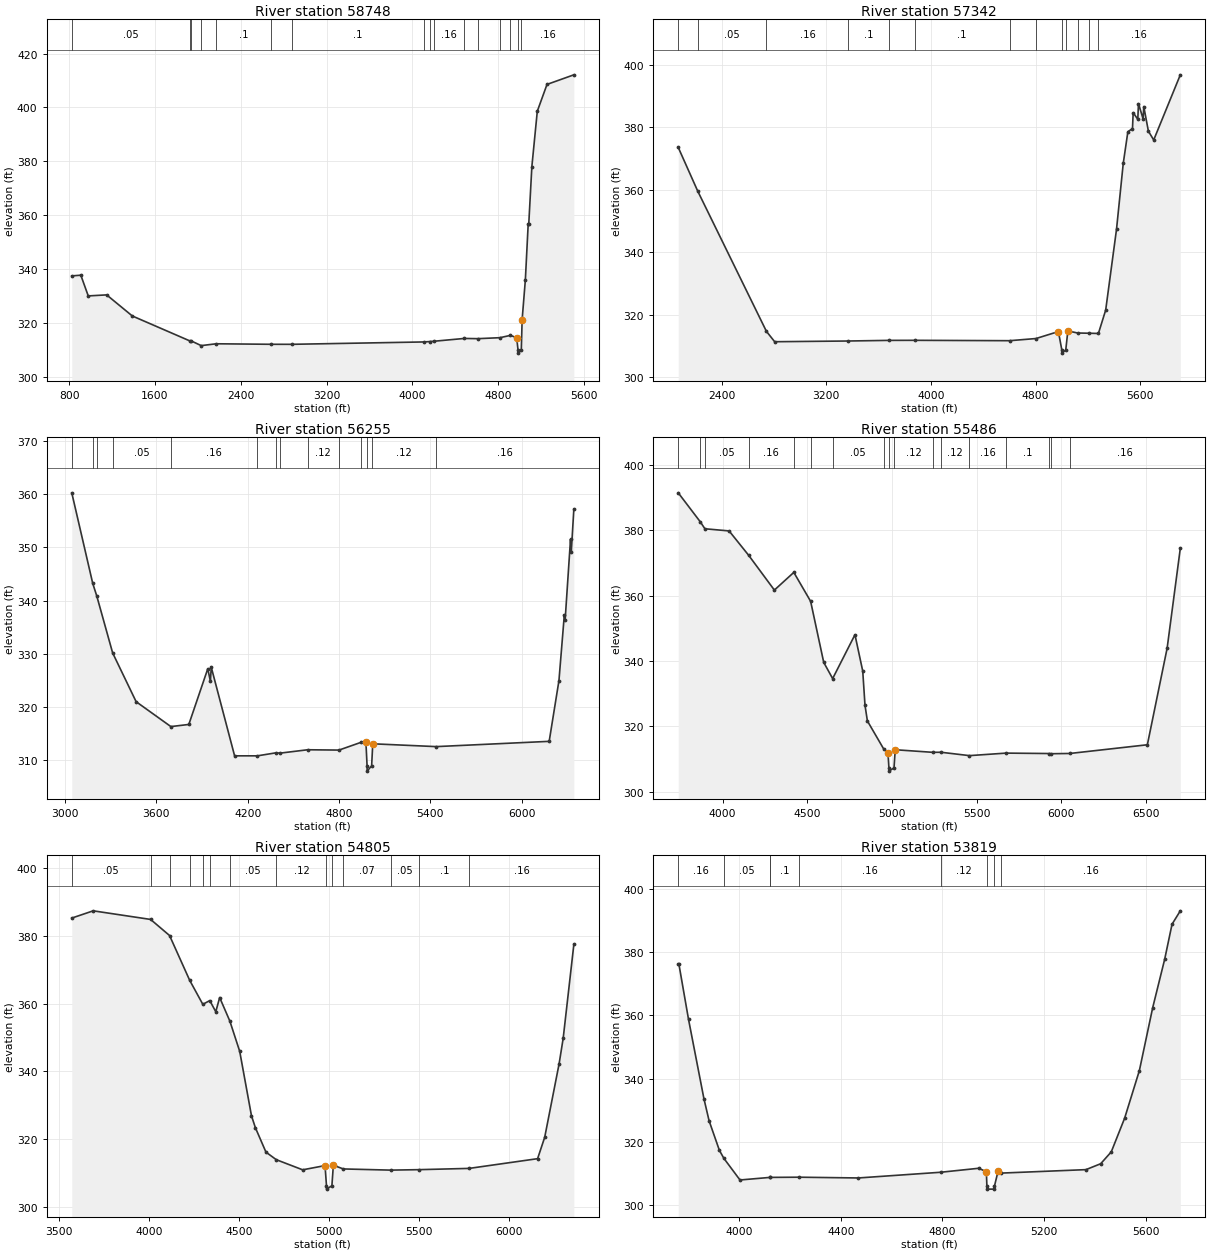
Type RM Length L Ch R = 1 ,58748   ,1406,1406,1406
BEGIN DESCRIPTION:
DUCK CREEK 33 2
END DESCRIPTION:
XS GIS Cut Line= 4
       3536203.8     10403670.82      3537578.78     10399962.52
      3537642.11     10399469.47      3537642.11     10399241.67
#Sta/Elev= 30
   824.4  337.48   908.8  337.74   977.9  330.05  1149.6  330.43  1388.8   322.6
  1927.6   313.3  1937.8  313.34  2030.8   311.6  2170.9  312.28  2682.9  312.09
  2874.2  312.08  4104.5  312.96  4165.2  313.11  4197.7  313.21  4483.3  314.26
  4610.4  314.18  4815.1  314.54  4913.6   315.4  4971.8  314.52  4984.4  309.81
  4984.9  308.81  5014.4  309.81  5022.3  321.23  5052.5  336.08    5079  356.89
    5084  356.67    5113  378.07  5163.6   398.6  5254.1  408.56  5504.3  412.12
#Mann= 16 ,-1 , 0
   824.4     .05       0  1927.6      .1       0  1937.8     .16       0
  2030.8     .05       0  2170.9      .1       0  2682.9     .05       0
  2874.2      .1       0  4104.5     .05       0  4165.2     .12       0
  4197.7     .16       0  4483.3     .12       0  4610.4     .16       0
  4815.1     .12       0  4913.6     .16       0  4984.4     .07       0
  5014.4     .16       0
Bank Sta=4971.8,5022.3
XS Rating Curve= 0 ,0
Exp/Cntr=0.3,0.1

Type RM Length L Ch R = 1 ,57342   ,1087,1087,1087
BEGIN DESCRIPTION:
DUCK CREEK 33 0
END DESCRIPTION:
XS GIS Cut Line= 2
      3537212.89     10403764.85      3538178.19      10400049.5
#Sta/Elev= 30
  2068.2   373.6    2217  359.63  2742.4  314.73  2805.5  311.41    3369  311.64
    3677  311.84  3875.4  311.86  4602.5  311.74  4803.3  312.43  4974.8  314.66
  5001.1  308.76  5001.6  307.76  5031.1  308.76  5047.1  314.88  5121.6   314.2
  5207.1  314.13  5280.7  314.05  5336.4  321.55  5419.1  347.38  5470.7  368.51
  5505.9   378.6  5541.3  379.65  5546.5  384.72  5581.8   382.6    5587   387.6
  5622.4  382.74  5627.6  386.66  5662.9   378.8  5703.5  375.98  5906.9  396.83
#Mann= 13 ,-1 , 0
  2068.2      .1       0    2217     .05       0  2742.4     .16       0
    3369      .1       0    3677     .05       0  3875.4      .1       0
  4602.5     .05       0  4803.3     .12       0  5001.1     .07       0
  5031.1     .12       0  5121.6     .16       0  5207.1     .12       0
  5280.7     .16       0
Bank Sta=4974.8,5047.1
XS Rating Curve= 0 ,0
Exp/Cntr=0.3,0.1

Type RM Length L Ch R = 1 ,56255   ,769,769,769
BEGIN DESCRIPTION:
DUCK CREEK 33 1
END DESCRIPTION:
XS GIS Cut Line= 3
      3537495.44     10403608.38      3538426.01     10401650.02
      3538141.78     10400554.71
#Sta/Elev= 30
  3044.1  360.23  3181.9  343.23    3208  340.91  3312.8  330.18  3467.1  321.03
  3695.5  316.36  3813.4  316.76  3938.1  327.22  3955.3  324.84  3960.8  327.51
  4114.3  310.87  4264.4  310.87  4387.2  311.44  4413.7  311.38  4594.8  312.01
  4800.4  311.95  4942.8  313.38  4977.2  313.54  4984.9     309  4985.4     308
  5014.9     309  5022.3  313.13    5439   312.6  6181.8  313.59    6246  324.99
  6281.4  337.34  6286.6  336.33    6322  351.51  6327.1  349.19  6343.9  357.15
#Mann= 14 ,-1 , 0
  3044.1     .16       0  3181.9     .05       0    3208     .16       0
  3312.8     .05       0  3695.5     .16       0  4264.4      .1       0
  4387.2     .12       0  4413.7     .07       0  4594.8     .12       0
  4800.4     .05       0  4942.8     .12       0  4984.9     .07       0
  5014.9     .12       0    5439     .16       0
Bank Sta=4977.2,5022.3
XS Rating Curve= 0 ,0
Exp/Cntr=0.3,0.1

Type RM Length L Ch R = 1 ,55486   ,681,681,681
BEGIN DESCRIPTION:
DUCK CREEK 32 2
END DESCRIPTION:
XS GIS Cut Line= 4
      3539492.16      10403090.9      3539078.69     10402077.69
      3538578.97     10401667.29      3538158.82     10400517.95
#Sta/Elev= 30
  3737.6  391.43  3867.7  382.57    3895  380.44    4038  379.78  4153.7  372.31
  4305.3  361.69  4420.1   367.1  4519.4  358.25  4596.7  339.58  4649.4  334.63
  4781.1  348.04  4827.1  336.92  4840.4  326.46  4854.6  321.67  4950.3  313.15
  4975.9  311.98  4981.7  307.33  4982.2  306.33  5011.7  307.33  5018.9  312.87
  5240.6  312.08  5289.3   312.1  5457.1  311.07  5673.4  311.84  5929.1  311.71
  5937.4  311.65  6050.4  311.73  6507.7  314.39  6624.5  343.92  6702.3  374.45
#Mann= 17 ,-1 , 0
  3737.6     .05       0  3867.7     .16       0    3895     .05       0
  4153.7     .16       0  4420.1     .05       0  4519.4     .16       0
  4649.4     .05       0  4950.3     .12       0  4981.7     .07       0
  5011.7     .12       0  5240.6     .16       0  5289.3     .12       0
  5457.1     .16       0  5673.4      .1       0  5929.1     .16       0
  5937.4      .1       0  6050.4     .16       0
#XS Ineff= 2 , 0
         4777.94  347.56
Permanent Ineff=
       F       F
Bank Sta=4975.9,5018.9
XS Rating Curve= 0 ,0
Exp/Cntr=0.3,0.1

Type RM Length L Ch R = 1 ,54805   ,986,986,986
BEGIN DESCRIPTION:
DUCK CREEK 32 1
END DESCRIPTION:
XS GIS Cut Line= 3
      3540249.14     10402236.76      3538537.31     10401247.16
      3538190.57     10400515.55
#Sta/Elev= 30
  3571.8  385.26  3690.8   387.4  4009.4  384.86  4114.6  380.11  4226.2   366.9
  4299.2   359.8  4337.8   360.9  4371.2  357.61  4392.7   361.8  4449.4  354.83
    4504  345.91  4569.3   326.9  4590.8   323.4  4649.7  316.16  4707.1  313.93
  4853.5  310.94  4977.6  312.19  4985.7  306.24  4986.2  305.24  5015.7  306.24
  5023.8  312.29  5079.2   311.2  5342.1  310.85  5501.4  310.99  5777.5  311.36
  6157.5  314.23    6197  320.56  6276.7  342.18  6299.5  349.75  6358.7  377.46
#Mann= 14 ,-1 , 0
  3571.8     .05       0  4009.4      .1       0  4114.6     .05       0
  4226.2      .1       0  4299.2     .05       0  4337.8      .1       0
  4449.4     .05       0  4707.1     .12       0  4985.7     .07       0
  5015.7     .12       0  5079.2     .07       0  5342.1     .05       0
  5501.4      .1       0  5777.5     .16       0
Bank Sta=4977.6,5023.8
XS Rating Curve= 0 ,0
Exp/Cntr=0.3,0.1

Type RM Length L Ch R = 1 ,53819   ,941,941,941
BEGIN DESCRIPTION:
DUCK CREEK 32 0
END DESCRIPTION:
XS GIS Cut Line= 3
      3540092.07     10400541.65      3538892.11     10400741.64
       3538192.1     10400441.64
#Sta/Elev= 30
    3759  376.28  3761.5  376.28  3799.5  358.77  3860.3  333.64  3880.6  326.69
  3921.2  317.34  3938.9  314.81  4002.3  307.98  4120.8   308.8  4121.6   308.8
  4234.3  308.86  4468.6  308.62  4792.5  310.42  4942.6  311.68    4973  310.61
    4975  306.09  4975.5  305.09  5004.5  305.09    5005  306.09    5019  310.72
  5031.9  310.16  5365.4  311.25  5423.4  313.12  5465.1  316.87  5517.7  327.51
  5575.7  342.53  5628.3  362.45  5675.4  377.72  5704.5  388.83  5737.1  393.07
#Mann= 9 ,-1 , 0
    3759     .16       0  3938.9     .05       0  4120.8     .12       0
  4121.6      .1       0  4234.3     .16       0  4792.5     .12       0
    4975     .07       0    5005     .12       0  5031.9     .16       0
Bank Sta=4973,5019
XS Rating Curve= 0 ,0
Exp/Cntr=0.3,0.1

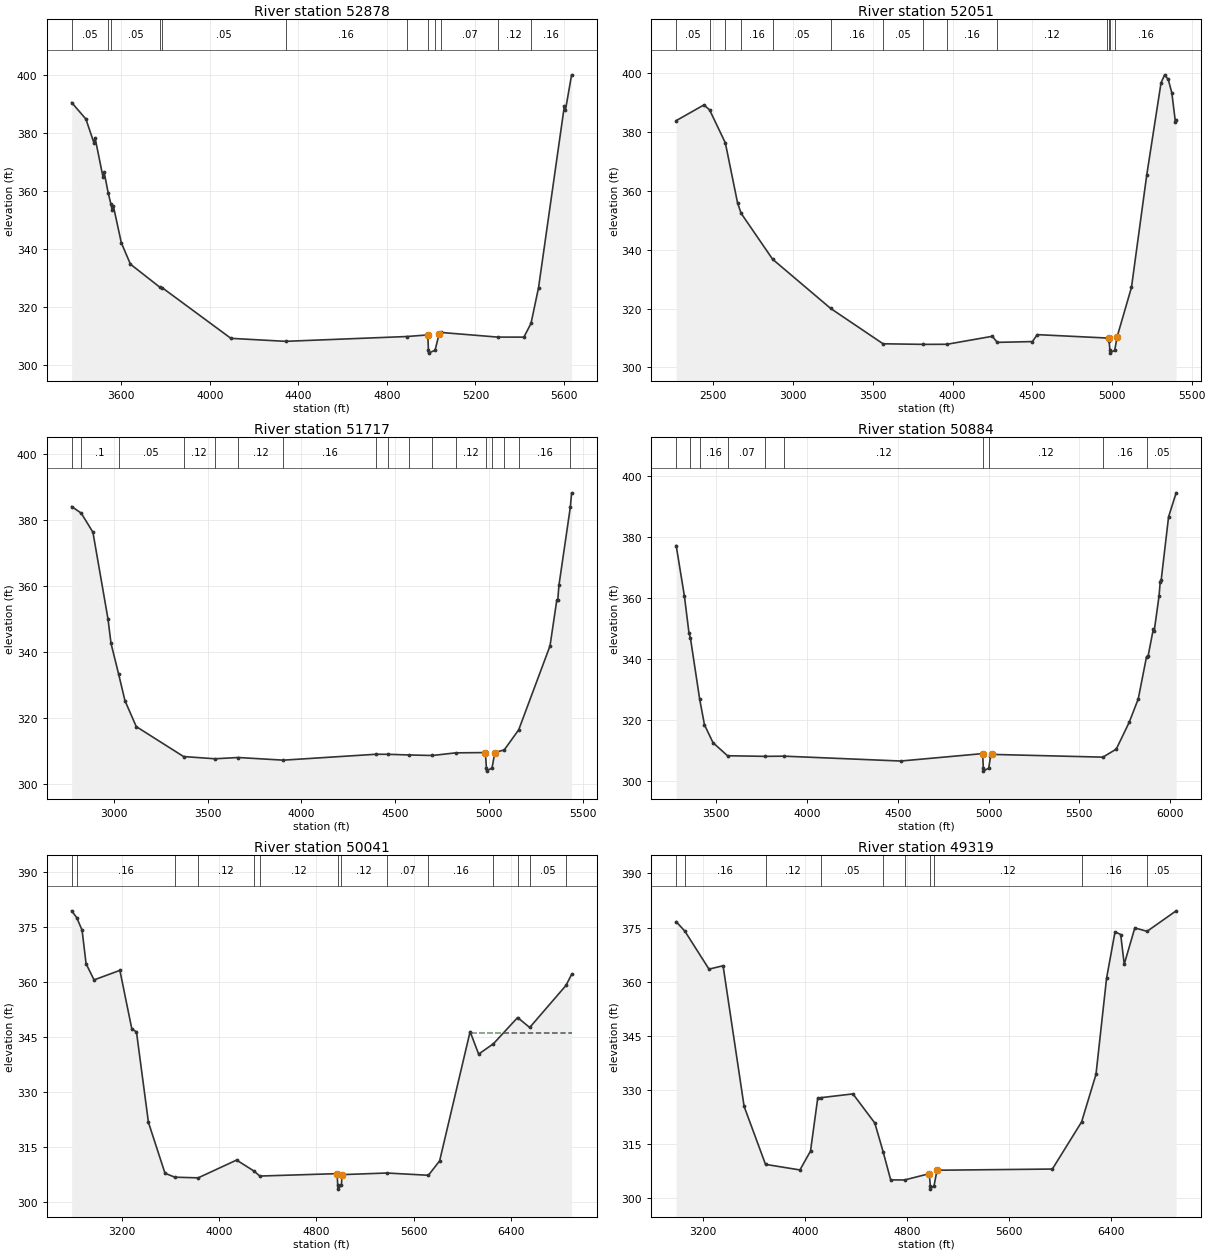
Type RM Length L Ch R = 1 ,52878   ,827,827,827
BEGIN DESCRIPTION:
DUCK CREEK 30 0
END DESCRIPTION:
XS GIS Cut Line= 3
      3540492.09     10400341.64      3538892.11     10399941.64
      3538292.11     10400041.64
#Sta/Elev= 30
  3376.6  390.45    3441  384.74  3477.1  376.57  3482.2  378.33  3518.3  364.72
  3523.5  366.36  3542.1  359.13  3553.7  355.56  3559.5  353.39  3564.7  354.89
  3600.8  342.17    3642   334.8  3775.8  326.81  3785.9  326.67  4095.6  309.27
  4342.3  308.24  4890.8   309.9  4984.6  310.45  4987.6  305.18  4988.1  304.18
  5017.6  305.18    5036  310.85  5043.9   311.3  5300.5   309.7  5418.7  309.69
  5450.7  314.43  5484.6  326.66  5601.2  389.17  5606.2  387.86  5634.1  399.98
#Mann= 12 ,-1 , 0
  3376.6     .05       0  3542.1      .1       0  3553.7     .05       0
  3775.8     .16       0  3785.9     .05       0  4342.3     .16       0
  4890.8     .12       0  4987.6     .07       0  5017.6     .12       0
  5043.9     .07       0  5300.5     .12       0  5450.7     .16       0
Bank Sta=4984.6,5036
XS Rating Curve= 0 ,0
Exp/Cntr=0.3,0.1

Type RM Length L Ch R = 1 ,52051   ,334,334,334
BEGIN DESCRIPTION:
DUCK CREEK 29 0
END DESCRIPTION:
XS GIS Cut Line= 3
      3541155.13     10399948.63      3538625.47     10399687.35
      3538092.71     10399948.62
#Sta/Elev= 30
  2266.4  383.93  2440.3  389.27  2475.8   387.6  2574.8  376.37  2651.5  355.94
  2673.7  352.42  2871.6  336.78  3235.7  320.05  3564.2  308.04  3817.8  307.84
  3964.8  307.87  4249.9  310.59  4280.5  308.52  4501.3  308.79  4531.4  311.15
  4968.1     310  4980.3  310.05  4982.1  309.02  4987.6  305.86  4988.1  304.86
  5017.6  305.86  5032.7  310.43  5122.7  327.24  5218.3  365.37  5308.2   396.8
  5330.7  399.51  5353.2  397.95  5375.7  393.43  5398.2  383.49  5402.9  384.24
#Mann= 14 ,-1 , 0
  2266.4     .05       0  2475.8     .16       0  2574.8     .05       0
  2673.7     .16       0  2871.6     .05       0  3235.7     .16       0
  3564.2     .05       0  3817.8     .12       0  3964.8     .16       0
  4280.5     .12       0  4968.1     .07       0  4982.1     .16       0
  4987.6     .07       0  5017.6     .16       0
Bank Sta=4980.3,5032.7
XS Rating Curve= 0 ,0
Exp/Cntr=0.3,0.1

Type RM Length L Ch R = 1 ,51717   ,833,833,833
BEGIN DESCRIPTION:
DUCK CREEK 3 0
END DESCRIPTION:
XS GIS Cut Line= 3
      3540564.92     10399663.91      3538453.78      10399490.3
      3537926.57      10399358.5
#Sta/Elev= 30
  2776.7  384.02  2827.6  382.01  2889.9  376.23  2970.2  349.97  2986.3  342.57
  3026.1  333.46  3060.5  325.26  3120.7  317.42  3372.6  308.36  3539.1  307.69
  3663.8  308.07  3903.7  307.27  4398.2  309.06  4459.7  309.04  4574.8  308.84
  4697.4  308.68  4820.9  309.48  4979.2  309.57  4984.8  304.95  4985.3  303.95
  5014.8  304.95  5029.6  309.58  5079.7  310.37  5156.8  316.47  5323.4  341.86
  5359.5  355.71  5364.6  355.64  5370.8  360.15  5431.4  383.77  5438.4  388.16
#Mann= 17 ,-1 , 0
  2776.7     .05       0  2827.6      .1       0  3026.1     .05       0
  3372.6     .12       0  3539.1     .05       0  3663.8     .12       0
  3903.7     .16       0  4398.2     .12       0  4459.7      .1       0
  4574.8     .12       0  4697.4      .1       0  4820.9     .12       0
  4984.8     .07       0  5014.8     .12       0  5079.7     .07       0
  5156.8     .16       0  5431.4     .05       0
Bank Sta=4979.2,5029.6
XS Rating Curve= 0 ,0
Exp/Cntr=0.3,0.1

Type RM Length L Ch R = 1 ,50884   ,843,843,843
BEGIN DESCRIPTION:
DUCK CREEK 28 1
END DESCRIPTION:
XS GIS Cut Line= 3
      3540442.12     10399491.65      3538842.11     10398891.64
      3537842.15     10398591.65
#Sta/Elev= 30
  3280.1  377.05  3325.5  360.45  3350.4   348.5  3358.9  346.63  3409.3  326.77
  3435.9  318.33    3483  312.47  3562.8   308.2  3770.8     308  3874.8  308.06
  4516.3  306.47  4967.6   308.9  4971.2  304.16  4971.7  303.16  5001.2  304.16
  5010.7  307.96  5020.2  308.64  5629.8  307.74  5703.2  310.37  5774.5  319.17
  5824.1  326.79  5869.9  340.64  5878.9  340.98  5906.8  349.56    5912  349.02
    5939  360.62  5945.1  365.11  5950.3  365.62  5991.2  386.45  6032.9  394.33
#Mann= 10 ,-1 , 0
  3280.1      .1       0  3358.9     .05       0  3409.3     .16       0
  3562.8     .07       0  3770.8     .05       0  3874.8     .12       0
  4971.2     .07       0  5001.2     .12       0  5629.8     .16       0
  5869.9     .05       0
Bank Sta=4967.6,5020.2
XS Rating Curve= 0 ,0
Exp/Cntr=0.3,0.1

Type RM Length L Ch R = 1 ,50041   ,722,722,722
BEGIN DESCRIPTION:
DUCK CREEK 28 0
END DESCRIPTION:
XS GIS Cut Line= 4
      3541030.14      10398851.4      3539210.73     10398295.85
      3538797.99     10398234.88      3537009.31     10398372.25
#Sta/Elev= 30
  2786.8  379.45  2828.9  377.57  2872.6  374.14  2905.4     365    2971  360.59
  3183.5  363.19  3281.9  347.19    3320  346.39  3418.4  321.69  3554.8  307.78
  3635.6  306.71  3827.5  306.53    4144  311.39  4288.6  308.35  4334.5  307.02
  4970.8  307.68    4976  304.45  4976.5  303.45    5006  304.45  5011.2  307.41
  5380.6  307.85  5722.1  307.23  5814.3  311.17  6065.1  346.46  6135.3  340.32
  6257.2  343.16    6456  350.31  6555.4  347.59  6853.7  359.07  6900.3   362.1
#Mann= 14 ,-1 , 0
  2786.8     .05       0  2828.9     .16       0  3635.6     .07       0
  3827.5     .12       0  4288.6     .07       0  4334.5     .12       0
    4976     .07       0    5006     .12       0  5380.6     .07       0
  5722.1     .16       0  6257.2     .05       0    6456     .16       0
  6555.4     .05       0  6853.7      .1       0
#XS Ineff= 2 , 0
                         6069.63          346.21
Permanent Ineff=
       F       F
Bank Sta=4970.8,5011.2
XS Rating Curve= 0 ,0
Exp/Cntr=0.3,0.1

Type RM Length L Ch R = 1 ,49319   ,592,592,592
BEGIN DESCRIPTION:
DUCK CREEK 27 1
END DESCRIPTION:
XS GIS Cut Line= 3
      3540960.88     10398725.83      3540570.51     10398580.24
      3537447.02     10396979.32
#Sta/Elev= 30
  2988.1  376.62  3056.9  373.96  3245.8  363.46  3356.4   364.4  3521.6  325.39
  3689.6  309.32  3959.9  307.77  4043.1  313.01  4099.6  327.65    4124  327.81
  4376.1  328.86  4548.1  320.78  4614.6  312.67  4672.7  305.01  4781.8  304.99
  4976.1  306.74  4983.6  303.45  4984.1  302.45  5013.6  303.45  5036.5  307.69
  5942.5  308.02  6171.9  321.08    6285  334.26  6368.1  360.91  6434.7  373.82
  6479.1  373.06  6506.9  364.83  6590.1   374.9  6686.1  373.94  6914.6  379.63
#Mann= 10 ,-1 , 0
  2988.1     .05       0  3056.9     .16       0  3689.6     .12       0
    4124     .05       0  4614.6     .07       0  4781.8     .12       0
  4983.6     .07       0  5013.6     .12       0  6171.9     .16       0
  6686.1     .05       0
Bank Sta=4976.1,5036.5
XS Rating Curve= 0 ,0
Exp/Cntr=0.3,0.1