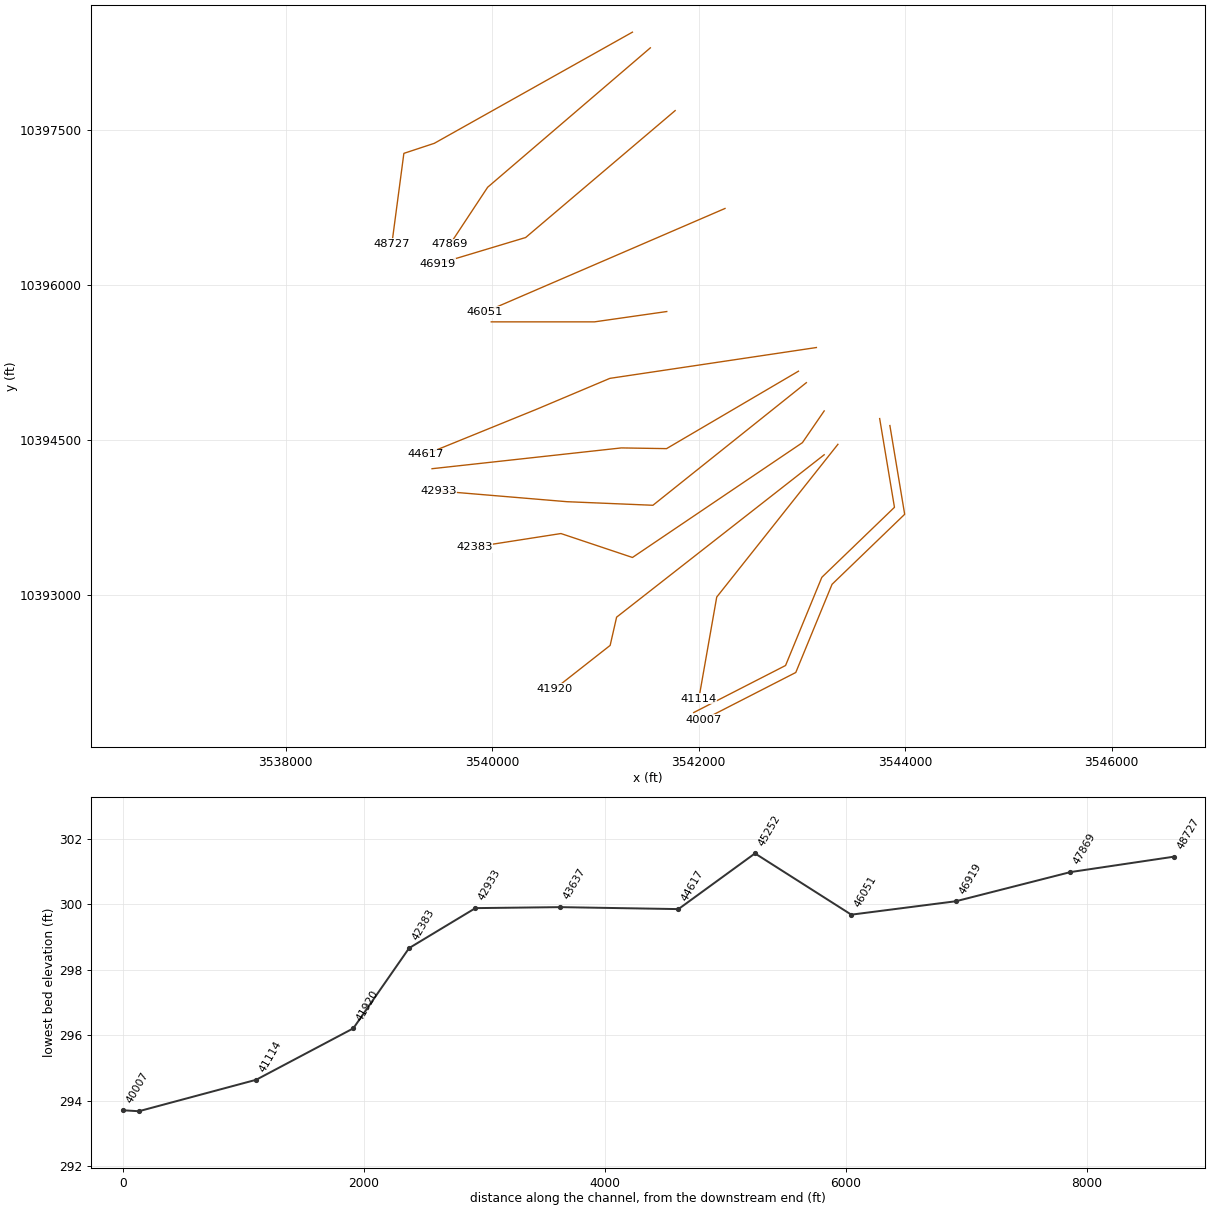
HEC-RAS study DUCK CREEK.prj: DUCK CREEK Base Level Engineering

--- DUCK CREEK.g01 (geometry) --- (continued)

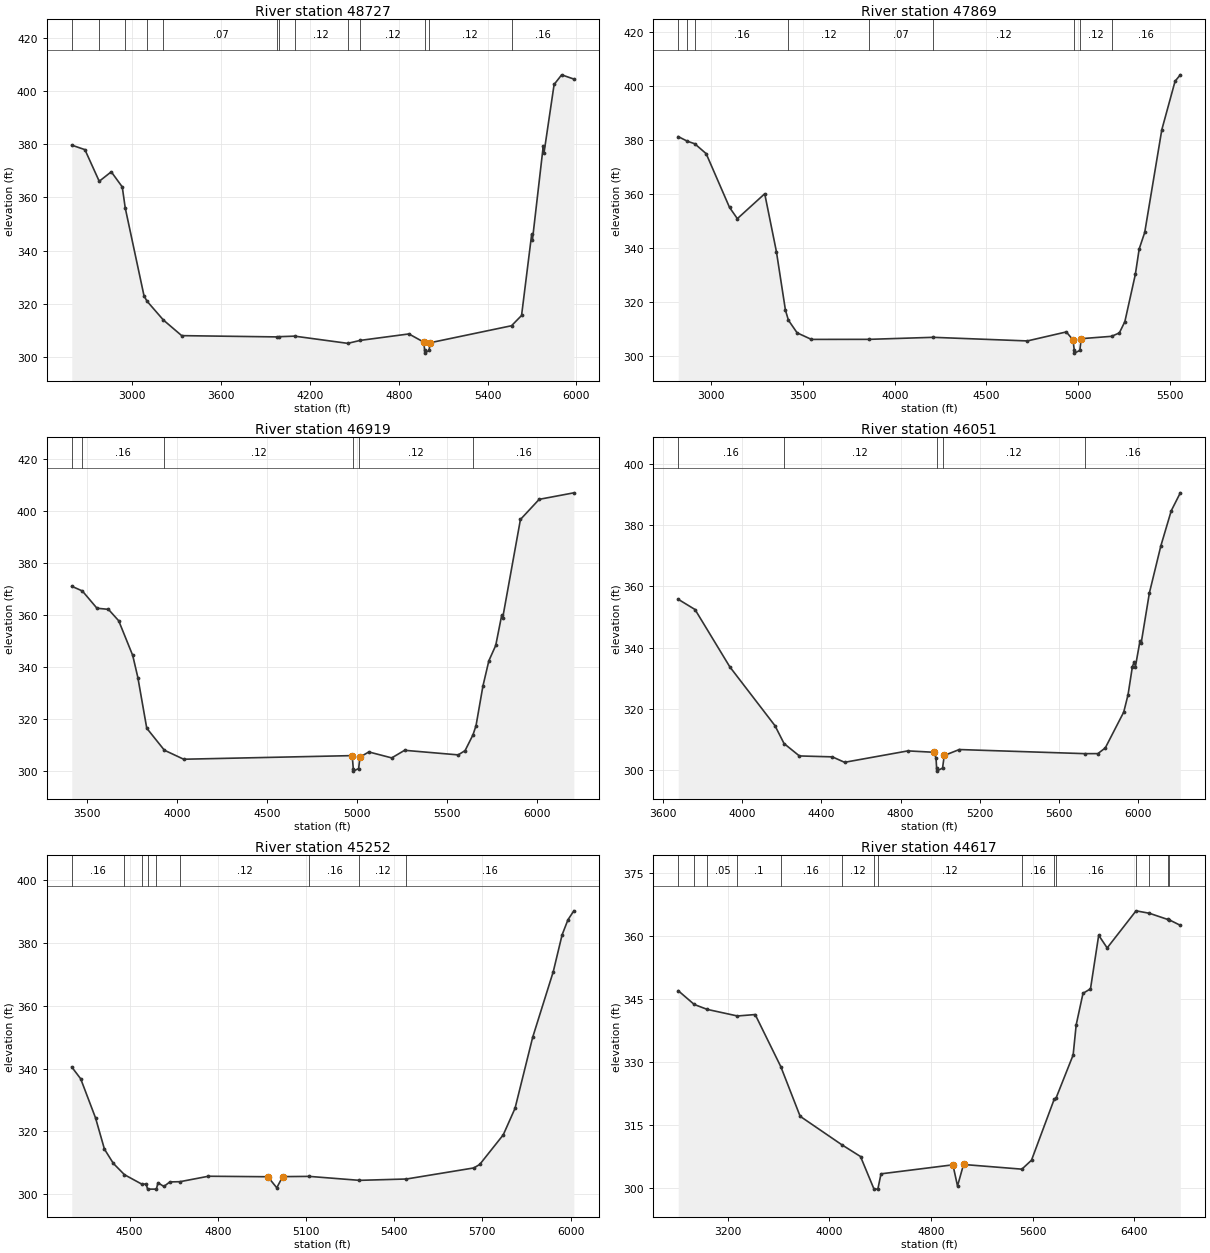
Type RM Length L Ch R = 1 ,48727   ,858,858,858
BEGIN DESCRIPTION:
DUCK CREEK 27 0
END DESCRIPTION:
XS GIS Cut Line= 4
      3541359.54     10398447.31      3539441.11      10397370.9
      3539146.06     10397273.51      3539030.18     10396400.05
#Sta/Elev= 30
  2590.7  379.58  2679.5  377.88  2776.2     366  2857.5  369.56  2931.8  363.88
  2951.9  355.98  3078.8  322.97  3098.9  320.97  3209.7  313.88  3333.3  308.02
  3979.3  307.54  3987.8  307.62  4095.8  307.83  4455.2  305.12    4539  306.23
  4868.1  308.66  4968.6  305.58  4974.5  302.45    4975  301.45  5004.5  302.45
  5010.6  305.34  5561.3  311.74  5629.1  315.59  5697.3  346.02  5702.4  343.88
  5775.7  379.23  5780.8  376.68    5849  402.37    5900  405.99  5982.3   404.4
#Mann= 13 ,-1 , 0
  2590.7     .05       0  2776.2     .16       0  2951.9     .05       0
  3098.9     .16       0  3209.7     .07       0  3979.3     .12       0
  3987.8     .07       0  4095.8     .12       0  4455.2     .07       0
    4539     .12       0  4974.5     .07       0  5004.5     .12       0
  5561.3     .16       0
Bank Sta=4968.6,5010.6
XS Rating Curve= 0 ,0
Exp/Cntr=0.3,0.1

Type RM Length L Ch R = 1 ,47869   ,950,950,950
BEGIN DESCRIPTION:
DUCK CREEK 26 0
END DESCRIPTION:
XS GIS Cut Line= 3
      3541533.15      10398295.4       3539957.6     10396945.55
      3539592.13     10396391.68
#Sta/Elev= 30
  2819.3  381.25  2869.3  379.53  2909.5  378.59  2971.6  374.93  3098.9  355.02
  3141.7  350.83    3291  360.06  3354.7  338.63  3404.1  316.86  3420.3  313.18
  3467.7   308.5  3545.6  306.07  3861.5  306.09  4209.4  306.84  4723.4   305.5
  4935.9  308.84  4972.1   305.9  4979.5  301.98    4980  300.98  5009.5  301.98
  5017.3  306.34  5182.8  307.21    5225  308.47  5255.1  312.64  5312.3  330.15
  5333.3   339.6  5363.5  345.73  5456.8  383.83  5529.1  401.79  5557.6  404.15
#Mann= 9 ,-1 , 0
  2819.3      .1       0  2869.3     .05       0  2909.5     .16       0
  3420.3     .12       0  3861.5     .07       0  4209.4     .12       0
  4979.5     .07       0  5009.5     .12       0  5182.8     .16       0
Bank Sta=4972.1,5017.3
XS Rating Curve= 0 ,0
Exp/Cntr=0.3,0.1

Type RM Length L Ch R = 1 ,46919   ,868,868,868
BEGIN DESCRIPTION:
DUCK CREEK 25 0
END DESCRIPTION:
XS GIS Cut Line= 3
      3541773.42     10397687.67      3540325.48     10396458.48
      3539471.32     10396201.53
#Sta/Elev= 30
  3413.7   371.1  3472.5  369.29  3553.8  362.66  3617.5  362.23  3674.6  357.85
  3752.6  344.52  3781.1  336.05  3830.6  316.57  3928.5  308.13  4035.9  304.66
  4972.9  306.05  4978.7  301.09  4979.2  300.09  5008.7  301.09  5015.7  305.47
  5065.2  307.46  5192.5  305.17    5264  308.09  5562.2  306.33  5600.4  307.98
  5644.4  314.06  5661.2  317.57  5699.5  332.76  5732.5  342.48  5770.7  348.37
  5803.8  359.92    5809   358.8  5908.1  396.76  6012.3  404.49    6205  406.99
#Mann= 6 ,-1 , 0
  3413.7     .05       0  3472.5     .16       0  3928.5     .12       0
  4978.7     .07       0  5008.7     .12       0  5644.4     .16       0
Bank Sta=4972.9,5015.7
XS Rating Curve= 0 ,0
Exp/Cntr=0.3,0.1

Type RM Length L Ch R = 1 ,46051   ,799,799,799
BEGIN DESCRIPTION:
DUCK CREEK 24 0
END DESCRIPTION:
XS GIS Cut Line= 2
      3542256.03     10396739.73      3539930.09     10395736.45
#Sta/Elev= 30
  3678.3   355.8    3763  352.46  3938.5  333.74  4166.5  314.51  4212.3  308.68
  4289.5  304.64  4455.8  304.34  4517.5  302.56    4837  306.29  4967.7  305.84
  4978.9  303.95  4981.9  300.68  4982.4  299.68  5011.9  300.68  5020.5   304.8
  5096.4  306.73  5728.6  305.39  5795.4   305.4  5832.8  307.25    5926  318.97
  5947.8  324.67  5969.6  333.79  5979.4  335.42  5984.8   333.8  6008.3   342.3
  6013.8  341.44  6055.4  357.88  6113.3  373.27  6165.7  384.72  6211.4  390.57
#Mann= 5 ,-1 , 0
  3678.3     .16       0  4212.3     .12       0  4981.9     .07       0
  5011.9     .12       0  5728.6     .16       0
Bank Sta=4967.7,5020.5
XS Rating Curve= 0 ,0
Exp/Cntr=0.3,0.1

Type RM Length L Ch R = 1 ,45252   ,635,635,635
BEGIN DESCRIPTION:
DUCK CREEK 21 2
END DESCRIPTION:
XS GIS Cut Line= 3
      3541692.14     10395741.65      3540992.11     10395641.64
      3539992.14     10395641.64
#Sta/Elev= 30
  4303.7  340.48    4334  336.73  4384.5  324.26  4414.8   314.3  4445.2  309.74
  4482.9  306.15  4543.8  303.04  4556.3  303.25  4561.5  301.55  4591.5  301.55
  4596.7  303.59  4616.9  302.39  4637.1  303.85  4671.6  303.92  4768.4  305.66
  4970.4   305.5  5000.7  301.98  5020.8  305.54  5111.4  305.61  5281.9  304.35
  5441.8  304.78  5670.8  308.31  5690.8  309.42  5770.8  318.86  5810.8  327.31
  5870.8  349.95  5940.8  370.88  5970.8   382.6  5990.8  387.44  6010.8  390.28
#Mann= 9 ,-1 , 0
  4303.7     .16       0  4482.9     .12       0  4543.8     .07       0
  4561.5     .07       0  4591.5     .07       0  4671.6     .12       0
  5111.4     .16       0  5281.9     .12       0  5441.8     .16       0
Bank Sta=4970.4,5020.8
XS Rating Curve= 0 ,0
Exp/Cntr=0.3,0.1

Type RM Length L Ch R = 1 ,44617   ,980,980,980
BEGIN DESCRIPTION:
DUCK CREEK 23 0
END DESCRIPTION:
XS GIS Cut Line= 4
      3543141.31     10395393.08      3541141.28     10395094.47
       3540434.1     10394796.26      3539356.84     10394358.47
#Sta/Elev= 30
  2810.1  346.95  2936.2  343.68  3038.9  342.51  3276.4  340.95  3415.9  341.29
  3617.7  328.91  3769.8  317.14  4095.5  310.43    4245  307.59  4351.4  299.85
  4381.4  299.85  4406.5  303.48  4972.5  305.62  5008.7  300.59  5056.1   305.7
  5515.4  304.59  5591.1  306.71  5769.1  321.13  5784.3  321.46  5918.9  331.69
    5943  338.86  5996.6  346.33  6055.5  347.39  6120.1  360.11  6186.7   357.1
  6414.2  365.91  6519.2  365.33  6662.9  363.87  6675.1  363.78  6762.6  362.47
#Mann= 15 ,-1 , 0
  2810.1     .05       0  2936.2     .16       0  3038.9     .05       0
  3276.4      .1       0  3617.7     .16       0  4095.5     .12       0
  4351.4     .07       0  4381.4     .12       0  5515.4     .16       0
  5769.1      .1       0  5784.3     .16       0  6414.2      .1       0
  6519.2     .05       0  6662.9      .1       0  6675.1     .05       0
Bank Sta=4972.5,5056.1
XS Rating Curve= 0 ,0
Exp/Cntr=0.3,0.1

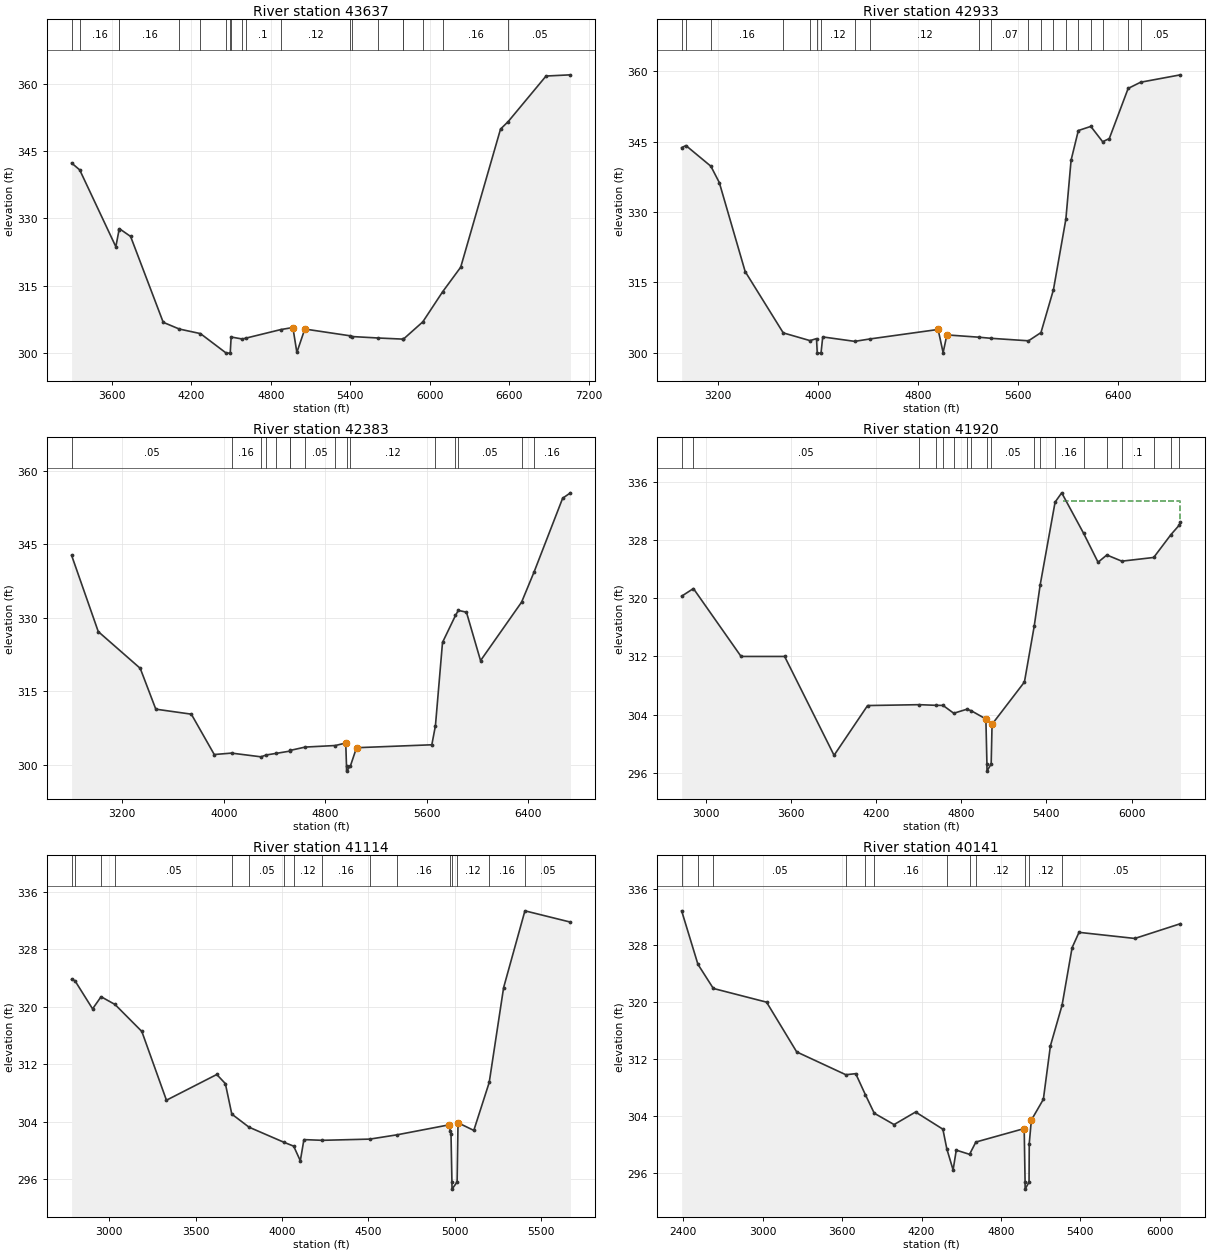
Type RM Length L Ch R = 1 ,43637   ,704,704,704
BEGIN DESCRIPTION:
DUCK CREEK 22 1
END DESCRIPTION:
XS GIS Cut Line= 4
      3542967.68     10395163.91      3541689.89     10394413.91
      3541252.39     10394420.85      3539419.01     10394219.46
#Sta/Elev= 30
  3297.9  342.36    3359  340.82  3631.6  323.67  3655.8  327.41    3659  327.69
    3743  325.96  3989.1  306.79  4110.4  305.29  4269.9  304.27  4464.6  299.91
  4494.6  299.91  4501.6  303.51  4585.5  303.06  4610.3  303.24  4876.4  305.17
  4967.3  305.63  4997.4  300.07  5057.4  305.29  5398.9  303.78  5414.7  303.61
  5609.7  303.29  5795.9  303.04  5800.2  303.01  5947.5  306.89  6096.9   313.6
  6233.5   319.1    6534  349.94  6591.8  351.61  6877.3  361.78  7061.5  362.05
#Mann= 20 ,-1 , 0
  3297.9     .05       0    3359     .16       0  3655.8      .1       0
    3659     .16       0  4110.4      .1       0  4269.9     .12       0
  4464.6     .07       0  4494.6     .12       0  4501.6      .1       0
  4585.5     .12       0  4610.3      .1       0  4876.4     .12       0
  5398.9     .16       0  5414.7     .12       0  5609.7     .07       0
  5795.9     .12       0  5800.2     .16       0  5947.5      .1       0
  6096.9     .16       0  6591.8     .05       0
Bank Sta=4967.3,5057.4
XS Rating Curve= 0 ,0
Exp/Cntr=0.3,0.1

Type RM Length L Ch R = 1 ,42933   ,550,550,550
BEGIN DESCRIPTION:
DUCK CREEK 22 0
END DESCRIPTION:
XS GIS Cut Line= 4
      3543044.07     10395052.81      3541557.95      10393865.3
      3540724.62     10393900.02      3539481.53     10394004.19
#Sta/Elev= 30
    2912  343.75  2946.5  344.18  3145.6  339.77  3212.8  336.29  3419.3   317.3
  3723.6   304.2  3937.3  302.55  3989.3  302.98  3995.1  299.88  4025.1  299.88
  4038.9  303.34  4294.3  302.39  4416.9  302.91  4960.3  304.93  5000.3  299.98
  5030.3  303.77  5284.8  303.28  5384.8  303.04  5682.1  302.51  5781.6  304.26
  5881.1  313.39  5980.6  328.48  6022.2  341.05  6080.1  347.39  6179.8  348.27
  6274.3     345  6327.3  345.67    6478  356.38  6577.5   357.7  6895.8  359.28
#Mann= 20 ,-1 , 0
    2912      .1       0  2946.5      .1       0  3145.6     .16       0
  3723.6      .1       0  3937.3     .12       0  3995.1     .07       0
  4025.1     .12       0  4294.3     .07       0  4416.9     .12       0
  5284.8     .16       0  5384.8     .07       0  5682.1     .05       0
  5781.6     .07       0  5881.1     .16       0  5980.6     .05       0
  6080.1      .1       0  6179.8      .1       0  6274.3     .05       0
    6478      .1       0  6577.5     .05       0
Bank Sta=4960.3,5030.3
XS Rating Curve= 0 ,0
Exp/Cntr=0.3,0.1

Type RM Length L Ch R = 1 ,42383   ,463,463,463
BEGIN DESCRIPTION:
DUCK CREEK 21 1
END DESCRIPTION:
XS GIS Cut Line= 5
      3543216.73     10394779.01      3543005.82     10394471.76
      3541359.98     10393359.78      3540667.27     10393591.55
      3539831.35     10393461.34
#Sta/Elev= 30
  2799.9  342.71  3010.1  327.15  3341.2  319.65  3464.1  311.31  3744.3  310.29
  3925.3  302.05  4061.6  302.34  4293.9  301.58  4335.8  301.96  4410.1  302.27
  4522.1  302.75  4526.2   302.9  4642.4  303.57  4880.5  303.89  4962.6   304.4
  4968.6  299.66  4969.1  298.66  4998.6  299.66  5047.7  303.44  5641.7  304.04
  5670.2  307.94    5726  324.94  5828.3  330.44  5850.8  331.48  5914.8  331.11
  6026.1  321.22    6350  333.17  6449.4  339.39  6673.8  354.38  6735.3  355.48
#Mann= 16 ,-1 , 0
  2799.9     .05       0  4061.6     .16       0  4293.9     .07       0
  4335.8     .05       0  4410.1     .12       0  4522.1     .05       0
  4526.2     .12       0  4642.4     .05       0  4880.5     .12       0
  4968.6     .07       0  4998.6     .12       0  5670.2     .05       0
  5828.3     .16       0  5850.8     .05       0    6350      .1       0
  6449.4     .16       0
#XS Ineff= 2 , 0
                         5870.68          331.14
Permanent Ineff=
       F       F
Bank Sta=4962.6,5047.7
XS Rating Curve= 0 ,0
Exp/Cntr=0.3,0.1

Type RM Length L Ch R = 1 ,41920   ,806,806,806
BEGIN DESCRIPTION:
DUCK CREEK 21 0
END DESCRIPTION:
XS GIS Cut Line= 4
      3543216.72     10394354.54      3541206.34     10392781.65
      3541143.84     10392508.22      3540609.96     10392088.93
#Sta/Elev= 30
  2831.9   320.3  2914.9  321.35  3250.4     312    3557     312  3905.1  298.39
  4141.1  305.24  4504.2  305.36  4625.9  305.27    4672  305.26  4747.6  304.18
  4839.8  304.73  4869.3  304.54  4973.9  303.39  4981.2  297.21  4981.7  296.21
  5011.2  297.21  5017.3  302.66  5245.2  308.48  5314.3  316.19  5356.1  321.85
  5461.1  333.25  5507.6  334.53  5661.7  328.96  5763.6  324.97  5825.3  325.97
  5930.9  325.12  6155.4  325.63  6277.3  328.79  6333.3  330.04  6343.8  330.49
#Mann= 19 ,-1 , 0
  2831.9      .1       0  2914.9     .05       0  4504.2     .05       0
  4625.9     .08       0    4672     .16       0  4747.6     .08       0
  4839.8     .16       0  4869.3     .05       0  4981.2     .04       0
  5011.2     .05       0  5314.3     .16       0  5356.1     .08       0
  5461.1     .16       0  5661.7      .1       0  5825.3     .16       0
  5930.9      .1       0  6155.4     .05       0  6277.3      .1       0
  6333.3     .05       0
#XS Ineff= 2 , 0
                         5516.97          333.46
Permanent Ineff=
       F       F
Bank Sta=4973.9,5017.3
XS Rating Curve= 0 ,0
Exp/Cntr=0.3,0.1

Type RM Length L Ch R = 1 ,41114   ,973,973,973
BEGIN DESCRIPTION:
DUCK CREEK 19 0
END DESCRIPTION:
XS GIS Cut Line= 3
      3543349.64      10394455.6      3542176.01     10392976.41
       3542002.4     10391990.31
#Sta/Elev= 30
  2781.9  323.82  2801.2  323.64  2903.4  319.72  2952.6  321.41  3033.3  320.33
  3188.6  316.58  3331.2  307.01  3622.8  310.59  3672.5  309.32  3709.8  305.08
  3809.5  303.26  4012.6  301.15  4068.2  300.62  4106.7  298.58  4127.5  301.53
  4234.1  301.43  4509.6   301.6  4667.7   302.2  4969.4  303.59  4976.4  302.68
  4979.6  302.26  4984.9  295.64  4985.4  294.64  5014.9  295.64  5020.2  303.87
  5111.6  302.81  5200.8  309.48  5284.2  322.67  5407.7  333.36  5671.4  331.79
#Mann= 16 ,-1 , 0
  2781.9      .1       0  2801.2     .05       0  2952.6      .1       0
  3033.3     .05       0  3709.8      .1       0  3809.5     .05       0
  4012.6     .07       0  4068.2     .12       0  4234.1     .16       0
  4509.6     .12       0  4667.7     .16       0  4976.4     .12       0
  4984.9     .07       0  5014.9     .12       0  5200.8     .16       0
  5407.7     .05       0
Bank Sta=4969.4,5020.2
XS Rating Curve= 0 ,0
Exp/Cntr=0.3,0.1

Type RM Length L Ch R = 1 ,40141   ,134,134,134
BEGIN DESCRIPTION:
DUCK CREEK 172 0
END DESCRIPTION:
XS GIS Cut Line= 5
      3543754.09     10394705.01      3543897.31     10393845.68
      3543193.92     10393167.65      3542842.63     10392313.56
      3541952.83     10391857.81
#Sta/Elev= 30
  2386.4  332.87  2509.6  325.34    2626  321.94  3028.5  320.01  3256.5     313
  3627.8  309.79  3702.6  309.94  3775.3  306.99  3842.7  304.37  3992.5  302.77
  4155.1  304.54  4361.5  302.12  4391.5  299.34  4438.8  296.38  4462.8  299.17
  4563.2  298.58  4610.9  300.31  4976.3  302.21    4983  294.68  4983.5  293.68
    5013  294.68  5014.5   300.1  5030.4   303.4  5121.2  306.33  5174.4  313.85
  5262.9   319.6  5338.4  327.68  5390.8  329.84  5812.7  328.98  6157.8  331.06
#Mann= 12 ,-1 , 0
  2386.4     .05       0  2509.6      .1       0    2626     .05       0
  3627.8     .16       0  3775.3     .05       0  3842.7     .16       0
  4391.5     .07       0  4563.2     .16       0  4610.9     .12       0
    4983     .07       0    5013     .12       0  5262.9     .05       0
Bank Sta=4976.3,5030.4
XS Rating Curve= 0 ,0
Exp/Cntr=0.3,0.1

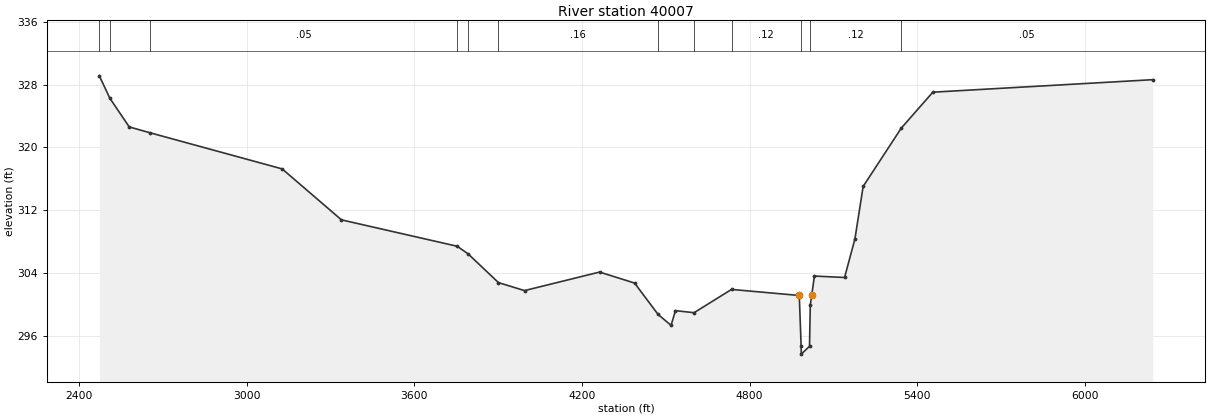
Type RM Length L Ch R = 1 ,40007   ,396,396,396
BEGIN DESCRIPTION:
DUCK CREEK 161 0
END DESCRIPTION:
XS GIS Cut Line= 5
      3543853.05     10394637.32      3543996.27     10393777.97
      3543292.87     10393099.94      3542941.59     10392245.86
       3542051.8     10391790.11
#Sta/Elev= 30
  2472.1  329.11  2509.7  326.26  2579.2  322.61  2654.3  321.86  3126.7  317.27
  3338.9  310.79  3753.4  307.43  3792.8  306.45  3900.9  302.81  3994.3  301.79
  4263.1  304.15  4388.4  302.75  4472.5  298.76    4519  297.37  4534.7  299.24
  4601.3  298.98  4735.5  301.94    4978  301.17  4984.7  294.71  4985.2  293.71
  5014.7  294.71  5017.4  299.97  5022.8  301.24  5032.1  303.64  5140.2  303.46
  5177.4  308.39  5206.7  315.04  5343.2  322.46  5456.2  327.03  6243.5  328.62
#Mann= 12 ,-1 , 0
  2472.1     .05       0  2509.7      .1       0  2654.3     .05       0
  3753.4     .16       0  3792.8     .05       0  3900.9     .16       0
  4472.5     .07       0  4601.3     .16       0  4735.5     .12       0
  4984.7     .07       0  5014.7     .12       0  5343.2     .05       0
Bank Sta=4978,5022.8
XS Rating Curve= 0 ,0
Exp/Cntr=0.3,0.1