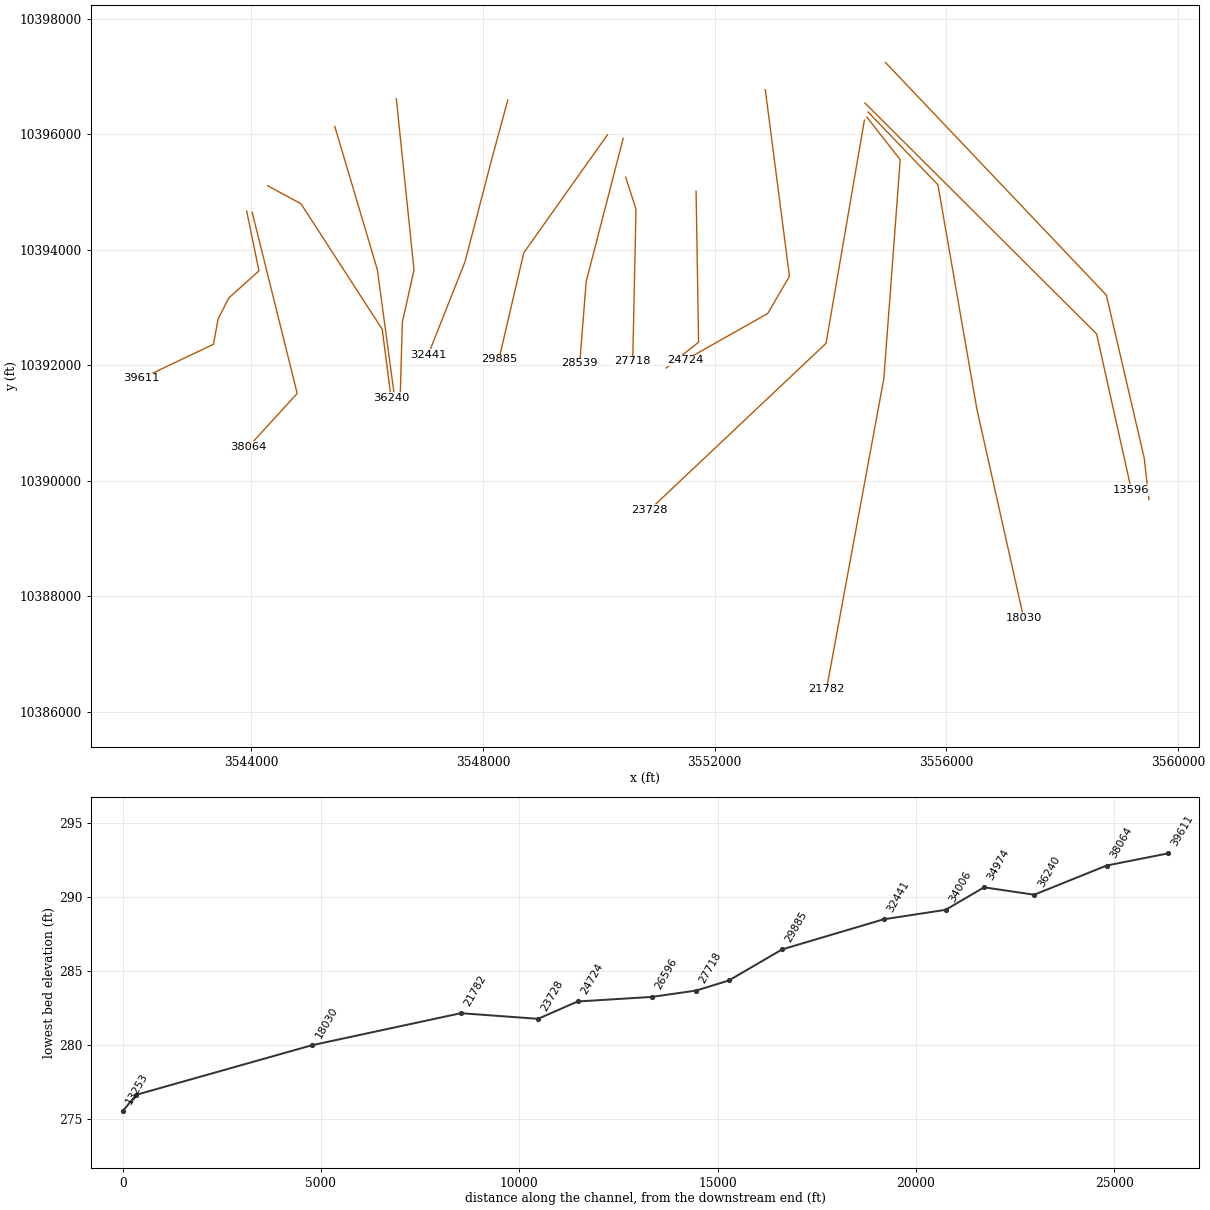
HEC-RAS study DUCK CREEK.prj: DUCK CREEK Base Level Engineering

--- DUCK CREEK.g01 (geometry) --- (continued)

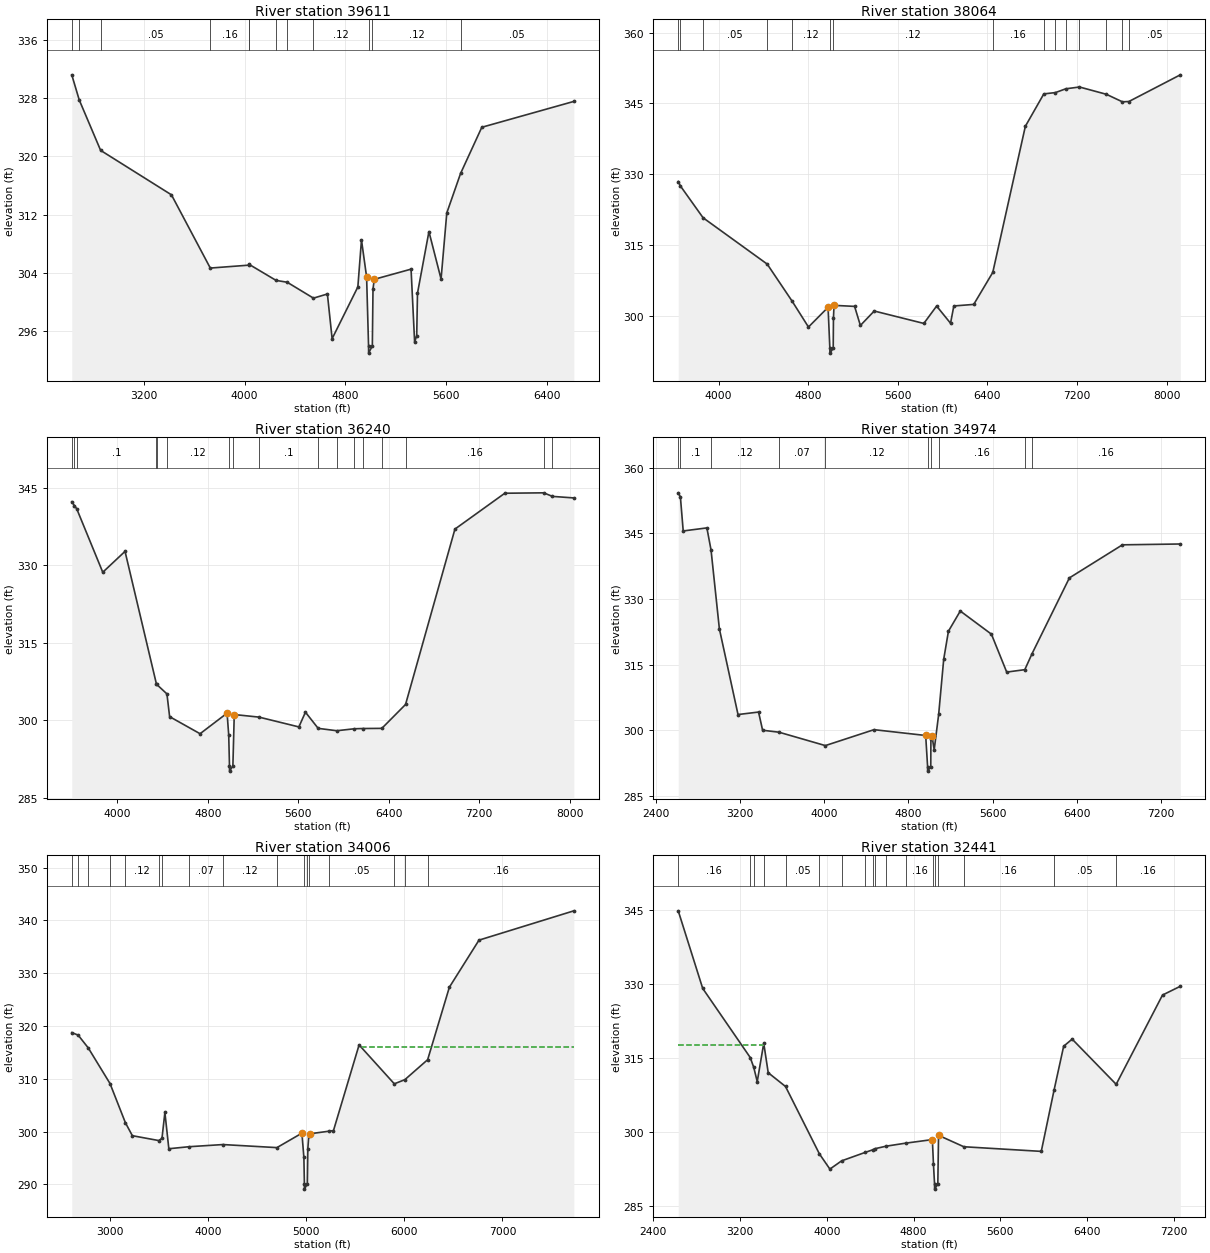
Type RM Length L Ch R = 1 ,39611   ,1547,1547,1547
BEGIN DESCRIPTION:
DUCK CREEK 150 0
END DESCRIPTION:
XS GIS Cut Line= 6
      3543918.14     10394672.09      3544130.82     10393634.74
      3543609.99     10393165.99      3543424.88     10392800.75
      3543345.02     10392363.25      3542105.49     10391773.52
#Sta/Elev= 30
  2628.5  331.23  2687.6  327.78  2857.6  320.83    3420  314.71  3728.4  304.63
  4034.6  305.03  4035.4  305.15  4250.8  302.93  4338.8  302.68  4547.4  300.49
  4658.2  301.06  4695.7  294.91    4900  302.03  4928.8   308.5  4969.5  303.41
    4985  293.92  4985.5  292.92    5015  293.92  5020.3  301.75  5030.5  303.08
  5322.5  304.48  5350.8  294.44  5367.4  295.34  5373.5  301.16  5464.4  309.65
  5560.7  303.12  5606.2  312.22  5715.6  317.65  5884.2  324.01    6615  327.57
#Mann= 12 ,-1 , 0
  2628.5     .05       0  2687.6      .1       0  2857.6     .05       0
  3728.4     .16       0  4034.6     .05       0  4035.4     .16       0
  4250.8     .12       0  4338.8     .16       0  4547.4     .12       0
    4985     .07       0    5015     .12       0  5715.6     .05       0
Bank Sta=4969.5,5030.5
XS Rating Curve= 0 ,0
Exp/Cntr=0.3,0.1

Type RM Length L Ch R = 1 ,38064   ,1824,1824,1824
BEGIN DESCRIPTION:
DUCK CREEK 151 0
END DESCRIPTION:
XS GIS Cut Line= 3
      3544013.62     10394650.41      3544790.54     10391512.35
      3543948.51     10390587.84
#Sta/Elev= 30
  3639.4  328.45  3658.8  327.51  3861.3  320.77  4433.8  310.96  4656.3  303.11
  4802.2  297.63  4977.4  301.81  4993.3   293.1  4993.8   292.1  5023.3   293.1
  5025.4   299.5  5030.5  302.22  5214.3     302  5265.8  297.96  5389.5  301.02
  5832.4  298.39  5946.7  302.07  6070.9  298.43  6100.3  302.09    6278  302.42
  6448.1   309.2    6739  340.15  6903.8  347.01  7007.6  347.29  7100.1  348.09
  7222.4  348.47  7462.1  346.93  7605.8  345.33  7663.7   345.4  8122.7  351.05
#Mann= 15 ,-1 , 0
  3639.4     .05       0  3658.8      .1       0  3861.3     .05       0
  4433.8     .16       0  4656.3     .12       0  4993.3     .07       0
  5023.3     .12       0  6448.1     .16       0  6903.8     .05       0
  7007.6     .16       0  7100.1     .05       0  7222.4      .1       0
  7462.1     .05       0  7605.8     .16       0  7663.7     .05       0
Bank Sta=4977.4,5030.5
XS Rating Curve= 0 ,0
Exp/Cntr=0.3,0.1

Type RM Length L Ch R = 1 ,36240   ,1266,1266,1266
BEGIN DESCRIPTION:
DUCK CREEK 140 0
END DESCRIPTION:
XS GIS Cut Line= 4
      3544279.69     10395109.23      3544856.07     10394796.74
      3546258.84     10392623.13      3546411.56     10391436.12
#Sta/Elev= 30
  3597.5  342.35  3620.4  341.62  3641.2  340.99  3871.6  328.68  4068.4  332.73
  4345.7  307.05  4348.5  306.94  4438.9   305.1  4462.7  300.69  4731.9  297.38
  4970.8  301.37  4985.2  297.14  4992.1  291.13  4992.6  290.13  5022.1  291.13
  5034.2   301.1  5253.2   300.6  5605.7   298.7  5663.6  301.56  5776.2  298.42
  5940.8  297.96  6095.5  298.34  6168.7  298.39  6339.1  298.42  6548.8  303.05
  6985.5  337.05  7426.4     344  7770.5  344.08  7847.3  343.39  8036.9  343.09
#Mann= 17 ,-1 , 0
  3597.5     .08       0  3620.4     .05       0  3641.2      .1       0
  4345.7     .12       0  4348.5      .1       0  4438.9     .12       0
  4992.1     .07       0  5022.1     .12       0  5253.2      .1       0
  5776.2     .07       0  5940.8     .12       0  6095.5     .07       0
  6168.7     .12       0  6339.1     .07       0  6548.8     .16       0
  7770.5     .05       0  7847.3     .16       0
Bank Sta=4970.8,5034.2
XS Rating Curve= 0 ,0
Exp/Cntr=0.3,0.1

Type RM Length L Ch R = 1 ,34974   ,968,968,968
BEGIN DESCRIPTION:
DUCK CREEK 141 0
END DESCRIPTION:
XS GIS Cut Line= 3
       3545439.4     10396137.03      3546175.51      10393650.9
      3546466.97     10391485.75
#Sta/Elev= 30
  2609.1  354.27  2629.8  353.31  2656.4  345.55  2881.7  346.25  2921.2  341.21
  3000.6  323.16  3177.9  303.57  3373.4  304.14  3411.9  299.98  3568.1  299.53
    4009  296.47  4472.1  300.11  4963.7  298.78    4982  291.63  4982.5  290.63
    5012  291.63  5013.4  298.04  5023.9  298.62  5044.7  295.52  5087.3  303.62
  5135.2  316.21  5180.3  322.63  5292.9  327.24  5589.1  321.95  5734.7  313.28
  5906.8  313.83  5976.3  317.51  6331.3  334.82  6835.8  342.38  7386.6  342.57
#Mann= 10 ,-1 , 0
  2609.1     .05       0  2629.8      .1       0  2921.2     .12       0
  3568.1     .07       0    4009     .12       0    4982     .07       0
    5012     .12       0  5087.3     .16       0  5906.8     .07       0
  5976.3     .16       0
#XS Ineff= 2 , 0
                         5289.64          327.01
Permanent Ineff=
       F       F
Bank Sta=4963.7,5023.9
XS Rating Curve= 0 ,0
Exp/Cntr=0.3,0.1

Type RM Length L Ch R = 1 ,34006   ,1565,1565,1565
BEGIN DESCRIPTION:
DUCK CREEK 169 0
END DESCRIPTION:
XS GIS Cut Line= 4
       3546501.9     10396616.22      3546807.46      10393650.9
      3546606.07     10392748.13       3546571.4     10391534.71
#Sta/Elev= 30
  2608.1  318.75  2672.9  318.28  2776.2  315.85  2997.9  309.11  3155.1  301.68
  3225.9  299.23  3494.3  298.31  3527.9  298.71  3557.7  303.63  3597.9  296.76
    3803  297.14  4149.7  297.55  4700.2  296.97    4955  299.71  4975.1  295.11
  4980.3  290.11  4980.8  289.11  5010.3  290.11  5015.4  296.77  5024.4  299.09
  5035.5  299.59  5230.9  300.08  5276.7  300.19  5538.1  316.42  5897.2  309.05
  6004.9  309.84  6237.2  313.62  6458.8  327.35  6760.7  336.26    7728  341.81
#Mann= 17 ,-1 , 0
  2608.1      .1       0  2672.9     .05       0  2776.2     .16       0
  2997.9      .1       0  3155.1     .12       0  3494.3     .07       0
  3527.9     .12       0    3803     .07       0  4149.7     .12       0
  4700.2     .16       0  4980.3     .07       0  5010.3     .16       0
  5024.4     .12       0  5230.9     .05       0  5897.2     .16       0
  6004.9     .12       0  6237.2     .16       0
#XS Ineff= 2 , 0
                         5563.49          316.01
Permanent Ineff=
       F       F
Bank Sta=4955,5035.5
XS Rating Curve= 0 ,0
Exp/Cntr=0.3,0.1

Type RM Length L Ch R = 1 ,32441   ,2556,2556,2556
BEGIN DESCRIPTION:
DUCK CREEK 131 0
END DESCRIPTION:
XS GIS Cut Line= 4
      3548426.34     10396592.97      3548148.56     10395564.29
      3547688.49     10393793.46      3547050.47     10392178.89
#Sta/Elev= 30
  2629.9  344.87  2855.5  329.15  3294.1  315.14  3326.6  313.13  3358.6  310.26
  3418.7  318.03  3459.9  312.06  3619.5  309.27  3931.9  295.62  4028.8  292.53
  4136.8   294.2  4352.6   295.9    4424  296.44  4444.3  296.66  4546.7  297.17
  4728.8  297.79    4974  298.51  4984.2   293.5  4994.3  289.47  4994.8  288.47
  5024.3  289.47    5031  299.37  5264.1  297.06  5978.6  296.12  6096.8  308.56
  6185.1  317.43  6263.5  318.87  6669.5  309.71  7096.9   327.8  7261.1  329.58
#Mann= 18 ,-1 , 0
  2629.9     .16       0  3294.1      .1       0  3326.6     .16       0
  3418.7      .1       0  3619.5     .05       0  3931.9     .12       0
  4136.8     .05       0  4352.6     .16       0    4424      .1       0
  4444.3     .16       0  4546.7     .05       0  4728.8     .16       0
  4984.2     .12       0  4994.3     .07       0  5024.3     .12       0
  5264.1     .16       0  6096.8     .05       0  6669.5     .16       0
#XS Ineff= 2 , 0
         3421.88  317.61 6255.12          318.42
Permanent Ineff=
       F       F
Bank Sta=4974,5031
XS Rating Curve= 0 ,0
Exp/Cntr=0.3,0.1

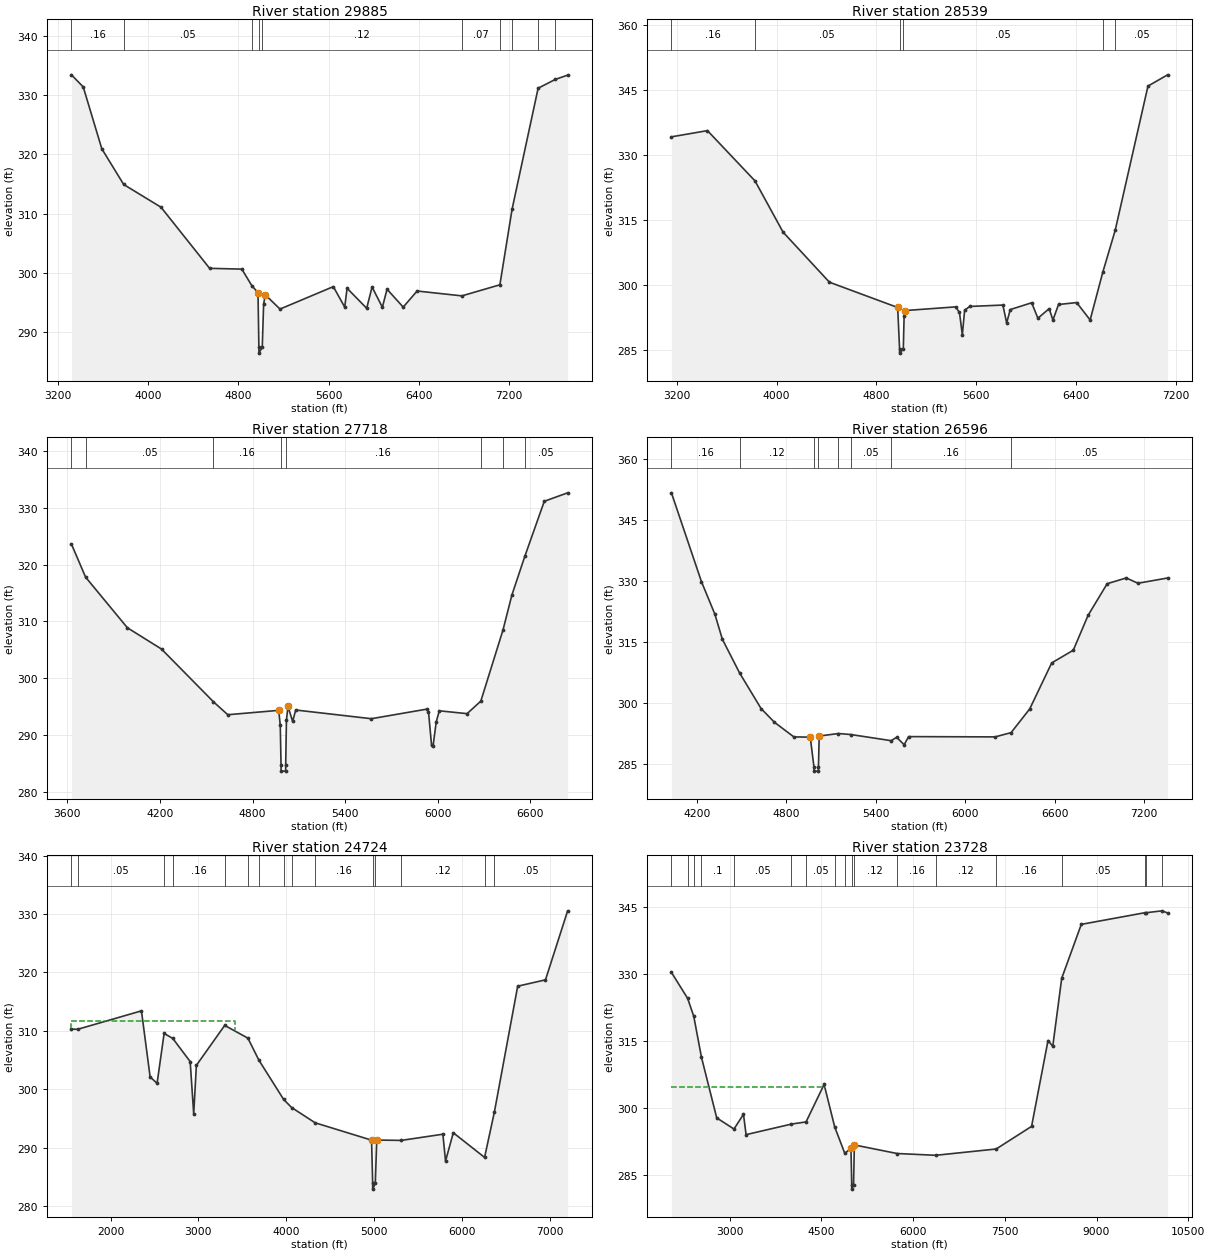
Type RM Length L Ch R = 1 ,29885   ,1346,1346,1346
BEGIN DESCRIPTION:
DUCK CREEK 121 0
END DESCRIPTION:
XS GIS Cut Line= 3
      3550147.74      10395991.2      3548703.29     10393949.52
      3548272.74     10392102.31
#Sta/Elev= 30
  3320.8  333.44  3425.1  331.39  3589.7  320.95  3783.7  314.92  4114.4  311.08
  4545.2  300.76  4830.7  300.63  4919.6  297.82    4974  296.66  4981.9  287.44
  4982.4  286.44  5011.9  287.44  5023.9  294.72  5038.7  296.29  5169.2  293.88
  5641.8  297.67  5742.7  294.21  5763.6   297.4  5937.4  294.01  5985.1  297.61
  6076.3  294.19  6117.9  297.23  6261.1  294.21  6384.3  296.93  6781.2  296.11
    7118  297.98  7226.3  310.77    7457  331.18  7608.7  332.66  7718.5  333.39
#Mann= 10 ,-1 , 0
  3320.8     .16       0  3783.7     .05       0  4919.6     .12       0
  4981.9     .07       0  5011.9     .12       0  6781.2     .07       0
    7118     .16       0  7226.3     .05       0    7457     .16       0
  7608.7     .05       0
Bank Sta=4974,5038.7
XS Rating Curve= 0 ,0
Exp/Cntr=0.3,0.1

Type RM Length L Ch R = 1 ,28539   ,821,821,821
BEGIN DESCRIPTION:
DUCK CREEK 110 1
END DESCRIPTION:
XS GIS Cut Line= 3
      3550418.57     10395928.71      3549779.68     10393449.52
      3549668.72     10392034.75
#Sta/Elev= 30
  3156.6  334.15  3445.4  335.58  3826.9     324    4052   312.2  4423.8  300.67
  4971.1  294.85  4986.3  285.34  4986.8  284.34  5016.3  285.34  5022.7   292.9
    5033  294.15  5435.8  294.99  5466.8   293.7  5489.6  288.55  5508.1  294.23
  5549.4  295.09    5815  295.41  5845.1  291.28  5873.9  294.37  6045.7  295.94
  6095.8  292.38  6186.1  294.58  6216.2  291.96  6261.3  295.54  6406.8  295.98
  6514.6  291.97  6616.6  303.02  6715.4   312.6  6978.5  345.84  7135.9  348.43
#Mann= 6 ,-1 , 0
  3156.6     .16       0  3826.9     .05       0  4986.3    .035       0
  5016.3     .05       0  6616.6     .16       0  6715.4     .05       0
Bank Sta=4971.1,5033
XS Rating Curve= 0 ,0
Exp/Cntr=0.3,0.1

Type RM Length L Ch R = 1 ,27718   ,1122,1122,1122
BEGIN DESCRIPTION:
DUCK CREEK 94 0
END DESCRIPTION:
XS GIS Cut Line= 3
      3550461.93      10395256.1      3550639.87     10394704.92
      3550583.45     10392070.42
#Sta/Elev= 30
  3626.9  323.58  3718.4  317.78  3988.9  308.88  4210.2  305.13  4546.8  295.85
  4639.5  293.58  4969.5  294.35  4979.5  291.73  4984.6  284.66  4985.1  283.66
  5014.1  283.66  5014.6  284.66  5019.6  292.68  5029.6  295.03  5059.6  292.41
  5079.6  294.41  5569.7  292.88  5929.8  294.57  5939.8  294.12  5959.8  288.18
  5969.8  288.16  5989.8  292.31  6009.8  294.27  6189.8  293.77  6278.7  295.97
  6422.4  308.48  6479.9  314.62  6564.6   321.5  6689.9  331.12  6841.2  332.61
#Mann= 8 ,-1 , 0
  3626.9     .16       0  3718.4     .05       0  4546.8     .16       0
  4984.6     .07       0  5014.6     .16       0  6278.7     .16       0
  6422.4      .1       0  6564.6     .05       0
Bank Sta=4969.5,5029.6
XS Rating Curve= 0 ,0
Exp/Cntr=0.3,0.1

Type RM Length L Ch R = 1 ,26596   ,1872,1872,1872
BEGIN DESCRIPTION:
DUCK CREEK 51 0
END DESCRIPTION:
XS GIS Cut Line= 3
       3551677.2     10395013.11       3551720.6     10392400.23
      3551160.72     10391953.19
#Sta/Elev= 30
  4028.2  351.76  4229.7  329.88  4319.7  321.88  4369.7  315.73    4485  307.45
  4629.7  298.64  4719.8  295.25  4849.8  291.66  4959.8   291.6  4984.8  284.23
  4985.3  283.23  5014.3  283.23  5014.8  284.23  5019.8  291.87  5149.1  292.49
  5232.5  292.24  5502.6  290.73  5539.9  291.56  5589.9  289.72  5619.9  291.73
    6200  291.66  6307.7  292.71  6432.9  298.57    6580  309.87    6725  313.01
  6824.3  321.59  6952.4  329.38  7080.5   330.8  7158.9  329.49  7357.9  330.79
#Mann= 8 ,-1 , 0
  4028.2     .16       0    4485     .12       0  4984.8     .07       0
  5014.8     .12       0  5149.1     .16       0  5232.5     .05       0
  5502.6     .16       0  6307.7     .05       0
Bank Sta=4959.8,5019.8
XS Rating Curve= 0 ,0
Exp/Cntr=0.3,0.1

Type RM Length L Ch R = 1 ,24724   ,996,996,996
BEGIN DESCRIPTION:
DUCK CREEK 61 0
END DESCRIPTION:
XS GIS Cut Line= 4
      3552872.19     10396771.55      3553288.85     10393542.38
      3552913.85     10392896.55      3551482.69     10392086.42
#Sta/Elev= 30
  1555.4  310.31    1625  310.27  2351.9  313.43  2450.5  302.12  2529.9  301.03
  2609.8  309.56  2708.3  308.72  2906.4  304.75  2946.7  295.77    2977   304.1
  3299.4  310.94  3563.6  308.76  3688.5  304.99  3970.7  298.26  4060.7  296.89
  4329.2  294.27  4971.2   291.3  4983.5  283.92    4984  282.92  5013.5  283.92
    5030  291.32  5309.7  291.26  5782.7  292.32    5813  287.72  5901.1  292.57
  6257.3  288.35  6368.4  296.07  6634.2  317.65  6950.6  318.74  7202.7  330.55
#Mann= 15 ,-1 , 0
  1555.4      .1       0    1625     .05       0  2609.8      .1       0
  2708.3     .16       0  3299.4      .1       0  3563.6     .16       0
  3688.5     .05       0  3970.7     .16       0  4060.7     .05       0
  4329.2     .16       0  4983.5     .07       0  5013.5     .16       0
  5309.7     .12       0  6257.3     .16       0  6368.4     .05       0
#XS Ineff= 2 , 0
         3420.71  311.72
Permanent Ineff=
       F       F
Bank Sta=4971.2,5030
XS Rating Curve= 0 ,0
Exp/Cntr=0.3,0.1

Type RM Length L Ch R = 1 ,23728   ,1946,1946,1946
BEGIN DESCRIPTION:
DUCK CREEK 4 2
END DESCRIPTION:
XS GIS Cut Line= 3
      3554582.77     10396243.09      3553920.88     10392380.22
      3550873.25     10389495.28
#Sta/Elev= 30
  2046.9  330.31  2311.3   324.5  2411.6   320.5  2537.5  311.33  2787.5  297.71
  3069.9  295.22  3225.3  298.51  3267.8  293.96  4009.5  296.32  4248.9  296.81
  4544.2  305.21  4717.9  295.66  4882.4  289.77  4983.7  290.89  4995.9  282.75
  4996.4  281.75  5025.9  282.75  5038.7  291.65  5738.1  289.73  6369.6  289.33
  7358.6  290.74  7937.7  295.81  8206.7  315.04  8284.4  313.75  8430.7  328.99
  8751.2  341.07  9788.4  343.67  9806.4  343.67 10071.8   344.1 10162.6  343.62
#Mann= 18 ,-1 , 0
  2046.9     .16       0  2311.3      .1       0  2411.6     .16       0
  2537.5      .1       0  3069.9     .05       0  4009.5      .1       0
  4248.9     .05       0  4717.9     .16       0  4882.4     .12       0
  4995.9     .07       0  5025.9     .12       0  5738.1     .16       0
  6369.6     .12       0  7358.6     .16       0  8430.7     .05       0
  9788.4      .1       0  9806.4     .15       0 10071.8      .1       0
#XS Ineff= 2 , 0
         4557.05  304.74
Permanent Ineff=
       F       F
Bank Sta=4983.7,5038.7
XS Rating Curve= 0 ,0
Exp/Cntr=0.3,0.1

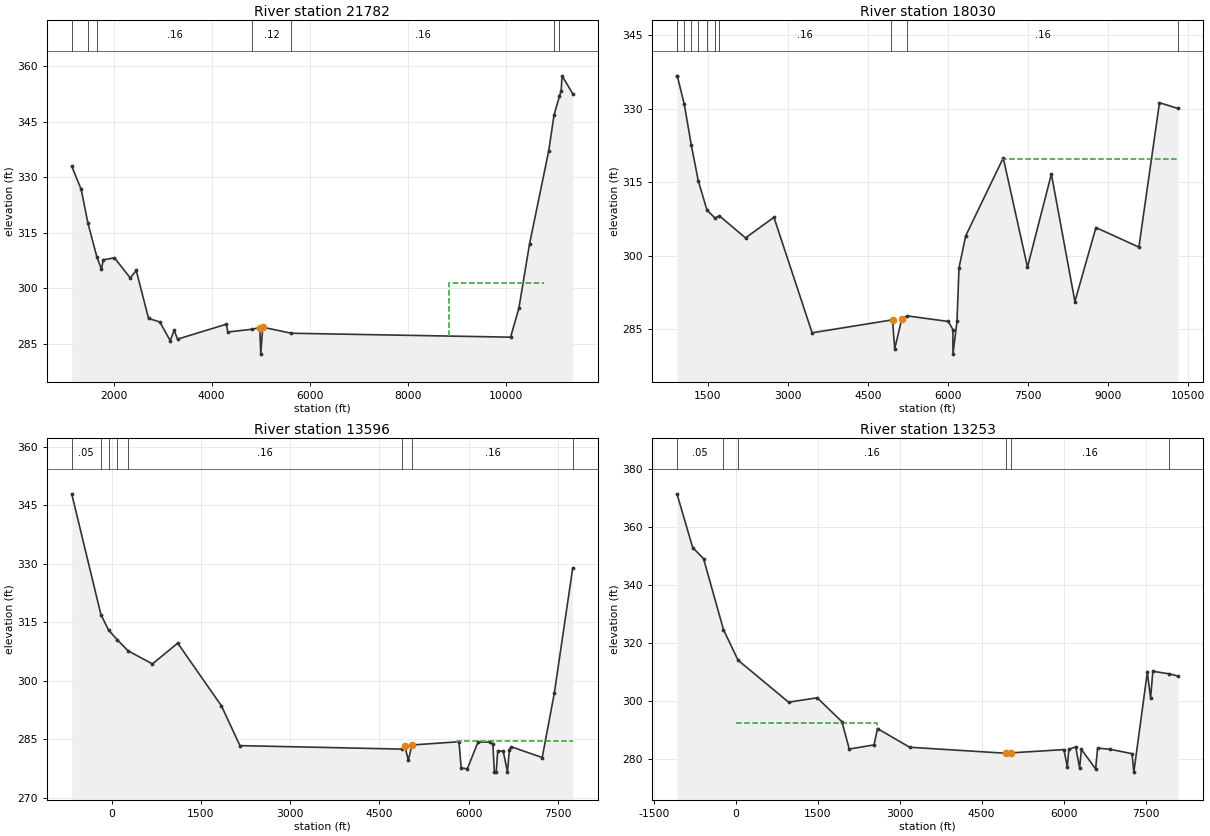
Type RM Length L Ch R = 1 ,21782   ,3752,3752,3752
BEGIN DESCRIPTION:
DUCK CREEK 40 1
END DESCRIPTION:
XS GIS Cut Line= 4
      3554626.18     10396297.32      3555201.26     10395559.48
      3554919.14     10391772.58      3553928.61     10386390.55
#Sta/Elev= 30
  1148.7  332.99  1342.6  326.67  1478.3  317.59    1663  308.35  1755.1  305.12
  1790.4  307.63  2018.4  308.18  2342.7  302.72  2463.1  304.77  2713.8  291.79
  2943.6  290.83    3155  285.78  3235.2  288.55  3305.4  286.19  4298.2  290.22
  4328.2  288.11  4828.4  288.87    4980  289.33  4999.8  282.13  5040.2  289.41
  5621.3  287.78 10089.3  286.72 10258.6  294.58 10475.9     312 10867.5  337.21
 10973.6  346.78 11084.3  351.88   11119  353.37 11137.8  357.41   11354  352.61
#Mann= 7 ,-1 , 0
  1148.7     .16       0  1478.3      .1       0    1663     .16       0
  4828.4     .12       0  5621.3     .16       0 10973.6     .05       0
 11084.3     .16       0
#XS Ineff= 1 ,-1
 8837.9110775.49  301.43
Permanent Ineff=
       T
Bank Sta=4980,5040.2
XS Rating Curve= 0 ,0
Exp/Cntr=0.3,0.1

Type RM Length L Ch R = 1 ,18030   ,4434,4434,4434
BEGIN DESCRIPTION:
DUCK CREEK 40 0
END DESCRIPTION:
XS GIS Cut Line= 5
      3554647.89     10396384.11       3555852.3     10395125.45
      3556214.62     10393033.34      3556525.05      10391240.9
      3557332.14      10387627.8
#Sta/Elev= 30
   921.2  336.72   927.4  336.67  1058.3  330.95  1189.2  322.63  1320.1  315.34
  1482.1  309.39  1631.2  307.73    1718  308.15  2206.1  303.67  2738.2  307.87
  3453.5  284.32  4930.3  286.91  4960.8  286.83  5001.4  281.08  5133.3  287.12
  5234.8  287.77  6006.1  286.63  6091.3  284.97  6092.6  279.97  6168.5  286.68
  6205.8  297.56  6330.9  304.08  7035.2  319.99  7488.9  297.71  7936.9  316.69
  8377.5   290.7  8771.5  305.78  9576.4  301.79  9962.1  331.24 10307.8  330.07
#Mann= 11 ,-1 , 0
   921.2     .05       0   927.4     .16       0  1058.3     .16       0
  1189.2     .16       0  1320.1      .1       0  1482.1     .05       0
  1631.2      .1       0    1718     .16       0  4930.3     .12       0
  5234.8     .16       0 10307.8     .16       0
#XS Ineff= 2 , 0
       0                 7013.47       0   319.8
Permanent Ineff=
       F       T
Bank Sta=4960.8,5133.3
XS Rating Curve= 0 ,0
Exp/Cntr=0.3,0.1

Type RM Length L Ch R = 1 ,13596   ,343,343,343
BEGIN DESCRIPTION:
DUCK CREEK 31 0
END DESCRIPTION:
XS GIS Cut Line= 3
      3554592.11     10396541.64      3558592.11     10392541.64
       3559192.1     10389841.66
#Sta/Elev= 30
  -673.6  347.94  -182.9     317   -53.2     313    92.3  310.55   273.9  307.71
     684  304.35  1108.3  309.68  1843.7   293.6  2154.8  283.41  4884.3  282.52
  4926.7  283.34  4985.8  279.65  5044.7  283.49  5051.1  283.58  5837.3  284.41
  5874.5  277.68  5978.2  277.49  6157.5  284.31  6366.2  284.34  6407.2  283.71
  6433.1  276.62  6463.1  276.62  6489.1  282.13  6581.3  281.98    6653  276.68
  6683.7  282.25  6715.8  283.13  7236.9  280.36  7441.8  296.98  7749.1  328.88
#Mann= 8 ,-1 , 0
  -673.6     .05       0  -182.9      .1       0   -53.2     .05       0
    92.3      .1       0   273.9     .16       0  4884.3     .12       0
  5051.1     .16       0  7749.1     .16       0
#XS Ineff= 2 , 0
       0                 5808.24       0  284.62
Permanent Ineff=
       F       T
Bank Sta=4926.7,5044.7
XS Rating Curve= 0 ,0
Exp/Cntr=0.3,0.1

Type RM Length L Ch R = 1 ,13253   ,0,0,0
BEGIN DESCRIPTION:
DUCK CREEK 1 0
END DESCRIPTION:
XS GIS Cut Line= 4
       3554946.6     10397243.51      3558759.73     10393215.72
      3559413.31     10390395.02      3559495.09     10389675.33
#Sta/Elev= 30
 -1073.8  371.34  -785.5  352.81  -587.7  349.04  -222.4  324.57    43.6  314.06
   968.5   299.6    1492   301.1  1944.6  292.88  2079.3  283.46    2532  284.89
  2595.5  290.51  3182.9  284.08  4946.1  282.01  5036.6  282.14  6006.3  283.27
  6067.9  277.29  6096.9  283.35  6221.9  284.22  6293.7   276.9  6325.7  283.33
  6586.9  276.62  6622.2   283.8  6858.4  283.35  7252.8  281.86  7285.6  275.51
  7532.5  309.87  7592.9  300.98  7633.1  310.23  7936.6  309.35  8092.4   308.6
#Mann= 6 ,-1 , 0
 -1073.8     .05       0  -222.4      .1       0    43.6     .16       0
  4946.1     .12       0  5036.6     .16       0  7936.6      .1       0
#XS Ineff= 2 , 0
       0 2593.18  292.36               0
Permanent Ineff=
       T       F
Bank Sta=4946.1,5036.6
XS Rating Curve= 0 ,0
Exp/Cntr=0.3,0.1

Chan Stop Cuts=-1
Use User Specified Reach Order=0
Composite Channel Slope=5