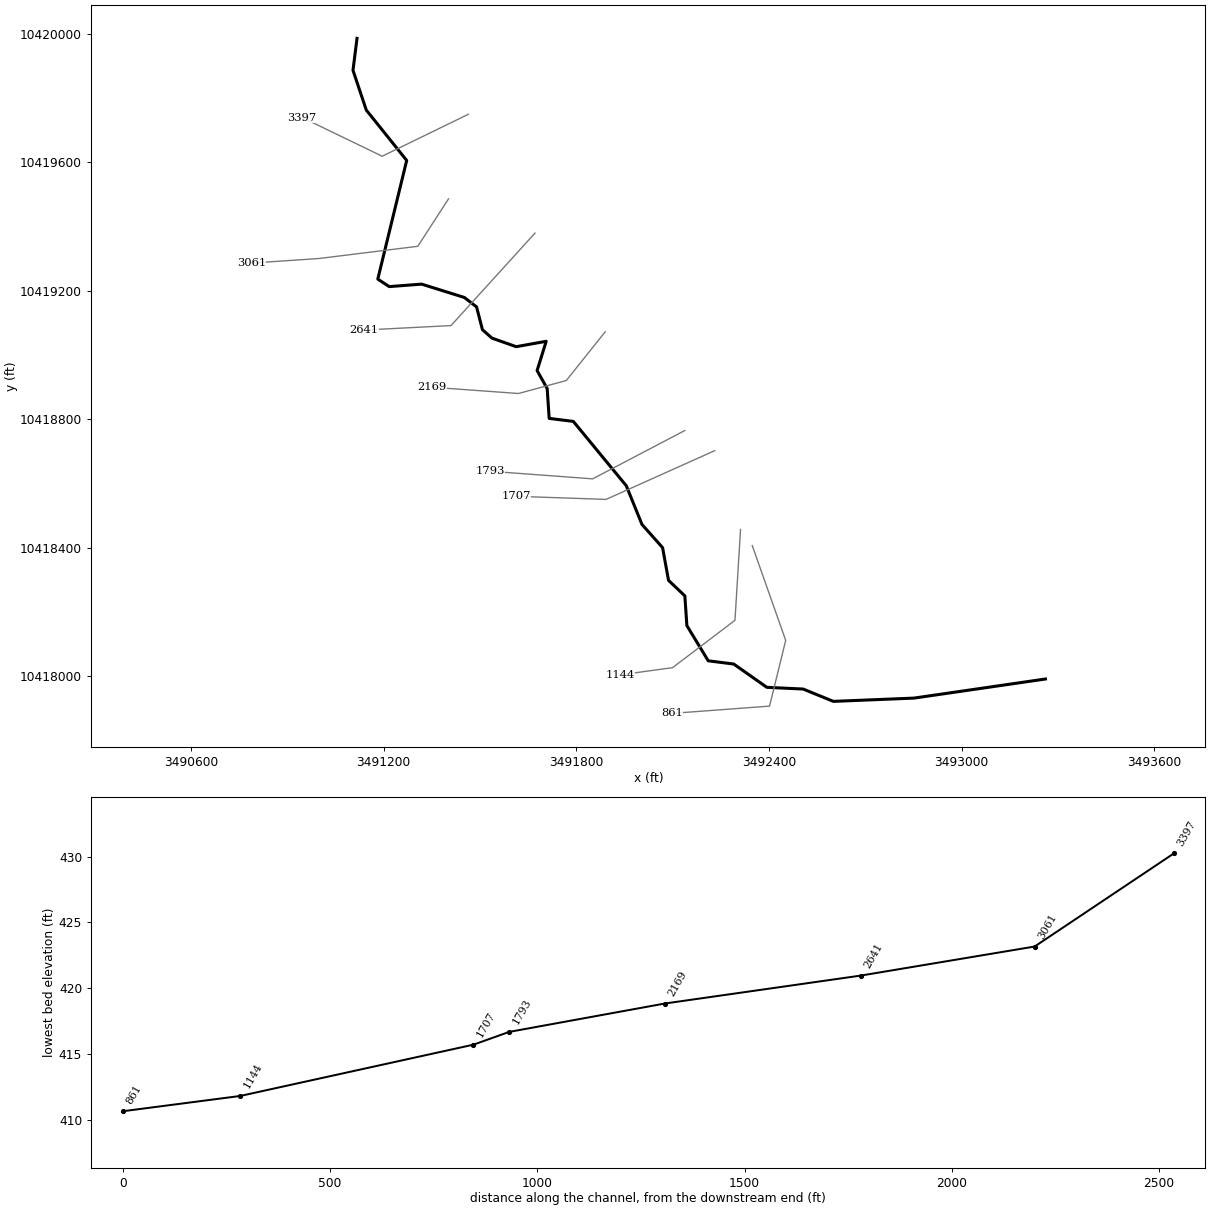
--- HERDS BRANCH TRIB 2.prj (project) ---

Proj Title=HERDS BRANCH TRIB 2 Base Level Engineering
Current Plan=p01
Default Exp/Contr=0.3,0.1
English Units
Geom File=g01
Flow File=f01
Plan File=p01
BEGIN DESCRIPTION:
HERDS BRANCH TRIB 2
END DESCRIPTION:

--- HERDS BRANCH TRIB 2.p01 (plan) ---

Plan Title=Multiple Run
Short Identifier=Multiple
Geom File=g01
Flow File=f01
Subcritical Flow
K Sum by GR= 0
Std Step Tol= 0.01
Critical Tol= 0.01
Num of Std Step Trials= 20
Max Error Tol= 0.3
Flow Tol Ratio= 0.001
Split Flow NTrial= 30
Split Flow Tol= 0.02
Split Flow Ratio= 0.02
Log Output Level= 0
Friction Slope Method= 1
Unsteady Friction Slope Method= 2
Unsteady Bridges Friction Slope Method= 1
Parabolic Critical Depth
Global Vel Dist=  1 , 1 , 1
Global Log Level= 0
CheckData=True
Encroach Param= -1, 0, 0, 0
BEGIN DESCRIPTION:
Multiple Run
END DESCRIPTION:

--- HERDS BRANCH TRIB 2.f01 (steady flow) ---

Flow Title=Multiple
Number of Profiles=7
Profile Names=10-year,25-year,50-year,1pct_min,100-year,1pct_plu,500-year
River Rch & RM= HERDS BRANCH TRI,Reach-1,3397
     325     419     492     424     573     775     772
Boundary for River Rch & Prof#=HERDS BRANCH TRI,Reach-1,1
Up Type=0
Dn Type=3
Dn Slope=0.005
Boundary for River Rch & Prof#=HERDS BRANCH TRI,Reach-1,2
Up Type=0
Dn Type=3
Dn Slope=0.005
Boundary for River Rch & Prof#=HERDS BRANCH TRI,Reach-1,3
Up Type=0
Dn Type=3
Dn Slope=0.005
Boundary for River Rch & Prof#=HERDS BRANCH TRI,Reach-1,4
Up Type=0
Dn Type=3
Dn Slope=0.005
Boundary for River Rch & Prof#=HERDS BRANCH TRI,Reach-1,5
Up Type=0
Dn Type=3
Dn Slope=0.005
Boundary for River Rch & Prof#=HERDS BRANCH TRI,Reach-1,6
Up Type=0
Dn Type=3
Dn Slope=0.005
Boundary for River Rch & Prof#=HERDS BRANCH TRI,Reach-1,7
Up Type=0
Dn Type=3
Dn Slope=0.005

--- HERDS BRANCH TRIB 2.g01 (geometry) ---

Geom Title=Existing Conditions

River Reach=HERDS BRANCH TRI,Reach-1
Reach XY= 30
      3491117.11     10419986.64      3491104.54     10419887.07
      3491145.97     10419763.22      3491271.84     10419606.27
      3491181.80     10419236.69      3491217.34     10419213.36
      3491318.35     10419221.03      3491451.44     10419179.50
      3491489.46     10419150.15      3491507.78     10419079.06
      3491537.36     10419052.91      3491612.85     10419026.20
      3491706.36     10419043.01      3491678.03     10418951.83
      3491709.41     10418895.85      3491715.63     10418802.86
      3491790.86     10418793.46      3491955.91     10418592.84
      3492004.60     10418472.68      3492068.89     10418400.26
      3492087.39     10418298.38      3492138.23     10418250.01
      3492144.53     10418157.43      3492211.04     10418047.81
      3492290.43     10418037.75      3492393.58     10417965.19
      3492506.62     10417959.87      3492600.86     10417921.44
      3492852.10     10417931.64      3493261.37     10417991.13

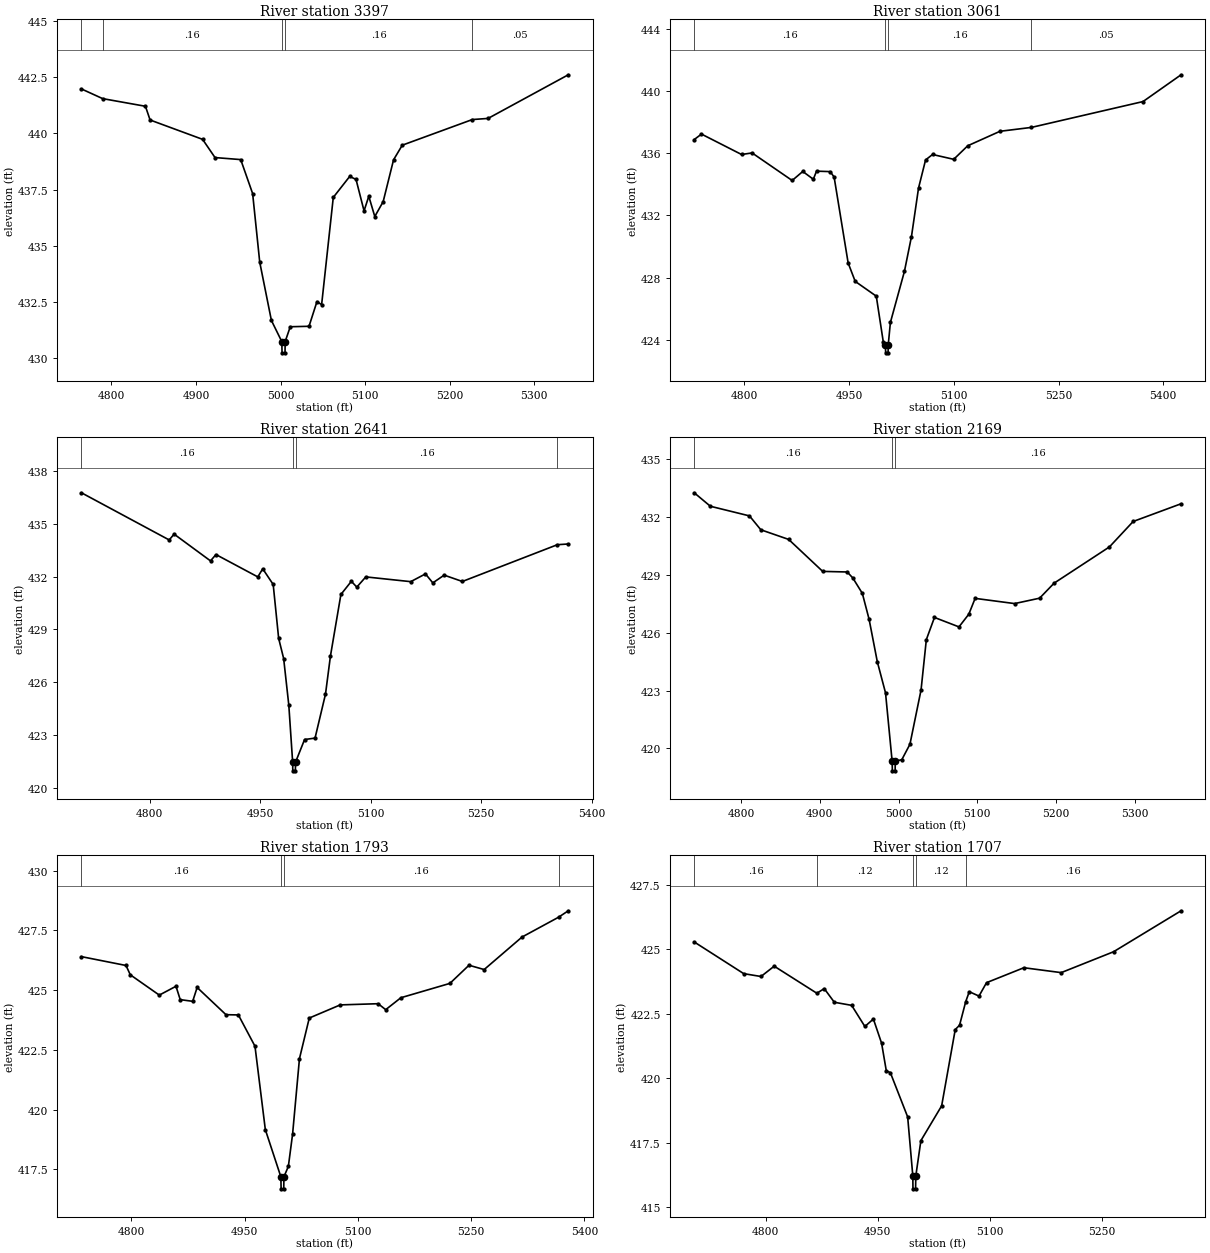
Type RM Length L Ch R = 1,3397,336,336,336
BEGIN DESCRIPTION:
HERDS BRANCH TRIB 2 9 0
END DESCRIPTION:
XS GIS Cut Line= 3
      3491464.15     10419750.26      3491195.54     10419619.43
      3490946.03     10419740.02
#Sta/Elev= 30
  4764.5  441.98  4789.6  441.55  4840.2  441.21  4845.7  440.60  4907.8  439.74
  4922.5  438.93  4952.9  438.84  4967.0  437.33  4975.4  434.28  4989.2  431.69
  5001.5  430.75  5001.8  430.25  5005.3  430.25  5005.5  430.75  5011.5  431.41
  5033.7  431.43  5043.1  432.53  5048.6  432.39  5062.4  437.16  5081.8  438.09
  5089.3  437.96  5098.8  436.56  5104.4  437.21  5111.5  436.31  5121.4  436.97
  5133.7  438.83  5144.0  439.48  5226.9  440.62  5245.5  440.67  5340.4  442.61
#Mann=5,-1,0
  4764.5    0.05       0  4789.6    0.16       0  5001.5    0.07       0
  5005.5    0.16       0  5226.9    0.05       0
Bank Sta=5001.5,5005.5
Exp/Cntr=0.3,0.1

Type RM Length L Ch R = 1,3061,420,420,420
BEGIN DESCRIPTION:
HERDS BRANCH TRIB 2 8 0
END DESCRIPTION:
XS GIS Cut Line= 4
      3491402.00     10419486.51      3491306.50     10419338.92
      3490997.47     10419300.73      3490787.72     10419286.61
#Sta/Elev= 30
  4728.1  436.87  4738.5  437.22  4795.9  435.91  4811.0  436.01  4868.4  434.24
  4883.6  434.82  4898.7  434.32  4903.3  434.84  4922.9  434.81  4928.5  434.46
  4948.6  428.94  4958.7  427.76  4988.9  426.81  4999.0  423.85  5002.0  423.67
  5002.3  423.17  5005.8  423.17  5006.0  423.67  5009.1  425.12  5029.2  428.40
  5039.3  430.64  5049.4  433.75  5059.5  435.56  5069.5  435.91  5099.8  435.60
  5119.9  436.47  5166.1  437.40  5211.2  437.65  5371.0  439.31  5425.5  441.03
#Mann=4,-1,0
  4728.1    0.16       0  5002.0    0.07       0  5006.0    0.16       0
  5211.2    0.05       0
Bank Sta=5002,5006
Exp/Cntr=0.3,0.1

Type RM Length L Ch R = 1,2641,472,472,472
BEGIN DESCRIPTION:
HERDS BRANCH TRIB 2 7 0
END DESCRIPTION:
XS GIS Cut Line= 3
      3491671.49     10419380.01      3491409.87     10419091.94
      3491138.46     10419078.03
#Sta/Elev= 30
  4707.5  436.76  4826.6  434.08  4833.3  434.41  4882.7  432.89  4890.1  433.25
  4946.9  431.98  4953.6  432.44  4967.8  431.55  4975.2  428.49  4982.0  427.34
  4989.0  424.69  4994.2  421.46  4994.4  420.96  4997.9  420.96  4998.2  421.46
  5010.4  422.74  5024.6  422.82  5038.8  425.32  5045.5  427.48  5059.7  430.98
  5073.9  431.73  5081.3  431.40  5093.5  431.98  5154.5  431.71  5174.5  432.15
  5184.5  431.64  5199.9  432.08  5224.6  431.72  5353.6  433.81  5368.4  433.85
#Mann=4,-1,0
  4707.5    0.16       0  4994.2    0.07       0  4998.2    0.16       0
  5353.6    0.05       0
Bank Sta=4994.2,4998.2
Exp/Cntr=0.3,0.1

Type RM Length L Ch R = 1,2169,376,376,376
BEGIN DESCRIPTION:
HERDS BRANCH TRIB 2 6 0
END DESCRIPTION:
XS GIS Cut Line= 4
      3491890.05     10419072.47      3491768.95     10418920.76
      3491620.03     10418880.39      3491351.45     10418899.88
#Sta/Elev= 30
  4740.8  433.27  4761.3  432.57  4810.9  432.07  4825.3  431.35  4860.6  430.85
  4903.8  429.19  4934.9  429.16  4942.0  428.85  4954.1  428.05  4962.7  426.70
  4973.1  424.50  4983.5  422.89  4991.9  419.34  4992.2  418.84  4995.7  418.84
  4995.9  419.34  5004.2  419.42  5014.5  420.22  5028.6  423.04  5035.3  425.65
  5045.6  426.80  5076.7  426.31  5089.2  426.97  5097.2  427.79  5147.3  427.52
  5179.0  427.80  5197.4  428.58  5267.6  430.46  5297.7  431.78  5358.5  432.70
#Mann=3,-1,0
  4740.8    0.16       0  4991.9    0.07       0  4995.9    0.16       0
Bank Sta=4991.9,4995.9
Exp/Cntr=0.3,0.1

Type RM Length L Ch R = 1,1793,86,86,86
BEGIN DESCRIPTION:
Mapping XS c665e6ad
END DESCRIPTION:
XS GIS Cut Line= 3
      3492137.79     10418764.88      3491851.07     10418614.56
      3491530.97     10418638.22
#Sta/Elev= 30
  4734.0  426.40  4793.0  426.03  4798.7  425.64  4837.1  424.79  4859.2  425.16
  4864.8  424.60  4881.3  424.53  4887.2  425.11  4925.4  423.97  4941.8  423.96
  4963.8  422.65  4977.5  419.16  4998.1  417.18  4998.4  416.68  5001.9  416.68
  5002.1  417.18  5008.0  417.62  5013.6  418.97  5022.7  422.13  5035.7  423.83
  5076.7  424.38  5126.9  424.43  5136.9  424.18  5157.0  424.68  5221.9  425.28
  5247.2  426.04  5267.3  425.86  5317.4  427.22  5365.8  428.05  5378.7  428.32
#Mann=4,-1,0
  4734.0    0.16       0  4998.1    0.07       0  5002.1    0.16       0
  5365.8    0.05       0
Bank Sta=4998.1,5002.1
Exp/Cntr=0.3,0.1

Type RM Length L Ch R = 1,1707,563,563,563
BEGIN DESCRIPTION:
Mapping XS 5716651b
END DESCRIPTION:
XS GIS Cut Line= 3
      3492230.99     10418702.23      3491892.82     10418550.54
      3491611.72     10418560.28
#Sta/Elev= 30
  4704.2  425.29  4770.5  424.06  4793.6  423.95  4811.3  424.35  4868.4  423.30
  4878.3  423.48  4891.8  422.95  4915.0  422.83  4932.7  422.01  4944.1  422.30
  4955.1  421.36  4961.4  420.29  4966.8  420.22  4990.0  418.50  4996.9  416.21
  4997.1  415.71  5000.6  415.71  5000.9  416.21  5007.7  417.58  5035.5  418.93
  5053.7  421.89  5059.5  422.06  5067.7  422.97  5072.5  423.36  5085.5  423.19
  5095.6  423.71  5145.6  424.29  5195.6  424.10  5265.7  424.91  5356.1  426.50
#Mann=5,-1,0
  4704.2    0.16       0  4868.4    0.12       0  4996.9    0.07       0
  5000.9    0.12       0  5067.7    0.16       0
Bank Sta=4996.9,5000.9
Exp/Cntr=0.3,0.1

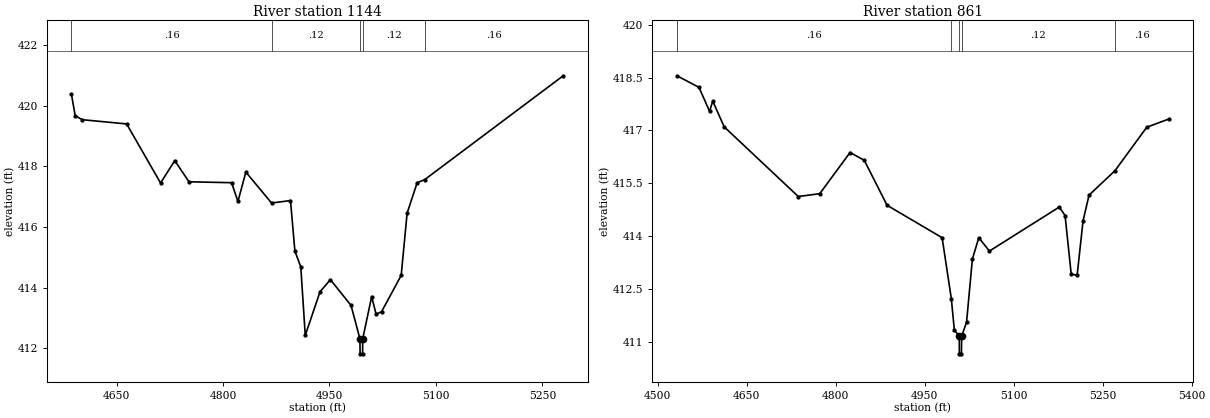
Type RM Length L Ch R = 1,1144,283,283,283
BEGIN DESCRIPTION:
HERDS BRANCH TRIB 2 5 0
END DESCRIPTION:
XS GIS Cut Line= 4
      3492311.70     10418456.96      3492294.34     10418173.99
      3492099.90     10418026.42      3491936.03     10418004.00
#Sta/Elev= 30
  4586.4  420.38  4591.7  419.67  4601.7  419.54  4664.2  419.40  4712.0  417.45
  4732.0  418.19  4752.0  417.49  4812.1  417.46  4821.0  416.84  4832.2  417.81
  4868.4  416.79  4895.1  416.87  4901.3  415.20  4909.6  414.68  4915.9  412.42
  4936.7  413.86  4951.3  414.26  4980.4  413.41  4992.9  412.31  4993.2  411.81
  4996.7  411.81  4996.9  412.31  5009.5  413.70  5015.7  413.12  5023.4  413.20
  5051.1  414.40  5059.4  416.45  5073.6  417.46  5084.1  417.56  5279.4  420.99
#Mann=5,-1,0
  4586.4    0.16       0  4868.4    0.12       0  4992.9    0.07       0
  4996.9    0.12       0  5084.1    0.16       0
Bank Sta=4992.9,4996.9
Exp/Cntr=0.3,0.1

Type RM Length L Ch R = 1,861,0,0,0
BEGIN DESCRIPTION:
HERDS BRANCH TRIB 2 4 0
END DESCRIPTION:
XS GIS Cut Line= 4
      3492348.17     10418406.61      3492452.33     10418111.49
      3492401.98     10417906.63      3492098.14     10417884.06
#Sta/Elev= 30
  4532.7  418.55  4569.8  418.22  4587.6  417.54  4592.9  417.83  4612.2  417.10
  4737.0  415.12  4773.2  415.20  4824.3  416.37  4848.2  416.15  4886.7  414.87
  4979.4  413.95  4994.9  412.22  5000.0  411.33  5008.3  411.15  5008.5  410.65
  5012.0  410.65  5012.3  411.15  5020.6  411.55  5030.4  413.34  5041.2  413.95
  5059.1  413.57  5176.8  414.82  5186.6  414.58  5196.9  412.92  5206.9  412.88
  5216.9  414.43  5227.0  415.16  5270.5  415.85  5324.3  417.09  5361.3  417.32
#Mann=5,-1,0
  4532.7    0.16       0  4994.9    0.12       0  5008.3    0.07       0
  5012.3    0.12       0  5270.5    0.16       0
Bank Sta=5008.3,5012.3
Exp/Cntr=0.3,0.1

Chan Stop Cuts=-1