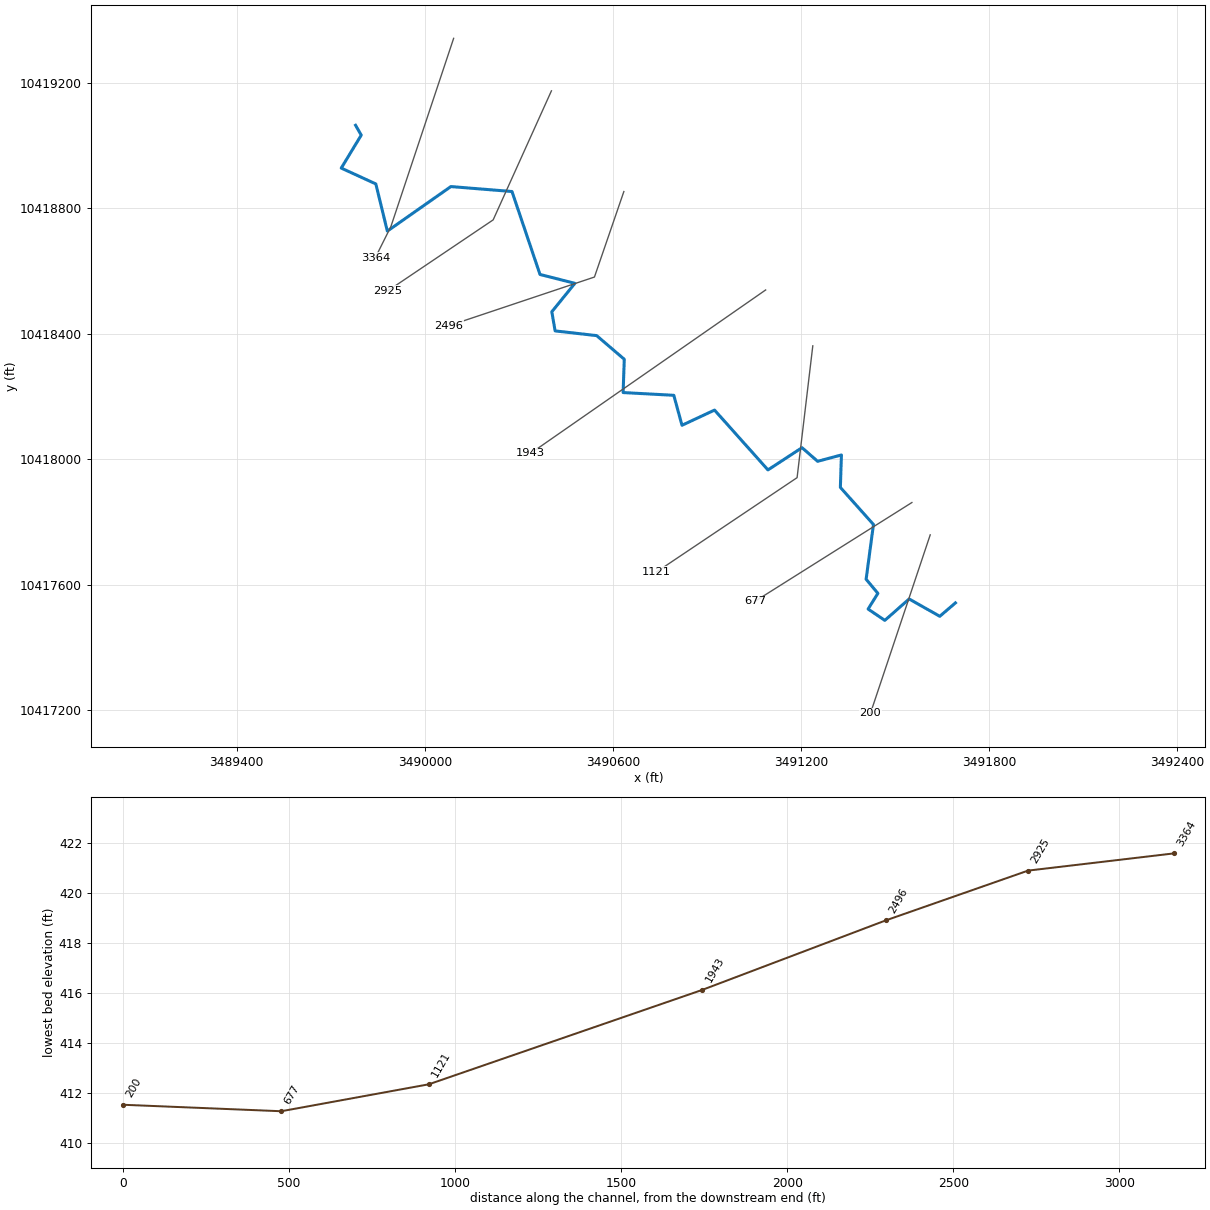
--- HERDS BRANCH TRIB 3.prj (project) ---

Proj Title=HERDS BRANCH TRIB 3 Base Level Engineering
Current Plan=p01
Default Exp/Contr=0.3,0.1
English Units
Geom File=g01
Flow File=f01
Plan File=p01
BEGIN DESCRIPTION:
HERDS BRANCH TRIB 3
END DESCRIPTION:

--- HERDS BRANCH TRIB 3.p01 (plan) ---

Plan Title=Multiple Run
Short Identifier=Multiple
Geom File=g01
Flow File=f01
Subcritical Flow
K Sum by GR= 0
Std Step Tol= 0.01
Critical Tol= 0.01
Num of Std Step Trials= 20
Max Error Tol= 0.3
Flow Tol Ratio= 0.001
Split Flow NTrial= 30
Split Flow Tol= 0.02
Split Flow Ratio= 0.02
Log Output Level= 0
Friction Slope Method= 1
Unsteady Friction Slope Method= 2
Unsteady Bridges Friction Slope Method= 1
Parabolic Critical Depth
Global Vel Dist=  1 , 1 , 1
Global Log Level= 0
CheckData=True
Encroach Param= -1, 0, 0, 0
BEGIN DESCRIPTION:
Multiple Run
END DESCRIPTION:

--- HERDS BRANCH TRIB 3.f01 (steady flow) ---

Flow Title=Multiple
Number of Profiles=7
Profile Names=10-year,25-year,50-year,1pct_min,100-year,1pct_plu,500-year
River Rch & RM= HERDS BRANCH TRI,Reach-1,3364
     559     746     895     786    1063    1438    1493
Boundary for River Rch & Prof#=HERDS BRANCH TRI,Reach-1,1
Up Type=0
Dn Type=3
Dn Slope=0.005
Boundary for River Rch & Prof#=HERDS BRANCH TRI,Reach-1,2
Up Type=0
Dn Type=3
Dn Slope=0.005
Boundary for River Rch & Prof#=HERDS BRANCH TRI,Reach-1,3
Up Type=0
Dn Type=3
Dn Slope=0.005
Boundary for River Rch & Prof#=HERDS BRANCH TRI,Reach-1,4
Up Type=0
Dn Type=3
Dn Slope=0.005
Boundary for River Rch & Prof#=HERDS BRANCH TRI,Reach-1,5
Up Type=0
Dn Type=3
Dn Slope=0.005
Boundary for River Rch & Prof#=HERDS BRANCH TRI,Reach-1,6
Up Type=0
Dn Type=3
Dn Slope=0.005
Boundary for River Rch & Prof#=HERDS BRANCH TRI,Reach-1,7
Up Type=0
Dn Type=3
Dn Slope=0.005

--- HERDS BRANCH TRIB 3.g01 (geometry) ---

Geom Title=Existing Conditions

River Reach=HERDS BRANCH TRI,Reach-1
Reach XY= 30
      3489779.40     10419064.42      3489797.52     10419033.05
      3489733.82     10418927.95      3489844.04     10418877.47
      3489880.74     10418727.05      3490083.34     10418869.06
      3490278.18     10418853.28      3490367.47     10418588.84
      3490478.72     10418560.53      3490405.20     10418469.92
      3490415.64     10418408.87      3490548.16     10418393.83
      3490636.18     10418318.42      3490632.52     10418212.26
      3490794.09     10418203.50      3490820.25     10418107.93
      3490924.01     10418156.37      3491094.34     10417965.60
      3491202.88     10418036.52      3491252.65     10417992.98
      3491328.55     10418013.30      3491325.19     10417909.87
      3491430.74     10417791.55      3491407.28     10417617.06
      3491444.83     10417572.11      3491413.61     10417521.98
      3491466.96     10417485.91      3491544.54     10417554.09
      3491642.13     10417498.87      3491692.11     10417541.64

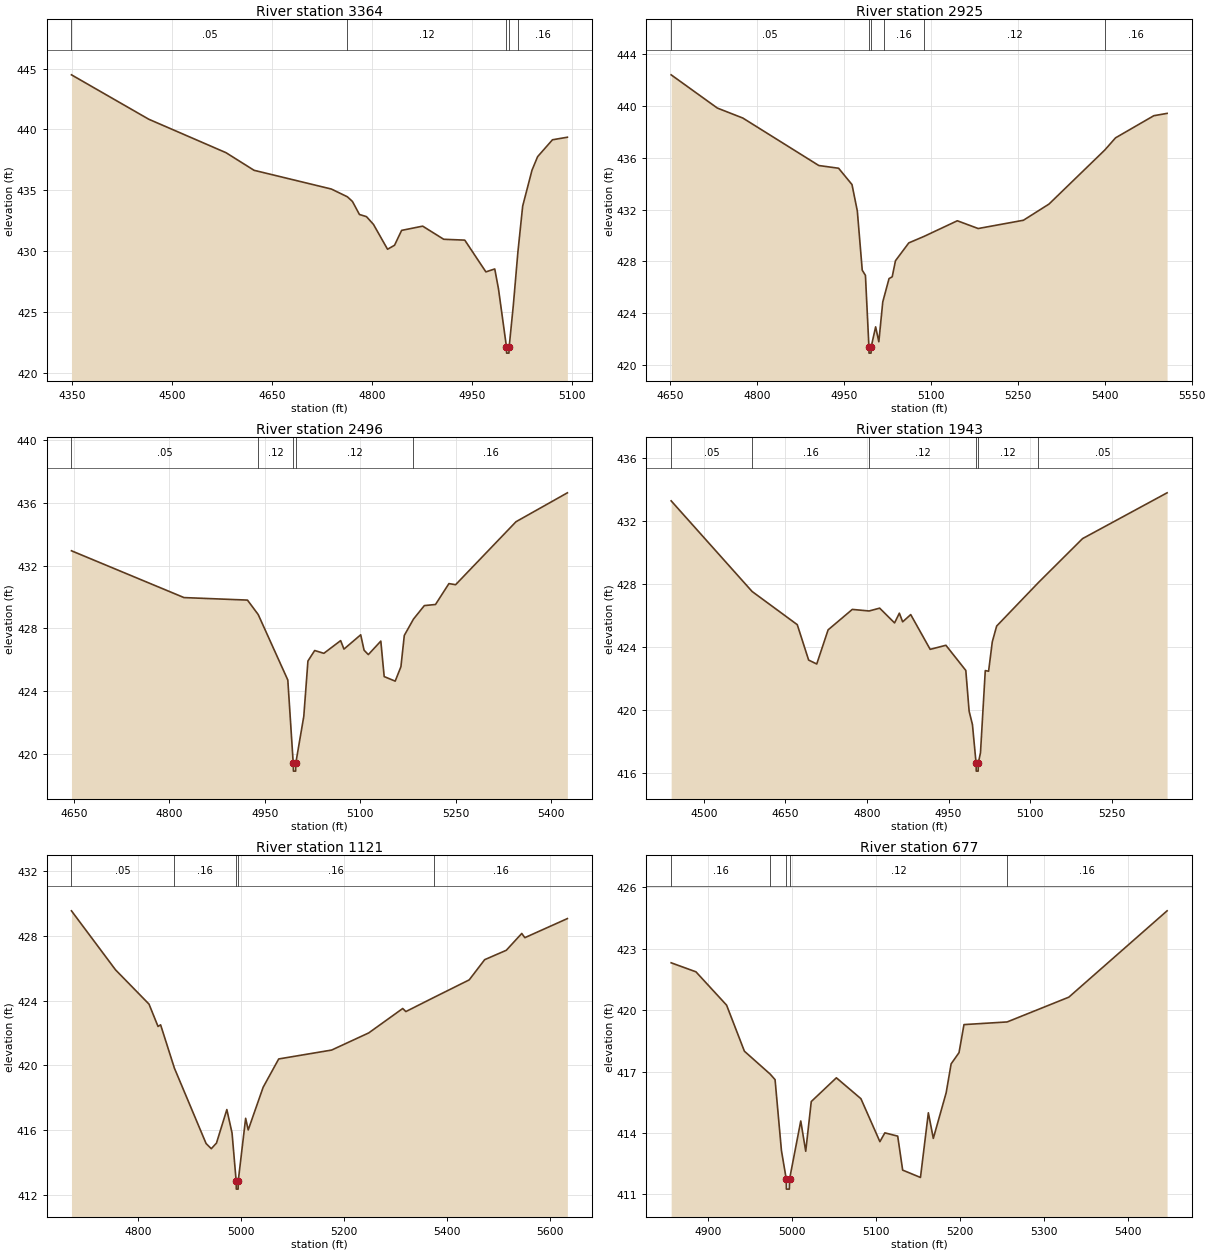
Type RM Length L Ch R = 1,3364,439,439,439
BEGIN DESCRIPTION:
HERDS BRANCH TRIB 3 8 0
END DESCRIPTION:
XS GIS Cut Line= 3
      3490092.12     10419341.68      3489892.11     10418741.64
      3489842.11     10418641.65
#Sta/Elev= 30
  4349.1  444.48  4465.1  440.83  4581.0  438.08  4623.2  436.63  4739.2  435.09
  4763.3  434.45  4770.8  434.07  4781.3  433.00  4791.9  432.82  4802.4  432.18
  4823.5  430.14  4834.0  430.47  4844.6  431.69  4876.2  432.04  4907.8  430.96
  4939.4  430.89  4971.1  428.28  4984.4  428.52  4990.0  426.88  5002.0  422.10
  5002.2  421.60  5005.7  421.60  5006.0  422.10  5012.3  425.55  5019.1  429.89
  5026.3  433.69  5040.3  436.64  5048.7  437.75  5071.0  439.14  5093.4  439.35
#Mann=5,-1,0
  4349.1    0.05       0  4763.3    0.12       0  5002.0    0.07       0
  5006.0    0.12       0  5019.1    0.16       0
Bank Sta=5002,5006
Exp/Cntr=0.3,0.1

Type RM Length L Ch R = 1,2925,429,429,429
BEGIN DESCRIPTION:
HERDS BRANCH TRIB 3 7 0
END DESCRIPTION:
XS GIS Cut Line= 3
      3490403.94     10419174.31      3490218.19     10418762.88
      3489883.13     10418537.19
#Sta/Elev= 30
  4652.2  442.42  4731.9  439.85  4775.8  439.08  4906.9  435.41  4941.0  435.20
  4964.1  433.94  4973.3  431.90  4981.8  427.32  4987.3  426.92  4993.3  421.41
  4993.5  420.91  4997.0  420.91  4997.3  421.41  5004.9  422.94  5010.4  421.79
  5017.2  424.87  5019.3  425.22  5028.0  426.67  5033.5  426.81  5039.1  428.05
  5062.1  429.43  5088.3  429.93  5145.8  431.14  5181.8  430.54  5259.8  431.18
  5303.9  432.43  5400.2  436.61  5418.7  437.55  5484.7  439.26  5507.6  439.44
#Mann=6,-1,0
  4652.2    0.05       0  4993.3   0.035       0  4997.3    0.05       0
  5019.3    0.16       0  5088.3    0.12       0  5400.2    0.16       0
Bank Sta=4993.3,4997.3
Exp/Cntr=0.3,0.1

Type RM Length L Ch R = 1,2496,553,553,553
BEGIN DESCRIPTION:
HERDS BRANCH TRIB 3 6 0
END DESCRIPTION:
XS GIS Cut Line= 3
      3490634.85     10418853.14      3490541.10     10418580.59
      3490075.59     10418424.84
#Sta/Elev= 30
  4646.2  432.94  4823.0  429.96  4922.7  429.80  4939.6  428.88  4986.1  424.71
  4994.6  419.41  4994.9  418.91  4998.4  418.91  4998.6  419.41  5011.2  422.40
  5017.7  425.92  5028.3  426.59  5042.7  426.41  5069.1  427.22  5074.3  426.68
  5100.6  427.59  5105.9  426.61  5112.6  426.33  5132.2  427.19  5137.5  424.93
  5154.8  424.64  5163.8  425.56  5169.1  427.55  5183.5  428.59  5200.6  429.45
  5218.1  429.52  5239.2  430.85  5249.7  430.78  5344.6  434.79  5425.3  436.63
#Mann=5,-1,0
  4646.2    0.05       0  4939.6    0.12       0  4994.6    0.07       0
  4998.6    0.12       0  5183.5    0.16       0
Bank Sta=4994.6,4998.6
Exp/Cntr=0.3,0.1

Type RM Length L Ch R = 1,1943,822,822,822
BEGIN DESCRIPTION:
HERDS BRANCH TRIB 3 5 0
END DESCRIPTION:
XS GIS Cut Line= 2
      3491086.94     10418539.38      3490338.18     10418018.87
#Sta/Elev= 30
  4439.9  433.30  4588.7  427.54  4671.8  425.43  4692.7  423.18  4707.6  422.93
  4728.5  425.10  4773.0  426.40  4803.9  426.30  4823.3  426.48  4850.7  425.54
  4859.5  426.16  4865.6  425.61  4880.4  426.07  4916.2  423.86  4945.1  424.12
  4981.7  422.52  4987.8  419.93  4993.9  419.08  5000.6  416.62  5000.9  416.12
  5004.4  416.12  5004.6  416.62  5008.7  417.29  5017.5  422.51  5023.6  422.47
  5030.4  424.34  5038.4  425.34  5115.3  428.11  5196.4  430.90  5351.8  433.81
#Mann=6,-1,0
  4439.9    0.05       0  4588.7    0.16       0  4803.9    0.12       0
  5000.6    0.07       0  5004.6    0.12       0  5115.3    0.05       0
Bank Sta=5000.6,5004.6
Exp/Cntr=0.3,0.1

Type RM Length L Ch R = 1,1121,444,444,444
BEGIN DESCRIPTION:
HERDS BRANCH TRIB 3 4 0
END DESCRIPTION:
XS GIS Cut Line= 3
      3491237.29     10418361.22      3491187.19     10417940.94
      3490739.04     10417640.32
#Sta/Elev= 30
  4671.3  429.55  4756.9  425.90  4821.9  423.78  4839.4  422.40  4844.4  422.50
  4871.2  419.82  4932.7  415.16  4942.8  414.84  4952.9  415.19  4973.0  417.26
  4983.1  415.81  4991.1  412.84  4991.4  412.34  4994.9  412.34  4995.1  412.84
  5009.5  416.72  5014.5  416.00  5043.5  418.64  5073.7  420.39  5176.5  420.94
  5248.5  422.00  5314.5  423.51  5320.6  423.32  5374.8  424.19  5443.6  425.28
  5473.6  426.53  5515.6  427.11  5545.6  428.15  5551.6  427.89  5634.2  429.07
#Mann=5,-1,0
  4671.3    0.05       0  4871.2    0.16       0  4991.1    0.07       0
  4995.1    0.16       0  5374.8    0.16       0
Bank Sta=4991.1,4995.1
Exp/Cntr=0.3,0.1

Type RM Length L Ch R = 1,677,477,477,477
BEGIN DESCRIPTION:
Mapping XS b0e90997
END DESCRIPTION:
XS GIS Cut Line= 2
      3491553.25     10417861.62      3491053.61     10417547.09
#Sta/Elev= 30
  4856.2  422.32  4885.7  421.88  4922.2  420.25  4943.4  418.00  4974.1  416.88
  4979.9  416.61  4987.5  413.14  4993.2  411.76  4993.4  411.26  4996.9  411.26
  4997.2  411.76  5010.5  414.59  5016.4  413.11  5023.0  415.54  5052.9  416.70
  5082.1  415.68  5104.7  413.58  5110.6  414.01  5125.9  413.85  5131.8  412.19
  5153.0  411.83  5162.4  414.99  5168.3  413.74  5183.6  415.97  5189.5  417.38
  5198.9  417.93  5204.8  419.30  5256.2  419.43  5329.6  420.64  5446.6  424.86
#Mann=5,-1,0
  4856.2    0.16       0  4974.1    0.12       0  4993.2    0.07       0
  4997.2    0.12       0  5256.2    0.16       0
Bank Sta=4993.2,4997.2
Exp/Cntr=0.3,0.1

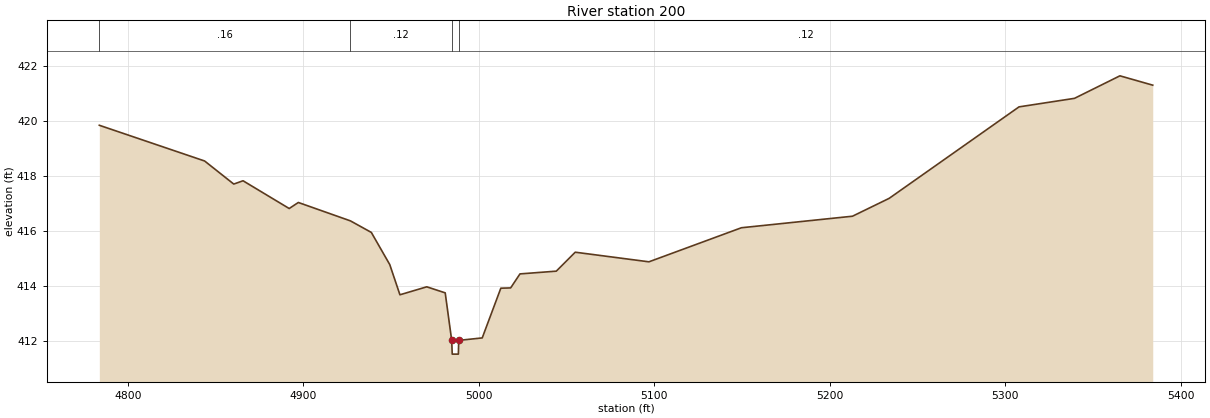
Type RM Length L Ch R = 1,200,0,0,0
BEGIN DESCRIPTION:
HERDS BRANCH TRIB 3 1 0
END DESCRIPTION:
XS GIS Cut Line= 2
      3491611.67     10417758.58      3491421.00     10417189.36
#Sta/Elev= 30
  4783.8  419.85  4843.8  418.55  4860.4  417.71  4865.7  417.83  4892.0  416.82
  4897.2  417.04  4926.9  416.37  4938.8  415.95  4949.3  414.78  4955.1  413.68
  4970.4  413.97  4980.9  413.75  4984.6  412.02  4984.9  411.52  4988.4  411.52
  4988.6  412.02  5002.0  412.11  5012.6  413.92  5018.2  413.93  5023.5  414.44
  5044.2  414.54  5055.0  415.23  5097.0  414.88  5149.7  416.12  5213.0  416.54
  5233.9  417.19  5307.9  420.52  5339.5  420.83  5365.4  421.65  5384.1  421.31
#Mann=4,-1,0
  4783.8    0.16       0  4926.9    0.12       0  4984.6    0.07       0
  4988.6    0.12       0
Bank Sta=4984.6,4988.6
Exp/Cntr=0.3,0.1

Chan Stop Cuts=-1