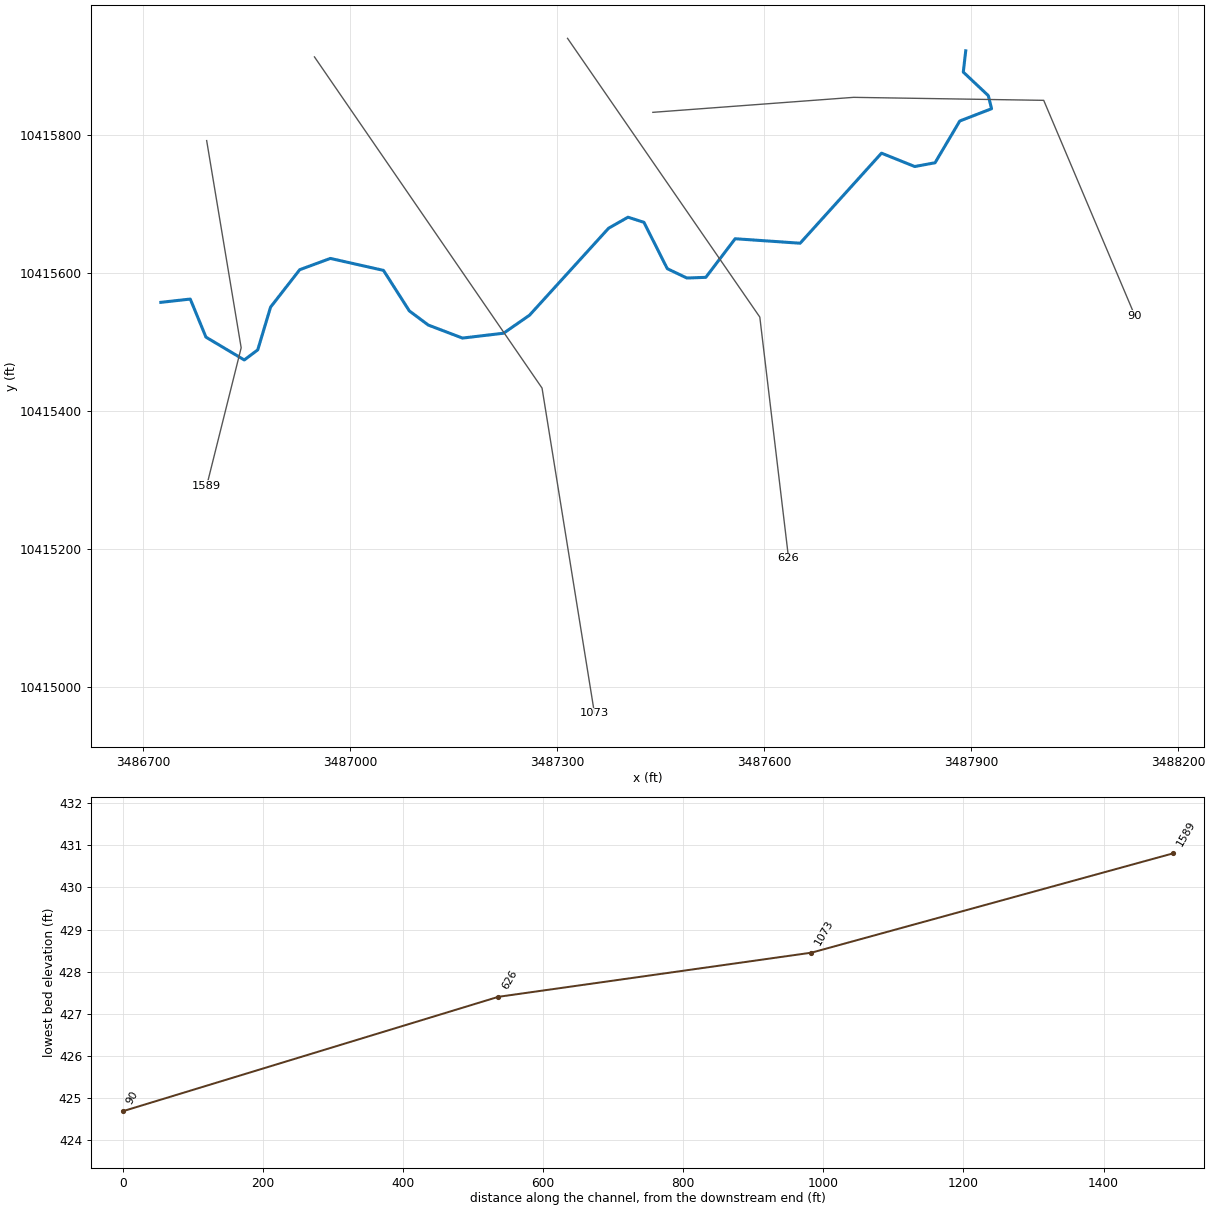
--- HERDS BRANCH TRIB 5.prj (project) ---

Proj Title=HERDS BRANCH TRIB 5 Base Level Engineering
Current Plan=p01
Default Exp/Contr=0.3,0.1
English Units
Geom File=g01
Flow File=f01
Plan File=p01
BEGIN DESCRIPTION:
HERDS BRANCH TRIB 5
END DESCRIPTION:

--- HERDS BRANCH TRIB 5.p01 (plan) ---

Plan Title=Multiple Run
Short Identifier=Multiple
Geom File=g01
Flow File=f01
Subcritical Flow
K Sum by GR= 0
Std Step Tol= 0.01
Critical Tol= 0.01
Num of Std Step Trials= 20
Max Error Tol= 0.3
Flow Tol Ratio= 0.001
Split Flow NTrial= 30
Split Flow Tol= 0.02
Split Flow Ratio= 0.02
Log Output Level= 0
Friction Slope Method= 1
Unsteady Friction Slope Method= 2
Unsteady Bridges Friction Slope Method= 1
Parabolic Critical Depth
Global Vel Dist=  1 , 1 , 1
Global Log Level= 0
CheckData=True
Encroach Param= -1, 0, 0, 0
BEGIN DESCRIPTION:
Multiple Run
END DESCRIPTION:

--- HERDS BRANCH TRIB 5.f01 (steady flow) ---

Flow Title=Multiple
Number of Profiles=7
Profile Names=10-year,25-year,50-year,1pct_min,100-year,1pct_plu,500-year
River Rch & RM= HERDS BRANCH TRI,Reach-1,1589
     615     828    1000     883    1194    1615    1696
Boundary for River Rch & Prof#=HERDS BRANCH TRI,Reach-1,1
Up Type=0
Dn Type=3
Dn Slope=0.005
Boundary for River Rch & Prof#=HERDS BRANCH TRI,Reach-1,2
Up Type=0
Dn Type=3
Dn Slope=0.005
Boundary for River Rch & Prof#=HERDS BRANCH TRI,Reach-1,3
Up Type=0
Dn Type=3
Dn Slope=0.005
Boundary for River Rch & Prof#=HERDS BRANCH TRI,Reach-1,4
Up Type=0
Dn Type=3
Dn Slope=0.005
Boundary for River Rch & Prof#=HERDS BRANCH TRI,Reach-1,5
Up Type=0
Dn Type=3
Dn Slope=0.005
Boundary for River Rch & Prof#=HERDS BRANCH TRI,Reach-1,6
Up Type=0
Dn Type=3
Dn Slope=0.005
Boundary for River Rch & Prof#=HERDS BRANCH TRI,Reach-1,7
Up Type=0
Dn Type=3
Dn Slope=0.005

--- HERDS BRANCH TRIB 5.g01 (geometry) ---

Geom Title=Existing Conditions

River Reach=HERDS BRANCH TRI,Reach-1
Reach XY= 30
      3486725.71     10415557.44      3486768.35     10415562.20
      3486791.09     10415507.05      3486846.62     10415474.01
      3486866.14     10415488.66      3486884.72     10415550.51
      3486926.96     10415604.70      3486971.39     10415621.04
      3487048.33     10415603.72      3487085.79     10415545.05
      3487113.25     10415524.57      3487162.84     10415505.70
      3487222.39     10415512.75      3487259.89     10415538.74
      3487374.58     10415664.79      3487402.74     10415680.71
      3487425.78     10415673.30      3487459.64     10415606.16
      3487487.99     10415592.66      3487515.46     10415593.66
      3487558.00     10415649.54      3487652.16     10415643.05
      3487770.06     10415773.45      3487818.20     10415754.10
      3487847.65     10415759.56      3487883.49     10415820.03
      3487929.55     10415837.81      3487924.85     10415856.72
      3487888.59     10415890.84      3487892.11     10415921.64

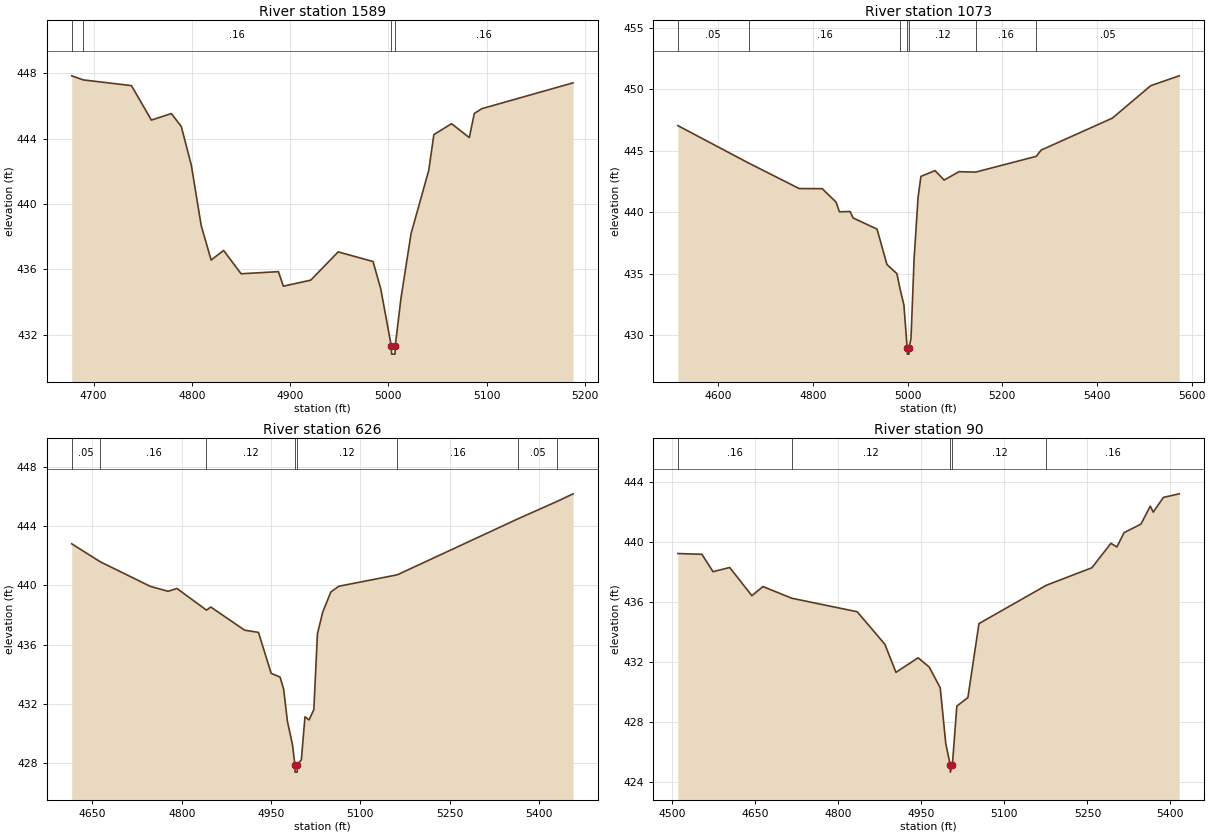
Type RM Length L Ch R = 1,1589,516,516,516
BEGIN DESCRIPTION:
HERDS BRANCH TRIB 5 4 0
END DESCRIPTION:
XS GIS Cut Line= 3
      3486792.10     10415791.66      3486842.11     10415491.64
      3486792.11     10415291.65
#Sta/Elev= 30
  4677.7  447.85  4689.5  447.60  4738.5  447.25  4758.8  445.14  4779.1  445.54
  4789.2  444.75  4799.4  442.39  4809.5  438.68  4819.6  436.57  4832.3  437.16
  4850.1  435.73  4888.1  435.86  4893.1  434.97  4921.0  435.34  4948.9  437.07
  4984.4  436.48  4992.2  434.82  5003.0  431.31  5003.3  430.81  5006.8  430.81
  5007.0  431.31  5012.8  434.22  5023.1  438.19  5041.1  442.06  5046.3  444.25
  5064.3  444.92  5082.4  444.07  5087.5  445.55  5095.2  445.84  5188.0  447.42
#Mann=4,-1,0
  4677.7    0.05       0  4689.5    0.16       0  5003.0    0.07       0
  5007.0    0.16       0
Bank Sta=5003,5007
Exp/Cntr=0.3,0.1

Type RM Length L Ch R = 1,1073,447,447,447
BEGIN DESCRIPTION:
HERDS BRANCH TRIB 5 3 0
END DESCRIPTION:
XS GIS Cut Line= 3
      3486948.30     10415912.83      3487278.14     10415433.27
      3487354.10     10414962.30
#Sta/Elev= 30
  4514.7  447.04  4664.4  443.99  4771.0  441.92  4819.6  441.91  4848.9  440.82
  4856.0  440.03  4878.7  440.05  4884.7  439.53  4935.5  438.62  4956.4  435.74
  4977.4  435.00  4984.6  433.67  4992.3  432.44  4999.1  428.95  4999.4  428.45
  5002.9  428.45  5003.1  428.95  5007.2  429.72  5013.8  436.21  5022.1  441.18
  5028.2  442.91  5057.9  443.38  5077.3  442.61  5108.5  443.29  5144.0  443.26
  5271.8  444.54  5282.2  445.05  5432.7  447.65  5513.7  450.29  5573.8  451.09
#Mann=7,-1,0
  4514.7    0.05       0  4664.4    0.16       0  4984.6    0.12       0
  4999.1    0.07       0  5003.1    0.12       0  5144.0    0.16       0
  5271.8    0.05       0
Bank Sta=4999.1,5003.1
Exp/Cntr=0.3,0.1

Type RM Length L Ch R = 1,626,536,536,536
BEGIN DESCRIPTION:
HERDS BRANCH TRIB 5 2 0
END DESCRIPTION:
XS GIS Cut Line= 3
      3487315.08     10415939.71      3487593.71     10415536.08
      3487635.38     10415187.12
#Sta/Elev= 30
  4615.2  442.79  4663.5  441.57  4747.3  439.92  4777.0  439.59  4791.9  439.78
  4841.5  438.32  4848.7  438.53  4905.5  436.97  4928.8  436.82  4950.1  434.06
  4965.0  433.81  4971.1  432.99  4977.4  430.83  4985.9  429.25  4990.0  427.90
  4990.3  427.40  4993.8  427.40  4994.0  427.90  5000.8  428.23  5006.9  431.13
  5013.8  430.92  5021.8  431.62  5027.8  436.72  5036.7  438.19  5050.3  439.54
  5063.7  439.93  5161.9  440.70  5364.8  444.48  5430.4  445.65  5457.1  446.16
#Mann=8,-1,0
  4615.2    0.05       0  4663.5    0.16       0  4841.5    0.12       0
  4990.0    0.07       0  4994.0    0.12       0  5161.9    0.16       0
  5364.8    0.05       0  5430.4    0.16       0
Bank Sta=4990,4994
Exp/Cntr=0.3,0.1

Type RM Length L Ch R = 1,90,0,0,0
BEGIN DESCRIPTION:
HERDS BRANCH TRIB 5 1 0
END DESCRIPTION:
XS GIS Cut Line= 4
      3487438.70     10415832.57      3487729.52     10415854.27
      3488005.13     10415849.93      3488137.29     10415537.95
#Sta/Elev= 30
  4509.8  439.25  4553.3  439.20  4573.4  438.04  4603.5  438.32  4643.6  436.44
  4663.6  437.05  4715.7  436.27  4834.0  435.37  4884.0  433.20  4904.0  431.33
  4944.0  432.30  4964.0  431.69  4984.0  430.30  4994.0  426.59  5002.0  425.18
  5002.3  424.68  5006.0  425.18  5014.0  429.08  5034.0  429.65  5054.0  434.58
  5176.0  437.14  5258.0  438.30  5292.5  439.93  5303.3  439.69  5316.2  440.64
  5346.7  441.21  5363.6  442.41  5369.0  442.01  5387.3  442.99  5415.9  443.23
#Mann=5,-1,0
  4509.8    0.16       0  4715.7    0.12       0  5002.0    0.07       0
  5006.0    0.12       0  5176.0    0.16       0
Bank Sta=5002,5006
Exp/Cntr=0.3,0.1

Chan Stop Cuts=-1