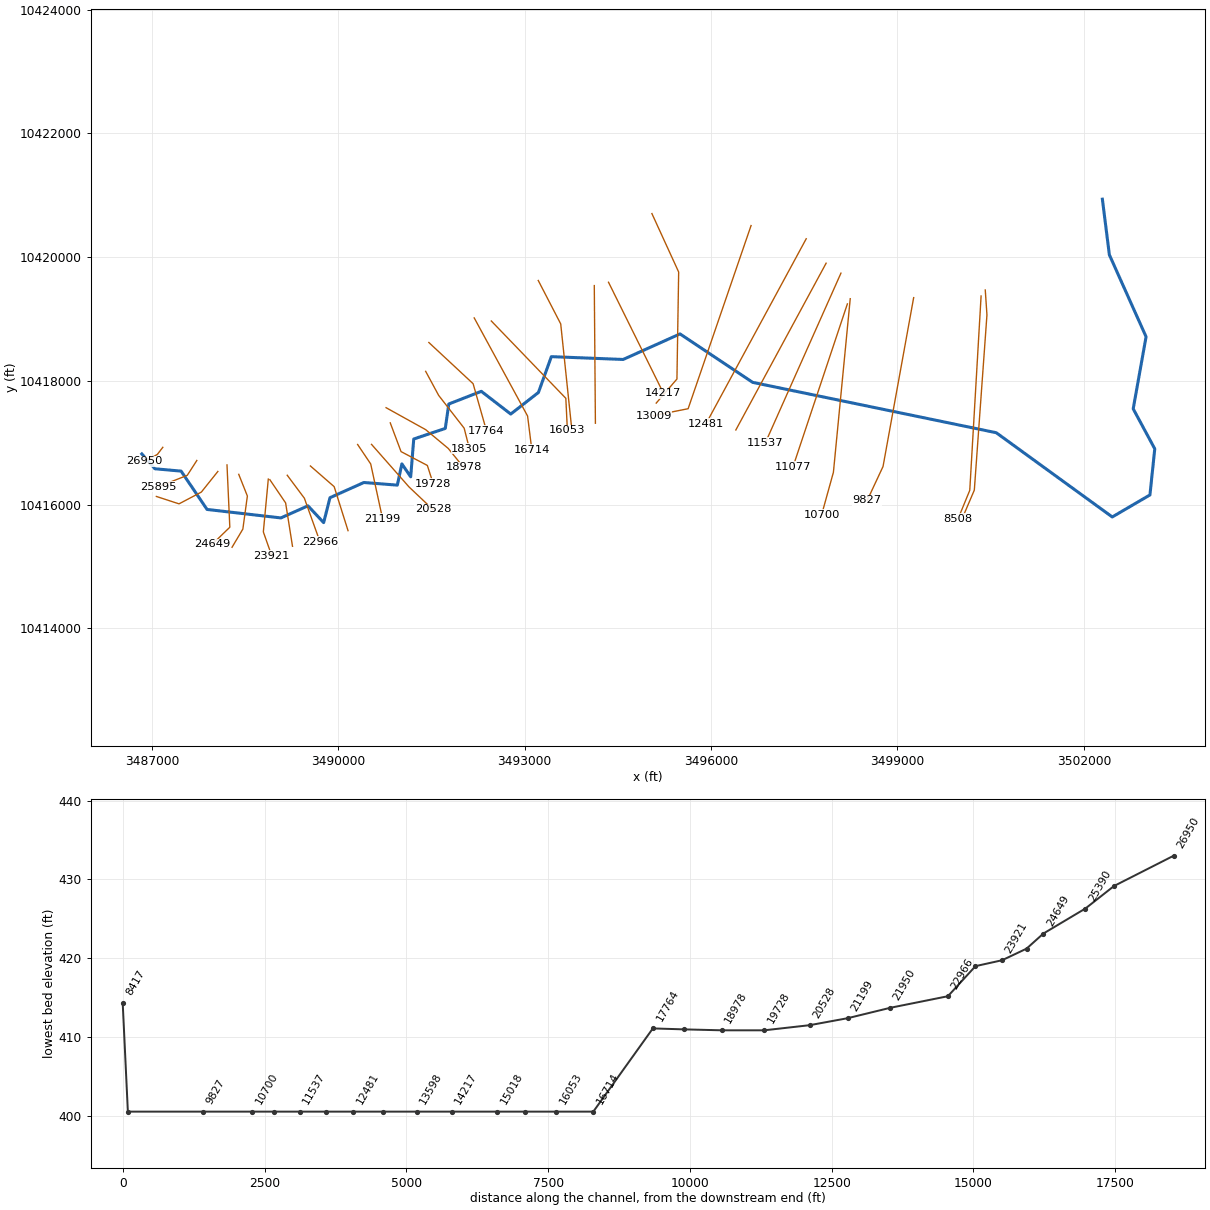
--- HERDS BRANCH.prj (project) ---

Proj Title=HERDS BRANCH Base Level Engineering
Current Plan=p01
Default Exp/Contr=0.3,0.1
English Units
Geom File=g01
Flow File=f01
Plan File=p01
Y Axis Title=Elevation
X Axis Title(PF)=Main Channel Distance
X Axis Title(XS)=Station
BEGIN DESCRIPTION:
HERDS BRANCH
END DESCRIPTION:
DSS Export Rating Curves= 0
DSS Export Rating Curve Sorted= 0
DSS Export Volume Flow Curves= 0
DXF OffsetX= 0
DXF OffsetY= 0
DXF ScaleX= 1
DXF ScaleY= 10

--- HERDS BRANCH.p01 (plan) ---

Plan Title=Multiple Run
Short Identifier=Multiple
Geom File=g01
Flow File=f01
Subcritical Flow
K Sum by GR= 0
Std Step Tol= 0.01
Critical Tol= 0.01
Num of Std Step Trials= 20
Max Error Tol= 0.3
Flow Tol Ratio= 0.001
Split Flow NTrial= 30
Split Flow Tol= 0.02
Split Flow Ratio= 0.02
Log Output Level= 0
Friction Slope Method= 1
Unsteady Friction Slope Method= 2
Unsteady Bridges Friction Slope Method= 1
Parabolic Critical Depth
Global Vel Dist=  1 , 1 , 1
Global Log Level= 0
CheckData=True
Encroach Param= -1, 0, 0, 0
BEGIN DESCRIPTION:
Multiple Run
END DESCRIPTION:

--- HERDS BRANCH.f01 (steady flow) ---

Flow Title=Multiple
Program Version=4.10
Number of Profiles= 7
Profile Names=10-year,25-year,50-year,1pct_min,100-year,1pct_plu,500-year
River Rch & RM=HERDS BRANCH,Reach-1         ,26950
     572     761     912     798    1080    1460    1509
River Rch & RM=HERDS BRANCH,Reach-1         ,24649
    1195    1658    2041    1830    2475    3347    3633
River Rch & RM=HERDS BRANCH,Reach-1         ,18305
    1494    2097    2602    2352    3180    4301    4742
River Rch & RM=HERDS BRANCH,Reach-1         ,16714
    1757    2473    3074    2779    3758    5082    5610
River Rch & RM=HERDS BRANCH,Reach-1         ,16053
    1757    2473    3074    2779    3758    5082    5610
River Rch & RM=HERDS BRANCH,Reach-1         ,11537
    2790    3995    5023    4585    6200    8385    9439
River Rch & RM=HERDS BRANCH,Reach-1         ,5137
    3608    5193    6550    5993    8105   10962   12398
Boundary for River Rch & Prof#=HERDS BRANCH,Reach-1         , 1
Up Type= 0
Dn Type= 3
Dn Slope=0.001
Boundary for River Rch & Prof#=HERDS BRANCH,Reach-1         , 2
Up Type= 0
Dn Type= 3
Dn Slope=0.001
Boundary for River Rch & Prof#=HERDS BRANCH,Reach-1         , 3
Up Type= 0
Dn Type= 3
Dn Slope=0.001
Boundary for River Rch & Prof#=HERDS BRANCH,Reach-1         , 4
Up Type= 0
Dn Type= 3
Dn Slope=0.001
Boundary for River Rch & Prof#=HERDS BRANCH,Reach-1         , 5
Up Type= 0
Dn Type= 3
Dn Slope=0.001
Boundary for River Rch & Prof#=HERDS BRANCH,Reach-1         , 6
Up Type= 0
Dn Type= 3
Dn Slope=0.001
Boundary for River Rch & Prof#=HERDS BRANCH,Reach-1         , 7
Up Type= 0
Dn Type= 3
Dn Slope=0.001
DSS Import GetInterval= 0
DSS Import GetPeak= 0
DSS Import FillOption= 0

--- HERDS BRANCH.g01 (geometry) ---

Geom Title=Existing Conditions
Program Version=4.10

River Reach=HERDS BRANCH    ,Reach-1
Reach XY= 30
      3486838.82     10416819.26      3487049.67     10416579.79
      3487471.31     10416541.38      3487888.67     10415922.23
      3489077.07     10415785.15      3489512.72     10415980.68
      3489765.37     10415709.27       3489866.9     10416111.99
      3490412.35     10416357.69      3490951.09     10416315.21
      3491023.77     10416659.02      3491166.08     10416449.97
      3491215.17     10417060.55      3491722.31     10417231.49
      3491779.52     10417626.31       3492302.4      10417830.9
      3492776.23     10417463.63      3493221.44     10417812.31
       3493429.6     10418391.48      3494585.06     10418345.95
      3495500.06     10418758.66      3496669.77     10417976.06
      3500589.62     10417162.11      3502456.58     10415800.83
       3503062.9     10416156.59      3503140.54     10416902.07
      3502793.47     10417548.34      3503000.67     10418712.83
      3502409.93     10420037.12      3502297.41     10420935.66

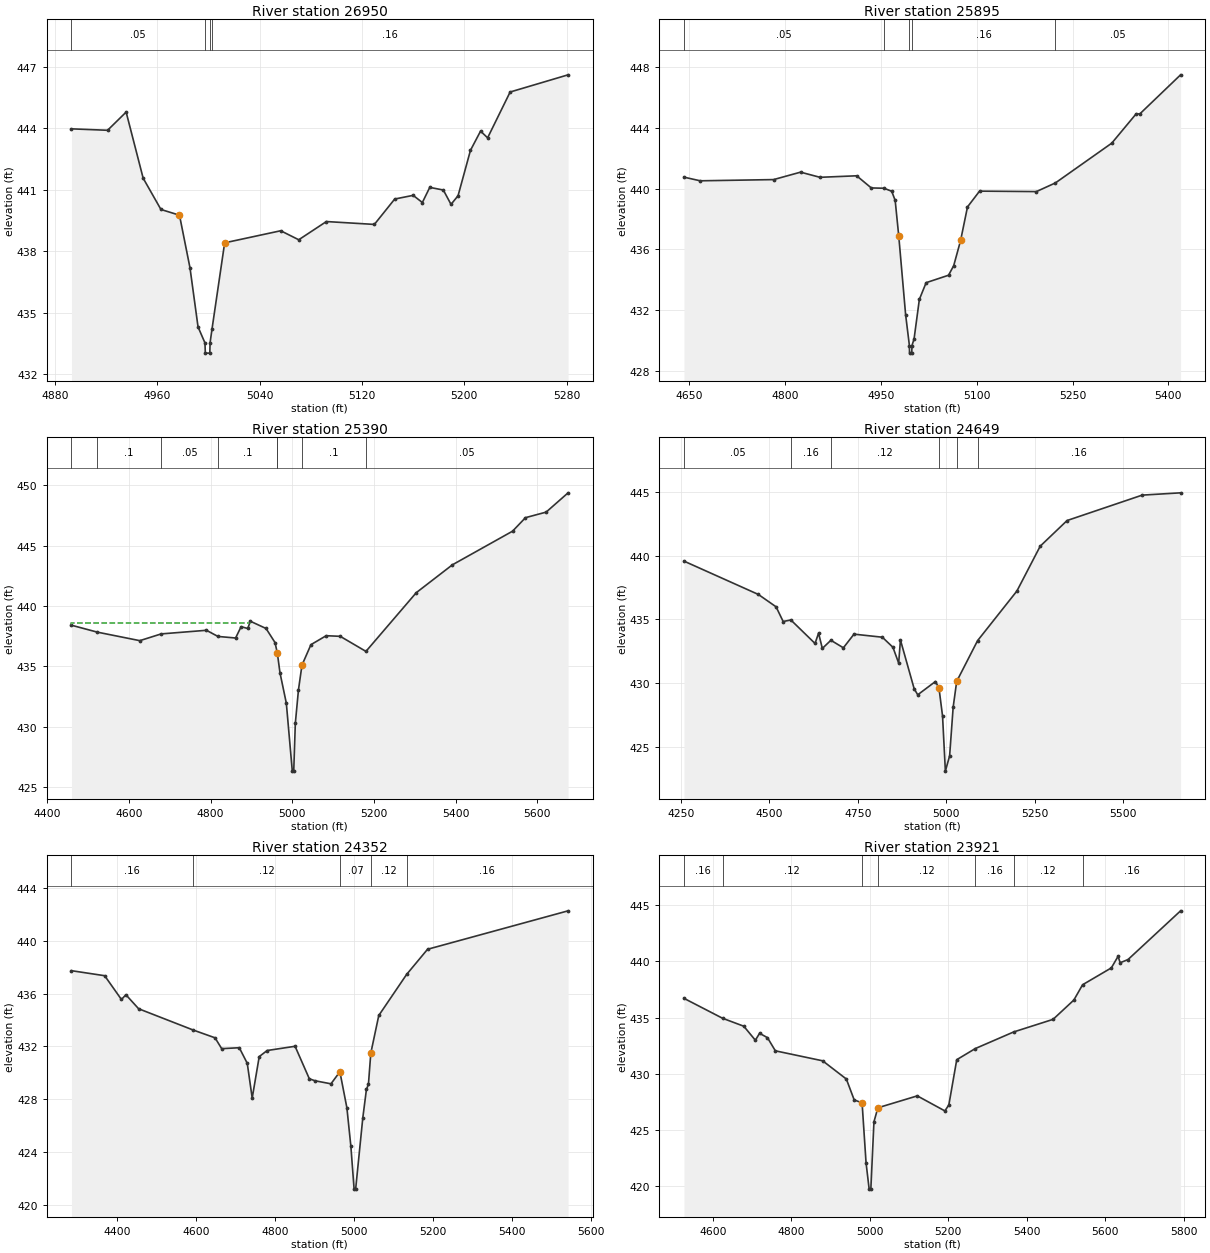
Type RM Length L Ch R = 1 ,26950   ,1055,1055,1055
BEGIN DESCRIPTION:
HERDS BRANCH 5 0
END DESCRIPTION:
XS GIS Cut Line= 4
      3487176.48     10416926.13      3487088.98     10416811.58
       3486965.7     10416741.59      3486872.61     10416699.42
#Sta/Elev= 30
    4893  443.98  4921.2  443.91  4935.7   444.8    4949  441.57  4962.9  440.04
  4977.4  439.76  4985.6  437.19  4991.9   434.3  4997.3  433.52  4997.6  433.02
  5001.1  433.02  5001.3  433.52  5002.8  434.19  5012.7  438.41  5056.5     439
  5070.6  438.56  5092.2  439.45  5129.7  439.31  5145.6  440.55    5160  440.73
  5167.2  440.38    5173  441.12  5183.6  440.99  5189.6  440.29  5195.1  440.71
  5204.8  442.93  5212.7  443.87  5218.2  443.54  5235.8  445.78  5281.1  446.62
#Mann= 4 ,-1 , 0
    4893     .05       0  4997.3    .035       0  5001.3     .05       0
  5002.8     .16       0
Bank Sta=4977.4,5012.7
XS Rating Curve= 0 ,0
Exp/Cntr=0.3,0.1

Type RM Length L Ch R = 1 ,25895   ,505,505,505
BEGIN DESCRIPTION:
HERDS BRANCH 4 0
END DESCRIPTION:
XS GIS Cut Line= 3
      3487723.91     10416713.16      3487570.27     10416473.58
       3487111.9     10416291.28
#Sta/Elev= 30
  4641.4  440.75  4666.8  440.51  4781.8  440.59    4824  441.08  4854.4  440.74
  4911.9  440.84  4934.8  440.04  4954.7  440.02  4966.8  439.82  4972.2  439.22
  4977.8  436.88  4988.6  431.68  4994.5  429.66  4994.7  429.16  4998.2  429.16
  4998.5  429.66  5001.8  430.09  5010.1   432.7  5020.7   433.8  5055.8  434.29
  5063.9  434.92  5074.7  436.58  5085.5  438.79  5104.4  439.83  5193.4   439.8
  5223.2  440.37  5311.5  442.99  5349.9  444.93  5355.3  444.91  5419.3  447.49
#Mann= 5 ,-1 , 0
  4641.4     .05       0  4954.7     .16       0  4994.5     .07       0
  4998.5     .16       0  5223.2     .05       0
Bank Sta=4977.8,5074.7
XS Rating Curve= 0 ,0
Exp/Cntr=0.3,0.1

Type RM Length L Ch R = 1 ,25390   ,741,741,741
BEGIN DESCRIPTION:
HERDS BRANCH 38 0
END DESCRIPTION:
XS GIS Cut Line= 4
      3488062.44     10416536.06      3487796.83     10416202.75
      3487437.46     10416012.65      3487072.89     10416132.43
#Sta/Elev= 30
  4459.1   438.4  4521.9  437.83  4626.4  437.12  4678.8  437.68  4789.7  437.98
  4817.8  437.47  4861.1  437.34  4874.6  438.28  4890.8  438.13  4897.3  438.73
  4935.7  438.13  4957.7  436.96  4963.4  436.08  4969.8  434.46  4985.4  431.93
    5000   426.3  5003.5   426.3  5007.4  430.26  5015.1  433.04  5023.7  435.09
  5045.7  436.79    5083  437.53  5117.4  437.48  5180.4  436.23  5303.7   441.1
  5392.2  443.41  5539.6   446.2  5571.2  447.32  5621.8  447.78  5675.6  449.38
#Mann= 8 ,-1 , 0
  4459.1     .05       0  4521.9      .1       0  4678.8     .05       0
  4817.8      .1       0  4963.4     .12       0  4963.4     .05       0
  5023.7      .1       0  5180.4     .05       0
#XS Ineff= 2 , 0
         4898.07  438.61
Permanent Ineff=
       F       F
Bank Sta=4963.4,5023.7
XS Rating Curve= 0 ,0
Exp/Cntr=0.3,0.1

Type RM Length L Ch R = 1 ,24649   ,297,297,297
BEGIN DESCRIPTION:
HERDS BRANCH 36 0
END DESCRIPTION:
XS GIS Cut Line= 3
      3488209.64     10416641.65      3488255.17     10415635.04
       3487971.3     10415358.99
#Sta/Elev= 30
  4258.9  439.57  4469.1  436.96  4519.2  435.99  4539.2  434.84    4561  434.96
  4629.3  433.12  4639.3  433.93  4649.9  432.73  4674.1  433.37  4709.4  432.78
  4739.4  433.85  4819.5  433.61  4849.5  432.82  4865.7  431.58  4870.7  433.39
  4909.6  429.56  4919.6   429.1  4969.6  430.14  4979.6  429.63  4989.7  427.44
  4997.7  423.12  5009.7  424.32  5019.7  428.13  5029.7  430.15  5088.7  433.34
  5199.9  437.23  5265.7  440.74  5341.7  442.75  5553.9  444.74  5662.5  444.92
#Mann= 6 ,-1 , 0
  4258.9     .05       0    4561     .16       0  4674.1     .12       0
  4979.6     .07       0  5029.7     .12       0  5088.7     .16       0
Bank Sta=4979.6,5029.7
XS Rating Curve= 0 ,0
Exp/Cntr=0.3,0.1

Type RM Length L Ch R = 1 ,24352   ,431,431,431
BEGIN DESCRIPTION:
HERDS BRANCH 37 0
END DESCRIPTION:
XS GIS Cut Line= 4
      3488398.74     10416489.73      3488537.63     10416139.04
      3488464.72     10415604.31      3488290.78     10415311.08
#Sta/Elev= 30
  4283.6  437.73  4367.6  437.35  4410.1  435.55  4421.4  435.91  4453.6  434.85
  4591.8  433.24  4647.2  432.65    4664  431.83  4708.6   431.9  4728.8  430.72
  4741.3  428.09  4759.1  431.23  4779.3  431.69  4849.9  432.01    4886  429.55
  4900.4   429.4  4940.8  429.17  4963.4  430.08  4981.1  427.36  4991.2  424.45
  4999.4   421.2  5003.3   421.2  5021.5  426.61  5030.6  428.74  5035.7  429.13
  5041.7  431.49  5061.9  434.34  5132.5  437.45  5185.4  439.35  5541.4  442.26
#Mann= 5 ,-1 , 0
  4283.6     .16       0  4591.8     .12       0  4963.4     .07       0
  5041.7     .12       0  5132.5     .16       0
Bank Sta=4963.4,5041.7
XS Rating Curve= 0 ,0
Exp/Cntr=0.3,0.1

Type RM Length L Ch R = 1 ,23921   ,469,469,469
BEGIN DESCRIPTION:
HERDS BRANCH 35 0
END DESCRIPTION:
XS GIS Cut Line= 3
      3488874.43      10416413.3      3488794.58     10415559.18
      3488929.47     10415175.24
#Sta/Elev= 30
  4526.8  436.71  4624.9  434.94  4679.1  434.23  4708.6  432.98  4719.3   433.6
  4739.4  433.21  4759.5  432.04    4880  431.15  4940.3  429.53  4960.3  427.67
  4980.4  427.41  4990.5  422.08  4998.4  419.73  5002.7  419.73  5010.6  425.72
  5020.6  426.97    5121  428.03  5191.3  426.69  5201.4  427.23  5221.5  431.25
  5268.7  432.24  5366.5  433.72  5466.8  434.84  5519.8  436.56    5542  437.92
  5615.2  439.42  5632.4  440.45  5637.7  439.88  5657.6  440.16  5791.6   444.5
#Mann= 7 ,-1 , 0
  4526.8     .16       0  4624.9     .12       0  4980.4     .07       0
  5020.6     .12       0  5268.7     .16       0  5366.5     .12       0
    5542     .16       0
Bank Sta=4980.4,5020.6
XS Rating Curve= 0 ,0
Exp/Cntr=0.3,0.1

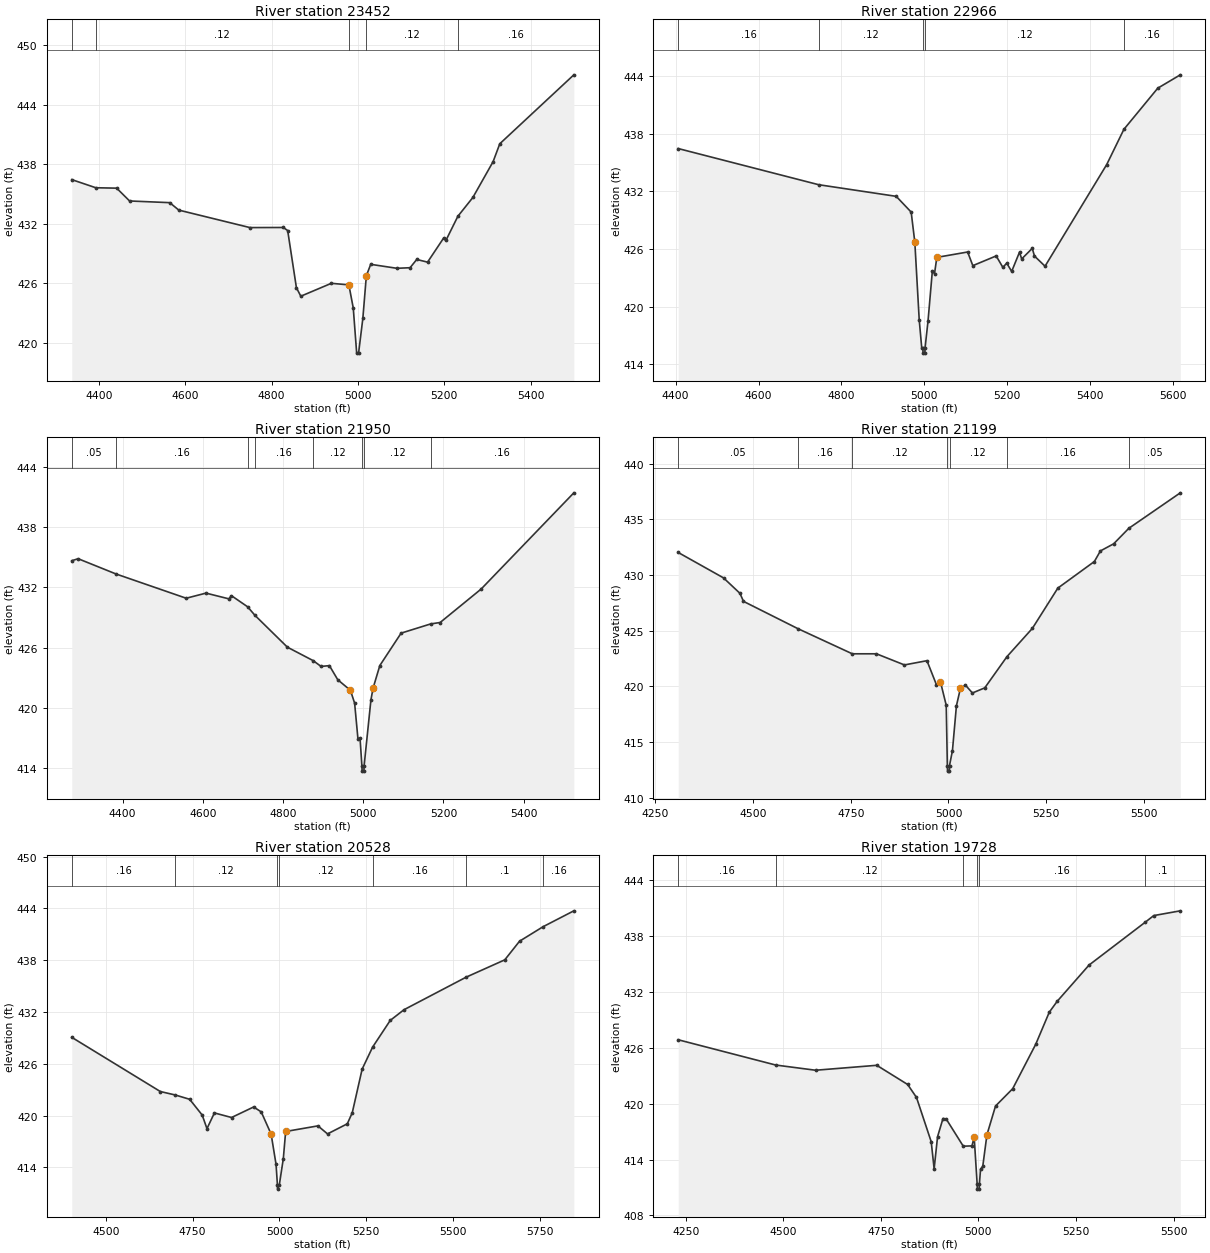
Type RM Length L Ch R = 1 ,23452   ,486,486,486
BEGIN DESCRIPTION:
HERDS BRANCH 35 1
END DESCRIPTION:
XS GIS Cut Line= 3
       3488899.2     10416403.36      3489153.14     10416027.88
      3489263.81     10415326.95
#Sta/Elev= 30
  4337.1  436.45  4392.8  435.63  4441.1  435.59    4471   434.3    4564  434.13
    4585  433.38  4749.8  431.62  4827.1  431.63  4837.2  431.32  4857.4  425.57
  4867.6  424.71  4938.4  426.01  4978.9  425.85  4989.1  423.52    4997  418.98
  5001.4  418.98  5011.3  422.48  5019.4  426.77  5029.5  427.92  5090.3  427.52
  5120.7  427.58  5136.1  428.41  5161.2  428.14  5198.6  430.58  5203.6  430.32
  5231.4  432.76  5266.1  434.65    5313  438.26  5328.5  440.06    5500     447
#Mann= 5 ,-1 , 0
  4337.1     .16       0  4392.8     .12       0  4978.9     .07       0
  5019.4     .12       0  5231.4     .16       0
Bank Sta=4978.9,5019.4
XS Rating Curve= 0 ,0
Exp/Cntr=0.3,0.1

Type RM Length L Ch R = 1 ,22966   ,1016,1016,1016
BEGIN DESCRIPTION:
HERDS BRANCH 34 0
END DESCRIPTION:
XS GIS Cut Line= 3
      3489179.19     10416474.91      3489454.78     10416103.84
      3489706.52     10415398.54
#Sta/Elev= 30
  4406.3  436.44    4745  432.68  4932.1  431.47  4968.2  429.83    4977   426.7
  4987.6  418.62  4993.7  415.69  4996.4  415.66  4996.8  415.16  5001.2  415.16
  5001.6  415.66  5008.9  418.53  5019.2  423.67  5024.5  423.43  5030.1  425.12
  5104.4  425.68  5116.9  424.26  5173.2  425.27  5189.4  424.08  5198.7  424.52
  5210.6  423.66  5229.5  425.66  5234.8  424.96  5260.3  426.06  5265.6  425.26
  5291.1   424.2  5439.8  434.77  5481.3  438.44    5563  442.72  5617.4  444.11
#Mann= 5 ,-1 , 0
  4406.3     .16       0    4745     .12       0  4996.4     .07       0
  5001.6     .12       0  5481.3     .16       0
Bank Sta=4977,5030.1
XS Rating Curve= 0 ,0
Exp/Cntr=0.3,0.1

Type RM Length L Ch R = 1 ,21950   ,751,751,751
BEGIN DESCRIPTION:
HERDS BRANCH 33 0
END DESCRIPTION:
XS GIS Cut Line= 3
      3489552.41      10416624.7      3489934.39     10416290.47
      3490157.51     10415579.93
#Sta/Elev= 30
  4273.1  434.67    4289  434.87  4383.4  433.35  4558.5  430.93  4607.9  431.44
  4664.8  430.87  4671.5  431.18  4711.6  430.08  4730.1  429.22  4810.9  426.05
  4875.1  424.71  4894.9  424.13  4915.7  424.21  4936.6   422.8  4968.1  421.75
  4978.6  420.47  4986.9  416.91  4992.1     417  4996.8  414.19  4997.3  413.69
  5001.8  413.69  5002.2  414.19  5019.3   420.8  5024.6  421.96  5041.5  424.22
  5094.6  427.45  5168.5  428.37  5191.9  428.51  5294.3  431.85  5525.4  441.44
#Mann= 8 ,-1 , 0
  4273.1     .05       0  4383.4     .16       0  4711.6     .12       0
  4730.1     .16       0  4875.1     .12       0  4996.8     .07       0
  5002.2     .12       0  5168.5     .16       0
Bank Sta=4968.1,5024.6
XS Rating Curve= 0 ,0
Exp/Cntr=0.3,0.1

Type RM Length L Ch R = 1 ,21199   ,671,671,671
BEGIN DESCRIPTION:
HERDS BRANCH 31 0
END DESCRIPTION:
XS GIS Cut Line= 3
      3490312.01     10416971.86      3490522.49     10416657.22
      3490713.46     10415771.83
#Sta/Elev= 30
  4308.7  432.01  4424.5  429.73  4466.6  428.34  4475.6  427.62  4614.7  425.17
  4753.9  422.91  4815.7  422.91  4887.3  421.91  4944.9  422.29  4969.2  420.13
  4979.4   420.4  4994.2  418.29  4997.1  412.87  4997.6  412.37  5002.2  412.37
  5002.6  412.87  5010.1  414.21  5020.3  418.24  5030.5   419.8  5043.5  420.09
  5061.2  419.39  5092.8  419.85  5149.7  422.66  5214.7   425.2  5279.7  428.81
  5373.2   431.2  5388.6  432.15  5422.5  432.79  5461.2  434.18    5593  437.37
#Mann= 7 ,-1 , 0
  4308.7     .05       0  4614.7     .16       0  4753.9     .12       0
  4997.1     .07       0  5002.6     .12       0  5149.7     .16       0
  5461.2     .05       0
Bank Sta=4979.4,5030.5
XS Rating Curve= 0 ,0
Exp/Cntr=0.3,0.1

Type RM Length L Ch R = 1 ,20528   ,800,800,800
BEGIN DESCRIPTION:
HERDS BRANCH 3 0
END DESCRIPTION:
XS GIS Cut Line= 3
      3490535.51     10416974.06      3491140.98     10416283.96
      3491522.94     10415921.53
#Sta/Elev= 30
  4402.4  429.07  4657.2  422.79  4700.1  422.39  4741.6  421.89  4777.7  420.06
  4791.4  418.49  4812.8  420.31  4862.1  419.78  4925.7     421  4947.5  420.43
    4976  417.86  4990.2  414.34  4994.1  411.98  4994.5  411.48  4999.6  411.98
  5011.1  415.02  5017.8  418.16  5110.7  418.81  5138.3  417.88  5195.2  419.05
  5209.5  420.34  5237.9  425.39  5267.9  427.93  5318.7  431.03  5358.3  432.27
  5537.5  436.05  5648.3  438.05  5690.8  440.21  5758.5  441.89    5847  443.73
#Mann= 7 ,-1 , 0
  4402.4     .16       0  4700.1     .12       0  4994.1     .07       0
  4999.6     .12       0  5267.9     .16       0  5537.5      .1       0
  5758.5     .16       0
Bank Sta=4976,5017.8
XS Rating Curve= 0 ,0
Exp/Cntr=0.3,0.1

Type RM Length L Ch R = 1 ,19728   ,750,750,750
BEGIN DESCRIPTION:
HERDS BRANCH 29 0
END DESCRIPTION:
XS GIS Cut Line= 4
      3490837.16     10417321.29      3491010.77     10416856.88
      3491433.95     10416633.35      3491529.33     10416336.38
#Sta/Elev= 30
    4231  426.86  4480.6  424.15  4582.9  423.59  4739.6  424.12  4818.8  422.06
  4841.4  420.67  4879.1  415.92  4886.6  413.01  4895.4  416.46  4909.3  418.41
  4917.5  418.36  4961.2  415.44  4983.5  415.47  4989.2   416.4  4996.9  411.33
  4997.4  410.83  5002.1  410.83  5002.5  411.33  5005.5  412.97  5011.2  413.28
  5021.9  416.67  5043.9  419.75  5087.9  421.61  5146.8  426.37  5181.6  429.82
  5201.9  430.99  5283.5  434.88  5427.5  439.48  5449.3  440.19  5517.3   440.7
#Mann= 6 ,-1 , 0
    4231     .16       0  4480.6     .12       0  4961.2     .16       0
  4996.9     .07       0  5002.5     .16       0  5427.5      .1       0
Bank Sta=4989.2,5021.9
XS Rating Curve= 0 ,0
Exp/Cntr=0.3,0.1

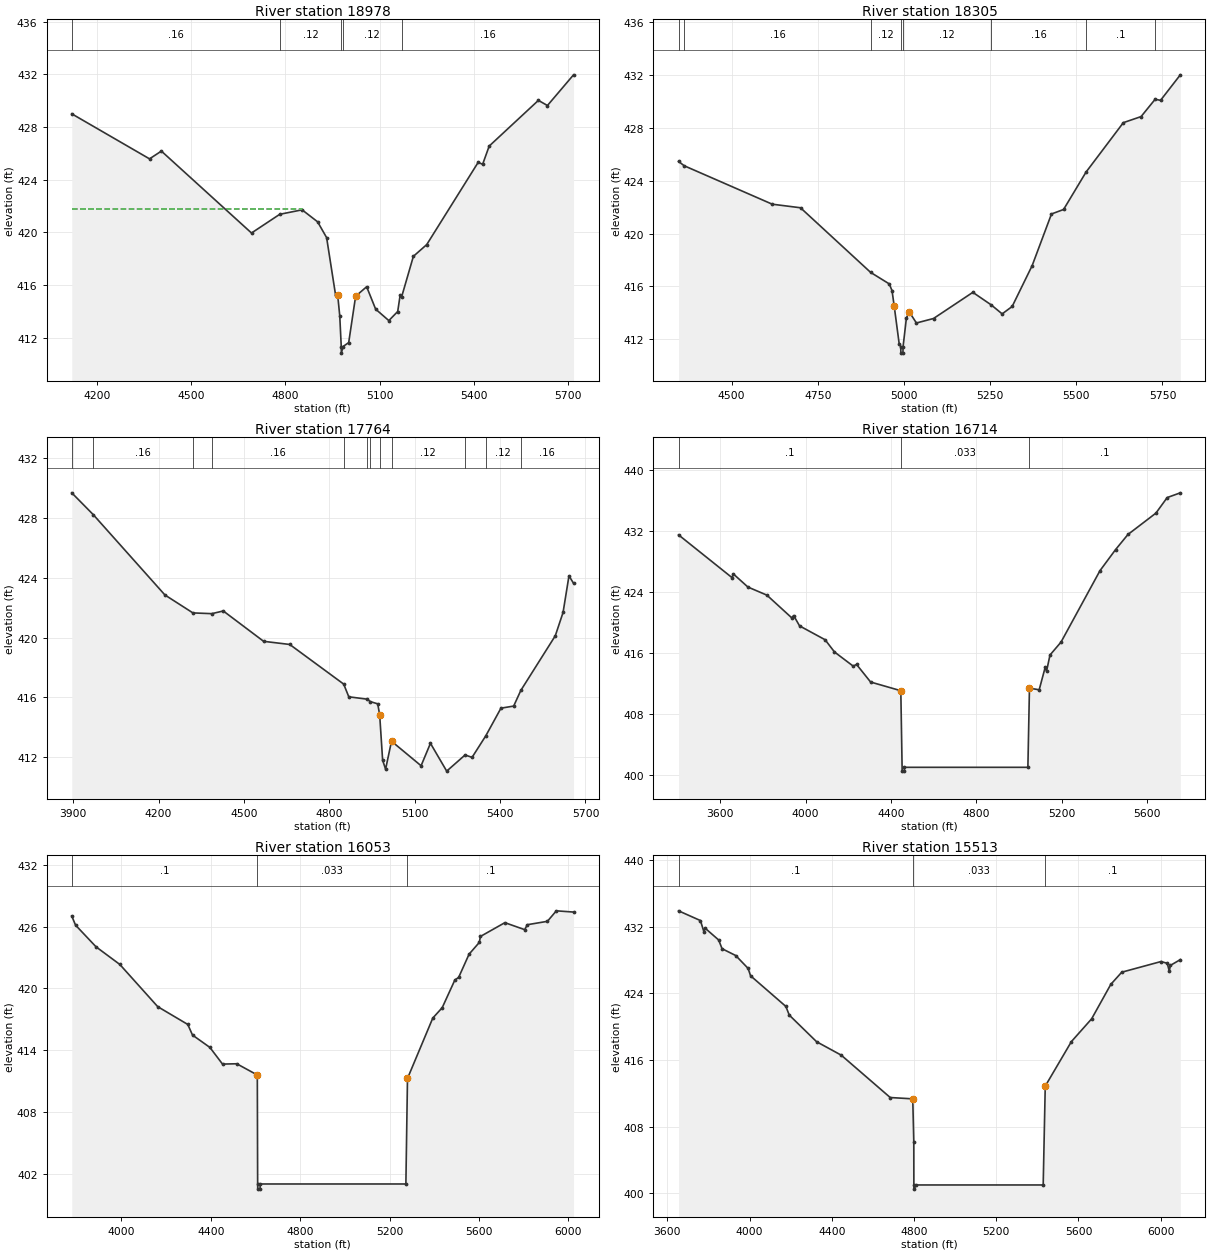
Type RM Length L Ch R = 1 ,18978   ,673,673,673
BEGIN DESCRIPTION:
HERDS BRANCH 28 0
END DESCRIPTION:
XS GIS Cut Line= 4
      3490769.66     10417566.54      3491407.09     10417211.64
      3491770.34     10416908.23       3492018.3     10416600.71
#Sta/Elev= 30
  4119.7     429  4367.4  425.58  4405.1  426.17  4692.1  419.95    4782  421.37
  4853.2  421.71  4902.6   420.8  4931.3   419.6  4959.9  415.23  4966.4  415.27
  4973.1  413.67  4977.9  411.33  4978.3  410.83  4983.6  411.33  5001.6  411.63
  5023.7  415.15  5058.8  415.87  5087.4  414.17  5129.4   413.3  5157.7  413.99
  5165.5  415.24  5169.8  415.07  5207.6  418.18  5250.1  419.07  5413.8  425.31
  5428.2  425.17    5449  426.55  5605.7  430.02  5634.5  429.63  5717.6  431.96
#Mann= 5 ,-1 , 0
  4119.7     .16       0    4782     .12       0  4977.9     .07       0
  4983.6     .12       0  5169.8     .16       0
#XS Ineff= 2 , 0
         4854.18  421.78
Permanent Ineff=
       F       F
Bank Sta=4966.4,5023.7
XS Rating Curve= 0 ,0
Exp/Cntr=0.3,0.1

Type RM Length L Ch R = 1 ,18305   ,541,541,541
BEGIN DESCRIPTION:
HERDS BRANCH 26 0
END DESCRIPTION:
XS GIS Cut Line= 4
      3491407.11     10418153.85      3491615.86     10417765.57
      3492026.43      10417235.3      3492111.33     10416901.29
#Sta/Elev= 30
  4345.8  425.46  4362.1  425.13  4617.7  422.22  4699.7  421.95  4903.2  417.06
  4957.2  416.19  4965.3  415.68  4971.7  414.49  4986.2  411.63  4990.5  411.45
    4991  410.95  4996.9  410.95  4997.4  411.45    5007   413.6  5015.1  414.08
    5036  413.23  5085.7  413.57  5199.8  415.55  5253.1   414.6  5284.9  413.92
  5313.9  414.48  5371.9  417.57    5428  421.48  5463.1  421.82  5528.3  424.65
  5636.5  428.39    5688  428.85  5728.8  430.16  5744.5  430.08  5801.9  432.01
#Mann= 8 ,-1 , 0
  4345.8     .05       0  4362.1     .16       0  4903.2     .12       0
  4990.5     .07       0  4997.4     .12       0  5253.1     .16       0
  5528.3      .1       0  5728.8     .05       0
Bank Sta=4971.7,5015.1
XS Rating Curve= 0 ,0
Exp/Cntr=0.3,0.1

Type RM Length L Ch R = 1 ,17764   ,1050,1050,1050
BEGIN DESCRIPTION:
HERDS BRANCH 25 0
END DESCRIPTION:
XS GIS Cut Line= 3
      3491458.14     10418620.21       3492170.3     10417954.57
      3492384.92     10417196.26
#Sta/Elev= 30
  3895.1  429.68  3970.7  428.22  4222.4  422.85  4320.8  421.65  4387.1   421.6
  4427.5  421.78  4569.2  419.75    4661  419.54  4850.5  416.89  4868.4  416.04
  4933.6  415.88  4943.7  415.72    4970  415.57  4976.9  414.84  4987.3   411.8
  4997.7   411.2  5018.5  413.07  5122.4  411.43  5155.3  412.93  5212.4  411.07
    5277  412.15  5301.5  411.99  5349.7  413.43    5403  415.28  5447.7  415.42
  5472.9  416.47  5593.9  420.12  5621.2  421.68    5642  424.13    5658  423.63
#Mann= 12 ,-1 , 0
  3895.1     .05       0  3970.7     .16       0  4320.8     .12       0
  4387.1     .16       0  4850.5     .12       0  4933.6     .16       0
  4943.7     .12       0  4976.9     .07       0  5018.5     .12       0
    5277     .16       0  5349.7     .12       0  5472.9     .16       0
Bank Sta=4976.9,5018.5
XS Rating Curve= 0 ,0
Exp/Cntr=0.3,0.1

Type RM Length L Ch R = 1 ,16714   ,661,661,661
BEGIN DESCRIPTION:
HERDS BRANCH 24 0
END DESCRIPTION:
XS GIS Cut Line= 3
      3492188.21     10419017.39      3493047.06     10417432.09
      3493115.06     10416888.12
#Sta/Elev= 30
  3405.1  431.47  3655.4  425.87  3661.8  426.35  3730.1  424.63    3819  423.57
  3934.8  420.61  3944.5  420.89  3972.1  419.54  4091.9  417.72  4135.7  416.12
  4223.2  414.27  4239.3  414.48    4305  412.18  4446.6  411.04  4452.9   400.5
  4463.1   400.5  4463.6     401    5042     401  5049.4  411.38  5094.9  411.16
  5123.8  414.18  5129.4  413.59  5145.6  415.72  5197.2  417.41  5379.9  426.78
  5452.9  429.54  5510.9  431.52  5641.9  434.32  5694.8  436.36  5756.3  436.98
#Mann= 3 , 0 , 0
  3405.1      .1       0  4446.6    .033       0  5049.4      .1       0
Bank Sta=4446.6,5049.4
XS Rating Curve= 0 ,0
Exp/Cntr=0.3,0.1

Type RM Length L Ch R = 1 ,16053   ,540,540,540
BEGIN DESCRIPTION:
HERDS BRANCH 23 1
END DESCRIPTION:
XS GIS Cut Line= 3
      3492463.78     10418967.29      3493662.58     10417718.38
      3493687.55     10417204.84
#Sta/Elev= 30
  3777.5  427.04  3794.5  426.15  3886.3  424.04  3992.6  422.33  4162.1  418.23
  4296.7   416.5  4317.8  415.47  4395.5  414.27  4452.1  412.65  4515.9  412.68
  4607.8  411.59  4609.3     401  4609.8   400.5  4620.1   400.5  4620.6     401
  5272.6     401  5279.8  411.25    5393  417.12  5435.2  418.13  5491.8  420.82
  5508.7  421.07  5555.4  423.33  5601.2  424.47  5606.2  425.05  5715.6  426.39
  5804.3  425.71  5815.8  426.19  5905.9  426.52  5945.9  427.54  6022.8  427.42
#Mann= 3 , 0 , 0
  3777.5      .1       0  4607.8    .033       0  5279.8      .1       0
Bank Sta=4607.8,5279.8
XS Rating Curve= 0 ,0
Exp/Cntr=0.3,0.1

Type RM Length L Ch R = 1 ,15513   ,495,495,495
BEGIN DESCRIPTION:
HERDS BRANCH 23 0
END DESCRIPTION:
XS GIS Cut Line= 3
      3493218.82     10419622.24      3493580.27     10418920.79
      3493752.04     10417278.25
#Sta/Elev= 30
  3654.8  433.92  3761.3  432.75  3777.8  431.43  3783.4  431.85  3849.9  430.42
  3866.5  429.37    3933  428.55    3993  427.01  4005.1  426.12  4176.8  422.44
  4193.3   421.4  4326.3   418.2    4446  416.59  4684.4   411.5    4794  411.34
    4799  406.18  4799.3     401  4799.8   400.5  4810.7     401  5428.4     401
  5438.4  412.87  5565.7  418.22    5664  420.95  5757.3  425.09  5810.5  426.55
  6001.5  427.83  6031.7  427.62  6041.7  426.68  6047.3  427.37  6095.4  428.06
#Mann= 3 , 0 , 0
  3654.8      .1       0    4794    .033       0  5438.4      .1       0
Bank Sta=4794,5438.4
XS Rating Curve= 0 ,0
Exp/Cntr=0.3,0.1

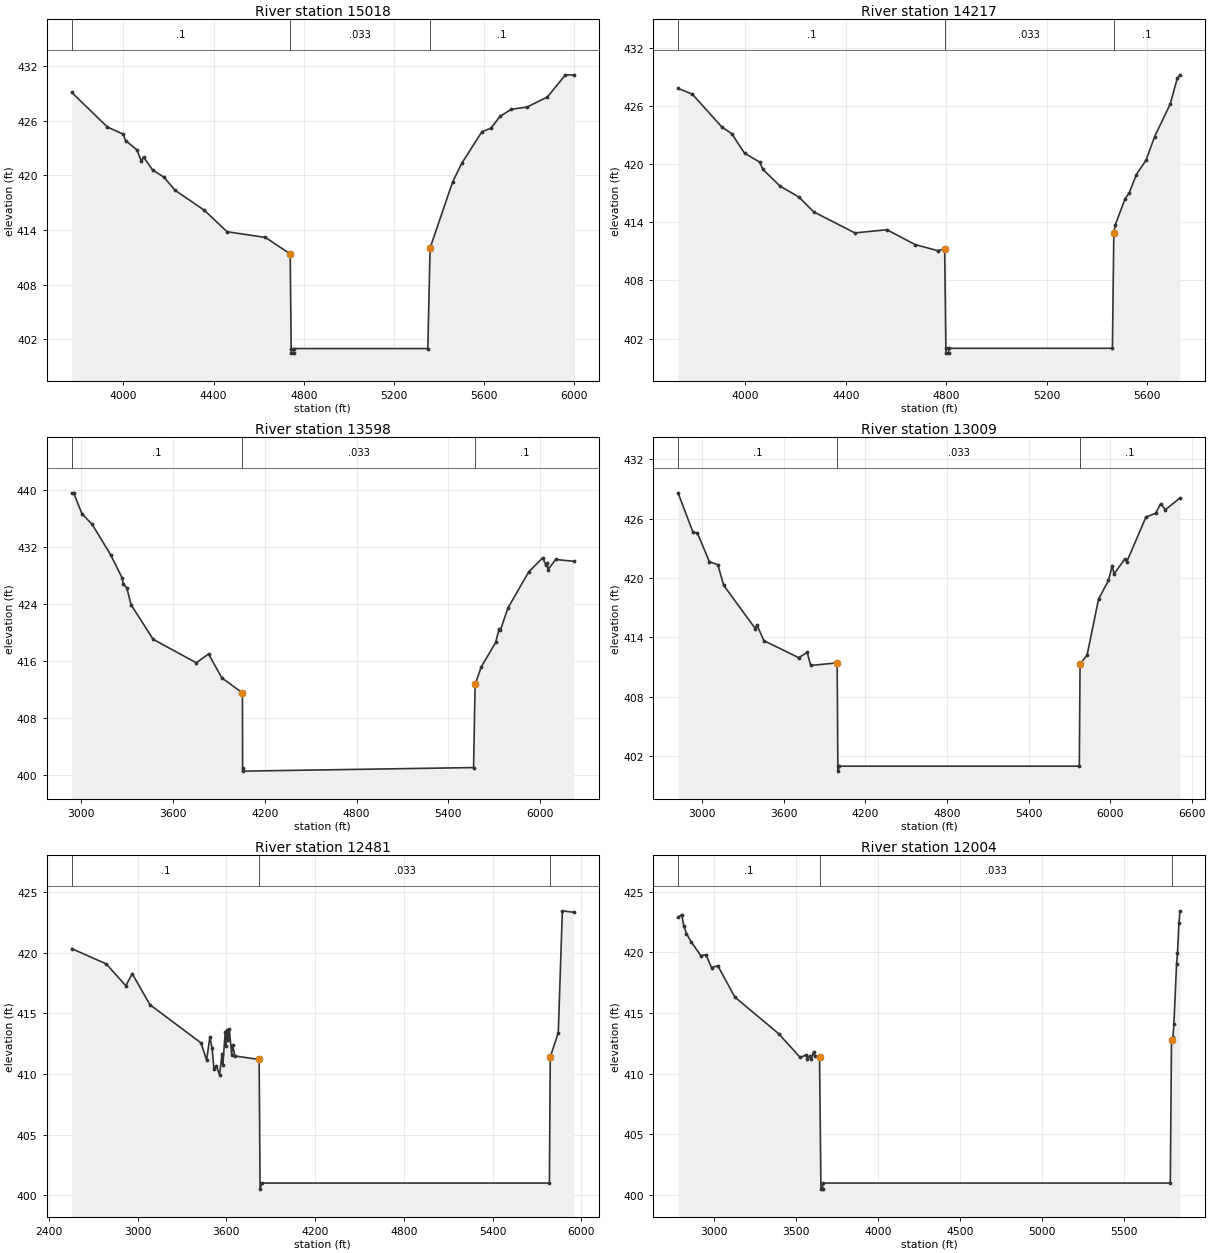
Type RM Length L Ch R = 1 ,15018   ,801,801,801
BEGIN DESCRIPTION:
HERDS BRANCH 22 0
END DESCRIPTION:
XS GIS Cut Line= 2
      3494120.64     10419539.92      3494138.53     10417315.29
#Sta/Elev= 30
  3771.6  429.09  3929.9  425.29  3999.9  424.51  4009.9  423.81  4059.9  422.81
  4079.9  421.56  4089.9     422  4129.9  420.59  4179.9   419.8  4229.9  418.35
  4359.9  416.16  4459.9  413.81  4629.9  413.19  4739.9  411.38  4744.2     401
  4744.7   400.5  4755.1   400.5  4755.6     401  5349.9     401  5359.9  412.02
  5459.9  419.28  5499.9   421.3  5589.9  424.79  5629.9  425.17  5669.9  426.46
  5719.9  427.24  5789.9  427.49  5879.9  428.59  5959.9  431.02  5996.3     431
#Mann= 3 , 0 , 0
  3771.6      .1       0  4739.9    .033       0  5359.9      .1       0
Bank Sta=4739.9,5359.9
XS Rating Curve= 0 ,0
Exp/Cntr=0.3,0.1

Type RM Length L Ch R = 1 ,14217   ,619,619,619
BEGIN DESCRIPTION:
HERDS BRANCH 21 0
END DESCRIPTION:
XS GIS Cut Line= 2
      3494349.68     10419593.55      3495233.59      10417800.7
#Sta/Elev= 30
  3731.7  427.83  3788.9  427.23  3906.7  423.83  3945.7  423.16  3996.5  421.14
  4057.2  420.22  4069.5  419.48  4136.9  417.77  4213.3  416.61  4271.6  415.09
  4436.2  412.91  4563.5  413.24  4675.8  411.71  4765.6  411.08  4793.7  411.26
  4798.5     401    4799   400.5  4809.4   400.5  4809.9     401  5461.8     401
  5467.4  412.88  5473.1  413.74  5512.3  416.44  5528.9  417.06  5557.2  418.94
  5595.8  420.43  5630.1  422.86  5691.9  426.21    5720  428.87  5730.6  429.23
#Mann= 3 , 0 , 0
  3731.7      .1       0  4793.7    .033       0  5467.4      .1       0
Bank Sta=4793.7,5467.4
XS Rating Curve= 0 ,0
Exp/Cntr=0.3,0.1

Type RM Length L Ch R = 1 ,13598   ,589,589,589
BEGIN DESCRIPTION:
HERDS BRANCH 20 0
END DESCRIPTION:
XS GIS Cut Line= 4
      3495047.94     10420703.48      3495478.49     10419759.06
      3495450.71     10418029.89      3495117.39     10417641.02
#Sta/Elev= 30
  2939.3  439.57  2952.3  439.54  3005.7  436.63  3073.2  435.13  3194.1  430.84
  3270.2  427.55  3275.6  426.73  3298.7  426.25  3327.2  423.85    3471  419.01
    3753  415.71  3833.1  416.95  3919.4  413.61  4054.7  411.48  4055.8     401
  4056.3   400.5  5564.9     401  5574.9  412.67  5614.9  415.12  5708.8  418.56
  5732.4  420.51  5740.1  420.29  5789.5   423.4  5924.5  428.45  6016.7  430.45
  6037.5  429.41  6045.2  429.75  6051.8   428.8  6101.2  430.22  6218.8  429.96
#Mann= 3 , 0 , 0
  2939.3      .1       0  4054.7    .033       0  5574.9      .1       0
Bank Sta=4054.7,5574.9
XS Rating Curve= 0 ,0
Exp/Cntr=0.3,0.1

Type RM Length L Ch R = 1 ,13009   ,528,528,528
BEGIN DESCRIPTION:
HERDS BRANCH 18 0
END DESCRIPTION:
XS GIS Cut Line= 3
      3496643.56     10420509.69      3495630.82     10417550.19
      3495076.59     10417439.34
#Sta/Elev= 30
  2820.6   428.6  2931.4   424.6  2962.7  424.56  3051.1  421.65  3113.9  421.33
  3156.8  419.26  3389.3  414.89  3400.8  415.27  3452.7  413.67  3708.5  411.96
  3771.1  412.48  3797.1  411.17  3991.7  411.43  3996.6     401  3997.1   400.5
  4008.1     401  5773.7     401    5779   411.3  5830.8  412.23  5915.3  417.88
  5988.1  419.75  6015.6  421.24  6028.9  420.41  6110.4  421.96  6122.7  421.63
  6263.4  426.14  6334.8  426.54  6372.5  427.51  6406.2  426.89  6513.8  428.07
#Mann= 3 , 0 , 0
  2820.6      .1       0  3991.7    .033       0    5779      .1       0
Bank Sta=3991.7,5779
XS Rating Curve= 0 ,0
Exp/Cntr=0.3,0.1

Type RM Length L Ch R = 1 ,12481   ,477,477,477
BEGIN DESCRIPTION:
HERDS BRANCH 16 0
END DESCRIPTION:
XS GIS Cut Line= 2
      3497531.31     10420296.73      3495920.21     10417310.63
#Sta/Elev= 30
  2555.1  420.35  2788.1  419.09  2920.4  417.29  2964.2  418.28  3083.6  415.72
  3428.8  412.57  3466.9  411.15  3488.8  413.07    3504  412.11  3516.3   410.4
  3532.6  410.68  3554.4  409.92  3570.7  411.65  3576.3  410.74  3592.6  413.45
  3598.2   412.3  3606.2  413.65  3614.4   412.8  3620.1  413.69  3636.3  411.61
    3642  412.41  3658.2  411.49    3822   411.2  3828.2   400.5  3839.2     401
  5784.2     401  5789.9  411.41  5844.2  413.41  5871.7  423.47  5948.1  423.35
#Mann= 3 , 0 , 0
  2555.1      .1       0    3822    .033       0  5789.9      .1       0
Bank Sta=3822,5789.9
XS Rating Curve= 0 ,0
Exp/Cntr=0.3,0.1

Type RM Length L Ch R = 1 ,12004   ,467,467,467
BEGIN DESCRIPTION:
Mapping XS 236d6c5e
END DESCRIPTION:
XS GIS Cut Line= 2
      3497851.62     10419901.75      3496398.53      10417206.5
#Sta/Elev= 30
  2781.4  422.87  2804.2   423.1  2816.6  422.18  2832.9  421.53  2861.1  420.86
  2920.4  419.73  2951.9  419.79  2986.1  418.73  3024.2  418.89    3128  416.31
    3395   413.3    3527  411.34  3565.2  411.56  3570.8  411.23  3587.1  411.49
  3592.7  411.22    3609  411.81  3614.6  411.44  3644.9  411.37  3653.2   400.5
  3663.7   400.5  3664.2     401  5784.8     401  5792.1  412.78    5801  413.03
  5806.7  414.07  5822.9  419.01  5828.6  419.96  5837.6  422.41  5843.4  423.41
#Mann= 3 , 0 , 0
  2781.4      .1       0  3644.9    .033       0  5792.1      .1       0
Bank Sta=3644.9,5792.1
XS Rating Curve= 0 ,0
Exp/Cntr=0.3,0.1

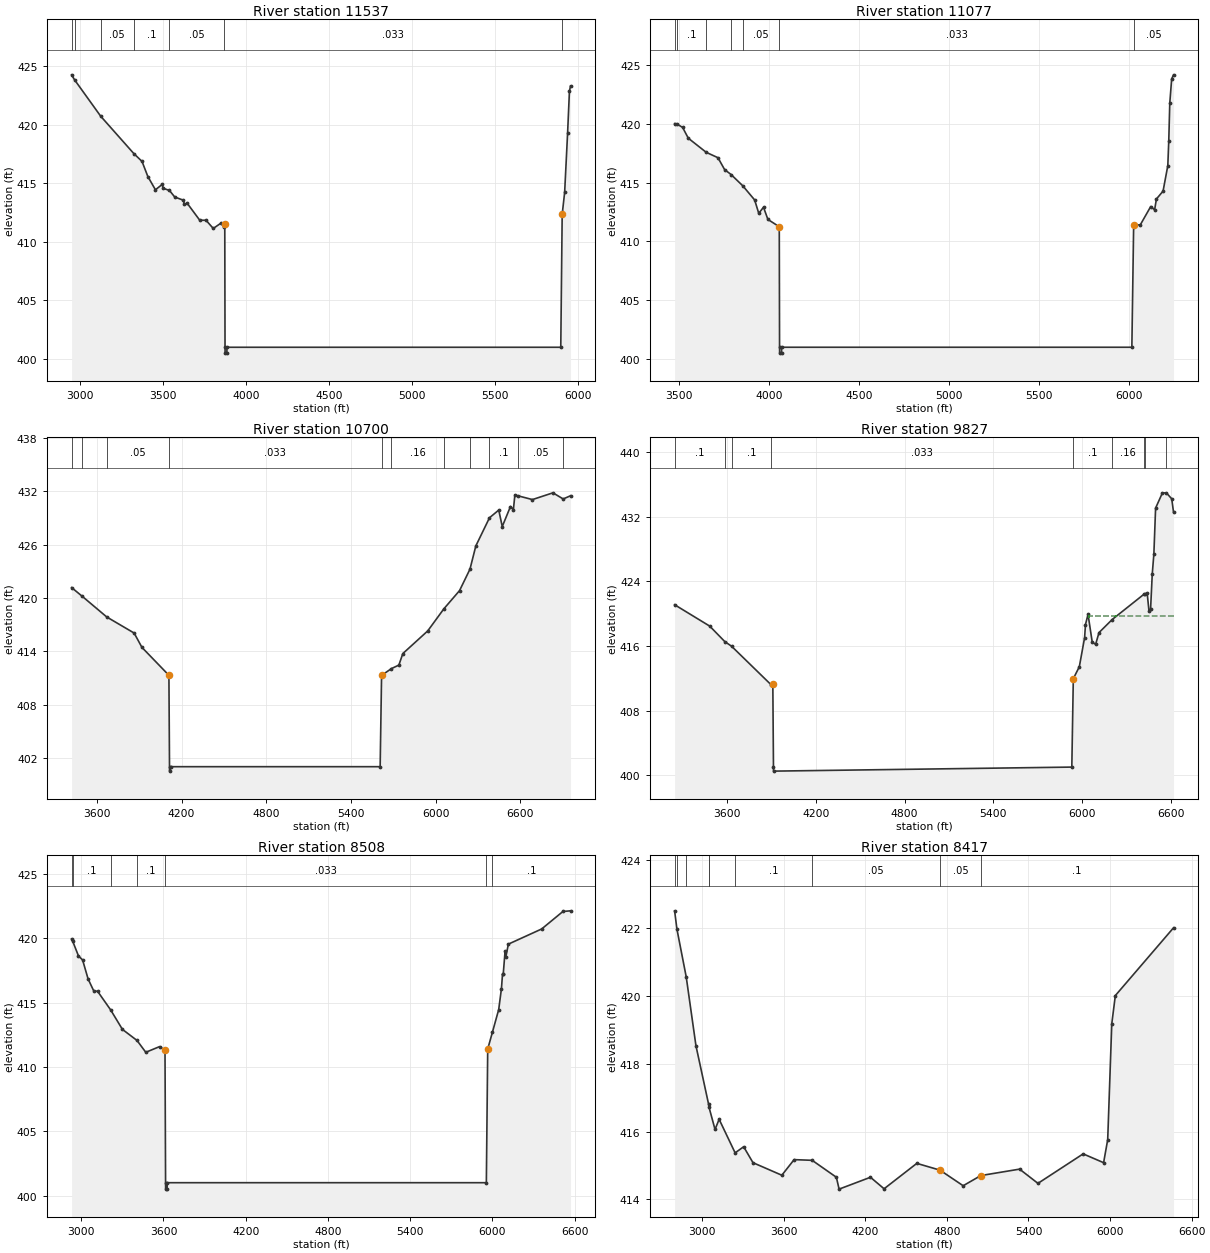
Type RM Length L Ch R = 1 ,11537   ,460,460,460
BEGIN DESCRIPTION:
Mapping XS f7c7a375
END DESCRIPTION:
XS GIS Cut Line= 2
      3498090.34     10419741.18      3496872.04     10416995.65
#Sta/Elev= 30
  2948.7  424.25  2966.2  423.83  3123.7  420.72  3323.2  417.53  3372.6  416.86
  3407.7  415.57  3453.3  414.44  3494.4   414.9  3499.9  414.57  3537.9  414.38
  3569.7  413.82  3621.7  413.55  3627.2  413.22    3645  413.28  3720.2  411.84
  3757.8  411.84  3801.5  411.14  3847.5  411.59  3865.3  411.26  3870.8  411.48
  3872.3     401  3872.8   400.5  3883.4   400.5  3883.9     401  5893.6     401
  5902.1  412.34  5916.9  414.21  5934.7  419.27  5945.8  422.86  5952.4   423.3
#Mann= 7 ,-1 , 0
  2948.7     .05       0  2966.2      .1       0  3123.7     .05       0
  3323.2      .1       0  3537.9     .05       0  3865.3    .033       0
  5902.1     .07       0
Bank Sta=3870.8,5902.1
XS Rating Curve= 0 ,0
Exp/Cntr=0.3,0.1

Type RM Length L Ch R = 1 ,11077   ,377,377,377
BEGIN DESCRIPTION:
Mapping XS 28c37420
END DESCRIPTION:
XS GIS Cut Line= 2
      3498193.63     10419243.77      3497318.63     10416611.81
#Sta/Elev= 30
  3475.8  420.02  3491.3  419.96  3520.2   419.7  3551.8  418.78  3651.4  417.58
  3716.8  417.12  3753.7  416.11  3789.7  415.69  3854.8  414.73  3920.6  413.53
  3943.6  412.39    3970  412.91  3994.4  411.87  4057.6  411.25  4059.2     401
  4059.7   400.5  4070.3   400.5  4070.8     401  6017.7     401  6027.7   411.4
  6064.6  411.41  6122.6  412.97  6144.2  412.69  6154.3  413.61  6191.2  414.28
  6217.6  416.45  6222.9  418.56  6228.5  421.76    6239  423.82  6249.4  424.17
#Mann= 7 ,-1 , 0
  3475.8     .05       0  3491.3      .1       0  3651.4     .05       0
  3789.7      .1       0  3854.8     .05       0  4057.6    .033       0
  6027.7     .05       0
Bank Sta=4057.6,6027.7
XS Rating Curve= 0 ,0
Exp/Cntr=0.3,0.1

Type RM Length L Ch R = 1 ,10700   ,873,873,873
BEGIN DESCRIPTION:
HERDS BRANCH 13 0
END DESCRIPTION:
XS GIS Cut Line= 3
      3498239.63     10419327.92       3497968.8      10416522.4
      3497777.84     10415831.47
#Sta/Elev= 30
  3421.2  421.17  3496.2  420.19  3670.1  417.86  3864.1  416.05  3919.8  414.43
  4110.7  411.29  4114.9     401  4115.4   400.5  4126.5     401  5607.6     401
  5617.6  411.28  5687.9  412.05  5740.1  412.44  5768.3  413.74  5944.7  416.29
  6059.1  418.78  6170.2  420.83  6244.1  423.25  6285.5  425.86  6382.2  429.03
    6448   429.9  6472.7  428.04    6531   430.3  6551.8  429.96  6562.2   431.6
  6582.6  431.51  6686.7  431.08  6831.9  431.84  6904.4  431.15  6956.6  431.51
#Mann= 11 ,-1 , 0
  3421.2     .05       0  3496.2      .1       0  3670.1     .05       0
  4110.7    .033       0  5617.6     .05       0  5687.9     .16       0
  6059.1     .05       0  6244.1     .16       0  6382.2      .1       0
  6582.6     .05       0  6904.4      .1       0
Bank Sta=4110.7,5617.6
XS Rating Curve= 0 ,0
Exp/Cntr=0.3,0.1

Type RM Length L Ch R = 1 ,9827    ,1319,1319,1319
BEGIN DESCRIPTION:
HERDS BRANCH 39 0
END DESCRIPTION:
XS GIS Cut Line= 3
      3499260.47     10419345.31      3498767.41     10416616.15
      3498513.95     10416071.04
#Sta/Elev= 30
  3245.1  421.11  3482.6  418.46  3584.7  416.54  3630.3  415.97  3899.2  411.17
  3909.4  411.23  3913.7     401  3914.2   400.5  5931.6     401  5941.7  411.95
  5982.4  413.43  6018.2  417.05    6024  418.66  6041.4  419.91  6069.8  416.46
  6092.7  416.21  6115.6  417.66  6204.8  419.28  6422.4  422.45  6423.6  422.44
  6441.5  422.52  6453.5  420.32  6464.4  420.59  6475.6   424.9  6486.6  427.39
  6498.3  433.08  6544.1  434.95    6571  434.97  6607.3  434.23  6619.6  432.57
#Mann= 9 ,-1 , 0
  3245.1      .1       0  3584.7     .16       0  3630.3      .1       0
  3899.2    .033       0  5941.7      .1       0  6204.8     .16       0
  6422.4      .1       0  6423.6     .16       0    6571      .1       0
#XS Ineff= 2 , 0
                         6045.06          419.66
Permanent Ineff=
       F       F
Bank Sta=3909.4,5941.7
XS Rating Curve= 0 ,0
Exp/Cntr=0.3,0.1

Type RM Length L Ch R = 1 ,8508    ,91,91,91
BEGIN DESCRIPTION:
HERDS BRANCH 9 0
END DESCRIPTION:
XS GIS Cut Line= 3
      3500345.54     10419371.72      3500163.24     10416231.08
      3499976.44     10415774.44
#Sta/Elev= 30
  2930.2  419.95    2938  419.78  2980.4  418.63  3010.4  418.32  3050.5  416.84
  3090.5  415.94  3120.6  415.87  3214.7  414.44  3300.9  412.92  3407.3  412.06
  3471.2  411.14  3571.4  411.58  3611.4   411.3  3615.6     401  3616.1   400.5
  3626.8   400.5  3627.3     401  5955.4     401  5965.4  411.39  6000.2  412.72
  6045.5  414.46  6065.5  416.09  6073.3  417.21  6078.5  417.21    6092  418.99
  6097.4  418.55    6116  419.55  6359.1  420.73    6514  422.09  6569.5  422.14
#Mann= 7 ,-1 , 0
  2930.2     .05       0    2938      .1       0  3214.7     .05       0
  3407.3      .1       0  3611.4    .033       0  5955.4     .16       0
  6000.2      .1       0
Bank Sta=3611.4,5965.4
XS Rating Curve= 0 ,0
Exp/Cntr=0.3,0.1

Type RM Length L Ch R = 1 ,8417    ,91,91,91
BEGIN DESCRIPTION:
HERDS BRANCH 7 0
END DESCRIPTION:
XS GIS Cut Line= 4
      3500412.68     10419468.16      3500439.77     10419066.21
      3500236.55     10416234.58      3500069.47     10415841.71
#Sta/Elev= 30
  2798.1  422.51  2815.1  421.97  2883.5  420.56    2955  418.53  3047.7  416.81
  3051.5  416.71  3095.3  416.06  3125.4  416.36  3243.1  415.37  3305.8  415.55
  3374.4  415.08  3586.5  414.71  3676.8  415.17  3809.5  415.15  3987.5  414.65
  4007.6   414.3  4238.2  414.65  4338.4  414.31  4579.1  415.06  4749.5  414.86
  4919.9   414.4  5049.7   414.7  5334.8  414.89  5469.8  414.47  5802.2  415.34
  5952.6  415.08  5982.7  415.76  6012.7  419.18  6038.8  420.01  6466.8  422.01
#Mann= 9 ,-1 , 0
  2798.1     .05       0  2815.1      .1       0  2883.5     .05       0
  3047.7      .1       0  3051.5     .05       0  3243.1      .1       0
  3809.5     .05       0  4749.5     .05       0  5049.7      .1       0
Bank Sta=4749.5,5049.7
XS Rating Curve= 0 ,0
Exp/Cntr=0.3,0.1