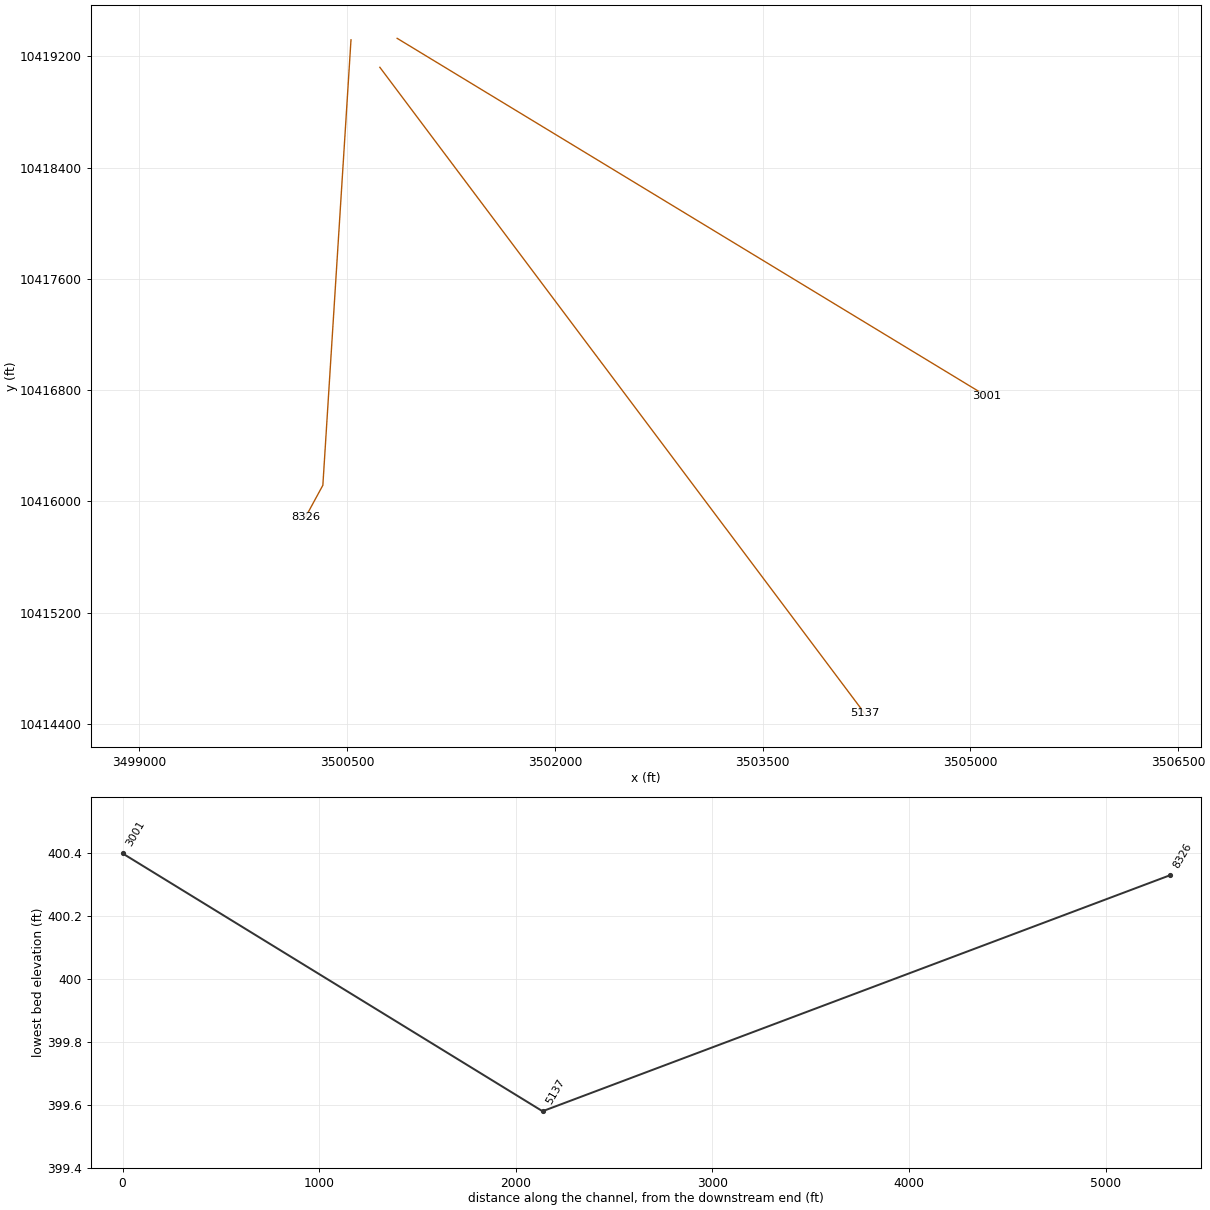
HEC-RAS study HERDS BRANCH.prj: HERDS BRANCH Base Level Engineering

--- HERDS BRANCH.g01 (geometry) --- (continued)

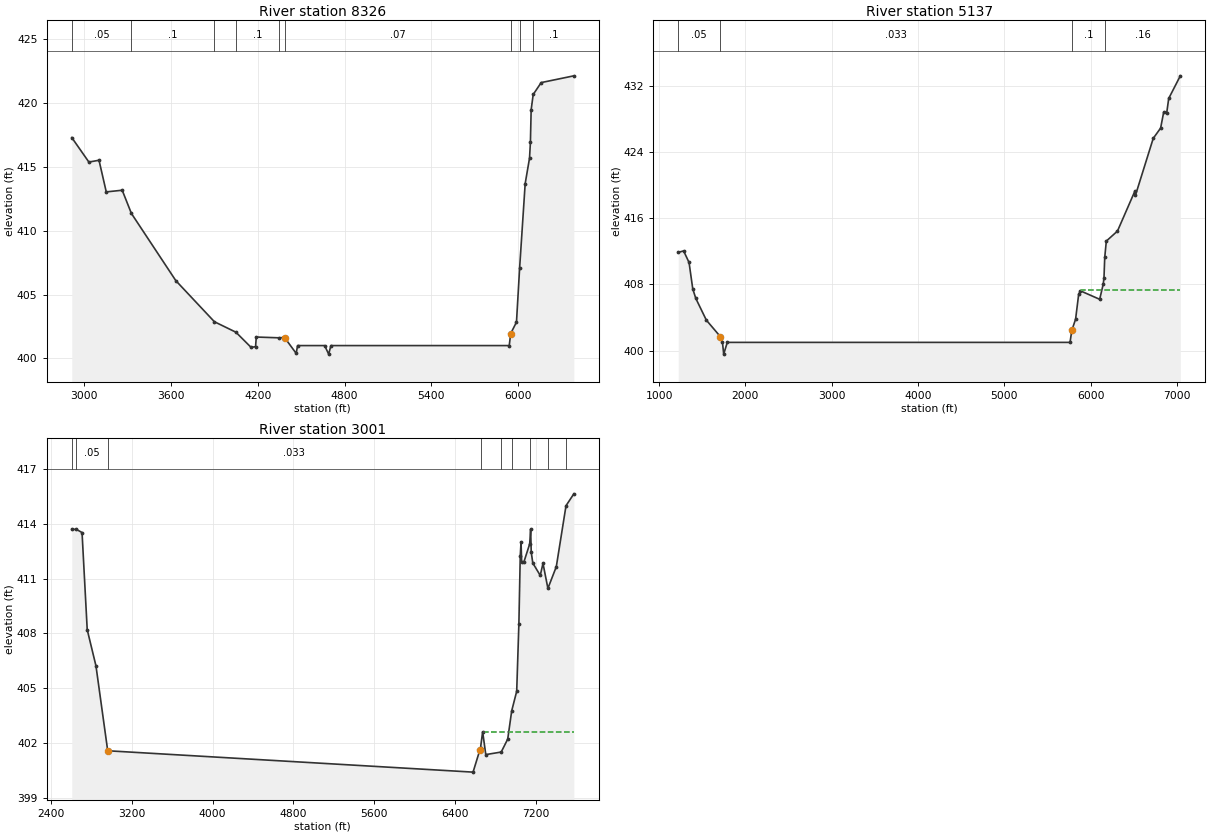
Type RM Length L Ch R = 1 ,8326    ,3189,3189,3189
BEGIN DESCRIPTION:
HERDS BRANCH 6 0
END DESCRIPTION:
XS GIS Cut Line= 3
      3500527.83     10419319.61       3500324.7      10416116.5
       3500199.7     10415887.32
#Sta/Elev= 30
  2914.6  417.31  3032.8  415.39  3102.9  415.53    3153  413.05  3263.3  413.18
  3326.8  411.36    3634  406.09  3900.5  402.87    4049  402.05    4155  400.85
  4185.1  400.92  4190.1  401.67  4344.8  401.61  4385.5  401.63  4465.7  400.39
  4475.7     401  4662.6     401  4690.3  400.33  4706.2     401  5938.6     401
  5948.6  401.94  5988.7  402.84  6010.4  407.08  6048.8   413.7  6078.9   415.7
    6085  416.95  6090.1  419.49  6104.3  420.69  6159.5  421.62  6385.2  422.15
#Mann= 9 ,-1 , 0
  2914.6     .05       0  3326.8      .1       0  3900.5     .05       0
    4049      .1       0  4344.8     .16       0  4385.5     .07       0
  5948.6      .1       0  6010.4     .08       0  6104.3      .1       0
Bank Sta=4385.5,5948.6
XS Rating Curve= 0 ,0
Exp/Cntr=0.3,0.1

Type RM Length L Ch R = 1 ,5137    ,2136,2136,2136
BEGIN DESCRIPTION:
Mapping XS c45fdcf3
END DESCRIPTION:
XS GIS Cut Line= 2
      3500736.15     10419121.72      3504235.86     10414476.27
#Sta/Elev= 30
  1222.1  411.88  1284.3  412.06  1347.4  410.66  1390.5  407.46  1425.9  406.31
  1547.7  403.69  1704.9  401.76  1711.2   401.7  1734.1  401.04  1748.9  399.58
  1790.3     401  5760.7     401  5781.6  402.45  5825.3  403.81  5860.7   406.8
  5881.5  407.23  6104.3  406.21  6145.9  408.07  6154.2  408.84  6162.8  411.27
  6181.3  413.25  6310.4  414.46  6510.3  419.25  6518.2  418.77  6724.7  425.67
  6810.1  426.91  6845.5  428.82  6881.3  428.78  6903.8  430.49  7038.3  433.23
#Mann= 4 ,-1 , 0
  1222.1     .05       0  1704.9    .033       0  5781.6      .1       0
  6162.8     .16       0
#XS Ineff= 2 , 0
                         5890.58          407.36
Permanent Ineff=
       F       F
Bank Sta=1711.2,5781.6
XS Rating Curve= 0 ,0
Exp/Cntr=0.3,0.1

Type RM Length L Ch R = 1 ,3001    ,0,0,0
BEGIN DESCRIPTION:
HERDS BRANCH 1 0
END DESCRIPTION:
XS GIS Cut Line= 2
      3500861.15     10419330.05      3505116.36     10416757.13
#Sta/Elev= 30
  2604.4   413.7    2651  413.69  2706.2  413.52  2757.4   408.2    2844  406.22
  2960.4  401.57  6578.8   400.4  6646.6  401.62  6652.5  401.72  6673.8  402.61
  6704.8  401.36  6857.7   401.5  6922.1  402.21  6961.7  403.76  7011.1  404.83
  7032.7  408.53  7046.2  412.24  7054.1  413.01  7059.9  411.93  7081.3  411.89
  7139.8   412.9  7149.1   413.7    7155  412.44  7170.5  411.85  7244.2  411.17
  7271.4  411.83  7320.1  410.46  7403.3  411.65  7499.5  414.99    7577  415.64
#Mann= 9 ,-1 , 0
  2604.4      .1       0    2651     .05       0  2960.4    .033       0
  6652.5      .1       0  6857.7     .16       0  6961.7     .05       0
  7139.8      .1       0  7320.1     .05       0  7499.5      .1       0
#XS Ineff= 2 , 0
                         6673.46          402.62
Permanent Ineff=
       F       F
Bank Sta=2960.4,6646.6
XS Rating Curve= 0 ,0
Exp/Cntr=0.3,0.1

Chan Stop Cuts=-1
Use User Specified Reach Order=0
Composite Channel Slope=5