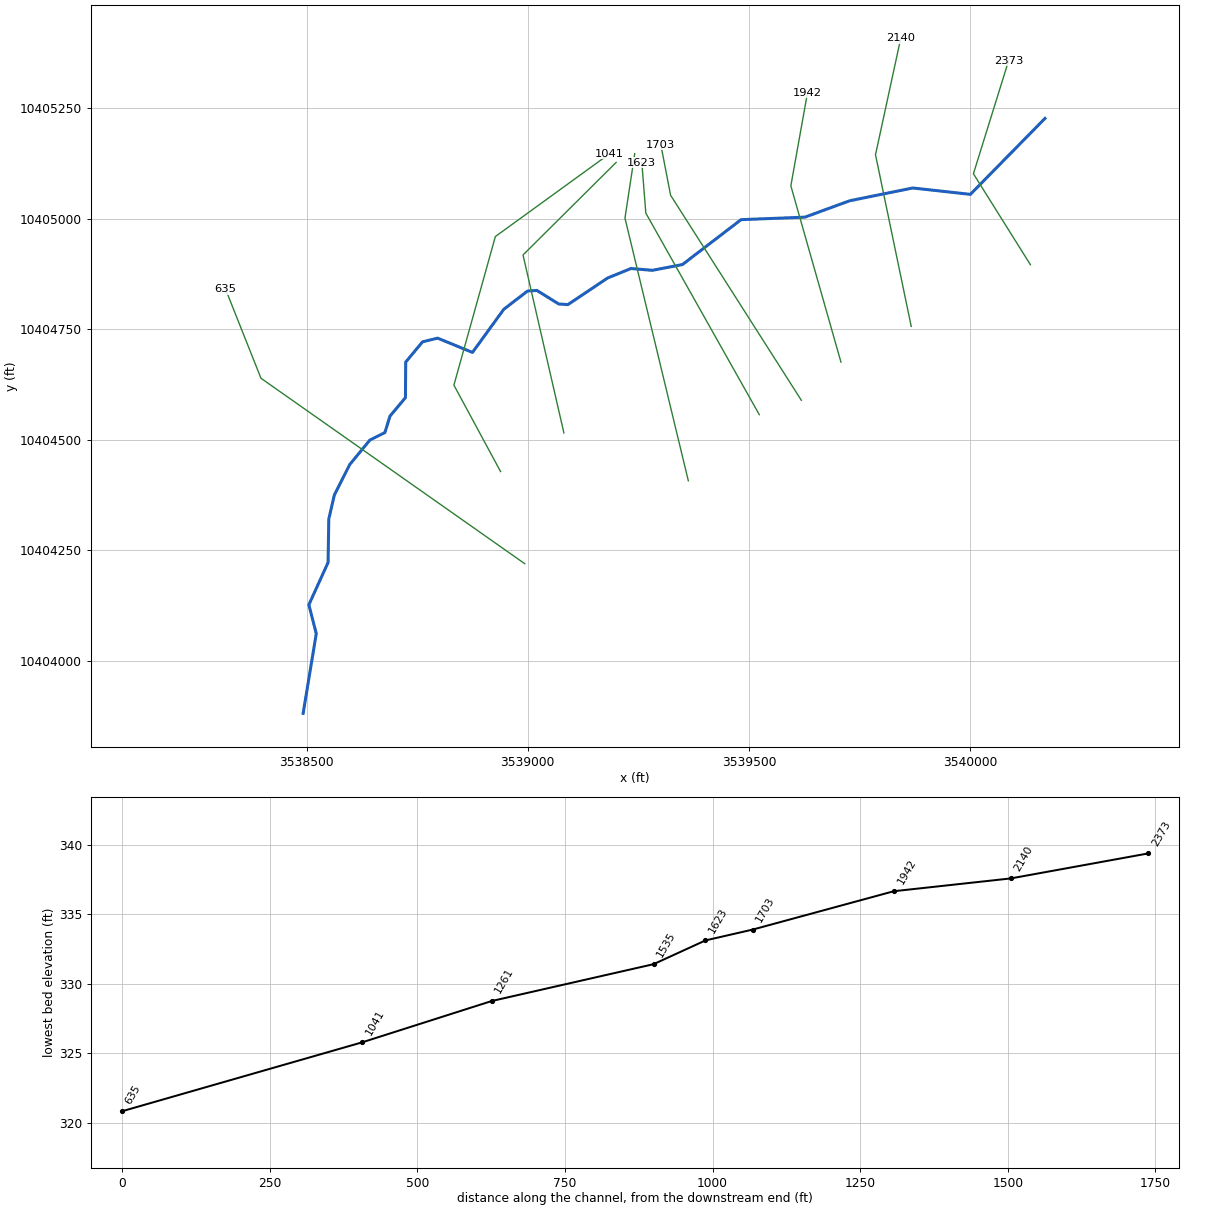
--- HOLLY BRANCH TRIB 1.prj (project) ---

Proj Title=HOLLY BRANCH TRIB 1 Base Level Engineering
Current Plan=p01
Default Exp/Contr=0.3,0.1
English Units
Geom File=g01
Flow File=f01
Plan File=p01
BEGIN DESCRIPTION:
HOLLY BRANCH TRIB 1
END DESCRIPTION:

--- HOLLY BRANCH TRIB 1.p01 (plan) ---

Plan Title=Multiple Run
Short Identifier=Multiple
Geom File=g01
Flow File=f01
Subcritical Flow
K Sum by GR= 0
Std Step Tol= 0.01
Critical Tol= 0.01
Num of Std Step Trials= 20
Max Error Tol= 0.3
Flow Tol Ratio= 0.001
Split Flow NTrial= 30
Split Flow Tol= 0.02
Split Flow Ratio= 0.02
Log Output Level= 0
Friction Slope Method= 1
Unsteady Friction Slope Method= 2
Unsteady Bridges Friction Slope Method= 1
Parabolic Critical Depth
Global Vel Dist=  1 , 1 , 1
Global Log Level= 0
CheckData=True
Encroach Param= -1, 0, 0, 0
BEGIN DESCRIPTION:
Multiple Run
END DESCRIPTION:

--- HOLLY BRANCH TRIB 1.f01 (steady flow) ---

Flow Title=Multiple
Number of Profiles=7
Profile Names=10-year,25-year,50-year,1pct_min,100-year,1pct_plu,500-year
River Rch & RM= HOLLY BRANCH TRI,Reach-1,2373
     437     574     683     596     806    1091    1116
Boundary for River Rch & Prof#=HOLLY BRANCH TRI,Reach-1,1
Up Type=0
Dn Type=3
Dn Slope=0.005
Boundary for River Rch & Prof#=HOLLY BRANCH TRI,Reach-1,2
Up Type=0
Dn Type=3
Dn Slope=0.005
Boundary for River Rch & Prof#=HOLLY BRANCH TRI,Reach-1,3
Up Type=0
Dn Type=3
Dn Slope=0.005
Boundary for River Rch & Prof#=HOLLY BRANCH TRI,Reach-1,4
Up Type=0
Dn Type=3
Dn Slope=0.005
Boundary for River Rch & Prof#=HOLLY BRANCH TRI,Reach-1,5
Up Type=0
Dn Type=3
Dn Slope=0.005
Boundary for River Rch & Prof#=HOLLY BRANCH TRI,Reach-1,6
Up Type=0
Dn Type=3
Dn Slope=0.005
Boundary for River Rch & Prof#=HOLLY BRANCH TRI,Reach-1,7
Up Type=0
Dn Type=3
Dn Slope=0.005

--- HOLLY BRANCH TRIB 1.g01 (geometry) ---

Geom Title=Existing Conditions

River Reach=HOLLY BRANCH TRI,Reach-1
Reach XY= 30
      3540169.15     10405226.64      3540000.53     10405054.96
      3539870.22     10405069.41      3539727.55     10405040.44
      3539626.38     10405003.41      3539482.14     10404997.79
      3539349.70     10404896.35      3539281.68     10404883.24
      3539233.07     10404887.33      3539180.05     10404865.68
      3539090.70     10404805.73      3539069.75     10404807.21
      3539020.63     10404837.76      3538999.54     10404836.48
      3538945.69     10404795.14      3538874.89     10404697.59
      3538796.16     10404729.97      3538762.08     10404721.59
      3538724.01     10404675.86      3538723.38     10404595.41
      3538688.43     10404553.57      3538676.90     10404516.36
      3538643.02     10404499.58      3538597.24     10404443.84
      3538562.61     10404375.09      3538550.11     10404320.92
      3538548.50     10404222.79      3538505.04     10404127.16
      3538521.80     10404062.00      3538492.11     10403881.64

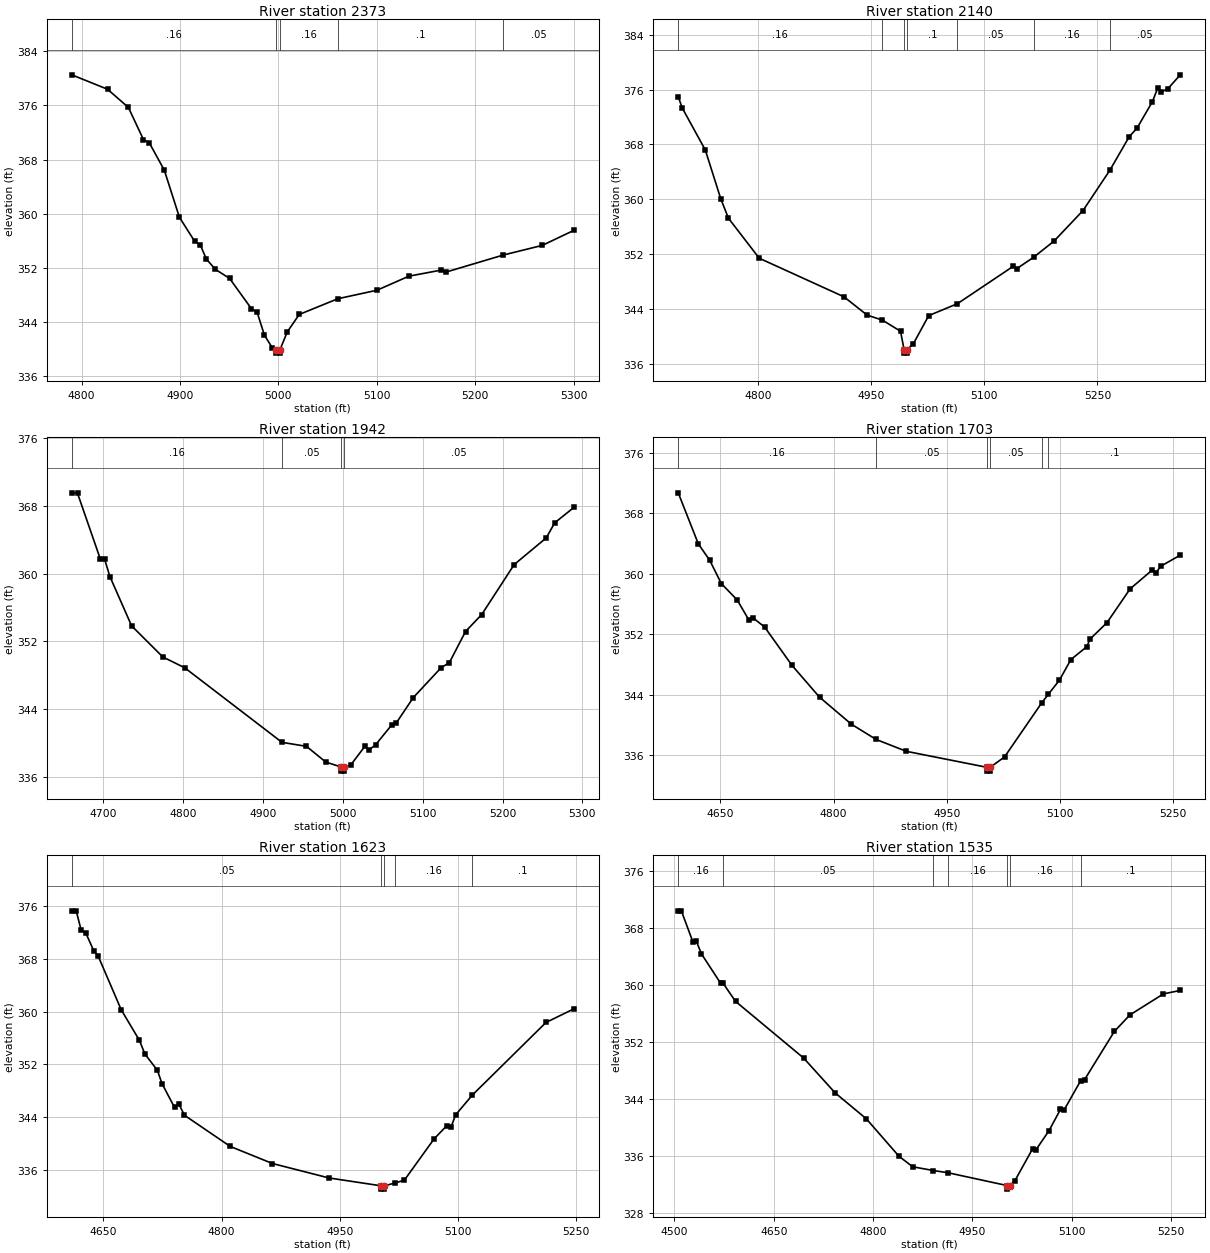
Type RM Length L Ch R = 1,2373,233,233,233
BEGIN DESCRIPTION:
HOLLY BRANCH TRIB 1 9 0
END DESCRIPTION:
XS GIS Cut Line= 3
      3540136.32     10404895.83      3540007.43     10405101.54
      3540086.84     10405356.72
#Sta/Elev= 30
  4790.1  380.53  4826.4  378.40  4847.6  375.71  4862.9  370.96  4868.8  370.49
  4884.1  366.43  4899.4  359.48  4914.8  355.94  4920.7  355.37  4926.8  353.29
  4936.0  351.76  4950.4  350.43  4972.5  345.97  4978.4  345.41  4985.8  342.03
  4993.7  340.19  4997.6  339.88  4997.9  339.38  5001.4  339.38  5001.6  339.88
  5009.0  342.52  5021.2  345.10  5060.3  347.42  5100.1  348.68  5132.6  350.76
  5165.1  351.65  5170.4  351.37  5228.3  353.88  5268.0  355.31  5300.1  357.53
#Mann=5,-1,0
  4790.1    0.16       0  4997.6    0.07       0  5001.6    0.16       0
  5060.3     0.1       0  5228.3    0.05       0
Bank Sta=4997.6,5001.6
Exp/Cntr=0.3,0.1

Type RM Length L Ch R = 1,2140,198,198,198
BEGIN DESCRIPTION:
HOLLY BRANCH TRIB 1 3 3
END DESCRIPTION:
XS GIS Cut Line= 3
      3539866.80     10404756.52      3539786.07     10405144.51
      3539843.12     10405407.70
#Sta/Elev= 30
  4694.3  374.94  4699.5  373.33  4730.2  367.18  4750.6  360.10  4760.8  357.25
  4801.7  351.41  4914.0  345.79  4944.7  343.12  4965.0  342.39  4989.0  340.77
  4993.7  338.08  4994.0  337.58  4997.5  337.58  4997.7  338.08  5006.0  338.95
  5026.4  343.05  5064.5  344.79  5138.2  350.22  5143.3  349.91  5165.3  351.54
  5192.5  353.91  5230.9  358.36  5266.6  364.25  5292.3  369.15  5302.5  370.36
  5323.0  374.25  5329.8  376.18  5334.9  375.65  5343.5  376.13  5359.9  378.14
#Mann=7,-1,0
  4694.3    0.16       0  4965.0     0.1       0  4993.7    0.07       0
  4997.7     0.1       0  5064.5    0.05       0  5165.3    0.16       0
  5266.6    0.05       0
Bank Sta=4993.7,4997.7
Exp/Cntr=0.3,0.1

Type RM Length L Ch R = 1,1942,239,239,239
BEGIN DESCRIPTION:
HOLLY BRANCH TRIB 1 8 0
END DESCRIPTION:
XS GIS Cut Line= 3
      3539707.95     10404675.77      3539594.67     10405074.20
      3539632.43     10405285.13
#Sta/Elev= 30
  4660.8  369.55  4668.0  369.50  4696.7  361.68  4701.9  361.71  4708.5  359.66
  4735.7  353.83  4774.8  350.15  4802.1  348.88  4924.0  340.06  4954.6  339.59
  4978.8  337.73  4997.6  337.16  4997.8  336.66  5001.3  336.66  5001.6  337.16
  5010.0  337.38  5027.6  339.58  5032.8  339.16  5041.2  339.78  5061.4  342.13
  5066.6  342.29  5088.3  345.35  5123.2  348.89  5133.4  349.47  5153.7  353.16
  5174.0  355.17  5214.6  361.07  5254.7  364.22  5265.4  366.01  5289.3  367.82
#Mann=4,-1,0
  4660.8    0.16       0  4924.0    0.05       0  4997.6   0.035       0
  5001.6    0.05       0
Bank Sta=4997.6,5001.6
Exp/Cntr=0.3,0.1

Type RM Length L Ch R = 1,1703,80,80,80
BEGIN DESCRIPTION:
HOLLY BRANCH TRIB 1 2 0
END DESCRIPTION:
XS GIS Cut Line= 3
      3539618.38     10404589.48      3539322.83     10405052.99
      3539300.79     10405167.06
#Sta/Elev= 30
  4594.0  370.70  4620.6  363.96  4635.8  361.77  4651.1  358.71  4672.2  356.53
  4687.4  353.94  4693.4  354.15  4708.6  352.95  4745.0  347.87  4781.4  343.68
  4823.7  340.10  4856.4  338.09  4896.5  336.52  5003.7  334.40  5003.9  333.90
  5007.4  333.90  5007.7  334.40  5026.8  335.78  5076.3  342.96  5085.0  344.08
  5099.6  345.93  5114.8  348.66  5136.0  350.36  5140.0  351.34  5162.7  353.54
  5193.3  358.00  5222.7  360.49  5227.8  360.16  5234.0  361.00  5259.9  362.46
#Mann=6,-1,0
  4594.0    0.16       0  4856.4    0.05       0  5003.7   0.035       0
  5007.7    0.05       0  5076.3    0.16       0  5085.0     0.1       0
Bank Sta=5003.7,5007.7
Exp/Cntr=0.3,0.1

Type RM Length L Ch R = 1,1623,88,88,88
BEGIN DESCRIPTION:
HOLLY BRANCH TRIB 1 5 0
END DESCRIPTION:
XS GIS Cut Line= 3
      3539523.34     10404556.91      3539266.84     10405012.63
      3539257.75     10405126.92
#Sta/Elev= 30
  4609.8  375.27  4615.4  375.27  4621.7  372.35  4627.5  371.94  4637.7  369.23
  4643.4  368.40  4672.6  360.28  4695.6  355.68  4702.7  353.58  4718.5  351.12
  4724.4  349.10  4740.3  345.49  4746.0  345.96  4752.9  344.31  4811.0  339.59
  4864.6  337.00  4936.5  334.81  5002.8  333.62  5003.0  333.12  5006.5  333.12
  5006.8  333.62  5020.3  334.05  5032.2  334.48  5069.8  340.71  5085.7  342.69
  5091.4  342.49  5097.2  344.36  5118.6  347.38  5212.0  358.36  5247.4  360.42
#Mann=5,-1,0
  4609.8    0.05       0  5002.8   0.035       0  5006.8    0.05       0
  5020.3    0.16       0  5118.6     0.1       0
Bank Sta=5002.8,5006.8
Exp/Cntr=0.3,0.1

Type RM Length L Ch R = 1,1535,274,274,274
BEGIN DESCRIPTION:
HOLLY BRANCH TRIB 1 14 0
END DESCRIPTION:
XS GIS Cut Line= 3
      3539362.90     10404407.51      3539219.67     10405001.28
      3539241.77     10405146.91
#Sta/Elev= 30
  4505.7  370.36  4510.4  370.36  4527.9  365.99  4533.0  366.12  4540.8  364.33
  4569.8  360.21  4572.9  360.29  4592.2  357.69  4695.1  349.75  4742.5  344.89
  4789.6  341.26  4839.1  336.00  4859.7  334.54  4891.0  334.01  4912.7  333.71
  5002.2  331.91  5002.4  331.41  5006.2  331.91  5014.0  332.58  5040.9  337.08
  5046.1  336.95  5065.4  339.57  5082.8  342.56  5088.0  342.43  5113.3  346.58
  5119.2  346.73  5164.2  353.48  5187.7  355.79  5238.2  358.73  5263.8  359.22
#Mann=7,-1,0
  4505.7    0.16       0  4572.9    0.05       0  4891.0     0.1       0
  4912.7    0.16       0  5002.2    0.07       0  5006.2    0.16       0
  5113.3     0.1       0
Bank Sta=5002.2,5006.2
Exp/Cntr=0.3,0.1

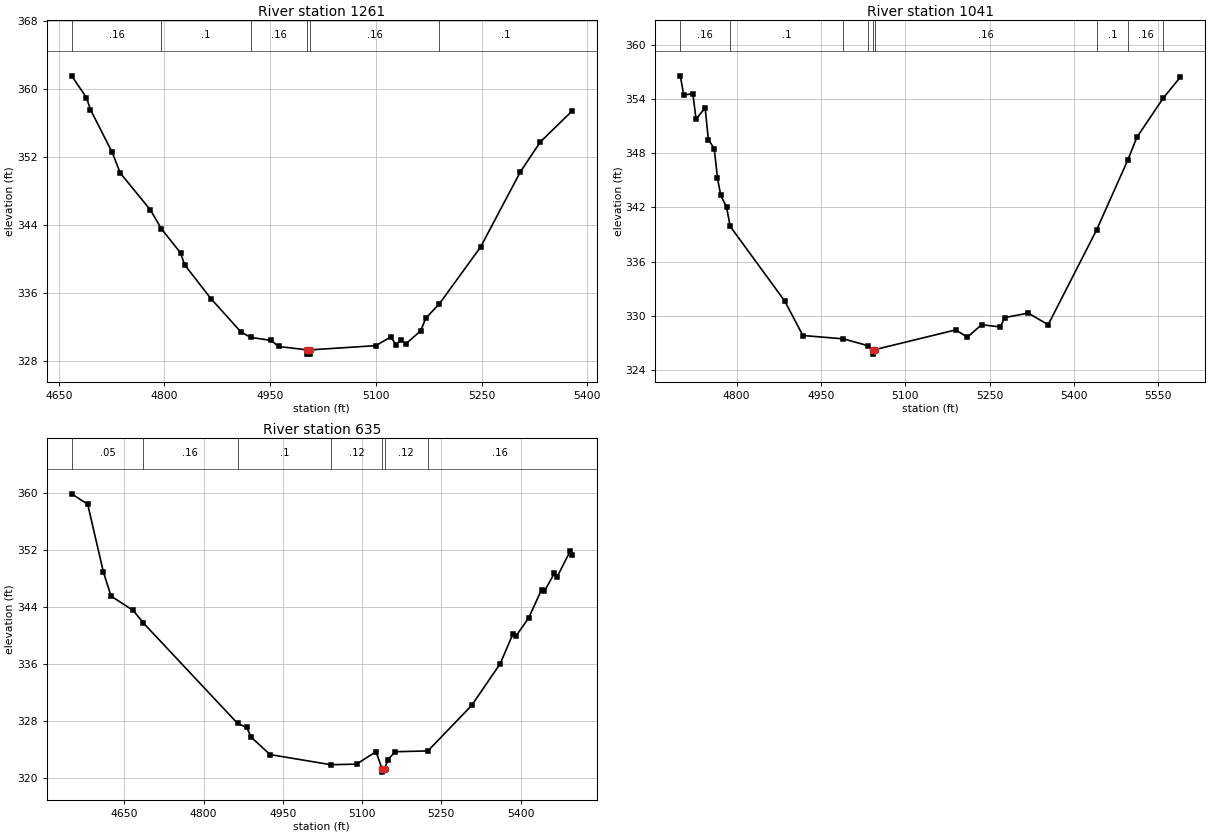
Type RM Length L Ch R = 1,1261,220,220,220
BEGIN DESCRIPTION:
HOLLY BRANCH TRIB 1 4 0
END DESCRIPTION:
XS GIS Cut Line= 3
      3539081.65     10404515.58      3538989.20     10404917.95
      3539199.67     10405127.13
#Sta/Elev= 30
  4668.3  361.56  4689.3  358.99  4695.0  357.57  4725.8  352.54  4737.2  350.11
  4780.1  345.74  4795.7  343.52  4822.9  340.68  4828.4  339.31  4865.8  335.31
  4908.6  331.36  4922.2  330.74  4951.5  330.37  4961.8  329.66  5002.6  329.26
  5002.8  328.76  5006.3  328.76  5006.6  329.26  5099.9  329.76  5121.2  330.79
  5128.2  329.89  5135.3  330.37  5142.4  329.97  5163.6  331.51  5170.7  332.99
  5190.1  334.70  5248.5  341.38  5305.0  350.25  5333.3  353.77  5377.9  357.38
#Mann=6,-1,0
  4668.3    0.16       0  4795.7     0.1       0  4922.2    0.16       0
  5002.6    0.07       0  5006.6    0.16       0  5190.1     0.1       0
Bank Sta=5002.6,5006.6
Exp/Cntr=0.3,0.1

Type RM Length L Ch R = 1,1041,406,406,406
BEGIN DESCRIPTION:
HOLLY BRANCH TRIB 1 1 0
END DESCRIPTION:
XS GIS Cut Line= 4
      3538938.43     10404428.34      3538832.95     10404623.68
      3538926.70     10404959.62      3539184.74     10405146.70
#Sta/Elev= 30
  4700.0  356.56  4706.1  354.43  4722.3  354.59  4728.0  351.79  4744.2  353.00
  4749.9  349.51  4760.4  348.51  4766.1  345.25  4771.9  343.35  4782.3  342.04
  4788.6  339.92  4885.6  331.66  4918.0  327.84  4989.9  327.47  5034.0  326.71
  5042.2  326.28  5042.4  325.78  5046.2  326.28  5189.8  328.46  5210.6  327.66
  5235.8  329.03  5269.2  328.79  5277.0  329.82  5318.8  330.32  5354.3  329.03
  5440.3  339.50  5496.3  347.30  5512.1  349.77  5558.9  354.09  5589.5  356.43
#Mann=9,-1,0
  4700.0    0.16       0  4788.6     0.1       0  4989.9    0.12       0
  5034.0    0.16       0  5042.2    0.07       0  5046.2    0.16       0
  5440.3     0.1       0  5496.3    0.16       0  5558.9     0.1       0
Bank Sta=5042.2,5046.2
Exp/Cntr=0.3,0.1

Type RM Length L Ch R = 1,635,0,0,0
BEGIN DESCRIPTION:
HOLLY BRANCH TRIB 1 1.1
END DESCRIPTION:
XS GIS Cut Line= 3
      3538993.07     10404220.06      3538396.75     10404639.31
      3538316.55     10404841.10
#Sta/Elev= 30
  4550.6  359.84  4580.9  358.38  4610.5  348.91  4625.1  345.50  4667.1  343.49
  4685.6  341.79  4864.6  327.65  4881.8  327.09  4890.2  325.73  4925.9  323.29
  5041.0  321.87  5089.7  321.95  5126.3  323.70  5137.6  321.33  5138.0  320.83
  5142.9  321.33  5148.9  322.60  5163.0  323.69  5224.5  323.80  5307.3  330.18
  5361.3  336.03  5385.6  340.24  5391.0  339.88  5415.3  342.47  5439.6  346.41
  5445.0  346.20  5463.9  348.72  5469.3  348.24  5493.5  351.78  5496.7  351.28
#Mann=7,-1,0
  4550.6    0.05       0  4685.6    0.16       0  4864.6     0.1       0
  5041.0    0.12       0  5137.6    0.07       0  5142.9    0.12       0
  5224.5    0.16       0
Bank Sta=5137.6,5142.9
Exp/Cntr=0.3,0.1

Chan Stop Cuts=-1