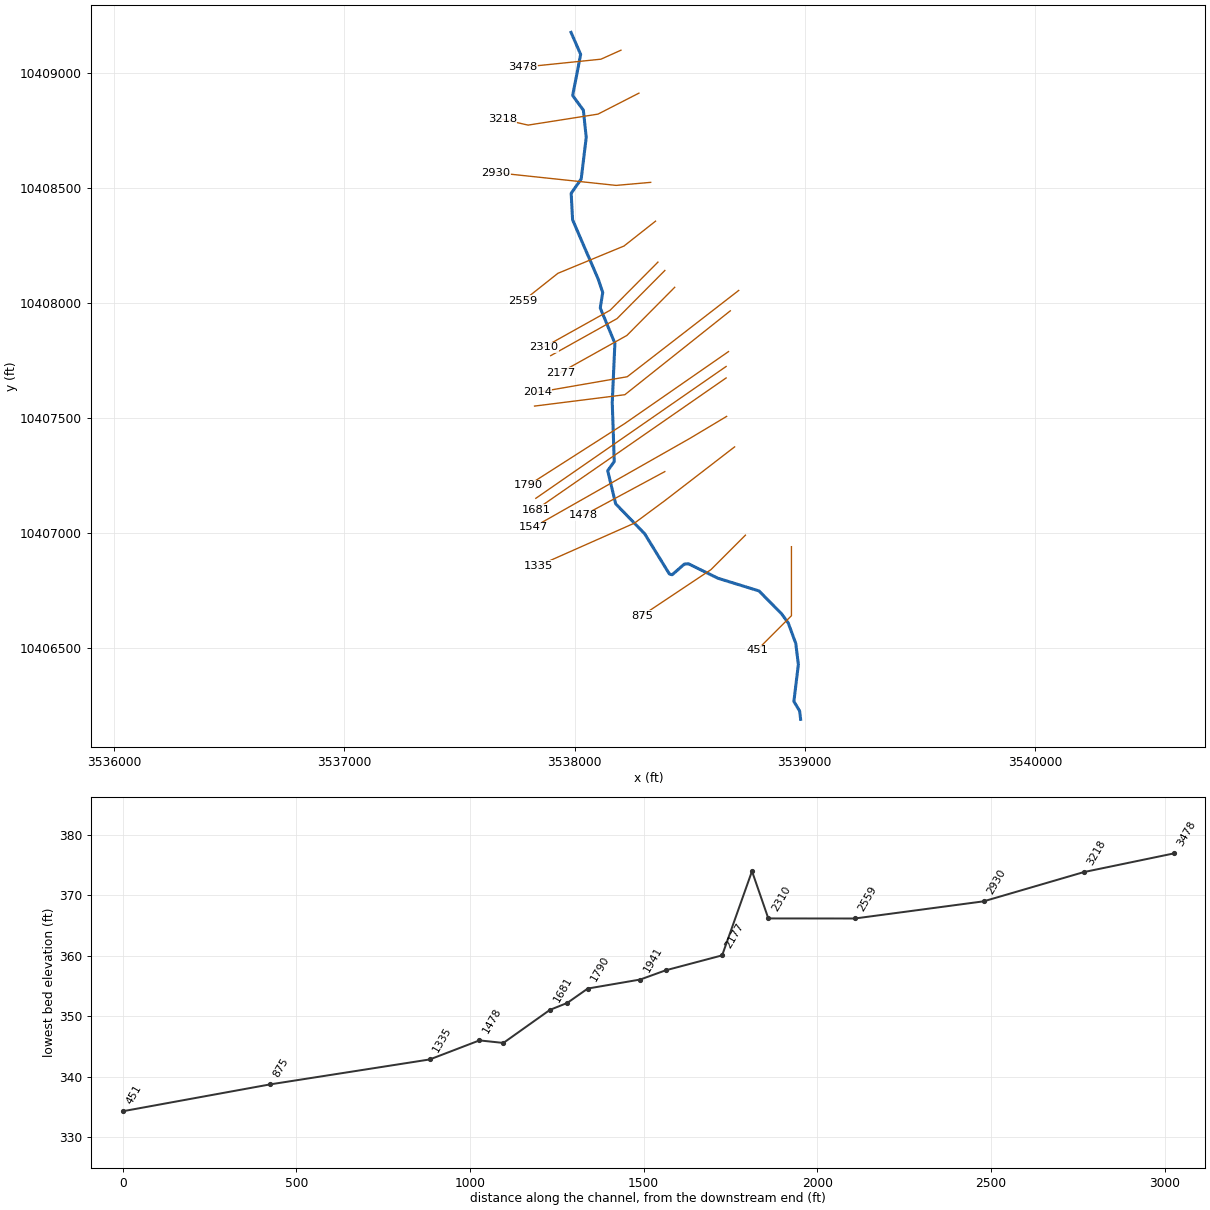
--- HOLLY BRANCH TRIB 2.prj (project) ---

Proj Title=HOLLY BRANCH TRIB 2 Base Level Engineering
Current Plan=p01
Default Exp/Contr=0.3,0.1
English Units
Geom File=g01
Flow File=f01
Plan File=p01
Y Axis Title=Elevation
X Axis Title(PF)=Main Channel Distance
X Axis Title(XS)=Station
BEGIN DESCRIPTION:
HOLLY BRANCH TRIB 2
END DESCRIPTION:
DSS Export Rating Curves= 0
DSS Export Rating Curve Sorted= 0
DSS Export Volume Flow Curves= 0
DXF OffsetX= 0
DXF OffsetY= 0
DXF ScaleX= 1
DXF ScaleY= 10

--- HOLLY BRANCH TRIB 2.p01 (plan) ---

Plan Title=Multiple Run
Short Identifier=Multiple
Geom File=g01
Flow File=f01
Subcritical Flow
K Sum by GR= 0
Std Step Tol= 0.01
Critical Tol= 0.01
Num of Std Step Trials= 20
Max Error Tol= 0.3
Flow Tol Ratio= 0.001
Split Flow NTrial= 30
Split Flow Tol= 0.02
Split Flow Ratio= 0.02
Log Output Level= 0
Friction Slope Method= 1
Unsteady Friction Slope Method= 2
Unsteady Bridges Friction Slope Method= 1
Parabolic Critical Depth
Global Vel Dist=  1 , 1 , 1
Global Log Level= 0
CheckData=True
Encroach Param= -1, 0, 0, 0
BEGIN DESCRIPTION:
Multiple Run
END DESCRIPTION:

--- HOLLY BRANCH TRIB 2.f01 (steady flow) ---

Flow Title=Multiple
Program Version=4.10
Number of Profiles= 7
Profile Names=10-year,25-year,50-year,1pct_min,100-year,1pct_plu,500-year
River Rch & RM=HOLLY BRANCH TRI,Reach-1         ,3478
     814    1121    1375    1235    1670    2258    2451
Boundary for River Rch & Prof#=HOLLY BRANCH TRI,Reach-1         , 1
Up Type= 0
Dn Type= 3
Dn Slope=0.01
Boundary for River Rch & Prof#=HOLLY BRANCH TRI,Reach-1         , 2
Up Type= 0
Dn Type= 3
Dn Slope=0.01
Boundary for River Rch & Prof#=HOLLY BRANCH TRI,Reach-1         , 3
Up Type= 0
Dn Type= 3
Dn Slope=0.01
Boundary for River Rch & Prof#=HOLLY BRANCH TRI,Reach-1         , 4
Up Type= 0
Dn Type= 3
Dn Slope=0.01
Boundary for River Rch & Prof#=HOLLY BRANCH TRI,Reach-1         , 5
Up Type= 0
Dn Type= 3
Dn Slope=0.01
Boundary for River Rch & Prof#=HOLLY BRANCH TRI,Reach-1         , 6
Up Type= 0
Dn Type= 3
Dn Slope=0.01
Boundary for River Rch & Prof#=HOLLY BRANCH TRI,Reach-1         , 7
Up Type= 0
Dn Type= 3
Dn Slope=0.01
DSS Import GetInterval= 0
DSS Import GetPeak= 0
DSS Import FillOption= 0

--- HOLLY BRANCH TRIB 2.g01 (geometry) ---

Geom Title=Existing Conditions
Program Version=4.10

River Reach=HOLLY BRANCH TRI,Reach-1
Reach XY= 30
      3537984.62     10409175.98      3538026.29     10409080.49
      3537991.57     10408901.67      3538038.03      10408838.2
      3538050.49     10408719.83      3538028.69     10408539.16
      3537985.08     10408476.86      3537991.31      10408361.6
      3538102.79     10408103.65      3538122.23     10408046.02
      3538111.47     10407978.65      3538175.01     10407825.53
      3538163.55     10407567.54      3538172.23     10407311.64
      3538143.76     10407271.71      3538178.41     10407127.79
      3538304.11     10406998.17      3538411.92     10406822.84
      3538424.18     10406819.81      3538477.04     10406866.19
      3538495.11     10406867.13       3538622.8     10406804.48
      3538801.24      10406749.3      3538899.41     10406649.73
       3538928.2     10406610.15      3538960.94     10406521.15
      3538972.17     10406429.75      3538952.68     10406269.42
      3538977.71     10406227.73      3538982.11     10406191.64

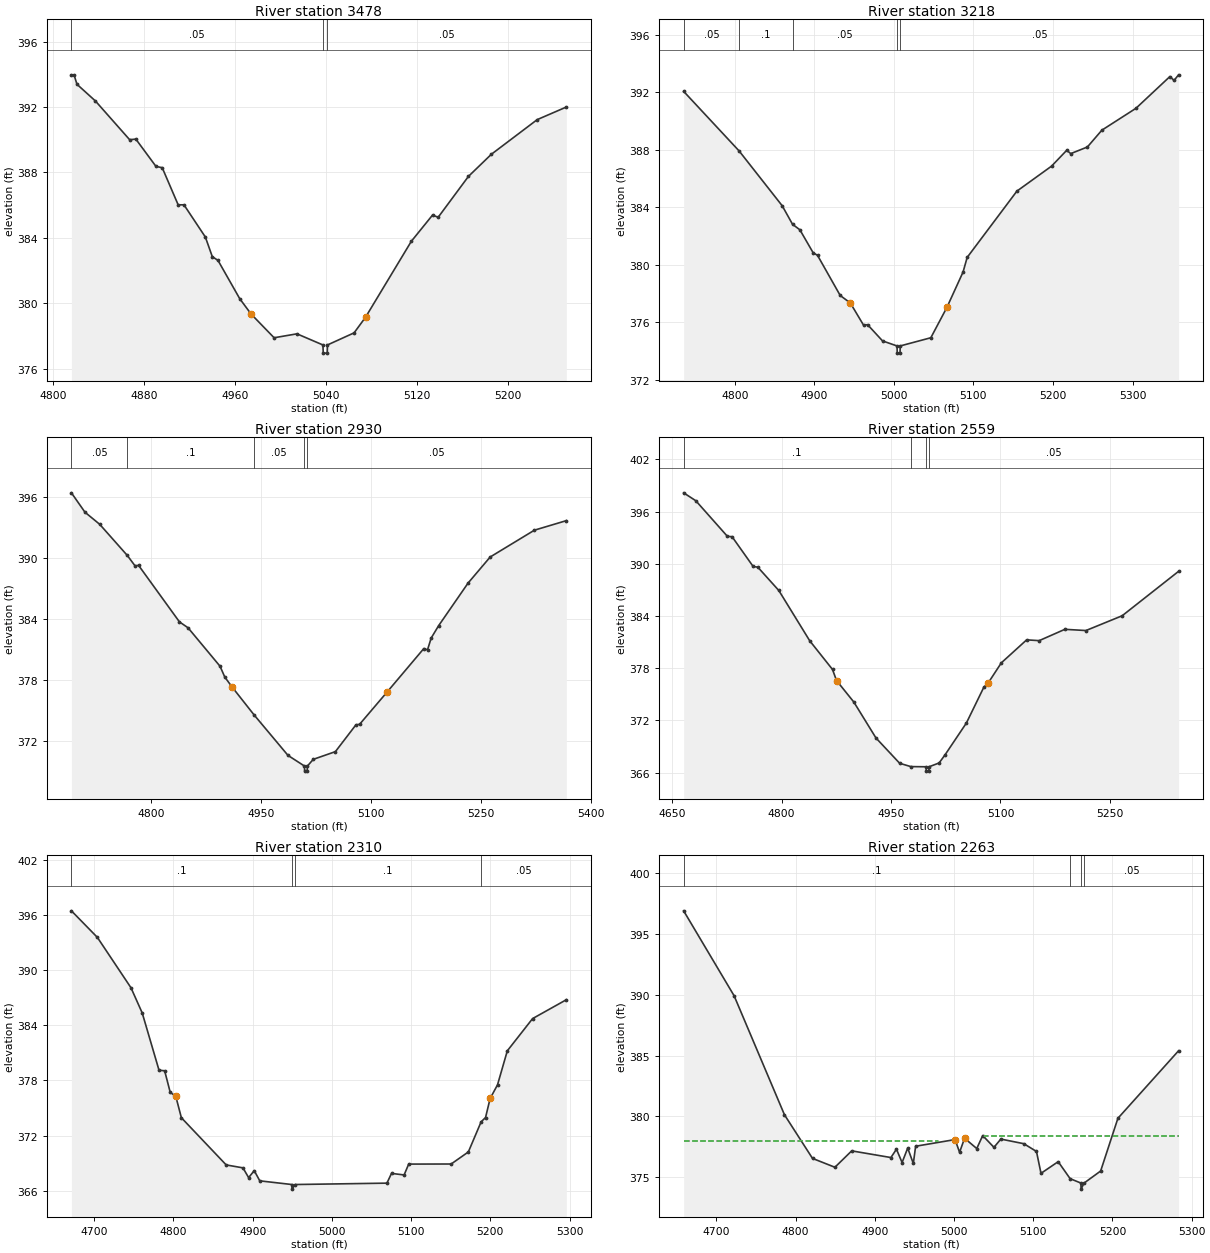
Type RM Length L Ch R = 1 ,3478    ,260,260,260
BEGIN DESCRIPTION:
HOLLY BRANCH TRIB 2 8 0
END DESCRIPTION:
XS GIS Cut Line= 3
      3538201.34     10409098.72      3538114.54     10409059.66
       3537776.6       10409025.
#Sta/Elev= 30
  4816.1  393.97  4818.4  393.97    4821  393.39  4837.2  392.37  4867.3     390
  4872.7  390.04  4890.4  388.37  4895.9  388.29  4909.9  386.02    4915  386.02
  4933.8  384.05  4939.9  382.85  4944.9  382.62    4964  380.28    4974  379.34
  4994.2  377.89  5014.3  378.13  5037.1  377.45  5037.4  376.95  5040.9  376.95
  5041.1  377.45  5064.5  378.19  5074.6  379.15  5114.8  383.79  5133.4  385.39
  5138.4  385.26    5165  387.76  5185.1  389.11  5225.4  391.23    5251     392
#Mann= 3 ,-1 , 0
  4816.1     .05       0  5037.1     .03       0  5041.1     .05       0
Bank Sta=4974,5074.6
XS Rating Curve= 0 ,0
Exp/Cntr=0.3,0.1

Type RM Length L Ch R = 1 ,3218    ,288,288,288
BEGIN DESCRIPTION:
Mapping XS e98f7bf2
END DESCRIPTION:
XS GIS Cut Line= 4
      3538279.47     10408912.09      3538101.52     10408820.94
       3537797.7      10408773.2      3537686.02     10408798.97
#Sta/Elev= 30
  4735.8  392.06  4805.6  387.91  4859.7   384.1  4872.7  382.81  4881.9  382.43
  4898.5  380.84  4904.1  380.65  4932.6  377.86  4945.3  377.34  4961.9   375.8
    4967  375.83  4985.8   374.7    5004  374.35  5004.3  373.85  5007.8  373.85
    5008  374.35  5046.5  374.92  5066.7  377.03    5087  379.49  5092.2  380.51
  5154.7  385.12  5198.3  386.86  5217.3  387.96  5222.4  387.73  5243.3  388.19
  5261.5  389.36  5304.3  390.88    5347  393.09  5352.2  392.82  5357.9  393.21
#Mann= 5 ,-1 , 0
  4735.8     .05       0  4805.6      .1       0  4872.7     .05       0
    5004     .03       0    5008     .05       0
Bank Sta=4945.3,5066.7
XS Rating Curve= 0 ,0
Exp/Cntr=0.3,0.1

Type RM Length L Ch R = 1 ,2930    ,371,371,371
BEGIN DESCRIPTION:
Mapping XS 69c58bad
END DESCRIPTION:
XS GIS Cut Line= 3
      3538330.54     10408524.48      3538180.36      10408511.3
      3537658.74     10408566.63
#Sta/Elev= 30
  4691.1  396.43  4709.6  394.52  4729.7  393.33  4767.4  390.26  4777.8  389.25
  4782.8  389.28  4838.5  383.72  4850.2  383.14  4893.9  379.35  4900.4  378.28
  4910.5  377.29  4940.1  374.58  4986.6  370.57  5009.1  369.52  5009.3  369.02
  5012.8  369.02  5013.1  369.52  5021.1  370.18  5051.3  370.94  5079.3  373.58
  5084.3  373.63  5121.7   376.8  5171.9  381.09    5177  380.97    5182  382.13
  5192.1  383.34  5232.3  387.54  5262.5  390.11  5322.8  392.75  5366.4  393.69
#Mann= 5 ,-1 , 0
  4691.1     .05       0  4767.4      .1       0  4940.1     .05       0
  5009.1     .03       0  5013.1     .05       0
Bank Sta=4910.5,5121.7
XS Rating Curve= 0 ,0
Exp/Cntr=0.3,0.1

Type RM Length L Ch R = 1 ,2559    ,249,249,249
BEGIN DESCRIPTION:
Mapping XS 96c599b3
END DESCRIPTION:
XS GIS Cut Line= 4
      3538351.61     10408355.89       3538214.6     10408247.86
      3537927.45     10408129.31      3537775.87      10408009.1
#Sta/Elev= 30
  4665.6  398.15  4682.3  397.24  4725.6  393.15    4732  393.11  4760.9  389.69
  4767.3  389.61  4796.1  386.93  4838.5  381.15  4869.7  377.86  4875.2  376.59
    4899  374.11  4929.3  369.99  4961.8  367.08  4977.1   366.7  4998.1  366.68
  4998.3  366.18  5001.8  366.18  5002.1  366.68  5015.9  367.12    5024  368.05
  5053.3  371.71  5077.2  375.82  5082.7  376.25  5101.2  378.62  5135.9  381.26
  5153.1  381.17  5188.3  382.47  5217.2  382.33  5266.9  384.03  5344.2  389.13
#Mann= 4 ,-1 , 0
  4665.6      .1       0  4977.1     .05       0  4998.1     .03       0
  5002.1     .05       0
Bank Sta=4875.2,5082.7
XS Rating Curve= 0 ,0
Exp/Cntr=0.3,0.1

Type RM Length L Ch R = 1 ,2310    ,47,47,47
BEGIN DESCRIPTION:
HOLLY BRANCH TRIB 2 5 22
END DESCRIPTION:
XS GIS Cut Line= 3
       3538362.1     10408178.02      3538154.38     10407968.93
      3537866.21     10407807.97
#Sta/Elev= 30
  4671.2  396.43    4704  393.54  4746.4  388.07  4760.6  385.33  4781.8  379.11
  4788.9  379.05  4795.9  376.72    4803  376.26    4810  373.95  4866.6  368.82
  4887.8   368.5  4894.9  367.44    4902   368.2    4909  367.09  4949.5  366.69
  4949.7  366.19  4953.5  366.69  5069.5  366.84  5075.3   367.9  5091.2  367.73
    5097  368.91  5150.6  368.92  5172.3  370.23  5188.4   373.5    5194  373.97
  5199.8  376.04  5209.1  377.52  5221.5  381.22  5253.4  384.72    5296  386.77
#Mann= 4 ,-1 , 0
  4671.2      .1       0  4949.5     .07       0  4953.5      .1       0
  5188.4     .05       0
Bank Sta=4803,5199.8
XS Rating Curve= 0 ,0
Exp/Cntr=0.3,0.1

Type RM Length L Ch R = 1 ,2263    ,86,86,86
BEGIN DESCRIPTION:
HOLLY BRANCH TRIB 2 5 1
END DESCRIPTION:
XS GIS Cut Line= 3
      3538392.14     10408141.68      3538184.37     10407932.54
      3537896.18     10407771.57
#Sta/Elev= 30
  4658.6  396.92  4722.3  389.93  4785.9  380.13  4821.3  376.54  4849.6  375.81
  4870.8  377.16  4920.3  376.61  4927.3   377.3  4934.4   376.2  4941.5  377.39
  4948.6  376.12  4951.5  377.54  5001.3  378.09    5007  377.04  5013.3   378.2
  5028.7  377.35  5036.2  378.42  5050.4  377.45  5059.1  378.13  5088.1  377.75
  5104.1  377.11  5109.8  375.31  5131.5  376.27  5146.6  374.87  5160.2  374.51
  5160.4  374.01  5164.2  374.51  5185.1   375.5  5206.9  379.84  5283.5   385.4
#Mann= 4 ,-1 , 0
  4658.6      .1       0  5146.6     .05       0  5160.2     .07       0
  5164.2     .05       0
#XS Ineff= 2 , 0
         4980.01  377.98  5037.5          378.39
Permanent Ineff=
       T       T
Bank Sta=5001.3,5013.3
XS Rating Curve= 0 ,0
Exp/Cntr=0.3,0.1

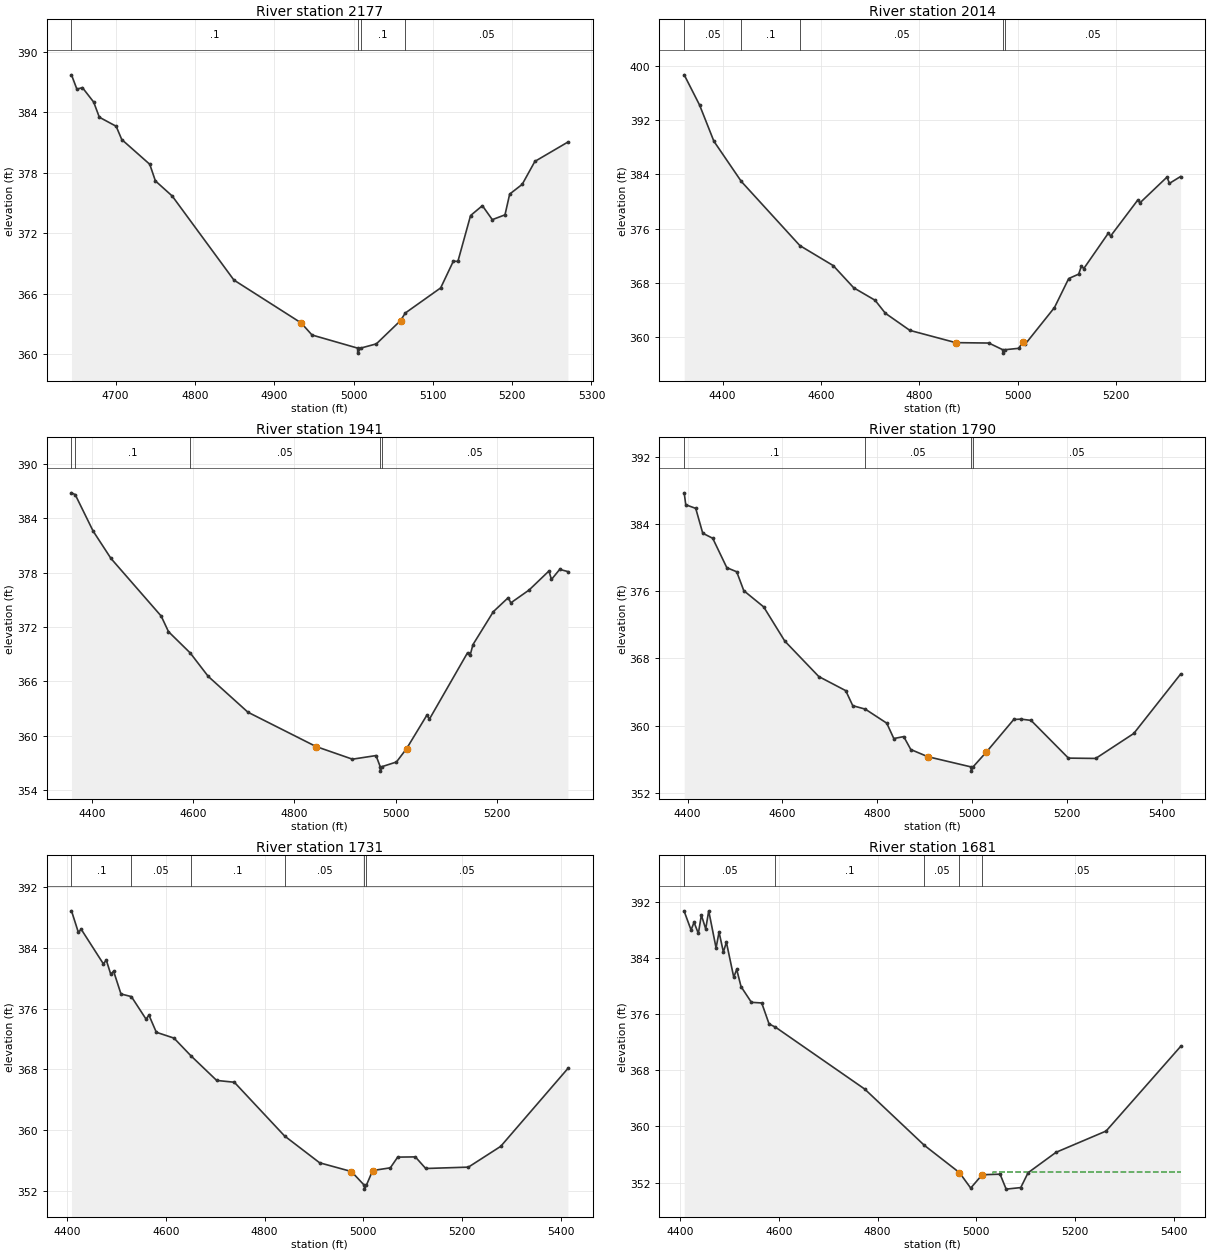
Type RM Length L Ch R = 1 ,2177    ,163,163,163
BEGIN DESCRIPTION:
HOLLY BRANCH TRIB 2 7 0
END DESCRIPTION:
XS GIS Cut Line= 3
      3538434.84      10408068.5      3538227.09     10407859.38
        3537938.     10407697.91
#Sta/Elev= 30
  4644.4  387.73  4651.2  386.31  4658.2  386.46  4672.4  385.02  4679.5  383.52
  4700.7  382.62  4707.8   381.3  4743.1  378.84  4750.2  377.19  4771.4  375.69
  4849.2  367.34    4934  363.08  4947.7  361.88  5005.1  360.58  5005.3  360.08
  5009.1  360.58  5028.8     361  5059.4  363.32  5065.2  364.06  5109.9  366.56
  5125.9  369.22  5131.6  369.19  5147.6  373.75  5162.5  374.73    5175  373.34
    5191  373.82  5196.9  375.88  5212.7  376.85  5228.7  379.13  5270.3  381.05
#Mann= 4 ,-1 , 0
  4644.4      .1       0  5005.1     .07       0  5009.1      .1       0
  5065.2     .05       0
Bank Sta=4934,5059.4
XS Rating Curve= 0 ,0
Exp/Cntr=0.3,0.1

Type RM Length L Ch R = 1 ,2014    ,73,73,73
BEGIN DESCRIPTION:
HOLLY BRANCH TRIB 2 4 4
END DESCRIPTION:
XS GIS Cut Line= 3
        3538713.     10408054.92      3538228.64     10407679.94
      3537838.01     10407612.23
#Sta/Elev= 30
  4322.1  398.71  4353.4  394.24  4382.4  388.91  4438.2  382.96  4557.3  373.48
    4625  370.53  4666.7  367.25  4710.1  365.41    4731  363.49  4780.8  360.96
    4874  359.15  4941.3  359.09  4969.7   358.1    4970   357.6  4973.7   358.1
  5002.2  358.31  5009.9   359.2  5014.9  358.89  5074.7  364.33  5103.7  368.62
    5124  369.27  5129.3  370.44  5134.4   370.1    5184   375.3    5189  374.91
  5243.7  380.18  5248.8  379.82  5303.4   383.6  5308.5  382.68  5331.1  383.69
#Mann= 5 ,-1 , 0
  4322.1     .05       0  4438.2      .1       0  4557.3     .05       0
  4969.7     .03       0  4973.7     .05       0
Bank Sta=4874,5009.9
XS Rating Curve= 0 ,0
Exp/Cntr=0.3,0.1

Type RM Length L Ch R = 1 ,1941    ,151,151,151
BEGIN DESCRIPTION:
HOLLY BRANCH TRIB 2 4 3
END DESCRIPTION:
XS GIS Cut Line= 3
      3538676.58     10407966.41      3538218.22     10407601.81
        3537826.     10407552.46
#Sta/Elev= 30
  4359.4  386.83  4366.8  386.63  4402.1  382.61  4437.4  379.58  4536.7  373.21
  4551.1  371.49    4594  369.14  4629.6  366.55  4708.1  362.59  4842.6   358.8
  4914.6   357.4  4961.3   357.8  4969.4  356.58  4969.7  356.08  4973.4  356.58
  5001.6  357.09  5021.8  358.58  5061.8  362.27  5066.9  361.84  5142.2  369.17
  5147.2  368.88  5152.8  370.06  5193.1   373.7  5222.6  375.25  5227.6  374.67
  5263.7  376.09  5302.9  378.19    5308  377.26  5324.2  378.37  5340.4  378.13
#Mann= 5 ,-1 , 0
  4359.4     .05       0  4366.8      .1       0    4594     .05       0
  4969.4     .03       0  4973.4     .05       0
Bank Sta=4842.6,5021.8
XS Rating Curve= 0 ,0
Exp/Cntr=0.3,0.1

Type RM Length L Ch R = 1 ,1790    ,59,59,59
BEGIN DESCRIPTION:
HOLLY BRANCH TRIB 2 4 5
END DESCRIPTION:
XS GIS Cut Line= 3
      3538668.72     10407789.29      3538218.22     10407476.81
      3537798.94     10407208.58
#Sta/Elev= 30
    4393  387.72  4396.3   386.3  4417.3  385.87  4432.1  382.91  4453.1  382.31
  4482.8  378.81  4503.7  378.32  4518.6  376.07  4560.5  374.14    4605  370.07
  4676.6  365.85  4733.4  364.17  4748.2  362.38  4774.6  361.97  4819.8   360.3
  4834.7  358.47  4855.6   358.7  4870.5  357.16  4906.3  356.31  4997.6  355.09
  4997.8  354.59  5001.6  355.09    5030  356.88  5087.5  360.74  5102.7  360.78
  5123.9  360.63  5202.6  356.14  5260.1   356.1  5340.3  359.07    5439  366.14
#Mann= 4 ,-1 , 0
    4393      .1       0  4774.6     .05       0  4997.6     .03       0
  5001.6     .05       0
#XS Ineff= 1 ,-1
 5089.24 5371.08   360.5
Permanent Ineff=
       T
Bank Sta=4906.3,5030
XS Rating Curve= 0 ,0
Exp/Cntr=0.3,0.1

Type RM Length L Ch R = 1 ,1731    ,50,50,50
BEGIN DESCRIPTION:
HOLLY BRANCH TRIB 2 5 0
END DESCRIPTION:
XS GIS Cut Line= 3
      3538658.32     10407724.64      3538199.95     10407406.78
      3537831.51     10407151.73
#Sta/Elev= 30
  4408.7   388.9  4422.5  386.09  4428.6  386.45  4473.2  381.92  4479.3  382.39
  4488.1  380.57  4494.1  380.93    4509  377.94  4530.1  377.59  4559.7  374.63
  4565.7  375.14  4580.6  372.89  4616.4  372.12  4650.7  369.79  4702.9  366.54
  4738.7   366.3  4840.5  359.22  4911.6  355.68    4976  354.53  5002.2  352.71
  5002.4  352.21  5006.2  352.71    5019  354.66  5054.8  355.02  5069.7  356.43
  5105.5  356.46  5126.5  354.93    5213  355.11  5278.5  357.85  5414.6  368.12
#Mann= 6 ,-1 , 0
  4408.7      .1       0  4530.1     .05       0  4650.7      .1       0
  4840.5     .05       0  5002.2     .03       0  5006.2     .05       0
Bank Sta=4976,5019
XS Rating Curve= 0 ,0
Exp/Cntr=0.3,0.1

Type RM Length L Ch R = 1 ,1681    ,134,134,134
BEGIN DESCRIPTION:
HOLLY BRANCH TRIB 2 4 0
END DESCRIPTION:
XS GIS Cut Line= 3
       3538658.3     10407674.71      3538199.95     10407356.87
      3537831.49      10407101.8
#Sta/Elev= 30
  4408.2  390.65  4422.1  387.99  4428.2  389.08  4436.9  387.49    4443  390.11
  4451.8  388.14  4457.9  390.72  4472.8  385.43  4478.8   387.7  4487.6  384.85
  4493.7  386.25  4508.6  381.27  4514.6  382.37  4523.4  379.92  4544.4  377.68
  4565.3  377.59  4580.2   374.6  4593.2  374.14    4774  365.32  4894.7  357.31
    4966  353.41  4988.8  351.21    5012  353.11  5048.3  353.19  5060.6  351.06
  5090.2  351.28  5105.1   353.4  5161.8  356.31  5263.2  359.34  5414.1  371.39
#Mann= 5 ,-1 , 0
  4408.2     .05       0  4593.2      .1       0  4894.7     .05       0
    4966     .03       0    5012     .05       0
#XS Ineff= 2 , 0
                         5033.14          353.52
Permanent Ineff=
       T       T
Bank Sta=4966,5012
XS Rating Curve= 0 ,0
Exp/Cntr=0.3,0.1

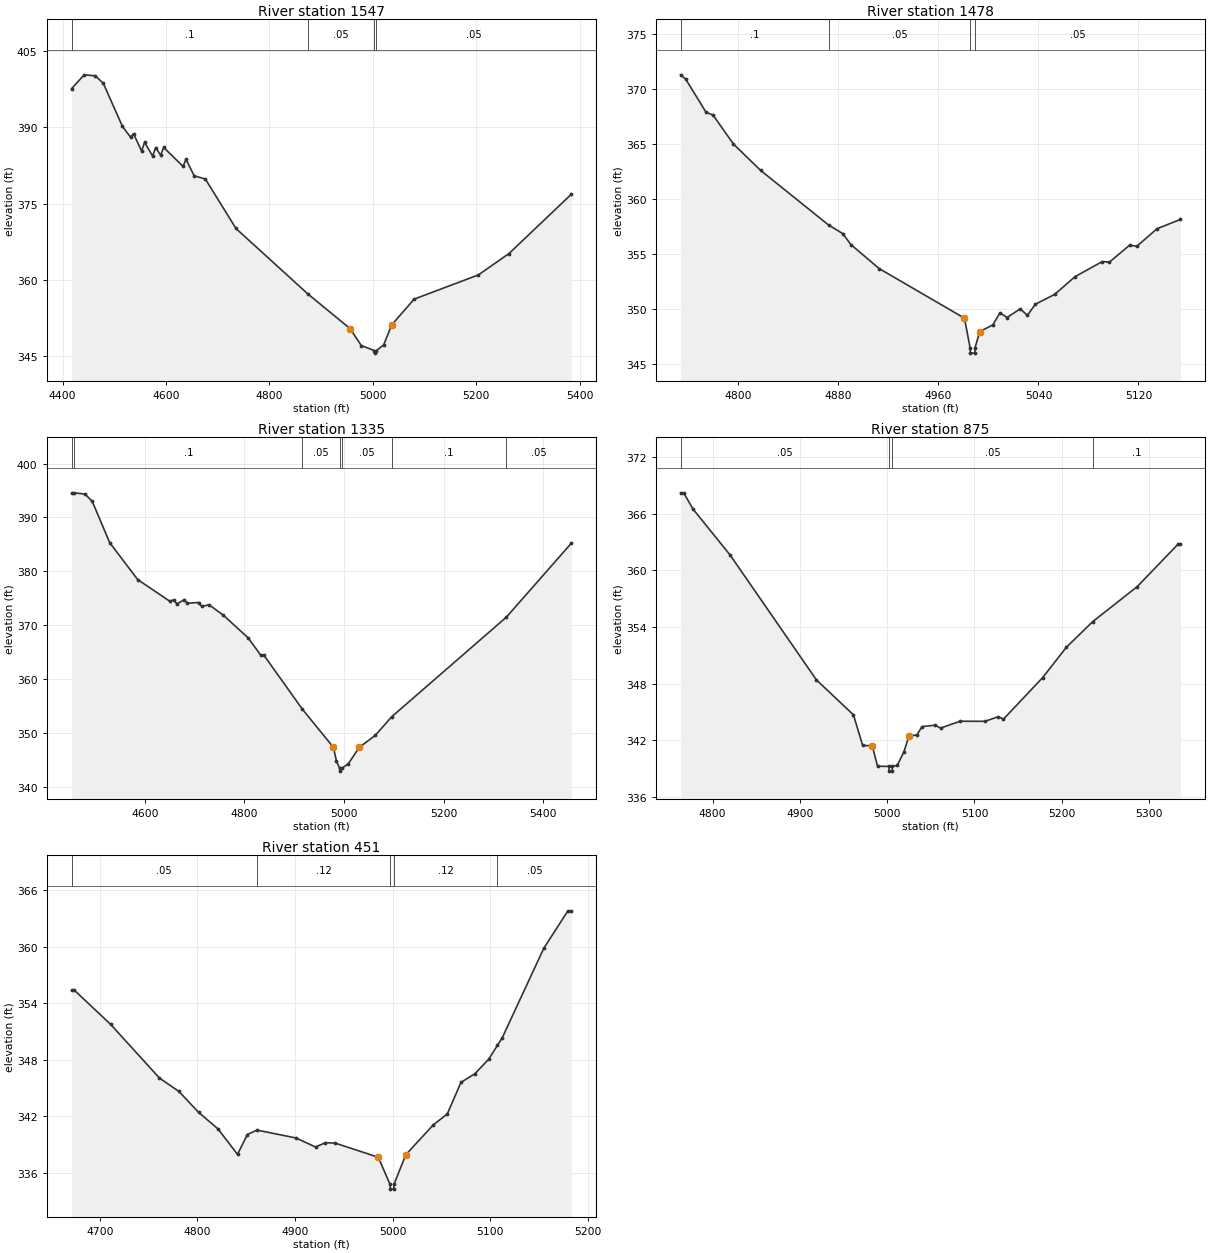
Type RM Length L Ch R = 1 ,1547    ,69,69,69
BEGIN DESCRIPTION:
HOLLY BRANCH TRIB 2 6 0
END DESCRIPTION:
XS GIS Cut Line= 3
      3538660.47     10407507.61        3538501.     10407412.19
      3537822.21      10407026.8
#Sta/Elev= 30
  4417.7  397.66    4442  400.36  4463.4  400.17  4478.9  398.69  4515.9  390.21
  4531.5  388.11  4537.3   388.8  4552.9  385.35  4558.7  387.08  4574.3  384.37
  4580.1  386.04  4589.8  384.54  4595.6  386.07    4633  382.35  4638.8  383.72
  4654.6   380.5  4676.3  379.84  4735.4  370.12  4874.3  357.25    4956  350.42
  4977.7  347.09    5003  346.09  5003.3  345.59    5007  346.09  5020.9   347.2
  5036.8  351.19    5080  356.22  5204.1  360.98  5263.2  365.18  5384.1  376.88
#Mann= 4 ,-1 , 0
  4417.7      .1       0  4874.3     .05       0    5003     .03       0
    5007     .05       0
Bank Sta=4956,5036.8
XS Rating Curve= 0 ,0
Exp/Cntr=0.3,0.1

Type RM Length L Ch R = 1 ,1478    ,143,143,143
BEGIN DESCRIPTION:
Mapping XS 51cc1ff4
END DESCRIPTION:
XS GIS Cut Line= 2
        3538392.     10407267.87      3538039.95     10407078.18
#Sta/Elev= 30
  4753.7  371.26  4757.8  370.86    4774  367.87  4779.7   367.6  4795.9  364.99
  4817.8  362.58  4872.1  357.63  4883.5  356.85  4889.9  355.86  4912.6  353.68
  4980.8  349.18  4985.3  346.51  4985.6  346.01  4989.1  346.01  4989.3  346.51
    4993  347.96  5003.5  348.57  5009.2  349.67  5014.9  349.24  5025.4  350.03
  5031.1  349.44  5037.6  350.45    5053  351.34  5069.2  352.94  5091.1  354.32
  5096.8  354.27    5113  355.81  5118.7   355.7  5134.9   357.3  5153.6  358.14
#Mann= 4 ,-1 , 0
  4753.7      .1       0  4872.1     .05       0  4985.3     .03       0
  4989.3     .05       0
Bank Sta=4980.8,4993
XS Rating Curve= 0 ,0
Exp/Cntr=0.3,0.1

Type RM Length L Ch R = 1 ,1335    ,460,460,460
BEGIN DESCRIPTION:
HOLLY BRANCH TRIB 2 4 2
END DESCRIPTION:
XS GIS Cut Line= 5
      3538695.21     10407375.24      3538392.11     10407141.64
      3538259.98     10407043.93      3538142.11     10406991.64
      3537842.39     10406858.77
#Sta/Elev= 30
    4453  394.56  4458.3  394.57  4479.7  394.34  4494.2  393.01  4529.5   385.3
  4585.6  378.45  4649.9  374.44  4658.1  374.68  4664.4  373.91    4679  374.71
  4685.3  374.06    4708  374.19  4714.3  373.46  4728.8  373.78  4757.8  371.82
  4807.6  367.61  4832.5  364.44  4838.8  364.44  4916.5  354.35  4978.7  347.28
  4984.9  344.69  4991.3  343.36  4991.5  342.86  4995.3  343.36  5008.6  344.22
  5030.5  347.27  5062.6  349.48  5095.4  352.93  5326.1  371.47  5456.8  385.23
#Mann= 7 ,-1 , 0
    4453     .05       0  4458.3      .1       0  4916.5     .05       0
  4991.3     .03       0  4995.3     .05       0  5095.4      .1       0
  5326.1     .05       0
Bank Sta=4978.7,5030.5
XS Rating Curve= 0 ,0
Exp/Cntr=0.3,0.1

Type RM Length L Ch R = 1 ,875     ,424,424,424
BEGIN DESCRIPTION:
HOLLY BRANCH TRIB 2 4 1
END DESCRIPTION:
XS GIS Cut Line= 3
       3538742.1     10406991.64      3538592.11     10406841.64
      3538292.09     10406641.63
#Sta/Elev= 30
  4763.3  368.23  4766.8  368.23  4777.4  366.52  4819.9  361.65  4918.9   348.4
  4961.3   344.7  4971.9  341.45  4982.9  341.42  4988.9  339.25    5002  339.23
  5002.2  338.73  5005.7  338.73    5006  339.23  5011.5  339.34    5019  340.73
    5025  342.47    5034  342.56    5040  343.45    5055   343.6  5061.1  343.29
  5083.6  344.02  5112.1  344.01  5127.2   344.5  5133.2  344.24  5178.2  348.65
  5205.3  351.86  5235.4  354.57  5286.4  358.28    5333  362.76    5336  362.76
#Mann= 4 ,-1 , 0
  4763.3     .05       0    5002     .03       0    5006     .05       0
  5235.4      .1       0
Bank Sta=4982.9,5025
XS Rating Curve= 0 ,0
Exp/Cntr=0.3,0.1

Type RM Length L Ch R = 1 ,451     ,0,0,0
BEGIN DESCRIPTION:
HOLLY BRANCH TRIB 2 1 0
END DESCRIPTION:
XS GIS Cut Line= 3
      3538942.11     10406941.66      3538942.11     10406641.64
      3538792.07     10406491.61
#Sta/Elev= 30
  4671.1   355.4  4673.6   355.4  4711.1  351.75  4761.1  346.06  4781.1  344.64
  4801.1  342.44  4821.1  340.67  4841.1  337.97  4851.1  340.07  4860.9  340.55
  4901.1  339.71  4921.1  338.75  4931.1  339.21  4941.1  339.17  4985.3  337.67
  4997.4  334.79  4997.7  334.29  5001.2  334.29  5001.4  334.79  5013.5  337.93
  5041.8  341.11    5056  342.25  5070.1  345.61  5084.3  346.52  5098.4  348.05
  5107.4  349.52  5112.5  350.36    5155  359.83  5179.7  363.79  5183.3  363.79
#Mann= 5 ,-1 , 0
  4671.1     .05       0  4860.9     .12       0  4997.4     .07       0
  5001.4     .12       0  5107.4     .05       0
Bank Sta=4985.3,5013.5
XS Rating Curve= 0 ,0
Exp/Cntr=0.3,0.1

Chan Stop Cuts=-1
Use User Specified Reach Order=0
Composite Channel Slope=5