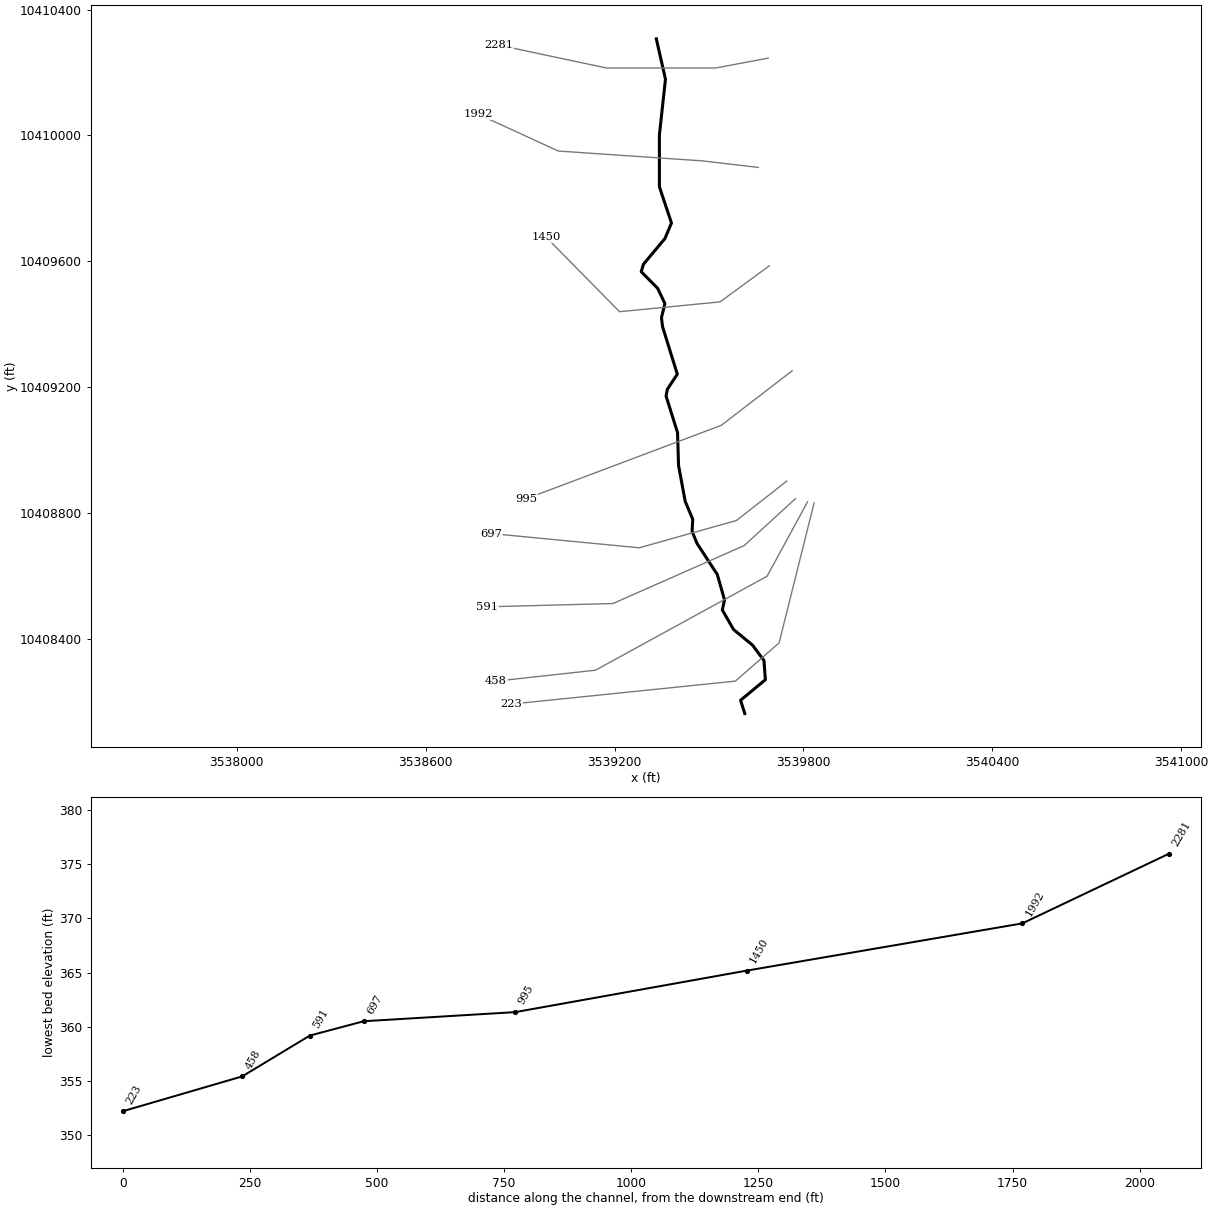
--- HOLLY BRANCH TRIBUTARY 3.prj (project) ---

Proj Title=HOLLY BRANCH TRIBUTARY 3 Base Level Engineering
Current Plan=p01
Default Exp/Contr=0.3,0.1
English Units
Geom File=g01
Flow File=f01
Plan File=p01
Y Axis Title=Elevation
X Axis Title(PF)=Main Channel Distance
X Axis Title(XS)=Station
BEGIN DESCRIPTION:
HOLLY BRANCH TRIBUTARY 3
END DESCRIPTION:
DSS Export Rating Curves= 0
DSS Export Rating Curve Sorted= 0
DSS Export Volume Flow Curves= 0
DXF OffsetX= 0
DXF OffsetY= 0
DXF ScaleX= 1
DXF ScaleY= 10

--- HOLLY BRANCH TRIBUTARY 3.p01 (plan) ---

Plan Title=Multiple Run
Short Identifier=Multiple
Geom File=g01
Flow File=f01
Subcritical Flow
K Sum by GR= 0
Std Step Tol= 0.01
Critical Tol= 0.01
Num of Std Step Trials= 20
Max Error Tol= 0.3
Flow Tol Ratio= 0.001
Split Flow NTrial= 30
Split Flow Tol= 0.02
Split Flow Ratio= 0.02
Log Output Level= 0
Friction Slope Method= 1
Unsteady Friction Slope Method= 2
Unsteady Bridges Friction Slope Method= 1
Parabolic Critical Depth
Global Vel Dist=  1 , 1 , 1
Global Log Level= 0
CheckData=True
Encroach Param= -1, 0, 0, 0
BEGIN DESCRIPTION:
Multiple Run
END DESCRIPTION:

--- HOLLY BRANCH TRIBUTARY 3.f01 (steady flow) ---

Flow Title=Multiple
Program Version=4.10
Number of Profiles= 7
Profile Names=10-year,25-year,50-year,1pct_min,100-year,1pct_plu,500-year
River Rch & RM=HOLLY BRANCH TRI,Reach-1         ,2281
     542     725     872     769    1040    1406    1469
Boundary for River Rch & Prof#=HOLLY BRANCH TRI,Reach-1         , 1
Up Type= 0
Dn Type= 3
Dn Slope=0.019
Boundary for River Rch & Prof#=HOLLY BRANCH TRI,Reach-1         , 2
Up Type= 0
Dn Type= 3
Dn Slope=0.019
Boundary for River Rch & Prof#=HOLLY BRANCH TRI,Reach-1         , 3
Up Type= 0
Dn Type= 3
Dn Slope=0.019
Boundary for River Rch & Prof#=HOLLY BRANCH TRI,Reach-1         , 4
Up Type= 0
Dn Type= 3
Dn Slope=0.019
Boundary for River Rch & Prof#=HOLLY BRANCH TRI,Reach-1         , 5
Up Type= 0
Dn Type= 3
Dn Slope=0.019
Boundary for River Rch & Prof#=HOLLY BRANCH TRI,Reach-1         , 6
Up Type= 0
Dn Type= 3
Dn Slope=0.019
Boundary for River Rch & Prof#=HOLLY BRANCH TRI,Reach-1         , 7
Up Type= 0
Dn Type= 3
Dn Slope=0.019
DSS Import GetInterval= 0
DSS Import GetPeak= 0
DSS Import FillOption= 0

--- HOLLY BRANCH TRIBUTARY 3.g01 (geometry) ---

Geom Title=Existing Conditions
Program Version=4.10

River Reach=HOLLY BRANCH TRI,Reach-1
Reach XY= 30
      3539332.79     10410306.93      3539361.84     10410178.91
      3539342.54     10410001.46      3539342.64     10409836.86
      3539380.96     10409721.96      3539360.02     10409672.53
      3539292.05     10409591.22      3539284.72     10409567.41
      3539337.18     10409514.34      3539360.08     10409465.93
      3539349.09     10409421.28      3539352.73     10409392.04
       3539399.5     10409241.67      3539367.88     10409193.88
      3539363.72     10409172.18      3539400.21     10409056.06
      3539403.38     10408951.77      3539424.61     10408837.63
      3539448.54     10408780.53       3539446.4     10408742.33
      3539462.25     10408703.71      3539526.48     10408605.44
       3539549.4     10408524.89      3539542.46      10408492.6
      3539578.22     10408430.44      3539638.29     10408381.14
      3539674.75     10408332.18      3539679.26     10408271.07
      3539600.44     10408205.79      3539613.79     10408163.49

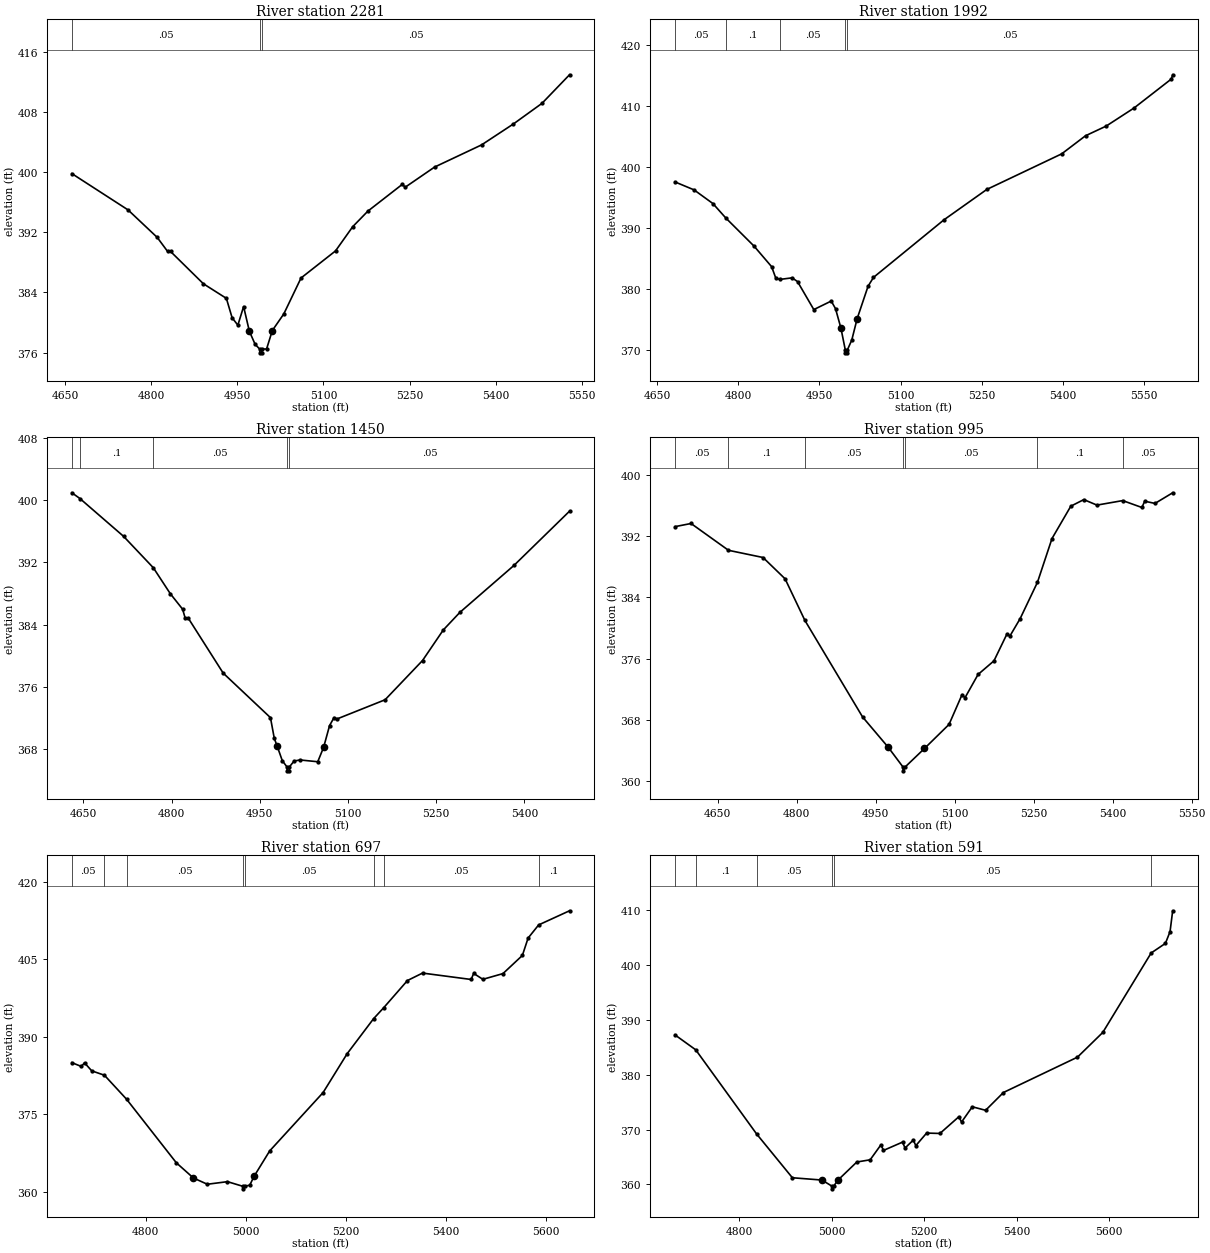
Type RM Length L Ch R = 1 ,2281    ,289,289,289
BEGIN DESCRIPTION:
HOLLY BRANCH TRIBUTARY 3 4.0
END DESCRIPTION:
XS GIS Cut Line= 4
      3539688.19     10410245.74       3539521.5     10410214.49
      3539174.28     10410214.49       3538832.3     10410287.03
#Sta/Elev= 30
  4662.1  399.81  4759.9  394.98  4810.7  391.32  4828.8  389.45  4833.9  389.45
  4891.1  385.15  4931.1  383.21  4941.1  380.63  4951.1  379.64  4961.1  382.12
  4971.1  378.84  4981.1   377.1  4989.1  376.46  4989.3  375.96  4992.8  375.96
  4993.1  376.46  5001.1  376.47  5011.1  378.93  5031.1  381.14  5061.1  385.92
  5121.1  389.52  5151.1  392.75  5177.5  394.82  5237.4  398.38  5242.5     398
  5293.6  400.68  5375.4  403.63  5430.9  406.42  5480.6  409.16  5528.5  412.96
#Mann= 3 ,-1 , 0
  4662.1     .05       0  4989.1     .03       0  4993.1     .05       0
Bank Sta=4971.1,5011.1
XS Rating Curve= 0 ,0
Exp/Cntr=0.3,0.1

Type RM Length L Ch R = 1 ,1992    ,542,542,542
BEGIN DESCRIPTION:
Mapping XS b9ae3a68
END DESCRIPTION:
XS GIS Cut Line= 4
      3539656.97     10409898.51      3539479.84     10409919.35
       3539021.5      10409950.6      3538765.85     10410068.06
#Sta/Elev= 30
  4683.5  397.58  4718.6  396.28  4753.5  394.03  4777.3  391.66  4829.4  387.05
  4861.9  383.67  4869.6  381.79  4877.1  381.58  4899.7  381.84  4909.7  381.23
  4939.8  376.63    4972  378.03  4979.9  376.78  4989.9  373.58  4997.9  370.03
  4998.2  369.53  5001.7  369.53  5001.9  370.03  5009.9  371.62  5019.9  375.15
    5040  380.46    5050  381.91  5180.3  391.37  5259.3  396.35  5397.6  402.19
  5441.6  405.16  5479.8  406.75  5531.3  409.72  5600.2  414.48  5602.6  415.17
#Mann= 5 ,-1 , 0
  4683.5     .05       0  4777.3      .1       0  4877.1     .05       0
  4997.9     .03       0  5001.9     .05       0
Bank Sta=4989.9,5019.9
XS Rating Curve= 0 ,0
Exp/Cntr=0.3,0.1

Type RM Length L Ch R = 1 ,1450    ,455,455,455
BEGIN DESCRIPTION:
HOLLY BRANCH TRIBUTARY 3 3.0
END DESCRIPTION:
XS GIS Cut Line= 4
      3539691.62       10409586.      3539535.39     10409471.43
      3539215.95     10409440.18      3538983.29     10409676.32
#Sta/Elev= 30
  4630.5  400.94  4644.2   400.2  4718.4  395.34  4769.1  391.29  4797.9  387.96
  4818.8  385.97  4823.2  384.82  4828.4  384.82  4887.8  377.75  4968.2  372.02
  4974.7  369.36  4979.7  368.34  4988.3  366.49  4996.3  365.68  4996.6  365.18
  5000.1  365.18  5000.3  365.68  5008.4  366.44  5018.4  366.58  5048.6  366.35
  5058.6  368.21  5068.7     371  5076.3  372.03  5081.3  371.85  5163.1  374.32
  5226.8  379.37  5262.1   383.3  5290.3  385.56  5382.3   391.6  5476.7  398.57
#Mann= 5 ,-1 , 0
  4630.5     .05       0  4644.2      .1       0  4769.1     .05       0
  4996.3     .03       0  5000.3     .05       0
Bank Sta=4979.7,5058.6
XS Rating Curve= 0 ,0
Exp/Cntr=0.3,0.1

Type RM Length L Ch R = 1 ,995     ,298,298,298
BEGIN DESCRIPTION:
Mapping XS fced25ec
END DESCRIPTION:
XS GIS Cut Line= 3
      3539764.52     10409252.65      3539538.86     10409079.07
      3538921.08     10408846.53
#Sta/Elev= 30
  4569.2  393.24  4599.6  393.65  4670.7  390.15  4736.3  389.21  4778.1  386.43
  4815.8  380.99  4925.2   368.4  4973.8  364.45    5002  361.86  5002.3  361.36
    5006  361.86  5042.8  364.28  5089.4  367.42  5114.2  371.32  5119.6  370.89
  5144.5  373.94  5174.7  375.72  5199.6  379.26  5204.9  378.95  5224.4  381.23
  5257.3  385.98  5284.9  391.69  5320.6  395.91  5345.3  396.77  5370.2  396.05
  5419.1  396.64  5455.5  395.74  5460.9  396.56  5480.4  396.27    5514  397.66
#Mann= 7 ,-1 , 0
  4569.2     .05       0  4670.7      .1       0  4815.8     .05       0
    5002     .03       0    5006     .05       0  5257.3      .1       0
  5419.1     .05       0
Bank Sta=4973.8,5042.8
XS Rating Curve= 0 ,0
Exp/Cntr=0.3,0.1

Type RM Length L Ch R = 1 ,697     ,106,106,106
BEGIN DESCRIPTION:
Mapping XS 14575a5a
END DESCRIPTION:
XS GIS Cut Line= 4
      3539747.23     10408902.02      3539587.47     10408776.99
      3539278.45     10408690.18      3538809.67     10408735.32
#Sta/Elev= 30
  4652.1  384.97    4671  384.23  4677.4  384.94  4691.8  383.38  4717.2  382.53
  4761.4  377.89    4861  365.56  4895.1  362.62  4922.9  361.41  4963.2  361.91
  4993.6  361.02  4993.8  360.52  4997.6  361.02  5007.7  361.23  5016.3  362.94
  5047.5  367.86  5154.3  379.17  5202.4   386.7  5255.2  393.48  5275.3  395.59
    5323  400.88  5353.1  402.32  5450.3  401.08  5455.3  402.26  5473.7  401.11
  5513.9  402.22  5552.7  405.74  5564.1   409.1  5585.2  411.65  5646.9  414.39
#Mann= 8 ,-1 , 0
  4652.1     .05       0  4717.2      .1       0  4761.4     .05       0
  4993.6     .03       0  4997.6     .05       0  5255.2      .1       0
  5275.3     .05       0  5585.2      .1       0
Bank Sta=4895.1,5016.3
XS Rating Curve= 0 ,0
Exp/Cntr=0.3,0.1

Type RM Length L Ch R = 1 ,591     ,133,133,133
BEGIN DESCRIPTION:
HOLLY BRANCH TRIBUTARY 3 2.0
END DESCRIPTION:
XS GIS Cut Line= 4
      3539774.96     10408846.42      3539611.78     10408697.13
      3539195.11      10408513.1      3538796.41      10408502.7
#Sta/Elev= 30
  4661.4  387.24  4706.1  384.53  4837.6  369.21    4915  361.22    4979   360.8
  5000.3   359.7  5000.5   359.2  5004.3   359.7  5013.4  360.78  5054.3  364.09
  5083.1  364.49  5106.4  367.22  5111.9   366.2    5153  367.71  5158.5  366.64
  5176.3  368.08  5181.8  367.07  5205.1  369.36  5233.9  369.29    5275  372.35
  5280.5  371.35  5303.8  374.15  5332.6  373.51  5371.1  376.75  5531.1  383.19
  5585.9   387.7  5690.4  402.17  5721.2  403.92  5731.2  406.06  5736.9  409.86
#Mann= 6 ,-1 , 0
  4661.4     .05       0  4706.1      .1       0  4837.6     .05       0
  5000.3     .03       0  5004.3     .05       0  5690.4      .1       0
Bank Sta=4979,5013.4
XS Rating Curve= 0 ,0
Exp/Cntr=0.3,0.1

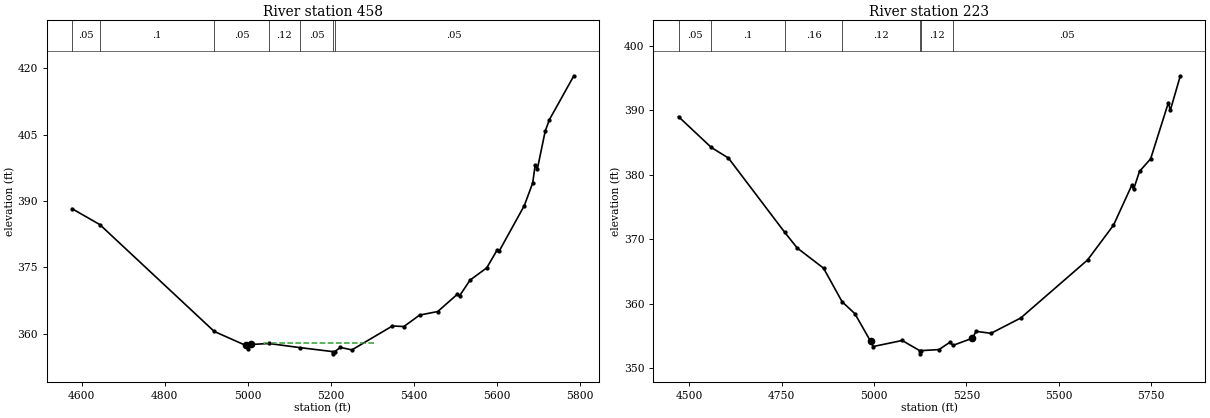
Type RM Length L Ch R = 1 ,458     ,235,235,235
BEGIN DESCRIPTION:
Mapping XS 4e593571
END DESCRIPTION:
XS GIS Cut Line= 4
      3539813.18     10408836.04       3539684.7      10408599.9
      3539139.56     10408301.29      3538823.55     10408266.57
#Sta/Elev= 30
  4576.6  388.24  4643.4  384.65  4918.9   360.5  4994.4  357.36  5000.1  356.59
    5008  357.56  5050.5  357.78    5125  356.85  5204.8  355.94  5205.1  355.44
  5208.8  355.94  5222.9  356.89  5250.4  356.33  5348.1  361.74  5375.6  361.61
  5413.5   364.2  5457.1     365  5504.6  368.93  5509.6  368.53  5534.8  372.09
  5575.1  374.87  5600.7  378.98  5605.7  378.76  5665.6  388.94  5685.8  394.07
  5691.7  398.07  5696.8  397.13  5715.9  405.77    5726  408.36  5784.9  418.28
#Mann= 7 ,-1 , 0
  4576.6     .05       0  4643.4      .1       0  4918.9     .05       0
  5050.5     .12       0    5125     .05       0  5204.8     .03       0
  5208.8     .05       0
#XS Ineff= 1 ,-1
 5037.94 5307.56   357.8
Permanent Ineff=
       T
Bank Sta=4994.4,5008
XS Rating Curve= 0 ,0
Exp/Cntr=0.3,0.1

Type RM Length L Ch R = 1 ,223     ,0,0,0
BEGIN DESCRIPTION:
HOLLY BRANCH TRIBUTARY 3 1.0
END DESCRIPTION:
XS GIS Cut Line= 4
        3539834.     10408832.52      3539722.89      10408388.1
        3539584.     10408266.57      3538872.18     10408193.65
#Sta/Elev= 30
  4470.9  389.01  4559.7  384.23  4605.8   382.6  4758.5  371.06  4792.2  368.64
  4863.5  365.51  4913.7   360.3  4948.2  358.46  4990.9  354.16  4997.5  353.36
  5076.2   354.3  5123.5  352.73  5123.8  352.23  5127.5  352.73  5175.8  352.89
  5205.9  354.04  5213.6  353.54  5266.2  354.65  5276.3  355.72  5316.5  355.41
  5396.9  357.78  5577.9  366.78  5648.2  372.18  5697.5  378.35  5702.6  377.74
  5718.6  380.52  5748.8  382.48  5796.9   391.2  5801.9  389.97  5829.1  395.35
#Mann= 7 ,-1 , 0
  4470.9     .05       0  4559.7      .1       0  4758.5     .16       0
  4913.7     .12       0  5123.5     .07       0  5127.5     .12       0
  5213.6     .05       0
Bank Sta=4990.9,5266.2
XS Rating Curve= 0 ,0
Exp/Cntr=0.3,0.1

Chan Stop Cuts=-1
Use User Specified Reach Order=0
Composite Channel Slope=5