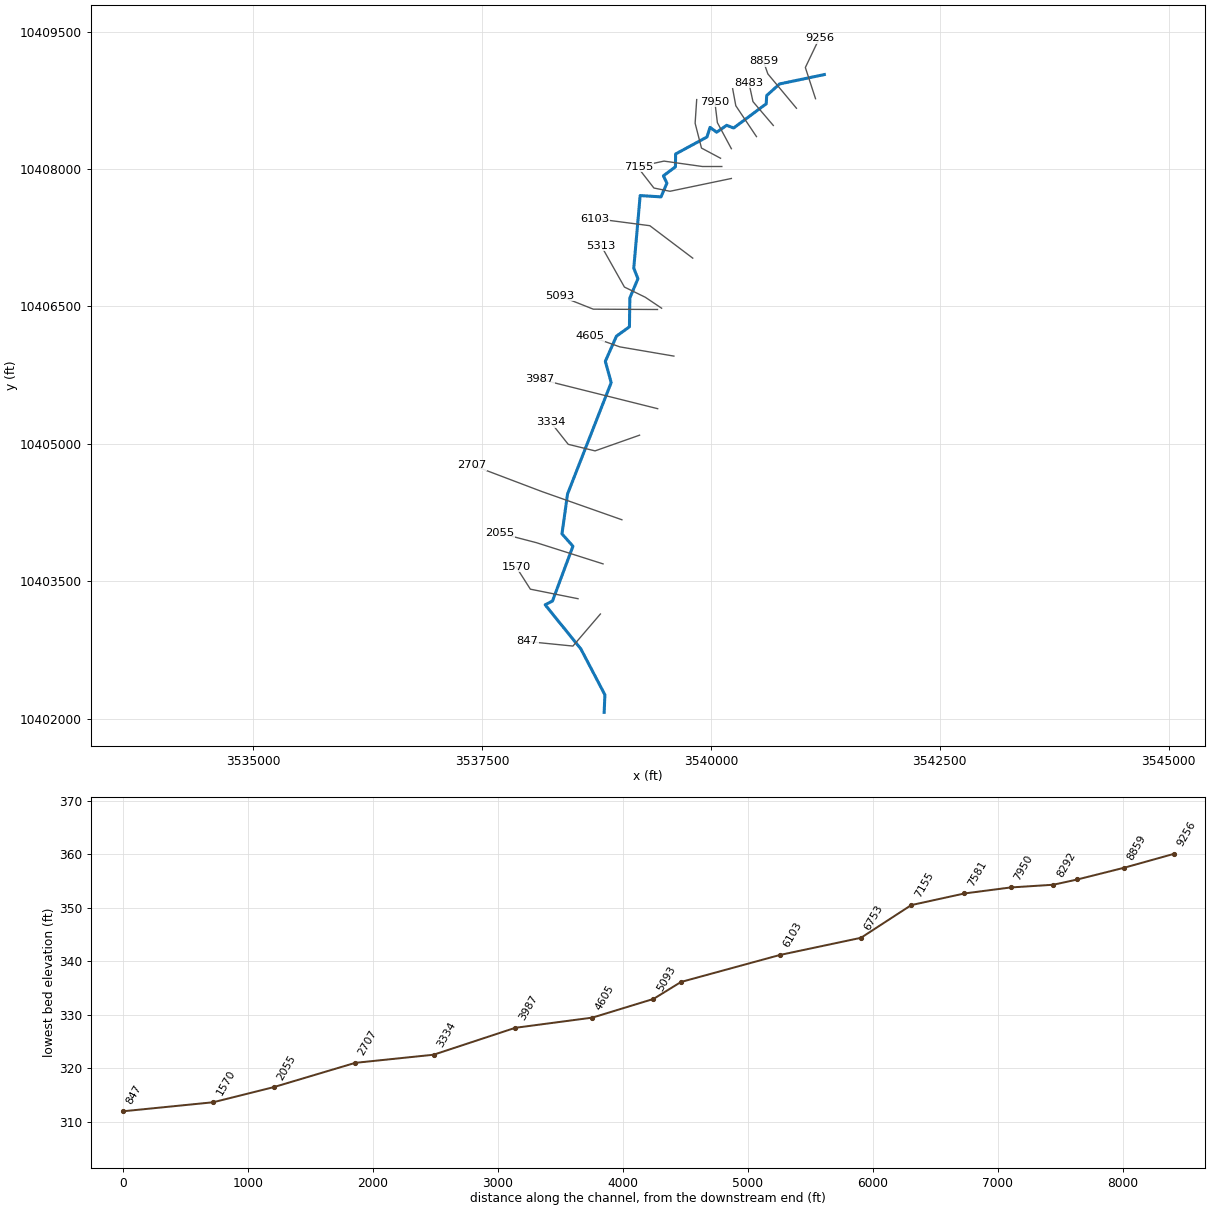
--- HOLLY BRANCH.prj (project) ---

Proj Title=HOLLY BRANCH Base Level Engineering
Current Plan=p01
Default Exp/Contr=0.3,0.1
English Units
Geom File=g01
Flow File=f01
Plan File=p01
Y Axis Title=Elevation
X Axis Title(PF)=Main Channel Distance
X Axis Title(XS)=Station
BEGIN DESCRIPTION:
cHOLLY BRANCH
END DESCRIPTION:
DSS Export Rating Curves= 0
DSS Export Rating Curve Sorted= 0
DSS Export Volume Flow Curves= 0
DXF OffsetX= 0
DXF OffsetY= 0
DXF ScaleX= 1
DXF ScaleY= 10

--- HOLLY BRANCH.p01 (plan) ---

Plan Title=Multiple Run
Short Identifier=Multiple
Geom File=g01
Flow File=f01
Subcritical Flow
K Sum by GR= 0
Std Step Tol= 0.01
Critical Tol= 0.01
Num of Std Step Trials= 20
Max Error Tol= 0.3
Flow Tol Ratio= 0.001
Split Flow NTrial= 30
Split Flow Tol= 0.02
Split Flow Ratio= 0.02
Log Output Level= 0
Friction Slope Method= 1
Unsteady Friction Slope Method= 2
Unsteady Bridges Friction Slope Method= 1
Parabolic Critical Depth
Global Vel Dist=  1 , 1 , 1
Global Log Level= 0
CheckData=True
Encroach Param= -1, 0, 0, 0
BEGIN DESCRIPTION:
Multiple Run
END DESCRIPTION:

--- HOLLY BRANCH.f01 (steady flow) ---

Flow Title=Multiple
Program Version=4.10
Number of Profiles= 7
Profile Names=10-year,25-year,50-year,1pct_min,100-year,1pct_plu,500-year
River Rch & RM=HOLLY BRANCH,Reach-1         ,9256
     424     552     652     563     762    1030    1036
River Rch & RM=HOLLY BRANCH,Reach-1         ,7155
    1034    1440    1779    1606    2172    2938    3229
River Rch & RM=HOLLY BRANCH,Reach-1         ,5093
    1719    2470    3119    2872    3884    5253    6011
River Rch & RM=HOLLY BRANCH,Reach-1         ,4605
    1719    2470    3119    2872    3884    5253    6011
River Rch & RM=HOLLY BRANCH,Reach-1         ,2707
    1913    2758    3489    3218    4351    5885    6753
River Rch & RM=HOLLY BRANCH,Reach-1         ,2055
    1913    2758    3489    3218    4351    5885    6753
Boundary for River Rch & Prof#=HOLLY BRANCH,Reach-1         , 1
Up Type= 0
Dn Type= 3
Dn Slope=0.005
Boundary for River Rch & Prof#=HOLLY BRANCH,Reach-1         , 2
Up Type= 0
Dn Type= 3
Dn Slope=0.005
Boundary for River Rch & Prof#=HOLLY BRANCH,Reach-1         , 3
Up Type= 0
Dn Type= 3
Dn Slope=0.005
Boundary for River Rch & Prof#=HOLLY BRANCH,Reach-1         , 4
Up Type= 0
Dn Type= 3
Dn Slope=0.005
Boundary for River Rch & Prof#=HOLLY BRANCH,Reach-1         , 5
Up Type= 0
Dn Type= 3
Dn Slope=0.005
Boundary for River Rch & Prof#=HOLLY BRANCH,Reach-1         , 6
Up Type= 0
Dn Type= 3
Dn Slope=0.005
Boundary for River Rch & Prof#=HOLLY BRANCH,Reach-1         , 7
Up Type= 0
Dn Type= 3
Dn Slope=0.005
DSS Import GetInterval= 0
DSS Import GetPeak= 0
DSS Import FillOption= 0

--- HOLLY BRANCH.g01 (geometry) ---

Geom Title=Existing Conditions
Program Version=4.10

River Reach=HOLLY BRANCH    ,Reach-1
Reach XY= 30
      3541238.85     10409030.69      3540749.44     10408928.26
      3540608.81     10408801.52       3540603.6     10408711.24
       3540247.7     10408447.35      3540171.31     10408476.87
      3540062.41     10408401.13      3539989.71      10408454.3
      3539956.08     10408349.05      3539613.79     10408163.49
      3539612.03     10408023.69      3539480.43     10407925.43
      3539518.62     10407844.87      3539454.62     10407695.59
      3539226.53     10407709.65      3539156.75     10406917.87
      3539202.14      10406801.9      3539113.73     10406591.93
      3539109.41     10406277.16      3538967.38     10406174.79
      3538846.09     10405900.23      3538910.02     10405667.65
      3538433.34     10404452.14      3538372.39     10404016.71
      3538492.11     10403881.64      3538268.45     10403282.92
      3538188.58     10403242.08      3538578.79     10402760.38
      3538841.12     10402259.82      3538833.53      10402068.2

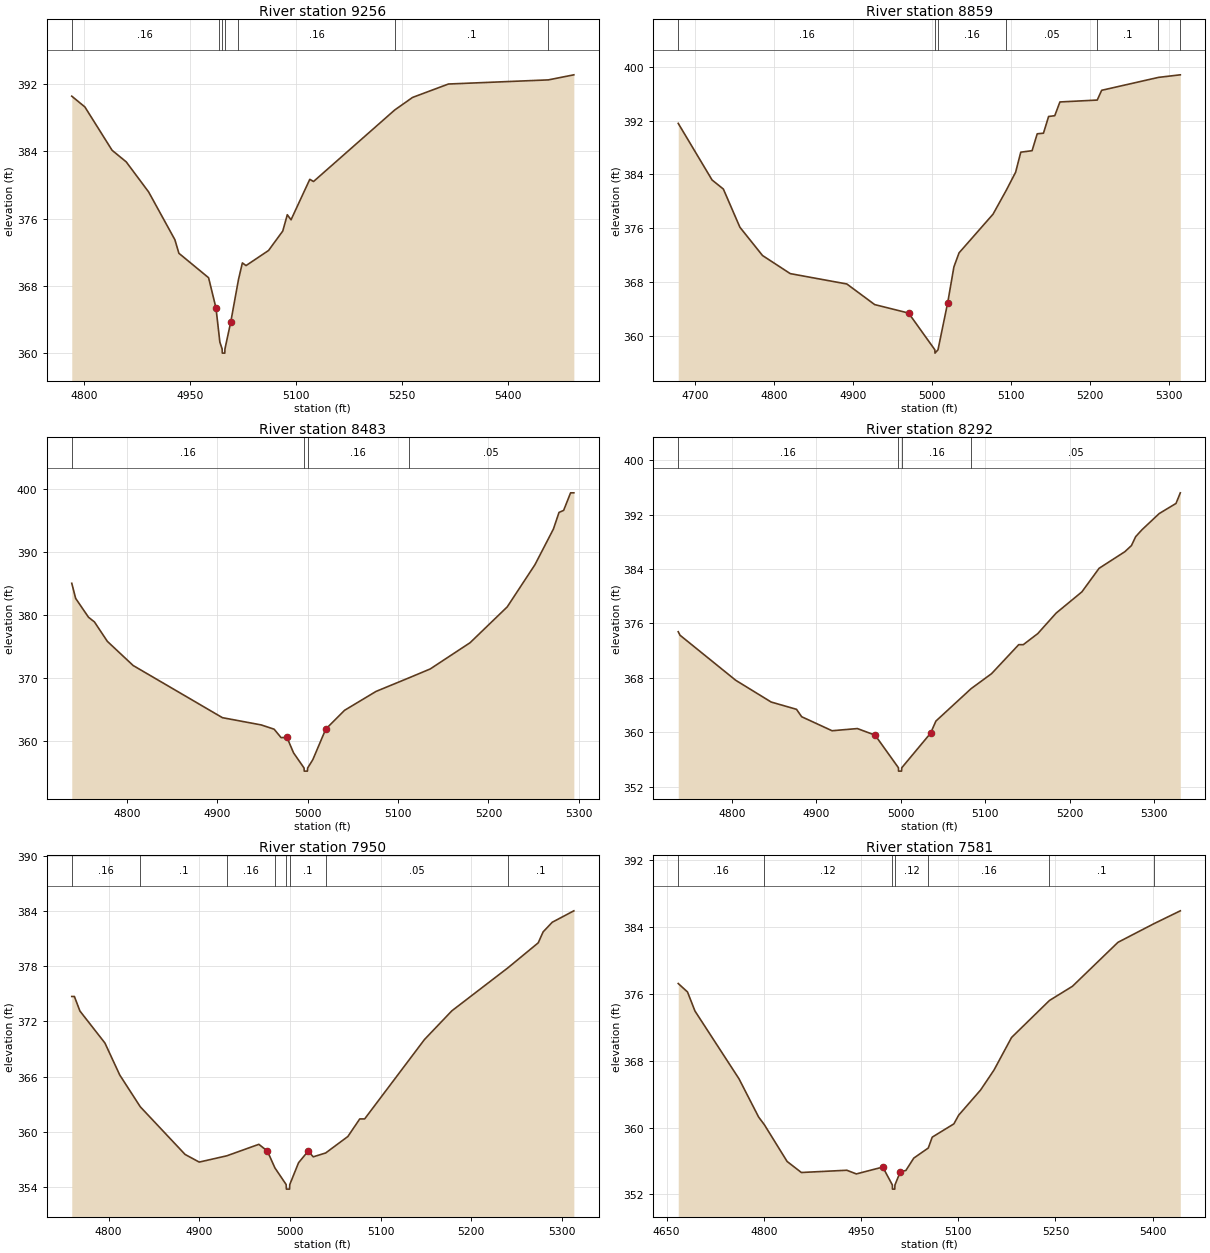
Type RM Length L Ch R = 1 ,9256    ,397,397,397
BEGIN DESCRIPTION:
HOLLY BRANCH 4 0
END DESCRIPTION:
XS GIS Cut Line= 3
      3541142.34     10408767.24      3541031.22     10409107.54
      3541183.92     10409426.82
#Sta/Elev= 30
    4782  390.51  4800.6  389.23  4839.2  384.09  4859.2  382.72    4891  379.15
  4928.2  373.49  4933.9  371.88    4976  368.98  4986.5  365.39  4990.3  362.59
    4992  361.34  4995.2  360.54  4995.5  360.04    4999  360.04  4999.2  360.54
  5007.5  363.76  5018.4  368.77  5023.9  370.74  5029.1  370.42    5061  372.21
  5081.2  374.52  5087.6  376.45  5092.9  375.85  5119.5  380.65  5124.8  380.39
  5239.9  388.87  5265.2  390.36  5316.1  391.95  5457.8  392.44  5493.9  393.04
#Mann= 7 ,-1 , 0
    4782     .16       0  4990.3      .1       0  4995.2     .07       0
  4999.2      .1       0  5018.4     .16       0  5239.9      .1       0
  5457.8     .05       0
Bank Sta=4986.5,5007.5
XS Rating Curve= 0 ,0
Exp/Cntr=0.3,0.1

Type RM Length L Ch R = 1 ,8859    ,376,376,376
BEGIN DESCRIPTION:
HOLLY BRANCH 3 0
END DESCRIPTION:
XS GIS Cut Line= 3
      3540933.98     10408663.12       3540621.5      10409038.1
      3540572.94     10409176.84
#Sta/Elev= 30
  4678.7  391.58  4721.5  383.17  4735.8  381.82  4756.7  376.15  4785.3  371.95
  4820.4  369.26    4892  367.72  4927.2  364.66  4970.1   363.4  5003.3  357.95
  5003.5  357.45  5007.3  357.95  5019.6  364.97  5027.4  370.25  5033.9  372.34
  5076.9  378.09  5093.6  381.63  5105.5  384.33    5112   387.3  5126.3  387.52
  5132.8  390.03  5140.7  390.12  5147.2   392.6    5155  392.72  5161.5  394.76
  5208.7  395.04  5214.3  396.49  5286.2  398.41  5313.6  398.79  5313.8  398.79
#Mann= 7 ,-1 , 0
  4678.7     .16       0  5003.3     .07       0  5007.3     .16       0
  5093.6     .05       0  5208.7      .1       0  5286.2     .05       0
  5313.6      .1       0
Bank Sta=4970.1,5019.6
XS Rating Curve= 0 ,0
Exp/Cntr=0.3,0.1

Type RM Length L Ch R = 1 ,8483    ,191,191,191
BEGIN DESCRIPTION:
HOLLY BRANCH 18 0
END DESCRIPTION:
XS GIS Cut Line= 3
       3540681.2     10408474.94        3540459.     10408735.32
      3540413.86     10408943.68
#Sta/Elev= 30
    4739  385.09  4743.3  382.69  4757.5   379.7  4764.1  378.95  4778.4  375.86
  4806.9  372.03  4905.7  363.74  4948.6  362.59  4962.9  361.91  4970.6  360.57
  4977.1  360.61  4984.4  358.15    4996  355.75  4996.2  355.25  4999.7  355.25
    5000  355.75  5005.7  357.07    5020  361.92  5040.8  364.91  5075.6  367.91
  5111.8  370.05  5135.6  371.48  5179.7  375.65  5220.8  381.34  5251.5  388.05
  5271.9  393.71  5278.1  396.35  5283.2  396.67  5290.9  399.46  5294.5  399.46
#Mann= 4 ,-1 , 0
    4739     .16       0    4996     .07       0    5000     .16       0
  5111.8     .05       0
Bank Sta=4977.1,5020
XS Rating Curve= 0 ,0
Exp/Cntr=0.3,0.1

Type RM Length L Ch R = 1 ,8292    ,342,342,342
BEGIN DESCRIPTION:
HOLLY BRANCH 17 0
END DESCRIPTION:
XS GIS Cut Line= 3
      3540497.21     10408353.36       3540271.5     10408690.18
      3540237.04     10408876.26
#Sta/Elev= 30
  4736.5  374.77  4738.6  374.26  4804.6  367.63  4846.6  364.43  4876.6  363.36
  4882.7  362.27  4918.7  360.21  4948.7  360.53  4969.7  359.56  4997.3  354.77
  4997.5  354.27    5001  354.27  5001.3  354.77  5035.4  359.85  5041.7  361.63
  5083.4   366.4  5107.6   368.6  5139.8  372.87  5145.2  372.87  5162.4   374.5
  5184.1  377.51  5214.6  380.63    5235   384.1  5265.5  386.54  5273.3  387.44
  5278.3  388.75  5285.8  389.77  5306.2  392.15  5326.1  393.64  5331.2   395.2
#Mann= 4 ,-1 , 0
  4736.5     .16       0  4997.3     .07       0  5001.3     .16       0
  5083.4     .05       0
Bank Sta=4969.7,5035.4
XS Rating Curve= 0 ,0
Exp/Cntr=0.3,0.1

Type RM Length L Ch R = 1 ,7950    ,369,369,369
BEGIN DESCRIPTION:
HOLLY BRANCH 14 1
END DESCRIPTION:
XS GIS Cut Line= 3
      3540222.88     10408221.46      3540070.11     10408506.15
      3540042.34     10408735.29
#Sta/Elev= 30
  4759.3   374.7  4762.2   374.7  4768.3  373.12  4795.9  369.64  4812.2  366.17
  4834.9  362.71  4884.3  357.53  4899.9   356.7  4930.3  357.38  4965.7  358.63
  4975.1   357.9  4983.4  356.07  4995.8  354.26  4996.1  353.76  4999.6  353.76
  4999.8  354.26  5009.5  356.63  5020.1  357.89  5025.7  357.27  5039.4  357.69
  5063.9  359.48    5077  361.39  5082.4  361.39  5148.4  370.02  5178.6  373.14
  5240.4  377.81  5273.9  380.53  5279.3  381.72  5289.4  382.77  5313.2  384.01
#Mann= 8 ,-1 , 0
  4759.3     .16       0  4834.9      .1       0  4930.3     .16       0
  4983.4      .1       0  4995.8     .07       0  4999.8      .1       0
  5039.4     .05       0  5240.4      .1       0
Bank Sta=4975.1,5020.1
XS Rating Curve= 0 ,0
Exp/Cntr=0.3,0.1

Type RM Length L Ch R = 1 ,7581    ,426,426,426
BEGIN DESCRIPTION:
HOLLY BRANCH 16 0
END DESCRIPTION:
XS GIS Cut Line= 4
      3540104.83     10408117.27       3539896.5     10408228.38
      3539827.06     10408499.21      3539844.27     10408757.64
#Sta/Elev= 30
  4667.9  377.25  4682.2  376.24  4693.7  373.96  4761.7  365.84    4792  361.26
  4800.8  360.35  4835.9  355.95  4857.9  354.63    4928   354.9  4942.7  354.46
  4983.5  355.28  4998.3  353.14  4998.5  352.64    5002  352.64  5002.3  353.14
  5010.6  354.73  5019.1  354.87  5031.3  356.35  5053.7  357.56  5059.8  358.86
  5093.2  360.45  5100.6  361.49  5134.5  364.51  5155.1  366.89  5182.2  370.79
  5240.7  375.22  5276.2  376.92  5346.4  382.18  5402.4  384.43  5442.6  385.95
#Mann= 7 ,-1 , 0
  4667.9     .16       0  4800.8     .12       0  4998.3     .07       0
  5002.3     .12       0  5053.7     .16       0  5240.7      .1       0
  5402.4     .05       0
Bank Sta=4983.5,5010.6
XS Rating Curve= 0 ,0
Exp/Cntr=0.3,0.1

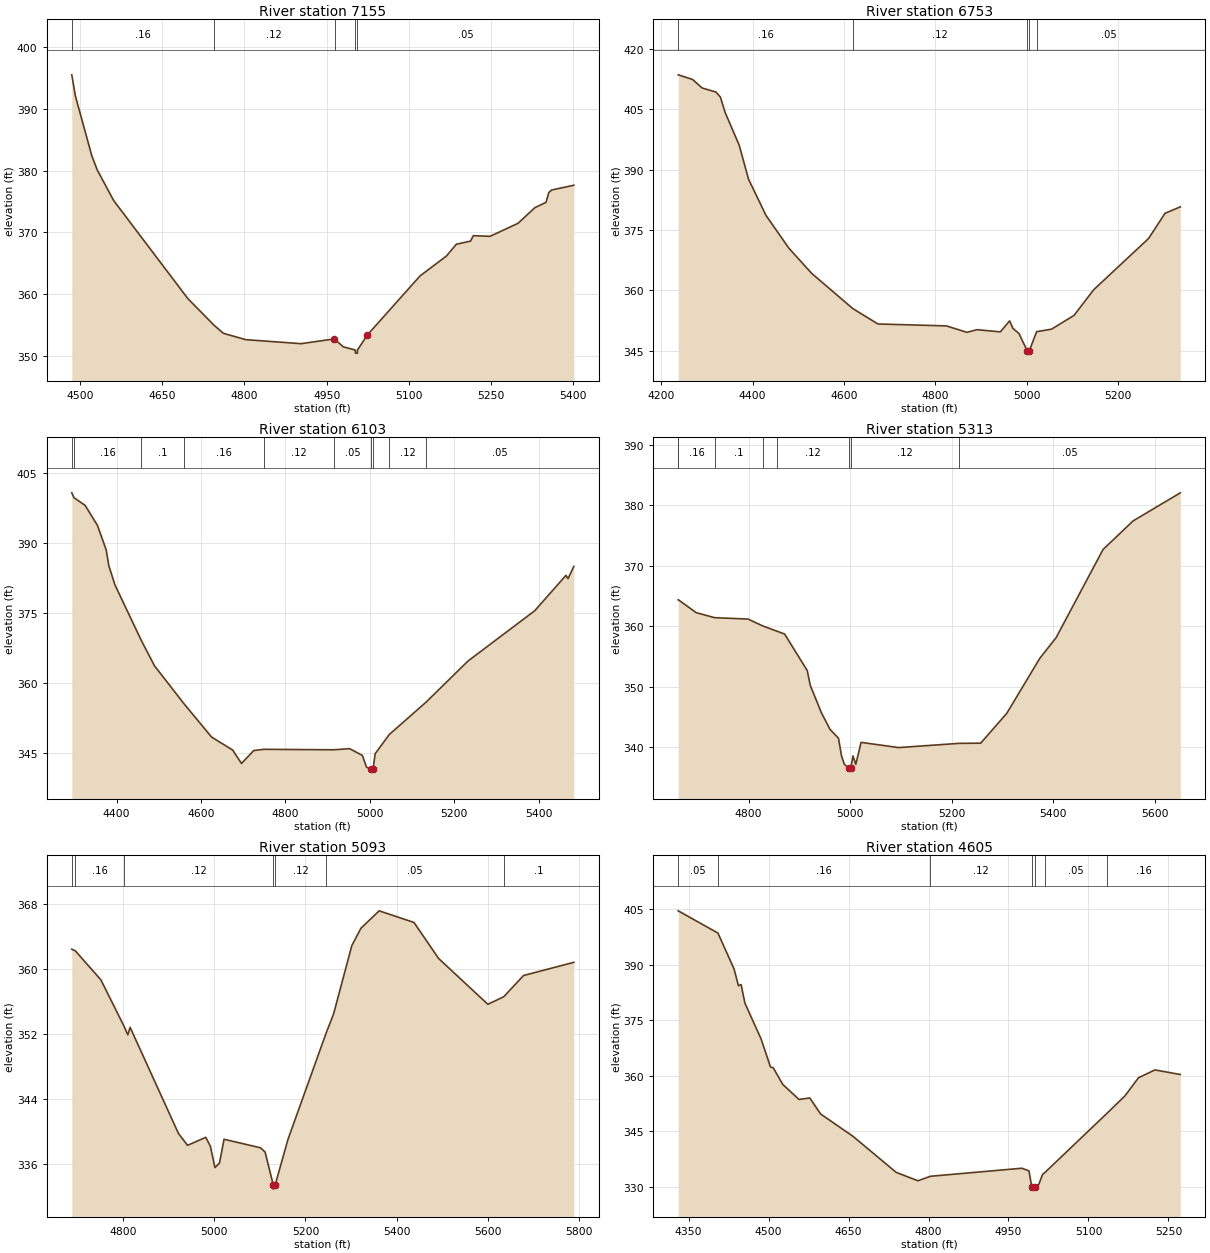
Type RM Length L Ch R = 1 ,7155    ,402,402,402
BEGIN DESCRIPTION:
HOLLY BRANCH 14 0
END DESCRIPTION:
XS GIS Cut Line= 4
      3540118.71     10408026.99      3539906.92     10408026.99
      3539486.78     10408086.02      3539212.52       10408027.
#Sta/Elev= 30
  4484.7   395.5  4491.3  392.08  4521.3   382.4  4531.3  380.09  4561.3  375.14
  4696.4  359.31  4743.8  355.03  4761.4  353.67  4802.3  352.64  4903.3  351.99
  4963.9  352.76  4964.8  352.72  4980.3  351.48  5002.3  350.96  5002.6  350.46
  5006.1  350.46  5006.3  350.96  5024.5  353.42  5120.6  362.96  5168.4  366.15
  5186.9  368.09  5212.7  368.59  5217.8  369.47  5248.3  369.36  5299.4  371.47
  5330.1     374  5350.5  374.86  5355.6  376.45  5360.8  376.86  5401.3  377.63
#Mann= 5 ,-1 , 0
  4484.7     .16       0  4743.8     .12       0  4964.8     .05       0
  5002.3     .03       0  5006.3     .05       0
Bank Sta=4963.9,5024.5
XS Rating Curve= 0 ,0
Exp/Cntr=0.3,0.1

Type RM Length L Ch R = 1 ,6753    ,650,650,650
BEGIN DESCRIPTION:
HOLLY BRANCH 13 1
END DESCRIPTION:
XS GIS Cut Line= 4
      3540222.87     10407896.38      3539552.12     10407756.64
      3539376.55     10407792.22       3539231.9      10407978.2
#Sta/Elev= 30
    4237  413.56  4268.4  412.41  4289.4  410.29  4319.5  409.28  4329.2  408.07
  4339.9  404.16  4370.6  396.05    4391  387.61  4429.3  378.59  4479.4  370.45
  4529.4  364.18  4619.4  355.43  4674.5   351.6  4824.6  351.12  4869.6  349.52
  4891.5  350.18  4942.6  349.64    4963  352.37  4970.3   350.5  4983.4  349.24
  5001.8  344.85    5002  344.35  5005.8  344.85  5022.2  349.69  5054.8  350.31
  5104.1  353.74  5147.1  360.11  5267.4  372.86  5303.3  379.11  5336.9  380.73
#Mann= 5 ,-1 , 0
    4237     .16       0  4619.4     .12       0  5001.8     .07       0
  5005.8     .12       0  5022.2     .05       0
Bank Sta=5001.8,5005.8
XS Rating Curve= 0 ,0
Exp/Cntr=0.3,0.1

Type RM Length L Ch R = 1 ,6103    ,790,790,790
BEGIN DESCRIPTION:
HOLLY BRANCH 13 0
END DESCRIPTION:
XS GIS Cut Line= 3
      3539801.05     10407026.59      3539332.28     10407380.76
      3538735.26     10407458.64
#Sta/Elev= 30
  4293.6  400.72  4299.1  399.66  4325.2  398.04  4354.4  393.76  4375.2  388.49
  4381.5   385.1    4396  380.99  4457.8  369.22  4489.6  363.68  4560.6  355.44
  4624.9  348.42  4674.9  345.64  4695.7  342.77  4724.8  345.54  4748.7   345.8
    4914   345.7  4951.9  345.94  4982.1   344.5  4992.2  341.94  5003.6  341.63
  5003.9  341.13  5007.6  341.63  5012.4  344.85  5045.9  348.97  5133.3  355.92
  5232.5  364.71  5390.5  375.47  5464.5  383.05  5469.5  382.35  5483.2  384.96
#Mann= 10 ,-1 , 0
  4293.6      .1       0  4299.1     .16       0  4457.8      .1       0
  4560.6     .16       0  4748.7     .12       0    4914     .05       0
  5003.6     .03       0  5007.6     .05       0  5045.9     .12       0
  5133.3     .05       0
Bank Sta=5003.6,5007.6
XS Rating Curve= 0 ,0
Exp/Cntr=0.3,0.1

Type RM Length L Ch R = 1 ,5313    ,220,220,220
BEGIN DESCRIPTION:
HOLLY BRANCH 11
END DESCRIPTION:
XS GIS Cut Line= 4
      3539461.02     10406479.99      3539282.17     10406599.81
      3539054.74     10406710.92      3538799.51     10407164.09
#Sta/Elev= 30
  4661.4   364.4  4661.7   364.4  4696.8  362.28  4733.1  361.45  4798.8  361.22
  4828.2  360.07  4855.3  359.23  4870.9  358.74  4915.4  352.71  4921.3  350.28
  4943.5  345.69  4960.4  342.98  4976.9  341.53  4982.9  338.61  4988.5  337.21
  4997.2  336.59  4997.4  336.09  5001.2  336.59  5005.4   338.6    5011  337.21
  5021.4  340.84  5095.5  339.98  5214.7  340.68  5256.9  340.71  5308.4  345.66
  5373.4  354.75  5405.3  358.14  5497.9  372.73    5557  377.44  5649.9  382.08
#Mann= 8 ,-1 , 0
  4661.4      .1       0  4661.7     .16       0  4733.1      .1       0
  4828.2     .16       0  4855.3     .12       0  4997.2     .07       0
  5001.2     .12       0  5214.7     .05       0
Bank Sta=4997.2,5001.2
XS Rating Curve= 0 ,0
Exp/Cntr=0.3,0.1

Type RM Length L Ch R = 1 ,5093    ,488,488,488
BEGIN DESCRIPTION:
HOLLY BRANCH 12
END DESCRIPTION:
XS GIS Cut Line= 3
      3539415.95     10406466.01      3538714.54     10406469.49
      3538343.55     10406616.84
#Sta/Elev= 30
  4687.9  362.41  4695.6  362.22  4751.7  358.65  4802.4  352.95  4810.8  351.89
  4815.8  352.81  4921.7  339.77  4941.7   338.3  4981.7  339.29  4991.7   338.2
  5001.7  335.57  5011.7  336.12  5021.7  339.05  5101.7     338  5111.7  337.48
  5129.7  333.42    5130  332.92  5133.7  333.42  5161.7  339.01  5245.4  352.09
  5261.7  354.43  5301.8  362.86  5321.8  364.99  5361.8  367.13  5438.1   365.7
  5492.1  361.27    5600  355.64  5634.8  356.57  5678.3  359.18  5788.5   360.8
#Mann= 7 ,-1 , 0
  4687.9      .1       0  4695.6     .16       0  4802.4     .12       0
  5129.7     .07       0  5133.7     .12       0  5245.4     .05       0
  5634.8      .1       0
Bank Sta=5129.7,5133.7
XS Rating Curve= 0 ,0
Exp/Cntr=0.3,0.1

Type RM Length L Ch R = 1 ,4605    ,618,618,618
BEGIN DESCRIPTION:
HOLLY BRANCH 10
END DESCRIPTION:
XS GIS Cut Line= 3
      3539595.34     10405957.15      3539005.03     10406057.85
       3538682.1     10406172.44
#Sta/Elev= 30
  4330.7  404.53  4405.1  398.53  4435.4  388.84  4443.6  384.32  4448.6  384.64
  4455.7  379.64  4486.1  369.95  4503.7  362.39  4508.8  362.19  4526.7  357.69
  4557.2  353.63  4577.4  354.03  4597.7  349.71  4658.6  343.66  4739.3  333.96
  4780.3  331.68  4803.7   332.9  4975.1  335.07  4988.4  334.36  4993.8  329.93
  4994.2  329.43  4998.8  329.93  5006.9  330.72  5013.9  333.43  5017.9  333.86
  5135.5     350  5168.3  354.58  5193.8  359.49  5224.7   361.6  5272.2  360.36
#Mann= 7 ,-1 , 0
  4330.7     .05       0  4405.1     .16       0  4803.7     .12       0
  4993.8     .07       0  4998.8     .12       0  5017.9     .05       0
  5135.5     .16       0
Bank Sta=4993.8,4998.8
XS Rating Curve= 0 ,0
Exp/Cntr=0.3,0.1

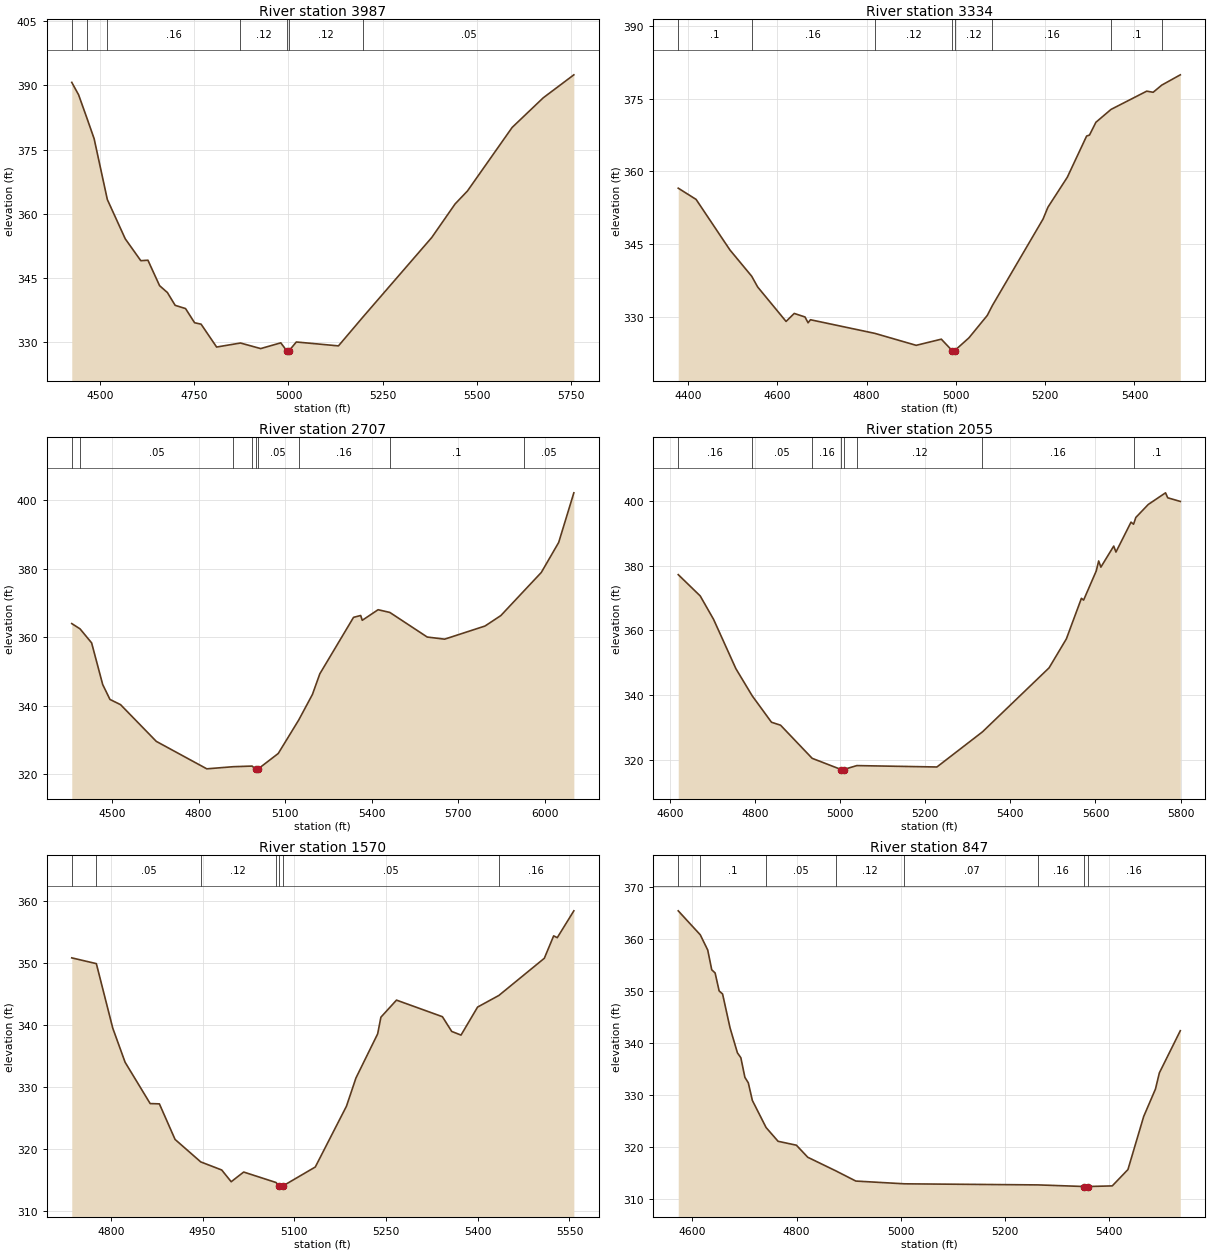
Type RM Length L Ch R = 1 ,3987    ,653,653,653
BEGIN DESCRIPTION:
HOLLY BRANCH 9 0
END DESCRIPTION:
XS GIS Cut Line= 2
      3539417.99     10405383.08      3538126.73     10405705.89
#Sta/Elev= 30
  4425.6   390.7  4443.7   387.8  4466.7  382.13  4484.9  377.55  4519.9  363.36
  4567.4  354.19  4608.6  349.09  4627.5   349.2  4658.4  343.26  4679.1  341.66
  4699.7  338.67  4727.2  337.92  4751.2  334.61  4768.4  334.28  4809.6  328.94
  4872.8  329.88  4926.4  328.58  4979.7  329.92    4996  328.02  4996.4  327.52
  5001.1  328.02  5020.9  330.12  5132.6  329.21  5197.2  335.91    5380  354.51
  5441.8  362.33  5474.5  365.35    5593  380.18  5675.5   387.1  5756.6  392.46
#Mann= 7 ,-1 , 0
  4425.6     .16       0  4466.7      .1       0  4519.9     .16       0
  4872.8     .12       0    4996     .07       0  5001.1     .12       0
  5197.2     .05       0
Bank Sta=4996,5001.1
XS Rating Curve= 0 ,0
Exp/Cntr=0.3,0.1

Type RM Length L Ch R = 1 ,3334    ,627,627,627
BEGIN DESCRIPTION:
HOLLY BRANCH 8 0
END DESCRIPTION:
XS GIS Cut Line= 4
      3539219.85     10405093.87      3538733.76     10404922.43
      3538440.79     10404994.04      3538249.84      10405234.9
#Sta/Elev= 30
  4378.3  356.53  4418.3  354.21    4494  343.79  4542.8  338.36  4556.2  336.14
  4619.8  329.03  4638.1  330.68  4662.2  329.95  4669.1  328.75  4674.4  329.38
  4818.5  326.57  4911.2   324.1  4967.5  325.37  4991.9  322.99  4992.3  322.49
  4997.1  322.99  5029.3  325.64  5070.4  330.27    5082  332.34  5195.3  350.16
  5206.3  352.61  5249.6  358.78  5292.9  367.29  5299.3  367.49  5313.7  370.13
  5347.5  372.78  5427.5  376.55  5441.9  376.32  5461.2   377.8  5502.7  379.92
#Mann= 8 ,-1 , 0
  4378.3      .1       0  4542.8     .16       0  4818.5     .12       0
  4991.9     .07       0  4997.1     .12       0    5082     .16       0
  5347.5      .1       0  5461.2     .05       0
Bank Sta=4991.9,4997.1
XS Rating Curve= 0 ,0
Exp/Cntr=0.3,0.1

Type RM Length L Ch R = 1 ,2707    ,652,652,652
BEGIN DESCRIPTION:
HOLLY BRANCH 19 0
END DESCRIPTION:
XS GIS Cut Line= 3
      3539026.96     10404170.56      3538154.56     10404477.85
      3537391.89     10404766.78
#Sta/Elev= 30
  4360.6  363.96  4389.3  362.42  4429.4  358.34  4467.8  346.21    4493  341.86
  4529.7  340.34  4653.6  329.64  4828.7  321.64  4920.5  322.26  4985.8  322.44
  4999.2  321.47  4999.6  320.97  5004.5  321.47  5076.3   326.1  5147.4  335.87
  5194.8   343.3  5220.5  349.32  5337.4  365.78  5362.2  366.32  5367.6  364.92
  5422.5     368  5463.2  367.21  5592.8  360.04  5653.1  359.42  5793.2  363.25
  5848.1   366.3  5929.2  373.57  5988.2  378.85  6048.5  387.59  6101.1  402.06
#Mann= 9 ,-1 , 0
  4360.6     .16       0  4389.3     .05       0  4920.5     .12       0
  4985.8     .05       0  4999.2     .04       0  5004.5     .05       0
  5147.4     .16       0  5463.2      .1       0  5929.2     .05       0
Bank Sta=4999.2,5004.5
XS Rating Curve= 0 ,0
Exp/Cntr=0.3,0.1

Type RM Length L Ch R = 1 ,2055    ,485,485,485
BEGIN DESCRIPTION:
HOLLY BRANCH 7 0
END DESCRIPTION:
XS GIS Cut Line= 3
      3538821.24     10403688.78      3538092.06     10403920.56
        3537691.     10404024.73
#Sta/Elev= 30
  4619.8  377.18  4671.4   370.6  4702.8  363.36  4755.3  348.09  4793.7  339.69
  4838.9  331.54  4860.2  330.63  4934.4  320.39  5002.4  316.93  5002.9  316.43
  5008.4  316.93  5039.4  318.14  5227.5  317.71  5334.5  328.57    5491  348.36
  5531.6  357.31    5567  369.86  5572.1   369.3  5601.9  378.35  5607.5  381.41
  5612.7   379.5  5642.9  386.01  5648.1  384.16  5683.5   393.4  5689.5  392.76
  5694.8  394.85    5724  398.87  5764.6  402.47  5769.7  400.94  5799.3  399.81
#Mann= 8 ,-1 , 0
  4619.8     .16       0  4793.7     .05       0  4934.4     .16       0
  5002.4     .07       0  5008.4     .16       0  5039.4     .12       0
  5334.5     .16       0  5689.5      .1       0
Bank Sta=5002.4,5008.4
XS Rating Curve= 0 ,0
Exp/Cntr=0.3,0.1

Type RM Length L Ch R = 1 ,1570    ,723,723,723
BEGIN DESCRIPTION:
HOLLY BRANCH 5 0
END DESCRIPTION:
XS GIS Cut Line= 3
      3538547.77     10403308.58      3538026.96     10403412.74
        3537871.     10403657.09
#Sta/Elev= 30
  4736.2  350.82  4776.4  349.89  4803.2  339.52  4823.4  334.02  4864.4  327.37
  4879.5  327.32  4905.1   321.6  4947.1  317.98  4981.4  316.68  4996.9  314.79
  5017.3  316.35  5070.1  314.67  5075.3   314.1  5075.8   313.6  5081.3   314.1
  5134.4  317.16  5185.4  326.95  5200.9  331.49  5236.4  338.59  5241.7  341.27
  5267.2  344.02  5342.3  341.35  5357.5  338.98  5372.7  338.39  5399.8   342.9
  5434.6  344.77  5508.9  350.75  5524.2  354.36  5530.1  354.07  5557.2  358.39
#Mann= 7 ,-1 , 0
  4736.2      .1       0  4776.4     .05       0  4947.1     .12       0
  5070.1     .05       0  5075.3     .07       0  5081.3     .05       0
  5434.6     .16       0
Bank Sta=5075.3,5081.3
XS Rating Curve= 0 ,0
Exp/Cntr=0.3,0.1

Type RM Length L Ch R = 1 ,847     ,0,0,0
BEGIN DESCRIPTION:
HOLLY BRANCH 1 0
END DESCRIPTION:
XS GIS Cut Line= 3
      3538792.14     10403141.68      3538492.11     10402791.64
      3537992.12     10402841.64
#Sta/Elev= 30
  4572.9  365.37  4615.2  360.76  4629.5  357.84  4637.2  354.05  4643.7  353.43
  4651.4  349.98    4658   349.4  4672.3   342.9  4686.5  338.09  4693.1  337.14
  4700.8  333.39  4707.4  332.32  4715.1  328.96  4741.5  323.74  4764.5   321.1
  4799.6  320.35  4821.5  318.03  4875.3  315.42  4913.7  313.46  5006.9  312.93
  5263.8  312.72  5352.5  312.41    5353  311.91  5358.5  312.41  5405.8  312.53
  5435.9  315.67  5466.1  325.86  5488.7  331.13  5496.2  334.24  5536.4  342.34
#Mann= 8 ,-1 , 0
  4572.9     .05       0  4615.2      .1       0  4741.5     .05       0
  4875.3     .12       0  5006.9     .07       0  5263.8     .16       0
  5352.5     .07       0  5358.5     .16       0
Bank Sta=5352.5,5358.5
XS Rating Curve= 0 ,0
Exp/Cntr=0.3,0.1

Chan Stop Cuts=-1
Use User Specified Reach Order=0
Composite Channel Slope=5