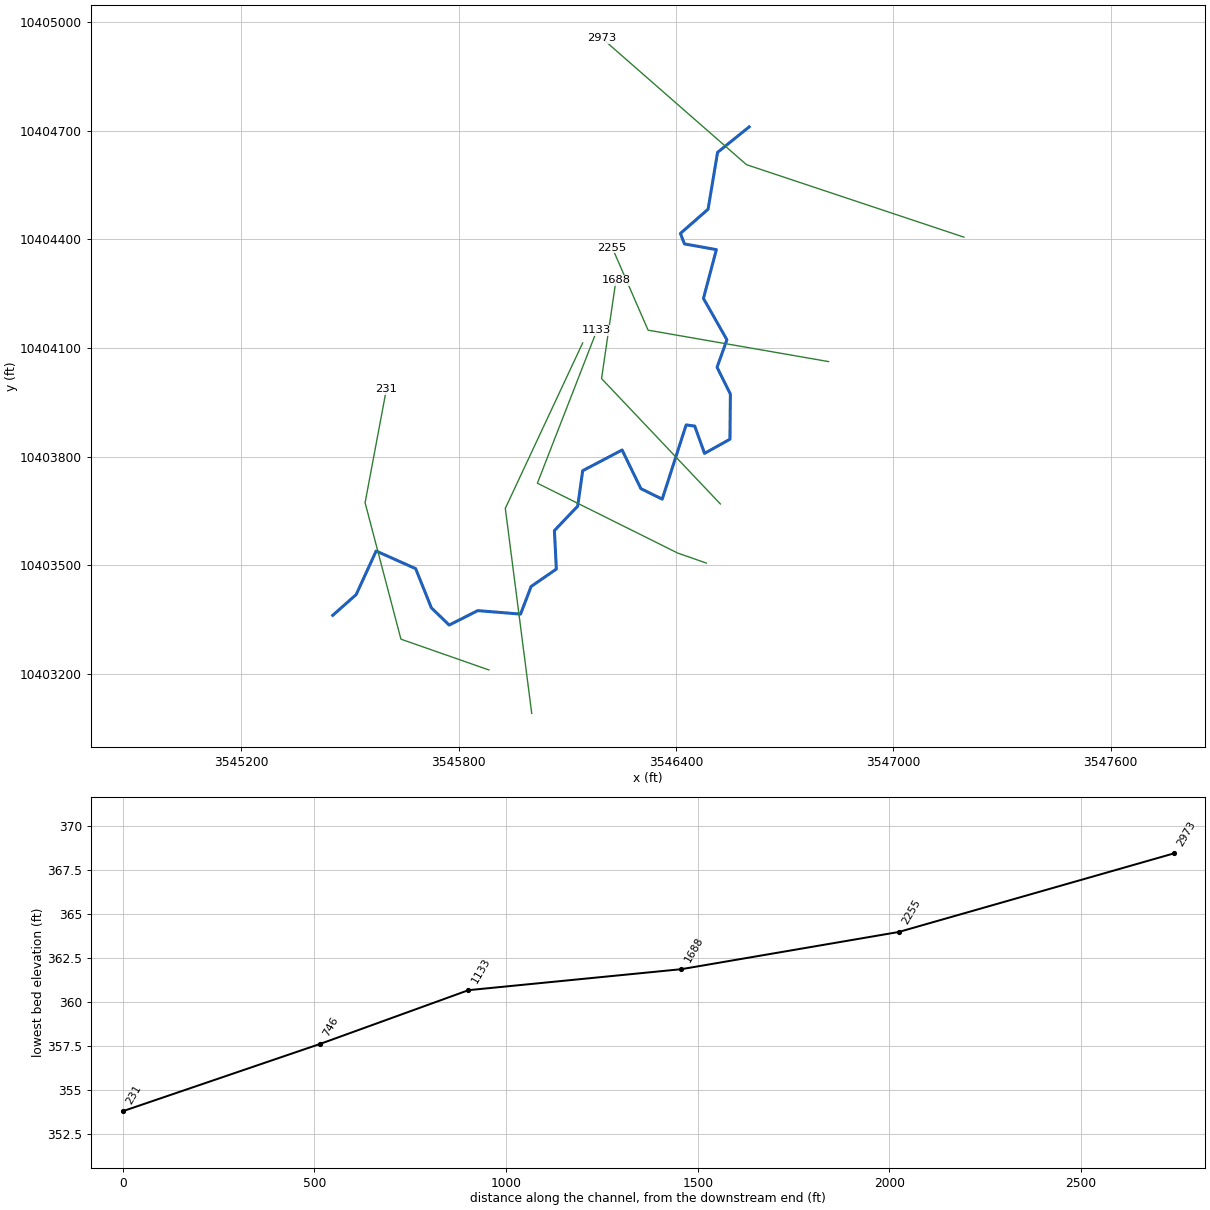
--- LAKE BRANCH TRIB 3.prj (project) ---

Proj Title=LAKE BRANCH TRIB 3 Base Level Engineering
Current Plan=p01
Default Exp/Contr=0.3,0.1
English Units
Geom File=g01
Flow File=f01
Plan File=p01
Y Axis Title=Elevation
X Axis Title(PF)=Main Channel Distance
X Axis Title(XS)=Station
BEGIN DESCRIPTION:
LAKE BRANCH TRIB 3
END DESCRIPTION:
DSS Export Rating Curves= 0
DSS Export Rating Curve Sorted= 0
DSS Export Volume Flow Curves= 0
DXF OffsetX= 0
DXF OffsetY= 0
DXF ScaleX= 1
DXF ScaleY= 10

--- LAKE BRANCH TRIB 3.p01 (plan) ---

Plan Title=Multiple Run
Short Identifier=Multiple
Geom File=g01
Flow File=f01
Subcritical Flow
K Sum by GR= 0
Std Step Tol= 0.01
Critical Tol= 0.01
Num of Std Step Trials= 20
Max Error Tol= 0.3
Flow Tol Ratio= 0.001
Split Flow NTrial= 30
Split Flow Tol= 0.02
Split Flow Ratio= 0.02
Log Output Level= 0
Friction Slope Method= 1
Unsteady Friction Slope Method= 2
Unsteady Bridges Friction Slope Method= 1
Parabolic Critical Depth
Global Vel Dist=  1 , 1 , 1
Global Log Level= 0
CheckData=True
Encroach Param= -1, 0, 0, 0
BEGIN DESCRIPTION:
Multiple Run
END DESCRIPTION:

--- LAKE BRANCH TRIB 3.f01 (steady flow) ---

Flow Title=Multiple
Program Version=4.10
Number of Profiles= 7
Profile Names=10-year,25-year,50-year,1pct_min,100-year,1pct_plu,500-year
River Rch & RM=LAKE BRANCH TRIB,Reach-1         ,2973
     646     862    1035     907    1227    1659    1720
Boundary for River Rch & Prof#=LAKE BRANCH TRIB,Reach-1         , 1
Up Type= 0
Dn Type= 3
Dn Slope=0.0074
Boundary for River Rch & Prof#=LAKE BRANCH TRIB,Reach-1         , 2
Up Type= 0
Dn Type= 3
Dn Slope=0.0074
Boundary for River Rch & Prof#=LAKE BRANCH TRIB,Reach-1         , 3
Up Type= 0
Dn Type= 3
Dn Slope=0.0074
Boundary for River Rch & Prof#=LAKE BRANCH TRIB,Reach-1         , 4
Up Type= 0
Dn Type= 3
Dn Slope=0.0074
Boundary for River Rch & Prof#=LAKE BRANCH TRIB,Reach-1         , 5
Up Type= 0
Dn Type= 3
Dn Slope=0.0074
Boundary for River Rch & Prof#=LAKE BRANCH TRIB,Reach-1         , 6
Up Type= 0
Dn Type= 3
Dn Slope=0.0074
Boundary for River Rch & Prof#=LAKE BRANCH TRIB,Reach-1         , 7
Up Type= 0
Dn Type= 3
Dn Slope=0.0074
DSS Import GetInterval= 0
DSS Import GetPeak= 0
DSS Import FillOption= 0

--- LAKE BRANCH TRIB 3.g01 (geometry) ---

Geom Title=Existing Conditions
Program Version=4.10

River Reach=LAKE BRANCH TRIB,Reach-1
Reach XY= 30
      3546601.85     10404710.26      3546514.61     10404639.93
      3546488.44     10404482.95      3546411.99     10404416.01
      3546423.21     10404387.15      3546511.32     10404371.37
      3546475.62     10404236.66       3546540.4     10404122.52
      3546513.24     10404046.62        3546550.     10403972.51
       3546548.8     10403847.94      3546478.63     10403808.82
      3546451.55     10403884.24      3546427.85     10403887.36
       3546361.8      10403682.5      3546302.87     10403711.46
      3546251.03     10403818.16      3546142.22     10403760.99
      3546128.45     10403663.17      3546064.14     10403595.69
      3546069.52     10403489.44      3545999.72     10403441.27
      3545970.78     10403365.12      3545852.51      10403374.7
      3545773.65     10403334.85      3545724.47     10403382.35
      3545681.04      10403490.6      3545571.94     10403539.34
      3545516.86     10403418.99      3545452.11     10403361.64

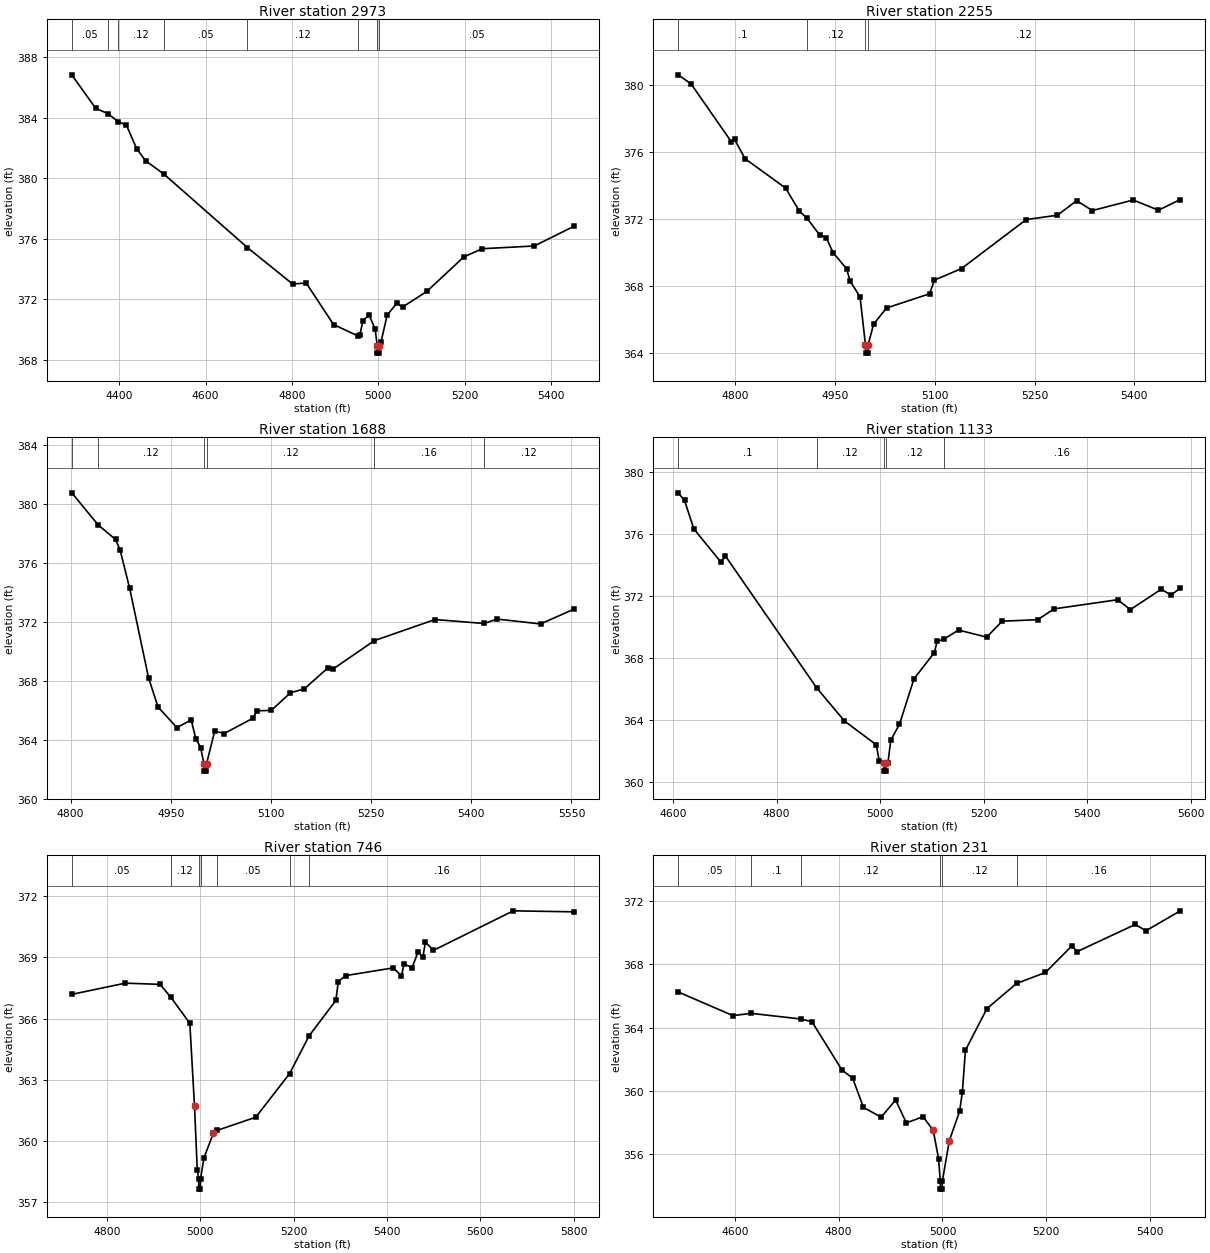
Type RM Length L Ch R = 1 ,2973    ,718,718,718
BEGIN DESCRIPTION:
LAKE BRANCH TRIB 3 7 0
END DESCRIPTION:
XS GIS Cut Line= 3
      3547194.58     10404405.86      3546594.54     10404605.88
      3546195.82     10404954.75
#Sta/Elev= 30
  4290.4  386.83  4345.7  384.62  4373.7  384.27  4397.8  383.74  4416.8  383.51
  4440.6  381.95  4461.7  381.14  4503.3  380.28  4697.2  375.41  4801.5  373.01
  4833.2  373.07  4896.4  370.33  4952.7  369.58  4956.9  369.61  4964.5  370.58
  4978.7  370.96  4992.6  370.03  4997.6  368.94  4997.9  368.44  5001.4  368.44
  5001.6  368.94  5006.2  369.16  5020.5  370.95  5042.3  371.72  5056.5  371.49
  5112.5  372.52    5198   374.8  5240.7  375.34  5361.2  375.52  5452.7  376.82
#Mann= 8 ,-1 , 0
  4290.4     .05       0  4373.7      .1       0  4397.8     .12       0
  4503.3     .05       0  4697.2     .12       0  4952.7     .05       0
  4997.6     .03       0  5001.6     .05       0
Bank Sta=4997.6,5001.6
XS Rating Curve= 0 ,0
Exp/Cntr=0.3,0.1

Type RM Length L Ch R = 1 ,2255    ,567,567,567
BEGIN DESCRIPTION:
LAKE BRANCH TRIB 3 6 0
END DESCRIPTION:
XS GIS Cut Line= 3
      3546821.05     10404062.25      3546322.77     10404149.06
      3546223.82     10404376.48
#Sta/Elev= 30
  4715.1  380.63  4734.3  380.09  4794.6  376.64  4799.6  376.77  4815.5  375.61
  4876.4  373.85  4896.7  372.49  4908.7  372.04  4927.2  371.06  4937.3  370.89
  4947.5     370  4967.8  369.03  4973.3  368.28  4988.1  367.34  4996.2  364.48
  4996.5  363.98    5000  363.98  5000.2  364.48  5008.4  365.71  5027.8  366.68
  5092.5  367.53  5099.8  368.35  5140.4  369.04  5237.6  371.97  5284.4  372.23
  5313.3   373.1  5336.8  372.51  5398.2  373.14    5436  372.53  5468.9  373.17
#Mann= 4 ,-1 , 0
  4715.1      .1       0  4908.7     .12       0  4996.2     .07       0
  5000.2     .12       0
Bank Sta=4996.2,5000.2
XS Rating Curve= 0 ,0
Exp/Cntr=0.3,0.1

Type RM Length L Ch R = 1 ,1688    ,555,555,555
BEGIN DESCRIPTION:
LAKE BRANCH TRIB 3 5 0
END DESCRIPTION:
XS GIS Cut Line= 3
      3546522.31     10403669.21       3546194.3     10404015.38
      3546234.13     10404287.29
#Sta/Elev= 30
  4801.9  380.74  4841.5  378.56  4867.4  377.58  4874.3  376.86  4888.5  374.28
  4916.8  368.21    4931  366.22  4959.3  364.82  4980.7  365.34  4987.6  364.07
  4994.9  363.47  4999.7  362.37    5000  361.87  5003.5  361.87  5003.7  362.37
  5015.9  364.59  5030.1  364.42  5072.5  365.44  5079.8  365.96  5100.8  365.99
  5129.2  367.18  5150.2  367.45  5185.8  368.89  5192.7  368.78    5255  370.72
  5345.8  372.15  5419.1  371.88  5438.9  372.18  5503.8  371.85  5553.6  372.85
#Mann= 6 ,-1 , 0
  4801.9      .1       0  4841.5     .12       0  4999.7     .07       0
  5003.7     .12       0    5255     .16       0  5419.1     .12       0
Bank Sta=4999.7,5003.7
XS Rating Curve= 0 ,0
Exp/Cntr=0.3,0.1

Type RM Length L Ch R = 1 ,1133    ,387,387,387
BEGIN DESCRIPTION:
LAKE BRANCH TRIB 3 4 1
END DESCRIPTION:
XS GIS Cut Line= 4
       3546483.5     10403506.01      3546404.29     10403533.76
      3546017.14     10403726.47      3546181.38     10404148.33
#Sta/Elev= 30
  4610.2  378.67  4622.3  378.18  4640.3  376.34  4692.6  374.19  4701.4  374.58
  4877.2  366.07  4931.1  363.92  4992.5  362.38  4998.2  361.32  5007.3  361.18
  5007.5  360.68    5011  360.68  5011.3  361.18  5014.8  361.18  5020.5  362.69
  5037.2   363.7  5065.2  366.64  5104.4  368.34    5110  369.07    5123  369.21
  5151.2   369.8  5205.5  369.34  5235.4  370.37  5303.8  370.47    5336  371.17
  5458.4  371.76  5482.9  371.12  5542.6  372.44  5561.4  372.06  5579.3  372.51
#Mann= 5 ,-1 , 0
  4610.2      .1       0  4877.2     .12       0  5007.3     .07       0
  5011.3     .12       0    5123     .16       0
Bank Sta=5007.3,5011.3
XS Rating Curve= 0 ,0
Exp/Cntr=0.3,0.1

Type RM Length L Ch R = 1 ,746     ,515,515,515
BEGIN DESCRIPTION:
LAKE BRANCH TRIB 3 4 0
END DESCRIPTION:
XS GIS Cut Line= 3
      3546001.52     10403091.01      3545928.59     10403657.02
      3546142.15     10404113.66
#Sta/Elev= 30
  4725.2  367.19  4839.9  367.74  4914.3  367.68  4937.5  367.04  4977.9  365.77
    4988  361.69  4993.8  358.58  4996.8  358.13  4997.1  357.63  5000.6  357.63
  5000.8  358.13  5008.2  359.17  5028.3  360.37    5036  360.51  5119.1  361.16
  5191.5   363.3  5233.4  365.16  5290.5  366.89  5295.7  367.81  5311.3  368.11
  5413.7  368.49    5431  368.09  5436.5  368.69  5453.8  368.49  5466.6  369.29
  5476.7     369  5482.2  369.75  5499.5  369.35  5670.4  371.29    5800  371.24
#Mann= 7 ,-1 , 0
  4725.2     .05       0  4937.5     .12       0  4996.8     .07       0
  5000.8     .12       0    5036     .05       0  5191.5     .12       0
  5233.4     .16       0
Bank Sta=4988,5028.3
XS Rating Curve= 0 ,0
Exp/Cntr=0.3,0.1

Type RM Length L Ch R = 1 ,231     ,0,0,0
BEGIN DESCRIPTION:
LAKE BRANCH TRIB 3 1 0
END DESCRIPTION:
XS GIS Cut Line= 4
      3545883.43     10403210.85       3545640.4     10403295.91
      3545541.44     10403672.65      3545600.44     10403986.76
#Sta/Elev= 30
  4491.3  366.25  4596.5  364.76  4632.2   364.9  4728.4  364.54  4748.8  364.37
  4806.4  361.33  4827.1  360.81  4847.8  358.97  4881.9  358.35  4909.8  359.43
  4930.5  357.99  4962.6  358.38  4982.2  357.52  4992.5  355.73  4995.8  354.31
    4996  353.81  4999.5  353.81  4999.8  354.31  5013.2  356.87    5033  358.72
  5038.2  359.91  5044.2  362.57  5085.6   365.2  5142.7  366.79  5198.3  367.48
  5249.2  369.16  5259.4   368.8  5371.3  370.51  5391.6  370.11  5457.9  371.37
#Mann= 6 ,-1 , 0
  4491.3     .05       0  4632.2      .1       0  4728.4     .12       0
  4995.8     .07       0  4999.8     .12       0  5142.7     .16       0
Bank Sta=4982.2,5013.2
XS Rating Curve= 0 ,0
Exp/Cntr=0.3,0.1

Chan Stop Cuts=-1
Use User Specified Reach Order=0
Composite Channel Slope=5