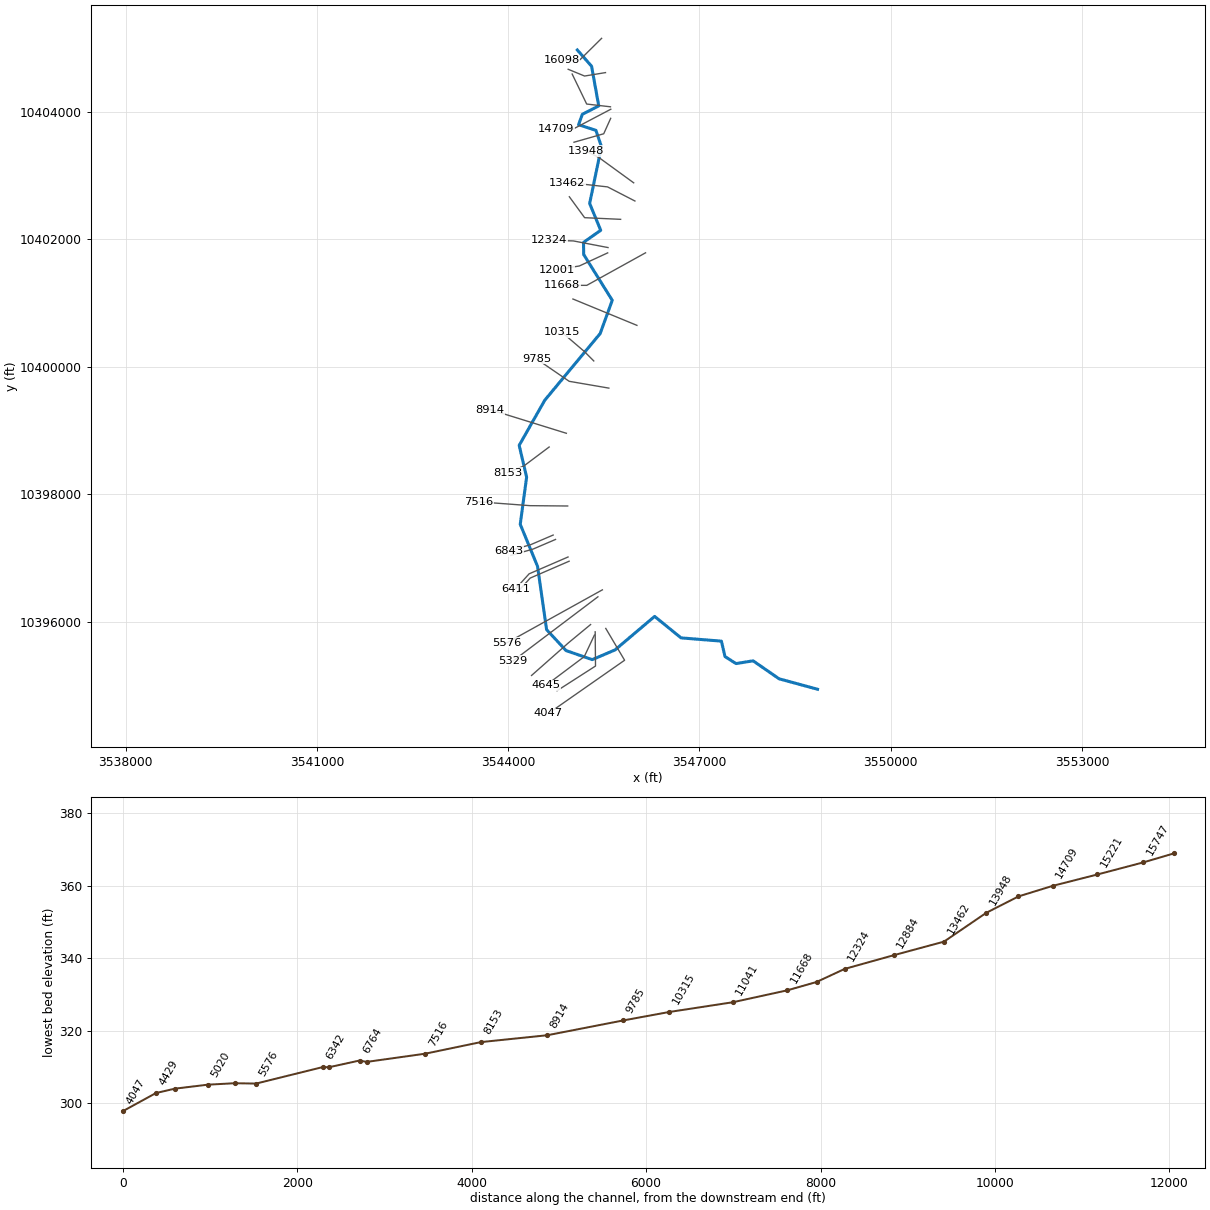
--- LAKE BRANCH.prj (project) ---

Proj Title=LAKE BRANCH Base Level Engineering
Current Plan=p01
Default Exp/Contr=0.3,0.1
English Units
Geom File=g01
Flow File=f01
Plan File=p01
BEGIN DESCRIPTION:
LAKE BRANCH
END DESCRIPTION:

--- LAKE BRANCH.p01 (plan) ---

Plan Title=Multiple Run
Short Identifier=Multiple
Geom File=g01
Flow File=f01
Subcritical Flow
K Sum by GR= 0
Std Step Tol= 0.01
Critical Tol= 0.01
Num of Std Step Trials= 20
Max Error Tol= 0.3
Flow Tol Ratio= 0.001
Split Flow NTrial= 30
Split Flow Tol= 0.02
Split Flow Ratio= 0.02
Log Output Level= 0
Friction Slope Method= 1
Unsteady Friction Slope Method= 2
Unsteady Bridges Friction Slope Method= 1
Parabolic Critical Depth
Global Vel Dist=  1 , 1 , 1
Global Log Level= 0
CheckData=True
Encroach Param= -1, 0, 0, 0
BEGIN DESCRIPTION:
Multiple Run
END DESCRIPTION:

--- LAKE BRANCH.f01 (steady flow) ---

Flow Title=Multiple
Number of Profiles=7
Profile Names=10-year,25-year,50-year,1pct_min,100-year,1pct_plu,500-year
River Rch & RM= LAKE BRANCH,Reach-1,16098
     424     551     651     562     761    1029    1034
River Rch & RM= LAKE BRANCH,Reach-1,13948
    1490    2084    2581    2328    3148    4257    4674
Boundary for River Rch & Prof#=LAKE BRANCH,Reach-1,1
Up Type=0
Dn Type=3
Dn Slope=0.005
Boundary for River Rch & Prof#=LAKE BRANCH,Reach-1,2
Up Type=0
Dn Type=3
Dn Slope=0.005
Boundary for River Rch & Prof#=LAKE BRANCH,Reach-1,3
Up Type=0
Dn Type=3
Dn Slope=0.005
Boundary for River Rch & Prof#=LAKE BRANCH,Reach-1,4
Up Type=0
Dn Type=3
Dn Slope=0.005
Boundary for River Rch & Prof#=LAKE BRANCH,Reach-1,5
Up Type=0
Dn Type=3
Dn Slope=0.005
Boundary for River Rch & Prof#=LAKE BRANCH,Reach-1,6
Up Type=0
Dn Type=3
Dn Slope=0.005
Boundary for River Rch & Prof#=LAKE BRANCH,Reach-1,7
Up Type=0
Dn Type=3
Dn Slope=0.005

--- LAKE BRANCH.g01 (geometry) ---

Geom Title=Existing Conditions

River Reach=LAKE BRANCH,Reach-1
Reach XY= 30
      3545084.09     10404969.13      3545307.48     10404714.54
      3545420.07     10404091.83      3545162.95     10403960.73
      3545103.43     10403796.64      3545375.46     10403708.42
      3545462.37     10403453.40      3545277.43     10402561.60
      3545451.00     10402141.00      3545182.11     10401951.64
      3545183.18     10401762.20      3545631.83     10401043.01
      3545442.87     10400522.43      3544574.12     10399476.42
      3544172.09     10398767.49      3544288.75     10398268.54
      3544188.75     10397529.47      3544460.15     10396869.94
      3544602.17     10395876.88      3544907.72     10395548.19
      3545318.66     10395406.53      3545676.47     10395559.65
      3546296.78     10396084.65      3546710.50     10395747.89
      3547344.28     10395696.44      3547400.00     10395455.16
      3547573.38     10395344.57      3547841.11     10395387.93
      3548249.02     10395105.89      3548852.11     10394941.64

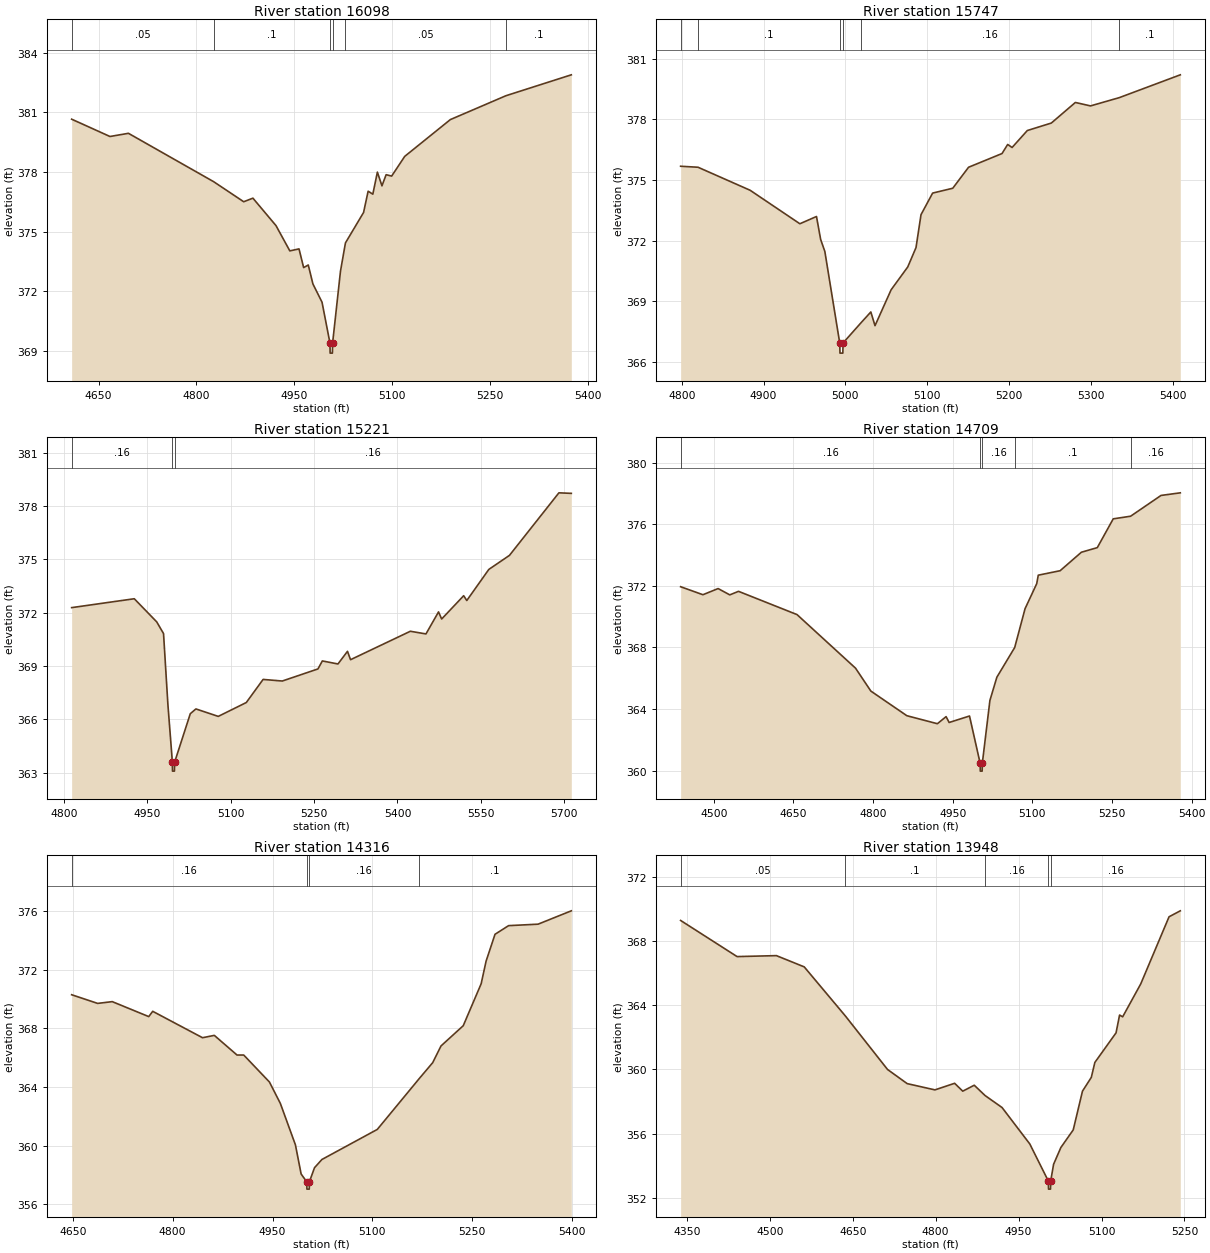
Type RM Length L Ch R = 1,16098,351,351,351
BEGIN DESCRIPTION:
LAKE BRANCH 4 0
END DESCRIPTION:
XS GIS Cut Line= 3
      3545465.07     10405151.83      3545126.51     10404816.75
      3544836.81     10404804.60
#Sta/Elev= 30
  4608.6  380.66  4667.4  379.79  4695.7  379.95  4826.3  377.52  4872.5  376.51
  4886.6  376.69  4922.0  375.31  4943.2  374.04  4957.3  374.14  4964.4  373.20
  4971.5  373.33  4978.6  372.38  4992.6  371.46  5004.8  369.40  5005.0  368.90
  5008.5  368.90  5008.8  369.40  5020.9  373.02  5028.5  374.44  5056.3  375.97
  5063.3  377.04  5070.5  376.89  5077.5  378.00  5084.5  377.31  5090.9  377.87
  5099.4  377.80  5119.4  378.79  5189.4  380.64  5274.7  381.84  5374.9  382.89
#Mann=6,-1,0
  4608.6    0.05       0  4826.3     0.1       0  5004.8    0.07       0
  5008.8     0.1       0  5028.5    0.05       0  5274.7     0.1       0
Bank Sta=5004.8,5008.8
Exp/Cntr=0.3,0.1

Type RM Length L Ch R = 1,15747,526,526,526
BEGIN DESCRIPTION:
Mapping XS 6f5a826d
END DESCRIPTION:
XS GIS Cut Line= 3
      3545525.93     10404614.34      3545197.77     10404560.52
      3544940.78     10404666.44
#Sta/Elev= 30
  4798.7  375.68  4820.0  375.63  4883.6  374.49  4944.4  372.83  4964.7  373.19
  4969.8  372.05  4974.9  371.46  4993.1  366.92  4993.4  366.42  4996.9  366.42
  4997.1  366.92  5019.0  367.92  5031.1  368.46  5036.2  367.78  5055.9  369.56
  5076.2  370.69  5086.3  371.65  5092.4  373.28  5106.6  374.35  5131.2  374.59
  5150.5  375.63  5191.4  376.31  5198.3  376.76  5203.7  376.61  5222.3  377.45
  5251.6  377.82  5281.0  378.84  5299.5  378.67  5334.7  379.08  5409.2  380.21
#Mann=6,-1,0
  4798.7    0.05       0  4820.0     0.1       0  4993.1    0.07       0
  4997.1     0.1       0  5019.0    0.16       0  5334.7     0.1       0
Bank Sta=4993.1,4997.1
Exp/Cntr=0.3,0.1

Type RM Length L Ch R = 1,15221,512,512,512
BEGIN DESCRIPTION:
LAKE BRANCH 3 0
END DESCRIPTION:
XS GIS Cut Line= 3
      3545603.98     10404077.88      3545230.76     10404121.28
      3545003.33     10404591.76
#Sta/Elev= 30
  4814.2  372.29  4926.8  372.79  4967.1  371.49  4979.4  370.83  4987.2  366.86
  4995.3  363.59  4995.5  363.09  4999.0  363.09  4999.3  363.59  5027.5  366.32
  5037.6  366.59  5077.8  366.17  5128.2  366.95  5158.4  368.25  5192.9  368.16
  5257.0  368.84  5264.9  369.29  5293.0  369.12  5310.1  369.83  5315.6  369.36
  5423.1  370.96  5451.2  370.81  5473.8  372.05  5479.4  371.65  5519.0  372.96
  5524.6  372.69  5564.2  374.44  5601.3  375.23  5690.2  378.75  5712.5  378.72
#Mann=3,-1,0
  4814.2    0.16       0  4995.3    0.07       0  4999.3    0.16       0
Bank Sta=4995.3,4999.3
Exp/Cntr=0.3,0.1

Type RM Length L Ch R = 1,14709,393,393,393
BEGIN DESCRIPTION:
Mapping XS aebbc903
END DESCRIPTION:
XS GIS Cut Line= 3
      3545609.23     10404039.69      3545012.01     10403725.45
      3544745.85     10403732.36
#Sta/Elev= 30
  4437.6  371.94  4479.6  371.42  4508.2  371.82  4530.2  371.41  4546.6  371.64
  4656.8  370.13  4767.0  366.65  4795.9  365.16  4863.7  363.56  4921.2  363.04
  4937.6  363.50  4943.3  363.12  4981.7  363.54  5001.8  360.46  5002.0  359.96
  5005.5  359.96  5005.8  360.46  5020.1  364.55  5033.2  366.06  5066.8  367.99
  5086.3  370.51  5108.3  372.14  5111.2  372.69  5152.4  372.98  5192.4  374.18
  5222.4  374.48  5252.4  376.35  5285.1  376.52  5342.4  377.87  5378.7  378.04
#Mann=5,-1,0
  4437.6    0.16       0  5001.8    0.07       0  5005.8    0.16       0
  5066.8     0.1       0  5285.1    0.16       0
Bank Sta=5001.8,5005.8
Exp/Cntr=0.3,0.1

Type RM Length L Ch R = 1,14316,368,368,368
BEGIN DESCRIPTION:
LAKE BRANCH 39 0
END DESCRIPTION:
XS GIS Cut Line= 3
      3545607.44     10403897.20      3545498.05     10403655.00
      3545031.86     10403522.17
#Sta/Elev= 30
  4648.3  370.29  4687.3  369.70  4709.3  369.82  4764.1  368.80  4770.1  369.16
  4844.9  367.36  4862.6  367.52  4896.7  366.18  4906.8  366.18  4945.4  364.34
  4961.8  362.88  4984.4  360.06  4993.0  358.07  5001.4  357.54  5001.7  357.04
  5005.2  357.04  5005.4  357.54  5013.1  358.50  5024.2  359.06  5107.4  361.11
  5170.1  364.56  5190.6  365.66  5203.1  366.80  5236.5  368.18  5263.4  371.04
  5270.8  372.58  5284.2  374.41  5304.6  375.00  5348.9  375.10  5398.8  376.01
#Mann=4,-1,0
  4648.3    0.16       0  5001.4    0.07       0  5005.4    0.16       0
  5170.1     0.1       0
Bank Sta=5001.4,5005.4
Exp/Cntr=0.3,0.1

Type RM Length L Ch R = 1,13948,486,486,486
BEGIN DESCRIPTION:
LAKE BRANCH 28 0
END DESCRIPTION:
XS GIS Cut Line= 3
      3545968.11     10402885.42      3545418.15     10403285.39
      3545218.18     10403385.38
#Sta/Elev= 30
  4338.8  369.27  4440.9  367.02  4512.0  367.08  4562.3  366.38  4636.8  363.32
  4713.0  359.99  4748.5  359.11  4798.7  358.72  4834.3  359.13  4849.0  358.64
  4869.8  359.01  4889.3  358.37  4920.1  357.62  4970.3  355.35  5003.8  353.04
  5004.1  352.54  5007.7  352.54  5008.0  353.04  5013.3  354.09  5026.4  355.13
  5048.8  356.23  5065.5  358.64  5081.5  359.50  5087.9  360.43  5126.2  362.27
  5132.6  363.38  5138.2  363.27  5170.9  365.32  5222.1  369.50  5242.4  369.87
#Mann=5,-1,0
  4338.8    0.05       0  4636.8     0.1       0  4889.3    0.16       0
  5003.8    0.07       0  5008.0    0.16       0
Bank Sta=5003.8,5008
Exp/Cntr=0.3,0.1

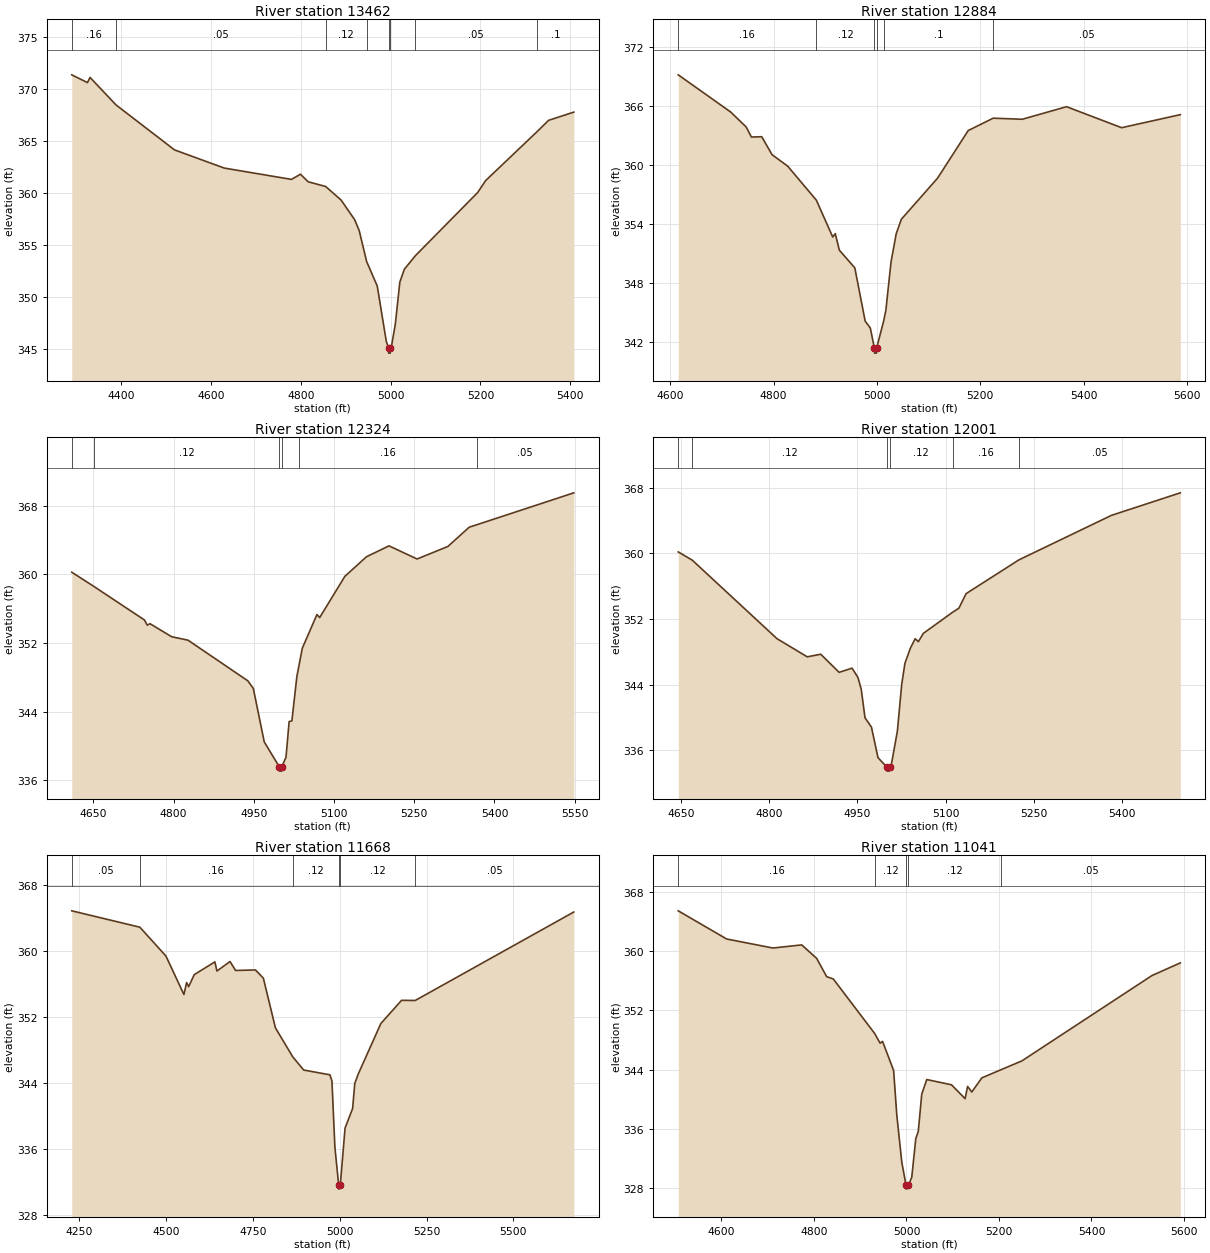
Type RM Length L Ch R = 1,13462,578,578,578
BEGIN DESCRIPTION:
LAKE BRANCH 27 0
END DESCRIPTION:
XS GIS Cut Line= 4
      3545987.66     10402600.30      3545557.95     10402821.66
      3545182.95     10402863.33      3544926.17     10402884.08
#Sta/Elev= 30
  4289.8  371.38  4324.8  370.63  4330.5  371.13  4388.4  368.48  4518.7  364.15
  4629.5  362.40  4779.1  361.31  4799.2  361.81  4816.3  361.08  4855.2  360.63
  4889.7  359.32  4919.9  357.43  4930.0  356.38  4946.6  353.40  4970.2  351.04
  4990.3  345.73  4995.3  345.08  4995.5  344.58  4999.2  344.58  4999.5  345.08
  5002.4  345.36  5010.5  347.38  5020.5  351.42  5030.6  352.66  5054.9  353.95
  5194.0  360.05  5211.5  361.19  5325.5  365.88  5352.0  367.00  5408.1  367.79
#Mann=8,-1,0
  4289.8    0.16       0  4388.4    0.05       0  4855.2    0.12       0
  4946.6    0.16       0  4995.3    0.07       0  4999.5    0.16       0
  5054.9    0.05       0  5325.5     0.1       0
Bank Sta=4995.3,4999.5
Exp/Cntr=0.3,0.1

Type RM Length L Ch R = 1,12884,560,560,560
BEGIN DESCRIPTION:
LAKE BRANCH 26 0
END DESCRIPTION:
XS GIS Cut Line= 3
      3545763.54     10402312.78      3545198.47     10402338.82
      3544958.97     10402666.82
#Sta/Elev= 30
  4615.4  369.20  4716.9  365.41  4747.0  363.88  4757.0  362.86  4777.0  362.89
  4797.0  361.06  4827.1  359.90  4882.8  356.42  4914.4  352.67  4919.4  353.01
  4927.2  351.33  4957.2  349.52  4977.2  344.10  4987.2  343.39  4995.1  341.33
  4995.4  340.83  4999.1  340.83  4999.3  341.33  5013.0  344.10  5017.3  345.20
  5027.3  350.13  5037.3  353.00  5047.3  354.48  5117.4  358.67  5176.7  363.52
  5225.0  364.78  5281.3  364.67  5367.0  365.95  5473.6  363.81  5587.2  365.14
#Mann=6,-1,0
  4615.4    0.16       0  4882.8    0.12       0  4995.1    0.07       0
  4999.3    0.12       0  5013.0     0.1       0  5225.0    0.05       0
Bank Sta=4995.1,4999.3
Exp/Cntr=0.3,0.1

Type RM Length L Ch R = 1,12324,323,323,323
BEGIN DESCRIPTION:
LAKE BRANCH 25 0
END DESCRIPTION:
XS GIS Cut Line= 3
      3545565.64     10401870.07      3545021.38     10401974.23
      3544636.56     10401984.63
#Sta/Elev= 30
  4609.4  360.25  4650.1  358.62  4745.4  354.68  4750.6  354.08  4755.7  354.25
  4796.3  352.73  4826.8  352.33  4938.8  347.59  4949.0  346.70  4969.4  340.48
  4997.6  337.57  4997.9  337.07  5001.8  337.07  5002.2  337.57  5010.1  338.69
  5016.0  342.85  5021.1  342.92  5030.4  348.08  5034.2  349.31  5040.6  351.39
  5068.0  355.32  5073.1  354.96  5120.1  359.76  5160.6  362.05  5202.8  363.32
  5255.3  361.79  5312.9  363.25  5352.9  365.50  5366.5  365.77  5548.5  369.50
#Mann=6,-1,0
  4609.4    0.16       0  4650.1    0.12       0  4997.6    0.07       0
  5002.2    0.12       0  5034.2    0.16       0  5366.5    0.05       0
Bank Sta=4997.6,5002.2
Exp/Cntr=0.3,0.1

Type RM Length L Ch R = 1,12001,333,333,333
BEGIN DESCRIPTION:
LAKE BRANCH 24 0
END DESCRIPTION:
XS GIS Cut Line= 3
      3545560.45     10401786.73      3545115.13     10401581.00
      3544756.40     10401523.82
#Sta/Elev= 30
  4645.3  360.18  4669.2  359.17  4813.3  349.60  4864.7  347.39  4887.6  347.71
  4918.9  345.50  4940.9  346.01  4950.9  344.88  4956.5  343.44  4962.9  339.97
  4973.9  338.82  4985.0  335.10  5000.0  333.96  5000.3  333.46  5004.3  333.46
  5004.6  333.96  5007.8  334.29  5018.0  338.35  5025.3  344.01  5030.8  346.60
  5040.0  348.43  5048.2  349.60  5053.7  349.24  5062.1  350.25  5112.2  352.84
  5122.5  353.31  5134.8  355.09  5224.7  359.21  5381.9  364.63  5499.1  367.38
#Mann=6,-1,0
  4645.3    0.16       0  4669.2    0.12       0  5000.0    0.07       0
  5004.6    0.12       0  5112.2    0.16       0  5224.7    0.05       0
Bank Sta=5000,5004.6
Exp/Cntr=0.3,0.1

Type RM Length L Ch R = 1,11668,627,627,627
BEGIN DESCRIPTION:
LAKE BRANCH 23 0
END DESCRIPTION:
XS GIS Cut Line= 3
      3546154.34     10401787.83      3545232.43     10401277.39
      3544841.81     10401277.39
#Sta/Elev= 30
  4229.4  364.83  4425.3  362.85  4500.4  359.36  4552.0  354.71  4559.9  356.16
  4565.7  355.66  4581.7  357.11  4641.2  358.66  4647.0  357.55  4684.7  358.70
  4700.6  357.62  4757.8  357.68  4780.6  356.69  4815.3  350.68  4865.1  347.18
  4896.6  345.58  4972.1  345.00  4977.9  344.25  4986.4  336.24  4997.3  331.68
  4997.6  331.18  5001.9  331.68  5015.6  338.56  5037.4  340.93  5043.5  343.94
  5053.4  345.08  5118.7  351.21  5178.2  354.01  5217.5  353.99  5673.8  364.69
#Mann=6,-1,0
  4229.4    0.05       0  4425.3    0.16       0  4865.1    0.12       0
  4997.3    0.07       0  5001.9    0.12       0  5217.5    0.05       0
Bank Sta=4997.3,5001.9
Exp/Cntr=0.3,0.1

Type RM Length L Ch R = 1,11041,726,726,726
BEGIN DESCRIPTION:
LAKE BRANCH 22 0
END DESCRIPTION:
XS GIS Cut Line= 2
      3546018.85     10400649.80      3545015.35     10401063.16
#Sta/Elev= 30
  4506.7  365.44  4611.3  361.64  4711.3  360.42  4773.6  360.84  4806.0  359.02
  4827.6  356.55  4841.8  356.25  4931.4  348.88  4943.0  347.58  4948.4  347.82
  4972.3  343.89  4979.1  337.91  4989.9  331.54  4999.2  328.38  4999.6  327.88
  5004.2  328.38  5011.5  329.48  5020.2  334.69  5025.6  335.68  5033.1  340.70
  5043.9  342.67  5097.4  341.96  5126.8  340.09  5132.2  341.74  5141.3  340.99
  5162.9  342.89  5203.8  343.98  5249.4  345.18  5530.6  356.70  5592.0  358.41
#Mann=5,-1,0
  4506.7    0.16       0  4931.4    0.12       0  4999.2    0.07       0
  5004.2    0.12       0  5203.8    0.05       0
Bank Sta=4999.2,5004.2
Exp/Cntr=0.3,0.1

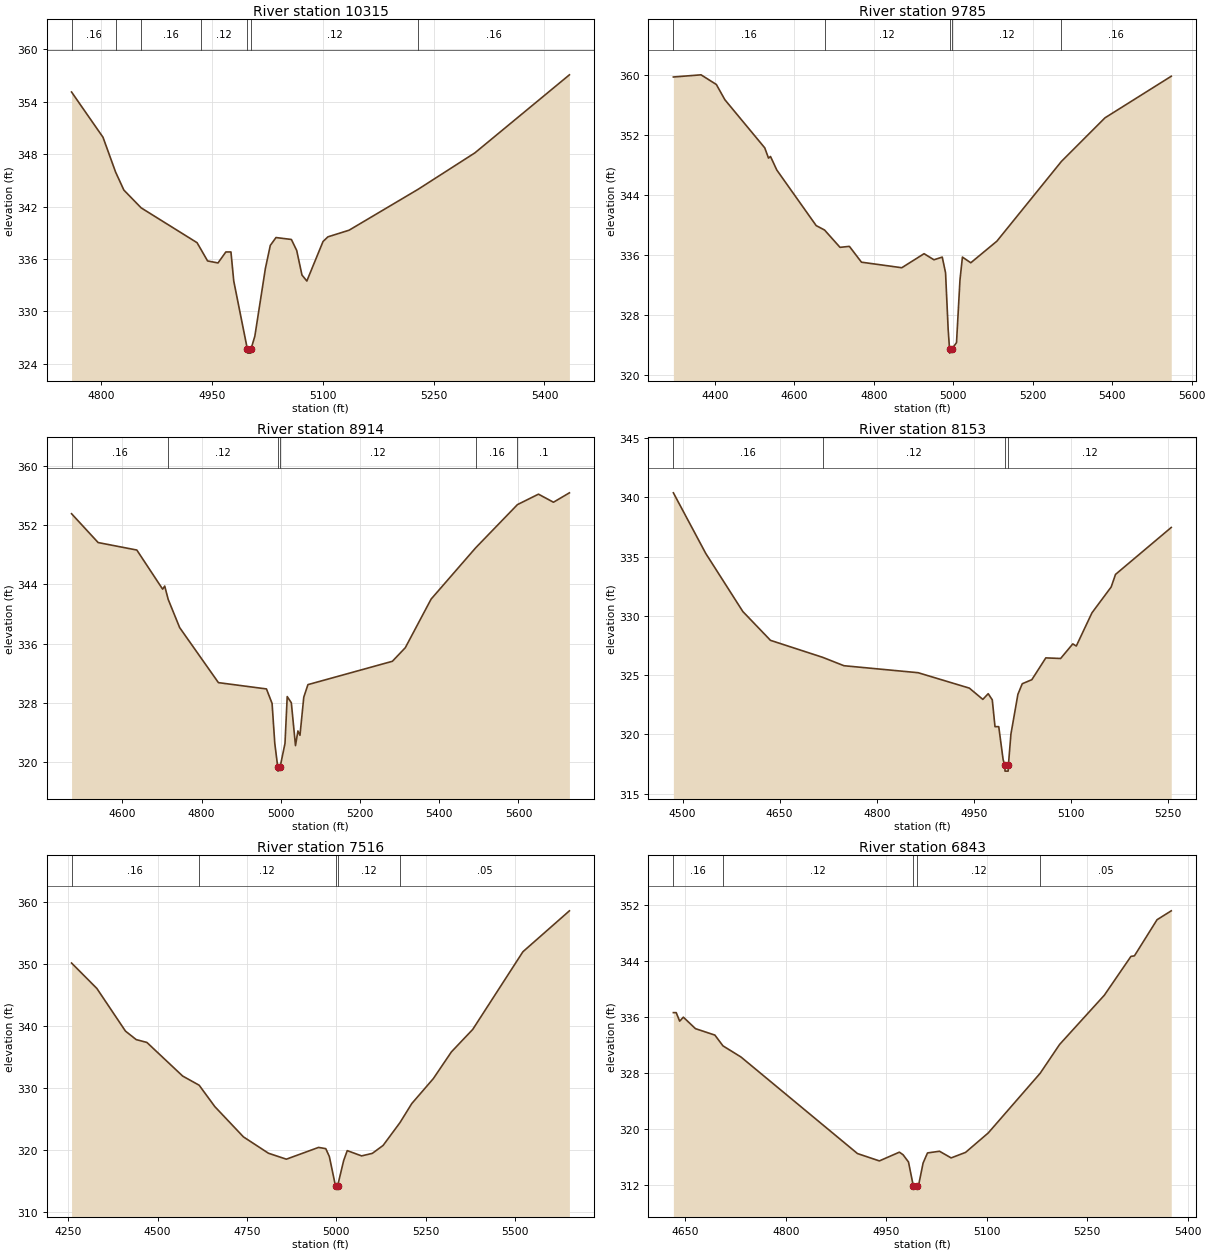
Type RM Length L Ch R = 1,10315,530,530,530
BEGIN DESCRIPTION:
LAKE BRANCH 20 0
END DESCRIPTION:
XS GIS Cut Line= 3
      3545342.13     10400091.62      3545192.11     10400241.64
      3544842.14     10400541.62
#Sta/Elev= 30
  4760.6  355.12  4803.1  349.94  4820.1  345.96  4831.3  343.89  4854.7  341.85
  4930.3  337.86  4936.1  337.01  4944.5  335.77  4958.6  335.54  4969.2  336.80
  4976.1  336.80  4979.9  333.46  4998.2  325.71  4998.6  325.21  5002.9  325.21
  5003.3  325.71  5008.4  327.15  5022.7  334.93  5029.3  337.55  5037.0  338.45
  5057.8  338.23  5065.0  336.97  5072.1  334.16  5078.7  333.47  5100.6  338.00
  5107.2  338.53  5135.8  339.29  5229.0  343.97  5305.9  348.15  5433.7  357.09
#Mann=7,-1,0
  4760.6    0.16       0  4820.1    0.12       0  4854.7    0.16       0
  4936.1    0.12       0  4998.2    0.07       0  5003.3    0.12       0
  5229.0    0.16       0
Bank Sta=4998.2,5003.3
Exp/Cntr=0.3,0.1

Type RM Length L Ch R = 1,9785,871,871,871
BEGIN DESCRIPTION:
LAKE BRANCH 2 0
END DESCRIPTION:
XS GIS Cut Line= 3
      3545578.78     10399665.41      3544956.39     10399772.18
      3544443.37     10400123.74
#Sta/Elev= 30
  4295.2  359.70  4364.8  359.99  4403.4  358.70  4424.8  356.67  4525.2  350.25
  4534.7  348.88  4539.7  349.10  4555.6  347.29  4654.7  339.88  4675.8  339.29
  4714.7  336.98  4738.3  337.11  4768.7  335.00  4870.2  334.26  4926.3  336.13
  4951.2  335.32  4972.1  335.68  4980.4  333.59  4987.0  326.03  4990.5  323.37
  4990.9  322.87  4995.7  323.37  5008.0  324.27  5016.7  332.62  5022.9  335.68
  5043.9  334.92  5109.6  337.80  5272.1  348.44  5381.7  354.25  5548.6  359.80
#Mann=5,-1,0
  4295.2    0.16       0  4675.8    0.12       0  4990.5    0.07       0
  4995.7    0.12       0  5272.1    0.16       0
Bank Sta=4990.5,4995.7
Exp/Cntr=0.3,0.1

Type RM Length L Ch R = 1,8914,761,761,761
BEGIN DESCRIPTION:
LAKE BRANCH 18 0
END DESCRIPTION:
XS GIS Cut Line= 2
      3544912.13     10398957.08      3543711.56     10399329.49
#Sta/Elev= 30
  4471.6  353.52  4538.7  349.63  4636.4  348.62  4701.6  343.34  4706.8  343.76
  4715.6  341.96  4744.6  338.15  4842.4  330.73  4963.7  329.88  4977.9  327.92
  4984.7  322.55  4992.3  319.29  4992.8  318.79  4997.9  319.29  5010.5  322.53
  5016.1  328.85  5026.5  328.01  5037.0  322.23  5043.1  324.21  5048.3  323.62
  5057.9  328.76  5068.4  330.46  5281.6  333.61  5314.2  335.44  5379.4  342.00
  5491.9  348.92  5597.4  354.75  5650.5  356.16  5688.3  355.07  5728.6  356.34
#Mann=6,-1,0
  4471.6    0.16       0  4715.6    0.12       0  4992.3    0.07       0
  4997.9    0.12       0  5491.9    0.16       0  5597.4     0.1       0
Bank Sta=4992.3,4997.9
Exp/Cntr=0.3,0.1

Type RM Length L Ch R = 1,8153,637,637,637
BEGIN DESCRIPTION:
LAKE BRANCH 17 0
END DESCRIPTION:
XS GIS Cut Line= 3
      3544642.10     10398741.64      3544242.11     10398441.64
      3543992.15     10398341.66
#Sta/Elev= 30
  4485.8  340.37  4535.8  335.26  4593.1  330.36  4635.8  327.93  4716.3  326.50
  4749.3  325.79  4863.9  325.20  4943.1  323.90  4963.9  322.95  4972.2  323.43
  4978.5  322.91  4982.7  320.65  4988.5  320.65  4995.2  317.89  4997.7  317.40
  4998.2  316.90  5003.0  316.90  5003.4  317.40  5007.3  320.02  5018.1  323.38
  5024.8  324.27  5039.6  324.61  5061.2  326.45  5084.1  326.40  5102.9  327.63
  5108.3  327.45  5132.5  330.25  5162.2  332.43  5168.9  333.49  5255.0  337.45
#Mann=4,-1,0
  4485.8    0.16       0  4716.3    0.12       0  4997.7    0.07       0
  5003.4    0.12       0
Bank Sta=4997.7,5003.4
Exp/Cntr=0.3,0.1

Type RM Length L Ch R = 1,7516,673,673,673
BEGIN DESCRIPTION:
LAKE BRANCH 15 0
END DESCRIPTION:
XS GIS Cut Line= 3
      3544932.91     10397816.46      3544344.41     10397821.66
      3543542.37     10397881.56
#Sta/Elev= 30
  4259.1  350.18  4329.9  346.08  4409.9  339.20  4439.9  337.83  4469.9  337.37
  4569.9  331.95  4616.1  330.47  4659.9  327.02  4739.9  322.14  4809.9  319.50
  4860.0  318.54  4950.2  320.44  4970.3  320.24  4980.3  318.97  4997.5  314.21
  4998.0  313.71  5002.8  313.71  5003.3  314.21  5020.4  318.33  5030.4  319.92
  5070.5  319.07  5100.6  319.48  5130.7  320.76  5177.9  324.44  5210.9  327.51
  5271.1  331.53  5321.8  335.85  5381.4  339.47  5521.8  352.00  5651.9  358.60
#Mann=5,-1,0
  4259.1    0.16       0  4616.1    0.12       0  4997.5    0.07       0
  5003.3    0.12       0  5177.9    0.05       0
Bank Sta=4997.5,5003.3
Exp/Cntr=0.3,0.1

Type RM Length L Ch R = 1,6843,79,79,79
BEGIN DESCRIPTION:
LAKE BRANCH 14 0
END DESCRIPTION:
XS GIS Cut Line= 3
      3544704.91     10397360.73      3544354.90     10397210.72
      3544005.96     10397111.03
#Sta/Elev= 30
  4632.0  336.65  4636.2  336.65  4641.4  335.43  4646.9  336.00  4665.0  334.36
  4694.0  333.44  4706.1  331.90  4733.0  330.31  4907.0  316.52  4939.7  315.47
  4969.6  316.72  4975.1  316.35  4983.2  315.32  4990.3  311.94  4990.8  311.44
  4996.2  311.94  4998.6  312.14  5005.0  315.16  5011.6  316.61  5029.5  316.85
  5046.9  315.90  5068.5  316.69  5102.3  319.46  5179.9  327.99  5208.9  332.10
  5275.7  339.13  5315.5  344.68  5320.7  344.76  5354.5  349.92  5375.7  351.19
#Mann=5,-1,0
  4632.0    0.16       0  4706.1    0.12       0  4990.3    0.07       0
  4996.2    0.12       0  5179.9    0.05       0
Bank Sta=4990.3,4996.2
Exp/Cntr=0.3,0.1

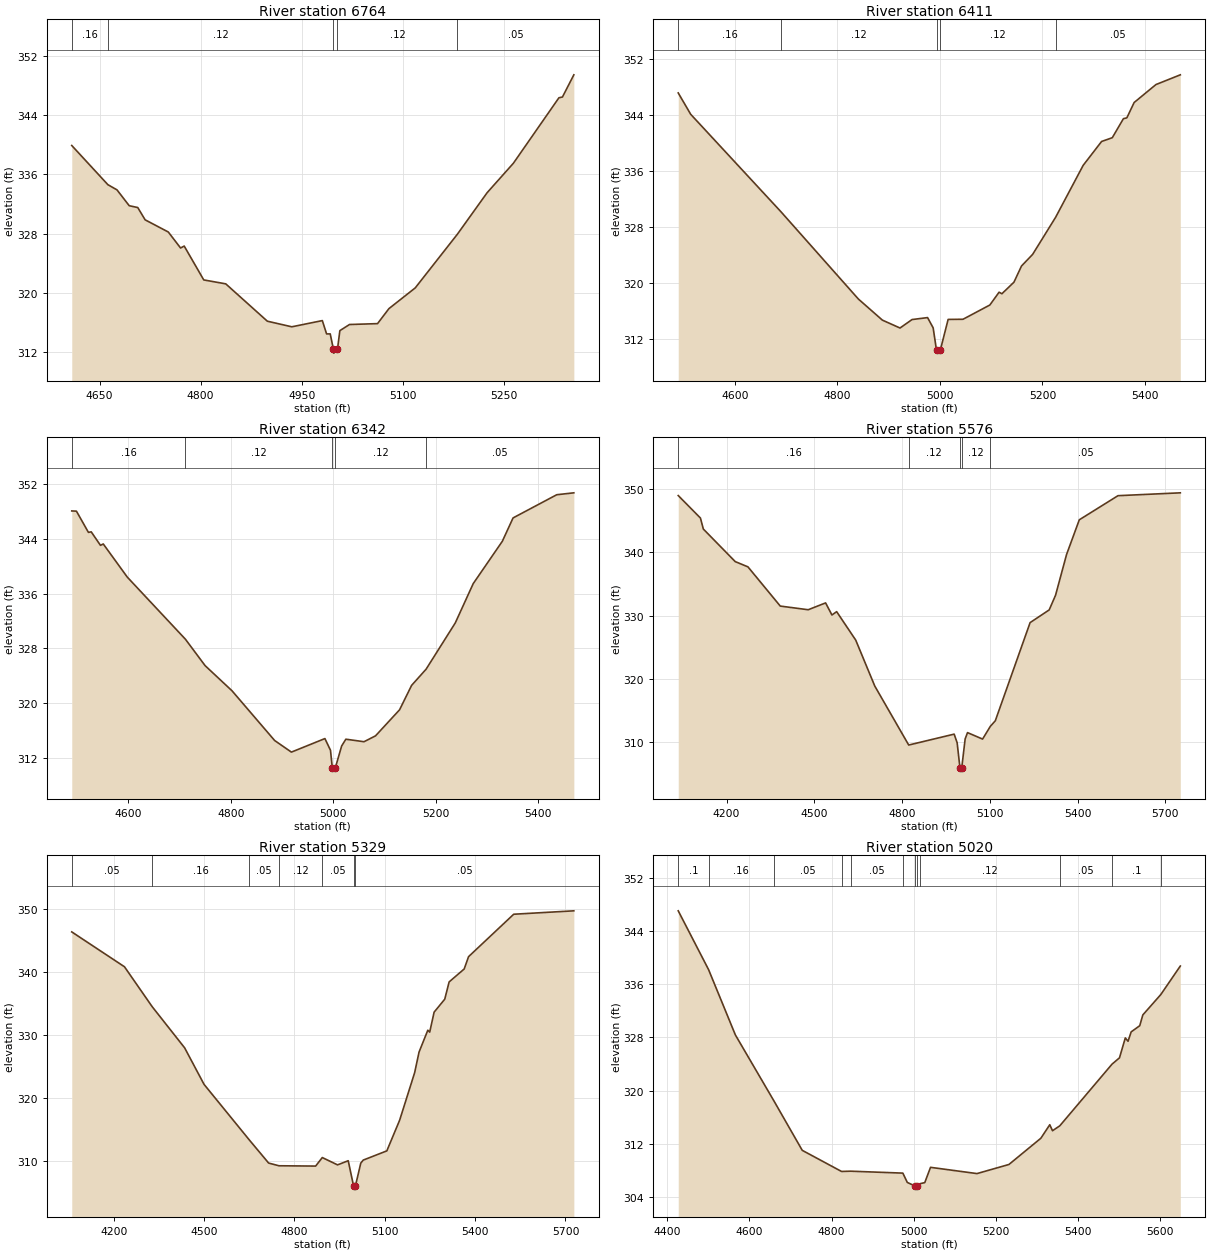
Type RM Length L Ch R = 1,6764,353,353,353
BEGIN DESCRIPTION:
LAKE BRANCH 13 0
END DESCRIPTION:
XS GIS Cut Line= 3
      3544742.08     10397291.63      3544392.11     10397141.64
      3544042.07     10397041.63
#Sta/Elev= 30
  4608.8  339.91  4662.4  334.61  4675.9  333.91  4694.0  331.77  4706.7  331.52
  4717.6  329.86  4752.0  328.21  4770.2  326.05  4775.6  326.31  4804.6  321.73
  4837.2  321.20  4898.9  316.15  4935.2  315.39  4980.5  316.23  4986.8  314.43
  4992.2  314.43  4997.0  312.33  4997.5  311.83  5002.9  312.33  5006.5  314.87
  5020.8  315.70  5062.4  315.82  5079.3  317.85  5118.3  320.65  5180.9  327.92
  5224.9  333.52  5263.9  337.51  5331.5  346.37  5336.7  346.47  5353.6  349.47
#Mann=5,-1,0
  4608.8    0.16       0  4662.4    0.12       0  4997.0    0.07       0
  5002.9    0.12       0  5180.9    0.05       0
Bank Sta=4997,5002.9
Exp/Cntr=0.3,0.1

Type RM Length L Ch R = 1,6411,69,69,69
BEGIN DESCRIPTION:
LAKE BRANCH 29 0
END DESCRIPTION:
XS GIS Cut Line= 3
      3544938.54     10397016.65      3544327.87     10396752.32
      3544117.05     10396519.38
#Sta/Elev= 30
  4489.5  347.17  4513.8  344.12  4690.2  330.16  4840.9  317.71  4887.8  314.69
  4922.2  313.56  4945.7  314.77  4976.0  315.05  4986.9  313.58  4992.7  310.73
  4995.1  310.47  4995.6  309.97  5001.1  310.47  5016.1  314.79  5045.1  314.81
  5097.5  316.85  5115.5  318.68  5121.0  318.46  5144.5  320.11  5159.3  322.43
  5181.0  324.09  5225.8  329.39  5279.6  336.82  5315.5  340.23  5336.4  340.77
  5358.1  343.49  5364.8  343.61  5379.0  345.80  5421.6  348.37  5469.1  349.76
#Mann=5,-1,0
  4489.5    0.16       0  4690.2    0.12       0  4995.1    0.07       0
  5001.1    0.12       0  5225.8    0.05       0
Bank Sta=4995.1,5001.1
Exp/Cntr=0.3,0.1

Type RM Length L Ch R = 1,6342,766,766,766
BEGIN DESCRIPTION:
LAKE BRANCH 33 0
END DESCRIPTION:
XS GIS Cut Line= 3
      3544955.44     10396950.23      3544344.79     10396685.92
      3544133.82     10396452.81
#Sta/Elev= 30
  4489.5  348.08  4498.6  348.05  4522.0  344.95  4527.5  345.02  4545.5  343.05
  4551.0  343.25  4597.9  338.40  4711.3  329.32  4749.7  325.46  4802.2  321.78
  4885.4  314.51  4918.1  312.81  4983.5  314.79  4994.4  313.08  4997.9  310.53
  4998.4  310.03  5003.9  310.53  5016.2  313.71  5024.4  314.70  5059.8  314.33
  5082.3  315.19  5129.2  319.00  5152.7  322.57  5181.0  324.94  5237.9  331.70
  5273.0  337.46  5329.8  343.65  5350.7  347.06  5435.9  350.45  5469.3  350.73
#Mann=5,-1,0
  4489.5    0.16       0  4711.3    0.12       0  4997.9    0.07       0
  5003.9    0.12       0  5181.0    0.05       0
Bank Sta=4997.9,5003.9
Exp/Cntr=0.3,0.1

Type RM Length L Ch R = 1,5576,247,247,247
BEGIN DESCRIPTION:
LAKE BRANCH 19 0
END DESCRIPTION:
XS GIS Cut Line= 2
      3545477.21     10396501.35      3543975.85     10395668.70
#Sta/Elev= 30
  4034.6  348.98  4110.5  345.43  4120.5  343.69  4229.5  338.55  4273.0  337.72
  4383.5  331.53  4479.0  330.95  4538.5  332.03  4560.2  330.12  4576.3  330.65
  4641.5  326.16  4706.7  318.90  4822.7  309.59  4978.1  311.31  4988.3  309.95
  4998.0  305.97  4998.5  305.47  5004.0  305.97  5015.7  310.56  5023.8  311.55
  5075.3  310.53  5101.8  312.54  5118.8  313.42  5237.8  328.92  5303.0  330.92
  5324.8  333.24  5362.5  339.68  5406.0  345.15  5538.4  348.96  5751.4  349.41
#Mann=5,-1,0
  4034.6    0.16       0  4822.7    0.12       0  4998.0    0.07       0
  5004.0    0.12       0  5101.8    0.05       0
Bank Sta=4998,5004
Exp/Cntr=0.3,0.1

Type RM Length L Ch R = 1,5329,309,309,309
BEGIN DESCRIPTION:
LAKE BRANCH 9 0
END DESCRIPTION:
XS GIS Cut Line= 2
      3545406.94     10396392.00      3544076.62     10395387.10
#Sta/Elev= 30
  4060.7  346.31  4235.7  340.79  4327.7  334.47  4435.5  327.95  4500.0  322.16
  4650.8  313.33  4714.4  309.70  4748.7  309.27  4870.5  309.22  4892.6  310.57
  4943.3  309.41  4978.7  310.07  4996.5  306.07  4997.0  305.57  5002.6  306.07
  5020.4  309.69  5028.7  310.17  5106.9  311.63  5149.4  316.48  5199.3  324.02
  5213.9  327.28  5243.0  330.74  5249.3  330.44  5263.9  333.60  5299.2  335.65
  5313.8  338.39  5363.8  340.44  5378.3  342.39  5528.2  349.11  5727.9  349.65
#Mann=7,-1,0
  4060.7    0.05       0  4327.7    0.16       0  4650.8    0.05       0
  4748.7    0.12       0  4892.6    0.05       0  4996.5    0.04       0
  5002.6    0.05       0
Bank Sta=4996.5,5002.6
Exp/Cntr=0.3,0.1

Type RM Length L Ch R = 1,5020,375,375,375
BEGIN DESCRIPTION:
LAKE BRANCH 7 1
END DESCRIPTION:
XS GIS Cut Line= 3
      3545292.32     10395957.08      3544948.57     10395673.23
      3544366.18     10395158.43
#Sta/Elev= 30
  4426.4  347.05  4500.4  338.19  4565.6  328.37  4659.7  318.42  4728.5  311.00
  4824.2  307.82  4846.8  307.86  4973.6  307.57  4984.4  306.17  5002.2  305.66
  5002.7  305.16  5008.3  305.66  5014.8  305.97  5027.0  306.14  5041.0  308.44
  5154.2  307.50  5232.0  308.87  5309.8  312.82  5331.5  314.85  5338.2  313.95
  5355.9  314.69  5483.3  323.98  5501.3  324.92  5515.5  327.92  5522.2  327.42
  5529.8  328.83  5550.7  329.76  5558.2  331.38  5602.0  334.45  5649.5  338.74
#Mann=12,-1,0
  4426.4     0.1       0  4500.4    0.16       0  4659.7    0.05       0
  4824.2    0.12       0  4846.8    0.05       0  4973.6    0.08       0
  5002.2    0.07       0  5008.3    0.08       0  5014.8    0.12       0
  5355.9    0.05       0  5483.3     0.1       0  5602.0    0.05       0
Bank Sta=5002.2,5008.3
Exp/Cntr=0.3,0.1

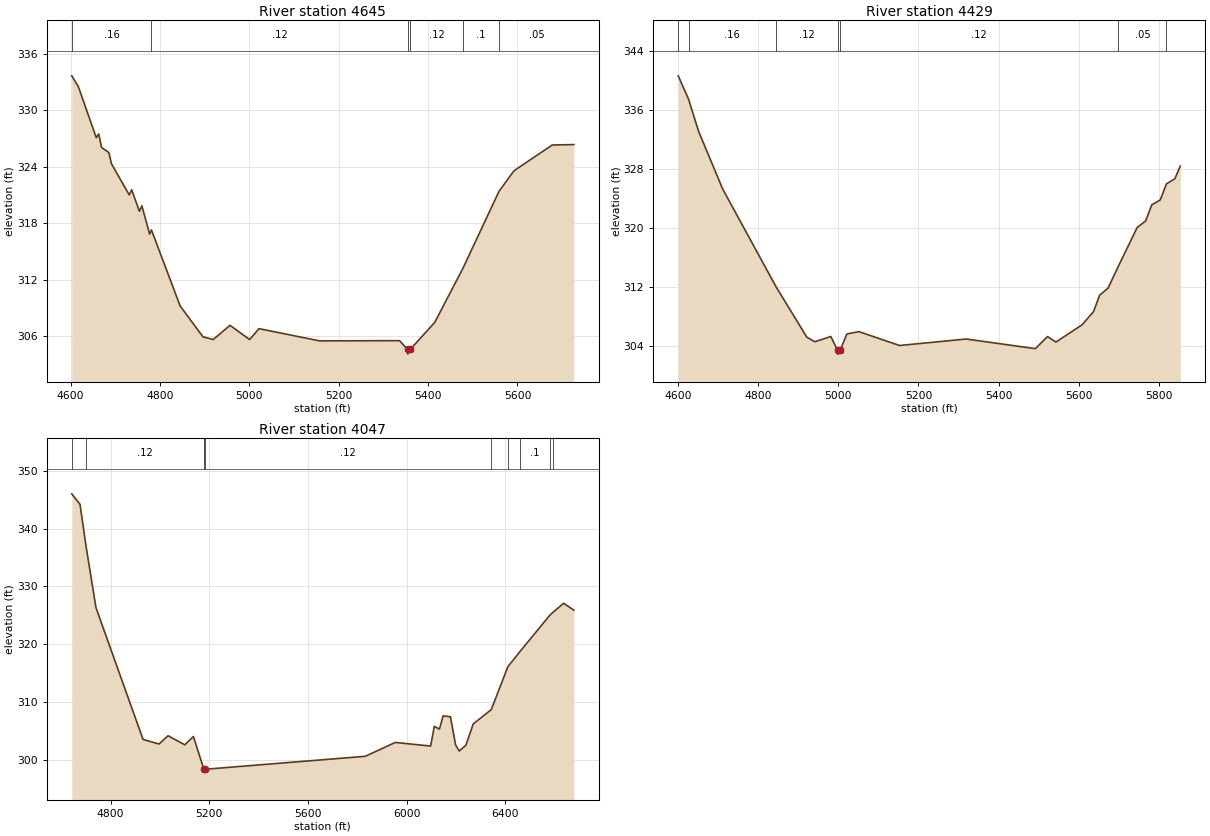
Type RM Length L Ch R = 1,4645,216,216,216
BEGIN DESCRIPTION:
LAKE BRANCH 37 0
END DESCRIPTION:
XS GIS Cut Line= 3
      3545352.45     10395791.94      3545193.15     10395454.14
      3544593.13     10395004.13
#Sta/Elev= 30
  4602.7  333.65  4617.4  332.50  4657.5  327.08  4663.0  327.47  4669.4  326.04
  4685.8  325.49  4691.5  324.31  4731.3  320.99  4736.8  321.53  4754.1  319.25
  4759.6  319.83  4776.9  316.83  4781.0  317.27  4845.2  309.19  4896.3  305.91
  4919.1  305.62  4956.8  307.13  5000.8  305.62  5021.6  306.78  5157.0  305.48
  5336.2  305.50  5354.0  304.57  5354.5  304.07  5360.1  304.57  5415.0  307.45
  5478.0  313.19  5558.8  321.38  5592.5  323.57  5677.9  326.30  5726.2  326.34
#Mann=6,-1,0
  4602.7    0.16       0  4781.0    0.12       0  5354.0    0.07       0
  5360.1    0.12       0  5478.0     0.1       0  5558.8    0.05       0
Bank Sta=5354,5360.1
Exp/Cntr=0.3,0.1

Type RM Length L Ch R = 1,4429,382,382,382
BEGIN DESCRIPTION:
LAKE BRANCH 7 0
END DESCRIPTION:
XS GIS Cut Line= 3
      3545364.18     10395842.61      3545369.39     10395306.16
      3544766.16     10394918.74
#Sta/Elev= 30
  4600.3  340.62  4626.0  337.46  4651.3  333.07  4711.3  325.26  4844.9  311.97
  4921.3  305.17  4941.3  304.55  4981.3  305.26  4998.2  303.37  4998.7  302.87
  5004.4  303.37  5021.3  305.61  5051.3  305.92  5152.9  304.04  5319.3  304.92
  5491.8  303.61  5522.1  305.25  5543.3  304.51  5608.9  306.87  5637.1  308.64
  5652.3  310.86  5673.4  311.83  5698.8  314.76  5746.1  320.06  5767.2  320.94
  5782.4  323.11  5803.6  323.79  5819.2  325.97  5839.9  326.65  5853.7  328.38
#Mann=7,-1,0
  4600.3    0.12       0  4626.0    0.16       0  4844.9    0.12       0
  4998.2    0.07       0  5004.4    0.12       0  5698.8    0.05       0
  5819.2     0.1       0
Bank Sta=4998.2,5004.4
Exp/Cntr=0.3,0.1

Type RM Length L Ch R = 1,4047,0,0,0
BEGIN DESCRIPTION:
LAKE BRANCH 1 0
END DESCRIPTION:
XS GIS Cut Line= 3
      3545530.41     10395896.11      3545825.55     10395396.99
      3544631.93     10394563.63
#Sta/Elev= 30
  4642.4  346.05  4675.9  344.22  4701.1  336.74  4740.5  326.34  4931.4  303.51
  4996.1  302.72  5032.8  304.15  5100.7  302.58  5135.5  304.02  5178.0  298.35
  5178.5  297.85  5184.2  298.35  5832.2  300.59  5954.3  302.99  6097.4  302.36
  6112.2  305.78  6133.1  305.30  6148.0  307.59  6177.6  307.44  6198.6  302.56
  6213.4  301.51  6240.4  302.52  6270.1  306.20  6343.5  308.69  6410.4  316.10
  6460.7  318.79  6580.9  325.04  6592.2  325.48  6636.5  327.10  6678.0  325.90
#Mann=9,-1,0
  4642.4     0.1       0  4701.1    0.12       0  5178.0    0.07       0
  5184.2    0.12       0  6343.5     0.1       0  6410.4    0.12       0
  6460.7     0.1       0  6580.9    0.05       0  6592.2    0.12       0
Bank Sta=5178,5184.2
Exp/Cntr=0.3,0.1

Chan Stop Cuts=-1