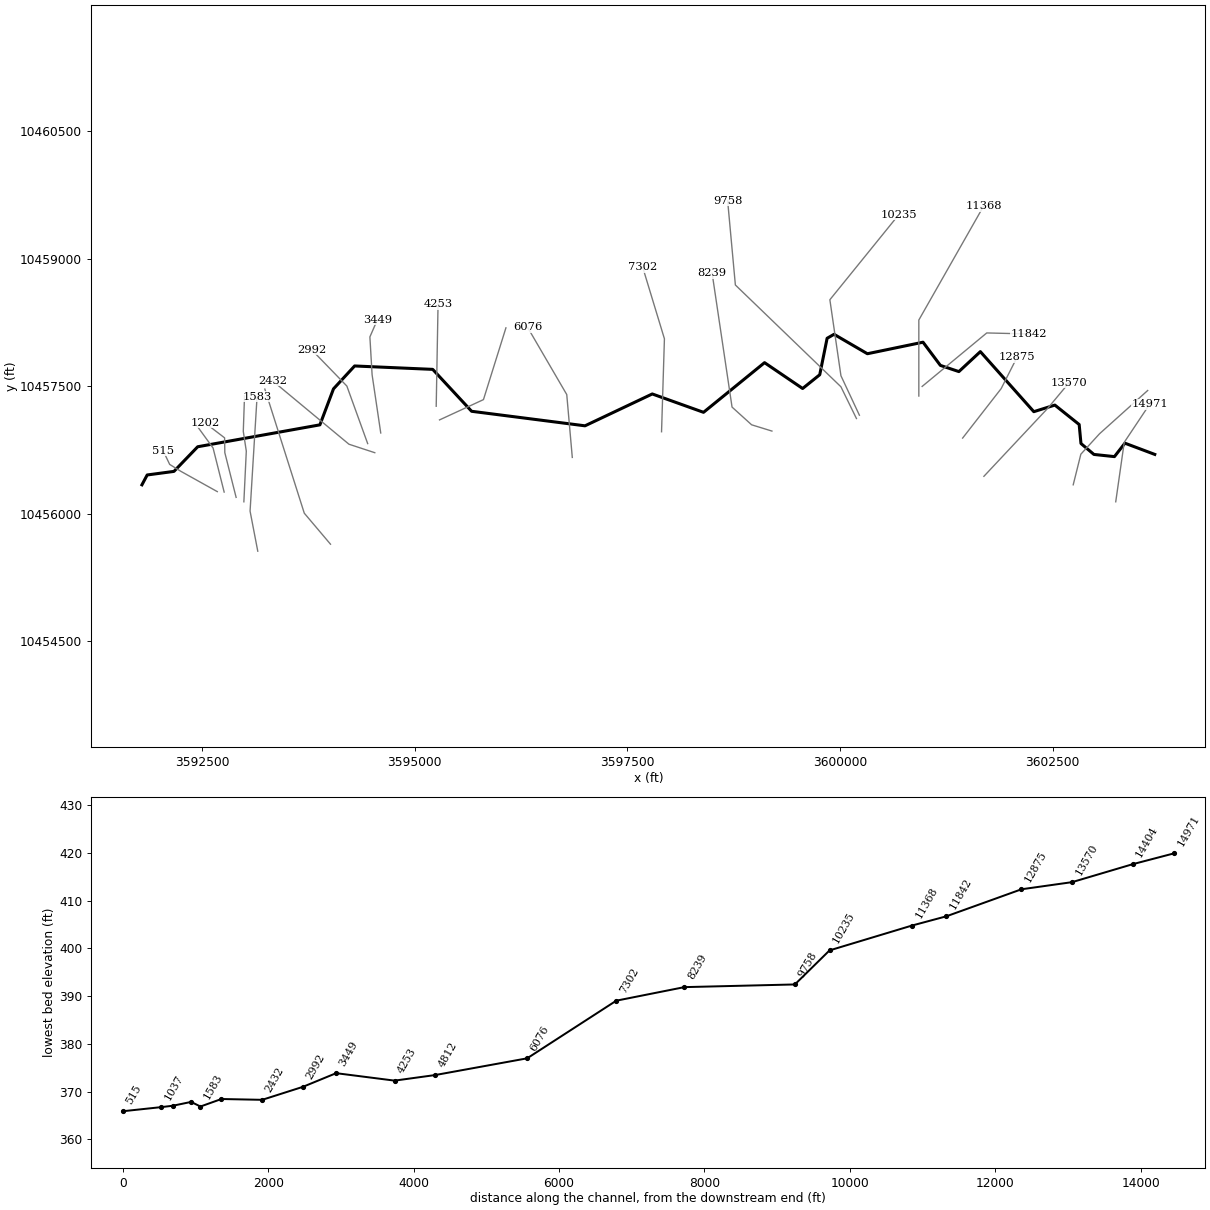
--- LITTLE BRUSHY CREEK.prj (project) ---

Proj Title=LITTLE BRUSHY CREEK Base Level Engineering
Current Plan=p01
Default Exp/Contr=0.3,0.1
English Units
Geom File=g01
Flow File=f01
Plan File=p01
Y Axis Title=Elevation
X Axis Title(PF)=Main Channel Distance
X Axis Title(XS)=Station
BEGIN DESCRIPTION:
LITTLE BRUSHY CREEK
END DESCRIPTION:
DSS Export Rating Curves= 0
DSS Export Rating Curve Sorted= 0
DSS Export Volume Flow Curves= 0
DXF OffsetX= 0
DXF OffsetY= 0
DXF ScaleX= 1
DXF ScaleY= 10

--- LITTLE BRUSHY CREEK.p01 (plan) ---

Plan Title=Multiple Run
Short Identifier=Multiple
Geom File=g01
Flow File=f01
Subcritical Flow
K Sum by GR= 0
Std Step Tol= 0.01
Critical Tol= 0.01
Num of Std Step Trials= 20
Max Error Tol= 0.3
Flow Tol Ratio= 0.001
Split Flow NTrial= 30
Split Flow Tol= 0.02
Split Flow Ratio= 0.02
Log Output Level= 0
Friction Slope Method= 1
Unsteady Friction Slope Method= 2
Unsteady Bridges Friction Slope Method= 1
Parabolic Critical Depth
Global Vel Dist=  1 , 1 , 1
Global Log Level= 0
CheckData=True
Encroach Param= -1, 0, 0, 0
BEGIN DESCRIPTION:
Multiple Run
END DESCRIPTION:

--- LITTLE BRUSHY CREEK.f01 (steady flow) ---

Flow Title=Multiple
Program Version=4.10
Number of Profiles= 7
Profile Names=10-year,25-year,50-year,1pct_min,100-year,1pct_plu,500-year
River Rch & RM=LITTLE BRUSHY CR,Reach-1         ,14971
    2249    3266    4152    3845    5200    7032    8140
River Rch & RM=LITTLE BRUSHY CR,Reach-1         ,11368
    2667    3895    4970    4616    6242    8442    9829
River Rch & RM=LITTLE BRUSHY CR,Reach-1         ,9758
    4312    6350    8144    7584   10257   13871   16244
River Rch & RM=LITTLE BRUSHY CR,Reach-1         ,7302
    4312    6350    8144    7584   10257   13871   16244
River Rch & RM=LITTLE BRUSHY CR,Reach-1         ,3449
    4312    6350    8144    7584   10257   13871   16244
Boundary for River Rch & Prof#=LITTLE BRUSHY CR,Reach-1         , 1
Up Type= 0
Dn Type= 3
Dn Slope=0.00135
Boundary for River Rch & Prof#=LITTLE BRUSHY CR,Reach-1         , 2
Up Type= 0
Dn Type= 3
Dn Slope=0.00135
Boundary for River Rch & Prof#=LITTLE BRUSHY CR,Reach-1         , 3
Up Type= 0
Dn Type= 3
Dn Slope=0.00135
Boundary for River Rch & Prof#=LITTLE BRUSHY CR,Reach-1         , 4
Up Type= 0
Dn Type= 3
Dn Slope=0.00135
Boundary for River Rch & Prof#=LITTLE BRUSHY CR,Reach-1         , 5
Up Type= 0
Dn Type= 3
Dn Slope=0.00135
Boundary for River Rch & Prof#=LITTLE BRUSHY CR,Reach-1         , 6
Up Type= 0
Dn Type= 3
Dn Slope=0.00135
Boundary for River Rch & Prof#=LITTLE BRUSHY CR,Reach-1         , 7
Up Type= 0
Dn Type= 3
Dn Slope=0.00135
DSS Import GetInterval= 0
DSS Import GetPeak= 0
DSS Import FillOption= 0

--- LITTLE BRUSHY CREEK.g01 (geometry) ---

Geom Title=Existing Conditions
Program Version=4.10

River Reach=LITTLE BRUSHY CR,Reach-1
Reach XY= 30
      3603701.17     10456699.38      3603349.88     10456831.57
      3603226.86     10456673.39      3602985.75     10456699.06
      3602833.39     10456827.56      3602812.26     10457051.11
      3602526.55     10457279.77      3602278.82     10457202.16
      3601650.35     10457908.69       3601397.8      10457673.8
      3601180.34     10457746.76      3600976.15     10458019.71
      3600322.04     10457883.92      3599930.05     10458112.51
      3599848.57     10458065.81      3599761.82      10457636.8
      3599560.55     10457474.84      3599112.81     10457778.98
      3598395.39     10457194.62      3597792.71     10457410.67
      3597001.57     10457035.87      3595668.58     10457206.72
      3595211.29     10457699.95      3594292.93     10457740.05
      3594044.45     10457470.67      3593884.78     10457047.27
      3592447.72     10456789.45      3592168.38     10456499.49
      3591853.98      10456457.5      3591792.11     10456341.64

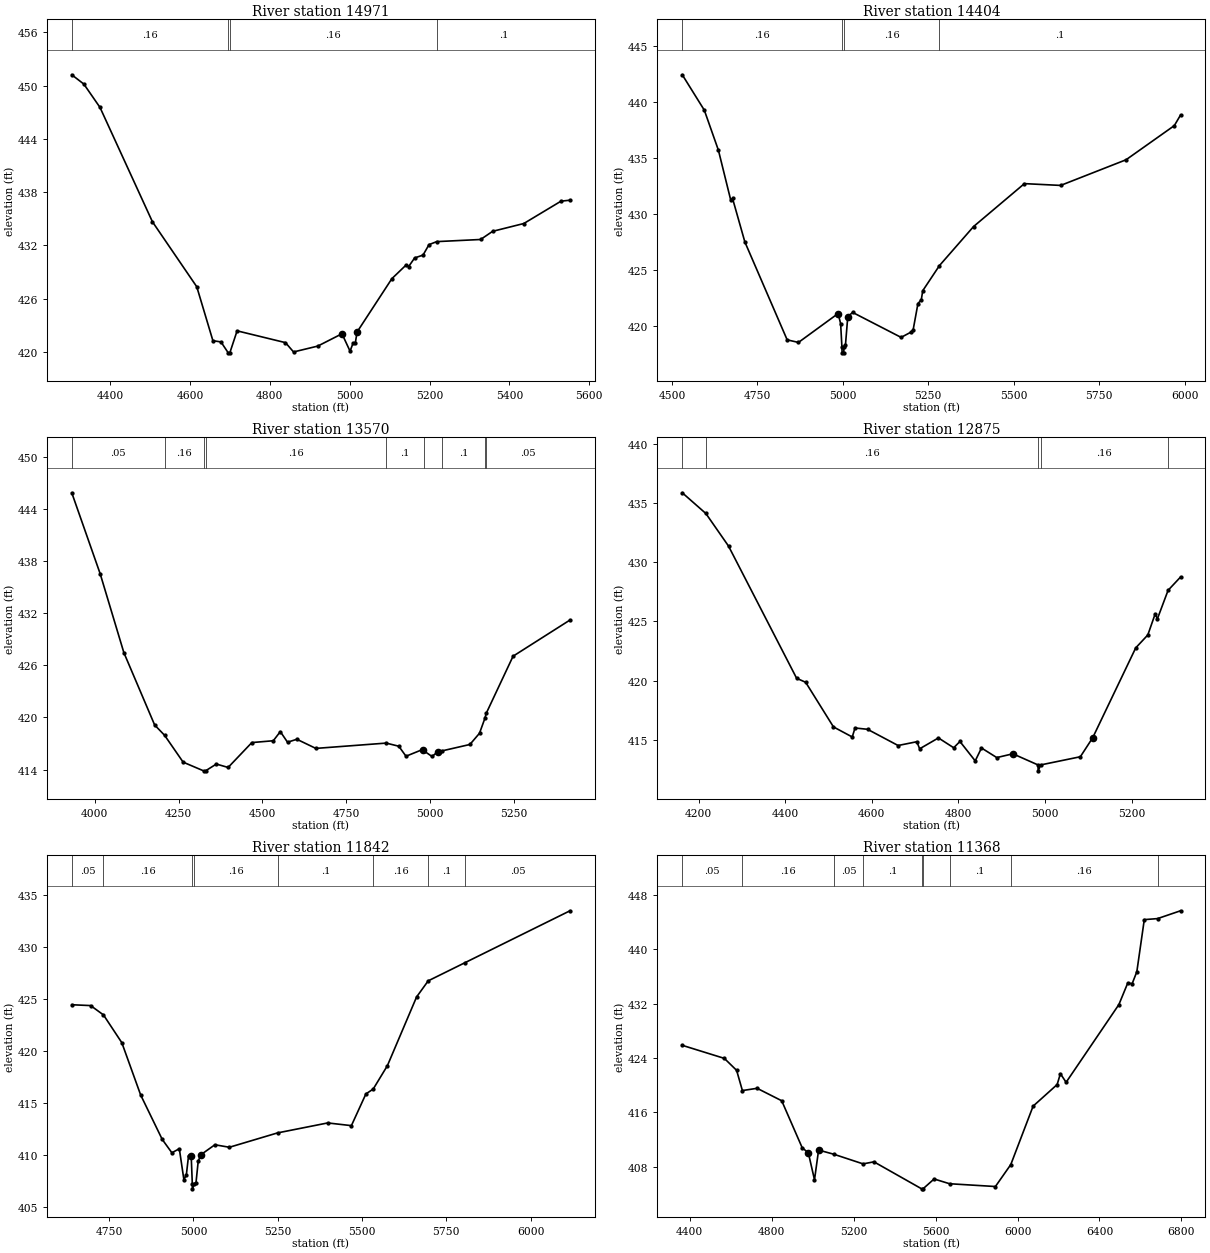
Type RM Length L Ch R = 1 ,14971   ,567,567,567
BEGIN DESCRIPTION:
LITTLE BRUSHY CREEK 2 1
END DESCRIPTION:
XS GIS Cut Line= 3
      3603242.11     10456141.69      3603342.11     10456841.64
      3603642.11     10457291.65
#Sta/Elev= 30
  4303.9  451.23  4334.2  450.18  4374.6  447.55  4505.9  434.66    4617  427.33
  4657.4  421.25  4677.6  421.11  4695.8  419.88  4699.8  419.88    4718  422.36
  4839.2  421.03  4859.4  419.98    4920  420.64  4980.7  422.03  5000.9  420.07
  5008.4  420.96    5014  420.96  5018.5  422.23  5105.6  428.24  5141.7   429.8
  5147.7  429.61  5162.7  430.58  5183.7   430.9  5198.7  432.08  5218.1  432.42
  5327.9  432.66    5358  433.58  5436.1  434.46  5529.3  436.98  5551.8  437.09
#Mann= 4 ,-1 , 0
  4303.9     .16       0  4695.8     .07       0  4699.8     .16       0
  5218.1      .1       0
Bank Sta=4980.7,5018.5
XS Rating Curve= 0 ,0
Exp/Cntr=0.3,0.1

Type RM Length L Ch R = 1 ,14404   ,834,834,834
BEGIN DESCRIPTION:
LITTLE BRUSHY CREEK 2 0
END DESCRIPTION:
XS GIS Cut Line= 4
       3602742.1     10456341.61      3602831.99     10456701.94
      3603050.74     10456941.53      3603617.76     10457451.33
#Sta/Elev= 30
    4530  442.45  4594.5  439.29  4635.8  435.71  4671.9  431.25  4677.1  431.41
  4713.2  427.52    4837  418.78  4870.1  418.55  4986.1  421.13  4993.5  420.23
  4997.3  418.12  4997.8  417.62  5002.7  417.62  5003.2  418.12  5007.7  418.34
  5014.4  420.85  5028.6  421.23  5170.5     419  5198.8  419.46  5205.6  419.65
  5219.8  422.02  5229.6  422.36  5233.9  423.17  5282.7  425.41  5382.7   428.9
  5531.4  432.73  5637.5  432.57  5828.9  434.86  5970.2  437.91  5988.3  438.85
#Mann= 4 ,-1 , 0
    4530     .16       0  4997.3     .07       0  5003.2     .16       0
  5282.7      .1       0
Bank Sta=4986.1,5014.4
XS Rating Curve= 0 ,0
Exp/Cntr=0.3,0.1

Type RM Length L Ch R = 1 ,13570   ,695,695,695
BEGIN DESCRIPTION:
LITTLE BRUSHY CREEK 15 0
END DESCRIPTION:
XS GIS Cut Line= 3
      3601692.13     10456441.67      3602442.11     10457241.64
      3602692.13     10457541.68
#Sta/Elev= 30
  3931.4  445.83  4016.1  436.53  4086.9  427.45  4178.8  419.13  4208.4  417.95
  4263.8  414.86  4324.8  413.86  4330.7  413.86  4362.9  414.64  4398.1  414.25
  4468.9  417.11  4532.9  417.32  4553.9  418.37  4575.4  417.15  4603.2  417.49
  4659.9  416.44  4869.9  417.05  4907.5  416.69    4929  415.54  4978.4  416.31
  4982.3  416.16  5006.7  415.51  5024.5  416.08  5037.1  416.16  5119.7  416.89
  5148.4  418.18  5164.3  419.88  5168.6  420.48  5248.6  427.04  5418.5   431.2
#Mann= 9 ,-1 , 0
  3931.4     .05       0  4208.4     .16       0  4324.8     .07       0
  4330.7     .16       0  4869.9      .1       0  4982.3     .16       0
  5037.1      .1       0  5164.3     .16       0  5168.6     .05       0
Bank Sta=4978.4,5024.5
XS Rating Curve= 0 ,0
Exp/Cntr=0.3,0.1

Type RM Length L Ch R = 1 ,12875   ,1033,1033,1033
BEGIN DESCRIPTION:
LITTLE BRUSHY CREEK 11 2
END DESCRIPTION:
XS GIS Cut Line= 3
      3601442.08     10456891.61      3601894.49     10457472.78
      3602081.98     10457842.56
#Sta/Elev= 30
    4162  435.86  4216.5  434.11  4268.8  431.36  4426.2  420.19  4447.1  419.85
  4511.3  416.08  4554.7  415.23  4561.1  415.99    4590  415.88  4660.6  414.51
    4704  414.83  4710.4  414.23  4753.8  415.15  4789.1  414.32  4803.5  414.85
  4838.8  413.21  4853.3   414.3  4888.6  413.49  4925.8  413.81  4983.8  412.87
  4984.3  412.37  4990.1  412.87  5081.7  413.56  5110.3  415.17  5209.7  422.76
  5237.6  423.85  5254.2  425.59  5259.9  425.23  5284.4  427.62  5313.1  428.74
#Mann= 5 ,-1 , 0
    4162     .05       0  4216.5     .16       0  4983.8     .07       0
  4990.1     .16       0  5284.4      .1       0
Bank Sta=4925.8,5110.3
XS Rating Curve= 0 ,0
Exp/Cntr=0.3,0.1

Type RM Length L Ch R = 1 ,11842   ,474,474,474
BEGIN DESCRIPTION:
LITTLE BRUSHY CREEK 10 2
END DESCRIPTION:
XS GIS Cut Line= 3
      3600965.97     10457499.23      3601725.52     10458128.58
      3602217.07     10458116.64
#Sta/Elev= 30
    4639  424.42    4695  424.34  4733.1  423.44  4787.5  420.77  4843.5  415.73
  4907.3  411.47    4936  410.18  4958.1  410.57  4971.6   407.6  4978.9  408.04
  4985.4  409.88  4993.3   409.9  4996.6  407.21  4997.1  406.71    5003  407.21
  5007.6  407.31  5014.1  409.36  5021.9  409.99  5063.6  410.95  5106.6  410.71
  5249.4  412.09  5398.3  413.05  5468.6  412.79  5511.6  415.84  5533.3  416.31
  5575.4  418.56    5662  425.17  5696.5  426.72  5805.8  428.47  6117.1  433.46
#Mann= 8 ,-1 , 0
    4639     .05       0  4733.1     .16       0  4996.6     .07       0
    5003     .16       0  5249.4      .1       0  5533.3     .16       0
  5696.5      .1       0  5805.8     .05       0
Bank Sta=4993.3,5021.9
XS Rating Curve= 0 ,0
Exp/Cntr=0.3,0.1

Type RM Length L Ch R = 1 ,11368   ,1133,1133,1133
BEGIN DESCRIPTION:
LITTLE BRUSHY CREEK 10 3
END DESCRIPTION:
XS GIS Cut Line= 3
      3600926.91     10457386.42      3600926.91     10458280.49
      3601686.27     10459616.96
#Sta/Elev= 30
  4364.2  425.87  4569.4  423.95  4629.4  422.19  4657.5  419.22  4729.4  419.55
  4849.4  417.72  4949.4  410.81  4979.4  410.06  5009.4   406.1  5029.4  410.47
  5103.4  409.86  5246.4  408.44  5299.5  408.74  5532.4  404.77  5538.8  404.77
  5593.1  406.22  5668.6  405.52  5892.2  405.11  5967.3  408.34  6076.2  416.93
  6193.4   420.1  6209.3   421.7  6237.2  420.43  6494.7  431.86    6538  435.03
  6559.6  434.94  6582.3  436.69  6618.7  444.35  6683.4   444.5  6795.4  445.65
#Mann= 9 ,-1 , 0
  4364.2     .05       0  4657.5     .16       0  5103.4     .05       0
  5246.4      .1       0  5532.4     .07       0  5538.8      .1       0
  5668.6      .1       0  5967.3     .16       0  6683.4     .05       0
Bank Sta=4979.4,5029.4
XS Rating Curve= 0 ,0
Exp/Cntr=0.3,0.1

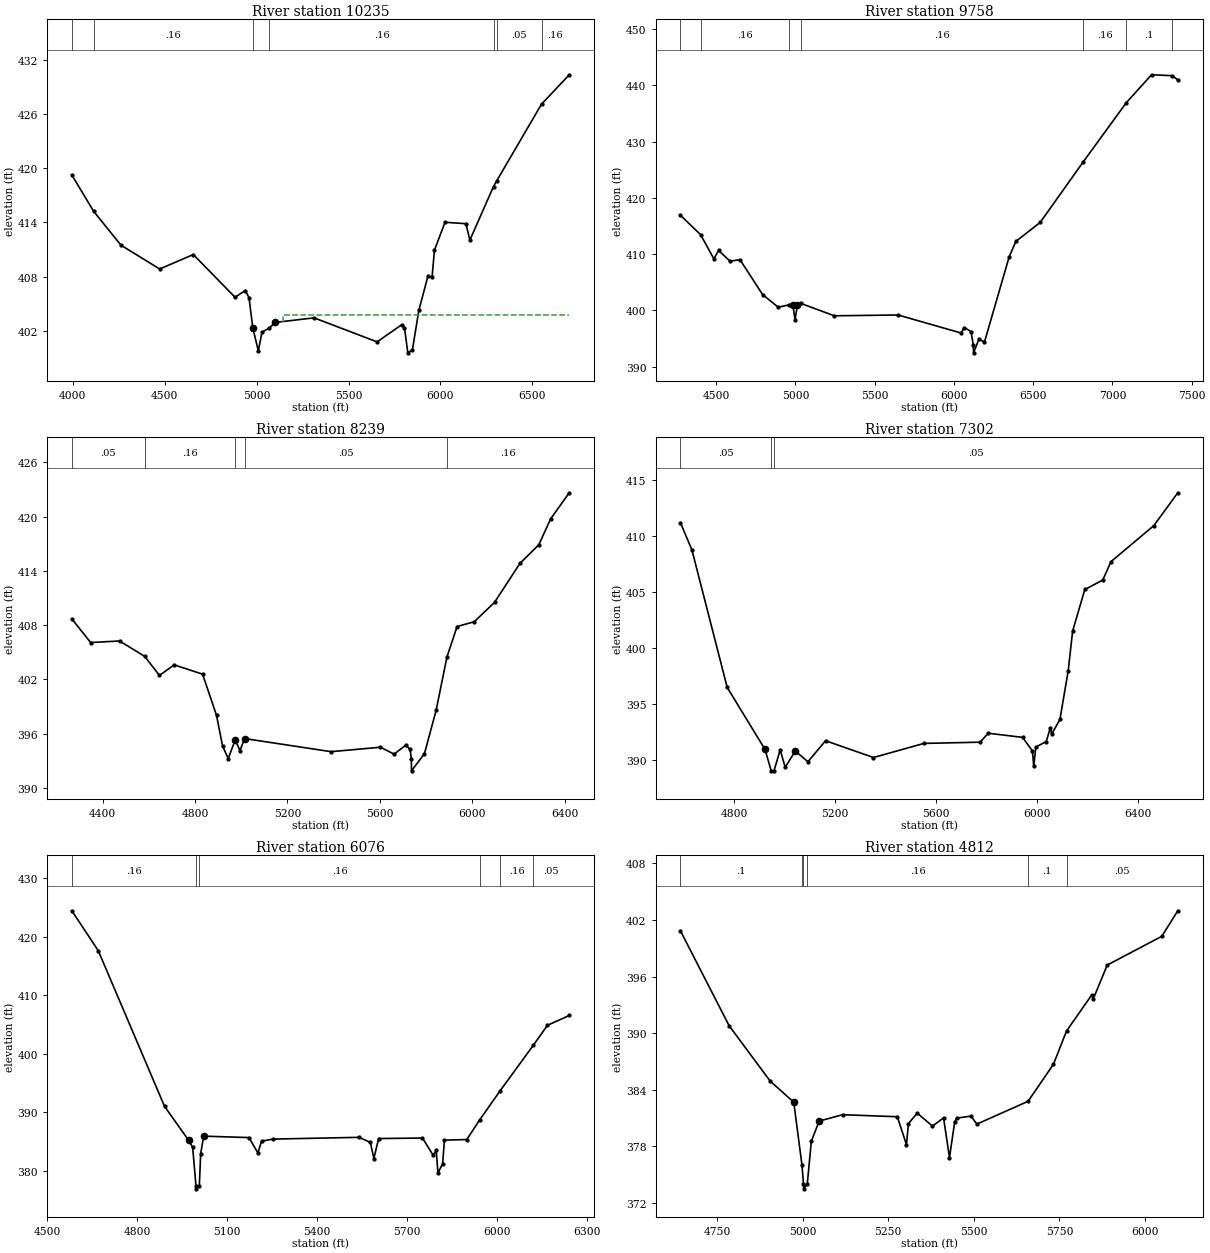
Type RM Length L Ch R = 1 ,10235   ,477,477,477
BEGIN DESCRIPTION:
LITTLE BRUSHY CREEK 13 2
END DESCRIPTION:
XS GIS Cut Line= 4
      3600228.13      10457160.7      3600011.11     10457625.11
       3599880.9      10458519.2      3600692.54     10459521.82
#Sta/Elev= 30
  3994.8  419.23  4113.5  415.22  4261.7  411.48  4472.8  408.84  4655.5  410.44
  4882.5  405.72  4938.4  406.46  4958.7  405.67  4978.9  402.37  5009.2  399.79
  5029.4  401.86  5069.8  402.32  5100.1  402.93  5312.4  403.44  5655.6  400.78
    5790  402.69  5804.4  402.35  5822.5  399.57  5847.5   399.9  5882.7  404.28
  5932.3  408.08  5954.4  407.94  5967.5  410.93    6025  414.01  6138.5  413.85
  6160.3  412.04  6288.7  417.96  6306.1  418.59  6549.9  427.07  6700.9  430.32
#Mann= 7 ,-1 , 0
  3994.8     .05       0  4113.5     .16       0  4978.9     .12       0
  5069.8     .16       0  6288.7      .1       0  6306.1     .05       0
  6549.9     .16       0
#XS Ineff= 2 , 0
       0                 5142.51       0  403.78
Permanent Ineff=
       F       T
Bank Sta=4978.9,5100.1
XS Rating Curve= 0 ,0
Exp/Cntr=0.3,0.1

Type RM Length L Ch R = 1 ,9758    ,1519,1519,1519
BEGIN DESCRIPTION:
LITTLE BRUSHY CREEK 12 1
END DESCRIPTION:
XS GIS Cut Line= 4
       3600193.4     10457121.65      3600011.11      10457494.9
      3598769.79     10458692.81      3598678.65     10459686.69
#Sta/Elev= 30
  4274.3  416.91  4402.4  413.44  4485.7  409.15    4515  410.64  4588.2  408.73
  4650.2  409.02  4792.8  402.81  4891.8  400.55  4962.6  400.99  4983.6  401.02
  4997.8   398.3  5011.9  400.86  5033.3  401.24  5245.3  399.03  5648.4  399.17
  6044.6  395.97  6065.7  396.94  6108.1  396.22  6122.3  393.88    6124  392.44
  6157.8  394.87    6193  394.36  6348.6   409.5  6391.1  412.27  6544.1  415.62
  6815.3  426.37    7088  436.93  7247.1  441.89  7377.1  441.73  7412.8  440.99
#Mann= 7 ,-1 , 0
  4274.3     .05       0  4402.4     .16       0  4962.6     .12       0
  5033.3     .16       0  6815.3     .16       0    7088      .1       0
  7377.1     .05       0
#Block Obstruct= 2 , 0
                         5052.16          398.23
Bank Sta=4983.6,5011.9
XS Rating Curve= 0 ,0
Exp/Cntr=0.3,0.1

Type RM Length L Ch R = 1 ,8239    ,937,937,937
BEGIN DESCRIPTION:
LITTLE BRUSHY CREEK 16 0
END DESCRIPTION:
XS GIS Cut Line= 4
      3599199.52     10456974.05      3598960.77     10457047.85
      3598730.73     10457256.18      3598496.36     10458831.69
#Sta/Elev= 30
  4266.7  408.68  4348.1  406.07  4473.3  406.24    4582  404.54  4645.9  402.43
  4709.4   403.6  4832.5  402.57  4893.1     398    4919  394.63  4943.7  393.24
    4974  395.32  4994.2  394.11  5014.5  395.45  5388.5     394  5602.5  394.49
  5661.5  393.73    5712  394.71  5731.2  394.24  5736.2  393.17  5736.9  391.88
  5792.9  393.78  5843.5  398.57  5890.4  404.48  5934.2  407.84  6008.6  408.37
  6096.2  410.51  6206.6  414.83  6288.3  416.89  6338.9  419.74  6419.8  422.63
#Mann= 5 ,-1 , 0
  4266.7     .05       0    4582     .16       0    4974     .07       0
  5014.5     .05       0  5890.4     .16       0
Bank Sta=4974,5014.5
XS Rating Curve= 0 ,0
Exp/Cntr=0.3,0.1

Type RM Length L Ch R = 1 ,7302    ,1226,1226,1226
BEGIN DESCRIPTION:
LITTLE BRUSHY CREEK 9 1
END DESCRIPTION:
XS GIS Cut Line= 3
      3597901.74       10456966.      3597935.59     10458059.79
      3597680.39     10458900.91
#Sta/Elev= 30
  4585.7  411.21  4631.4  408.78  4771.4  396.49  4921.5  390.95    4946  389.04
  4957.1  389.04  4981.5  390.92  5001.5  389.36  5041.6  390.81  5091.6  389.85
  5161.6  391.73  5351.7  390.23  5551.8  391.49  5774.5   391.6  5807.3   392.4
  5943.2  392.03  5982.3  390.82  5987.5  389.43  5995.5  391.16  6037.3  391.66
  6053.3   392.9  6058.5  392.31  6091.4  393.64  6124.3  397.99  6141.8  401.53
  6190.1  405.24  6261.1  406.08    6294  407.73  6463.7  410.94    6559  413.88
#Mann= 3 ,-1 , 0
  4585.7     .05       0    4946     .03       0  4957.1     .05       0
Bank Sta=4921.5,5041.6
XS Rating Curve= 0 ,0
Exp/Cntr=0.3,0.1

Type RM Length L Ch R = 1 ,6076    ,1264,1264,1264
BEGIN DESCRIPTION:
LITTLE BRUSHY CREEK 13 0
END DESCRIPTION:
XS GIS Cut Line= 3
      3596852.26     10456663.97      3596787.15     10457403.54
      3596326.67     10458194.42
#Sta/Elev= 30
  4582.5  424.42  4670.5  417.61  4891.4  391.04  4971.7  385.25    4985  384.08
  4996.2  377.47  4996.7  376.97  5007.3  377.47  5011.8     383  5021.9  385.96
  5172.4  385.72  5202.6  383.09  5214.5   385.1  5252.8  385.46  5540.2  385.76
  5577.3  384.88    5589  382.14  5604.7  385.55  5750.9  385.64  5786.8  382.68
  5796.7  383.53  5802.5  379.66  5818.2  381.28    5824  385.28  5898.4  385.38
  5941.7  388.75  6008.9  393.65  6119.9  401.44  6167.5  404.88  6240.1  406.55
#Mann= 6 ,-1 , 0
  4582.5     .16       0  4996.2     .07       0  5007.3     .16       0
  5941.7     .05       0  6008.9     .16       0  6119.9     .05       0
Bank Sta=4971.7,5021.9
XS Rating Curve= 0 ,0
Exp/Cntr=0.3,0.1

Type RM Length L Ch R = 1 ,4812    ,559,559,559
BEGIN DESCRIPTION:
LITTLE BRUSHY CREEK 11 0
END DESCRIPTION:
XS GIS Cut Line= 3
      3595291.29     10457105.36      3595807.77     10457344.07
      3596071.94     10458188.54
#Sta/Elev= 30
  4642.3  400.86  4784.6  390.79  4904.8   384.9  4973.6  382.67  4997.8  375.96
    5002  373.97  5002.5  373.47  5013.1  373.97    5025  378.51  5047.9  380.66
  5116.7  381.34  5276.4  381.12    5303  378.16  5308.9   380.4  5334.5   381.5
  5379.1  380.13  5411.5     381  5428.8  376.79    5444  380.57  5449.7  380.97
  5491.6  381.19  5508.9  380.34  5658.5  382.76  5732.6  386.69  5770.9  390.22
    5844  394.02  5849.3  393.65  5889.8  397.22  6049.3  400.27  6096.1  402.98
#Mann= 6 ,-1 , 0
  4642.3      .1       0  4997.8     .16       0    5002     .07       0
  5013.1     .16       0  5658.5      .1       0  5770.9     .05       0
Bank Sta=4973.6,5047.9
XS Rating Curve= 0 ,0
Exp/Cntr=0.3,0.1

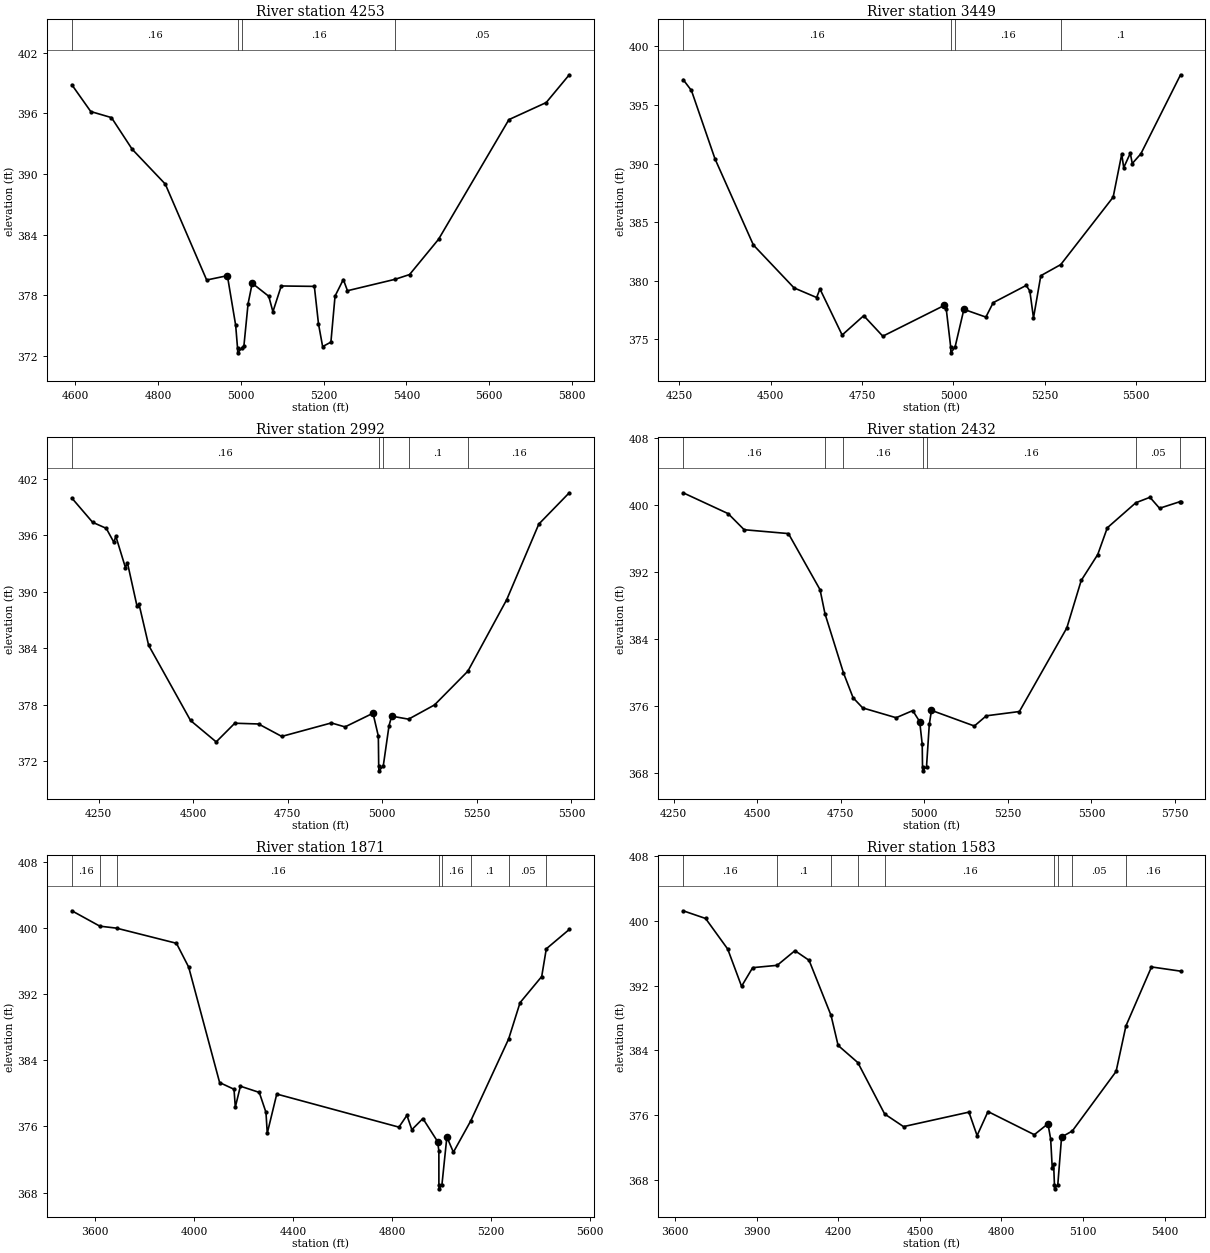
Type RM Length L Ch R = 1 ,4253    ,804,804,804
BEGIN DESCRIPTION:
LITTLE BRUSHY CREEK 1 0
END DESCRIPTION:
XS GIS Cut Line= 2
      3595252.22     10457265.97       3595273.9     10458467.38
#Sta/Elev= 30
  4591.8  398.84  4637.5  396.19  4687.5  395.59  4737.5  392.46  4817.5  389.01
  4917.5  379.51  4967.5  379.94  4987.5  375.04    4992   372.8  4992.5   372.3
  5003.1   372.8  5007.5  373.01  5017.5  377.16  5027.5  379.19  5067.5   377.9
  5077.5  376.37  5097.6  378.92  5177.6  378.88  5187.6  375.17  5197.6  372.92
  5217.6  373.36  5227.6  377.92  5247.6  379.56  5257.6  378.45  5372.6  379.58
  5407.6  380.05  5477.6  383.54  5647.6  395.39  5737.7  397.08  5793.4  399.83
#Mann= 4 ,-1 , 0
  4591.8     .16       0    4992     .07       0  5003.1     .16       0
  5372.6     .05       0
Bank Sta=4967.5,5027.5
XS Rating Curve= 0 ,0
Exp/Cntr=0.3,0.1

Type RM Length L Ch R = 1 ,3449    ,457,457,457
BEGIN DESCRIPTION:
LITTLE BRUSHY CREEK 9 0
END DESCRIPTION:
XS GIS Cut Line= 4
      3594600.05     10456951.58      3594498.48     10457636.52
      3594472.44     10458081.83      3594560.98     10458284.97
#Sta/Elev= 30
    4261  397.17  4283.7  396.24  4348.1  390.41  4453.1  383.06  4564.3   379.4
    4626  378.58  4635.1  379.31  4695.8  375.38  4754.8  377.03    4807  375.28
  4975.3  377.91  4980.3  377.64  4992.6  374.36  4993.1  373.86  5004.6  374.36
  5028.7  377.57  5088.8  376.91  5108.8  378.14    5199  379.61    5209  379.14
    5219  376.84    5239  380.44  5293.6  381.39  5436.8  387.14  5460.3  390.81
  5465.7  389.66  5483.7  390.89  5489.1  390.01  5512.6  390.84  5621.1  397.58
#Mann= 4 ,-1 , 0
    4261     .16       0  4992.6     .07       0  5004.6     .16       0
  5293.6      .1       0
Bank Sta=4975.3,5028.7
XS Rating Curve= 0 ,0
Exp/Cntr=0.3,0.1

Type RM Length L Ch R = 1 ,2992    ,560,560,560
BEGIN DESCRIPTION:
LITTLE BRUSHY CREEK 8 0
END DESCRIPTION:
XS GIS Cut Line= 3
      3594446.39     10456826.64      3594201.61     10457503.71
      3593787.55     10457930.79
#Sta/Elev= 30
  4179.5  399.93  4234.4  397.36  4270.4  396.72  4290.4  395.25  4295.8  395.87
  4321.1  392.56  4326.4  393.07  4351.8  388.46  4357.1  388.67  4382.4  384.32
  4493.2  376.34    4561  374.07  4610.2  376.05    4673  375.97  4734.3  374.65
  4865.4  376.08  4901.5  375.66  4975.5  377.11  4989.6  374.69  4990.6   371.5
  4991.1     371  5002.6   371.5  5017.9  375.79  5024.9   376.8  5069.5  376.48
  5138.1  377.99  5226.3  381.57  5328.9  389.15  5413.8  397.17  5494.3  400.49
#Mann= 5 ,-1 , 0
  4179.5     .16       0  4990.6     .07       0  5002.6     .16       0
  5069.5      .1       0  5226.3     .16       0
Bank Sta=4975.5,5024.9
XS Rating Curve= 0 ,0
Exp/Cntr=0.3,0.1

Type RM Length L Ch R = 1 ,2432    ,561,561,561
BEGIN DESCRIPTION:
LITTLE BRUSHY CREEK 7 0
END DESCRIPTION:
XS GIS Cut Line= 3
      3594530.03     10456719.49      3594226.17     10456819.33
       3593327.7     10457565.89
#Sta/Elev= 30
  4278.5  401.47  4413.2  398.98  4461.1  397.06  4593.5   396.6  4688.1   389.9
  4702.8  387.04  4758.1  379.98    4787     377  4815.7  375.79  4915.7  374.62
  4965.4  375.47  4986.2  374.15  4993.7  371.46  4994.6  368.78  4995.1  368.28
  5006.6  368.78  5014.9  373.83  5021.4   375.5  5149.7  373.63  5185.5  374.85
  5284.4  375.36  5426.3  385.34  5469.3     391  5518.8   394.1  5547.4  397.29
  5632.7  400.28    5675  400.93  5703.7  399.62  5765.6  400.42  5766.5  400.42
#Mann= 7 ,-1 , 0
  4278.5     .16       0  4702.8      .1       0  4758.1     .16       0
  4994.6     .07       0  5006.6     .16       0  5632.7     .05       0
  5765.6     .16       0
Bank Sta=4986.2,5021.4
XS Rating Curve= 0 ,0
Exp/Cntr=0.3,0.1

Type RM Length L Ch R = 1 ,1871    ,288,288,288
BEGIN DESCRIPTION:
Mapping XS 50bb73ef
END DESCRIPTION:
XS GIS Cut Line= 3
      3594009.14     10455643.14        3593701.      10456007.7
      3593237.43     10457467.73
#Sta/Elev= 30
    3507  402.07    3620  400.21  3687.4  399.97  3929.5  398.14  3978.9  395.26
  4103.9   381.3    4162  380.49  4167.3  378.33  4187.8  380.86    4264  380.11
  4291.1   377.7  4296.3  375.17  4334.7  379.91  4828.2  375.91  4860.5  377.34
  4880.3   375.6    4925  376.95  4984.3  374.17  4989.5  373.04  4989.6  368.95
  4990.1  368.45  5001.9  368.95  5021.8  374.72  5048.2  372.88  5118.3  376.67
  5271.3  386.57  5317.4  390.96  5404.9  394.12  5423.4  397.47  5516.2  399.81
#Mann= 8 ,-1 , 0
    3507     .16       0    3620      .1       0  3687.4     .16       0
  4989.6     .07       0  5001.9     .16       0  5118.3      .1       0
  5271.3     .05       0  5423.4     .16       0
Bank Sta=4984.3,5021.8
XS Rating Curve= 0 ,0
Exp/Cntr=0.3,0.1

Type RM Length L Ch R = 1 ,1583    ,129,129,129
BEGIN DESCRIPTION:
LITTLE BRUSHY CREEK 6 0
END DESCRIPTION:
XS GIS Cut Line= 3
      3593154.12     10455560.66      3593063.58     10456032.35
      3593145.82     10457378.24
#Sta/Elev= 30
  3629.6  401.24  3712.1  400.29  3793.5  396.51  3844.4  391.91  3885.2  394.21
  3975.4   394.5  4040.6  396.31  4092.6  395.12  4173.4  388.31  4199.4   384.6
  4271.9  382.48  4370.5  376.13  4439.8  374.57  4680.3  376.36  4710.3  373.46
  4750.4  376.43  4920.7  373.57  4970.8  374.92  4980.8  373.03  4986.7  369.42
  4991.7  369.93  4994.7  367.38  4995.2  366.88    5007  367.38  5020.9  373.28
  5060.4  374.03  5221.3  381.38  5257.5  387.01  5351.5   394.3  5458.3  393.78
#Mann= 9 ,-1 , 0
  3629.6     .16       0  3975.4      .1       0  4173.4     .05       0
  4271.9      .1       0  4370.5     .16       0  4994.7     .07       0
    5007     .16       0  5060.4     .05       0  5257.5     .16       0
Bank Sta=4970.8,5020.9
XS Rating Curve= 0 ,0
Exp/Cntr=0.3,0.1

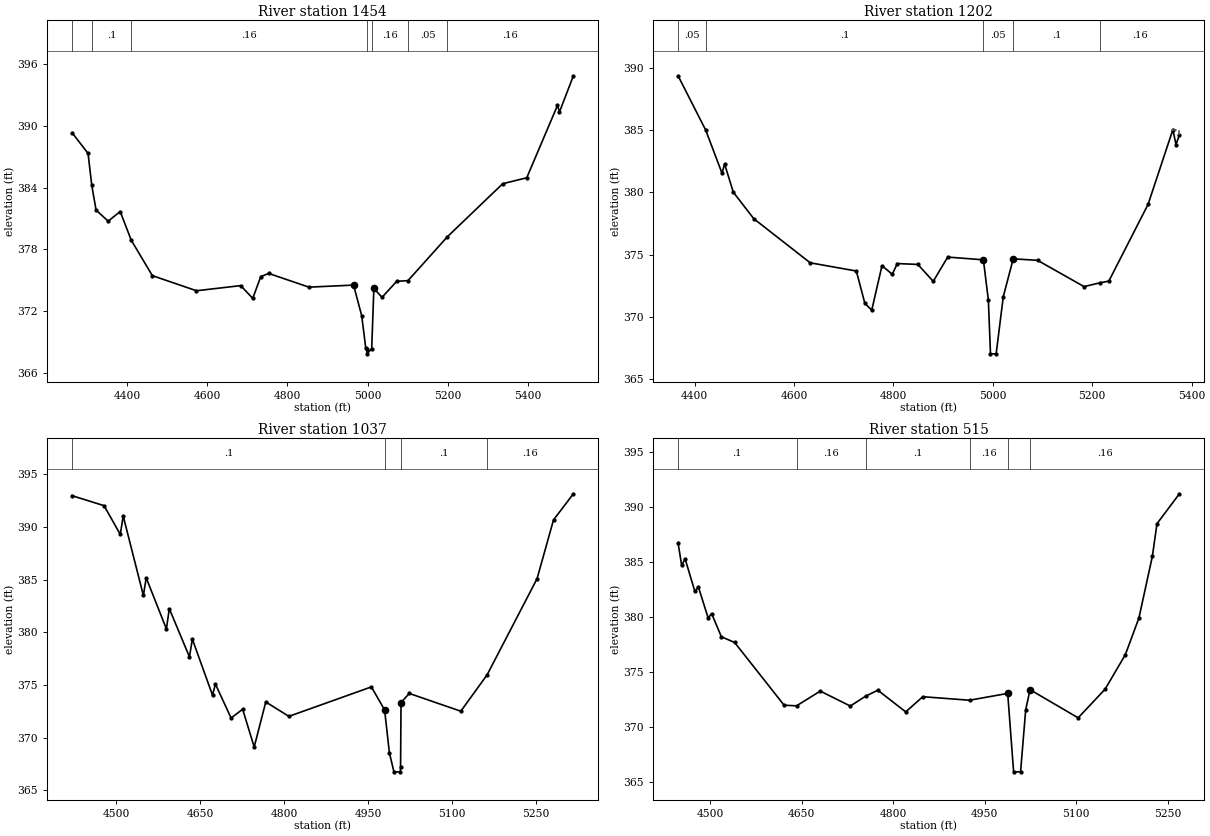
Type RM Length L Ch R = 1 ,1454    ,252,252,252
BEGIN DESCRIPTION:
LITTLE BRUSHY CREEK 5 0
END DESCRIPTION:
XS GIS Cut Line= 4
      3592990.67     10456141.78      3593019.31     10456738.08
      3592983.87      10456970.5      3592998.44     10457387.85
#Sta/Elev= 30
  4263.2  389.33  4303.1  387.32  4312.4   384.2  4323.1  381.81  4353.2  380.73
  4383.2  381.67  4410.8  378.88  4463.3  375.44  4573.4  373.97  4683.5  374.47
  4713.6  373.23  4733.6  375.35  4753.6  375.65  4853.7  374.32  4964.9  374.52
  4985.2  371.54  4995.3  368.41  4997.8  368.34  4998.3  367.84  5010.1  368.34
  5015.5   374.2  5035.8  373.33  5072.5  374.89  5100.5  374.95  5198.8  379.22
  5336.6  384.37  5396.6  384.95  5473.2  391.98  5478.2  391.35  5512.9  394.86
#Mann= 7 ,-1 , 0
  4263.2     .05       0  4312.4      .1       0  4410.8     .16       0
  4997.8     .07       0  5010.1     .16       0  5100.5     .05       0
  5198.8     .16       0
Bank Sta=4964.9,5015.5
XS Rating Curve= 0 ,0
Exp/Cntr=0.3,0.1

Type RM Length L Ch R = 1 ,1202    ,165,165,165
BEGIN DESCRIPTION:
LITTLE BRUSHY CREEK 3 1
END DESCRIPTION:
XS GIS Cut Line= 4
      3592899.52     10456193.84      3592766.71     10456719.85
      3592764.11     10456894.33      3592532.33     10457071.42
#Sta/Elev= 30
  4366.6  389.37  4422.1  385.02  4455.1  381.54  4460.2  382.29  4477.8  380.02
    4519  377.89  4632.5  374.35  4725.3  373.69  4742.4   371.1  4756.3  370.55
  4776.9  374.12  4797.5  373.43  4807.8  374.29  4849.1  374.22    4880  372.86
  4909.1  374.81  4980.9  374.59  4990.9  371.37  4995.2  367.04  5006.6  367.04
  5020.9  371.62  5040.9  374.67  5089.9  374.55  5183.4  372.44    5215  372.74
  5233.3  372.88  5312.2  379.04  5362.1  385.04  5368.4  383.85  5375.3  384.62
#Mann= 5 ,-1 , 0
  4366.6     .05       0  4422.1      .1       0  4980.9     .05       0
  5040.9      .1       0    5215     .16       0
#XS Ineff= 2 , 0
                         5361.38          385.01
Permanent Ineff=
       F       F
Bank Sta=4980.9,5040.9
XS Rating Curve= 0 ,0
Exp/Cntr=0.3,0.1

Type RM Length L Ch R = 1 ,1037    ,522,522,522
BEGIN DESCRIPTION:
LITTLE BRUSHY CREEK 3 0
END DESCRIPTION:
XS GIS Cut Line= 3
       3592758.9      10456256.3      3592628.69     10456774.54
      3592416.93     10457066.36
#Sta/Elev= 30
  4421.4  392.98  4478.5  392.03  4507.5   389.3  4512.7  391.05  4548.7   383.5
  4553.8  385.17  4589.8  380.32    4595  382.24    4631  377.66  4636.1  379.35
  4672.1  374.03  4677.3  375.08  4705.3  371.85  4725.9  372.69  4746.5   369.1
  4767.2  373.38  4808.4  372.01  4955.7  374.81  4979.3  372.62  4987.8  368.56
  4995.9  366.74  5007.3  366.74  5007.8  367.24  5008.6  373.32  5023.3  374.19
  5115.3   372.5  5162.3  375.96  5251.4  385.09  5280.8  390.68  5316.3  393.16
#Mann= 4 ,-1 , 0
  4421.4      .1       0  4979.3     .05       0  5008.6      .1       0
  5162.3     .16       0
Bank Sta=4979.3,5008.6
XS Rating Curve= 0 ,0
Exp/Cntr=0.3,0.1

Type RM Length L Ch R = 1 ,515     ,0,0,0
BEGIN DESCRIPTION:
LITTLE BRUSHY CREEK 10 1
END DESCRIPTION:
XS GIS Cut Line= 4
      3592678.21      10456261.5      3592248.48      10456501.1
      3592118.27     10456581.83      3592042.12      10456741.6
#Sta/Elev= 30
    4447  386.72  4452.9  384.67  4458.6  385.25  4474.6  382.29  4480.3  382.71
  4496.3  379.89  4502.1  380.27  4518.1  378.17  4539.8  377.65  4620.9  371.95
  4641.3  371.89  4680.3  373.23  4729.5  371.87  4754.6  372.77  4774.6  373.31
  4820.4  371.34  4848.3  372.72    4925   372.4  4987.6  373.02  4997.3  365.89
  5008.7  365.89  5017.1  371.52  5024.2  373.36  5103.1   370.8  5147.4  373.41
  5180.6  376.55  5202.8  379.88  5224.9   385.5  5232.4  388.45  5269.2  391.17
#Mann= 6 ,-1 , 0
    4447      .1       0  4641.3     .16       0  4754.6      .1       0
    4925     .16       0  4987.6     .07       0  5024.2     .16       0
Bank Sta=4987.6,5024.2
XS Rating Curve= 0 ,0
Exp/Cntr=0.3,0.1

Chan Stop Cuts=-1
Use User Specified Reach Order=0
Composite Channel Slope=5