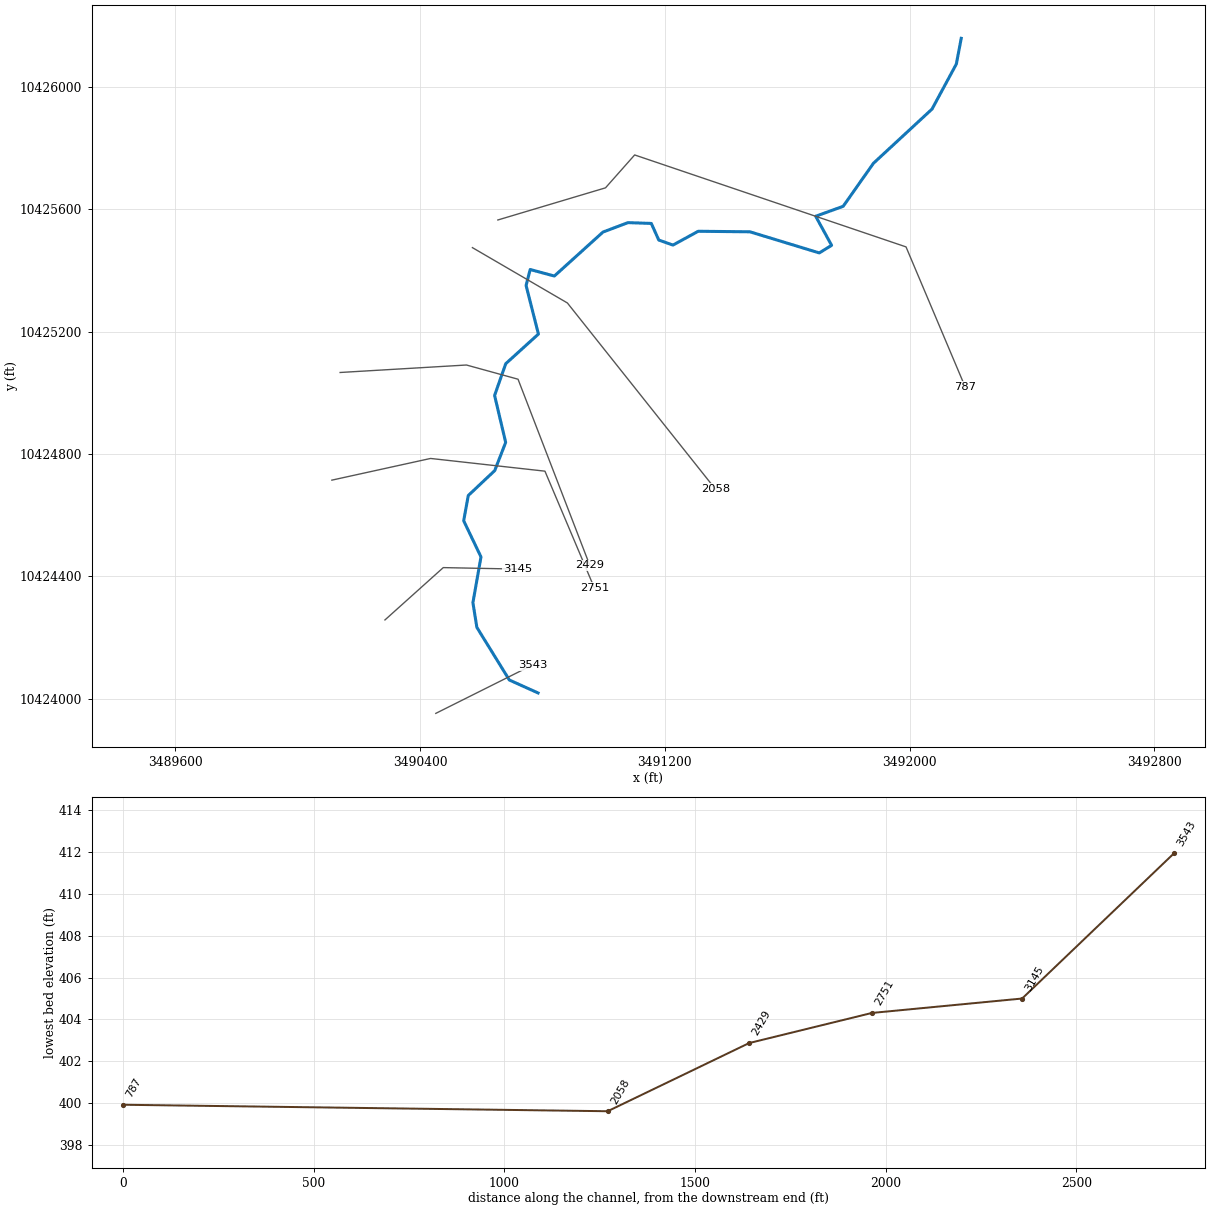
--- LONG BRANCH TRIB 1.prj (project) ---

Proj Title=LONG BRANCH TRIB 1 Base Level Engineering
Current Plan=p01
Default Exp/Contr=0.3,0.1
English Units
Geom File=g01
Flow File=f01
Plan File=p01
BEGIN DESCRIPTION:
LONG BRANCH TRIB 1
END DESCRIPTION:

--- LONG BRANCH TRIB 1.p01 (plan) ---

Plan Title=Multiple Run
Short Identifier=Multiple
Geom File=g01
Flow File=f01
Subcritical Flow
K Sum by GR= 0
Std Step Tol= 0.01
Critical Tol= 0.01
Num of Std Step Trials= 20
Max Error Tol= 0.3
Flow Tol Ratio= 0.001
Split Flow NTrial= 30
Split Flow Tol= 0.02
Split Flow Ratio= 0.02
Log Output Level= 0
Friction Slope Method= 1
Unsteady Friction Slope Method= 2
Unsteady Bridges Friction Slope Method= 1
Parabolic Critical Depth
Global Vel Dist=  1 , 1 , 1
Global Log Level= 0
CheckData=True
Encroach Param= -1, 0, 0, 0
BEGIN DESCRIPTION:
Multiple Run
END DESCRIPTION:

--- LONG BRANCH TRIB 1.f01 (steady flow) ---

Flow Title=Multiple
Number of Profiles=7
Profile Names=10-year,25-year,50-year,1pct_min,100-year,1pct_plu,500-year
River Rch & RM= LONG BRANCH TRIB,Reach-1,3543
     524     697     835     733     991    1340    1389
Boundary for River Rch & Prof#=LONG BRANCH TRIB,Reach-1,1
Up Type=0
Dn Type=3
Dn Slope=0.005
Boundary for River Rch & Prof#=LONG BRANCH TRIB,Reach-1,2
Up Type=0
Dn Type=3
Dn Slope=0.005
Boundary for River Rch & Prof#=LONG BRANCH TRIB,Reach-1,3
Up Type=0
Dn Type=3
Dn Slope=0.005
Boundary for River Rch & Prof#=LONG BRANCH TRIB,Reach-1,4
Up Type=0
Dn Type=3
Dn Slope=0.005
Boundary for River Rch & Prof#=LONG BRANCH TRIB,Reach-1,5
Up Type=0
Dn Type=3
Dn Slope=0.005
Boundary for River Rch & Prof#=LONG BRANCH TRIB,Reach-1,6
Up Type=0
Dn Type=3
Dn Slope=0.005
Boundary for River Rch & Prof#=LONG BRANCH TRIB,Reach-1,7
Up Type=0
Dn Type=3
Dn Slope=0.005

--- LONG BRANCH TRIB 1.g01 (geometry) ---

Geom Title=Existing Conditions

River Reach=LONG BRANCH TRIB,Reach-1
Reach XY= 30
      3490785.71     10424018.81      3490691.86     10424061.09
      3490585.65     10424233.15      3490572.76     10424313.86
      3490599.12     10424463.40      3490542.55     10424581.59
      3490557.64     10424664.11      3490644.04     10424745.48
      3490679.80     10424837.70      3490643.60     10424991.11
      3490680.06     10425094.84      3490786.83     10425191.63
      3490746.47     10425350.48      3490759.92     10425402.57
      3490838.92     10425381.30      3490997.77     10425524.96
      3491079.37     10425555.78      3491155.76     10425553.17
      3491180.06     10425498.92      3491226.50     10425482.43
      3491308.97     10425527.57      3491478.02     10425525.83
      3491704.58     10425456.82      3491744.95     10425481.56
      3491692.87     10425576.61      3491782.71     10425609.16
      3491881.67     10425749.79      3492073.07     10425926.87
      3492152.50     10426074.01      3492168.49     10426158.05

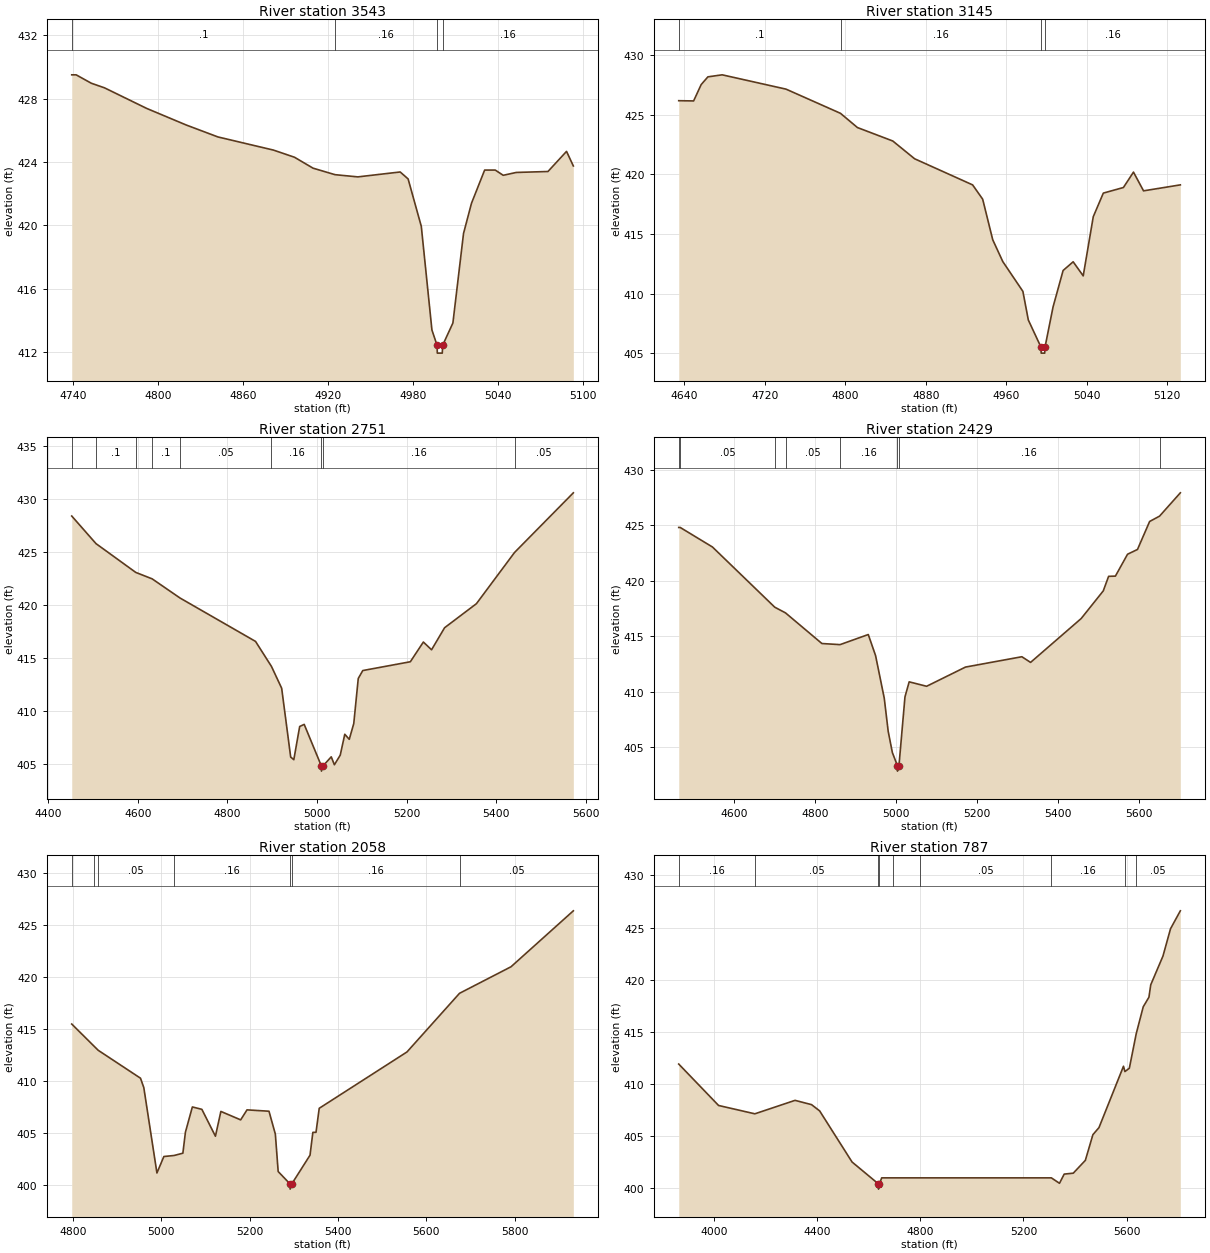
Type RM Length L Ch R = 1,3543,398,398,398
BEGIN DESCRIPTION:
LONG BRANCH TRIB 1 7 0
END DESCRIPTION:
XS GIS Cut Line= 2
      3490451.48     10423952.11      3490768.11     10424110.43
#Sta/Elev= 30
  4739.0  429.50  4742.1  429.50  4752.8  428.97  4762.1  428.68  4791.9  427.38
  4819.9  426.33  4842.2  425.58  4881.4  424.75  4896.2  424.30  4909.3  423.61
  4924.8  423.20  4940.9  423.06  4970.8  423.37  4976.4  422.93  4985.7  419.94
  4993.2  413.40  4996.8  412.44  4997.0  411.94  5000.5  411.94  5000.8  412.44
  5008.0  413.84  5015.5  419.49  5021.1  421.39  5030.4  423.49  5037.9  423.49
  5043.5  423.16  5052.7  423.34  5075.1  423.40  5088.2  424.67  5093.0  423.75
#Mann=4,-1,0
  4739.0     0.1       0  4924.8    0.16       0  4996.8    0.07       0
  5000.8    0.16       0
Bank Sta=4996.8,5000.8
Exp/Cntr=0.3,0.1

Type RM Length L Ch R = 1,3145,394,394,394
BEGIN DESCRIPTION:
Mapping XS d68e5917
END DESCRIPTION:
XS GIS Cut Line= 3
      3490285.33     10424257.46      3490475.90     10424428.48
      3490718.70     10424423.63
#Sta/Elev= 30
  4634.3  426.17  4649.1  426.15  4656.6  427.52  4663.3  428.17  4677.5  428.34
  4741.0  427.14  4795.2  425.11  4812.0  423.92  4847.2  422.79  4868.9  421.30
  4926.6  419.11  4936.6  417.91  4946.6  414.51  4956.6  412.68  4976.6  410.18
  4982.0  407.78  4994.6  405.50  4994.8  405.00  4998.3  405.00  4998.6  405.50
  5006.6  408.87  5016.6  411.93  5026.6  412.66  5036.6  411.48  5046.6  416.44
  5056.6  418.42  5076.6  418.89  5086.6  420.18  5096.6  418.61  5133.2  419.11
#Mann=4,-1,0
  4634.3     0.1       0  4795.2    0.16       0  4994.6    0.07       0
  4998.6    0.16       0
Bank Sta=4994.6,4998.6
Exp/Cntr=0.3,0.1

Type RM Length L Ch R = 1,2751,322,322,322
BEGIN DESCRIPTION:
LONG BRANCH TRIB 1 6 0
END DESCRIPTION:
XS GIS Cut Line= 4
      3490111.86     10424714.30      3490434.37     10424785.16
      3490808.14     10424743.62      3490969.38     10424362.51
#Sta/Elev= 30
  4452.3  428.38  4506.4  425.78  4595.3  423.06  4632.0  422.45  4693.9  420.65
  4862.7  416.55  4898.3  414.19  4921.1  412.13  4941.2  405.64  4948.2  405.39
  4961.3  408.52  4971.4  408.72  5009.6  404.81  5009.9  404.31  5013.6  404.81
  5031.8  405.66  5038.8  404.91  5051.9  405.82  5062.0  407.79  5072.0  407.31
  5082.1  408.80  5092.1  413.05  5102.2  413.80  5208.4  414.63  5237.5  416.49
  5255.8  415.76  5284.9  417.84  5356.0  420.11  5441.1  424.94  5572.4  430.57
#Mann=9,-1,0
  4452.3    0.05       0  4506.4     0.1       0  4595.3    0.05       0
  4632.0     0.1       0  4693.9    0.05       0  4898.3    0.16       0
  5009.6    0.07       0  5013.6    0.16       0  5441.1    0.05       0
Bank Sta=5009.6,5013.6
Exp/Cntr=0.3,0.1

Type RM Length L Ch R = 1,2429,371,371,371
BEGIN DESCRIPTION:
LONG BRANCH TRIB 1 5 0
END DESCRIPTION:
XS GIS Cut Line= 4
      3490138.81     10425066.10      3490551.63     10425090.52
      3490720.20     10425044.11      3490954.57     10424436.21
#Sta/Elev= 30
  4462.6  424.81  4466.3  424.81  4546.0  423.05  4700.0  417.63  4726.5  417.12
  4816.5  414.36  4861.3  414.26  4931.1  415.17  4949.2  413.27  4970.6  409.44
  4980.4  406.44  4990.7  404.54  5003.0  403.37  5003.3  402.87  5007.0  403.37
  5021.8  409.55  5032.2  410.91  5075.3  410.51  5171.5  412.24  5310.8  413.17
  5332.3  412.66  5457.4  416.61  5512.0  419.10  5525.2  420.41  5542.0  420.43
  5572.0  422.40  5596.6  422.83  5626.6  425.35  5651.1  425.83  5702.5  427.93
#Mann=8,-1,0
  4462.6    0.16       0  4466.3    0.05       0  4700.0    0.16       0
  4726.5    0.05       0  4861.3    0.16       0  5003.0    0.07       0
  5007.0    0.16       0  5651.1    0.05       0
Bank Sta=5003,5007
Exp/Cntr=0.3,0.1

Type RM Length L Ch R = 1,2058,1271,1271,1271
BEGIN DESCRIPTION:
LONG BRANCH TRIB 1 4 0
END DESCRIPTION:
XS GIS Cut Line= 3
      3490571.16     10425474.07      3490881.43     10425293.29
      3491364.47     10424685.83
#Sta/Elev= 30
  4797.5  415.46  4846.9  413.38  4857.4  412.94  4953.1  410.26  4960.6  409.36
  4990.3  401.16  5006.0  402.74  5029.2  402.84  5049.0  403.06  5054.8  405.08
  5070.5  407.50  5092.0  407.27  5122.7  404.69  5135.0  407.07  5179.8  406.26
  5194.2  407.22  5243.9  407.09  5258.3  404.89  5264.7  401.30  5291.5  400.11
  5291.8  399.61  5295.5  400.11  5336.8  402.87  5343.2  405.06  5350.3  405.06
  5357.6  407.37  5556.2  412.78  5675.1  418.41  5791.7  420.96  5932.7  426.33
#Mann=7,-1,0
  4797.5    0.05       0  4846.9    0.16       0  4857.4    0.05       0
  5029.2    0.16       0  5291.5   0.035       0  5295.5    0.16       0
  5675.1    0.05       0
Bank Sta=5291.5,5295.5
Exp/Cntr=0.3,0.1

Type RM Length L Ch R = 1,787,0,0,0
BEGIN DESCRIPTION:
LONG BRANCH TRIB 1 1 0
END DESCRIPTION:
XS GIS Cut Line= 5
      3490654.26     10425564.46      3491006.02     10425669.50
      3491101.30     10425776.99      3491988.09     10425476.51
      3492181.08     10425019.67
#Sta/Elev= 30
  3864.6  411.91  4018.9  407.94  4159.4  407.14  4315.1  408.43  4379.0  408.02
  4410.4  407.42  4536.0  402.52  4638.2  400.42  4638.4  399.92  4642.2  400.42
  4650.7  401.00  4693.9  401.00  4799.7  401.00  5308.0  401.00  5339.5  400.48
  5357.7  401.36  5392.9  401.45  5439.7  402.68  5468.9  405.14  5492.5  405.82
  5587.4  411.70  5593.0  411.19  5610.1  411.51  5636.9  414.84  5663.9  417.40
  5686.0  418.32  5693.0  419.51  5740.3  422.26  5769.6  424.88  5807.6  426.60
#Mann=9,-1,0
  3864.6    0.16       0  4159.4    0.05       0  4638.2   0.033       0
  4642.2    0.05       0  4693.9    0.16       0  4799.7    0.05       0
  5308.0    0.16       0  5593.0     0.1       0  5636.9    0.05       0
Bank Sta=4638.2,4642.2
Exp/Cntr=0.3,0.1

Chan Stop Cuts=-1