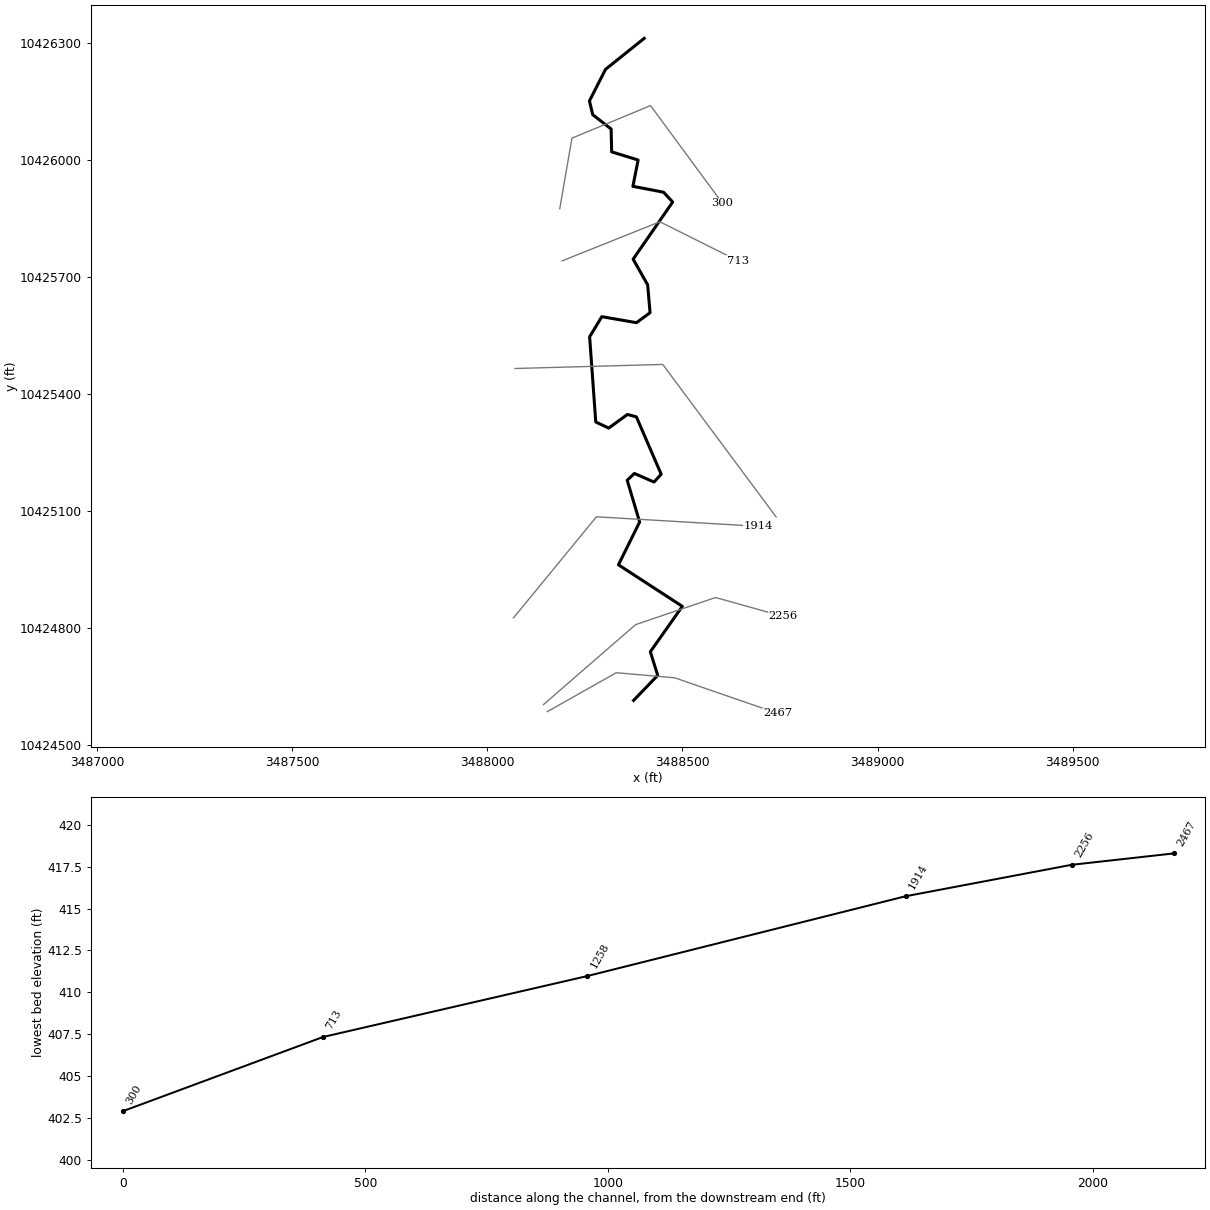
--- LONG BRANCH TRIB 2.prj (project) ---

Proj Title=LONG BRANCH TRIB 2 Base Level Engineering
Current Plan=p01
Default Exp/Contr=0.3,0.1
English Units
Geom File=g01
Flow File=f01
Plan File=p01
Y Axis Title=Elevation
X Axis Title(PF)=Main Channel Distance
X Axis Title(XS)=Station
BEGIN DESCRIPTION:
LONG BRANCH TRIB 2
END DESCRIPTION:
DSS Export Rating Curves= 0
DSS Export Rating Curve Sorted= 0
DSS Export Volume Flow Curves= 0
DXF OffsetX= 0
DXF OffsetY= 0
DXF ScaleX= 1
DXF ScaleY= 10

--- LONG BRANCH TRIB 2.p01 (plan) ---

Plan Title=Multiple Run
Short Identifier=Multiple
Geom File=g01
Flow File=f01
Subcritical Flow
K Sum by GR= 0
Std Step Tol= 0.01
Critical Tol= 0.01
Num of Std Step Trials= 20
Max Error Tol= 0.3
Flow Tol Ratio= 0.001
Split Flow NTrial= 30
Split Flow Tol= 0.02
Split Flow Ratio= 0.02
Log Output Level= 0
Friction Slope Method= 1
Unsteady Friction Slope Method= 2
Unsteady Bridges Friction Slope Method= 1
Parabolic Critical Depth
Global Vel Dist=  1 , 1 , 1
Global Log Level= 0
CheckData=True
Encroach Param= -1, 0, 0, 0
BEGIN DESCRIPTION:
Multiple Run
END DESCRIPTION:

--- LONG BRANCH TRIB 2.f01 (steady flow) ---

Flow Title=Multiple
Program Version=4.10
Number of Profiles= 7
Profile Names=10-year,25-year,50-year,1pct_min,100-year,1pct_plu,500-year
River Rch & RM=LONG BRANCH TRIB,Reach-1         ,2467
     352     455     536     463     626     846     848
Boundary for River Rch & Prof#=LONG BRANCH TRIB,Reach-1         , 1
Up Type= 0
Dn Type= 3
Dn Slope=0.005
Boundary for River Rch & Prof#=LONG BRANCH TRIB,Reach-1         , 2
Up Type= 0
Dn Type= 3
Dn Slope=0.005
Boundary for River Rch & Prof#=LONG BRANCH TRIB,Reach-1         , 3
Up Type= 0
Dn Type= 3
Dn Slope=0.005
Boundary for River Rch & Prof#=LONG BRANCH TRIB,Reach-1         , 4
Up Type= 0
Dn Type= 3
Dn Slope=0.005
Boundary for River Rch & Prof#=LONG BRANCH TRIB,Reach-1         , 5
Up Type= 0
Dn Type= 3
Dn Slope=0.005
Boundary for River Rch & Prof#=LONG BRANCH TRIB,Reach-1         , 6
Up Type= 0
Dn Type= 3
Dn Slope=0.005
Boundary for River Rch & Prof#=LONG BRANCH TRIB,Reach-1         , 7
Up Type= 0
Dn Type= 3
Dn Slope=0.005
DSS Import GetInterval= 0
DSS Import GetPeak= 0
DSS Import FillOption= 0

--- LONG BRANCH TRIB 2.g01 (geometry) ---

Geom Title=Existing Conditions
Program Version=4.10

River Reach=LONG BRANCH TRIB,Reach-1
Reach XY= 30
      3488374.84     10424615.05      3488436.65      10424679.4
      3488417.74     10424739.88      3488499.78     10424856.17
      3488336.01     10424962.62      3488390.32     10425072.26
      3488358.46     10425179.29      3488376.91     10425196.71
      3488427.08     10425174.68      3488445.56     10425194.68
      3488382.02     10425341.59      3488359.14     10425347.91
      3488311.16     10425312.96      3488277.92     10425328.55
       3488262.2     10425546.78      3488293.39     10425598.43
      3488382.27     10425583.05      3488417.03     10425608.68
      3488410.87     10425680.05      3488373.65     10425745.76
      3488475.01      10425892.2      3488451.57     10425917.35
      3488373.07     10425932.46      3488386.48     10425999.87
      3488318.61     10426020.81      3488317.26      10426079.3
      3488270.12       10426116.      3488261.71     10426151.32
      3488302.97      10426232.2      3488402.11     10426311.64

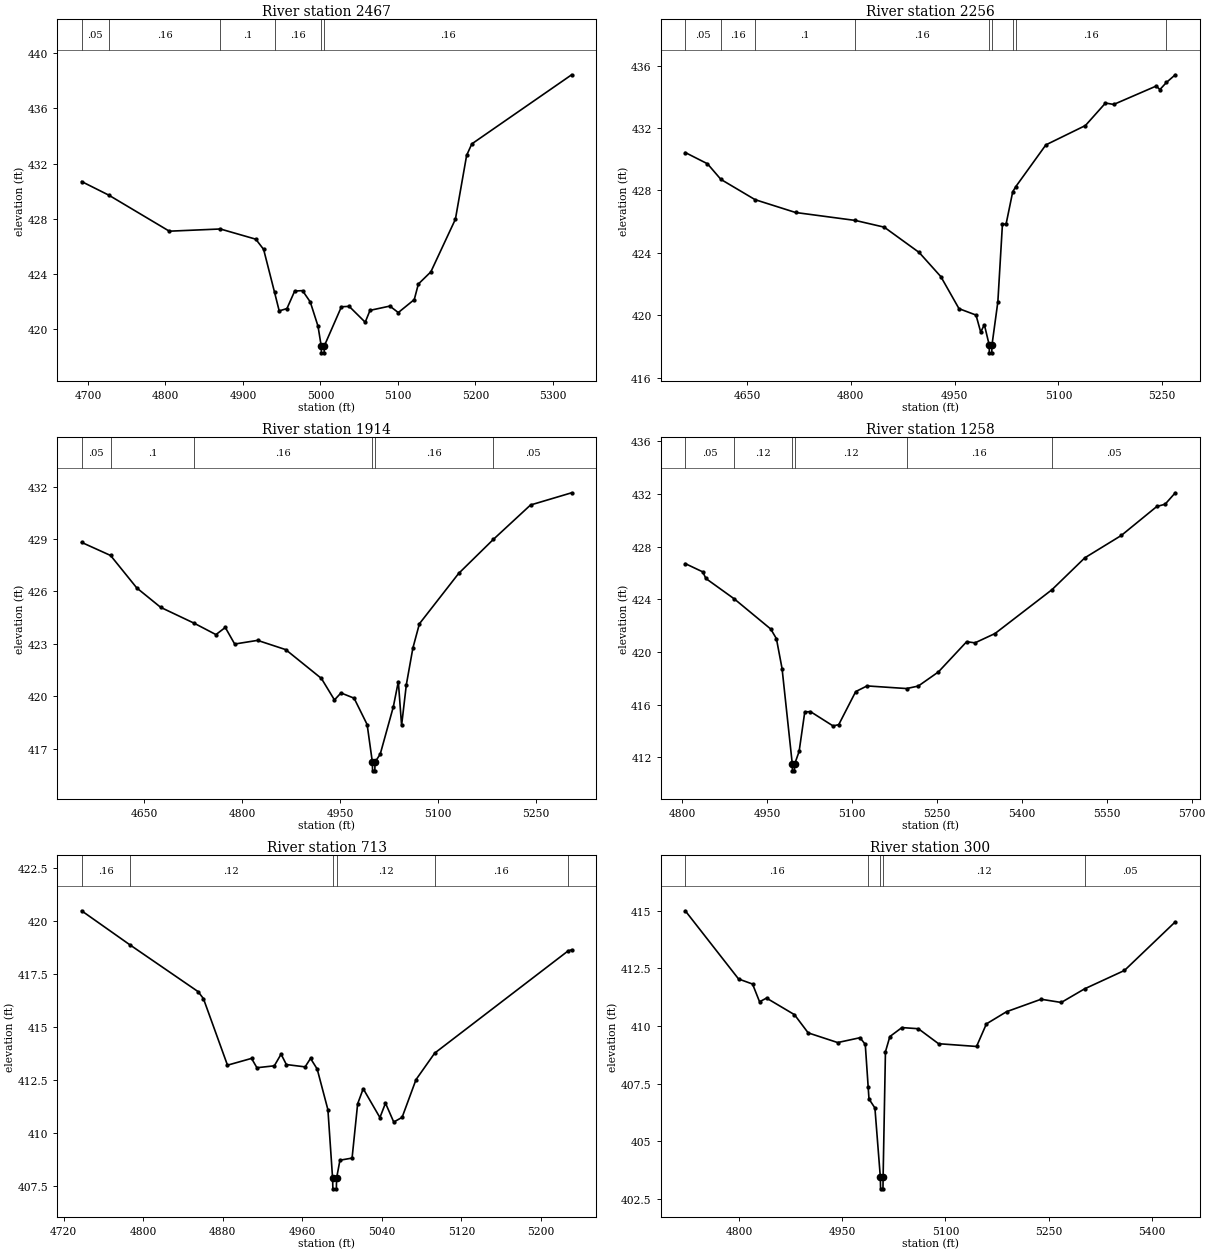
Type RM Length L Ch R = 1 ,2467    ,211,211,211
BEGIN DESCRIPTION:
LONG BRANCH TRIB 2 6 0
END DESCRIPTION:
XS GIS Cut Line= 4
      3488153.57     10424586.27      3488330.44      10424686.1
      3488480.18     10424673.08      3488743.86     10424581.93
#Sta/Elev= 30
  4691.8   430.7    4727  429.71    4805   427.1  4870.8  427.26  4916.6  426.52
  4926.7  425.78  4940.8  422.67  4946.8  421.32  4956.8  421.49  4966.8  422.76
  4976.9  422.79  4986.9  421.97  4996.9  420.21    5001  418.78  5001.3  418.28
  5004.8  418.28    5005  418.78  5027.1  421.62  5037.1  421.65  5057.8   420.5
    5064  421.36  5089.6  421.67  5100.5   421.2  5121.1  422.14  5126.4  423.27
  5142.5  424.15  5174.2  427.97  5188.7   432.6  5195.4  433.43  5324.2  438.44
#Mann= 6 ,-1 , 0
  4691.8     .05       0    4727     .16       0  4870.8      .1       0
  4940.8     .16       0    5001     .07       0    5005     .16       0
Bank Sta=5001,5005
XS Rating Curve= 0 ,0
Exp/Cntr=0.3,0.1

Type RM Length L Ch R = 1 ,2256    ,342,342,342
BEGIN DESCRIPTION:
LONG BRANCH TRIB 2 6 0
END DESCRIPTION:
XS GIS Cut Line= 4
      3488144.02     10424604.54       3488380.1     10424809.38
      3488584.97     10424878.82      3488757.85     10424830.42
#Sta/Elev= 30
  4560.6  430.43  4592.7  429.71  4612.1  428.71  4661.6  427.41    4720  426.59
  4806.5  426.08  4848.2  425.65  4898.7  424.03  4930.1  422.48  4956.3  420.43
  4980.9  420.02  4987.7  418.93    4993   419.4    5000   418.1  5000.2   417.6
  5003.7   417.6    5004   418.1  5012.5  420.87  5019.1  425.83  5024.4  425.85
    5034  427.92  5038.5  428.25  5081.9  430.92  5139.1  432.16  5168.1   433.6
    5180  433.51  5241.5  434.69  5246.7  434.46  5256.2  434.92    5269  435.41
#Mann= 9 ,-1 , 0
  4560.6     .05       0  4612.1     .16       0  4661.6      .1       0
  4806.5     .16       0    5000     .07       0    5004     .16       0
    5034     .05       0  5038.5     .16       0  5256.2     .05       0
Bank Sta=5000,5004
XS Rating Curve= 0 ,0
Exp/Cntr=0.3,0.1

Type RM Length L Ch R = 1 ,1914    ,656,656,656
BEGIN DESCRIPTION:
LONG BRANCH TRIB 2 5 0
END DESCRIPTION:
XS GIS Cut Line= 3
      3488067.16     10424826.69      3488279.69     10425085.64
      3488694.98     10425061.21
#Sta/Elev= 30
    4554  428.81  4598.4  428.06  4638.6   426.2  4675.2  425.09  4726.6  424.18
  4759.9  423.53  4774.2  423.94  4788.6  422.99  4823.7   423.2  4866.8  422.67
  4921.5  421.02  4941.5  419.79  4951.5  420.19  4971.6  419.89  4991.6  418.38
  4999.6  416.23  4999.9  415.73  5003.4  415.73  5003.6  416.23  5011.6  416.68
  5031.7  419.39  5039.4  420.84  5044.4  418.33  5051.7  420.67  5061.7  422.76
  5071.7  424.15  5131.8  427.03    5185  428.98    5242  430.95    5305  431.65
#Mann= 6 ,-1 , 0
    4554     .05       0  4598.4      .1       0  4726.6     .16       0
  4999.6     .07       0  5003.6     .16       0    5185     .05       0
Bank Sta=4999.6,5003.6
XS Rating Curve= 0 ,0
Exp/Cntr=0.3,0.1

Type RM Length L Ch R = 1 ,1258    ,545,545,545
BEGIN DESCRIPTION:
LONG BRANCH TRIB 2 4 0
END DESCRIPTION:
XS GIS Cut Line= 3
      3488071.12     10425465.63      3488449.55     10425476.04
       3488740.1     10425085.18
#Sta/Elev= 30
  4805.5  426.72  4836.5  426.09  4841.9  425.59  4892.1  424.04  4956.5  421.75
  4966.5  421.02  4976.5  418.75  4994.6  411.48  4994.8  410.98  4998.3  410.98
  4998.6  411.48  5006.6  412.45  5016.6  415.45  5026.6  415.48  5066.6  414.39
  5076.6  414.49  5106.6     417  5126.6  417.43  5196.5  417.23  5217.1  417.42
  5252.6  418.49  5302.6  420.79  5317.2   420.7  5352.7  421.41  5453.3  424.74
  5511.3  427.16  5575.8  428.86  5638.5  431.06  5653.1  431.23  5671.1   432.1
#Mann= 6 ,-1 , 0
  4805.5     .05       0  4892.1     .12       0  4994.6     .07       0
  4998.6     .12       0  5196.5     .16       0  5453.3     .05       0
Bank Sta=4994.6,4998.6
XS Rating Curve= 0 ,0
Exp/Cntr=0.3,0.1

Type RM Length L Ch R = 1 ,713     ,413,413,413
BEGIN DESCRIPTION:
LONG BRANCH TRIB 2 2 0
END DESCRIPTION:
XS GIS Cut Line= 3
      3488192.14     10425741.66      3488442.11     10425841.64
      3488642.08     10425741.65
#Sta/Elev= 30
    4738  420.46  4786.4  418.86  4855.1  416.65  4860.5  416.32  4884.7  413.18
  4908.9   413.5  4914.3  413.06  4931.8  413.15  4938.6   413.7  4943.9  413.21
  4962.8   413.1  4968.2   413.5  4974.9     413  4985.7  411.08  4990.4  407.85
  4990.7  407.35  4994.2  407.35  4994.4  407.85  4997.8   408.7    5010   408.8
  5015.6  411.36  5021.2  412.07    5038  410.71  5043.6  411.39  5051.9   410.5
  5060.3  410.72  5074.3   412.5  5093.1  413.75  5227.3  418.57  5230.8  418.62
#Mann= 6 ,-1 , 0
    4738     .16       0  4786.4     .12       0  4990.4     .07       0
  4994.4     .12       0  5093.1     .16       0  5227.3     .05       0
Bank Sta=4990.4,4994.4
XS Rating Curve= 0 ,0
Exp/Cntr=0.3,0.1

Type RM Length L Ch R = 1 ,300     ,0,0,0
BEGIN DESCRIPTION:
LONG BRANCH TRIB 2 1 0
END DESCRIPTION:
XS GIS Cut Line= 4
      3488185.66     10425875.35      3488216.91     10426055.91
       3488418.3     10426139.24      3488602.32     10425889.25
#Sta/Elev= 30
  4722.1     415  4799.5  412.04  4819.8  411.82    4830  411.05  4840.1  411.21
  4880.7  410.49  4900.6   409.7  4943.4  409.28  4975.9  409.49  4983.5   409.2
  4987.7  407.36  4988.9  406.83  4997.5  406.44  5005.4  403.43  5005.7  402.93
  5009.2  402.93  5009.4  403.43  5012.8  408.88  5019.2  409.54  5036.7  409.93
  5060.6  409.88  5089.9  409.23  5145.1  409.11  5159.4  410.09  5188.7  410.62
  5238.8  411.16  5268.1  411.02  5301.9  411.61  5359.9  412.41  5433.7  414.52
#Mann= 5 ,-1 , 0
  4722.1     .16       0  4987.7     .12       0  5005.4     .07       0
  5009.4     .12       0  5301.9     .05       0
Bank Sta=5005.4,5009.4
XS Rating Curve= 0 ,0
Exp/Cntr=0.3,0.1

Chan Stop Cuts=-1
Use User Specified Reach Order=0
Composite Channel Slope=5