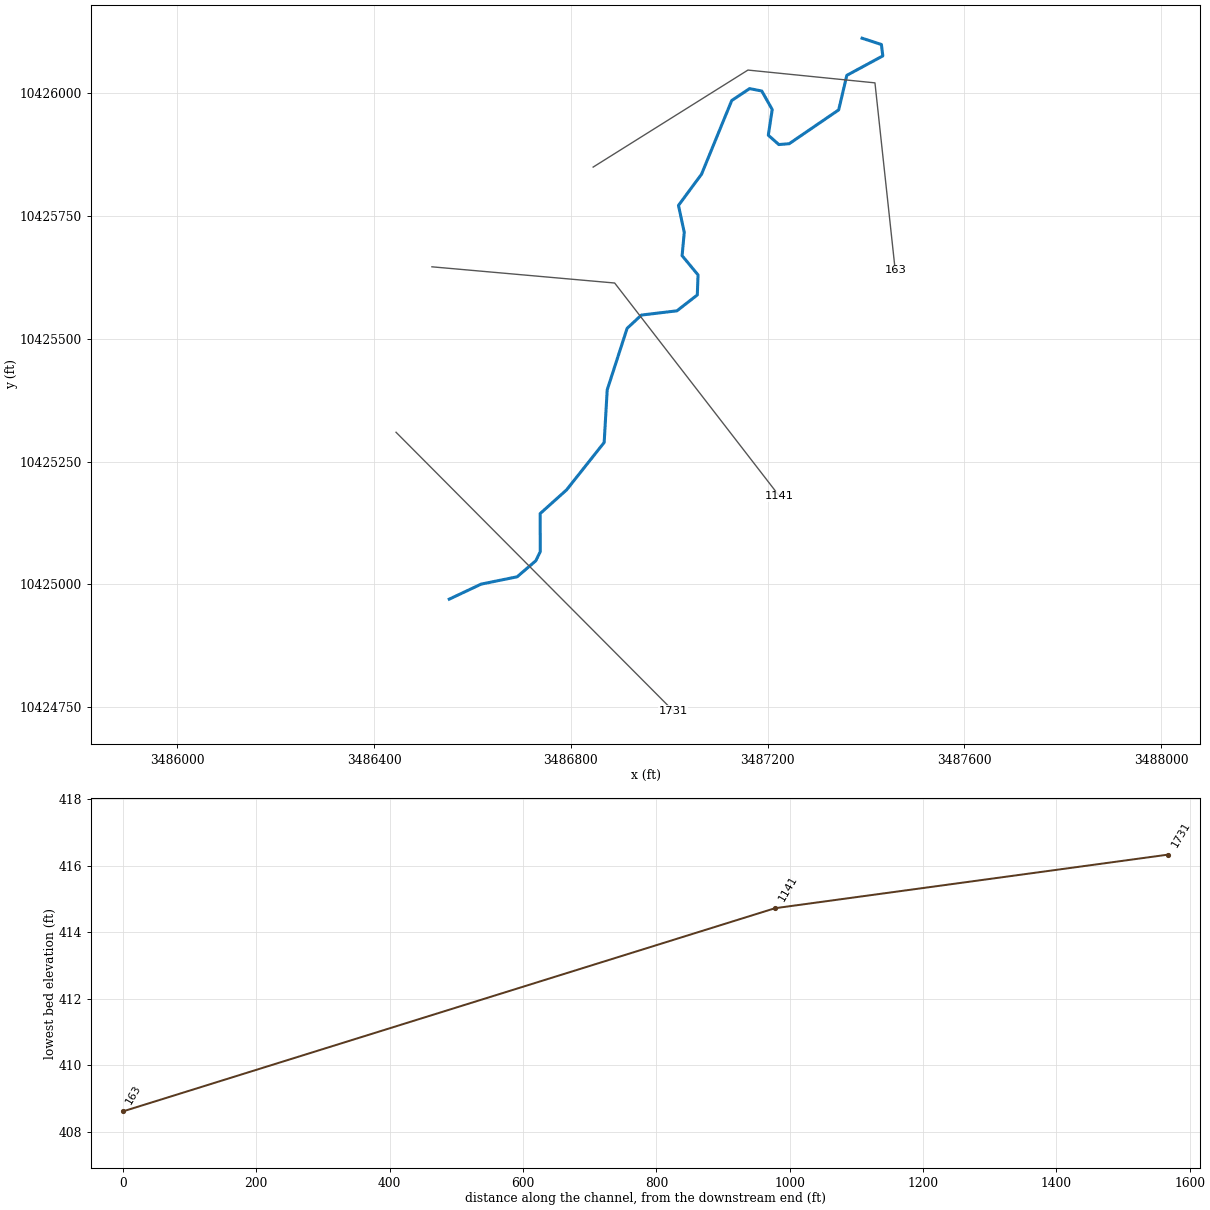
--- LONG BRANCH TRIB 3.prj (project) ---

Proj Title=LONG BRANCH TRIB 3 Base Level Engineering
Current Plan=p01
Default Exp/Contr=0.3,0.1
English Units
Geom File=g01
Flow File=f01
Plan File=p01
BEGIN DESCRIPTION:
LONG BRANCH TRIB 3
END DESCRIPTION:

--- LONG BRANCH TRIB 3.p01 (plan) ---

Plan Title=Multiple Run
Short Identifier=Multiple
Geom File=g01
Flow File=f01
Subcritical Flow
K Sum by GR= 0
Std Step Tol= 0.01
Critical Tol= 0.01
Num of Std Step Trials= 20
Max Error Tol= 0.3
Flow Tol Ratio= 0.001
Split Flow NTrial= 30
Split Flow Tol= 0.02
Split Flow Ratio= 0.02
Log Output Level= 0
Friction Slope Method= 1
Unsteady Friction Slope Method= 2
Unsteady Bridges Friction Slope Method= 1
Parabolic Critical Depth
Global Vel Dist=  1 , 1 , 1
Global Log Level= 0
CheckData=True
Encroach Param= -1, 0, 0, 0
BEGIN DESCRIPTION:
Multiple Run
END DESCRIPTION:

--- LONG BRANCH TRIB 3.f01 (steady flow) ---

Flow Title=Multiple
Number of Profiles=7
Profile Names=10-year,25-year,50-year,1pct_min,100-year,1pct_plu,500-year
River Rch & RM= LONG BRANCH TRIB,Reach-1,1731
     339     438     514     443     599     810     808
Boundary for River Rch & Prof#=LONG BRANCH TRIB,Reach-1,1
Up Type=0
Dn Type=3
Dn Slope=0.005
Boundary for River Rch & Prof#=LONG BRANCH TRIB,Reach-1,2
Up Type=0
Dn Type=3
Dn Slope=0.005
Boundary for River Rch & Prof#=LONG BRANCH TRIB,Reach-1,3
Up Type=0
Dn Type=3
Dn Slope=0.005
Boundary for River Rch & Prof#=LONG BRANCH TRIB,Reach-1,4
Up Type=0
Dn Type=3
Dn Slope=0.005
Boundary for River Rch & Prof#=LONG BRANCH TRIB,Reach-1,5
Up Type=0
Dn Type=3
Dn Slope=0.005
Boundary for River Rch & Prof#=LONG BRANCH TRIB,Reach-1,6
Up Type=0
Dn Type=3
Dn Slope=0.005
Boundary for River Rch & Prof#=LONG BRANCH TRIB,Reach-1,7
Up Type=0
Dn Type=3
Dn Slope=0.005

--- LONG BRANCH TRIB 3.g01 (geometry) ---

Geom Title=Existing Conditions

River Reach=LONG BRANCH TRIB,Reach-1
Reach XY= 30
      3486552.85     10424969.83      3486617.62     10425000.43
      3486690.85     10425015.35      3486728.74     10425047.94
      3486737.90     10425066.55      3486737.60     10425144.02
      3486791.19     10425192.10      3486867.75     10425288.73
      3486873.96     10425395.87      3486914.40     10425521.07
      3486943.46     10425548.10      3487015.72     10425556.76
      3487057.12     10425589.02      3487058.63     10425629.80
      3487026.21     10425669.02      3487030.60     10425716.35
      3487018.84     10425771.33      3487065.70     10425834.80
      3487127.12     10425984.83      3487163.45     10426009.07
      3487188.21     10426004.11      3487209.42     10425966.49
      3487201.46     10425914.17      3487222.88     10425895.18
      3487243.98     10425896.91      3487344.55     10425965.73
      3487361.09     10426036.05      3487434.25     10426075.60
      3487431.43     10426098.85      3487392.11     10426111.64

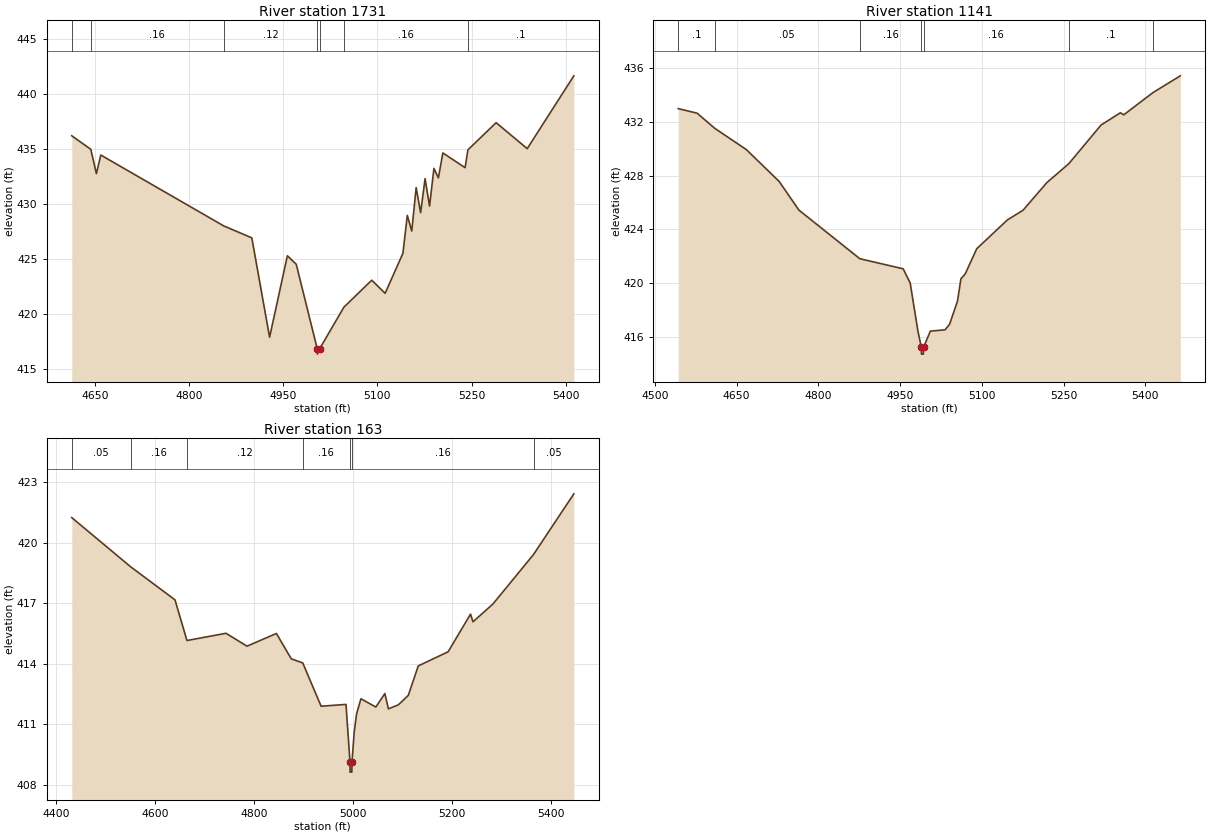
Type RM Length L Ch R = 1,1731,590,590,590
BEGIN DESCRIPTION:
LONG BRANCH TRIB 3 3 0
END DESCRIPTION:
XS GIS Cut Line= 2
      3486444.65     10425309.54      3487008.03     10424742.69
#Sta/Elev= 30
  4613.5  436.18  4643.8  434.95  4652.7  432.74  4659.7  434.43  4855.6  427.98
  4900.1  426.90  4928.4  417.87  4956.7  425.27  4970.8  424.50  5004.2  416.83
  5004.4  416.33  5008.2  416.83  5046.7  420.60  5091.0  423.05  5112.3  421.86
  5140.6  425.49  5147.6  428.94  5154.7  427.52  5161.7  431.47  5168.8  429.19
  5175.9  432.28  5183.0  429.79  5190.0  433.21  5197.1  432.35  5204.2  434.62
  5239.6  433.28  5244.1  434.90  5289.0  437.37  5338.5  435.01  5412.7  441.63
#Mann=7,-1,0
  4613.5     0.1       0  4643.8    0.16       0  4855.6    0.12       0
  5004.2    0.07       0  5008.2    0.12       0  5046.7    0.16       0
  5244.1     0.1       0
Bank Sta=5004.2,5008.2
Exp/Cntr=0.3,0.1

Type RM Length L Ch R = 1,1141,978,978,978
BEGIN DESCRIPTION:
LONG BRANCH TRIB 3 2 0
END DESCRIPTION:
XS GIS Cut Line= 3
      3486517.59     10425646.32      3486889.12     10425613.33
      3487224.18     10425179.32
#Sta/Elev= 30
  4542.8  432.99  4577.5  432.65  4609.6  431.53  4667.8  429.94  4728.0  427.57
  4764.2  425.44  4876.0  421.82  4955.6  421.07  4968.5  420.00  4982.7  416.42
  4988.9  415.22  4989.1  414.72  4992.6  414.72  4992.9  415.22  5005.4  416.43
  5032.5  416.53  5040.7  416.94  5055.2  418.66  5061.5  420.32  5069.5  420.70
  5090.5  422.56  5146.6  424.70  5175.6  425.43  5219.1  427.48  5259.5  428.89
  5318.7  431.77  5354.1  432.68  5360.4  432.53  5414.2  434.19  5464.1  435.43
#Mann=7,-1,0
  4542.8     0.1       0  4609.6    0.05       0  4876.0    0.16       0
  4988.9    0.07       0  4992.9    0.16       0  5259.5     0.1       0
  5414.2    0.05       0
Bank Sta=4988.9,4992.9
Exp/Cntr=0.3,0.1

Type RM Length L Ch R = 1,163,0,0,0
BEGIN DESCRIPTION:
LONG BRANCH TRIB 3 1 0
END DESCRIPTION:
XS GIS Cut Line= 4
      3486845.37     10425849.30      3487160.05     10426046.79
      3487418.30     10426020.75      3487459.53     10425638.85
#Sta/Elev= 30
  4431.6  421.25  4550.6  418.81  4640.3  417.17  4664.5  415.15  4743.5  415.51
  4785.9  414.87  4845.4  415.50  4875.5  414.24  4898.6  414.04  4935.8  411.89
  4986.1  411.98  4994.2  409.12  4994.4  408.62  4997.9  408.62  4998.2  409.12
  5002.6  410.59  5007.6  411.52  5016.3  412.26  5046.4  411.85  5064.7  412.52
  5071.8  411.76  5092.0  411.96  5112.1  412.43  5132.2  413.89  5192.5  414.59
  5237.9  416.46  5242.9  416.08  5283.1  416.96  5365.3  419.42  5446.8  422.43
#Mann=7,-1,0
  4431.6    0.05       0  4550.6    0.16       0  4664.5    0.12       0
  4898.6    0.16       0  4994.2    0.07       0  4998.2    0.16       0
  5365.3    0.05       0
Bank Sta=4994.2,4998.2
Exp/Cntr=0.3,0.1

Chan Stop Cuts=-1