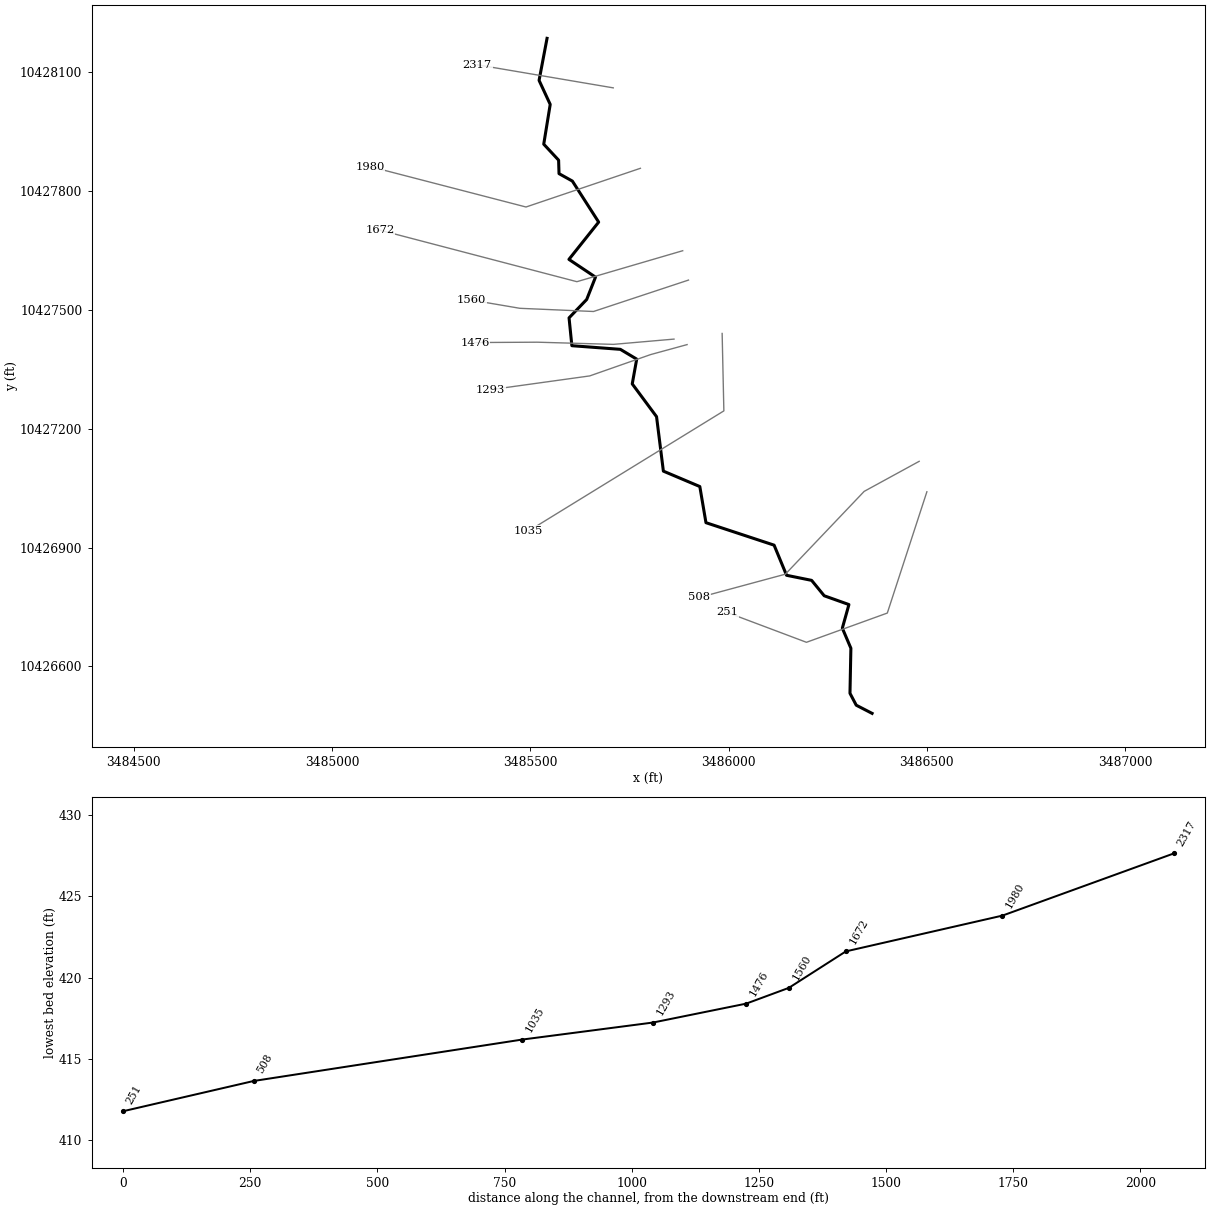
--- LONG BRANCH TRIB 4.prj (project) ---

Proj Title=LONG BRANCH TRIB 4 Base Level Engineering
Current Plan=p01
Default Exp/Contr=0.3,0.1
English Units
Geom File=g01
Flow File=f01
Plan File=p01
BEGIN DESCRIPTION:
LONG BRANCH TRIB 4
END DESCRIPTION:

--- LONG BRANCH TRIB 4.p01 (plan) ---

Plan Title=Multiple Run
Short Identifier=Multiple
Geom File=g01
Flow File=f01
Subcritical Flow
K Sum by GR= 0
Std Step Tol= 0.01
Critical Tol= 0.01
Num of Std Step Trials= 20
Max Error Tol= 0.3
Flow Tol Ratio= 0.001
Split Flow NTrial= 30
Split Flow Tol= 0.02
Split Flow Ratio= 0.02
Log Output Level= 0
Friction Slope Method= 1
Unsteady Friction Slope Method= 2
Unsteady Bridges Friction Slope Method= 1
Parabolic Critical Depth
Global Vel Dist=  1 , 1 , 1
Global Log Level= 0
CheckData=True
Encroach Param= -1, 0, 0, 0
BEGIN DESCRIPTION:
Multiple Run
END DESCRIPTION:

--- LONG BRANCH TRIB 4.f01 (steady flow) ---

Flow Title=Multiple
Number of Profiles=7
Profile Names=10-year,25-year,50-year,1pct_min,100-year,1pct_plu,500-year
River Rch & RM= LONG BRANCH TRIB,Reach-1,2317
     294     376     439     376     509     688     680
Boundary for River Rch & Prof#=LONG BRANCH TRIB,Reach-1,1
Up Type=0
Dn Type=3
Dn Slope=0.005
Boundary for River Rch & Prof#=LONG BRANCH TRIB,Reach-1,2
Up Type=0
Dn Type=3
Dn Slope=0.005
Boundary for River Rch & Prof#=LONG BRANCH TRIB,Reach-1,3
Up Type=0
Dn Type=3
Dn Slope=0.005
Boundary for River Rch & Prof#=LONG BRANCH TRIB,Reach-1,4
Up Type=0
Dn Type=3
Dn Slope=0.005
Boundary for River Rch & Prof#=LONG BRANCH TRIB,Reach-1,5
Up Type=0
Dn Type=3
Dn Slope=0.005
Boundary for River Rch & Prof#=LONG BRANCH TRIB,Reach-1,6
Up Type=0
Dn Type=3
Dn Slope=0.005
Boundary for River Rch & Prof#=LONG BRANCH TRIB,Reach-1,7
Up Type=0
Dn Type=3
Dn Slope=0.005

--- LONG BRANCH TRIB 4.g01 (geometry) ---

Geom Title=Existing Conditions

River Reach=LONG BRANCH TRIB,Reach-1
Reach XY= 30
      3485542.13     10428184.51      3485522.04     10428078.42
      3485550.12     10428017.84      3485533.80     10427917.49
      3485571.30     10427877.21      3485572.34     10427843.19
      3485606.02     10427824.44      3485672.34     10427720.96
      3485597.34     10427626.87      3485664.36     10427582.07
      3485642.16     10427525.79      3485597.65     10427479.37
      3485604.76     10427409.14      3485727.02     10427399.98
      3485768.30     10427375.27      3485757.07     10427312.79
      3485818.37     10427230.11      3485835.59     10427092.72
      3485927.52     10427053.84      3485943.01     10426962.69
      3486114.91     10426905.98      3486146.37     10426829.96
      3486209.58     10426817.18      3486241.31     10426778.33
      3486303.66     10426756.13      3486287.03     10426696.59
      3486308.60     10426645.94      3486306.30     10426532.32
      3486322.14     10426502.25      3486362.11     10426481.64

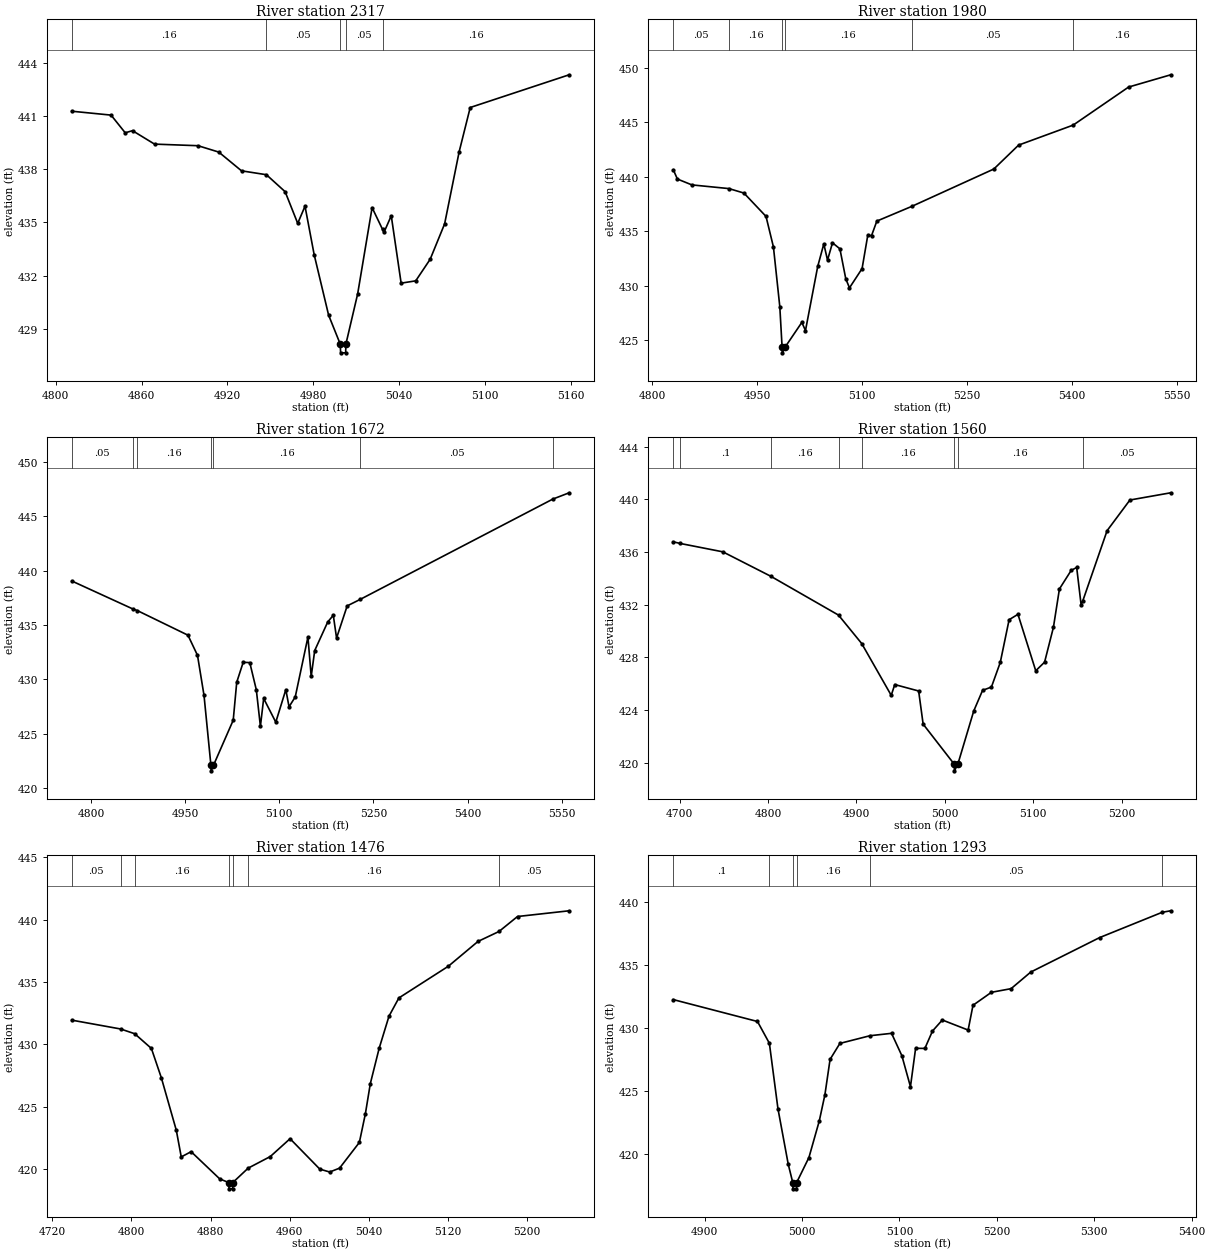
Type RM Length L Ch R = 1,2317,337,337,337
BEGIN DESCRIPTION:
LONG BRANCH TRIB 4 7 0
END DESCRIPTION:
XS GIS Cut Line= 2
      3485709.17     10428059.57      3485366.27     10428117.76
#Sta/Elev= 30
  4811.1  441.29  4838.6  441.07  4848.5  440.07  4853.6  440.19  4869.0  439.43
  4899.4  439.34  4913.9  438.98  4929.8  437.92  4947.2  437.70  4960.3  436.74
  4969.1  434.95  4974.2  435.92  4980.6  433.18  4990.7  429.76  4998.8  428.13
  4999.1  427.63  5002.6  427.63  5002.8  428.13  5011.0  430.96  5021.1  435.84
  5028.4  434.61  5029.4  434.44  5034.5  435.38  5041.4  431.57  5051.6  431.70
  5061.7  432.92  5071.8  434.92  5082.0  439.01  5089.7  441.50  5158.9  443.35
#Mann=5,-1,0
  4811.1    0.16       0  4947.2    0.05       0  4998.8    0.03       0
  5002.8    0.05       0  5028.4    0.16       0
Bank Sta=4998.8,5002.8
Exp/Cntr=0.3,0.1

Type RM Length L Ch R = 1,1980,308,308,308
BEGIN DESCRIPTION:
LONG BRANCH TRIB 4 6 0
END DESCRIPTION:
XS GIS Cut Line= 3
      3485777.64     10427856.67      3485489.05     10427759.03
      3485095.70     10427860.97
#Sta/Elev= 30
  4830.3  440.65  4836.1  439.80  4856.8  439.26  4909.8  438.92  4931.2  438.51
  4962.8  436.36  4973.4  433.55  4982.5  428.06  4985.8  424.31  4986.1  423.81
  4989.8  424.31  5014.0  426.61  5019.2  425.86  5036.7  431.76  5045.4  433.83
  5050.7  432.34  5057.8  433.93  5068.4  433.38  5076.8  430.62  5082.1  429.79
  5100.1  431.56  5108.3  434.65  5113.6  434.59  5121.2  435.93  5171.0  437.28
  5288.4  440.72  5323.8  442.92  5401.8  444.76  5481.0  448.26  5541.3  449.39
#Mann=6,-1,0
  4830.3    0.05       0  4909.8    0.16       0  4985.8    0.07       0
  4989.8    0.16       0  5171.0    0.05       0  5401.8    0.16       0
Bank Sta=4985.8,4989.8
Exp/Cntr=0.3,0.1

Type RM Length L Ch R = 1,1672,112,112,112
BEGIN DESCRIPTION:
LONG BRANCH TRIB 4 3 3
END DESCRIPTION:
XS GIS Cut Line= 3
      3485884.36     10427648.74      3485617.43     10427570.62
      3485120.02     10427700.83
#Sta/Elev= 30
  4769.5  439.05  4866.8  436.48  4874.0  436.33  4954.6  434.07  4969.8  432.22
  4980.2  428.54  4991.2  422.11  4991.5  421.61  4995.2  422.11  5026.7  426.26
  5032.3  429.75  5042.6  431.58  5053.1  431.55  5063.5  429.05  5070.0  425.70
  5075.2  428.26  5094.5  426.08  5110.5  429.07  5115.6  427.49  5125.5  428.40
  5145.7  433.90  5150.9  430.28  5156.5  432.66  5177.2  435.28  5186.1  435.90
  5191.3  433.81  5208.2  436.76  5228.7  437.35  5535.7  446.57  5561.8  447.15
#Mann=7,-1,0
  4769.5    0.05       0  4866.8     0.1       0  4874.0    0.16       0
  4991.2    0.07       0  4995.2    0.16       0  5228.7    0.05       0
  5535.7    0.16       0
Bank Sta=4991.2,4995.2
Exp/Cntr=0.3,0.1

Type RM Length L Ch R = 1,1560,84,84,84
BEGIN DESCRIPTION:
LONG BRANCH TRIB 4 3 2
END DESCRIPTION:
XS GIS Cut Line= 4
      3485898.94     10427574.68      3485659.34     10427495.43
      3485473.56     10427503.49      3485351.14     10427524.33
#Sta/Elev= 30
  4692.9  436.78  4700.5  436.66  4748.9  436.02  4803.2  434.16  4879.7  431.21
  4905.9  429.05  4939.3  425.11  4943.3  425.93  4970.3  425.44  4975.4  422.92
  5010.6  419.87  5010.8  419.37  5014.6  419.87  5032.6  423.92  5042.6  425.49
  5052.6  425.74  5062.6  427.61  5072.6  430.86  5082.6  431.27  5102.7  426.98
  5112.7  427.63  5122.7  430.28  5129.5  433.20  5142.8  434.61  5149.0  434.83
  5154.0  432.00  5155.8  432.27  5183.4  437.63  5209.2  439.96  5255.4  440.51
#Mann=8,-1,0
  4692.9    0.05       0  4700.5     0.1       0  4803.2    0.16       0
  4879.7    0.05       0  4905.9    0.16       0  5010.6    0.07       0
  5014.6    0.16       0  5155.8    0.05       0
Bank Sta=5010.6,5014.6
Exp/Cntr=0.3,0.1

Type RM Length L Ch R = 1,1476,183,183,183
BEGIN DESCRIPTION:
LONG BRANCH TRIB 4 4 0
END DESCRIPTION:
XS GIS Cut Line= 4
      3485862.45     10427425.80      3485709.47     10427412.50
      3485517.83     10427417.99      3485359.81     10427417.12
#Sta/Elev= 30
  4739.6  431.93  4789.1  431.22  4803.3  430.84  4820.2  429.66  4830.3  427.30
  4845.4  423.10  4850.4  420.96  4860.4  421.38  4889.3  419.20  4898.5  418.90
  4898.8  418.40  4902.3  418.40  4902.5  418.90  4918.1  420.06  4940.5  420.99
  4960.5  422.42  4990.6  419.98  5000.6  419.75  5010.6  420.06  5030.6  422.12
  5036.7  424.42  5041.7  426.84  5050.6  429.66  5060.6  432.25  5070.6  433.71
  5120.6  436.25  5150.6  438.24  5171.9  439.04  5190.6  440.24  5242.9  440.70
#Mann=7,-1,0
  4739.6    0.05       0  4789.1     0.1       0  4803.3    0.16       0
  4898.5    0.07       0  4902.5    0.16       0  4918.1    0.16       0
  5171.9    0.05       0
Bank Sta=4898.5,4902.5
Exp/Cntr=0.3,0.1

Type RM Length L Ch R = 1,1293,258,258,258
BEGIN DESCRIPTION:
LONG BRANCH TRIB 4 5 0
END DESCRIPTION:
XS GIS Cut Line= 4
      3485895.45     10427411.92      3485803.42     10427386.74
      3485649.77     10427332.92      3485399.79     10427298.20
#Sta/Elev= 30
  4867.9  432.28  4954.3  430.54  4966.5  428.81  4975.3  423.61  4985.9  419.18
  4990.5  417.74  4990.8  417.24  4994.3  417.24  4994.5  417.74  5007.1  419.73
  5017.7  422.63  5023.5  424.72  5028.8  427.53  5038.9  428.80  5069.8  429.41
  5091.9  429.60  5102.5  427.82  5111.3  425.36  5116.6  428.41  5126.1  428.40
  5133.9  429.78  5144.0  430.66  5170.5  429.86  5175.5  431.83  5194.4  432.86
  5214.6  433.15  5234.8  434.47  5305.5  437.21  5369.7  439.22  5378.5  439.34
#Mann=6,-1,0
  4867.9     0.1       0  4966.5    0.16       0  4990.5    0.07       0
  4994.5    0.16       0  5069.8    0.05       0  5369.7    0.16       0
Bank Sta=4990.5,4994.5
Exp/Cntr=0.3,0.1

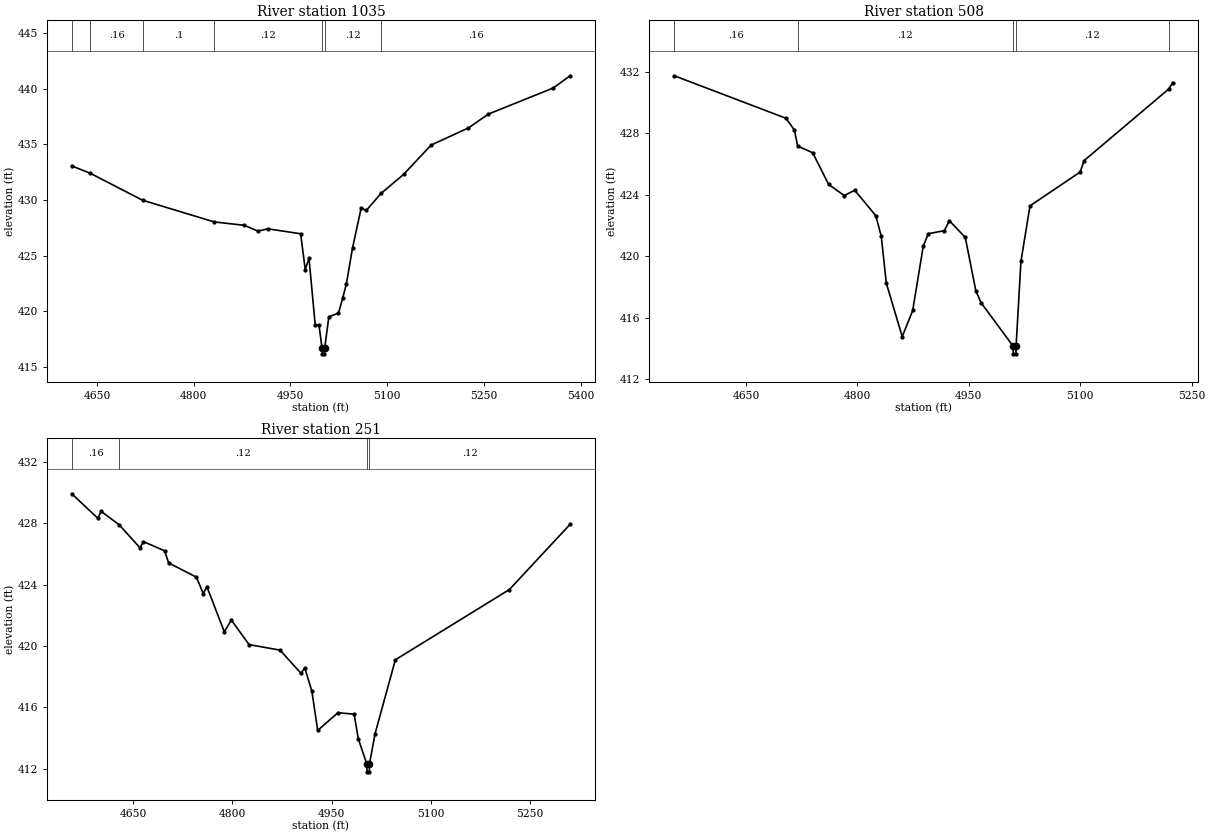
Type RM Length L Ch R = 1,1035,527,527,527
BEGIN DESCRIPTION:
LONG BRANCH TRIB 4 3 1
END DESCRIPTION:
XS GIS Cut Line= 3
      3485983.84     10427440.03      3485988.18     10427244.71
      3485495.95     10426942.05
#Sta/Elev= 30
  4610.7  433.06  4639.7  432.39  4720.5  429.98  4831.7  428.03  4878.3  427.73
  4899.5  427.21  4915.0  427.41  4965.8  426.97  4972.9  423.76  4978.8  424.76
  4988.4  418.79  4994.2  418.79  4999.0  416.69  4999.3  416.19  5002.8  416.19
  5003.0  416.69  5009.6  419.52  5024.5  419.84  5030.9  421.16  5036.8  422.49
  5046.3  425.70  5059.7  429.27  5067.6  429.06  5090.5  430.59  5125.6  432.30
  5168.2  434.93  5226.2  436.47  5257.0  437.71  5357.6  440.05  5383.9  441.15
#Mann=7,-1,0
  4610.7     0.1       0  4639.7    0.16       0  4720.5     0.1       0
  4831.7    0.12       0  4999.0    0.07       0  5003.0    0.12       0
  5090.5    0.16       0
Bank Sta=4999,5003
Exp/Cntr=0.3,0.1

Type RM Length L Ch R = 1,508,257,257,257
BEGIN DESCRIPTION:
LONG BRANCH TRIB 4 2 0
END DESCRIPTION:
XS GIS Cut Line= 4
      3486480.87     10427117.47      3486342.11     10427041.64
      3486143.28     10426832.78      3485926.65     10426774.23
#Sta/Elev= 30
  4553.5  431.74  4703.6  428.98  4715.1  428.22  4719.5  427.17  4739.8  426.73
  4761.2  424.67  4782.2  423.95  4796.4  424.29  4824.7  422.64  4832.0  421.31
  4838.9  418.24  4860.3  414.77  4874.4  416.47  4888.6  420.66  4895.5  421.47
  4916.9  421.66  4923.8  422.31  4945.2  421.22  4959.3  417.77  4966.2  416.99
  5009.6  414.15  5009.8  413.65  5013.3  413.65  5013.6  414.15  5020.1  419.66
  5032.3  423.28  5099.9  425.48  5105.1  426.22  5219.1  430.88  5224.4  431.30
#Mann=5,-1,0
  4553.5    0.16       0  4719.5    0.12       0  5009.6    0.07       0
  5013.6    0.12       0  5219.1    0.16       0
Bank Sta=5009.6,5013.6
Exp/Cntr=0.3,0.1

Type RM Length L Ch R = 1,251,0,0,0
BEGIN DESCRIPTION:
LONG BRANCH TRIB 4 1 0
END DESCRIPTION:
XS GIS Cut Line= 4
      3486500.32     10427040.69      3486400.50     10426734.72
      3486196.51     10426660.94      3485996.19     10426736.33
#Sta/Elev= 30
  4557.6  429.93  4596.8  428.34  4602.1  428.78  4629.4  427.90  4660.6  426.41
  4665.9  426.81  4697.8  426.21  4703.9  425.42  4745.9  424.49  4756.3  423.41
  4761.6  423.88  4788.0  420.93  4798.7  421.69  4825.4  420.09  4872.2  419.73
  4903.8  418.22  4909.6  418.57  4920.3  417.05  4929.1  414.49  4959.7  415.65
  4984.1  415.55  4990.4  413.95  5003.3  412.29  5003.6  411.79  5007.1  411.79
  5007.3  412.29  5015.7  414.27  5046.4  419.10  5218.6  423.68  5310.4  427.94
#Mann=4,-1,0
  4557.6    0.16       0  4629.4    0.12       0  5003.3    0.07       0
  5007.3    0.12       0
Bank Sta=5003.3,5007.3
Exp/Cntr=0.3,0.1

Chan Stop Cuts=-1