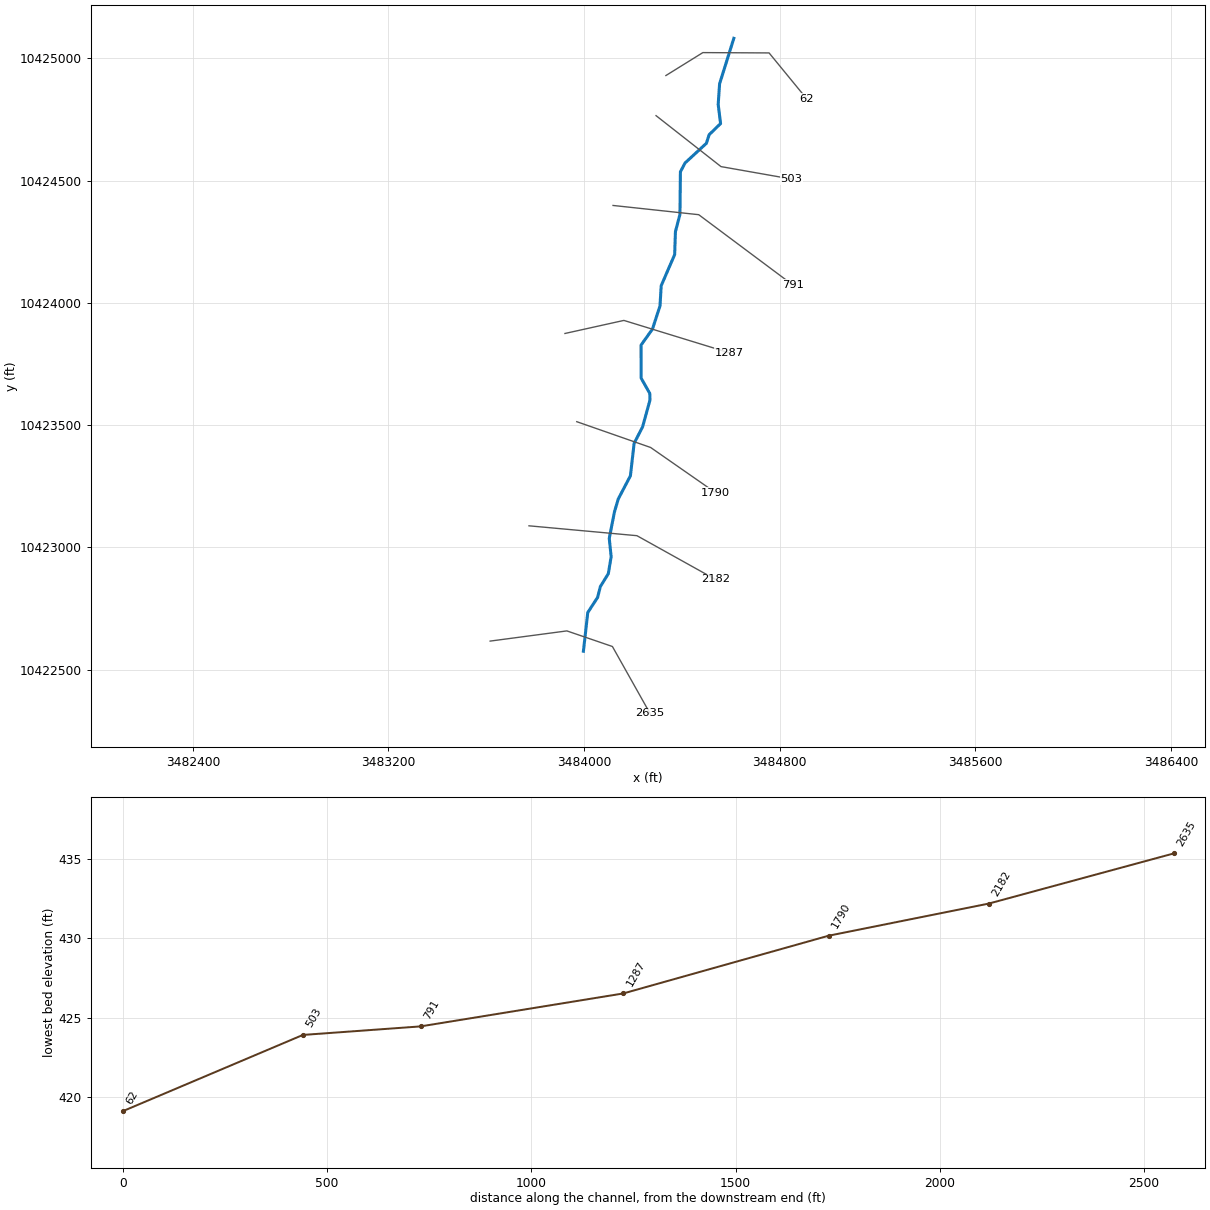
--- LONG BRANCH TRIB 6.prj (project) ---

Proj Title=LONG BRANCH TRIB 6 Base Level Engineering
Current Plan=p01
Default Exp/Contr=0.3,0.1
English Units
Geom File=g01
Flow File=f01
Plan File=p01
BEGIN DESCRIPTION:
LONG BRANCH TRIB 6
END DESCRIPTION:

--- LONG BRANCH TRIB 6.p01 (plan) ---

Plan Title=Multiple Run
Short Identifier=Multiple
Geom File=g01
Flow File=f01
Subcritical Flow
K Sum by GR= 0
Std Step Tol= 0.01
Critical Tol= 0.01
Num of Std Step Trials= 20
Max Error Tol= 0.3
Flow Tol Ratio= 0.001
Split Flow NTrial= 30
Split Flow Tol= 0.02
Split Flow Ratio= 0.02
Log Output Level= 0
Friction Slope Method= 1
Unsteady Friction Slope Method= 2
Unsteady Bridges Friction Slope Method= 1
Parabolic Critical Depth
Global Vel Dist=  1 , 1 , 1
Global Log Level= 0
CheckData=True
Encroach Param= -1, 0, 0, 0
BEGIN DESCRIPTION:
Multiple Run
END DESCRIPTION:

--- LONG BRANCH TRIB 6.f01 (steady flow) ---

Flow Title=Multiple
Number of Profiles=7
Profile Names=10-year,25-year,50-year,1pct_min,100-year,1pct_plu,500-year
River Rch & RM= LONG BRANCH TRIB,Reach-1,2635
     537     718     864     760    1027    1389    1448
Boundary for River Rch & Prof#=LONG BRANCH TRIB,Reach-1,1
Up Type=0
Dn Type=3
Dn Slope=0.005
Boundary for River Rch & Prof#=LONG BRANCH TRIB,Reach-1,2
Up Type=0
Dn Type=3
Dn Slope=0.005
Boundary for River Rch & Prof#=LONG BRANCH TRIB,Reach-1,3
Up Type=0
Dn Type=3
Dn Slope=0.005
Boundary for River Rch & Prof#=LONG BRANCH TRIB,Reach-1,4
Up Type=0
Dn Type=3
Dn Slope=0.005
Boundary for River Rch & Prof#=LONG BRANCH TRIB,Reach-1,5
Up Type=0
Dn Type=3
Dn Slope=0.005
Boundary for River Rch & Prof#=LONG BRANCH TRIB,Reach-1,6
Up Type=0
Dn Type=3
Dn Slope=0.005
Boundary for River Rch & Prof#=LONG BRANCH TRIB,Reach-1,7
Up Type=0
Dn Type=3
Dn Slope=0.005

--- LONG BRANCH TRIB 6.g01 (geometry) ---

Geom Title=Existing Conditions

River Reach=LONG BRANCH TRIB,Reach-1
Reach XY= 30
      3483997.09     10422575.68      3484014.86     10422733.76
      3484055.10     10422795.62      3484066.35     10422839.81
      3484098.98     10422892.97      3484110.47     10422961.95
      3484102.81     10423037.40      3484124.17     10423145.93
      3484139.76     10423198.46      3484189.25     10423292.79
      3484204.46     10423425.67      3484239.01     10423492.93
      3484269.44     10423602.97      3484268.30     10423630.00
      3484233.18     10423692.14      3484232.66     10423827.26
      3484279.38     10423892.73      3484310.20     10423987.43
      3484315.23     10424070.35      3484370.18     10424197.44
      3484373.35     10424291.13      3484391.80     10424361.77
      3484393.73     10424535.97      3484412.74     10424572.03
      3484499.96     10424652.47      3484511.21     10424687.65
      3484557.96     10424733.11      3484548.17     10424811.54
      3484553.95     10424895.83      3484612.11     10425081.64

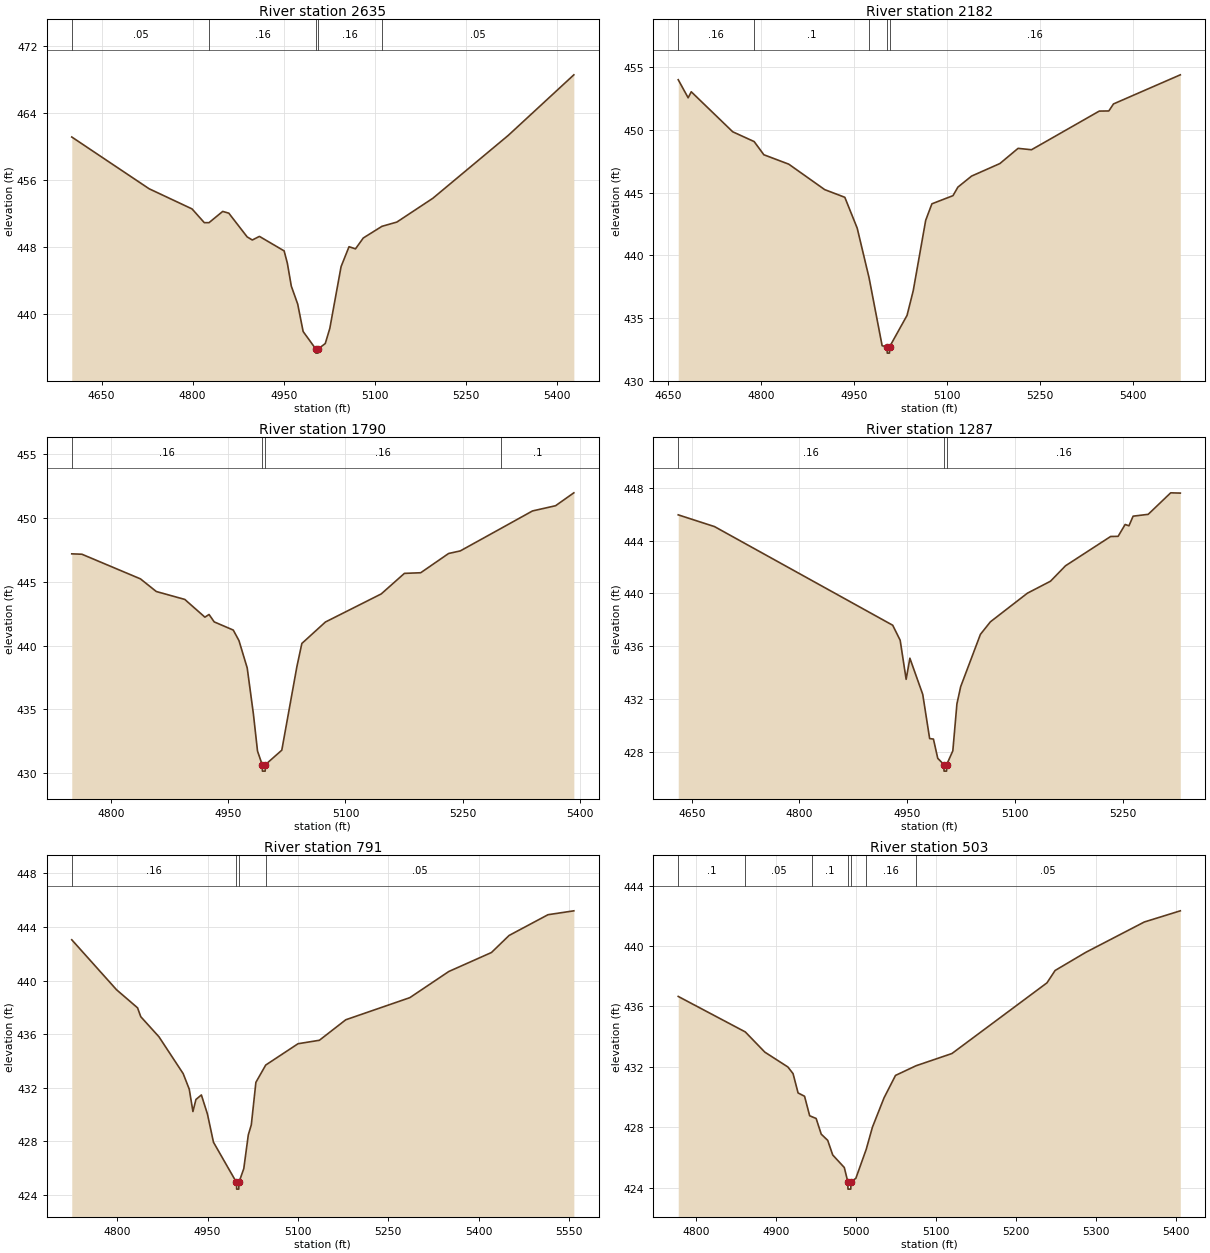
Type RM Length L Ch R = 1,2635,453,453,453
BEGIN DESCRIPTION:
LONG BRANCH TRIB 6 8 0
END DESCRIPTION:
XS GIS Cut Line= 4
      3483615.70     10422617.06      3483929.50     10422658.72
      3484115.69     10422594.92      3484269.33     10422321.51
#Sta/Elev= 30
  4600.9  461.16  4728.4  454.98  4799.0  452.58  4819.2  450.94  4827.0  450.94
  4849.5  452.28  4859.6  452.07  4889.8  449.24  4898.3  448.87  4910.0  449.30
  4950.7  447.57  4956.0  446.10  4962.5  443.37  4973.1  441.21  4982.0  437.95
  5002.8  435.87  5003.0  435.37  5006.5  435.37  5006.8  435.87  5018.5  436.52
  5025.9  438.31  5044.5  445.69  5057.6  448.07  5068.2  447.81  5081.1  449.11
  5111.8  450.50  5136.4  451.01  5195.7  453.85  5320.0  461.36  5427.9  468.58
#Mann=5,-1,0
  4600.9    0.05       0  4827.0    0.16       0  5002.8    0.07       0
  5006.8    0.16       0  5111.8    0.05       0
Bank Sta=5002.8,5006.8
Exp/Cntr=0.3,0.1

Type RM Length L Ch R = 1,2182,392,392,392
BEGIN DESCRIPTION:
LONG BRANCH TRIB 6 7 0
END DESCRIPTION:
XS GIS Cut Line= 3
      3483774.57     10423088.41      3484215.95     10423048.05
      3484536.30     10422869.64
#Sta/Elev= 30
  4665.9  453.99  4681.9  452.55  4686.9  453.03  4753.8  449.84  4788.4  449.06
  4804.0  448.01  4844.2  447.26  4902.2  445.23  4934.6  444.62  4954.6  442.16
  4973.8  438.19  4994.8  432.79  5002.8  432.70  5003.1  432.20  5006.6  432.20
  5006.8  432.70  5035.0  435.21  5045.0  437.18  5065.1  442.79  5075.1  444.10
  5109.1  444.75  5117.0  445.43  5139.1  446.31  5184.8  447.31  5214.1  448.52
  5235.8  448.41  5345.1  451.49  5360.5  451.50  5368.0  452.06  5475.8  454.38
#Mann=5,-1,0
  4665.9    0.16       0  4788.4     0.1       0  4973.8    0.16       0
  5002.8    0.07       0  5006.8    0.16       0
Bank Sta=5002.8,5006.8
Exp/Cntr=0.3,0.1

Type RM Length L Ch R = 1,1790,503,503,503
BEGIN DESCRIPTION:
LONG BRANCH TRIB 6 6 0
END DESCRIPTION:
XS GIS Cut Line= 3
      3483969.84     10423514.20      3484271.94     10423408.72
      3484537.30     10423224.01
#Sta/Elev= 30
  4749.3  447.19  4762.3  447.16  4837.3  445.23  4857.6  444.24  4894.1  443.62
  4919.9  442.23  4925.2  442.44  4931.8  441.86  4956.2  441.22  4963.5  440.40
  4974.1  438.25  4982.0  434.66  4987.3  431.74  4993.3  430.67  4993.6  430.17
  4997.1  430.17  4997.3  430.67  5018.4  431.81  5037.7  438.34  5044.1  440.17
  5074.3  441.85  5145.8  444.05  5175.5  445.66  5196.4  445.71  5232.2  447.22
  5247.1  447.42  5299.2  449.18  5339.6  450.55  5369.2  450.96  5392.6  451.97
#Mann=4,-1,0
  4749.3    0.16       0  4993.3    0.07       0  4997.3    0.16       0
  5299.2     0.1       0
Bank Sta=4993.3,4997.3
Exp/Cntr=0.3,0.1

Type RM Length L Ch R = 1,1287,496,496,496
BEGIN DESCRIPTION:
LONG BRANCH TRIB 6 5 0
END DESCRIPTION:
XS GIS Cut Line= 3
      3483921.66     10423874.86      3484162.57     10423928.25
      3484594.87     10423795.44
#Sta/Elev= 30
  4631.2  445.95  4681.7  445.06  4929.8  437.58  4940.2  436.44  4948.5  433.48
  4953.7  435.08  4971.6  432.34  4981.2  428.99  4986.5  428.95  4992.5  427.49
  5001.0  427.02  5001.3  426.52  5004.8  426.52  5005.0  427.02  5013.5  428.06
  5019.2  431.62  5024.4  432.92  5051.9  436.89  5065.8  437.84  5117.3  440.01
  5149.5  440.92  5170.4  442.09  5233.2  444.31  5243.6  444.32  5253.4  445.22
  5258.7  445.12  5264.5  445.85  5285.5  445.99  5316.8  447.62  5330.2  447.60
#Mann=3,-1,0
  4631.2    0.16       0  5001.0    0.07       0  5005.0    0.16       0
Bank Sta=5001,5005
Exp/Cntr=0.3,0.1

Type RM Length L Ch R = 1,791,288,288,288
BEGIN DESCRIPTION:
LONG BRANCH TRIB 6 4 0
END DESCRIPTION:
XS GIS Cut Line= 3
      3484118.25     10424398.31      3484468.56     10424360.55
      3484853.95     10424072.80
#Sta/Elev= 30
  4724.6  443.05  4798.9  439.32  4833.8  437.97  4839.1  437.31  4869.3  435.81
  4909.5  433.06  4919.6  431.90  4925.7  430.23  4930.7  431.13  4939.7  431.47
  4949.8  430.04  4959.8  427.94  4998.0  424.94  4998.3  424.44  5001.8  424.44
  5002.0  424.94  5010.1  425.97  5017.6  428.49  5022.6  429.24  5030.2  432.41
  5046.5  433.70  5100.1  435.29  5135.6  435.55  5179.4  437.08  5285.7  438.73
  5350.3  440.68  5421.2  442.10  5450.4  443.37  5515.0  444.92  5557.9  445.21
#Mann=4,-1,0
  4724.6    0.16       0  4998.0    0.07       0  5002.0    0.16       0
  5046.5    0.05       0
Bank Sta=4998,5002
Exp/Cntr=0.3,0.1

Type RM Length L Ch R = 1,503,441,441,441
BEGIN DESCRIPTION:
LONG BRANCH TRIB 6 2 0
END DESCRIPTION:
XS GIS Cut Line= 3
      3484294.10     10424765.48      3484559.70     10424557.16
      3484846.52     10424506.55
#Sta/Elev= 30
  4777.2  436.66  4861.2  434.31  4885.7  432.97  4914.5  431.99  4921.0  431.55
  4927.3  430.27  4935.4  430.05  4941.8  428.76  4945.3  428.68  4949.9  428.58
  4956.3  427.54  4964.4  427.13  4970.7  426.16  4985.2  425.33  4989.5  424.40
  4989.8  423.90  4993.3  423.90  4993.5  424.40  4999.6  424.61  5012.6  426.53
  5020.4  428.00  5034.9  429.94  5049.3  431.43  5075.0  432.07  5120.0  432.88
  5239.0  437.56  5249.2  438.38  5287.6  439.58  5360.9  441.59  5406.0  442.33
#Mann=7,-1,0
  4777.2     0.1       0  4861.2    0.05       0  4945.3     0.1       0
  4989.5    0.07       0  4993.5     0.1       0  5012.6    0.16       0
  5075.0    0.05       0
Bank Sta=4989.5,4993.5
Exp/Cntr=0.3,0.1

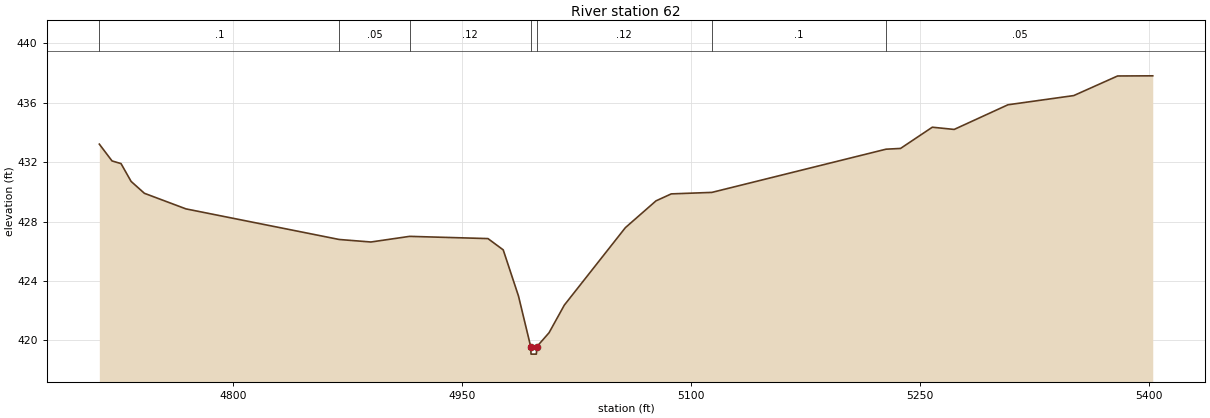
Type RM Length L Ch R = 1,62,0,0,0
BEGIN DESCRIPTION:
LONG BRANCH TRIB 6 1 0
END DESCRIPTION:
XS GIS Cut Line= 4
      3484334.44     10424929.55      3484485.49     10425023.31
      3484756.32     10425022.00      3484909.06     10424835.61
#Sta/Elev= 30
  4712.7  433.22  4721.0  432.09  4726.9  431.91  4733.5  430.71  4742.2  429.91
  4769.4  428.86  4869.7  426.80  4890.5  426.63  4915.8  427.01  4967.1  426.86
  4977.1  426.10  4987.1  422.99  4995.1  419.58  4995.3  419.08  4998.8  419.08
  4999.1  419.58  5007.1  420.52  5017.1  422.38  5057.1  427.60  5077.1  429.40
  5087.1  429.87  5113.7  429.97  5227.7  432.88  5237.2  432.93  5258.0  434.36
  5272.3  434.21  5307.5  435.87  5350.6  436.49  5379.3  437.81  5402.3  437.82
#Mann=7,-1,0
  4712.7     0.1       0  4869.7    0.05       0  4915.8    0.12       0
  4995.1    0.07       0  4999.1    0.12       0  5113.7     0.1       0
  5227.7    0.05       0
Bank Sta=4995.1,4999.1
Exp/Cntr=0.3,0.1

Chan Stop Cuts=-1