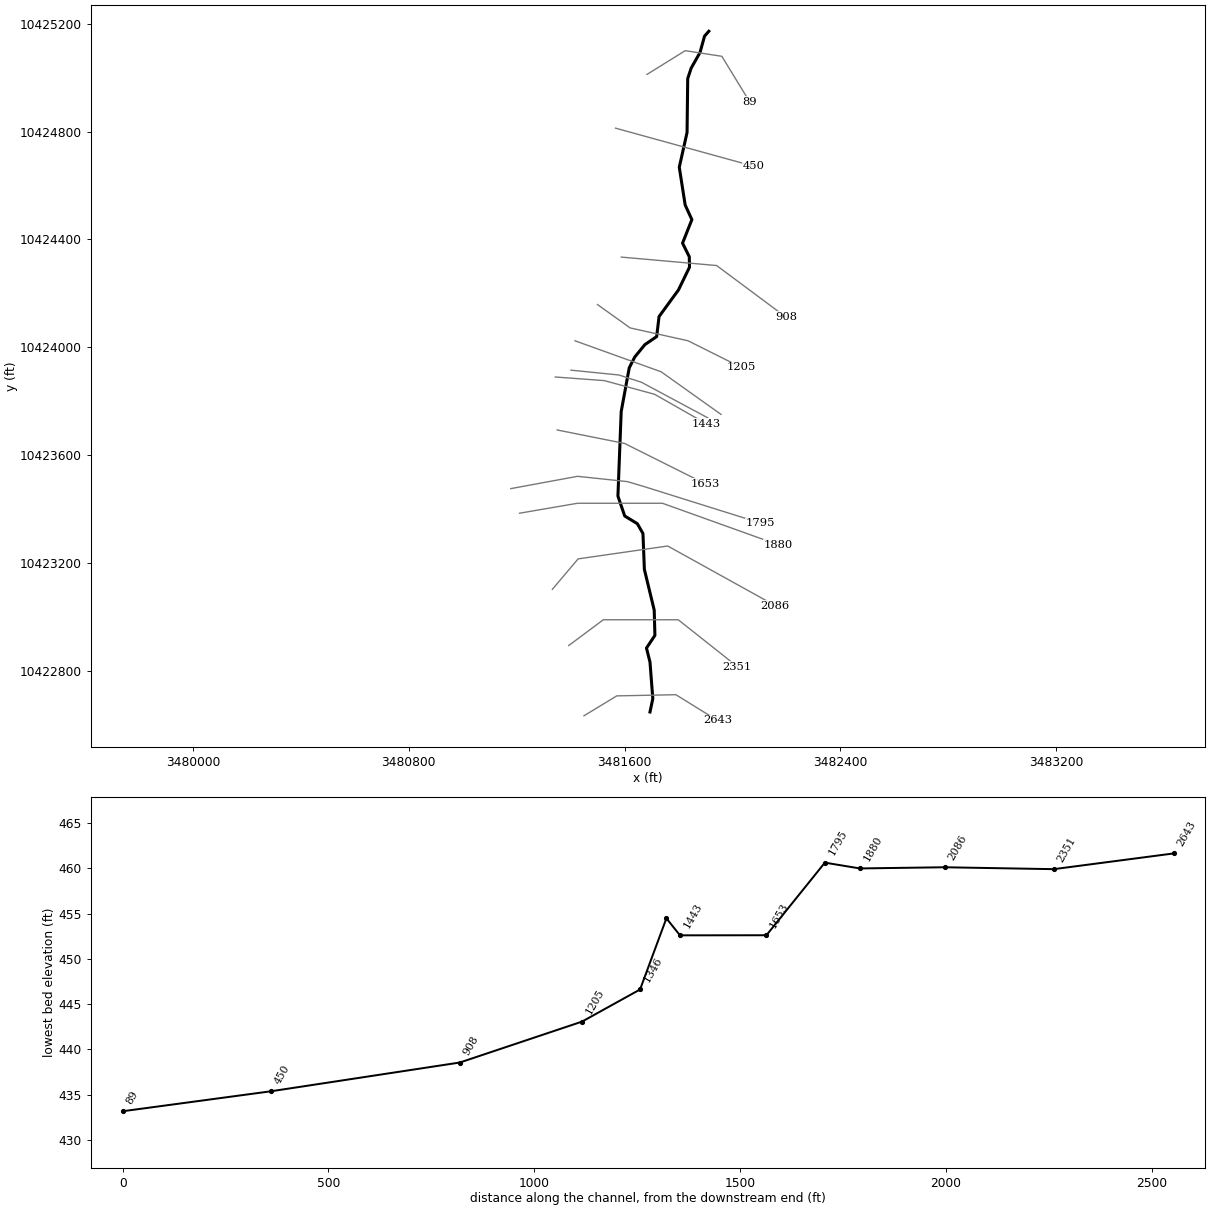
--- LONG BRANCH TRIB 7.prj (project) ---

Proj Title=LONG BRANCH TRIB 7 Base Level Engineering
Current Plan=p01
Default Exp/Contr=0.3,0.1
English Units
Geom File=g01
Flow File=f01
Plan File=p01
Y Axis Title=Elevation
X Axis Title(PF)=Main Channel Distance
X Axis Title(XS)=Station
BEGIN DESCRIPTION:
LONG BRANCH TRIB 7
END DESCRIPTION:
DSS Export Rating Curves= 0
DSS Export Rating Curve Sorted= 0
DSS Export Volume Flow Curves= 0
DXF OffsetX= 0
DXF OffsetY= 0
DXF ScaleX= 1
DXF ScaleY= 10

--- LONG BRANCH TRIB 7.p01 (plan) ---

Plan Title=Multiple Run
Short Identifier=Multiple
Geom File=g01
Flow File=f01
Subcritical Flow
K Sum by GR= 0
Std Step Tol= 0.01
Critical Tol= 0.01
Num of Std Step Trials= 20
Max Error Tol= 0.3
Flow Tol Ratio= 0.001
Split Flow NTrial= 30
Split Flow Tol= 0.02
Split Flow Ratio= 0.02
Log Output Level= 0
Friction Slope Method= 1
Unsteady Friction Slope Method= 2
Unsteady Bridges Friction Slope Method= 1
Parabolic Critical Depth
Global Vel Dist=  1 , 1 , 1
Global Log Level= 0
CheckData=True
Encroach Param= -1, 0, 0, 0
BEGIN DESCRIPTION:
Multiple Run
END DESCRIPTION:

--- LONG BRANCH TRIB 7.f01 (steady flow) ---

Flow Title=Multiple
Program Version=4.10
Number of Profiles= 7
Profile Names=10-year,25-year,50-year,1pct_min,100-year,1pct_plu,500-year
River Rch & RM=LONG BRANCH TRIB,Reach-1         ,2643
     334     434     511     442     598     809     814
Boundary for River Rch & Prof#=LONG BRANCH TRIB,Reach-1         , 1
Up Type= 0
Dn Type= 3
Dn Slope=0.005
Boundary for River Rch & Prof#=LONG BRANCH TRIB,Reach-1         , 2
Up Type= 0
Dn Type= 3
Dn Slope=0.005
Boundary for River Rch & Prof#=LONG BRANCH TRIB,Reach-1         , 3
Up Type= 0
Dn Type= 3
Dn Slope=0.005
Boundary for River Rch & Prof#=LONG BRANCH TRIB,Reach-1         , 4
Up Type= 0
Dn Type= 3
Dn Slope=0.005
Boundary for River Rch & Prof#=LONG BRANCH TRIB,Reach-1         , 5
Up Type= 0
Dn Type= 3
Dn Slope=0.005
Boundary for River Rch & Prof#=LONG BRANCH TRIB,Reach-1         , 6
Up Type= 0
Dn Type= 3
Dn Slope=0.005
Boundary for River Rch & Prof#=LONG BRANCH TRIB,Reach-1         , 7
Up Type= 0
Dn Type= 3
Dn Slope=0.005
DSS Import GetInterval= 0
DSS Import GetPeak= 0
DSS Import FillOption= 0

--- LONG BRANCH TRIB 7.g01 (geometry) ---

Geom Title=Existing Conditions
Program Version=4.10

River Reach=LONG BRANCH TRIB,Reach-1
Reach XY= 30
      3481694.01     10422648.36      3481704.43     10422697.84
      3481694.01     10422833.25      3481680.99     10422885.34
      3481712.24     10422932.21      3481709.64     10423025.96
      3481673.18       10423177.      3481667.97     10423309.82
      3481647.14     10423346.27      3481600.26     10423374.92
      3481575.13     10423448.67      3481587.29     10423762.04
      3481617.12     10423924.08      3481637.53     10423964.15
        3481675.     10424009.94      3481718.81     10424039.91
      3481727.58     10424114.01      3481799.53     10424212.72
       3481840.5     10424297.14      3481839.62     10424335.95
      3481814.68     10424386.23      3481849.27     10424473.33
      3481824.42     10424527.47      3481802.58     10424667.54
       3481831.4     10424796.53      3481833.83     10424996.04
      3481846.46     10425034.56       3481879.4      10425092.8
      3481896.18     10425153.51      3481912.11     10425171.64

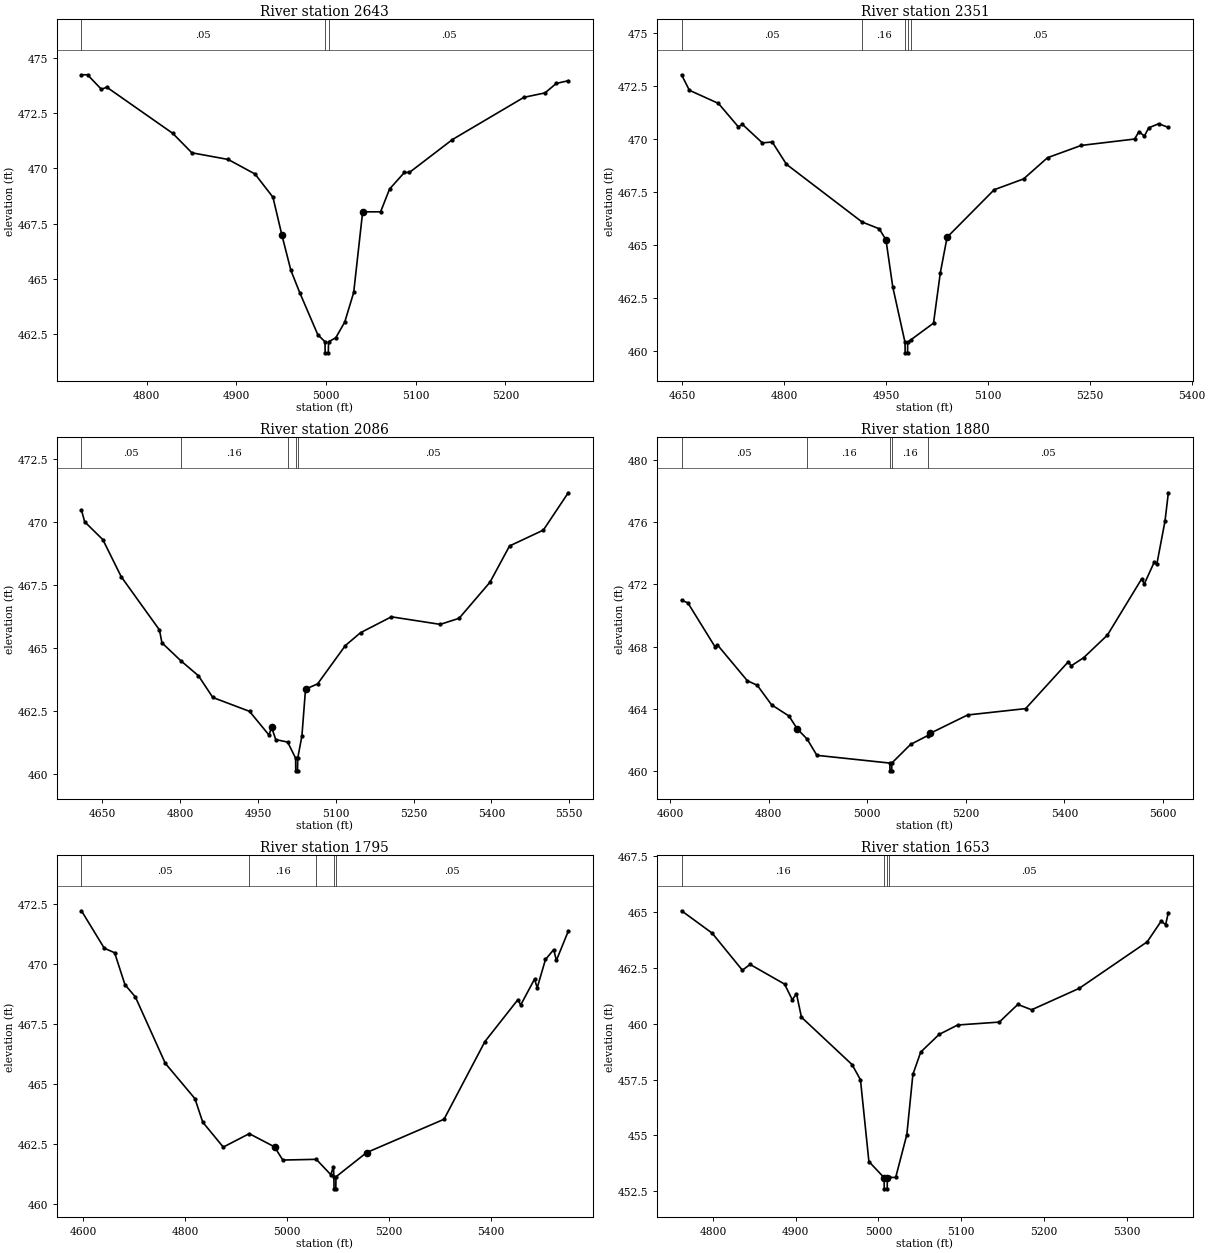
Type RM Length L Ch R = 1 ,2643    ,292,292,292
BEGIN DESCRIPTION:
LONG BRANCH TRIB 7 3 2
END DESCRIPTION:
XS GIS Cut Line= 4
       3481449.3     10422634.27      3481570.86     10422708.08
      3481790.04     10422712.42      3481944.12     10422616.93
#Sta/Elev= 30
  4727.4  474.23  4734.2  474.23  4749.7  473.57  4755.6  473.67  4829.2  471.58
  4850.5   470.7  4890.9   470.4  4920.9  469.74  4940.9  468.69  4950.9  466.97
  4960.9  465.38  4970.9  464.36  4990.9  462.47  4998.9  462.15  4999.1  461.65
  5002.6  461.65  5002.9  462.15  5010.9  462.33  5020.9  463.04  5030.9  464.38
  5040.9  468.03  5060.9  468.03  5070.9  469.06  5087.4  469.81    5093  469.81
    5141   471.3  5220.7  473.21  5244.2  473.41  5256.8  473.84  5270.1  473.96
#Mann= 3 ,-1 , 0
  4727.4     .05       0  4998.9     .03       0  5002.9     .05       0
Bank Sta=4950.9,5040.9
XS Rating Curve= 0 ,0
Exp/Cntr=0.3,0.1

Type RM Length L Ch R = 1 ,2351    ,265,265,265
BEGIN DESCRIPTION:
Mapping XS 2e5486fb
END DESCRIPTION:
XS GIS Cut Line= 4
      3481392.88     10422894.69      3481520.95      10422990.2
      3481798.72      10422990.2      3482017.48     10422816.92
#Sta/Elev= 30
    4649  473.02  4660.5  472.29  4703.3  471.67  4732.5  470.57  4738.7  470.68
  4767.9  469.81  4782.5  469.85  4803.4   468.8  4914.7  466.08  4939.9  465.76
  4949.9  465.24  4959.9  463.02  4977.9  460.41  4978.2  459.91  4981.7  459.91
  4981.9  460.41  4986.4  460.52  5019.9  461.31  5029.9  463.68  5039.9  465.36
  5109.2   467.6  5152.5  468.11  5187.7  469.11  5237.4  469.69  5315.9  469.99
  5322.3  470.34  5330.3  470.13  5336.7  470.52  5351.2  470.71  5365.6  470.54
#Mann= 5 ,-1 , 0
    4649     .05       0  4914.7     .16       0  4977.9     .03       0
  4981.9     .16       0  4986.4     .05       0
Bank Sta=4949.9,5039.9
XS Rating Curve= 0 ,0
Exp/Cntr=0.3,0.1

Type RM Length L Ch R = 1 ,2086    ,206,206,206
BEGIN DESCRIPTION:
Mapping XS 1ebfa15b
END DESCRIPTION:
XS GIS Cut Line= 4
      3481332.17     10423103.07      3481427.63     10423215.89
      3481759.66     10423263.63      3482158.01     10423042.81
#Sta/Elev= 30
  4609.4  470.47  4615.6     470  4650.7  469.29  4686.1  467.82  4759.8  465.71
  4764.6   465.2  4800.9  464.49  4835.1  463.89  4862.7  463.03  4933.5  462.48
    4971  461.54  4976.1  461.85    4984  461.36  5007.1  461.26  5022.4  460.62
  5022.6  460.12  5026.1  460.12  5026.4  460.62  5034.5   461.5  5041.5  463.36
  5064.8  463.57  5118.3  465.09  5147.6   465.6  5207.1  466.23  5301.2  465.93
  5337.6  466.17  5397.1   467.6  5434.9  469.04  5500.1  469.67  5548.1  471.15
#Mann= 5 ,-1 , 0
  4609.4     .05       0  4800.9     .16       0  5007.1     .05       0
  5022.4     .07       0  5026.4     .05       0
Bank Sta=4976.1,5041.5
XS Rating Curve= 0 ,0
Exp/Cntr=0.3,0.1

Type RM Length L Ch R = 1 ,1880    ,85,85,85
BEGIN DESCRIPTION:
Mapping XS ecc1a990
END DESCRIPTION:
XS GIS Cut Line= 4
      3481210.65     10423385.17      3481425.46     10423422.05
      3481740.13     10423422.05       3482168.5     10423268.45
#Sta/Elev= 30
  4623.3  470.98    4636  470.82  4690.9     468    4696  468.11  4756.7   465.8
    4777   465.5  4805.8  464.25  4841.3  463.52  4857.9   462.7    4878  462.04
  4897.9  460.99  5045.9  460.49  5046.2  459.99  5049.7  459.99  5049.9  460.49
  5087.9  461.69  5122.6  462.26  5127.9  462.41  5203.7  463.59  5321.4     464
  5408.3  467.03  5413.6  466.75  5439.1  467.28  5487.4  468.74  5556.8  472.36
  5562.1  472.03  5582.2  473.43  5587.5  473.29  5604.2  476.09    5611  477.91
#Mann= 5 ,-1 , 0
  4623.3     .05       0    4878     .16       0  5045.9     .07       0
  5049.9     .16       0  5122.6     .05       0
Bank Sta=4857.9,5127.9
XS Rating Curve= 0 ,0
Exp/Cntr=0.3,0.1

Type RM Length L Ch R = 1 ,1795    ,142,142,142
BEGIN DESCRIPTION:
Mapping XS 8221c6cc
END DESCRIPTION:
XS GIS Cut Line= 5
      3481178.09     10423476.31      3481425.46     10423521.88
      3481609.92     10423502.35      3481668.52     10423484.99
      3482104.75     10423348.26
#Sta/Elev= 30
  4596.2  472.22    4641  470.66  4661.3  470.47  4681.6  469.14    4702  468.63
  4760.8  465.86  4818.9  464.39  4834.2  463.41  4874.5  462.37  4925.5  462.93
  4975.1  462.38  4991.3  461.83  5057.1  461.86  5085.5  461.22  5090.7  461.56
  5091.6  461.13  5091.9  460.63  5095.4  460.63  5095.6  461.13  5155.7  462.14
  5307.7  463.53    5388  466.77  5452.9  468.52  5458.1  468.29  5485.3  469.37
  5490.6  469.01  5506.8  470.19    5523   470.6  5528.2  470.15  5551.5  471.37
#Mann= 5 ,-1 , 0
  4596.2     .05       0  4925.5     .16       0  5057.1     .05       0
  5091.6     .07       0  5095.6     .05       0
Bank Sta=4975.1,5155.7
XS Rating Curve= 0 ,0
Exp/Cntr=0.3,0.1

Type RM Length L Ch R = 1 ,1653    ,210,210,210
BEGIN DESCRIPTION:
LONG BRANCH TRIB 7 3 2
END DESCRIPTION:
XS GIS Cut Line= 3
       3481349.9     10423693.73      3481599.92     10423643.73
      3481898.51     10423494.43
#Sta/Elev= 30
  4761.8  465.05  4798.8  464.05  4835.4  462.39  4844.7  462.65  4886.4  461.77
  4895.7  461.07  4900.8  461.34  4906.8  460.29    4968  458.17  4978.2  457.49
  4988.4  453.83  5006.8  453.11    5007  452.61  5010.5  452.61  5010.8  453.11
  5013.1  453.12  5020.8  453.12  5034.3  455.04  5041.6  457.73  5051.1  458.73
  5073.4  459.52  5095.8  459.94  5146.1  460.07  5168.5  460.86  5185.2  460.62
  5242.8  461.58    5325  463.66  5341.8  464.58  5347.3  464.43  5350.6  464.97
#Mann= 4 ,-1 , 0
  4761.8     .16       0  5006.8     .07       0  5010.8     .16       0
  5013.1     .05       0
Bank Sta=5006.8,5010.8
XS Rating Curve= 0 ,0
Exp/Cntr=0.3,0.1

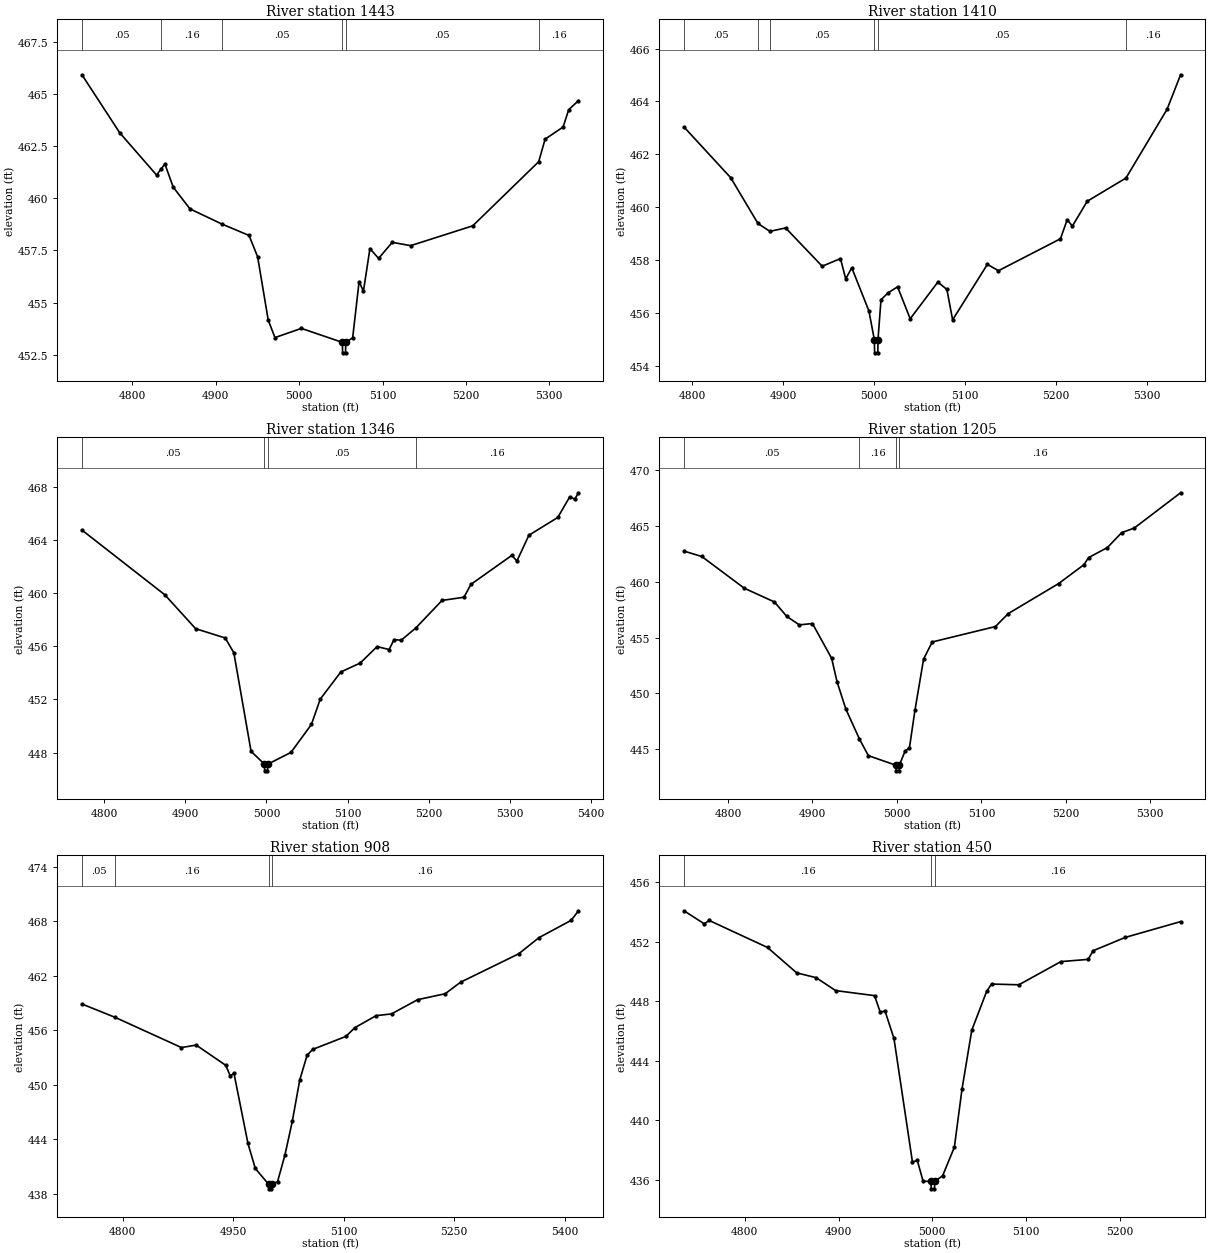
Type RM Length L Ch R = 1 ,1443    ,33,33,33
BEGIN DESCRIPTION:
Mapping XS 6d245244
END DESCRIPTION:
XS GIS Cut Line= 4
      3481342.86     10423890.06      3481524.87     10423876.63
      3481711.31     10423825.92      3481902.23     10423717.03
#Sta/Elev= 30
  4739.4  465.91  4784.8  463.13  4828.9  461.11  4834.5  461.41  4838.9  461.64
  4848.9  460.53    4869  459.49  4907.5  458.76  4939.8  458.22  4950.1   457.2
  4962.8  454.17  4970.9  453.33  5002.6  453.77  5051.8   453.1    5052   452.6
  5055.5   452.6  5055.8   453.1  5064.1  453.32  5071.8  456.01    5077  455.55
  5084.8  457.59  5095.2  457.12  5111.6  457.89  5133.6  457.73  5208.1  458.68
  5287.2  461.75  5294.9  462.83  5316.5  463.41  5323.2  464.24  5334.9  464.67
#Mann= 6 ,-1 , 0
  4739.4     .05       0  4834.5     .16       0  4907.5     .05       0
  5051.8    .035       0  5055.8     .05       0  5287.2     .16       0
Bank Sta=5051.8,5055.8
XS Rating Curve= 0 ,0
Exp/Cntr=0.3,0.1

Type RM Length L Ch R = 1 ,1410    ,64,64,64
BEGIN DESCRIPTION:
LONG BRANCH TRIB 7 3 3
END DESCRIPTION:
XS GIS Cut Line= 4
       3481401.1     10423915.41      3481578.57     10423897.51
      3481662.09     10423870.66      3481908.42      10423738.6
#Sta/Elev= 30
  4791.2  463.03  4842.5  461.11  4872.4  459.38  4885.5  459.08  4902.8  459.21
    4943  457.76  4963.1  458.05  4968.8  457.28  4975.5   457.7  4994.3  456.07
  5000.3  454.98  5000.6  454.48  5004.1  454.48  5004.3  454.98  5007.6  456.49
  5015.3  456.75  5025.8  456.98  5039.7  455.77  5070.1  457.16    5080  456.88
  5086.3  455.73  5124.5  457.83  5136.7  457.59  5204.8   458.8  5212.2  459.52
  5217.9  459.28  5234.2  460.22  5276.8   461.1  5321.9   463.7  5336.8  465.01
#Mann= 6 ,-1 , 0
  4791.2     .05       0  4872.4     .16       0  4885.5     .05       0
  5000.3    .035       0  5004.3     .05       0  5276.8     .16       0
Bank Sta=5000.3,5004.3
XS Rating Curve= 0 ,0
Exp/Cntr=0.3,0.1

Type RM Length L Ch R = 1 ,1346    ,141,141,141
BEGIN DESCRIPTION:
LONG BRANCH TRIB 7 3 4
END DESCRIPTION:
XS GIS Cut Line= 3
      3481415.97     10424024.29      3481735.17     10423909.44
      3481957.27     10423751.44
#Sta/Elev= 30
  4772.6  464.76  4874.8  459.88  4912.7  457.33  4949.2  456.63  4959.8  455.51
    4981  448.09  4997.5  447.12  4997.7  446.62  5001.2  446.62  5001.5  447.12
  5030.2  448.01  5055.4  450.12  5066.2  452.02  5091.6  454.07  5115.4  454.74
  5136.3  455.98  5151.1  455.76  5157.2  456.51  5165.9  456.46  5183.9  457.38
  5216.3  459.46  5243.3   459.7  5251.9  460.67  5302.4  462.86  5308.5  462.42
  5323.3  464.37  5358.9  465.71  5373.7  467.27  5379.8  467.09  5384.4  467.57
#Mann= 4 ,-1 , 0
  4772.6     .05       0  4997.5    .035       0  5001.5     .05       0
  5183.9     .16       0
Bank Sta=4997.5,5001.5
XS Rating Curve= 0 ,0
Exp/Cntr=0.3,0.1

Type RM Length L Ch R = 1 ,1205    ,297,297,297
BEGIN DESCRIPTION:
Mapping XS 2f1ed7ae
END DESCRIPTION:
XS GIS Cut Line= 4
      3481499.54      10424158.5      3481620.33     10424072.01
       3481835.1     10424024.29      3482031.19     10423926.24
#Sta/Elev= 30
    4748  462.73    4769  462.25  4819.3  459.41    4855  458.18  4869.7  456.88
  4884.5  456.13    4900  456.25  4922.7  453.14  4929.1  451.05  4939.4  448.62
  4955.6  445.92  4966.2  444.43  4998.8  443.57  4999.1  443.07  5002.6  443.07
  5002.8  443.57  5009.7  444.84  5014.8  445.12  5021.3  448.47  5031.6  453.08
  5041.8   454.6  5116.6  455.98  5131.8  457.14  5191.5  459.83  5221.3  461.51
  5226.9  462.15  5249.2  463.05    5266  464.38  5280.9  464.79  5335.8  467.95
#Mann= 4 ,-1 , 0
    4748     .05       0  4955.6     .16       0  4998.8     .07       0
  5002.8     .16       0
Bank Sta=4998.8,5002.8
XS Rating Curve= 0 ,0
Exp/Cntr=0.3,0.1

Type RM Length L Ch R = 1 ,908     ,458,458,458
BEGIN DESCRIPTION:
LONG BRANCH TRIB 7 3 1
END DESCRIPTION:
XS GIS Cut Line= 3
      3481587.49     10424334.52        3481941.     10424303.19
      3482197.32     10424112.44
#Sta/Elev= 30
  4744.4  458.89  4789.8  457.41  4879.5   454.1  4899.6  454.37  4939.8  452.14
  4945.8  450.98  4950.9  451.26  4969.9  443.54  4979.9  440.79    4998  439.05
  4998.3  438.55  5001.8  438.55    5002  439.05  5010.1  439.34  5020.1  442.26
  5030.1  445.97  5040.2  450.51  5050.2  453.25  5057.7  453.89  5103.1  455.33
  5114.8  456.27    5144  457.61  5164.9   457.8  5200.4  459.37  5237.8  460.02
  5258.7  461.29  5337.5  464.41  5365.1  466.19  5408.9   468.1  5418.8  469.15
#Mann= 4 ,-1 , 0
  4744.4     .05       0  4789.8     .16       0    4998     .07       0
    5002     .16       0
Bank Sta=4998,5002
XS Rating Curve= 0 ,0
Exp/Cntr=0.3,0.1

Type RM Length L Ch R = 1 ,450     ,361,361,361
BEGIN DESCRIPTION:
LONG BRANCH TRIB 7 3 0
END DESCRIPTION:
XS GIS Cut Line= 2
      3481566.34      10424812.4      3482076.72     10424671.79
#Sta/Elev= 30
  4735.3  454.09  4756.9  453.21  4762.1  453.44  4824.3  451.62  4855.4  449.91
  4876.1  449.59  4896.9  448.72  4938.4  448.38  4944.4  447.28  4949.6  447.34
  4959.1   445.5  4978.8  437.19    4984  437.29  4990.2  435.89  4998.6  435.88
  4998.8  435.38  5002.3  435.38  5002.6  435.88    5011  436.26  5023.5  438.18
  5031.7  442.11  5042.1  446.06  5057.9  448.66  5063.1  449.16  5092.3  449.11
  5137.1  450.67  5166.2  450.82  5171.4   451.4  5205.8   452.3  5264.7  453.36
#Mann= 3 ,-1 , 0
  4735.3     .16       0  4998.6     .07       0  5002.6     .16       0
Bank Sta=4998.6,5002.6
XS Rating Curve= 0 ,0
Exp/Cntr=0.3,0.1

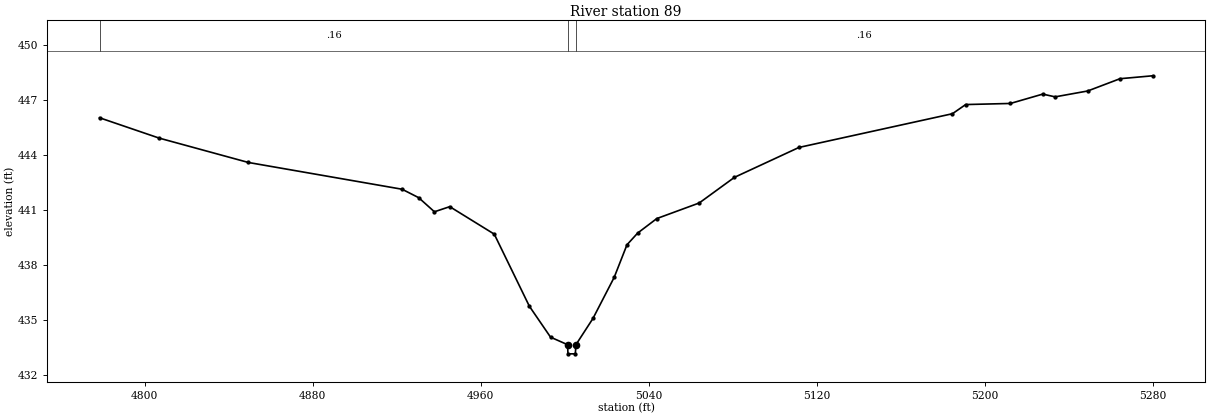
Type RM Length L Ch R = 1 ,89      ,0,0,0
BEGIN DESCRIPTION:
LONG BRANCH TRIB 7 1 0
END DESCRIPTION:
XS GIS Cut Line= 4
      3481682.99     10425011.65      3481824.66     10425099.64
      3481960.38     10425078.76      3482063.31     10424910.19
#Sta/Elev= 30
  4778.5  446.05  4806.9  444.94  4849.4  443.61  4922.6  442.15  4930.5  441.69
    4938  440.92  4945.3   441.2  4966.5   439.7  4983.2  435.77  4993.3  434.08
  5001.4  433.67  5001.6  433.17  5005.1  433.17  5005.4  433.67  5013.5   435.1
  5023.6  437.34  5029.7  439.12  5034.8  439.76  5043.9  440.55  5064.1   441.4
  5080.9   442.8  5111.6  444.43  5184.7  446.27    5191  446.77  5212.3  446.83
  5227.7  447.34  5233.6  447.19  5249.1  447.51  5264.5  448.18  5280.1  448.34
#Mann= 3 ,-1 , 0
  4778.5     .16       0  5001.4     .07       0  5005.4     .16       0
Bank Sta=5001.4,5005.4
XS Rating Curve= 0 ,0
Exp/Cntr=0.3,0.1

Chan Stop Cuts=-1
Use User Specified Reach Order=0
Composite Channel Slope=5