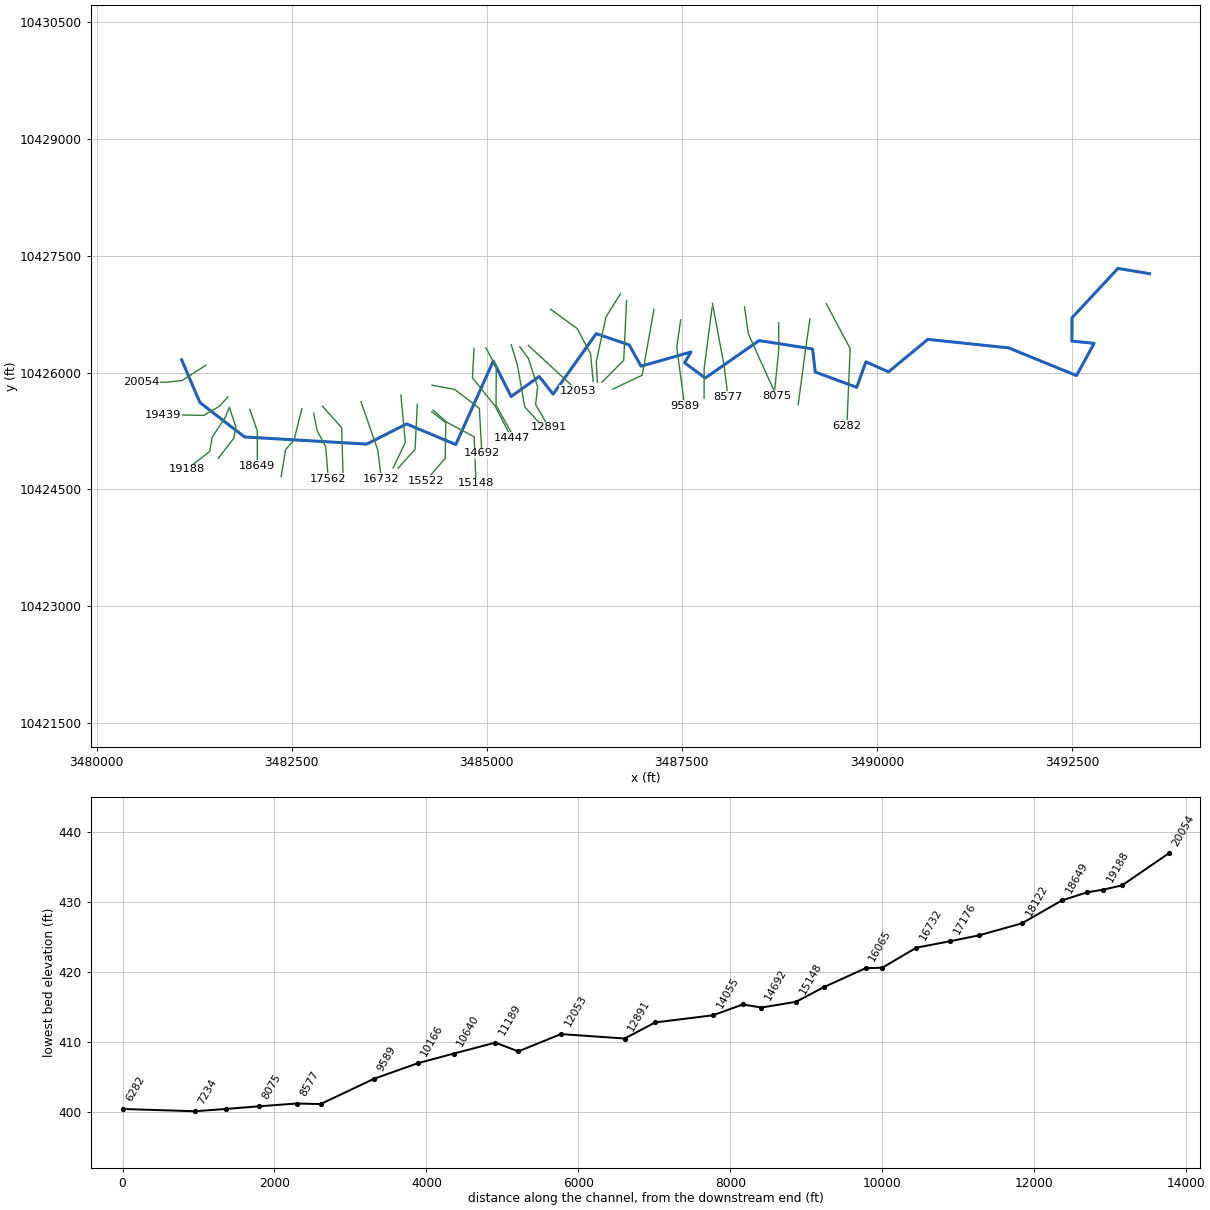
--- LONG BRANCH.prj (project) ---

Proj Title=LONG BRANCH Base Level Engineering
Current Plan=p01
Default Exp/Contr=0.3,0.1
English Units
Geom File=g01
Flow File=f01
Plan File=p01
BEGIN DESCRIPTION:
LONG BRANCH
END DESCRIPTION:

--- LONG BRANCH.p01 (plan) ---

Plan Title=Multiple Run
Short Identifier=Multiple
Geom File=g01
Flow File=f01
Subcritical Flow
K Sum by GR= 0
Std Step Tol= 0.01
Critical Tol= 0.01
Num of Std Step Trials= 20
Max Error Tol= 0.3
Flow Tol Ratio= 0.001
Split Flow NTrial= 30
Split Flow Tol= 0.02
Split Flow Ratio= 0.02
Log Output Level= 0
Friction Slope Method= 1
Unsteady Friction Slope Method= 2
Unsteady Bridges Friction Slope Method= 1
Parabolic Critical Depth
Global Vel Dist=  1 , 1 , 1
Global Log Level= 0
CheckData=True
Encroach Param= -1, 0, 0, 0
BEGIN DESCRIPTION:
Multiple Run
END DESCRIPTION:

--- LONG BRANCH.f01 (steady flow) ---

Flow Title=Multiple
Number of Profiles=7
Profile Names=10-year,25-year,50-year,1pct_min,100-year,1pct_plu,500-year
River Rch & RM= LONG BRANCH,Reach-1,20054
     722     988    1207    1079    1459    1973    2123
River Rch & RM= LONG BRANCH,Reach-1,18649
    1002    1393    1719    1548    2094    2832    3099
River Rch & RM= LONG BRANCH,Reach-1,15522
    1582    2248    2815    2567    3472    4695    5275
River Rch & RM= LONG BRANCH,Reach-1,11189
    1683    2396    3002    2741    3706    5012    5639
River Rch & RM= LONG BRANCH,Reach-1,9589
    1849    2642    3321    3038    4109    5557    6283
River Rch & RM= LONG BRANCH,Reach-1,8075
    1954    2784    3490    3184    4306    5824    6545
Boundary for River Rch & Prof#=LONG BRANCH,Reach-1,1
Up Type=0
Dn Type=3
Dn Slope=0.005
Boundary for River Rch & Prof#=LONG BRANCH,Reach-1,2
Up Type=0
Dn Type=3
Dn Slope=0.005
Boundary for River Rch & Prof#=LONG BRANCH,Reach-1,3
Up Type=0
Dn Type=3
Dn Slope=0.005
Boundary for River Rch & Prof#=LONG BRANCH,Reach-1,4
Up Type=0
Dn Type=3
Dn Slope=0.005
Boundary for River Rch & Prof#=LONG BRANCH,Reach-1,5
Up Type=0
Dn Type=3
Dn Slope=0.005
Boundary for River Rch & Prof#=LONG BRANCH,Reach-1,6
Up Type=0
Dn Type=3
Dn Slope=0.005
Boundary for River Rch & Prof#=LONG BRANCH,Reach-1,7
Up Type=0
Dn Type=3
Dn Slope=0.005

--- LONG BRANCH.g01 (geometry) ---

Geom Title=Existing Conditions

River Reach=LONG BRANCH,Reach-1
Reach XY= 30
      3481089.00     10426165.05      3481323.60     10425616.40
      3481894.96     10425174.66      3483461.63     10425083.10
      3483972.36     10425341.95      3484602.76     10425077.03
      3485083.67     10426149.55      3485312.52     10425693.43
      3485672.30     10425951.49      3485850.78     10425724.18
      3486402.62     10426500.99      3486825.05     10426357.04
      3486978.17     10426083.71      3487618.68     10426266.07
      3487535.34     10426128.22      3487799.58     10425931.35
      3488490.68     10426412.74      3489176.35     10426304.93
      3489209.95     10426008.31      3489741.72     10425812.22
      3489859.95     10426139.82      3490149.01     10426010.40
      3490653.70     10426428.11      3491688.42     10426318.73
      3492559.16     10425963.25      3492785.17     10426376.96
      3492500.15     10426405.34      3492502.03     10426705.45
      3493090.67     10427339.49      3493497.03     10427271.24

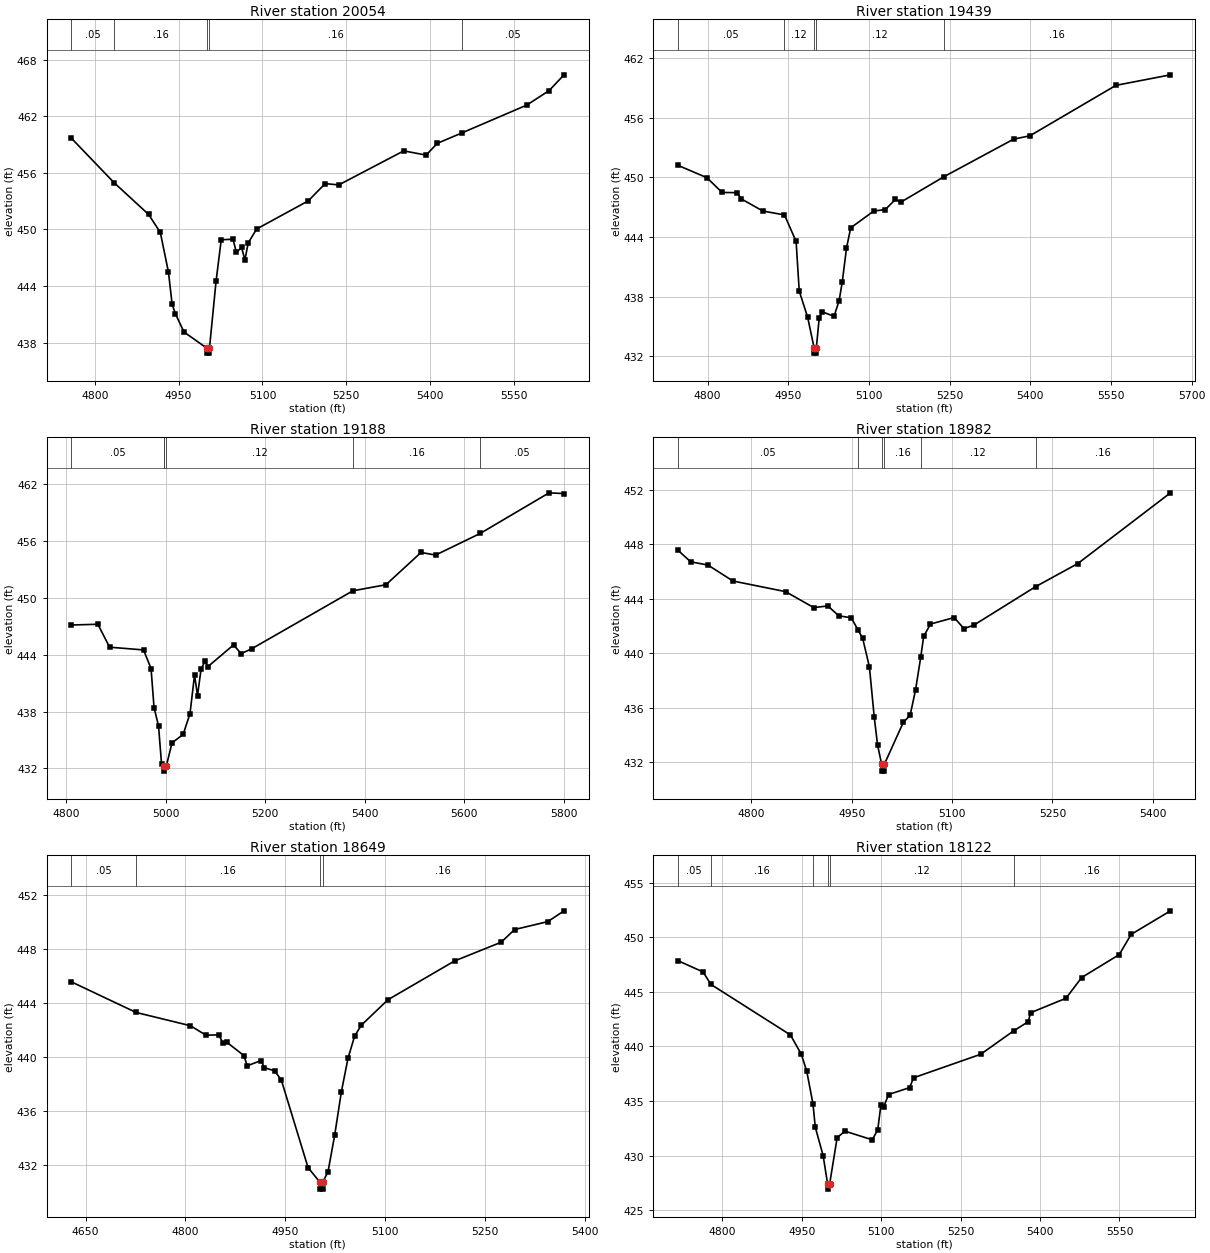
Type RM Length L Ch R = 1,20054,615,615,615
BEGIN DESCRIPTION:
LONG BRANCH 5 0
END DESCRIPTION:
XS GIS Cut Line= 4
      3481398.31     10426094.52      3481094.51     10425899.22
      3480894.86     10425877.52      3480575.45     10425876.18
#Sta/Elev= 30
  4758.1  459.67  4834.4  454.96  4896.2  451.59  4917.3  449.68  4931.9  445.46
  4938.5  442.04  4944.4  441.05  4959.6  439.12  5001.2  437.38  5001.5  436.88
  5005.0  436.88  5005.2  437.38  5017.1  444.53  5026.3  448.90  5047.4  448.95
  5053.4  447.55  5062.6  448.09  5068.6  446.76  5074.6  448.57  5089.7  450.04
  5182.0  453.02  5212.2  454.85  5236.5  454.71  5352.8  458.32  5392.8  457.87
  5412.8  459.12  5456.7  460.22  5572.8  463.17  5612.8  464.71  5639.5  466.38
#Mann=5,-1,0
  4758.1    0.05       0  4834.4    0.16       0  5001.2    0.07       0
  5005.2    0.16       0  5456.7    0.05       0
Bank Sta=5001.2,5005.2
Exp/Cntr=0.3,0.1

Type RM Length L Ch R = 1,19439,251,251,251
BEGIN DESCRIPTION:
LONG BRANCH 31 0
END DESCRIPTION:
XS GIS Cut Line= 4
      3481681.50     10425688.80      3481574.09     10425569.46
      3481374.23     10425451.63      3480850.70     10425462.07
#Sta/Elev= 30
  4744.4  451.23  4798.5  449.98  4826.9  448.49  4855.3  448.47  4862.0  447.86
  4902.7  446.62  4942.9  446.23  4964.5  443.56  4970.3  438.58  4986.0  435.92
  4998.1  432.82  4998.4  432.32  5001.9  432.32  5002.1  432.82  5007.4  435.84
  5013.2  436.48  5035.0  436.02  5044.5  437.60  5050.4  439.51  5058.2  442.89
  5066.0  444.93  5108.9  446.62  5130.4  446.77  5149.1  447.79  5159.1  447.51
  5239.5  450.08  5369.1  453.86  5399.1  454.19  5559.2  459.27  5660.6  460.33
#Mann=5,-1,0
  4744.4    0.05       0  4942.9    0.12       0  4998.1    0.07       0
  5002.1    0.12       0  5239.5    0.16       0
Bank Sta=4998.1,5002.1
Exp/Cntr=0.3,0.1

Type RM Length L Ch R = 1,19188,206,206,206
BEGIN DESCRIPTION:
LONG BRANCH 4 0
END DESCRIPTION:
XS GIS Cut Line= 5
      3481696.41     10425539.66      3481647.17     10425424.78
      3481480.13     10425171.23      3481450.30     10424989.27
      3481153.51     10424758.10
#Sta/Elev= 30
  4810.8  447.13  4864.1  447.21  4887.7  444.79  4955.8  444.50  4970.9  442.54
  4976.9  438.42  4985.9  436.49  4991.9  432.50  4996.3  432.27  4997.4  432.21
  4997.7  431.71  5001.4  432.21  5013.0  434.70  5035.3  435.58  5049.1  437.78
  5058.2  441.86  5064.2  439.69  5071.3  442.48  5079.3  443.31  5085.3  442.75
  5136.5  445.03  5151.6  444.11  5172.6  444.61  5376.1  450.74  5442.4  451.38
  5513.0  454.79  5542.0  454.51  5631.6  456.79  5770.0  461.08  5800.0  461.00
#Mann=6,-1,0
  4810.8    0.05       0  4996.3    0.12       0  4997.4    0.07       0
  5001.4    0.12       0  5376.1    0.16       0  5631.6    0.05       0
Bank Sta=4997.4,5001.4
Exp/Cntr=0.3,0.1

Type RM Length L Ch R = 1,18982,333,333,333
BEGIN DESCRIPTION:
LONG BRANCH 30 0
END DESCRIPTION:
XS GIS Cut Line= 4
      3481700.87     10425554.53      3481782.90     10425308.45
      3481759.03     10425160.79      3481559.19     10424901.29
#Sta/Elev= 30
  4690.0  447.56  4709.3  446.70  4735.2  446.46  4772.5  445.29  4851.2  444.51
  4893.3  443.34  4914.4  443.46  4930.6  442.74  4949.4  442.59  4959.8  441.67
  4966.4  441.09  4976.5  438.99  4983.7  435.31  4988.7  433.26  4994.8  431.84
  4995.1  431.34  4998.6  431.34  4998.8  431.84  5027.2  434.92  5037.3  435.43
  5045.4  437.28  5053.2  439.70  5057.6  441.22  5067.7  442.13  5103.2  442.61
  5117.7  441.80  5132.2  442.04  5225.1  444.88  5288.0  446.57  5426.5  451.76
#Mann=6,-1,0
  4690.0    0.05       0  4959.8    0.16       0  4994.8    0.07       0
  4998.8    0.16       0  5053.2    0.12       0  5225.1    0.16       0
Bank Sta=4994.8,4998.8
Exp/Cntr=0.3,0.1

Type RM Length L Ch R = 1,18649,527,527,527
BEGIN DESCRIPTION:
LONG BRANCH 3 0
END DESCRIPTION:
XS GIS Cut Line= 3
      3481961.89     10425530.64      3482058.82     10425251.77
      3482058.82     10424807.30
#Sta/Elev= 30
  4628.6  445.58  4725.6  443.31  4807.5  442.32  4830.6  441.62  4849.9  441.64
  4856.4  441.03  4861.7  441.11  4887.5  440.11  4892.8  439.35  4913.3  439.73
  4918.6  439.20  4934.0  438.97  4944.0  438.27  4984.0  431.79  5002.0  430.69
  5002.2  430.19  5005.7  430.19  5006.0  430.69  5014.0  431.49  5024.0  434.20
  5034.0  437.41  5044.0  439.91  5054.0  441.56  5064.0  442.36  5104.0  444.25
  5204.0  447.13  5274.0  448.52  5294.0  449.46  5344.0  450.05  5368.3  450.85
#Mann=4,-1,0
  4628.6    0.05       0  4725.6    0.16       0  5002.0    0.07       0
  5006.0    0.16       0
Bank Sta=5002,5006
Exp/Cntr=0.3,0.1

Type RM Length L Ch R = 1,18122,560,560,560
BEGIN DESCRIPTION:
LONG BRANCH 29 0
END DESCRIPTION:
XS GIS Cut Line= 4
      3482630.06     10425538.15      3482528.64     10425130.96
      3482421.25     10425013.14      3482364.66     10424666.17
#Sta/Elev= 30
  4715.7  447.86  4763.6  446.82  4778.3  445.68  4928.5  441.05  4949.1  439.28
  4959.4  437.71  4971.1  434.74  4975.5  432.59  4990.3  429.99  4998.7  427.42
  4998.9  426.92  5002.7  427.42  5016.8  431.64  5031.6  432.23  5083.1  431.44
  5093.4  432.35  5099.4  434.62  5104.6  434.46  5114.0  435.59  5153.6  436.22
  5161.0  437.12  5288.0  439.28  5350.1  441.42  5377.3  442.25  5382.5  443.09
  5449.0  444.41  5478.6  446.31  5549.6  448.41  5572.0  450.26  5646.3  452.42
#Mann=6,-1,0
  4715.7    0.05       0  4778.3    0.16       0  4971.1    0.12       0
  4998.7    0.07       0  5002.7    0.12       0  5350.1    0.16       0
Bank Sta=4998.7,5002.7
Exp/Cntr=0.3,0.1

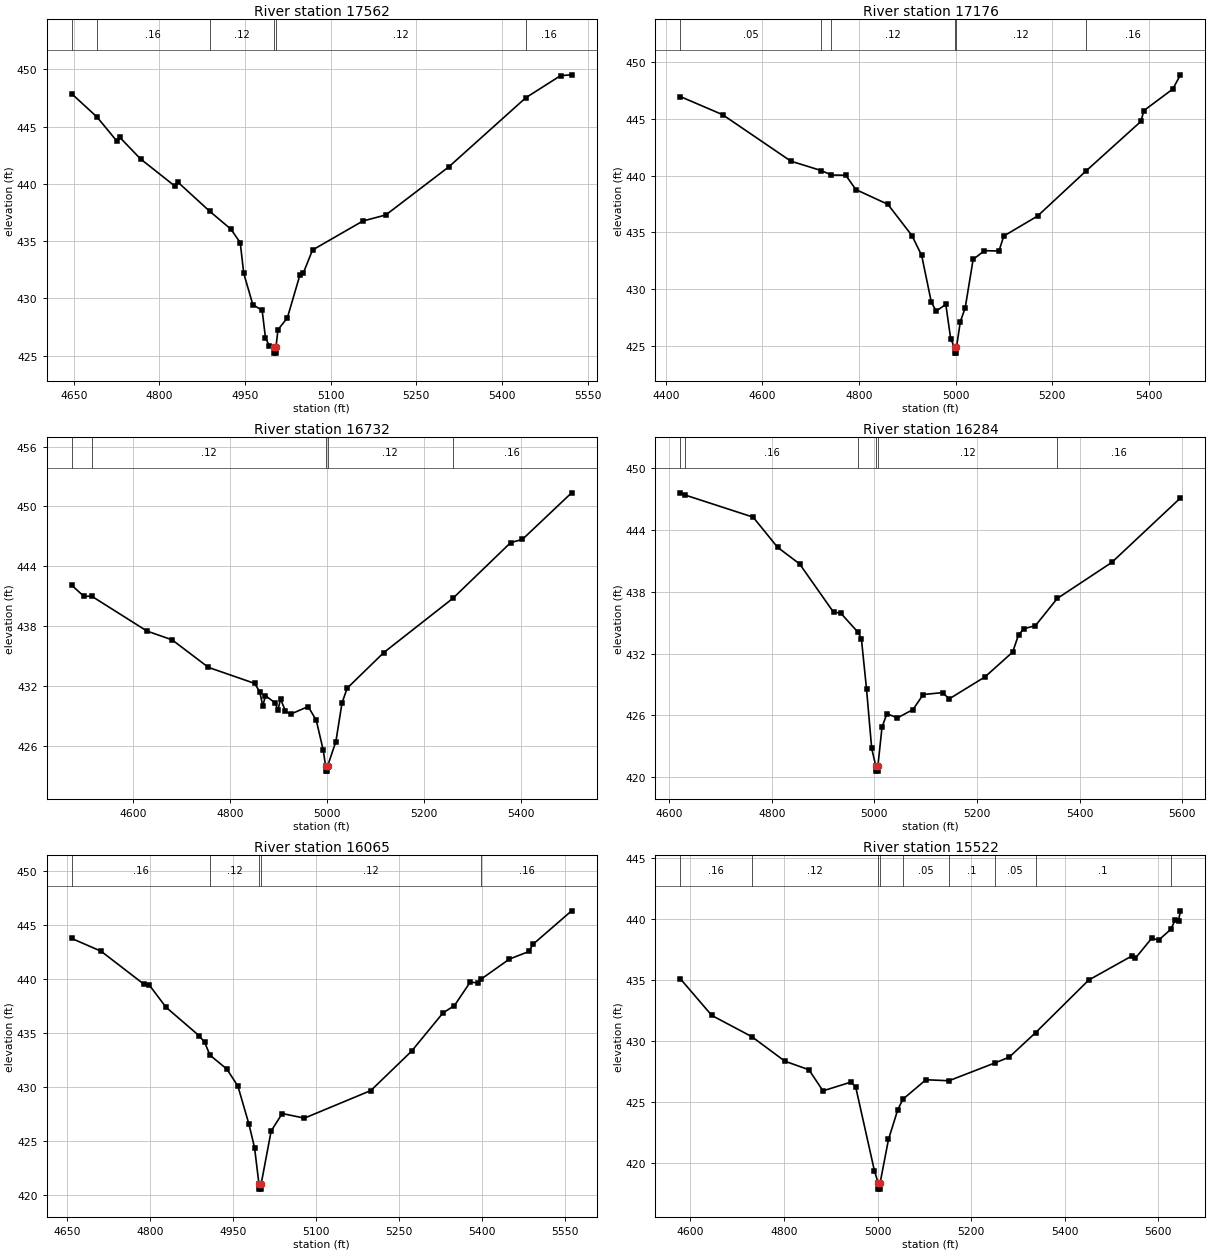
Type RM Length L Ch R = 1,17562,386,386,386
BEGIN DESCRIPTION:
LONG BRANCH 28 0
END DESCRIPTION:
XS GIS Cut Line= 4
      3482780.69     10425479.98      3482825.44     10425257.74
      3482935.81     10425047.44      3482968.62     10424637.26
#Sta/Elev= 30
  4646.4  447.88  4690.9  445.84  4725.4  443.75  4730.5  444.08  4767.1  442.18
  4827.0  439.82  4832.1  440.17  4888.0  437.62  4925.3  436.05  4941.7  434.87
  4947.8  432.19  4963.7  429.46  4980.1  428.95  4985.8  426.58  4992.9  425.82
  5000.2  425.72  5000.4  425.22  5003.9  425.22  5004.2  425.72  5007.8  427.27
  5024.2  428.30  5046.3  432.06  5051.9  432.18  5068.3  434.23  5156.5  436.76
  5196.7  437.29  5307.0  441.49  5441.9  447.53  5502.8  449.46  5522.1  449.53
#Mann=6,-1,0
  4646.4    0.05       0  4690.9    0.16       0  4888.0    0.12       0
  5000.2    0.07       0  5004.2    0.12       0  5441.9    0.16       0
Bank Sta=5000.2,5004.2
Exp/Cntr=0.3,0.1

Type RM Length L Ch R = 1,17176,444,444,444
BEGIN DESCRIPTION:
LONG BRANCH 26 0
END DESCRIPTION:
XS GIS Cut Line= 3
      3482895.57     10425567.94      3483140.14     10425293.53
      3483159.51     10424625.99
#Sta/Elev= 30
  4430.3  446.95  4517.6  445.36  4658.9  441.27  4722.0  440.44  4742.9  440.05
  4772.6  440.03  4793.5  438.77  4859.8  437.47  4909.8  434.71  4929.8  432.97
  4949.8  428.86  4959.8  428.07  4979.8  428.66  4989.9  425.64  4997.9  424.87
  4998.1  424.37  5001.6  424.37  5001.9  424.87  5009.9  427.15  5019.9  428.34
  5036.4  432.62  5059.9  433.39  5089.9  433.36  5099.9  434.68  5169.9  436.44
  5269.8  440.39  5383.9  444.77  5390.0  445.72  5450.0  447.62  5465.7  448.87
#Mann=6,-1,0
  4430.3    0.05       0  4722.0    0.16       0  4742.9    0.12       0
  4997.9    0.07       0  5001.9    0.12       0  5269.8    0.16       0
Bank Sta=4997.9,5001.9
Exp/Cntr=0.3,0.1

Type RM Length L Ch R = 1,16732,448,448,448
BEGIN DESCRIPTION:
LONG BRANCH 27 0
END DESCRIPTION:
XS GIS Cut Line= 3
      3483387.72     10425627.64      3483602.50     10425008.66
      3483650.23     10424637.30
#Sta/Elev= 30
  4473.8  442.10  4499.2  440.98  4514.7  441.01  4629.0  437.50  4680.7  436.62
  4755.4  433.86  4850.6  432.25  4861.2  431.41  4867.5  429.97  4872.8  431.02
  4893.0  430.29  4898.6  429.54  4903.9  430.70  4914.1  429.47  4924.5  429.16
  4960.9  429.93  4977.6  428.54  4992.0  425.53  4996.8  423.95  4997.1  423.45
  5000.6  423.45  5000.8  423.95  5017.9  426.41  5030.6  430.30  5041.2  431.77
  5116.5  435.34  5258.8  440.78  5378.0  446.38  5401.9  446.69  5503.4  451.37
#Mann=5,-1,0
  4473.8    0.16       0  4514.7    0.12       0  4996.8    0.07       0
  5000.8    0.12       0  5258.8    0.16       0
Bank Sta=4996.8,5000.8
Exp/Cntr=0.3,0.1

Type RM Length L Ch R = 1,16284,219,219,219
BEGIN DESCRIPTION:
Mapping XS a6985db4
END DESCRIPTION:
XS GIS Cut Line= 3
      3483899.30     10425712.64      3483955.98     10425105.61
      3483799.55     10424776.35
#Sta/Elev= 30
  4622.1  447.60  4631.5  447.38  4763.7  445.24  4811.2  442.32  4854.1  440.71
  4920.3  436.02  4934.4  435.93  4967.9  434.08  4974.6  433.46  4984.7  428.53
  4994.7  422.80  5002.7  421.10  5003.0  420.60  5006.6  420.60  5006.8  421.10
  5014.8  424.86  5024.3  426.17  5044.9  425.77  5075.1  426.57  5095.1  428.03
  5133.3  428.22  5145.4  427.60  5215.7  429.75  5269.4  432.15  5280.9  433.83
  5291.5  434.42  5313.7  434.71  5356.3  437.35  5462.6  440.85  5596.3  447.10
#Mann=6,-1,0
  4622.1    0.05       0  4631.5    0.16       0  4967.9    0.12       0
  5002.7    0.07       0  5006.8    0.12       0  5356.3    0.16       0
Bank Sta=5002.7,5006.8
Exp/Cntr=0.3,0.1

Type RM Length L Ch R = 1,16065,543,543,543
BEGIN DESCRIPTION:
LONG BRANCH 25 1
END DESCRIPTION:
XS GIS Cut Line= 3
      3484109.60     10425591.80      3484081.26     10425016.12
      3483862.05     10424773.04
#Sta/Elev= 30
  4658.7  443.77  4711.7  442.59  4789.0  439.54  4799.0  439.45  4829.1  437.40
  4889.1  434.75  4899.1  434.14  4908.7  432.95  4939.2  431.66  4959.2  430.08
  4979.2  426.54  4989.3  424.37  4997.2  421.03  4997.5  420.53  5001.1  420.53
  5001.3  421.03  5019.3  425.92  5039.3  427.54  5079.4  427.11  5199.5  429.67
  5273.0  433.31  5329.8  436.86  5350.7  437.55  5379.1  439.72  5393.3  439.65
  5398.9  440.00  5450.1  441.86  5485.2  442.56  5492.7  443.23  5562.4  446.33
#Mann=5,-1,0
  4658.7    0.16       0  4908.7    0.12       0  4997.2    0.07       0
  5001.3    0.12       0  5398.9    0.16       0
Bank Sta=4997.2,5001.3
Exp/Cntr=0.3,0.1

Type RM Length L Ch R = 1,15522,374,374,374
BEGIN DESCRIPTION:
LONG BRANCH 25 0
END DESCRIPTION:
XS GIS Cut Line= 4
      3484295.38     10425498.57      3484475.07     10425357.94
      3484467.26     10424900.91      3484216.53     10424611.22
#Sta/Elev= 30
  4578.9  435.09  4645.8  432.10  4731.4  430.36  4802.0  428.35  4853.4  427.65
  4883.4  425.92  4943.4  426.64  4953.4  426.23  4993.4  419.37  5001.4  418.37
  5001.6  417.87  5005.2  417.87  5005.5  418.37  5023.4  421.94  5043.4  424.39
  5054.4  425.24  5103.4  426.83  5152.7  426.75  5250.9  428.21  5281.4  428.68
  5337.8  430.69  5451.4  435.00  5543.5  436.97  5551.1  436.79  5586.3  438.44
  5600.5  438.26  5626.6  439.15  5635.6  439.88  5643.3  439.86  5647.3  440.67
#Mann=9,-1,0
  4578.9    0.16       0  4731.4    0.12       0  5001.4    0.07       0
  5005.5    0.12       0  5054.4    0.05       0  5152.7     0.1       0
  5250.9    0.05       0  5337.8     0.1       0  5626.6    0.16       0
Bank Sta=5001.4,5005.5
Exp/Cntr=0.3,0.1

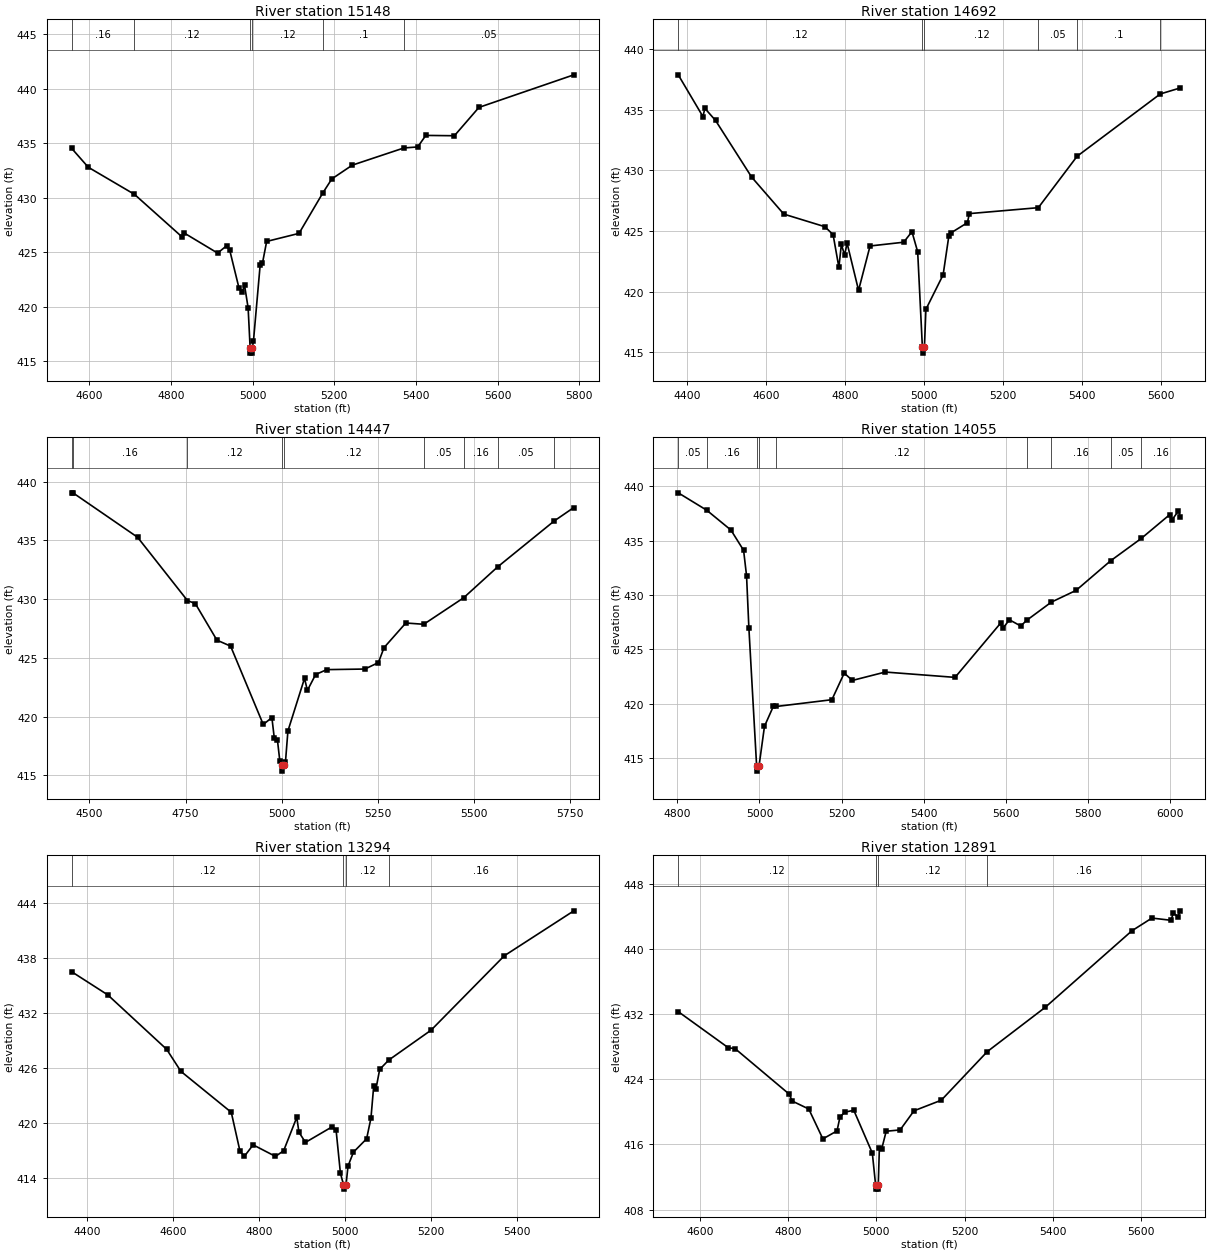
Type RM Length L Ch R = 1,15148,456,456,456
BEGIN DESCRIPTION:
LONG BRANCH 24 0
END DESCRIPTION:
XS GIS Cut Line= 4
      3484312.32     10425519.39      3484486.79     10425364.45
      3484838.35     10425176.95      3484861.79     10424579.29
#Sta/Elev= 30
  4556.9  434.52  4597.3  432.80  4710.5  430.31  4826.3  426.43  4832.0  426.77
  4914.2  424.92  4936.1  425.59  4943.6  425.22  4966.3  421.75  4974.4  421.34
  4980.1  421.97  4988.9  419.90  4993.8  416.24  4994.2  415.74  4998.5  415.74
  4998.9  416.24  5002.0  416.86  5018.3  423.79  5024.0  423.99  5034.3  425.99
  5113.6  426.73  5172.2  430.46  5194.0  431.73  5244.0  432.99  5370.6  434.57
  5404.2  434.66  5424.2  435.72  5494.2  435.69  5554.3  438.29  5786.8  441.28
#Mann=6,-1,0
  4556.9    0.16       0  4710.5    0.12       0  4993.8    0.07       0
  4998.9    0.12       0  5172.2     0.1       0  5370.6    0.05       0
Bank Sta=4993.8,4998.9
Exp/Cntr=0.3,0.1

Type RM Length L Ch R = 1,14692,245,245,245
BEGIN DESCRIPTION:
LONG BRANCH 23 0
END DESCRIPTION:
XS GIS Cut Line= 4
      3484299.28     10425838.41      3484587.05     10425786.33
      3484904.76     10425542.84      3484937.31     10424965.98
#Sta/Elev= 30
  4377.5  437.88  4439.9  434.44  4445.0  435.11  4471.8  434.12  4563.3  429.44
  4644.6  426.39  4748.6  425.35  4769.4  424.69  4784.0  422.00  4790.3  423.89
  4798.5  423.01  4804.8  423.99  4833.8  420.10  4862.9  423.76  4948.0  424.07
  4968.9  424.94  4983.4  423.28  4995.3  415.42  4995.7  414.92  5000.5  415.42
  5004.2  418.53  5047.8  421.38  5062.3  424.59  5067.1  424.83  5109.2  425.68
  5114.2  426.43  5288.7  426.92  5386.8  431.16  5597.2  436.30  5648.0  436.80
#Mann=6,-1,0
  4377.5    0.12       0  4995.3    0.07       0  5000.5    0.12       0
  5288.7    0.05       0  5386.8     0.1       0  5597.2    0.05       0
Bank Sta=4995.3,5000.5
Exp/Cntr=0.3,0.1

Type RM Length L Ch R = 1,14447,392,392,392
BEGIN DESCRIPTION:
LONG BRANCH 22 0
END DESCRIPTION:
XS GIS Cut Line= 4
      3484837.05     10426312.40      3484816.21     10425934.77
      3485109.18     10425567.58      3485317.31     10425160.44
#Sta/Elev= 30
  4454.2  439.05  4457.3  439.05  4625.2  435.27  4754.9  429.88  4775.4  429.62
  4831.5  426.51  4867.1  426.00  4952.0  419.33  4974.4  419.92  4980.8  418.14
  4988.8  418.02  4995.2  416.18  4999.7  415.86  5000.2  415.36  5005.7  415.86
  5009.7  416.13  5016.1  418.78  5059.3  423.26  5066.7  422.23  5088.1  423.58
  5116.9  424.00  5216.2  424.05  5251.4  424.60  5265.9  425.87  5322.6  427.97
  5369.2  427.86  5473.1  430.12  5561.1  432.74  5708.6  436.66  5759.4  437.80
#Mann=9,-1,0
  4454.2    0.05       0  4457.3    0.16       0  4754.9    0.12       0
  4999.7    0.07       0  5005.7    0.12       0  5369.2    0.05       0
  5473.1    0.16       0  5561.1    0.05       0  5708.6    0.16       0
Bank Sta=4999.7,5005.7
Exp/Cntr=0.3,0.1

Type RM Length L Ch R = 1,14055,761,761,761
BEGIN DESCRIPTION:
LONG BRANCH 21 0
END DESCRIPTION:
XS GIS Cut Line= 4
      3484986.81     10426321.45      3485122.20     10426072.79
      3485118.30     10425584.50      3485337.71     10425189.83
#Sta/Elev= 30
  4802.2  439.38  4871.7  437.78  4930.6  435.96  4961.4  434.10  4968.6  431.77
  4974.3  426.96  4993.1  414.32  4993.6  413.82  4999.1  414.32  5012.3  417.94
  5034.1  419.79  5041.5  419.76  5176.5  420.38  5206.5  422.82  5226.5  422.15
  5306.5  422.92  5476.5  422.43  5587.2  427.40  5592.9  426.93  5608.9  427.72
  5636.4  427.15  5651.0  427.67  5711.0  429.34  5771.3  430.42  5855.5  433.14
  5930.1  435.19  5998.9  437.36  6004.7  436.88  6020.7  437.72  6025.2  437.18
#Mann=9,-1,0
  4802.2    0.05       0  4871.7    0.16       0  4993.1    0.07       0
  4999.1    0.16       0  5041.5    0.12       0  5651.0    0.05       0
  5711.0    0.16       0  5855.5    0.05       0  5930.1    0.16       0
Bank Sta=4993.1,4999.1
Exp/Cntr=0.3,0.1

Type RM Length L Ch R = 1,13294,403,403,403
BEGIN DESCRIPTION:
LONG BRANCH 20 0
END DESCRIPTION:
XS GIS Cut Line= 4
      3485313.61     10426359.25      3485394.34     10426092.32
      3485486.79     10425561.07      3485721.17     10425301.95
#Sta/Elev= 30
  4364.3  436.51  4448.0  433.99  4585.0  428.05  4618.0  425.65  4735.2  421.18
  4755.5  416.93  4765.7  416.38  4786.0  417.63  4838.0  416.37  4857.0  416.99
  4887.5  420.63  4892.6  419.00  4907.8  417.90  4968.7  419.57  4978.8  419.30
  4989.0  414.54  4996.1  413.30  4996.6  412.80  5002.1  413.30  5006.7  415.32
  5019.4  416.84  5049.9  418.29  5060.0  420.54  5066.4  424.05  5071.4  423.68
  5080.3  425.86  5101.4  426.88  5199.8  430.14  5370.2  438.26  5531.8  443.16
#Mann=4,-1,0
  4364.3    0.12       0  4996.1    0.07       0  5002.1    0.12       0
  5101.4    0.16       0
Bank Sta=4996.1,5002.1
Exp/Cntr=0.3,0.1

Type RM Length L Ch R = 1,12891,838,838,838
BEGIN DESCRIPTION:
LONG BRANCH 19 0
END DESCRIPTION:
XS GIS Cut Line= 5
      3485422.99     10426333.20      3485534.96     10426180.86
      3485652.15     10425817.58      3485626.11     10425589.71
      3485797.17     10425296.84
#Sta/Elev= 30
  4550.4  432.31  4664.4  427.86  4679.1  427.78  4801.7  422.20  4809.3  421.32
  4846.6  420.35  4878.6  416.68  4910.7  417.66  4917.3  419.34  4927.8  419.96
  4948.8  420.19  4990.8  414.94  4998.3  411.01  4998.8  410.51  5003.8  410.51
  5004.3  411.01  5006.8  415.53  5012.1  415.44  5022.3  417.62  5053.9  417.78
  5085.4  420.13  5147.3  421.43  5251.7  427.40  5383.0  432.83  5579.9  442.24
  5625.3  443.80  5668.3  443.53  5674.0  444.40  5684.0  443.99  5689.7  444.69
#Mann=4,-1,0
  4550.4    0.12       0  4998.3    0.07       0  5004.3    0.12       0
  5251.7    0.16       0
Bank Sta=4998.3,5004.3
Exp/Cntr=0.3,0.1

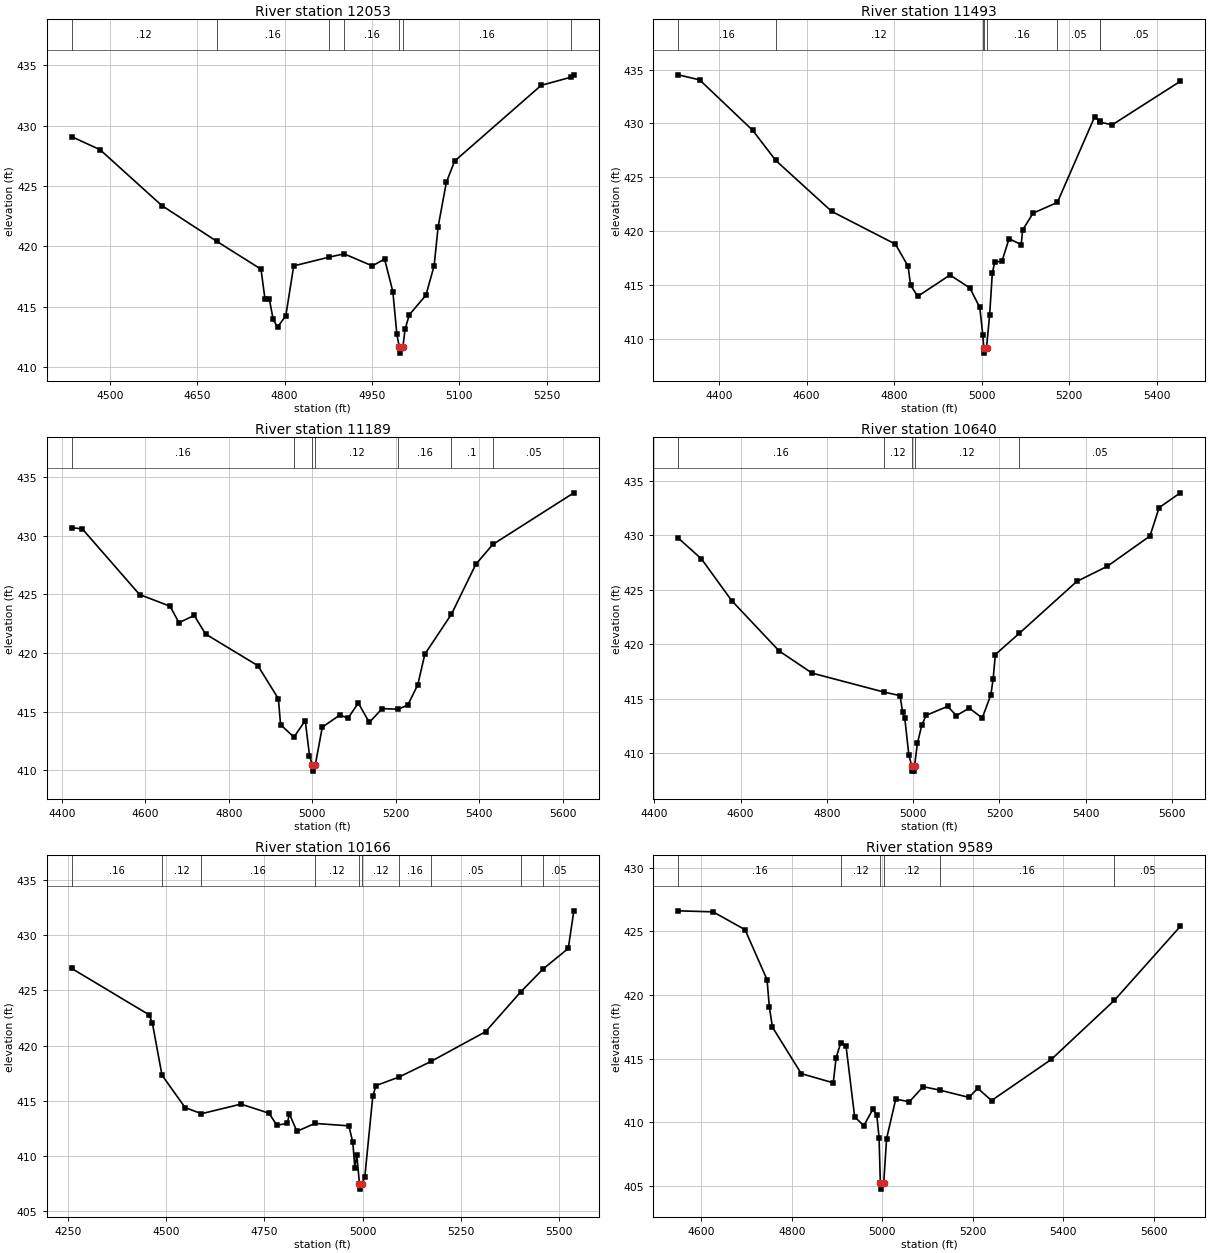
Type RM Length L Ch R = 1,12053,560,560,560
BEGIN DESCRIPTION:
LONG BRANCH 18 0
END DESCRIPTION:
XS GIS Cut Line= 2
      3485532.46     10426350.60      3486165.06     10425765.66
#Sta/Elev= 30
  4434.9  429.08  4483.5  428.00  4589.5  423.37  4684.0  420.40  4759.6  418.10
  4766.4  415.65  4773.8  415.64  4780.6  413.93  4788.0  413.29  4802.2  414.24
  4815.8  418.37  4876.7  419.10  4902.3  419.37  4950.7  418.37  4971.7  418.94
  4985.9  416.24  4992.8  412.70  4997.0  411.64  4997.5  411.14  5003.1  411.64
  5006.9  413.13  5014.2  414.32  5042.6  415.94  5056.7  418.37  5063.6  421.61
  5077.7  425.30  5091.9  427.06  5240.5  433.34  5291.3  434.01  5296.5  434.21
#Mann=7,-1,0
  4434.9    0.12       0  4684.0    0.16       0  4876.7    0.12       0
  4902.3    0.16       0  4997.0    0.07       0  5003.1    0.16       0
  5291.3     0.1       0
Bank Sta=4997,5003.1
Exp/Cntr=0.3,0.1

Type RM Length L Ch R = 1,11493,304,304,304
BEGIN DESCRIPTION:
LONG BRANCH 17 0
END DESCRIPTION:
XS GIS Cut Line= 4
      3485817.24     10426815.22      3486159.22     10426566.06
      3486330.22     10426243.59      3486364.42     10425886.95
#Sta/Elev= 30
  4307.0  434.51  4355.9  434.04  4477.2  429.35  4529.5  426.57  4657.2  421.84
  4803.0  418.79  4831.8  416.74  4837.5  414.99  4853.8  413.95  4927.5  415.93
  4972.8  414.73  4995.5  412.92  5002.3  410.40  5004.7  409.18  5005.2  408.68
  5010.9  409.18  5018.1  412.26  5024.1  416.09  5029.8  417.15  5046.1  417.20
  5062.4  419.30  5090.1  418.75  5093.4  420.11  5117.2  421.67  5172.7  422.67
  5257.8  430.61  5270.4  430.20  5270.9  430.11  5298.0  429.87  5453.4  433.91
#Mann=8,-1,0
  4307.0    0.16       0  4529.5    0.12       0  5002.3    0.16       0
  5004.7    0.07       0  5010.9    0.16       0  5172.7    0.05       0
  5270.4     0.1       0  5270.9    0.05       0
Bank Sta=5004.7,5010.9
Exp/Cntr=0.3,0.1

Type RM Length L Ch R = 1,11189,549,549,549
BEGIN DESCRIPTION:
LONG BRANCH 16 0
END DESCRIPTION:
XS GIS Cut Line= 4
      3486713.76     10427013.11      3486528.10     10426715.08
      3486403.51     10426140.99      3486418.17     10425877.18
#Sta/Elev= 30
  4424.0  430.68  4449.3  430.57  4586.3  424.98  4659.5  423.98  4680.7  422.58
  4717.3  423.19  4744.5  421.61  4869.9  418.91  4919.0  416.09  4924.2  413.88
  4956.3  412.82  4983.3  414.23  4993.5  411.25  5000.4  410.42  5000.9  409.92
  5007.2  410.42  5024.2  413.67  5066.5  414.71  5085.6  414.43  5110.5  415.72
  5136.8  414.07  5167.5  415.25  5206.3  415.20  5228.9  415.55  5252.9  417.28
  5269.8  419.89  5333.7  423.31  5392.0  427.56  5432.7  429.25  5626.8  433.65
#Mann=7,-1,0
  4424.0    0.16       0  4956.3    0.12       0  5000.4    0.07       0
  5007.2    0.12       0  5206.3    0.16       0  5333.7     0.1       0
  5432.7    0.05       0
Bank Sta=5000.4,5007.2
Exp/Cntr=0.3,0.1

Type RM Length L Ch R = 1,10640,474,474,474
BEGIN DESCRIPTION:
LONG BRANCH 15 0
END DESCRIPTION:
XS GIS Cut Line= 3
      3486791.94     10426925.19      3486755.30     10426158.09
      3486476.99     10425877.34
#Sta/Elev= 30
  4455.7  429.73  4509.3  427.83  4579.4  424.00  4689.5  419.38  4765.6  417.35
  4931.4  415.62  4969.8  415.28  4975.5  413.75  4980.5  413.26  4989.9  409.87
  4996.5  408.86  4997.0  408.36  5002.8  408.36  5003.3  408.86  5009.9  410.92
  5019.9  412.56  5029.9  413.47  5080.0  414.30  5100.0  413.45  5130.0  414.14
  5160.1  413.23  5180.1  415.37  5185.4  416.84  5190.4  419.05  5246.3  421.01
  5379.0  425.75  5449.7  427.14  5548.7  429.92  5569.9  432.52  5619.0  433.88
#Mann=5,-1,0
  4455.7    0.16       0  4931.4    0.12       0  4996.5    0.07       0
  5003.3    0.12       0  5246.3    0.05       0
Bank Sta=4996.5,5003.3
Exp/Cntr=0.3,0.1

Type RM Length L Ch R = 1,10166,577,577,577
BEGIN DESCRIPTION:
LONG BRANCH 14 0
END DESCRIPTION:
XS GIS Cut Line= 3
      3487143.72     10426815.21      3486992.26     10425967.54
      3486616.62     10425789.48
#Sta/Elev= 30
  4259.9  426.99  4456.5  422.79  4464.8  422.06  4489.3  417.32  4548.0  414.38
  4589.7  413.82  4690.2  414.69  4761.3  413.87  4781.6  412.77  4808.1  412.95
  4813.2  413.81  4832.4  412.22  4878.1  412.94  4964.4  412.72  4974.6  411.24
  4979.7  408.93  4984.8  410.06  4991.5  407.48  4992.0  406.98  4998.3  407.48
  5005.1  408.08  5025.4  415.40  5033.5  416.37  5091.8  417.14  5173.4  418.56
  5312.3  421.26  5401.7  424.87  5458.6  426.95  5522.5  428.81  5536.7  432.22
#Mann=10,-1,0
  4259.9    0.16       0  4489.3    0.12       0  4589.7    0.16       0
  4878.1    0.12       0  4991.5    0.07       0  4998.3    0.12       0
  5091.8    0.16       0  5173.4    0.05       0  5401.7    0.16       0
  5458.6    0.05       0
Bank Sta=4991.5,4998.3
Exp/Cntr=0.3,0.1

Type RM Length L Ch R = 1,9589,700,700,700
BEGIN DESCRIPTION:
LONG BRANCH 13 0
END DESCRIPTION:
XS GIS Cut Line= 3
      3487485.32     10426677.89      3487435.33     10426327.90
      3487535.33     10425577.88
#Sta/Elev= 30
  4548.6  426.62  4625.6  426.54  4696.3  425.14  4745.0  421.21  4750.0  419.07
  4756.9  417.48  4820.7  413.83  4891.4  413.11  4897.7  415.09  4908.0  416.25
  4919.6  416.01  4938.7  410.44  4958.9  409.74  4979.1  411.04  4987.7  410.56
  4992.7  408.81  4995.5  405.26  4996.0  404.76  5003.0  405.26  5009.3  408.72
  5029.5  411.83  5059.8  411.62  5090.0  412.81  5127.7  412.53  5190.9  411.97
  5211.1  412.67  5241.4  411.72  5373.6  414.95  5513.0  419.59  5658.8  425.40
#Mann=6,-1,0
  4548.6    0.16       0  4908.0    0.12       0  4995.5    0.07       0
  5003.0    0.12       0  5127.7    0.16       0  5513.0    0.05       0
Bank Sta=4995.5,5003
Exp/Cntr=0.3,0.1

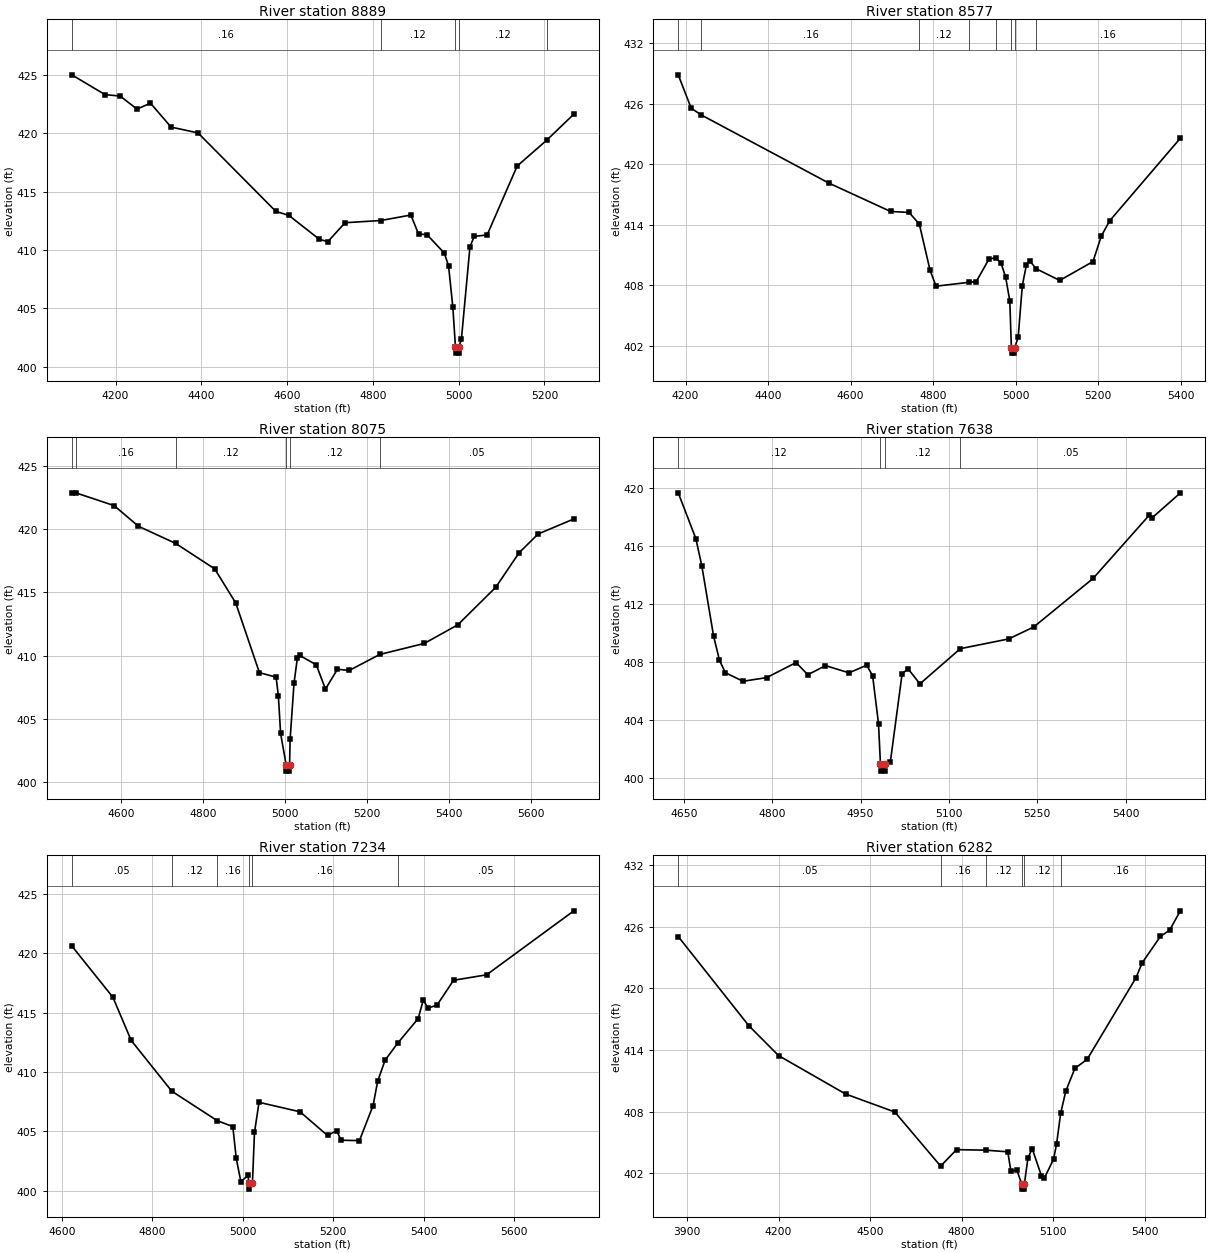
Type RM Length L Ch R = 1,8889,312,312,312
BEGIN DESCRIPTION:
LONG BRANCH 12 0
END DESCRIPTION:
XS GIS Cut Line= 3
      3487887.05     10426833.66      3487786.35     10426052.43
      3487785.86     10425669.43
#Sta/Elev= 30
  4097.8  425.03  4175.5  423.33  4210.7  423.21  4249.9  422.09  4281.3  422.60
  4329.4  420.55  4392.2  420.05  4573.7  413.32  4604.0  412.98  4674.6  410.94
  4694.7  410.72  4735.1  412.35  4818.6  412.54  4888.4  413.01  4906.3  411.39
  4926.3  411.32  4966.3  409.75  4976.3  408.67  4986.3  405.13  4992.5  401.67
  4993.0  401.17  4999.6  401.17  5000.1  401.67  5006.3  402.36  5026.3  410.30
  5036.3  411.18  5066.3  411.30  5136.3  417.21  5204.8  419.41  5268.5  421.66
#Mann=5,-1,0
  4097.8    0.16       0  4818.6    0.12       0  4992.5    0.07       0
  5000.1    0.12       0  5204.8     0.1       0
Bank Sta=4992.5,5000.1
Exp/Cntr=0.3,0.1

Type RM Length L Ch R = 1,8577,502,502,502
BEGIN DESCRIPTION:
LONG BRANCH TRIB 12 0
END DESCRIPTION:
XS GIS Cut Line= 3
      3487892.10     10426891.67      3488042.11     10426091.64
      3488092.11     10425691.62
#Sta/Elev= 30
  4182.1  428.85  4213.5  425.54  4238.4  424.86  4548.4  418.09  4696.8  415.30
  4741.7  415.20  4766.5  414.05  4792.6  409.46  4807.0  407.89  4886.4  408.27
  4904.5  408.34  4935.0  410.55  4951.3  410.73  4964.7  410.15  4975.7  408.81
  4985.9  406.41  4989.7  401.75  4990.2  401.25  4996.8  401.25  4997.3  401.75
  5006.1  402.80  5016.2  407.95  5026.3  410.03  5033.9  410.41  5050.1  409.61
  5106.9  408.46  5187.5  410.33  5207.7  412.86  5227.9  414.37  5399.2  422.56
#Mann=8,-1,0
  4182.1    0.05       0  4238.4    0.16       0  4766.5    0.12       0
  4886.4    0.16       0  4951.3    0.12       0  4989.7    0.07       0
  4997.3    0.12       0  5050.1    0.16       0
Bank Sta=4989.7,4997.3
Exp/Cntr=0.3,0.1

Type RM Length L Ch R = 1,8075,437,437,437
BEGIN DESCRIPTION:
LONG BRANCH TRIB 11 0
END DESCRIPTION:
XS GIS Cut Line= 3
      3488303.72     10426844.07      3488352.33     10426500.35
      3488713.45     10425698.24
#Sta/Elev= 30
  4478.7  422.89  4489.4  422.88  4582.1  421.88  4641.7  420.24  4732.2  418.89
  4827.9  416.87  4879.3  414.17  4937.2  408.65  4978.0  408.29  4983.5  406.81
  4989.0  403.83  5002.5  401.35  5003.0  400.85  5010.4  400.85  5010.9  401.35
  5012.2  403.37  5021.8  407.83  5029.8  409.77  5035.3  410.02  5076.1  409.27
  5098.6  407.35  5127.9  408.92  5156.5  408.82  5231.3  410.09  5339.9  410.96
  5422.1  412.44  5514.7  415.41  5571.9  418.15  5618.2  419.63  5705.5  420.82
#Mann=6,-1,0
  4478.7    0.05       0  4489.4    0.16       0  4732.2    0.12       0
  5002.5    0.07       0  5010.9    0.12       0  5231.3    0.05       0
Bank Sta=5002.5,5010.9
Exp/Cntr=0.3,0.1

Type RM Length L Ch R = 1,7638,404,404,404
BEGIN DESCRIPTION:
LONG BRANCH 9 0
END DESCRIPTION:
XS GIS Cut Line= 3
      3488742.11     10426641.59      3488742.11     10426291.64
      3488692.11     10425791.69
#Sta/Elev= 30
  4640.4  419.67  4670.4  416.50  4680.4  414.64  4700.4  409.79  4710.4  408.12
  4720.4  407.26  4750.4  406.67  4790.4  406.92  4840.4  407.96  4860.4  407.12
  4890.4  407.75  4930.4  407.25  4960.4  407.78  4970.4  407.05  4980.4  403.75
  4983.7  400.97  4984.2  400.47  4991.6  400.47  4992.1  400.97  5000.4  401.07
  5020.5  407.19  5030.6  407.53  5050.7  406.49  5119.4  408.92  5201.4  409.59
  5244.1  410.42  5344.6  413.76  5440.1  418.13  5445.1  417.95  5492.8  419.66
#Mann=4,-1,0
  4640.4    0.12       0  4983.7    0.07       0  4992.1    0.12       0
  5119.4    0.05       0
Bank Sta=4983.7,4992.1
Exp/Cntr=0.3,0.1

Type RM Length L Ch R = 1,7234,952,952,952
BEGIN DESCRIPTION:
LONG BRANCH 8 1
END DESCRIPTION:
XS GIS Cut Line= 3
      3489142.11     10426691.69      3489092.11     10426341.64
      3488992.11     10425591.68
#Sta/Elev= 30
  4622.1  420.60  4713.1  416.28  4753.5  412.65  4843.1  408.39  4943.5  405.91
  4978.2  405.41  4985.8  402.74  4995.9  400.79  5012.3  401.30  5013.0  400.65
  5013.5  400.15  5021.6  400.65  5026.1  404.92  5036.2  407.45  5127.0  406.65
  5187.6  404.66  5207.7  405.06  5217.8  404.26  5258.2  404.23  5288.4  407.18
  5298.5  409.22  5314.9  410.99  5342.5  412.41  5388.1  414.49  5399.4  416.06
  5409.5  415.37  5429.7  415.62  5466.3  417.71  5539.4  418.17  5732.3  423.55
#Mann=6,-1,0
  4622.1    0.05       0  4843.1    0.12       0  4943.5    0.16       0
  5013.0    0.07       0  5021.6    0.16       0  5342.5    0.05       0
Bank Sta=5013,5021.6
Exp/Cntr=0.3,0.1

Type RM Length L Ch R = 1,6282,536,536,536
BEGIN DESCRIPTION:
LONG BRANCH 8 0
END DESCRIPTION:
XS GIS Cut Line= 3
      3489352.32     10426885.78      3489657.88     10426309.38
      3489616.22     10425316.43
#Sta/Elev= 30
  3871.2  425.04  4102.2  416.38  4200.1  413.46  4420.0  409.72  4581.4  407.97
  4731.5  402.71  4783.6  404.31  4879.4  404.26  4951.7  404.10  4961.7  402.25
  4981.7  402.30  4997.4  400.97  4997.9  400.47  5005.6  400.47  5006.1  400.97
  5018.0  403.52  5031.8  404.40  5061.8  401.79  5071.8  401.55  5101.8  403.38
  5111.8  404.88  5125.1  407.84  5141.9  410.01  5171.9  412.22  5211.9  413.09
  5372.1  421.03  5392.1  422.47  5452.1  425.05  5482.2  425.65  5517.4  427.54
#Mann=6,-1,0
  3871.2    0.05       0  4731.5    0.16       0  4879.4    0.12       0
  4997.4    0.07       0  5006.1    0.12       0  5125.1    0.16       0
Bank Sta=4997.4,5006.1
Exp/Cntr=0.3,0.1