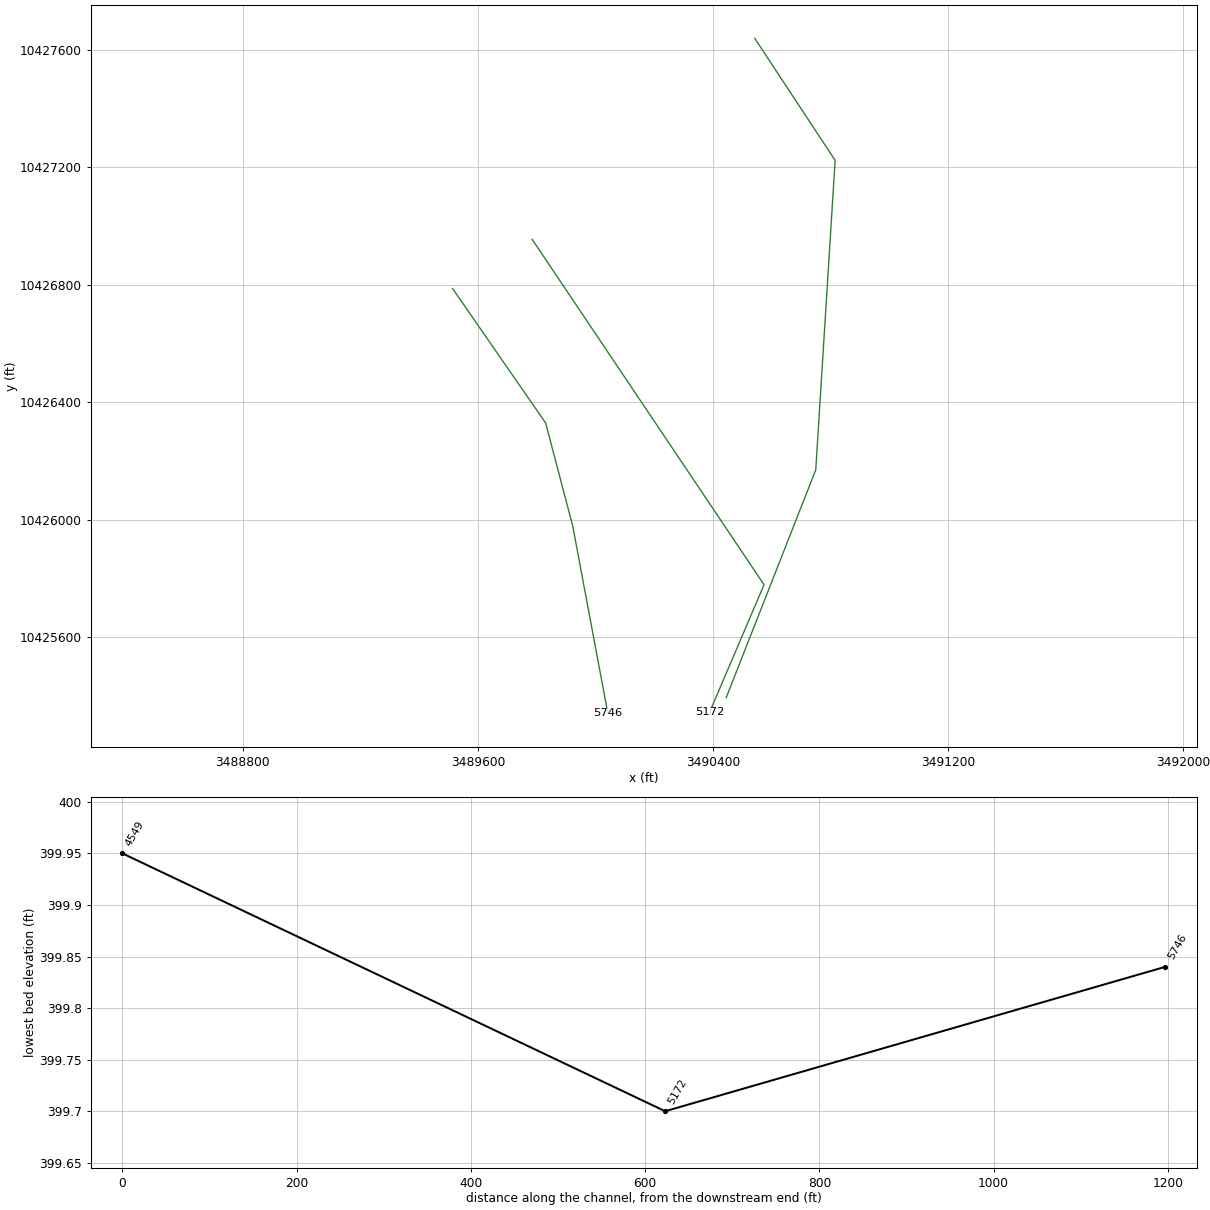
HEC-RAS study LONG BRANCH.prj: LONG BRANCH Base Level Engineering

--- LONG BRANCH.g01 (geometry) --- (continued)

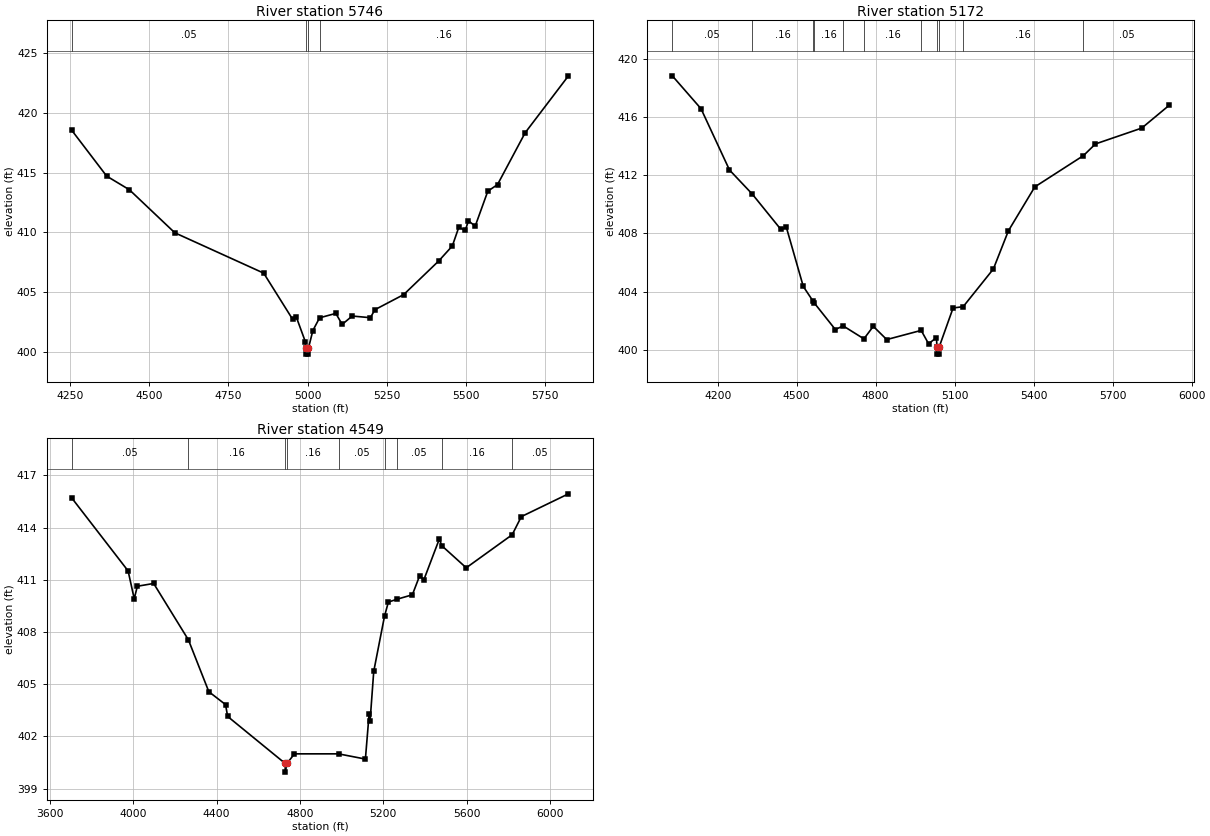
Type RM Length L Ch R = 1,5746,574,574,574
BEGIN DESCRIPTION:
LONG BRANCH 7 0
END DESCRIPTION:
XS GIS Cut Line= 4
      3489513.59     10426787.33      3489830.52     10426329.55
      3489922.70     10425978.47      3490042.11     10425341.63
#Sta/Elev= 30
  4255.2  418.55  4366.1  414.70  4437.8  413.56  4581.0  409.97  4861.5  406.60
  4952.7  402.75  4964.9  402.90  4993.1  400.86  4993.9  400.34  4994.4  399.84
  5002.2  399.84  5002.7  400.34  5016.6  401.81  5037.8  402.87  5089.0  403.24
  5109.0  402.32  5140.7  403.02  5198.0  402.88  5212.4  403.55  5303.2  404.81
  5413.4  407.61  5456.6  408.87  5477.0  410.43  5497.3  410.16  5507.5  410.97
  5528.7  410.52  5568.5  413.44  5599.1  413.99  5686.4  418.32  5822.9  423.07
#Mann=4,-1,0
  4255.2    0.05       0  4993.9    0.03       0  5002.7    0.05       0
  5037.8    0.16       0
Bank Sta=4993.9,5002.7
Exp/Cntr=0.3,0.1

Type RM Length L Ch R = 1,5172,623,623,623
BEGIN DESCRIPTION:
LONG BRANCH 6 0
END DESCRIPTION:
XS GIS Cut Line= 3
      3489784.53     10426954.52      3490573.62     10425779.43
      3490388.41     10425345.66
#Sta/Elev= 30
  4027.8  418.82  4136.8  416.56  4244.9  412.35  4331.2  410.70  4439.9  408.27
  4460.9  408.41  4525.1  404.35  4561.5  403.36  4567.0  403.21  4646.9  401.39
  4676.6  401.64  4755.4  400.75  4791.0  401.61  4842.0  400.70  4972.8  401.33
  5001.0  400.41  5031.0  400.84  5032.6  400.20  5033.1  399.70  5040.9  399.70
  5041.4  400.20  5094.0  402.87  5132.3  402.96  5247.0  405.55  5304.0  408.17
  5404.4  411.19  5589.1  413.34  5634.6  414.14  5810.5  415.23  5914.9  416.80
#Mann=11,-1,0
  4027.8    0.05       0  4331.2    0.16       0  4561.5    0.12       0
  4567.0    0.16       0  4676.6    0.12       0  4755.4    0.16       0
  4972.8    0.12       0  5032.6    0.07       0  5041.4    0.12       0
  5132.3    0.16       0  5589.1    0.05       0
Bank Sta=5032.6,5041.4
Exp/Cntr=0.3,0.1

Type RM Length L Ch R = 1,4549,0,0,0
BEGIN DESCRIPTION:
LONG BRANCH 1 0
END DESCRIPTION:
XS GIS Cut Line= 4
      3490541.88     10427638.50      3490815.47     10427223.22
      3490749.51     10426170.31      3490444.77     10425395.03
#Sta/Elev= 30
  3703.8  415.72  3975.5  411.51  4004.8  409.91  4019.8  410.63  4098.1  410.79
  4264.9  407.55  4363.0  404.57  4443.2  403.83  4453.2  403.15  4729.3  400.45
  4729.8  399.95  4738.2  400.45  4773.8  401.00  4985.4  401.00  5114.5  400.70
  5132.1  403.27  5137.1  402.91  5154.5  405.74  5206.2  408.91  5224.7  409.72
  5265.2  409.88  5339.9  410.14  5375.1  411.24  5394.1  410.97  5469.5  413.35
  5481.0  412.96  5598.5  411.69  5819.0  413.59  5862.9  414.63  6089.1  415.94
#Mann=9,-1,0
  3703.8    0.05       0  4264.9    0.16       0  4729.3   0.033       0
  4738.2    0.16       0  4985.4    0.05       0  5206.2    0.16       0
  5265.2    0.05       0  5481.0    0.16       0  5819.0    0.05       0
Bank Sta=4729.3,4738.2
Exp/Cntr=0.3,0.1

Chan Stop Cuts=-1