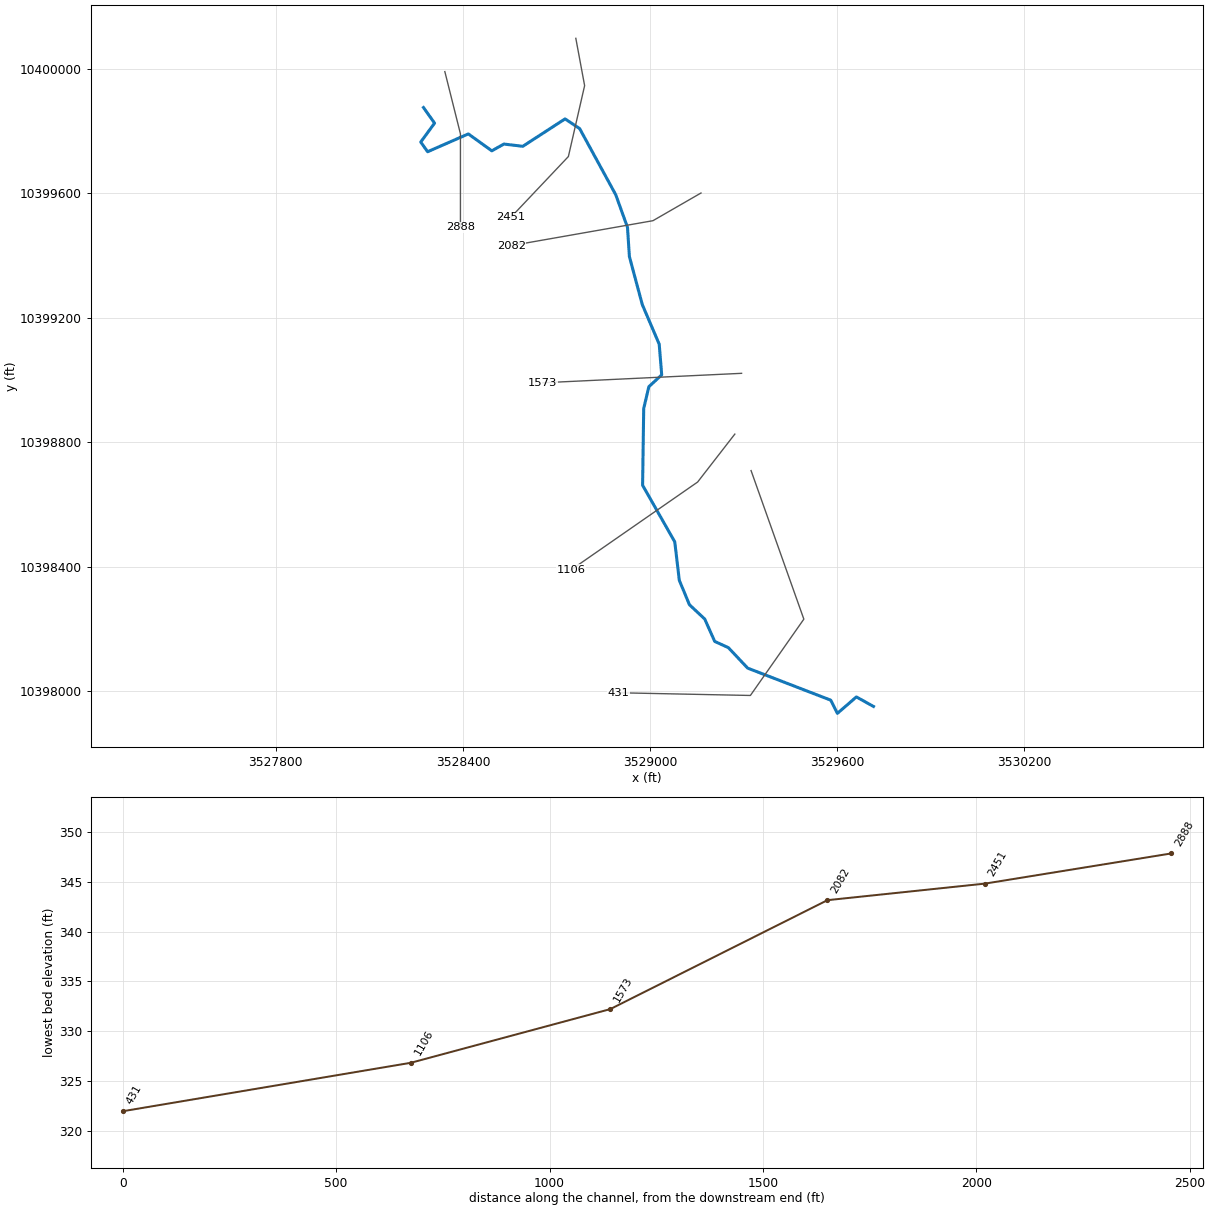
--- MINERAL CR TRIB 1 1.prj (project) ---

Proj Title=MINERAL CR TRIB 1 1 Base Level Engineering
Current Plan=p01
Default Exp/Contr=0.3,0.1
English Units
Geom File=g01
Flow File=f01
Plan File=p01
BEGIN DESCRIPTION:
MINERAL CR TRIB 1 1
END DESCRIPTION:

--- MINERAL CR TRIB 1 1.p01 (plan) ---

Plan Title=Multiple Run
Short Identifier=Multiple
Geom File=g01
Flow File=f01
Subcritical Flow
K Sum by GR= 0
Std Step Tol= 0.01
Critical Tol= 0.01
Num of Std Step Trials= 20
Max Error Tol= 0.3
Flow Tol Ratio= 0.001
Split Flow NTrial= 30
Split Flow Tol= 0.02
Split Flow Ratio= 0.02
Log Output Level= 0
Friction Slope Method= 1
Unsteady Friction Slope Method= 2
Unsteady Bridges Friction Slope Method= 1
Parabolic Critical Depth
Global Vel Dist=  1 , 1 , 1
Global Log Level= 0
CheckData=True
Encroach Param= -1, 0, 0, 0
BEGIN DESCRIPTION:
Multiple Run
END DESCRIPTION:

--- MINERAL CR TRIB 1 1.f01 (steady flow) ---

Flow Title=Multiple
Number of Profiles=7
Profile Names=10-year,25-year,50-year,1pct_min,100-year,1pct_plu,500-year
River Rch & RM= MINERAL CR TRIB ,Reach-1,2888
     463     616     739     650     879    1188    1236
Boundary for River Rch & Prof#=MINERAL CR TRIB ,Reach-1,1
Up Type=0
Dn Type=3
Dn Slope=0.005
Boundary for River Rch & Prof#=MINERAL CR TRIB ,Reach-1,2
Up Type=0
Dn Type=3
Dn Slope=0.005
Boundary for River Rch & Prof#=MINERAL CR TRIB ,Reach-1,3
Up Type=0
Dn Type=3
Dn Slope=0.005
Boundary for River Rch & Prof#=MINERAL CR TRIB ,Reach-1,4
Up Type=0
Dn Type=3
Dn Slope=0.005
Boundary for River Rch & Prof#=MINERAL CR TRIB ,Reach-1,5
Up Type=0
Dn Type=3
Dn Slope=0.005
Boundary for River Rch & Prof#=MINERAL CR TRIB ,Reach-1,6
Up Type=0
Dn Type=3
Dn Slope=0.005
Boundary for River Rch & Prof#=MINERAL CR TRIB ,Reach-1,7
Up Type=0
Dn Type=3
Dn Slope=0.005

--- MINERAL CR TRIB 1 1.g01 (geometry) ---

Geom Title=Existing Conditions

River Reach=MINERAL CR TRIB ,Reach-1
Reach XY= 30
      3528273.57     10399876.22      3528309.11     10399826.00
      3528264.74     10399765.28      3528286.93     10399734.12
      3528417.46     10399791.42      3528492.76     10399737.02
      3528531.50     10399758.84      3528592.20     10399751.63
      3528727.70     10399839.64      3528774.48     10399808.57
      3528890.32     10399595.82      3528927.93     10399491.07
      3528934.01     10399397.50      3528975.38     10399243.00
      3529029.64     10399115.83      3529037.64     10399017.12
      3528996.50     10398979.22      3528979.95     10398908.90
      3528976.38     10398662.43      3529079.55     10398480.58
      3529094.08     10398357.21      3529126.52     10398278.68
      3529175.61     10398232.65      3529207.71     10398160.64
      3529251.57     10398140.57      3529313.37     10398074.84
      3529579.83     10397971.87      3529601.19     10397929.42
      3529662.12     10397982.29      3529717.01     10397951.64

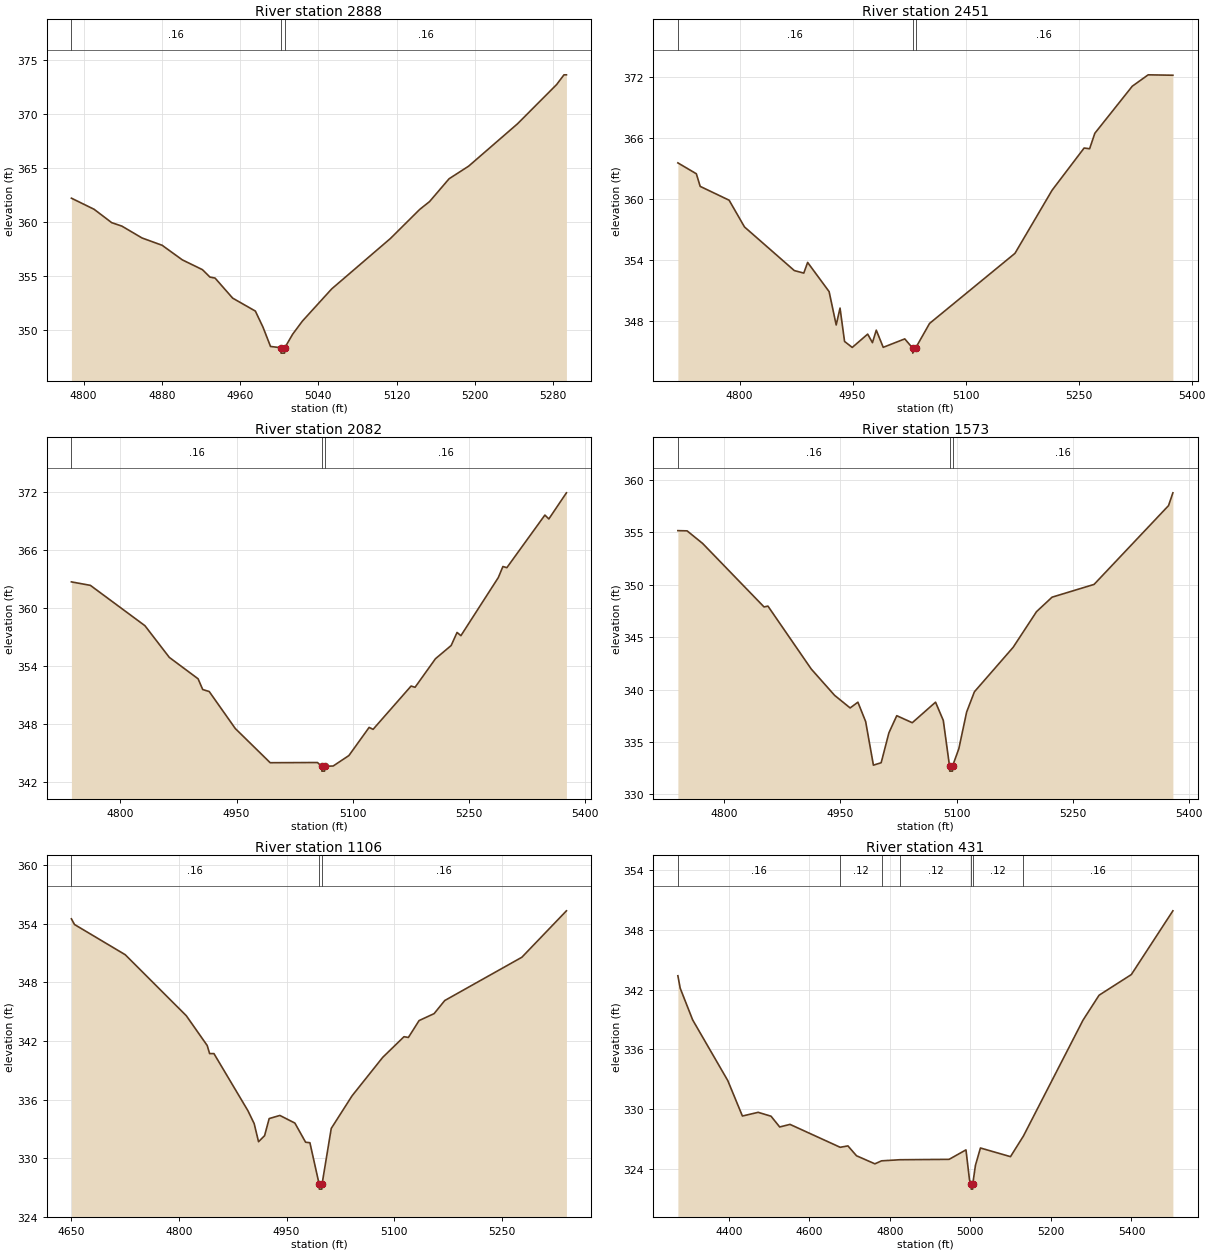
Type RM Length L Ch R = 1,2888,437,437,437
BEGIN DESCRIPTION:
MINERAL CR TRIB 1 11 0
END DESCRIPTION:
XS GIS Cut Line= 3
      3528342.10     10399991.66      3528392.11     10399791.64
      3528392.11     10399491.61
#Sta/Elev= 30
  4787.5  362.21  4810.7  361.18  4828.7  359.94  4839.1  359.62  4859.7  358.52
  4880.3  357.84  4900.9  356.49  4921.5  355.58  4929.2  354.89  4934.4  354.80
  4952.4  352.94  4975.6  351.74  4983.4  350.25  4991.1  348.46  5001.7  348.34
  5001.9  347.84  5005.4  347.84  5005.7  348.34  5013.7  349.59  5023.7  350.81
  5053.7  353.80  5113.7  358.47  5143.7  361.17  5153.7  361.89  5173.7  364.01
  5193.7  365.18  5243.7  369.11  5283.7  372.75  5291.2  373.65  5293.7  373.65
#Mann=3,-1,0
  4787.5    0.16       0  5001.7    0.07       0  5005.7    0.16       0
Bank Sta=5001.7,5005.7
Exp/Cntr=0.3,0.1

Type RM Length L Ch R = 1,2451,369,369,369
BEGIN DESCRIPTION:
MINERAL CR TRIB 1 10 0
END DESCRIPTION:
XS GIS Cut Line= 4
      3528762.21     10400098.54      3528790.43     10399946.60
      3528738.35     10399718.73      3528553.91     10399523.45
#Sta/Elev= 30
  4718.2  363.52  4742.7  362.45  4747.8  361.21  4786.2  359.85  4806.6  357.22
  4872.7  352.93  4885.3  352.68  4890.4  353.73  4918.9  350.86  4928.3  347.58
  4933.4  349.24  4939.4  345.96  4949.6  345.37  4970.1  346.68  4976.4  345.84
  4981.5  347.07  4990.7  345.38  5019.3  346.21  5029.7  345.31  5029.9  344.81
  5033.7  345.31  5052.2  347.73  5165.5  354.62  5214.8  360.83  5257.3  364.98
  5264.6  364.91  5271.5  366.43  5321.2  371.06  5342.3  372.18  5375.1  372.14
#Mann=3,-1,0
  4718.2    0.16       0  5029.7    0.07       0  5033.7    0.16       0
Bank Sta=5029.7,5033.7
Exp/Cntr=0.3,0.1

Type RM Length L Ch R = 1,2082,509,509,509
BEGIN DESCRIPTION:
MINERAL CR TRIB 1 1 6 0
END DESCRIPTION:
XS GIS Cut Line= 3
      3529163.70     10399601.55      3529009.62     10399512.57
      3528555.54     10399432.57
#Sta/Elev= 30
  4736.8  362.72  4761.3  362.36  4831.7  358.19  4863.2  354.91  4900.3  352.70
  4906.3  351.59  4914.7  351.38  4948.3  347.56  4993.4  344.02  5054.4  344.04
  5059.8  343.65  5060.1  343.15  5063.6  343.15  5063.8  343.65  5074.7  343.68
  5095.0  344.76  5121.1  347.67  5126.2  347.47  5175.3  351.95  5180.4  351.82
  5206.7  354.77  5227.0  356.14  5234.6  357.49  5239.6  357.16  5287.9  363.17
  5293.8  364.31  5298.9  364.19  5348.0  369.63  5353.1  369.23  5375.8  371.93
#Mann=3,-1,0
  4736.8    0.16       0  5059.8    0.07       0  5063.8    0.16       0
Bank Sta=5059.8,5063.8
Exp/Cntr=0.3,0.1

Type RM Length L Ch R = 1,1573,467,467,467
BEGIN DESCRIPTION:
MINERAL CR TRIB 1 1 5 0
END DESCRIPTION:
XS GIS Cut Line= 2
      3529293.94     10399022.12      3528656.46     10398991.76
#Sta/Elev= 30
  4740.5  355.17  4752.4  355.15  4772.4  353.95  4851.6  347.89  4856.6  347.97
  4912.5  341.96  4942.6  339.45  4962.6  338.25  4972.6  338.80  4982.6  336.95
  4992.6  332.79  5002.6  333.02  5012.6  335.88  5022.7  337.51  5042.7  336.84
  5072.7  338.80  5082.7  337.06  5090.7  332.72  5091.0  332.22  5094.5  332.22
  5094.7  332.72  5102.7  334.35  5112.8  337.86  5122.8  339.79  5172.8  344.04
  5202.9  347.44  5222.9  348.82  5277.1  350.04  5373.1  357.56  5378.7  358.78
#Mann=3,-1,0
  4740.5    0.16       0  5090.7    0.07       0  5094.7    0.16       0
Bank Sta=5090.7,5094.7
Exp/Cntr=0.3,0.1

Type RM Length L Ch R = 1,1106,675,675,675
BEGIN DESCRIPTION:
MINERAL CR TRIB 1 1 4 0
END DESCRIPTION:
XS GIS Cut Line= 3
      3529272.21     10398826.82      3529152.84     10398672.73
      3528747.08     10398390.65
#Sta/Elev= 30
  4650.5  354.50  4654.8  353.92  4725.4  350.83  4810.5  344.58  4839.5  341.54
  4842.9  340.71  4848.9  340.71  4896.1  334.88  4904.9  333.55  4911.0  331.69
  4919.4  332.31  4925.8  334.06  4940.7  334.38  4961.6  333.60  4976.5  331.64
  4982.5  331.59  4995.4  327.34  4995.6  326.84  4999.1  326.84  4999.4  327.34
  5012.2  333.05  5041.2  336.39  5083.8  340.32  5113.5  342.44  5119.6  342.36
  5134.5  344.09  5155.4  344.80  5170.2  346.14  5277.6  350.57  5339.6  355.32
#Mann=3,-1,0
  4650.5    0.16       0  4995.4    0.07       0  4999.4    0.16       0
Bank Sta=4995.4,4999.4
Exp/Cntr=0.3,0.1

Type RM Length L Ch R = 1,431,0,0,0
BEGIN DESCRIPTION:
MINERAL CR TRIB 1 1 1 0
END DESCRIPTION:
XS GIS Cut Line= 4
      3529324.29     10398709.61      3529493.56     10398232.19
      3529322.12     10397986.96      3528898.95     10397995.64
#Sta/Elev= 30
  4273.8  343.40  4279.6  342.15  4310.5  338.97  4397.8  332.87  4434.0  329.32
  4473.2  329.69  4505.1  329.30  4526.6  328.22  4552.2  328.48  4676.8  326.18
  4696.0  326.32  4717.3  325.33  4763.0  324.52  4779.5  324.82  4824.8  324.93
  4947.2  324.97  4989.1  325.92  4997.8  322.92  5001.9  322.48  5002.1  321.98
  5005.6  321.98  5005.9  322.48  5012.6  324.37  5025.0  326.11  5099.6  325.24
  5131.7  327.31  5279.6  338.94  5319.6  341.45  5399.6  343.52  5502.8  349.92
#Mann=7,-1,0
  4273.8    0.16       0  4676.8    0.12       0  4779.5    0.16       0
  4824.8    0.12       0  5001.9    0.07       0  5005.9    0.12       0
  5131.7    0.16       0
Bank Sta=5001.9,5005.9
Exp/Cntr=0.3,0.1

Chan Stop Cuts=-1