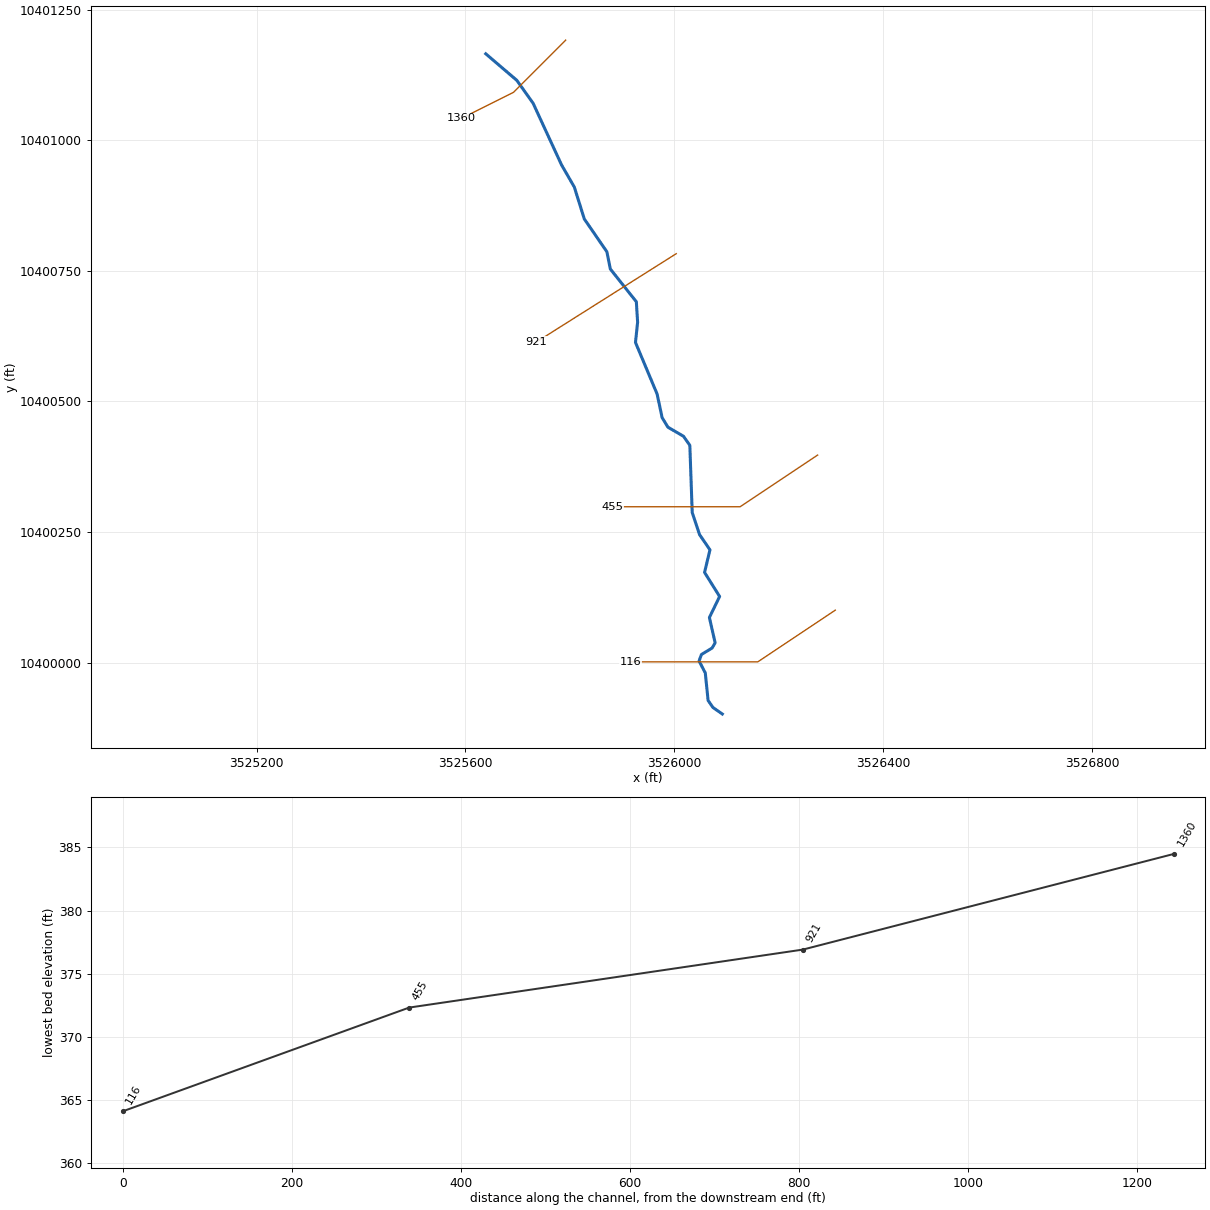
--- MINERAL CR TRIB 1 2.prj (project) ---

Proj Title=MINERAL CR TRIB 1 2 Base Level Engineering
Current Plan=p01
Default Exp/Contr=0.3,0.1
English Units
Geom File=g01
Flow File=f01
Plan File=p01
BEGIN DESCRIPTION:
MINERAL CR TRIB 1 2
END DESCRIPTION:

--- MINERAL CR TRIB 1 2.p01 (plan) ---

Plan Title=Multiple Run
Short Identifier=Multiple
Geom File=g01
Flow File=f01
Subcritical Flow
K Sum by GR= 0
Std Step Tol= 0.01
Critical Tol= 0.01
Num of Std Step Trials= 20
Max Error Tol= 0.3
Flow Tol Ratio= 0.001
Split Flow NTrial= 30
Split Flow Tol= 0.02
Split Flow Ratio= 0.02
Log Output Level= 0
Friction Slope Method= 1
Unsteady Friction Slope Method= 2
Unsteady Bridges Friction Slope Method= 1
Parabolic Critical Depth
Global Vel Dist=  1 , 1 , 1
Global Log Level= 0
CheckData=True
Encroach Param= -1, 0, 0, 0
BEGIN DESCRIPTION:
Multiple Run
END DESCRIPTION:

--- MINERAL CR TRIB 1 2.f01 (steady flow) ---

Flow Title=Multiple
Number of Profiles=7
Profile Names=10-year,25-year,50-year,1pct_min,100-year,1pct_plu,500-year
River Rch & RM= MINERAL CR TRIB ,Reach-1,1360
     397     523     625     548     741    1002    1034
Boundary for River Rch & Prof#=MINERAL CR TRIB ,Reach-1,1
Up Type=0
Dn Type=3
Dn Slope=0.005
Boundary for River Rch & Prof#=MINERAL CR TRIB ,Reach-1,2
Up Type=0
Dn Type=3
Dn Slope=0.005
Boundary for River Rch & Prof#=MINERAL CR TRIB ,Reach-1,3
Up Type=0
Dn Type=3
Dn Slope=0.005
Boundary for River Rch & Prof#=MINERAL CR TRIB ,Reach-1,4
Up Type=0
Dn Type=3
Dn Slope=0.005
Boundary for River Rch & Prof#=MINERAL CR TRIB ,Reach-1,5
Up Type=0
Dn Type=3
Dn Slope=0.005
Boundary for River Rch & Prof#=MINERAL CR TRIB ,Reach-1,6
Up Type=0
Dn Type=3
Dn Slope=0.005
Boundary for River Rch & Prof#=MINERAL CR TRIB ,Reach-1,7
Up Type=0
Dn Type=3
Dn Slope=0.005

--- MINERAL CR TRIB 1 2.g01 (geometry) ---

Geom Title=Existing Conditions

River Reach=MINERAL CR TRIB ,Reach-1
Reach XY= 30
      3525638.96     10401165.37      3525698.41     10401114.63
      3525729.68     10401070.68      3525784.23     10400952.52
      3525808.64     10400910.20      3525827.73     10400849.22
      3525870.93     10400786.48      3525877.59     10400753.41
      3525927.40     10400690.77      3525929.84     10400651.61
      3525925.74     10400612.87      3525967.15     10400514.24
      3525976.83     10400468.82      3525987.93     10400450.64
      3526017.77     10400433.26      3526029.84     10400415.93
      3526034.42     10400287.32      3526048.47     10400245.07
      3526068.40     10400215.91      3526058.06     10400172.69
      3526086.91     10400126.67      3526067.33     10400086.39
      3526078.31     10400037.86      3526072.48     10400027.97
      3526052.00     10400015.50      3526047.61     10400003.16
      3526059.46     10399980.25      3526064.86     10399927.57
      3526074.13     10399914.18      3526092.11     10399901.64

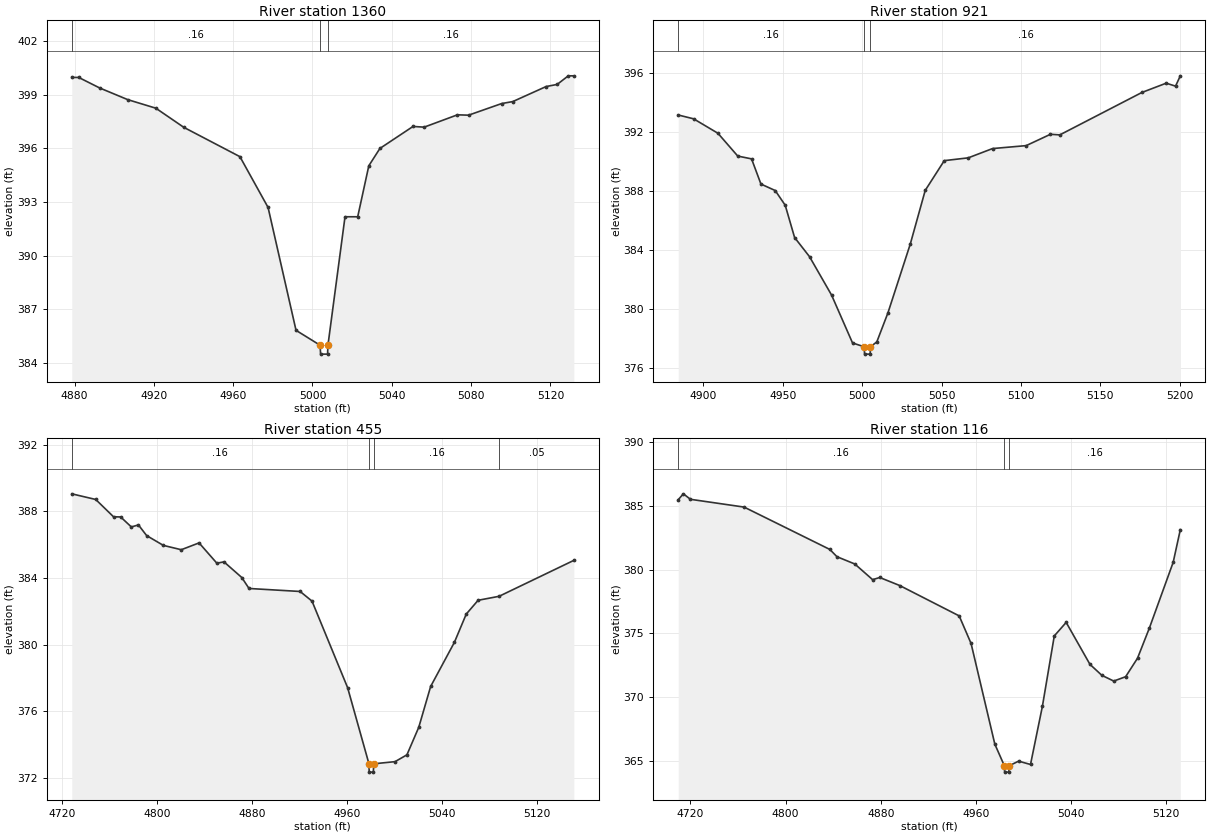
Type RM Length L Ch R = 1,1360,439,439,439
BEGIN DESCRIPTION:
MINERAL CR TRIB 1 2 4 0
END DESCRIPTION:
XS GIS Cut Line= 3
      3525792.08     10401191.61      3525692.11     10401091.64
      3525592.09     10401041.64
#Sta/Elev= 27
  4878.6  399.96  4882.1  399.96  4892.7  399.37  4906.8  398.72  4921.0  398.24
  4935.1  397.17  4963.4  395.53  4977.6  392.69  4991.7  385.82  5003.8  384.99
  5004.1  384.49  5007.6  384.49  5007.8  384.99  5016.4  392.17  5022.8  392.17
  5028.4  395.02  5034.0  395.99  5050.7  397.22  5056.3  397.18  5073.1  397.87
  5078.7  397.85  5095.4  398.50  5101.0  398.61  5117.8  399.45  5123.4  399.57
  5129.0  400.05  5131.8  400.05
#Mann=3,-1,0
  4878.6    0.16       0  5003.8    0.07       0  5007.8    0.16       0
Bank Sta=5003.8,5007.8
Exp/Cntr=0.3,0.1

Type RM Length L Ch R = 1,921,466,466,466
BEGIN DESCRIPTION:
MINERAL CR TRIB 1 2 3 0
END DESCRIPTION:
XS GIS Cut Line= 2
      3526003.81     10400782.78      3525736.32     10400613.98
#Sta/Elev= 30
  4884.1  393.16  4893.8  392.90  4909.1  391.92  4921.6  390.37  4930.3  390.18
  4936.2  388.47  4945.2  388.03  4951.5  387.03  4957.4  384.84  4966.8  383.54
  4980.7  380.93  4993.9  377.68  5001.2  377.42  5001.5  376.92  5005.0  376.92
  5005.2  377.42  5009.2  377.75  5016.2  379.72  5030.3  384.40  5039.7  388.04
  5051.7  390.06  5066.8  390.25  5082.1  390.88  5103.3  391.08  5118.6  391.85
  5124.5  391.81  5176.2  394.69  5191.5  395.32  5197.4  395.12  5200.4  395.82
#Mann=3,-1,0
  4884.1    0.16       0  5001.2    0.07       0  5005.2    0.16       0
Bank Sta=5001.2,5005.2
Exp/Cntr=0.3,0.1

Type RM Length L Ch R = 1,455,339,339,339
BEGIN DESCRIPTION:
MINERAL CR TRIB 1 2 1 1
END DESCRIPTION:
XS GIS Cut Line= 3
      3526274.60     10400397.34      3526126.18     10400298.40
      3525881.36     10400298.40
#Sta/Elev= 30
  4728.2  389.06  4748.4  388.72  4763.4  387.68  4769.4  387.67  4778.4  387.07
  4784.4  387.19  4791.3  386.55  4805.4  385.96  4820.5  385.70  4835.5  386.11
  4850.5  384.89  4856.5  384.97  4871.5  384.03  4877.6  383.37  4920.7  383.19
  4930.7  382.61  4960.7  377.41  4978.7  372.83  4978.9  372.33  4982.4  372.33
  4982.7  372.83  5000.7  372.96  5010.7  373.37  5020.7  375.03  5030.7  377.48
  5050.7  380.13  5060.7  381.83  5070.7  382.66  5088.4  382.90  5151.4  385.06
#Mann=4,-1,0
  4728.2    0.16       0  4978.7    0.07       0  4982.7    0.16       0
  5088.4    0.05       0
Bank Sta=4978.7,4982.7
Exp/Cntr=0.3,0.1

Type RM Length L Ch R = 1,116,0,0,0
BEGIN DESCRIPTION:
MINERAL CR TRIB 1 2 1 0
END DESCRIPTION:
XS GIS Cut Line= 3
      3526308.48     10400100.48      3526160.04     10400001.52
      3525916.15     10400001.52
#Sta/Elev= 30
  4709.7  385.48  4714.0  385.94  4720.0  385.51  4765.1  384.90  4837.2  381.58
  4843.2  381.01  4858.2  380.44  4873.2  379.21  4879.2  379.38  4896.0  378.75
  4946.0  376.37  4956.0  374.21  4976.0  366.31  4984.0  364.62  4984.3  364.12
  4987.8  364.12  4988.0  364.62  4996.0  364.98  5006.0  364.72  5016.0  369.28
  5026.0  374.80  5036.0  375.86  5056.0  372.57  5066.0  371.71  5076.0  371.26
  5086.0  371.60  5096.0  373.05  5106.0  375.42  5126.0  380.57  5132.0  383.13
#Mann=3,-1,0
  4709.7    0.16       0  4984.0    0.07       0  4988.0    0.16       0
Bank Sta=4984,4988
Exp/Cntr=0.3,0.1

Chan Stop Cuts=-1