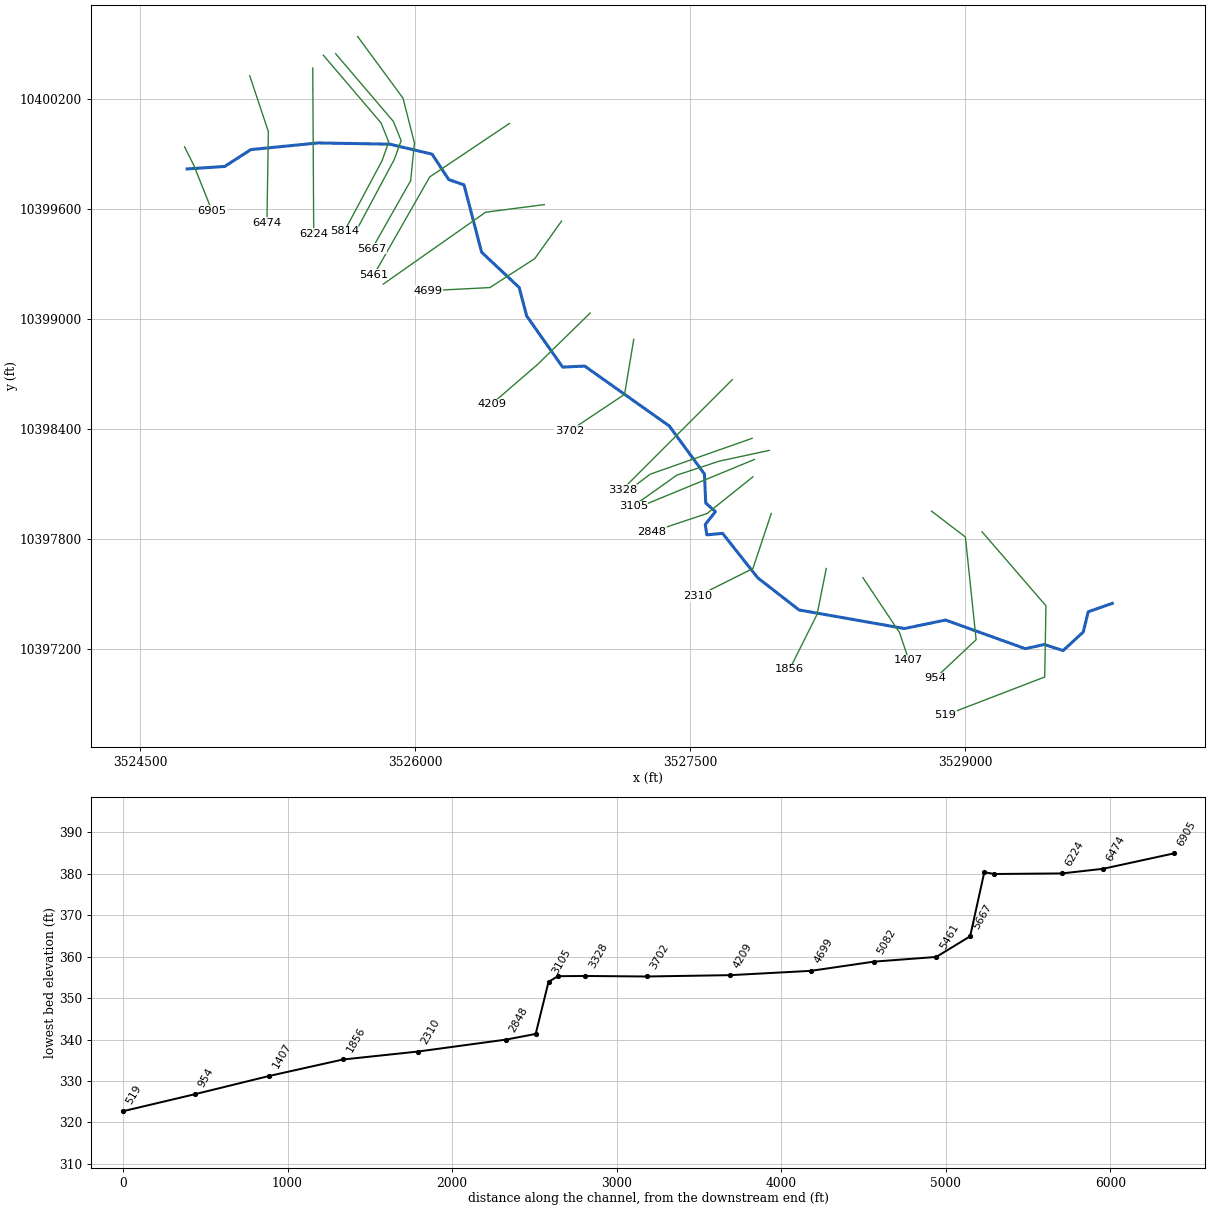
--- MINERAL CR TRIB 1.prj (project) ---

Proj Title=MINERAL CR TRIB 1 Base Level Engineering
Current Plan=p01
Default Exp/Contr=0.3,0.1
English Units
Geom File=g01
Flow File=f01
Plan File=p01
BEGIN DESCRIPTION:
MINERAL CR TRIB 1
END DESCRIPTION:

--- MINERAL CR TRIB 1.p01 (plan) ---

Plan Title=Multiple Run
Short Identifier=Multiple
Geom File=g01
Flow File=f01
Subcritical Flow
K Sum by GR= 0
Std Step Tol= 0.01
Critical Tol= 0.01
Num of Std Step Trials= 20
Max Error Tol= 0.3
Flow Tol Ratio= 0.001
Split Flow NTrial= 30
Split Flow Tol= 0.02
Split Flow Ratio= 0.02
Log Output Level= 0
Friction Slope Method= 1
Unsteady Friction Slope Method= 2
Unsteady Bridges Friction Slope Method= 1
Parabolic Critical Depth
Global Vel Dist=  1 , 1 , 1
Global Log Level= 0
CheckData=True
Encroach Param= -1, 0, 0, 0
BEGIN DESCRIPTION:
Multiple Run
END DESCRIPTION:

--- MINERAL CR TRIB 1.f01 (steady flow) ---

Flow Title=Multiple
Number of Profiles=7
Profile Names=10-year,25-year,50-year,1pct_min,100-year,1pct_plu,500-year
River Rch & RM= MINERAL CR TRIB ,Reach-1,6905
     511     686     828     733     991    1340    1412
River Rch & RM= MINERAL CR TRIB ,Reach-1,5461
     966    1346    1664    1504    2034    2751    3028
Boundary for River Rch & Prof#=MINERAL CR TRIB ,Reach-1,1
Up Type=0
Dn Type=3
Dn Slope=0.005
Boundary for River Rch & Prof#=MINERAL CR TRIB ,Reach-1,2
Up Type=0
Dn Type=3
Dn Slope=0.005
Boundary for River Rch & Prof#=MINERAL CR TRIB ,Reach-1,3
Up Type=0
Dn Type=3
Dn Slope=0.005
Boundary for River Rch & Prof#=MINERAL CR TRIB ,Reach-1,4
Up Type=0
Dn Type=3
Dn Slope=0.005
Boundary for River Rch & Prof#=MINERAL CR TRIB ,Reach-1,5
Up Type=0
Dn Type=3
Dn Slope=0.005
Boundary for River Rch & Prof#=MINERAL CR TRIB ,Reach-1,6
Up Type=0
Dn Type=3
Dn Slope=0.005
Boundary for River Rch & Prof#=MINERAL CR TRIB ,Reach-1,7
Up Type=0
Dn Type=3
Dn Slope=0.005

--- MINERAL CR TRIB 1.g01 (geometry) ---

Geom Title=Existing Conditions

River Reach=MINERAL CR TRIB ,Reach-1
Reach XY= 30
      3524755.92     10399820.95      3524960.91     10399834.57
      3525103.68     10399926.55      3525469.15     10399962.81
      3525860.99     10399956.21      3526092.11     10399901.64
      3526183.32     10399762.69      3526266.40     10399734.14
      3526362.34     10399366.65      3526567.24     10399174.34
      3526607.94     10399019.38      3526804.29     10398740.17
      3526924.55     10398745.72      3527385.91     10398419.06
      3527577.75     10398156.91      3527584.69     10397998.92
      3527637.64     10397952.04      3527582.01     10397881.37
      3527590.89     10397825.42      3527676.67     10397833.25
      3527868.37     10397590.80      3528093.69     10397415.51
      3528668.40     10397314.23      3528892.61     10397360.49
      3529328.17     10397204.26      3529431.48     10397227.28
      3529534.11     10397193.84      3529644.02     10397295.57
      3529671.00     10397405.52      3529802.11     10397451.64

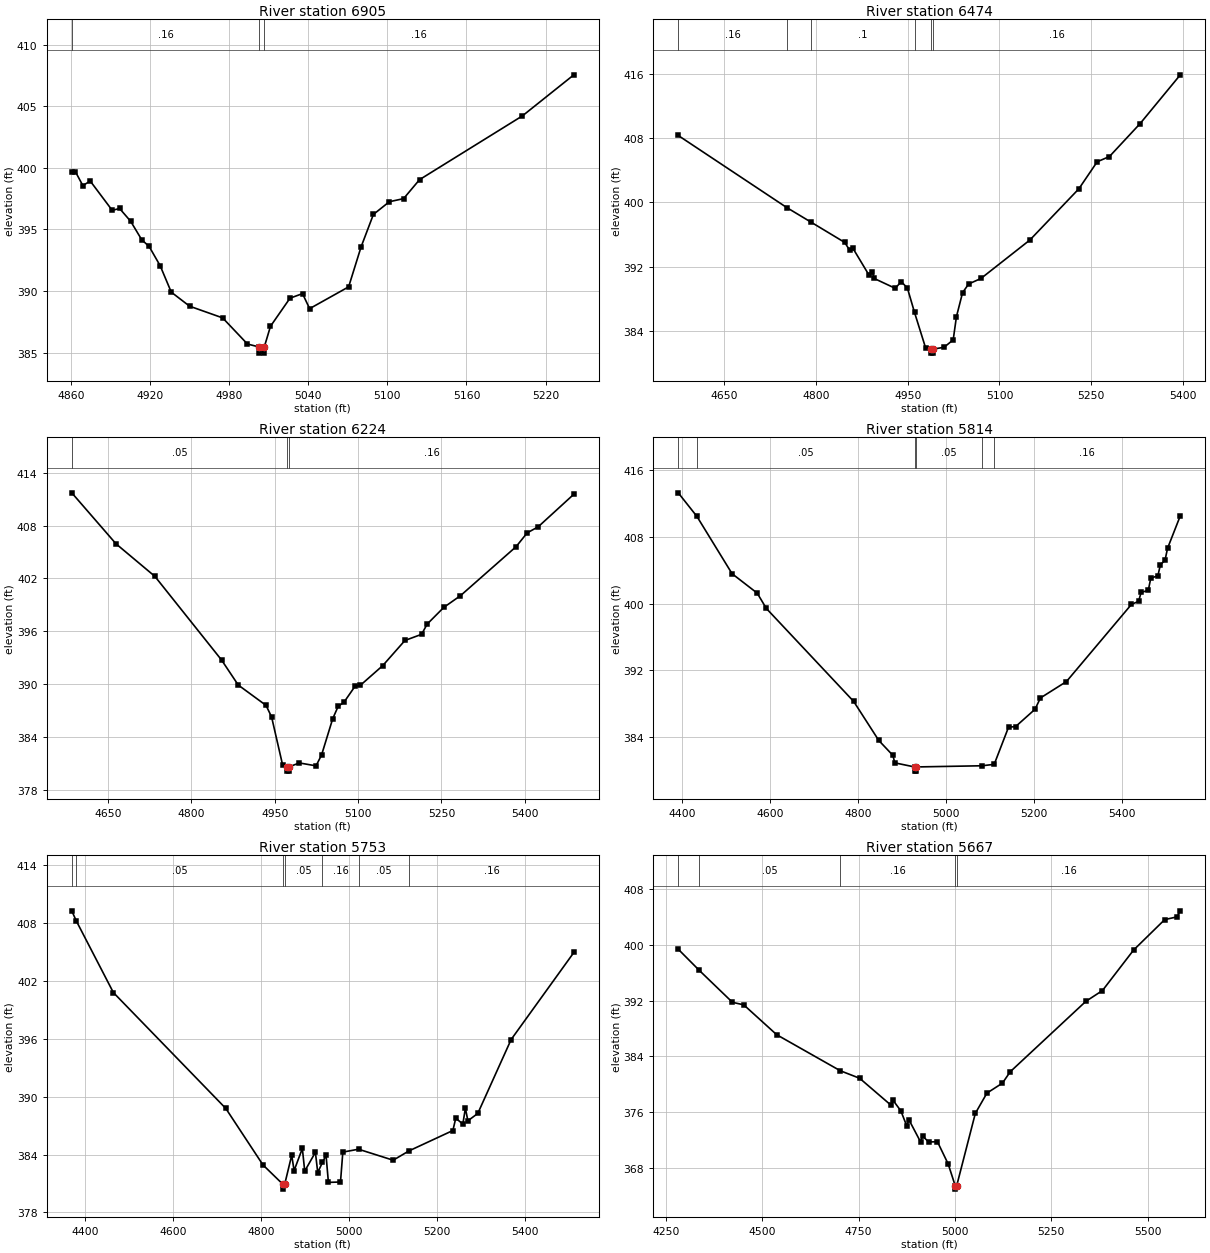
Type RM Length L Ch R = 1,6905,431,431,431
BEGIN DESCRIPTION:
MINERAL CR TRIB 1 21 0
END DESCRIPTION:
XS GIS Cut Line= 3
      3524742.11     10399941.63      3524792.11     10399841.64
      3524892.09     10399591.69
#Sta/Elev= 30
  4860.5  399.67  4863.3  399.67  4868.9  398.55  4874.5  398.92  4891.2  396.54
  4896.8  396.69  4905.2  395.65  4913.6  394.15  4919.2  393.61  4927.6  392.04
  4936.0  389.90  4949.9  388.76  4975.0  387.81  4993.8  385.69  5002.6  385.45
  5002.9  384.95  5006.4  384.95  5006.6  385.45  5011.3  387.13  5026.1  389.41
  5035.6  389.78  5041.0  388.56  5070.6  390.33  5080.0  393.56  5089.4  396.21
  5101.5  397.24  5112.3  397.49  5124.4  399.03  5202.5  404.21  5241.5  407.54
#Mann=3,-1,0
  4860.5    0.16       0  5002.6    0.07       0  5006.6    0.16       0
Bank Sta=5002.6,5006.6
Exp/Cntr=0.3,0.1

Type RM Length L Ch R = 1,6474,250,250,250
BEGIN DESCRIPTION:
MINERAL CR TRIB 1 2 0
END DESCRIPTION:
XS GIS Cut Line= 3
      3525097.52     10400329.69      3525199.10     10400024.96
      3525191.30     10399525.84
#Sta/Elev= 30
  4575.1  408.32  4752.6  399.34  4792.6  397.51  4847.1  395.01  4855.4  394.02
  4860.7  394.26  4887.0  390.92  4892.3  391.30  4895.4  390.52  4929.6  389.30
  4939.6  390.13  4949.6  389.32  4961.2  386.29  4979.6  381.81  4987.6  381.73
  4987.9  381.23  4991.4  381.23  4991.6  381.73  5009.6  381.96  5024.4  382.89
  5029.7  385.77  5039.7  388.76  5049.7  389.84  5069.7  390.52  5149.7  395.31
  5229.7  401.68  5259.7  405.05  5279.7  405.70  5329.7  409.79  5395.5  415.87
#Mann=6,-1,0
  4575.1    0.16       0  4752.6    0.05       0  4792.6     0.1       0
  4961.2    0.16       0  4987.6    0.07       0  4991.6    0.16       0
Bank Sta=4987.6,4991.6
Exp/Cntr=0.3,0.1

Type RM Length L Ch R = 1,6224,410,410,410
BEGIN DESCRIPTION:
MINERAL CR TRIB 1 14 0
END DESCRIPTION:
XS GIS Cut Line= 2
      3525441.29     10400371.27      3525446.50     10399467.68
#Sta/Elev= 30
  4584.7  411.73  4664.3  405.94  4734.3  402.24  4854.3  392.74  4884.3  389.90
  4934.3  387.59  4944.3  386.28  4964.3  380.78  4972.3  380.62  4972.6  380.12
  4976.1  380.12  4976.3  380.62  4994.3  381.05  5024.3  380.72  5034.3  381.96
  5054.3  386.07  5064.3  387.50  5074.3  387.92  5094.3  389.74  5104.3  389.88
  5144.3  392.10  5184.3  394.96  5214.3  395.66  5224.3  396.82  5254.3  398.72
  5284.3  400.05  5384.3  405.61  5404.3  407.18  5424.3  407.88  5488.3  411.57
#Mann=3,-1,0
  4584.7    0.05       0  4972.3    0.07       0  4976.3    0.16       0
Bank Sta=4972.3,4976.3
Exp/Cntr=0.3,0.1

Type RM Length L Ch R = 1,5814,61,61,61
BEGIN DESCRIPTION:
MINERAL CR TRIB 1 14 3
END DESCRIPTION:
XS GIS Cut Line= 5
      3525498.94     10400441.46      3525814.02     10400071.70
      3525855.69     10399967.53      3525819.23     10399865.97
      3525613.56     10399480.84
#Sta/Elev= 30
  4390.5  413.22  4432.9  410.41  4513.0  403.56  4570.2  401.24  4591.0  399.41
  4789.8  388.30  4846.9  383.64  4879.0  381.86  4883.2  380.97  4928.2  380.48
  4928.5  379.98  4932.0  379.98  4932.2  380.48  5081.7  380.62  5109.5  380.79
  5142.2  385.24  5158.0  385.29  5202.4  387.37  5214.7  388.72  5273.9  390.68
  5421.9  399.90  5438.1  400.26  5443.8  401.33  5460.1  401.57  5465.8  403.02
  5482.0  403.32  5487.7  404.64  5498.1  405.15  5504.0  406.60  5533.0  410.48
#Mann=6,-1,0
  4390.5    0.16       0  4432.9    0.05       0  4928.2    0.03       0
  4932.2    0.05       0  5081.7    0.07       0  5109.5    0.16       0
Bank Sta=4928.2,4932.2
Exp/Cntr=0.3,0.1

Type RM Length L Ch R = 1,5753,86,86,86
BEGIN DESCRIPTION:
MINERAL CR TRIB 1 14 2
END DESCRIPTION:
XS GIS Cut Line= 5
      3525566.31     10400449.42      3525881.39     10400079.65
      3525923.06     10399975.48      3525886.60     10399873.92
      3525680.94     10399488.80
#Sta/Elev= 30
  4368.8  409.29  4378.7  408.28  4463.5  400.81  4719.3  388.79  4803.9  382.93
  4849.3  380.92  4849.6  380.42  4853.3  380.92  4869.3  383.94  4874.7  382.34
  4893.5  384.64  4898.9  382.29  4923.2  384.24  4928.5  382.14  4939.2  383.19
  4947.4  383.94  4952.8  381.12  4980.3  381.16  4985.6  384.26  5021.3  384.56
  5100.2  383.42  5136.3  384.39  5236.0  386.50  5242.6  387.78  5258.7  387.17
  5264.5  388.81  5270.2  387.51  5292.7  388.27  5368.6  395.94  5511.3  404.97
#Mann=7,-1,0
  4368.8    0.16       0  4378.7    0.05       0  4849.3    0.07       0
  4853.3    0.05       0  4939.2    0.16       0  5021.3    0.05       0
  5136.3    0.16       0
Bank Sta=4849.3,4853.3
Exp/Cntr=0.3,0.1

Type RM Length L Ch R = 1,5667,206,206,206
BEGIN DESCRIPTION:
MINERAL CR TRIB 1 14 1
END DESCRIPTION:
XS GIS Cut Line= 5
      3525686.08     10400543.19      3525933.48     10400207.25
      3525995.98     10399962.46      3525975.14     10399756.73
      3525764.85     10399385.48
#Sta/Elev= 30
  4281.6  399.37  4336.3  396.33  4422.3  391.75  4451.6  391.39  4537.2  387.10
  4702.2  381.93  4752.5  380.85  4834.2  376.97  4839.3  377.68  4859.4  376.18
  4875.0  373.98  4880.2  374.92  4910.7  371.71  4915.9  372.57  4931.6  371.70
  4954.4  371.75  4982.4  368.54  5000.5  365.44  5000.8  364.94  5004.5  365.44
  5052.8  375.81  5082.9  378.72  5123.1  380.15  5143.5  381.79  5339.5  391.88
  5382.8  393.44  5463.6  399.25  5544.4  403.62  5576.2  404.01  5584.9  404.88
#Mann=5,-1,0
  4281.6    0.16       0  4336.3    0.05       0  4702.2    0.16       0
  5000.5    0.07       0  5004.5    0.16       0
Bank Sta=5000.5,5004.5
Exp/Cntr=0.3,0.1

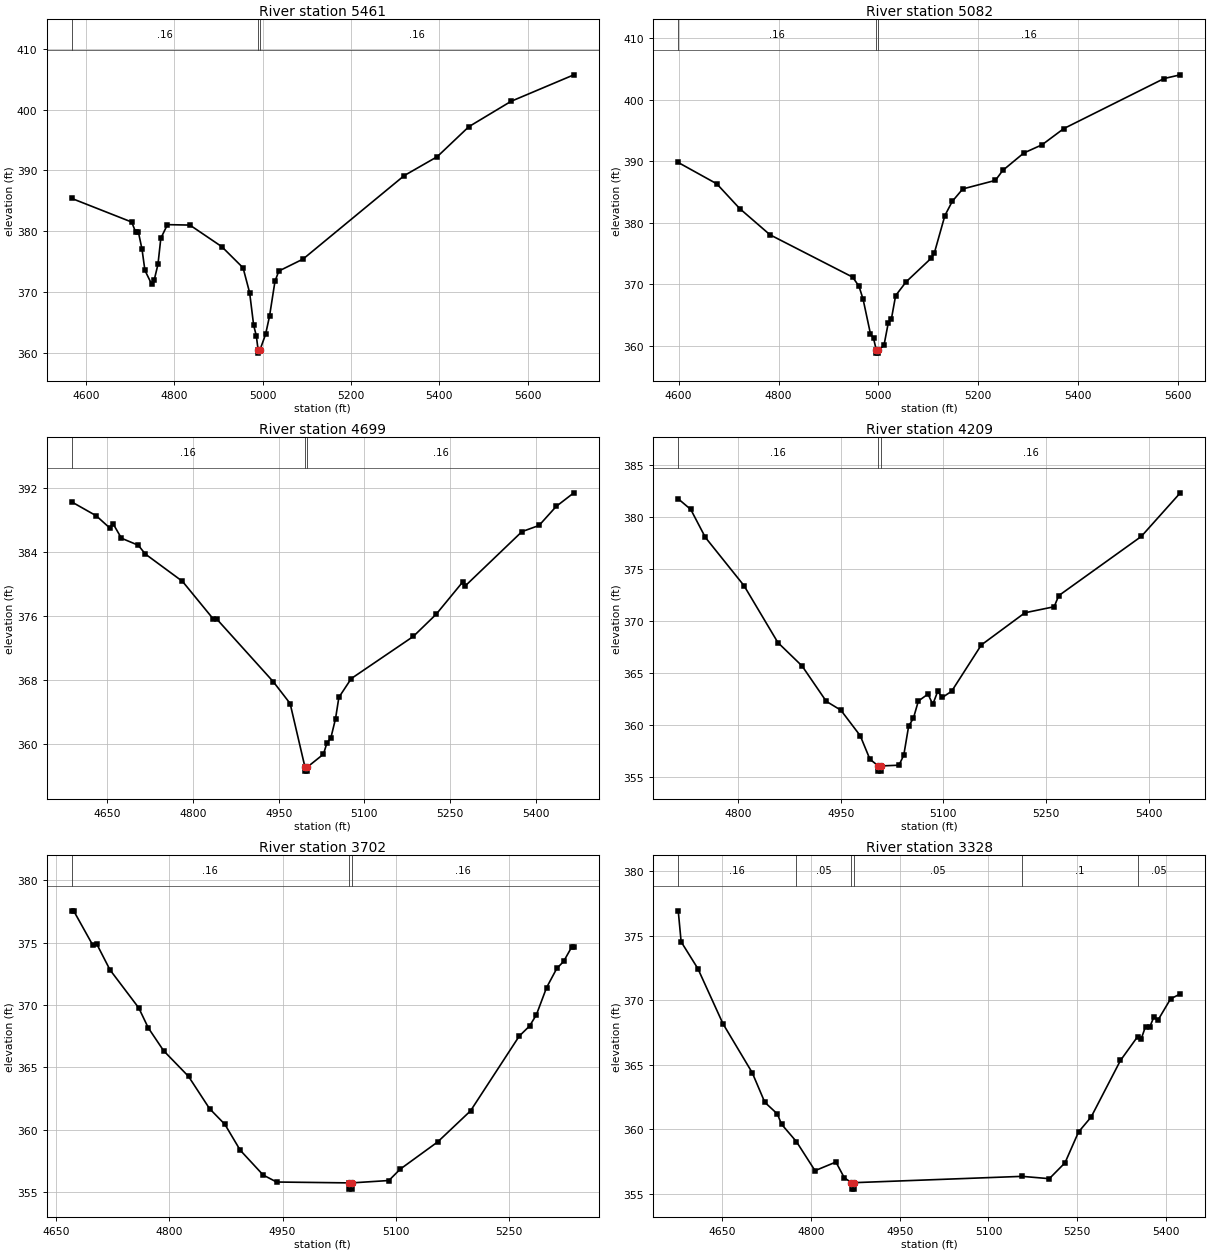
Type RM Length L Ch R = 1,5461,379,379,379
BEGIN DESCRIPTION:
MINERAL CR TRIB 1 13 0
END DESCRIPTION:
XS GIS Cut Line= 3
      3526514.18     10400069.21      3526079.31     10399777.56
      3525775.46     10399245.18
#Sta/Elev= 30
  4567.7  385.40  4703.3  381.52  4712.3  379.88  4718.3  379.95  4726.7  377.05
  4733.3  373.57  4748.3  371.34  4754.3  371.99  4762.8  374.54  4769.3  378.85
  4784.3  381.09  4835.1  381.02  4907.3  377.47  4955.5  373.99  4970.4  369.88
  4979.4  364.57  4985.4  362.83  4989.6  360.46  4989.9  359.96  4993.6  360.46
  5006.4  363.04  5015.4  366.04  5027.7  371.76  5036.4  373.46  5091.3  375.43
  5320.2  389.15  5395.1  392.27  5466.6  397.20  5562.1  401.37  5704.3  405.73
#Mann=3,-1,0
  4567.7    0.16       0  4989.6    0.07       0  4993.6    0.16       0
Bank Sta=4989.6,4993.6
Exp/Cntr=0.3,0.1

Type RM Length L Ch R = 1,5082,383,383,383
BEGIN DESCRIPTION:
MINERAL CR TRIB 1 13 11
END DESCRIPTION:
XS GIS Cut Line= 3
      3526704.28     10399626.52      3526384.00     10399584.85
      3525825.63     10399192.70
#Sta/Elev= 30
  4599.2  389.81  4676.4  386.34  4722.4  382.31  4782.9  378.06  4948.3  371.18
  4961.1  369.70  4969.3  367.59  4984.1  361.95  4990.2  361.24  4995.8  359.32
  4996.1  358.82  4999.6  358.82  4999.8  359.32  5011.1  360.06  5019.8  363.76
  5025.9  364.33  5034.5  368.17  5055.5  370.41  5106.1  374.28  5112.2  375.15
  5133.1  381.18  5147.9  383.49  5168.9  385.51  5234.2  386.90  5249.0  388.52
  5291.1  391.35  5327.7  392.69  5371.0  395.31  5572.1  403.46  5604.5  404.06
#Mann=3,-1,0
  4599.2    0.16       0  4995.8    0.07       0  4999.8    0.16       0
Bank Sta=4995.8,4999.8
Exp/Cntr=0.3,0.1

Type RM Length L Ch R = 1,4699,490,490,490
BEGIN DESCRIPTION:
MINERAL CR TRIB 1 12 0
END DESCRIPTION:
XS GIS Cut Line= 4
      3526798.27     10399536.48      3526652.84     10399332.45
      3526407.62     10399174.03      3526071.27     10399156.67
#Sta/Elev= 30
  4587.6  390.28  4630.4  388.55  4653.7  387.05  4659.8  387.57  4674.6  385.74
  4704.1  384.86  4716.3  383.77  4781.5  380.34  4835.6  375.62  4841.6  375.62
  4940.6  367.78  4970.0  365.06  4996.0  357.10  4996.3  356.60  4999.8  356.60
  5000.0  357.10  5028.4  358.72  5034.3  360.09  5041.4  360.77  5049.5  363.15
  5055.4  365.83  5077.1  368.18  5185.7  373.45  5225.7  376.22  5272.1  380.25
  5277.1  379.80  5375.9  386.56  5406.0  387.34  5436.0  389.72  5466.9  391.42
#Mann=3,-1,0
  4587.6    0.16       0  4996.0    0.07       0  5000.0    0.16       0
Bank Sta=4996,5000
Exp/Cntr=0.3,0.1

Type RM Length L Ch R = 1,4209,507,507,507
BEGIN DESCRIPTION:
MINERAL CR TRIB 1 29 0
END DESCRIPTION:
XS GIS Cut Line= 3
      3526954.52     10399035.16      3526668.04     10398755.19
      3526416.02     10398537.64
#Sta/Elev= 30
  4712.7  381.78  4731.0  380.76  4752.3  378.07  4808.8  373.42  4858.3  367.94
  4893.7  365.68  4929.0  362.28  4950.3  361.43  4978.6  358.97  4992.7  356.71
  5004.9  356.06  5005.1  355.56  5008.6  355.56  5008.9  356.06  5035.2  356.13
  5042.2  357.10  5049.3  359.89  5056.3  360.66  5063.5  362.31  5077.6  362.98
  5084.6  361.99  5091.7  363.23  5098.7  362.66  5112.2  363.26  5155.5  367.71
  5219.2  370.81  5261.9  371.39  5268.6  372.46  5389.2  378.16  5446.2  382.36
#Mann=3,-1,0
  4712.7    0.16       0  5004.9    0.07       0  5008.9    0.16       0
Bank Sta=5004.9,5008.9
Exp/Cntr=0.3,0.1

Type RM Length L Ch R = 1,3702,374,374,374
BEGIN DESCRIPTION:
MINERAL CR TRIB 1 19 0
END DESCRIPTION:
XS GIS Cut Line= 3
      3527192.10     10398891.60      3527142.11     10398591.64
      3526842.07     10398391.62
#Sta/Elev= 30
  4670.9  377.54  4673.4  377.54  4698.7  374.79  4703.8  374.90  4721.5  372.81
  4759.6  369.76  4772.2  368.16  4792.5  366.33  4825.5  364.27  4853.3  361.69
  4873.6  360.43  4893.9  358.36  4924.3  356.37  4942.1  355.81  5037.6  355.74
  5037.8  355.24  5041.3  355.24  5041.6  355.74  5090.7  355.93  5105.7  356.84
  5155.3  359.02  5198.8  361.51  5263.4  367.51  5277.0  368.31  5286.0  369.21
  5299.5  371.39  5313.0  372.92  5322.0  373.48  5332.5  374.61  5335.6  374.61
#Mann=3,-1,0
  4670.9    0.16       0  5037.6    0.07       0  5041.6    0.16       0
Bank Sta=5037.6,5041.6
Exp/Cntr=0.3,0.1

Type RM Length L Ch R = 1,3328,166,166,166
BEGIN DESCRIPTION:
MINERAL CR TRIB 1 8 0
END DESCRIPTION:
XS GIS Cut Line= 3
      3527729.33     10398671.34      3527429.31     10398371.31
      3527129.28     10398071.29
#Sta/Elev= 30
  4575.7  376.93  4580.6  374.53  4608.9  372.45  4651.3  368.18  4700.8  364.38
  4722.0  362.09  4743.2  361.19  4750.3  360.39  4775.5  359.04  4806.9  356.79
  4842.2  357.46  4856.4  356.24  4868.5  355.86  4868.8  355.36  4872.3  355.36
  4872.5  355.86  5156.8  356.35  5202.9  356.17  5229.4  357.40  5252.3  359.79
  5273.6  360.95  5323.1  365.33  5352.0  367.17  5358.4  367.03  5365.5  367.96
  5372.6  367.93  5379.6  368.69  5386.7  368.47  5407.9  370.11  5424.3  370.49
#Mann=6,-1,0
  4575.7    0.16       0  4775.5    0.05       0  4868.5   0.033       0
  4872.5    0.05       0  5156.8     0.1       0  5352.0    0.05       0
Bank Sta=4868.5,4872.5
Exp/Cntr=0.3,0.1

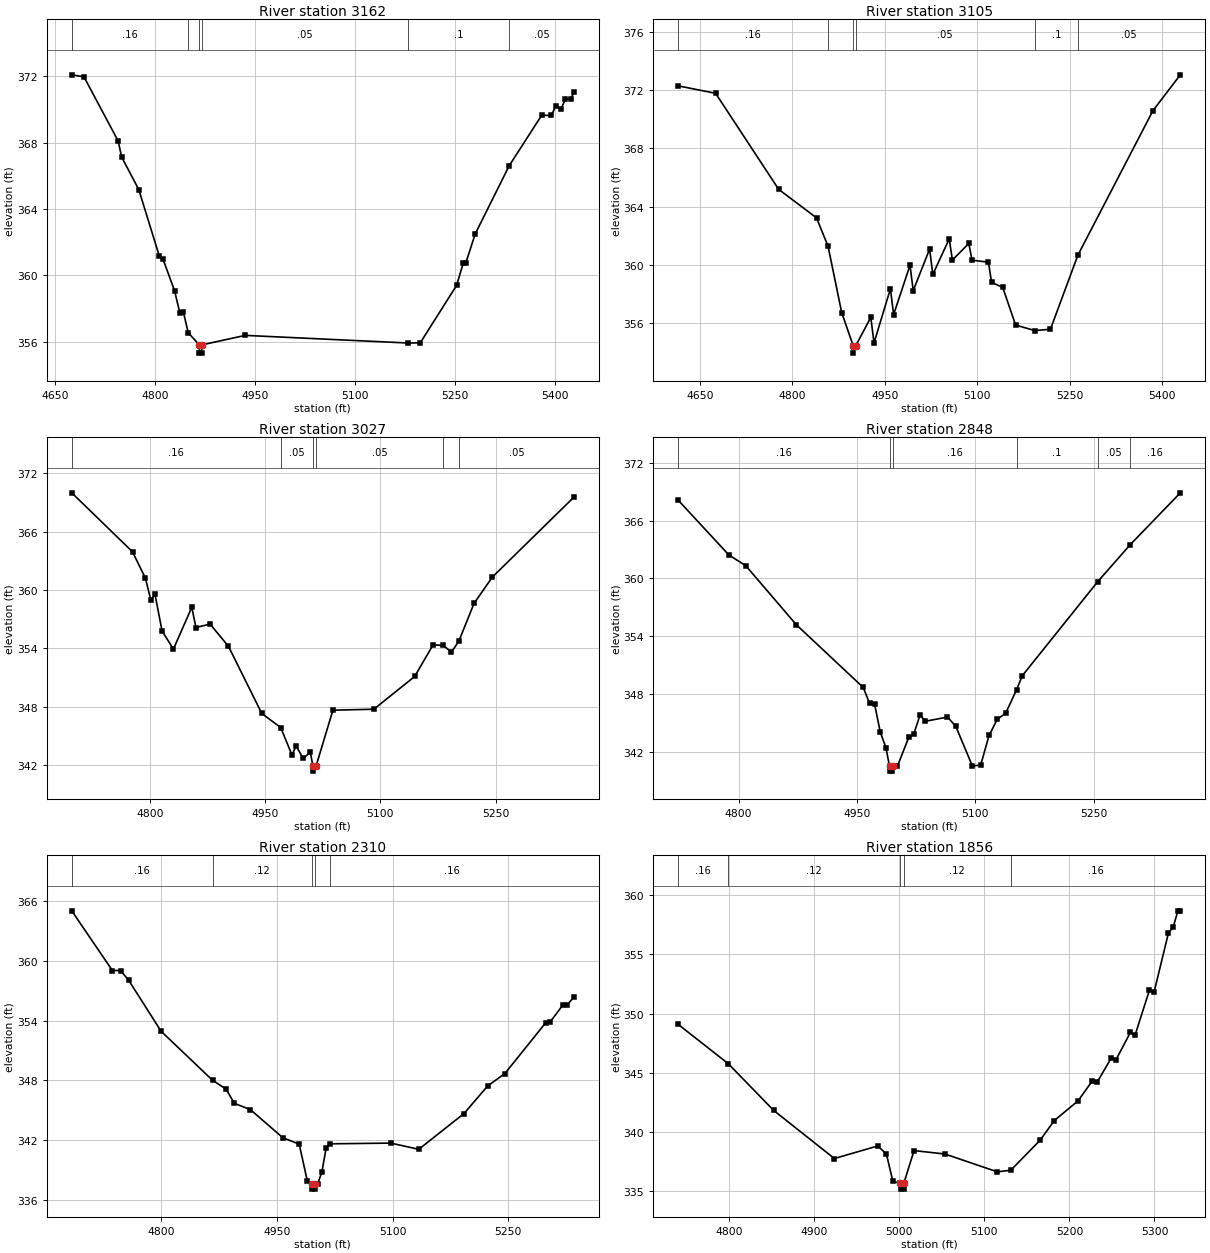
Type RM Length L Ch R = 1,3162,57,57,57
BEGIN DESCRIPTION:
Mapping XS 85b8b20d
END DESCRIPTION:
XS GIS Cut Line= 3
      3527837.74     10398351.55      3527282.18     10398156.23
      3527149.96     10398056.52
#Sta/Elev= 30
  4674.5  372.09  4692.8  371.97  4744.1  368.11  4749.5  367.13  4775.2  365.17
  4806.1  361.16  4811.4  361.00  4828.9  359.08  4837.1  357.70  4842.4  357.76
  4849.5  356.54  4866.1  355.81  4866.3  355.31  4869.8  355.31  4870.1  355.81
  4935.3  356.38  5179.6  355.92  5198.2  355.93  5252.9  359.40  5262.8  360.74
  5266.6  360.74  5280.8  362.50  5332.0  366.62  5380.7  369.65  5395.3  369.64
  5401.6  370.20  5409.9  370.03  5416.1  370.63  5424.4  370.63  5429.0  371.04
#Mann=6,-1,0
  4674.5    0.16       0  4849.5    0.05       0  4866.1   0.035       0
  4870.1    0.05       0  5179.6     0.1       0  5332.0    0.05       0
Bank Sta=4866.1,4870.1
Exp/Cntr=0.3,0.1

Type RM Length L Ch R = 1,3105,78,78,78
BEGIN DESCRIPTION:
MINERAL CR TRIB 1 9 0
END DESCRIPTION:
XS GIS Cut Line= 4
      3527931.37     10398285.82      3527659.78     10398227.52
      3527427.87     10398151.26      3527189.19     10397982.01
#Sta/Elev= 30
  4614.7  372.30  4675.3  371.79  4777.6  365.19  4839.0  363.23  4857.8  361.27
  4879.9  356.71  4898.6  354.43  4898.8  353.93  4902.6  354.43  4927.1  356.39
  4932.3  354.63  4958.9  358.35  4964.1  356.58  4990.7  359.97  4995.9  358.23
  5022.5  361.08  5027.7  359.34  5054.3  361.78  5059.5  360.33  5086.1  361.47
  5091.3  360.32  5117.9  360.18  5123.1  358.79  5141.1  358.45  5162.0  355.86
  5193.1  355.48  5218.5  355.57  5263.1  360.67  5384.7  370.59  5429.2  373.06
#Mann=6,-1,0
  4614.7    0.16       0  4857.8    0.05       0  4898.6   0.035       0
  4902.6    0.05       0  5193.1     0.1       0  5263.1    0.05       0
Bank Sta=4898.6,4902.6
Exp/Cntr=0.3,0.1

Type RM Length L Ch R = 1,3027,179,179,179
BEGIN DESCRIPTION:
Mapping XS a43ef7f2
END DESCRIPTION:
XS GIS Cut Line= 2
      3527850.79     10398236.54      3527246.24     10397987.35
#Sta/Elev= 30
  4698.0  370.01  4777.1  363.94  4793.9  361.23  4801.0  358.96  4806.4  359.56
  4815.6  355.79  4830.4  353.93  4854.3  358.23  4859.7  356.15  4878.2  356.50
  4902.1  354.21  4945.4  347.31  4970.2  345.85  4984.8  343.02  4990.2  343.96
  4999.4  342.68  5008.7  343.31  5012.1  341.87  5012.4  341.37  5016.1  341.87
  5038.1  347.64  5091.4  347.74  5144.6  351.11  5168.6  354.37  5181.8  354.30
  5192.5  353.62  5202.1  354.74  5221.9  358.63  5245.8  361.34  5351.9  369.56
#Mann=6,-1,0
  4698.0    0.16       0  4970.2    0.05       0  5012.1   0.035       0
  5016.1    0.05       0  5181.8     0.1       0  5202.1    0.05       0
Bank Sta=5012.1,5016.1
Exp/Cntr=0.3,0.1

Type RM Length L Ch R = 1,2848,538,538,538
BEGIN DESCRIPTION:
MINERAL CR TRIB 1 7 1
END DESCRIPTION:
XS GIS Cut Line= 3
      3527842.12     10398141.65      3527592.11     10397941.64
      3527292.11     10397841.64
#Sta/Elev= 30
  4723.6  368.12  4787.7  362.45  4809.3  361.32  4873.3  355.20  4958.1  348.69
  4966.1  347.05  4972.5  346.95  4979.7  344.06  4986.9  342.43  4991.4  340.51
  4991.6  340.01  4995.1  340.01  4995.4  340.51  5001.4  340.51  5015.8  343.52
  5022.2  343.88  5030.2  345.85  5036.6  345.18  5064.9  345.62  5075.4  344.66
  5096.5  340.53  5107.0  340.65  5117.6  343.72  5128.1  345.40  5138.6  346.01
  5152.5  348.47  5159.7  349.91  5255.3  359.67  5296.4  363.50  5360.0  368.89
#Mann=6,-1,0
  4723.6    0.16       0  4991.4    0.07       0  4995.4    0.16       0
  5152.5     0.1       0  5255.3    0.05       0  5296.4    0.16       0
Bank Sta=4991.4,4995.4
Exp/Cntr=0.3,0.1

Type RM Length L Ch R = 1,2310,454,454,454
BEGIN DESCRIPTION:
MINERAL CR TRIB 1 7 0
END DESCRIPTION:
XS GIS Cut Line= 3
      3527942.12     10397941.68      3527842.11     10397641.64
      3527542.09     10397491.63
#Sta/Elev= 30
  4683.6  364.99  4736.3  359.01  4746.9  359.01  4757.4  358.04  4799.6  352.92
  4866.4  348.01  4883.9  347.13  4894.5  345.71  4915.5  345.07  4957.7  342.25
  4978.8  341.62  4989.3  337.94  4995.2  337.61  4995.5  337.11  4999.0  337.11
  4999.2  337.61  5002.7  337.61  5008.3  338.85  5013.8  341.24  5018.6  341.65
  5097.7  341.72  5134.0  341.10  5192.7  344.68  5223.5  347.45  5245.8  348.69
  5298.9  353.79  5304.5  353.85  5321.3  355.58  5326.9  355.56  5335.3  356.38
#Mann=5,-1,0
  4683.6    0.16       0  4866.4    0.12       0  4995.2    0.07       0
  4999.2    0.12       0  5018.6    0.16       0
Bank Sta=4995.2,4999.2
Exp/Cntr=0.3,0.1

Type RM Length L Ch R = 1,1856,449,449,449
BEGIN DESCRIPTION:
MINERAL CR TRIB 1 6 0
END DESCRIPTION:
XS GIS Cut Line= 3
      3528242.11     10397641.65      3528192.11     10397391.64
      3528042.09     10397091.61
#Sta/Elev= 30
  4740.0  349.09  4798.8  345.78  4852.2  341.84  4923.6  337.78  4974.6  338.84
  4984.8  338.16  4992.4  335.85  5001.3  335.70  5001.6  335.20  5005.1  335.20
  5005.3  335.70  5017.3  338.45  5053.7  338.16  5115.1  336.66  5131.0  336.79
  5165.5  339.32  5182.2  340.98  5210.2  342.65  5227.0  344.34  5232.5  344.20
  5249.3  346.27  5254.9  346.13  5271.7  348.42  5277.3  348.21  5294.0  351.96
  5299.6  351.83  5316.4  356.79  5322.0  357.30  5327.6  358.67  5330.4  358.67
#Mann=5,-1,0
  4740.0    0.16       0  4798.8    0.12       0  5001.3    0.07       0
  5005.3    0.12       0  5131.0    0.16       0
Bank Sta=5001.3,5005.3
Exp/Cntr=0.3,0.1

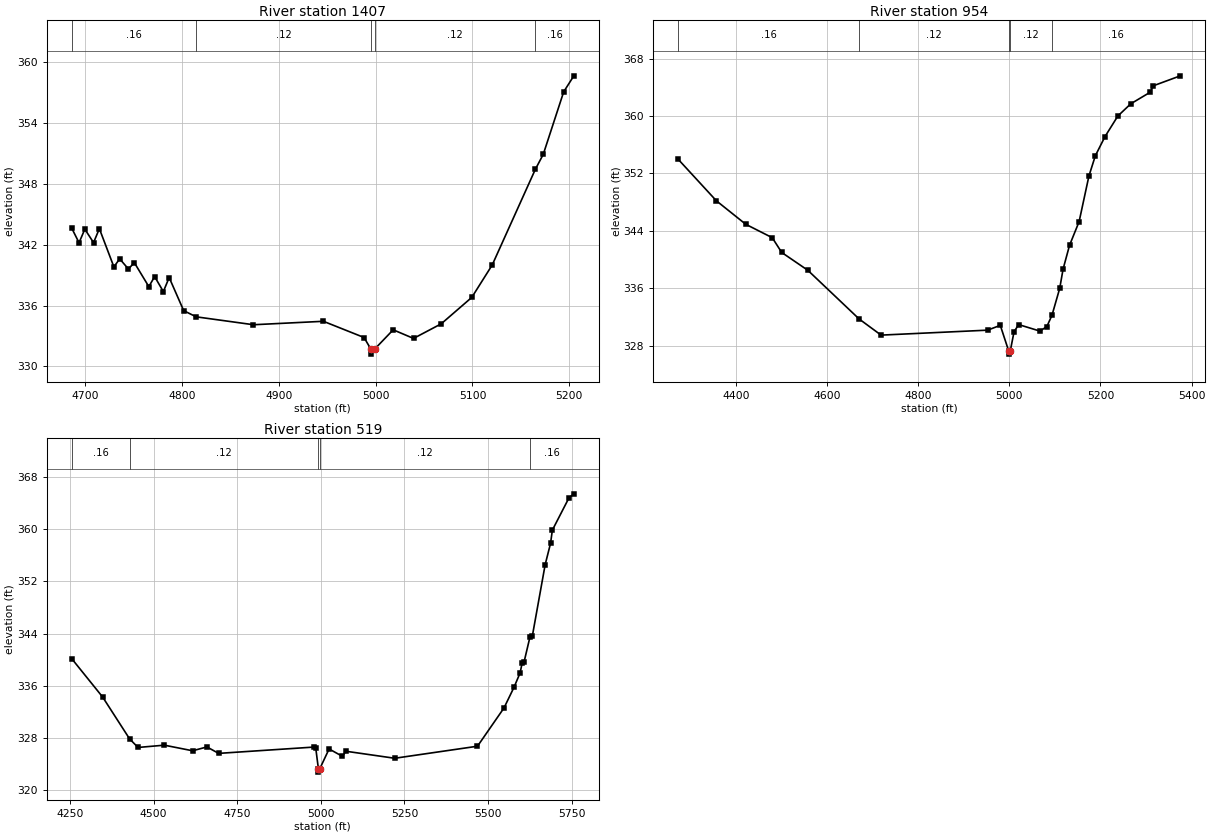
Type RM Length L Ch R = 1,1407,453,453,453
BEGIN DESCRIPTION:
MINERAL CR TRIB 1 5 0
END DESCRIPTION:
XS GIS Cut Line= 3
      3528442.13     10397591.60      3528642.11     10397291.64
      3528692.10     10397141.66
#Sta/Elev= 30
  4686.1  343.64  4693.6  342.21  4699.6  343.55  4708.6  342.22  4714.6  343.60
  4729.6  339.83  4735.6  340.62  4744.6  339.62  4750.7  340.25  4765.7  337.88
  4771.7  338.87  4780.7  337.39  4786.7  338.78  4801.7  335.51  4814.6  334.90
  4873.8  334.12  4946.0  334.46  4988.0  332.86  4995.0  331.72  4995.3  331.22
  4999.0  331.72  5018.1  333.62  5039.1  332.77  5067.7  334.21  5099.3  336.82
  5120.4  340.02  5165.0  349.47  5173.1  350.93  5194.2  357.10  5204.7  358.68
#Mann=5,-1,0
  4686.1    0.16       0  4814.6    0.12       0  4995.0    0.07       0
  4999.0    0.12       0  5165.0    0.16       0
Bank Sta=4995,4999
Exp/Cntr=0.3,0.1

Type RM Length L Ch R = 1,954,435,435,435
BEGIN DESCRIPTION:
MINERAL CR TRIB 1 2 2 0
END DESCRIPTION:
XS GIS Cut Line= 4
      3528816.51     10397954.38      3529000.93     10397813.35
      3529059.53     10397253.46      3528836.56     10397043.48
#Sta/Elev= 30
  4273.8  353.95  4357.5  348.17  4421.9  344.90  4480.0  343.03  4500.8  340.97
  4558.0  338.49  4670.6  331.70  4718.8  329.45  4952.3  330.14  4980.3  330.81
  4998.4  327.30  4998.6  326.80  5002.4  327.30  5010.4  329.90  5020.5  330.92
  5067.3  330.01  5082.4  330.64  5093.7  332.22  5110.7  335.98  5118.0  338.64
  5132.2  341.97  5153.2  345.27  5174.7  351.62  5188.8  354.45  5209.9  357.11
  5238.2  359.99  5266.5  361.69  5309.0  363.30  5315.9  364.20  5375.2  365.59
#Mann=5,-1,0
  4273.8    0.16       0  4670.6    0.12       0  4998.4    0.07       0
  5002.4    0.12       0  5093.7    0.16       0
Bank Sta=4998.4,5002.4
Exp/Cntr=0.3,0.1

Type RM Length L Ch R = 1,519,0,0,0
BEGIN DESCRIPTION:
MINERAL CR TRIB 1 1 2 0
END DESCRIPTION:
XS GIS Cut Line= 4
      3529092.13     10397841.61      3529440.44     10397438.29
      3529433.68     10397049.86      3528892.12     10396841.65
#Sta/Elev= 30
  4255.2  340.13  4347.6  334.24  4428.1  327.82  4453.4  326.50  4532.1  326.85
  4616.6  325.99  4659.4  326.58  4694.5  325.59  4979.7  326.56  4984.8  326.45
  4992.8  323.21  4993.0  322.71  4996.8  323.21  5024.8  326.27  5064.8  325.13
  5074.8  325.92  5221.1  324.84  5468.6  326.69  5547.9  332.57  5577.9  335.75
  5596.1  337.96  5602.5  339.55  5607.9  339.63  5625.8  343.52  5632.5  343.57
  5671.1  354.60  5687.2  357.87  5692.5  359.88  5741.8  364.80  5756.8  365.46
#Mann=5,-1,0
  4255.2    0.16       0  4428.1    0.12       0  4992.8    0.07       0
  4996.8    0.12       0  5625.8    0.16       0
Bank Sta=4992.8,4996.8
Exp/Cntr=0.3,0.1

Chan Stop Cuts=-1