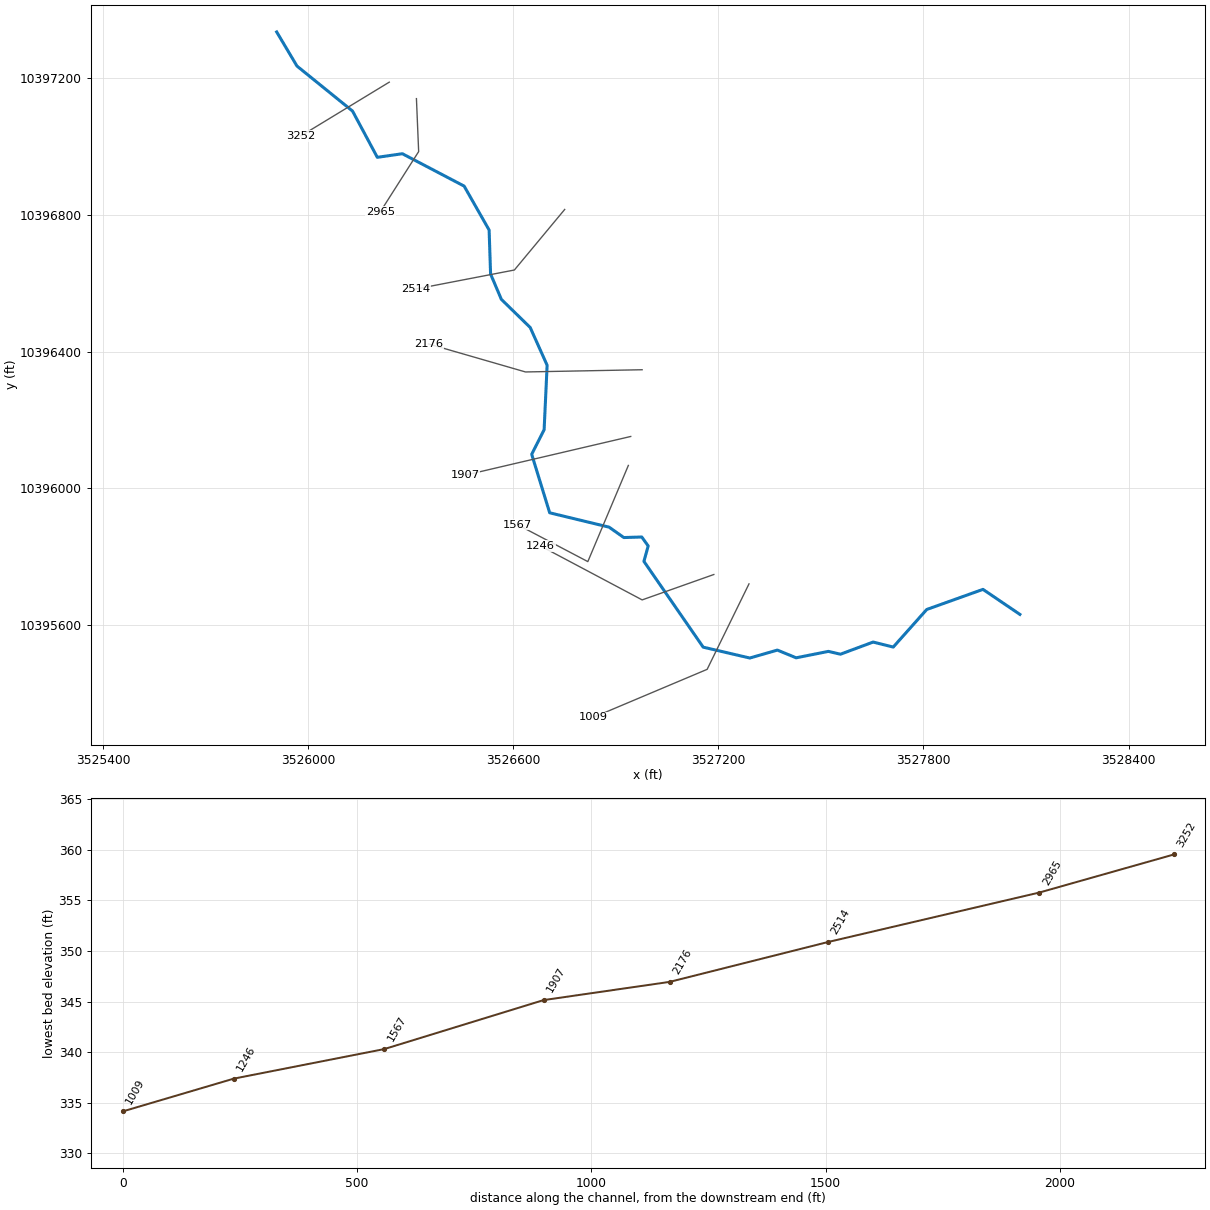
--- MINERAL CR TRIB 2 1.prj (project) ---

Proj Title=MINERAL CR TRIB 2 1 Base Level Engineering
Current Plan=p01
Default Exp/Contr=0.3,0.1
English Units
Geom File=g01
Flow File=f01
Plan File=p01
Y Axis Title=Elevation
X Axis Title(PF)=Main Channel Distance
X Axis Title(XS)=Station
BEGIN DESCRIPTION:
MINERAL CR TRIB 2 1
END DESCRIPTION:
DSS Export Rating Curves= 0
DSS Export Rating Curve Sorted= 0
DSS Export Volume Flow Curves= 0
DXF OffsetX= 0
DXF OffsetY= 0
DXF ScaleX= 1
DXF ScaleY= 10

--- MINERAL CR TRIB 2 1.p01 (plan) ---

Plan Title=Multiple Run
Short Identifier=Multiple
Geom File=g01
Flow File=f01
Subcritical Flow
K Sum by GR= 0
Std Step Tol= 0.01
Critical Tol= 0.01
Num of Std Step Trials= 20
Max Error Tol= 0.3
Flow Tol Ratio= 0.001
Split Flow NTrial= 30
Split Flow Tol= 0.02
Split Flow Ratio= 0.02
Log Output Level= 0
Friction Slope Method= 1
Unsteady Friction Slope Method= 2
Unsteady Bridges Friction Slope Method= 1
Parabolic Critical Depth
Global Vel Dist=  1 , 1 , 1
Global Log Level= 0
CheckData=True
Encroach Param= -1, 0, 0, 0
BEGIN DESCRIPTION:
Multiple Run
END DESCRIPTION:

--- MINERAL CR TRIB 2 1.f01 (steady flow) ---

Flow Title=Multiple
Program Version=4.10
Number of Profiles= 7
Profile Names=10-year,25-year,50-year,1pct_min,100-year,1pct_plu,500-year
River Rch & RM=MINERAL CR TRIB,Reach-1         ,3252
     309     399     468     404     546     739     738
Boundary for River Rch & Prof#=MINERAL CR TRIB,Reach-1         , 1
Up Type= 0
Dn Type= 3
Dn Slope=0.01218
Boundary for River Rch & Prof#=MINERAL CR TRIB,Reach-1         , 2
Up Type= 0
Dn Type= 3
Dn Slope=0.01218
Boundary for River Rch & Prof#=MINERAL CR TRIB,Reach-1         , 3
Up Type= 0
Dn Type= 3
Dn Slope=0.01218
Boundary for River Rch & Prof#=MINERAL CR TRIB,Reach-1         , 4
Up Type= 0
Dn Type= 3
Dn Slope=0.01218
Boundary for River Rch & Prof#=MINERAL CR TRIB,Reach-1         , 5
Up Type= 0
Dn Type= 3
Dn Slope=0.01218
Boundary for River Rch & Prof#=MINERAL CR TRIB,Reach-1         , 6
Up Type= 0
Dn Type= 3
Dn Slope=0.01218
Boundary for River Rch & Prof#=MINERAL CR TRIB,Reach-1         , 7
Up Type= 0
Dn Type= 3
Dn Slope=0.01218
DSS Import GetInterval= 0
DSS Import GetPeak= 0
DSS Import FillOption= 0

--- MINERAL CR TRIB 2 1.g01 (geometry) ---

Geom Title=Existing Conditions
Program Version=4.10

River Reach=MINERAL CR TRIB ,Reach-1
Reach XY= 30
      3525908.39     10397335.21      3525967.69     10397235.48
      3526130.22      10397103.8      3526202.73     10396968.51
      3526275.99     10396979.03      3526456.63     10396884.37
      3526529.72     10396755.83      3526533.99     10396627.24
      3526565.48     10396553.13       3526649.9     10396470.77
      3526699.35     10396360.44      3526690.58     10396171.77
      3526654.23     10396099.95      3526706.84     10395928.84
      3526880.63     10395886.83      3526923.73     10395856.42
       3526976.1     10395858.05      3526994.96     10395831.81
      3526982.47     10395786.73      3527155.76     10395535.86
      3527292.11     10395504.05      3527372.73     10395527.26
      3527427.62     10395504.71      3527522.12     10395523.46
      3527557.29      10395515.2      3527652.76     10395550.73
      3527711.67     10395536.08      3527809.63       10395646.
      3527974.13     10395704.86      3528082.11     10395631.64

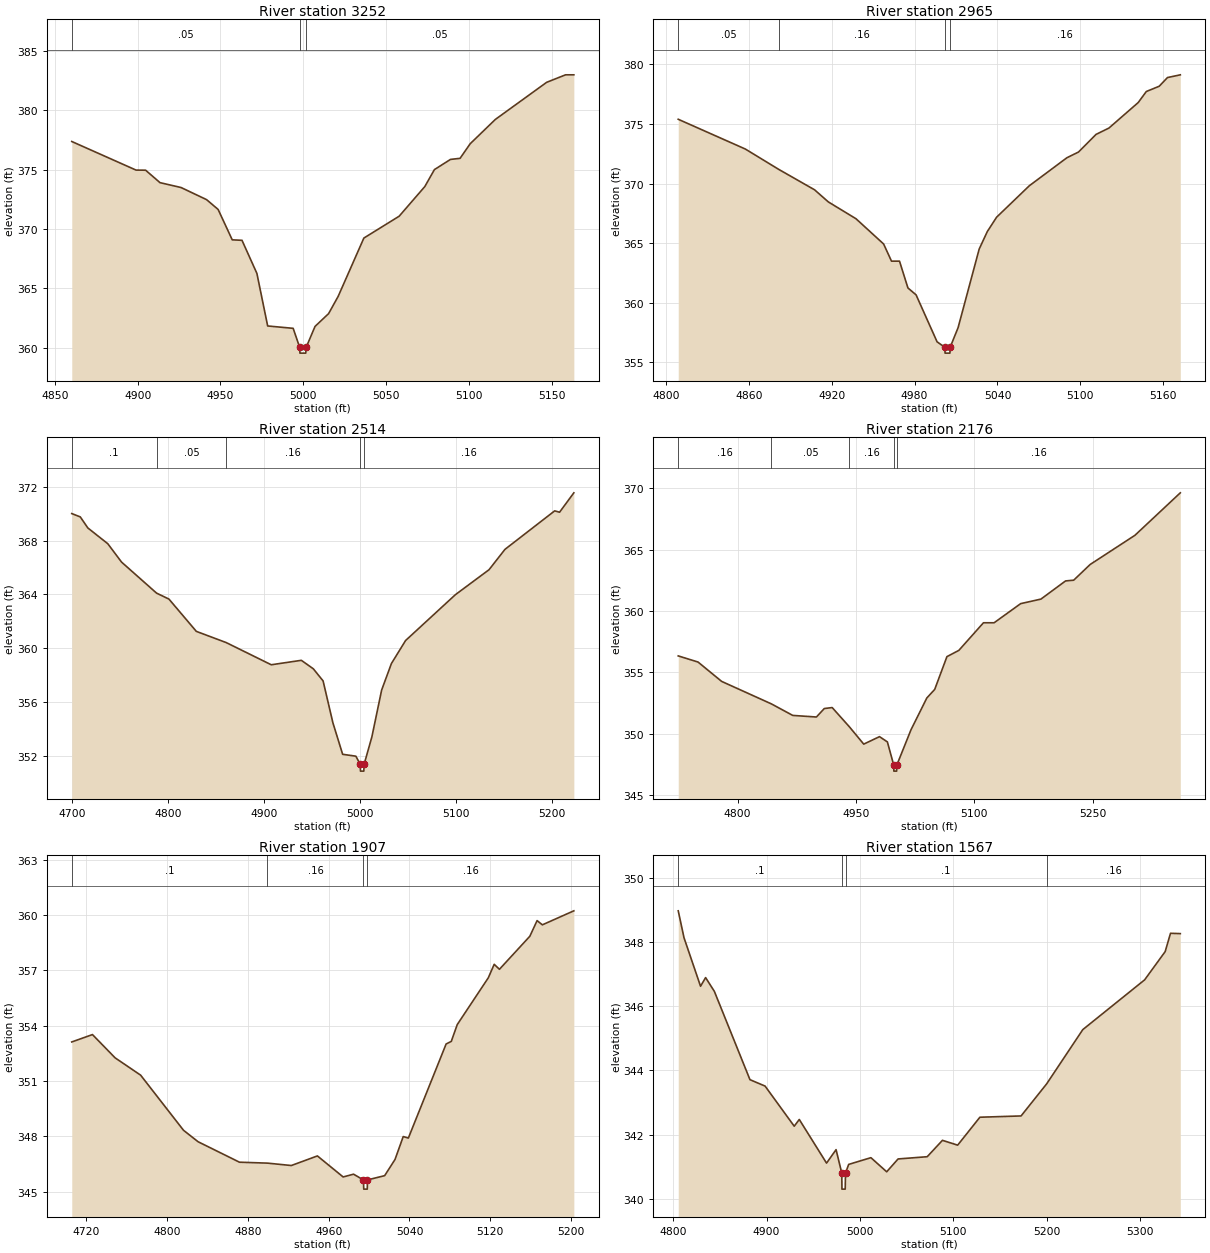
Type RM Length L Ch R = 1 ,3252    ,287,287,287
BEGIN DESCRIPTION:
MINERAL CR TRIB 2 1 4 1
END DESCRIPTION:
XS GIS Cut Line= 2
      3526237.65     10397188.38      3525978.59     10397030.85
#Sta/Elev= 30
  4860.2  377.37    4899  374.96  4904.8  374.95  4913.5   373.9  4926.2  373.49
  4941.6  372.47  4948.6  371.64  4957.1  369.08    4963  369.04    4972  366.25
  4978.5  361.82  4993.9  361.62  4997.8  360.03    4998  359.53  5001.5  359.53
  5001.8  360.03  5007.1  361.78  5015.3  362.86  5021.1  364.32  5036.6  369.23
  5057.9  371.07  5073.4  373.57  5079.2     375  5088.9  375.86  5094.7  375.95
  5100.8  377.18    5116  379.23    5147  382.36  5158.4  382.99  5163.4  382.99
#Mann= 3 ,-1 , 0
  4860.2     .05       0  4997.8     .03       0  5001.8     .05       0
Bank Sta=4997.8,5001.8
XS Rating Curve= 0 ,0
Exp/Cntr=0.3,0.1

Type RM Length L Ch R = 1 ,2965    ,451,451,451
BEGIN DESCRIPTION:
MINERAL CR TRIB 2 1 3 1
END DESCRIPTION:
XS GIS Cut Line= 3
      3526317.11     10397140.21      3526323.62     10396985.27
      3526211.64     10396809.48
#Sta/Elev= 30
  4808.9   375.4  4857.5   372.9  4881.7  371.19  4907.6  369.48  4917.6  368.46
  4937.6  367.05  4957.6  364.93  4963.3  363.49  4969.1  363.49  4975.2  361.24
  4981.1  360.66  4996.3  356.72  5001.8  356.27  5002.1  355.77  5005.6  355.77
  5005.8  356.27  5011.5   357.9  5026.8  364.51  5032.7  365.98  5039.4  367.18
  5063.1  369.82  5090.3  372.17  5098.7  372.65  5111.4  374.13  5120.7  374.66
  5141.9   376.8  5147.8  377.73  5157.1  378.17  5163.1   378.9  5172.4  379.13
#Mann= 4 ,-1 , 0
  4808.9     .05       0  4881.7     .16       0  5001.8     .07       0
  5005.8     .16       0
Bank Sta=5001.8,5005.8
XS Rating Curve= 0 ,0
Exp/Cntr=0.3,0.1

Type RM Length L Ch R = 1 ,2514    ,338,338,338
BEGIN DESCRIPTION:
MINERAL CR TRIB 2 1 2 0
END DESCRIPTION:
XS GIS Cut Line= 3
      3526750.73     10396816.03      3526603.57     10396638.92
      3526315.16      10396583.3
#Sta/Elev= 30
  4699.3  370.01  4708.2  369.76  4716.1  368.94  4736.9  367.77  4751.2  366.41
  4787.8   364.1  4800.7  363.66  4829.3  361.26  4860.4  360.43  4907.5  358.78
  4938.9  359.11  4951.4  358.48  4961.6  357.58  4971.8  354.48    4982  352.13
  4995.8  351.99  5000.4  351.38  5000.6  350.88  5004.1  350.88  5004.4  351.38
  5012.5  353.42  5022.7   356.9  5032.9  358.87  5047.7  360.58  5099.6  363.98
  5134.8  365.84  5151.4  367.35  5203.3  370.21  5208.4  370.11  5223.3  371.55
#Mann= 5 ,-1 , 0
  4699.3      .1       0  4787.8     .05       0  4860.4     .16       0
  5000.4     .07       0  5004.4     .16       0
Bank Sta=5000.4,5004.4
XS Rating Curve= 0 ,0
Exp/Cntr=0.3,0.1

Type RM Length L Ch R = 1 ,2176    ,269,269,269
BEGIN DESCRIPTION:
Mapping XS 913c841e
END DESCRIPTION:
XS GIS Cut Line= 3
      3526977.24     10396347.25      3526636.12     10396340.74
      3526352.31     10396422.76
#Sta/Elev= 30
  4724.7  356.33  4749.8  355.83  4779.8  354.25  4842.8  352.42  4869.9  351.48
  4899.9  351.35  4909.9  352.04  4919.9  352.12  4941.6  350.56  4959.9  349.14
  4979.9  349.75  4989.9  349.32  4997.9  347.44  4998.1  346.94  5001.6  346.94
  5001.9  347.44  5019.9  350.32  5039.9   352.9  5049.9   353.6  5065.4  356.27
  5080.5  356.78  5111.7  359.03  5125.2  359.03  5158.9  360.59  5184.6  360.96
  5215.8  362.44  5226.1   362.5    5247  363.78  5303.8  366.16  5361.3  369.62
#Mann= 5 ,-1 , 0
  4724.7     .16       0  4842.8     .05       0  4941.6     .16       0
  4997.9     .07       0  5001.9     .16       0
Bank Sta=4997.9,5001.9
XS Rating Curve= 0 ,0
Exp/Cntr=0.3,0.1

Type RM Length L Ch R = 1 ,1907    ,340,340,340
BEGIN DESCRIPTION:
MINERAL CR TRIB 2 1 5 0
END DESCRIPTION:
XS GIS Cut Line= 2
      3526943.88     10396152.07      3526459.64     10396038.85
#Sta/Elev= 30
  4705.5  353.12    4726  353.52  4748.4  352.26  4773.7  351.32  4816.2  348.33
  4830.6  347.71  4871.6   346.6  4899.3  346.55    4923  346.42  4948.8  346.94
  4974.3   345.8  4984.6  345.95  4994.4  345.64  4994.7  345.14  4998.2  345.14
  4998.4  345.64  5015.4  345.87  5025.7  346.75  5033.8  347.99  5038.9  347.91
  5076.3  353.01  5081.4  353.15  5087.3  354.06  5118.1   356.6  5123.9  357.33
  5129.1  357.06  5159.2  358.85  5166.4   359.7  5171.6  359.47  5202.8  360.23
#Mann= 4 ,-1 , 0
  4705.5      .1       0  4899.3     .16       0  4994.4     .07       0
  4998.4     .16       0
Bank Sta=4994.4,4998.4
XS Rating Curve= 0 ,0
Exp/Cntr=0.3,0.1

Type RM Length L Ch R = 1 ,1567    ,321,321,321
BEGIN DESCRIPTION:
MINERAL CR TRIB 2 1 2 2
END DESCRIPTION:
XS GIS Cut Line= 3
      3526936.92     10396067.34      3526818.41     10395786.05
       3526612.7     10395894.11
#Sta/Elev= 30
  4805.4  348.97  4811.6  348.13  4829.3  346.62  4834.7  346.89  4844.1  346.46
  4882.2  343.71  4898.4  343.51  4929.6  342.26    4935  342.47  4964.2  341.11
  4974.4  341.53  4980.5   340.8  4980.7   340.3  4984.2   340.3  4984.5   340.8
  4987.9  341.07  5011.7  341.28  5028.6  340.84  5040.8  341.24    5072  341.31
  5088.3  341.82  5104.6  341.67  5128.4  342.54  5172.5  342.58  5199.9  343.58
  5238.6  345.27  5304.8  346.82  5326.8   347.7  5332.5  348.27    5343  348.26
#Mann= 4 ,-1 , 0
  4805.4      .1       0  4980.5     .07       0  4984.5      .1       0
  5199.9     .16       0
Bank Sta=4980.5,4984.5
XS Rating Curve= 0 ,0
Exp/Cntr=0.3,0.1

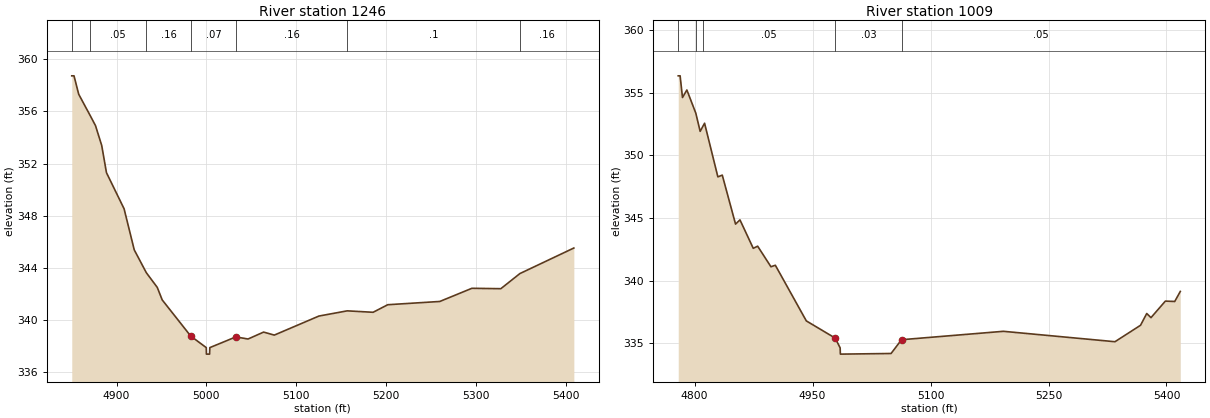
Type RM Length L Ch R = 1 ,1246    ,237,237,237
BEGIN DESCRIPTION:
MINERAL CR TRIB 2 1 4 0
END DESCRIPTION:
XS GIS Cut Line= 3
      3527186.95     10395748.31      3526977.27     10395674.07
      3526680.41     10395831.61
#Sta/Elev= 30
  4850.2  358.73  4852.7  358.73  4857.9  357.32  4870.7  355.68  4876.6  354.91
  4883.5  353.39  4888.8   351.3  4908.4  348.53  4919.7  345.38  4933.1  343.63
  4945.3   342.5  4950.8  341.54  4982.6  338.76  4999.8  337.88    5000  337.38
  5003.5  337.38  5003.8  337.88  5032.7   338.7  5046.3  338.54  5063.6  339.07
  5075.5  338.84  5125.1   340.3  5156.6   340.7  5185.4  340.59  5201.7  341.17
  5259.6  341.42  5295.3  342.43  5327.5   342.4  5348.7  343.56  5408.7  345.52
#Mann= 7 ,-1 , 0
  4850.2     .16       0  4870.7     .05       0  4933.1     .16       0
  4982.6     .07       0  5032.7     .16       0  5156.6      .1       0
  5348.7     .16       0
Bank Sta=4982.6,5032.7
XS Rating Curve= 0 ,0
Exp/Cntr=0.3,0.1

Type RM Length L Ch R = 1 ,1009    ,0,0,0
BEGIN DESCRIPTION:
MINERAL CR TRIB 2 1 3 2
END DESCRIPTION:
XS GIS Cut Line= 3
      3527289.76     10395720.93      3527167.37     10395470.95
      3526835.53     10395330.95
#Sta/Elev= 30
  4779.1  356.34  4781.5  356.34  4784.5  354.61  4790.1  355.21  4801.4  353.37
    4807  351.91    4810  352.26  4812.6  352.56  4829.5  348.28  4835.1  348.42
    4852  344.51  4857.6  344.85  4874.5  342.58  4880.1  342.75    4897  341.11
  4902.6  341.23    4942  336.79  4978.7  335.42    4985  334.64  4985.3  334.14
 5049.76  334.19  5063.1  335.29  5192.6  335.96  5334.5  335.13    5367  336.44
  5374.9  337.38  5380.3  337.05  5398.6  338.37  5410.5  338.34  5417.6  339.14
#Mann= 5 ,-1 , 0
  4779.1     .05       0  4801.4     .16       0    4810     .05       0
  4978.7     .03       0  5063.1     .05       0
Bank Sta=4978.7,5063.1
XS Rating Curve= 0 ,0
Exp/Cntr=0.3,0.1

Chan Stop Cuts=-1
Use User Specified Reach Order=0
Composite Channel Slope=5