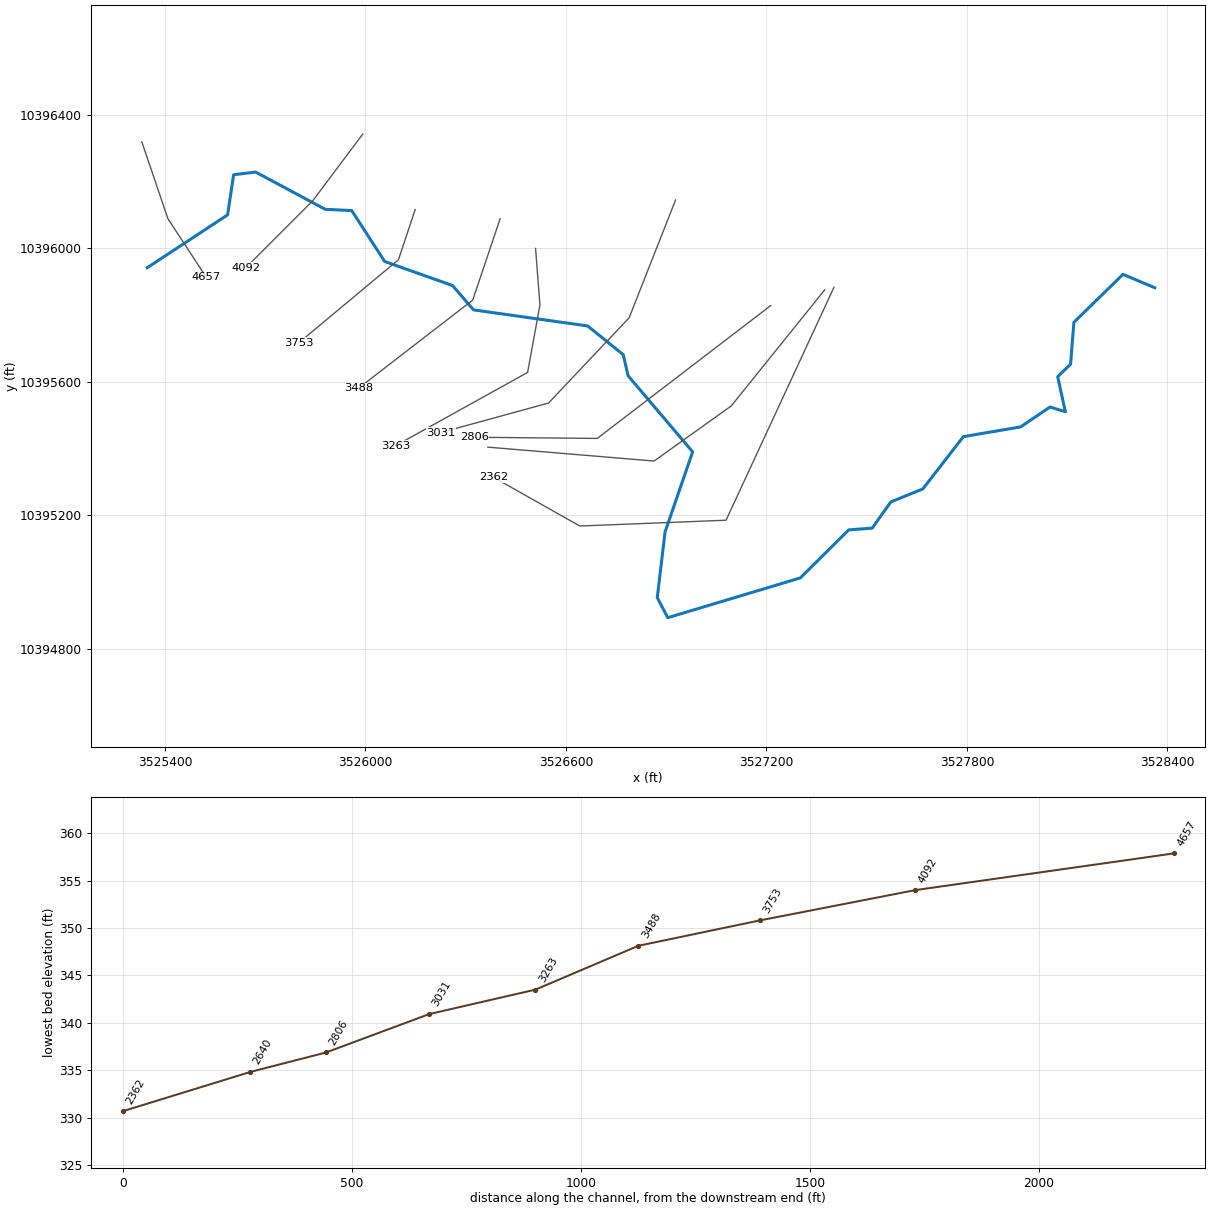
--- MINERAL CR TRIB 2.prj (project) ---

Proj Title=MINERAL CR TRIB 2 Base Level Engineering
Current Plan=p01
Default Exp/Contr=0.3,0.1
English Units
Geom File=g01
Flow File=f01
Plan File=p01
BEGIN DESCRIPTION:
MINERAL CR TRIB 2
END DESCRIPTION:

--- MINERAL CR TRIB 2.p01 (plan) ---

Plan Title=Multiple Run
Short Identifier=Multiple
Geom File=g01
Flow File=f01
Subcritical Flow
K Sum by GR= 0
Std Step Tol= 0.01
Critical Tol= 0.01
Num of Std Step Trials= 20
Max Error Tol= 0.3
Flow Tol Ratio= 0.001
Split Flow NTrial= 30
Split Flow Tol= 0.02
Split Flow Ratio= 0.02
Log Output Level= 0
Friction Slope Method= 1
Unsteady Friction Slope Method= 2
Unsteady Bridges Friction Slope Method= 1
Parabolic Critical Depth
Global Vel Dist=  1 , 1 , 1
Global Log Level= 0
CheckData=True
Encroach Param= -1, 0, 0, 0
BEGIN DESCRIPTION:
Multiple Run
END DESCRIPTION:

--- MINERAL CR TRIB 2.f01 (steady flow) ---

Flow Title=Multiple
Number of Profiles=7
Profile Names=10-year,25-year,50-year,1pct_min,100-year,1pct_plu,500-year
River Rch & RM= MINERAL CR TRIB ,Reach-1,4657
     389     508     603     524     709     958     974
Boundary for River Rch & Prof#=MINERAL CR TRIB ,Reach-1,1
Up Type=0
Dn Type=3
Dn Slope=0.005
Boundary for River Rch & Prof#=MINERAL CR TRIB ,Reach-1,2
Up Type=0
Dn Type=3
Dn Slope=0.005
Boundary for River Rch & Prof#=MINERAL CR TRIB ,Reach-1,3
Up Type=0
Dn Type=3
Dn Slope=0.005
Boundary for River Rch & Prof#=MINERAL CR TRIB ,Reach-1,4
Up Type=0
Dn Type=3
Dn Slope=0.005
Boundary for River Rch & Prof#=MINERAL CR TRIB ,Reach-1,5
Up Type=0
Dn Type=3
Dn Slope=0.005
Boundary for River Rch & Prof#=MINERAL CR TRIB ,Reach-1,6
Up Type=0
Dn Type=3
Dn Slope=0.005
Boundary for River Rch & Prof#=MINERAL CR TRIB ,Reach-1,7
Up Type=0
Dn Type=3
Dn Slope=0.005

--- MINERAL CR TRIB 2.g01 (geometry) ---

Geom Title=Existing Conditions

River Reach=MINERAL CR TRIB ,Reach-1
Reach XY= 30
      3525347.11     10395941.64      3525587.51     10396099.71
      3525605.42     10396219.77      3525671.31     10396227.75
      3525879.46     10396116.34      3525959.03     10396112.42
      3526057.40     10395960.16      3526260.63     10395888.20
      3526323.47     10395815.25      3526665.01     10395767.25
      3526771.37     10395681.28      3526786.03     10395618.08
      3526979.13     10395390.46      3526896.63     10395150.87
      3526873.31     10394954.23      3526904.69     10394894.11
      3527301.48     10395013.20      3527446.22     10395156.92
      3527516.54     10395162.14      3527572.14     10395240.60
      3527667.94     10395279.44      3527789.39     10395435.91
      3527960.58     10395465.12      3528048.78     10395524.71
      3528094.56     10395510.39      3528071.56     10395615.54
      3528110.03     10395652.53      3528120.15     10395778.24
      3528267.06     10395921.61      3528362.11     10395881.64

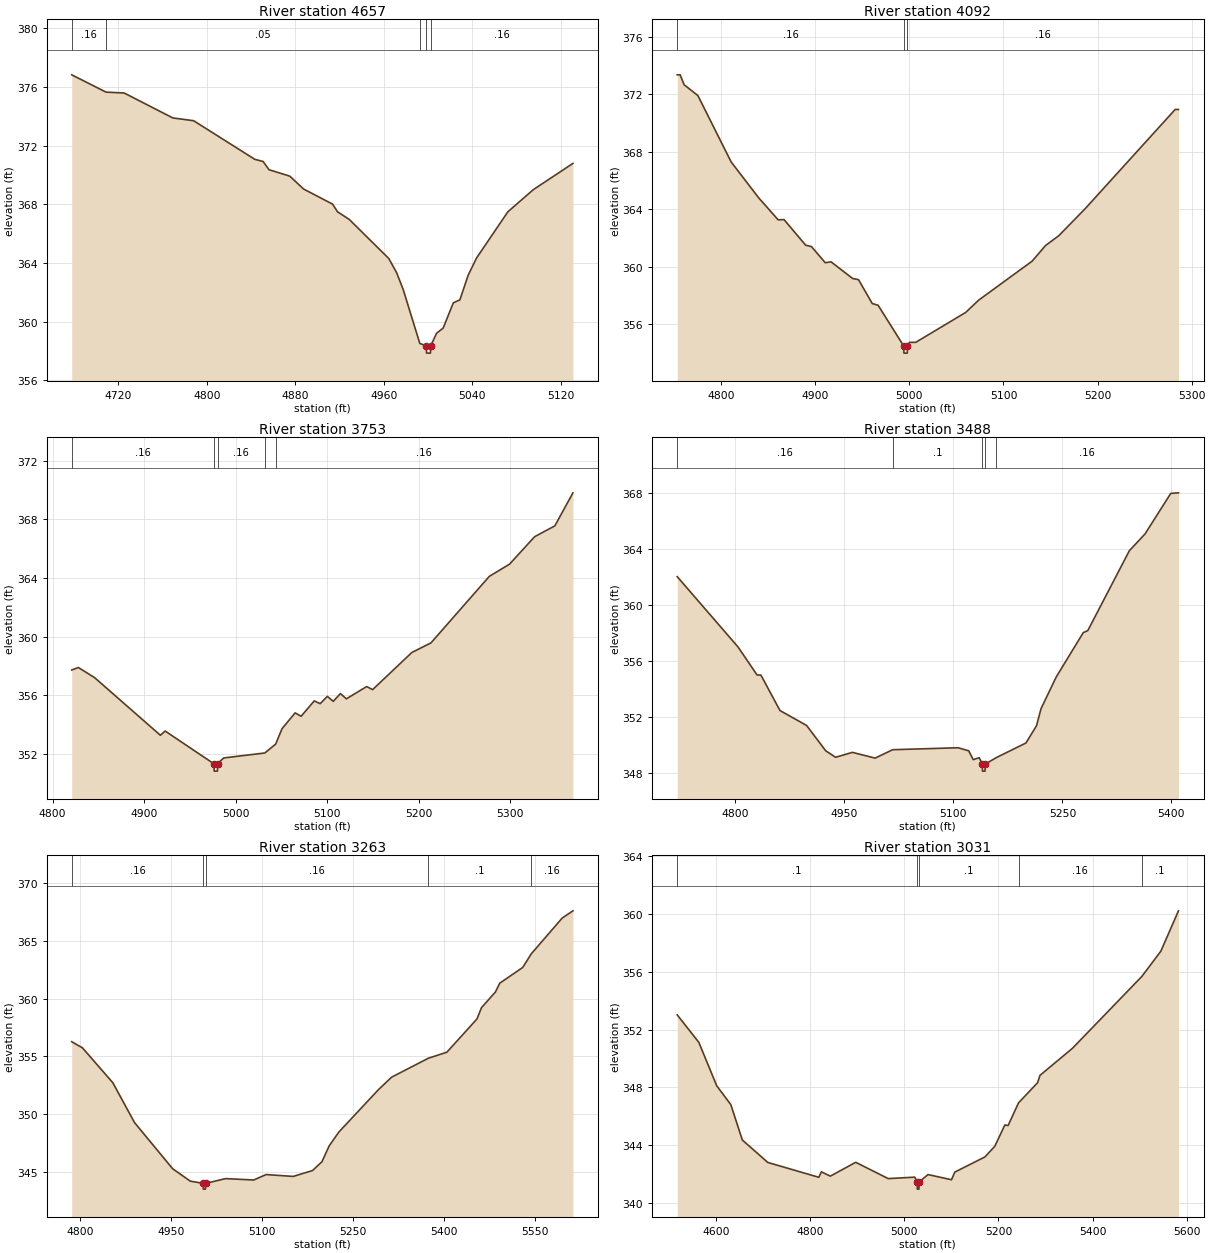
Type RM Length L Ch R = 1,4657,565,565,565
BEGIN DESCRIPTION:
MINERAL CR TRIB 2 4 1
END DESCRIPTION:
XS GIS Cut Line= 3
      3525330.73     10396318.23      3525408.85     10396088.21
      3525523.88     10395912.42
#Sta/Elev= 30
  4677.9  376.84  4708.9  375.66  4725.3  375.60  4769.3  373.90  4788.1  373.71
  4843.3  371.08  4850.9  370.93  4856.2  370.37  4875.0  369.93  4887.5  369.05
  4913.7  368.02  4918.1  367.50  4928.7  366.98  4964.5  364.31  4971.5  363.35
  4977.4  362.22  4992.5  358.52  4998.4  358.36  4998.6  357.86  5002.1  357.86
  5002.4  358.36  5007.6  359.21  5013.6  359.57  5022.8  361.29  5028.7  361.49
  5036.2  363.17  5043.8  364.35  5072.1  367.50  5095.1  369.01  5130.9  370.80
#Mann=5,-1,0
  4677.9    0.16       0  4708.9    0.05       0  4992.5    0.16       0
  4998.4    0.07       0  5002.4    0.16       0
Bank Sta=4998.4,5002.4
Exp/Cntr=0.3,0.1

Type RM Length L Ch R = 1,4092,339,339,339
BEGIN DESCRIPTION:
MINERAL CR TRIB 2 3 2
END DESCRIPTION:
XS GIS Cut Line= 3
      3525992.10     10396341.64      3525842.11     10396141.64
      3525642.13     10395941.67
#Sta/Elev= 30
  4753.2  373.35  4756.3  373.35  4760.5  372.66  4775.1  371.91  4810.5  367.29
  4839.7  364.80  4860.5  363.26  4866.7  363.28  4889.7  361.50  4895.9  361.40
  4910.5  360.28  4916.7  360.34  4939.7  359.18  4945.9  359.10  4960.5  357.44
  4966.7  357.32  4993.9  354.49  4994.2  353.99  4997.7  353.99  4997.9  354.49
  5000.1  354.74  5006.7  354.74  5059.8  356.82  5073.9  357.69  5130.5  360.39
  5144.6  361.47  5158.8  362.16  5187.0  364.05  5282.5  370.94  5286.0  370.94
#Mann=3,-1,0
  4753.2    0.16       0  4993.9    0.07       0  4997.9    0.16       0
Bank Sta=4993.9,4997.9
Exp/Cntr=0.3,0.1

Type RM Length L Ch R = 1,3753,265,265,265
BEGIN DESCRIPTION:
MINERAL CR TRIB 2 2 1
END DESCRIPTION:
XS GIS Cut Line= 3
      3526148.78     10396115.40      3526098.79     10395965.43
      3525799.48     10395716.00
#Sta/Elev= 30
  4821.0  357.71  4828.3  357.88  4846.0  357.19  4917.9  353.25  4923.1  353.54
  4976.4  351.30  4976.7  350.80  4980.2  350.80  4980.4  351.30  4987.0  351.70
  5032.0  352.04  5043.9  352.65  5050.8  353.70  5065.1  354.78  5071.7  354.55
  5086.0  355.60  5092.5  355.41  5100.3  355.91  5106.8  355.57  5114.6  356.10
  5121.1  355.74  5143.3  356.58  5149.8  356.37  5192.7  358.91  5213.5  359.56
  5277.3  364.11  5299.5  364.95  5326.8  366.82  5348.9  367.56  5368.7  369.82
#Mann=5,-1,0
  4821.0    0.16       0  4976.4    0.07       0  4980.4    0.16       0
  5032.0     0.1       0  5043.9    0.16       0
Bank Sta=4976.4,4980.4
Exp/Cntr=0.3,0.1

Type RM Length L Ch R = 1,3488,225,225,225
BEGIN DESCRIPTION:
Mapping XS 9fe3a9eb
END DESCRIPTION:
XS GIS Cut Line= 3
      3526403.03     10396088.09      3526321.02     10395844.65
      3525978.56     10395580.31
#Sta/Elev= 30
  4720.2  362.02  4803.8  357.00  4830.0  355.00  4835.3  354.99  4861.5  352.46
  4898.2  351.39  4924.5  349.58  4938.1  349.12  4961.2  349.47  4992.4  349.06
  5016.6  349.66  5106.6  349.80  5121.1  349.58  5127.4  348.95  5135.6  349.09
  5139.9  348.63  5140.1  348.13  5143.6  348.13  5143.9  348.63  5158.9  349.09
  5199.9  350.14  5214.4  351.37  5220.7  352.60  5241.5  354.85  5278.7  358.02
  5285.0  358.17  5342.1  363.87  5363.8  365.08  5399.1  367.97  5409.7  368.01
#Mann=5,-1,0
  4720.2    0.16       0  5016.6     0.1       0  5139.9    0.07       0
  5143.9     0.1       0  5158.9    0.16       0
Bank Sta=5139.9,5143.9
Exp/Cntr=0.3,0.1

Type RM Length L Ch R = 1,3263,232,232,232
BEGIN DESCRIPTION:
MINERAL CR TRIB 2 2 22
END DESCRIPTION:
XS GIS Cut Line= 4
      3526509.11     10395999.24      3526522.13     10395829.96
      3526485.24     10395628.14      3526090.23     10395408.93
#Sta/Elev= 30
  4786.3  356.27  4804.0  355.74  4854.1  352.72  4889.9  349.27  4952.7  345.28
  4981.9  344.20  5003.2  344.01  5003.4  343.51  5006.9  343.51  5007.2  344.01
  5040.2  344.42  5086.5  344.30  5106.9  344.77  5151.7  344.61  5183.5  345.12
  5199.1  345.89  5210.9  347.25  5226.9  348.45  5292.2  352.12  5313.9  353.20
  5374.5  354.84  5405.0  355.36  5454.7  358.24  5462.2  359.22  5485.1  360.57
  5492.4  361.34  5530.2  362.70  5544.3  363.88  5595.4  366.98  5613.0  367.60
#Mann=5,-1,0
  4786.3    0.16       0  5003.2    0.07       0  5007.2    0.16       0
  5374.5     0.1       0  5544.3    0.16       0
Bank Sta=5003.2,5007.2
Exp/Cntr=0.3,0.1

Type RM Length L Ch R = 1,3031,225,225,225
BEGIN DESCRIPTION:
MINERAL CR TRIB 2 3 1
END DESCRIPTION:
XS GIS Cut Line= 4
      3526928.08     10396144.21      3526789.19     10395791.77
      3526547.87     10395536.56      3526226.00     10395448.31
#Sta/Elev= 30
  4518.2  353.01  4564.0  351.11  4602.1  348.09  4631.9  346.79  4656.3  344.34
  4710.4  342.78  4818.7  341.75  4824.1  342.13  4843.1  341.83  4897.0  342.79
  4966.0  341.66  5022.2  341.76  5027.5  341.43  5027.7  340.93  5031.2  340.93
  5031.5  341.43  5050.5  341.94  5100.3  341.58  5107.2  342.11  5171.1  343.16
  5192.1  343.90  5213.6  345.38  5220.4  345.34  5242.5  346.91  5283.0  348.31
  5288.1  348.82  5357.1  350.70  5504.3  355.68  5544.6  357.43  5582.0  360.23
#Mann=5,-1,0
  4518.2     0.1       0  5027.5    0.07       0  5031.5     0.1       0
  5242.5    0.16       0  5504.3     0.1       0
Bank Sta=5027.5,5031.5
Exp/Cntr=0.3,0.1

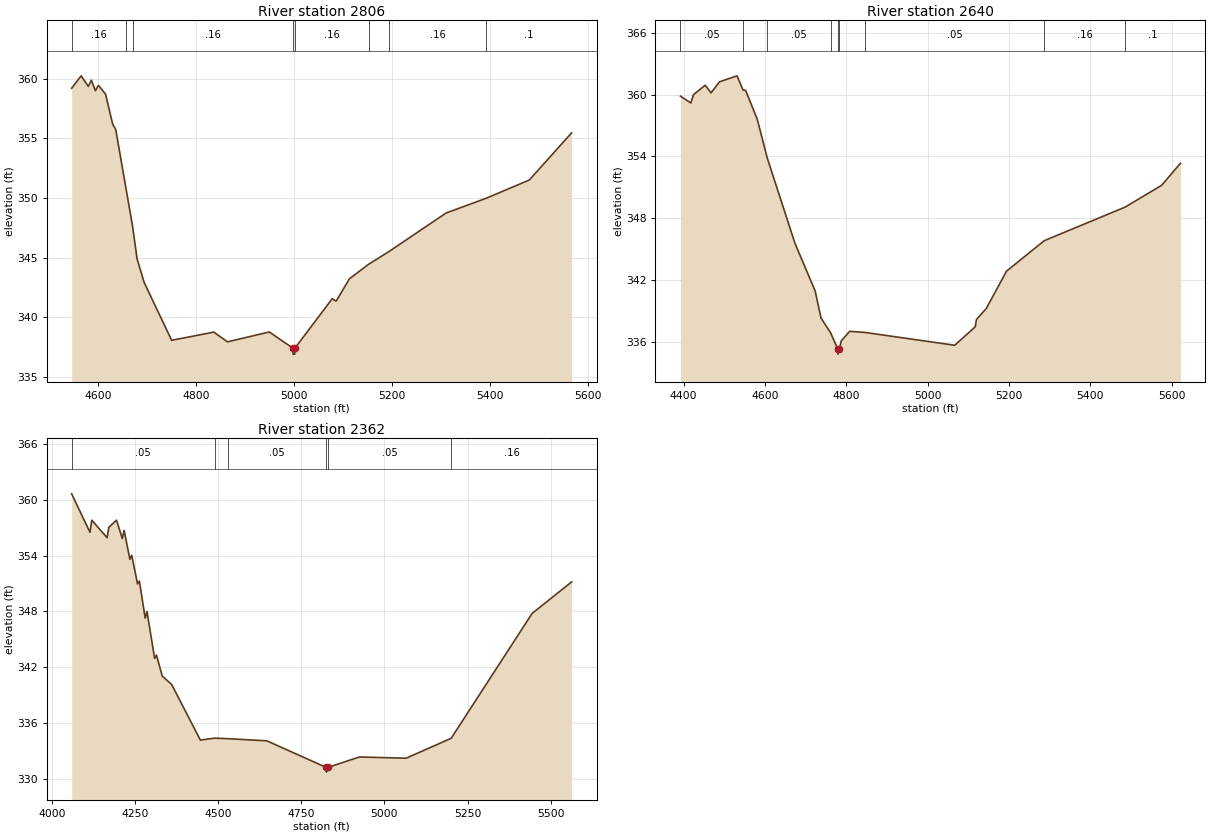
Type RM Length L Ch R = 1,2806,166,166,166
BEGIN DESCRIPTION:
MINERAL CR TRIB 2 4 2
END DESCRIPTION:
XS GIS Cut Line= 3
      3527212.83     10395828.25      3526693.70     10395430.66
      3526325.51     10395434.11
#Sta/Elev= 30
  4545.4  359.22  4564.8  360.26  4579.4  359.37  4585.7  359.89  4593.9  359.01
  4600.2  359.46  4614.7  358.72  4629.2  356.21  4635.5  355.75  4656.5  350.79
  4669.9  347.64  4679.1  344.90  4693.6  342.91  4749.8  338.05  4836.0  338.74
  4864.0  337.92  4949.4  338.75  4997.8  337.39  4998.0  336.89  5001.5  336.89
  5001.8  337.39  5078.0  341.54  5086.2  341.34  5113.3  343.22  5152.7  344.44
  5194.3  345.51  5310.9  348.74  5392.9  349.98  5480.9  351.51  5567.5  355.47
#Mann=8,-1,0
  4545.4    0.16       0  4656.5    0.05       0  4669.9    0.16       0
  4997.8    0.07       0  5001.8    0.16       0  5152.7    0.05       0
  5194.3    0.16       0  5392.9     0.1       0
Bank Sta=4997.8,5001.8
Exp/Cntr=0.3,0.1

Type RM Length L Ch R = 1,2640,278,278,278
BEGIN DESCRIPTION:
MINERAL CR TRIB 2 4 0
END DESCRIPTION:
XS GIS Cut Line= 4
      3527374.28     10395875.13      3527094.74     10395527.88
      3526863.84     10395362.95      3526366.32     10395404.55
#Sta/Elev= 30
  4392.5  359.85  4418.1  359.19  4424.5  359.99  4453.3  360.91  4467.7  360.17
  4488.5  361.24  4531.6  361.82  4546.4  360.43  4552.5  360.42  4581.2  357.62
  4605.8  353.85  4674.0  345.57  4723.6  340.95  4738.0  338.33  4761.5  336.90
  4779.2  335.33  4779.4  334.83  4783.2  335.33  4787.6  336.11  4808.4  337.04
  4845.0  336.94  5066.5  335.69  5116.9  337.47  5120.0  338.19  5143.9  339.24
  5194.0  342.88  5286.6  345.83  5485.5  349.09  5575.4  351.21  5621.3  353.34
#Mann=9,-1,0
  4392.5    0.05       0  4546.4    0.16       0  4605.8    0.05       0
  4761.5    0.16       0  4779.2    0.03       0  4783.2    0.16       0
  4845.0    0.05       0  5286.6    0.16       0  5485.5     0.1       0
Bank Sta=4779.2,4783.2
Exp/Cntr=0.3,0.1

Type RM Length L Ch R = 1,2362,0,0,0
BEGIN DESCRIPTION:
MINERAL CR TRIB 2 4 3
END DESCRIPTION:
XS GIS Cut Line= 4
      3527402.04     10395882.74      3527079.12     10395185.86
      3526641.62     10395168.50      3526382.90     10395314.36
#Sta/Elev= 30
  4059.8  360.66  4114.8  356.52  4120.4  357.82  4166.2  355.94  4171.7  357.06
  4194.6  357.83  4212.0  355.85  4217.5  356.72  4234.9  353.61  4240.4  354.05
  4257.8  350.96  4263.4  351.27  4280.8  347.28  4286.3  347.99  4309.2  342.95
  4314.7  343.30  4332.1  341.04  4360.5  340.13  4446.7  334.15  4489.8  334.36
  4529.3  334.30  4646.5  334.07  4825.4  331.20  4825.7  330.70  4829.4  331.20
  4924.9  332.33  5065.2  332.20  5200.6  334.34  5444.1  347.79  5562.7  351.18
#Mann=6,-1,0
  4059.8    0.05       0  4489.8    0.16       0  4529.3    0.05       0
  4825.4    0.03       0  4829.4    0.05       0  5200.6    0.16       0
Bank Sta=4825.4,4829.4
Exp/Cntr=0.3,0.1

Chan Stop Cuts=-1