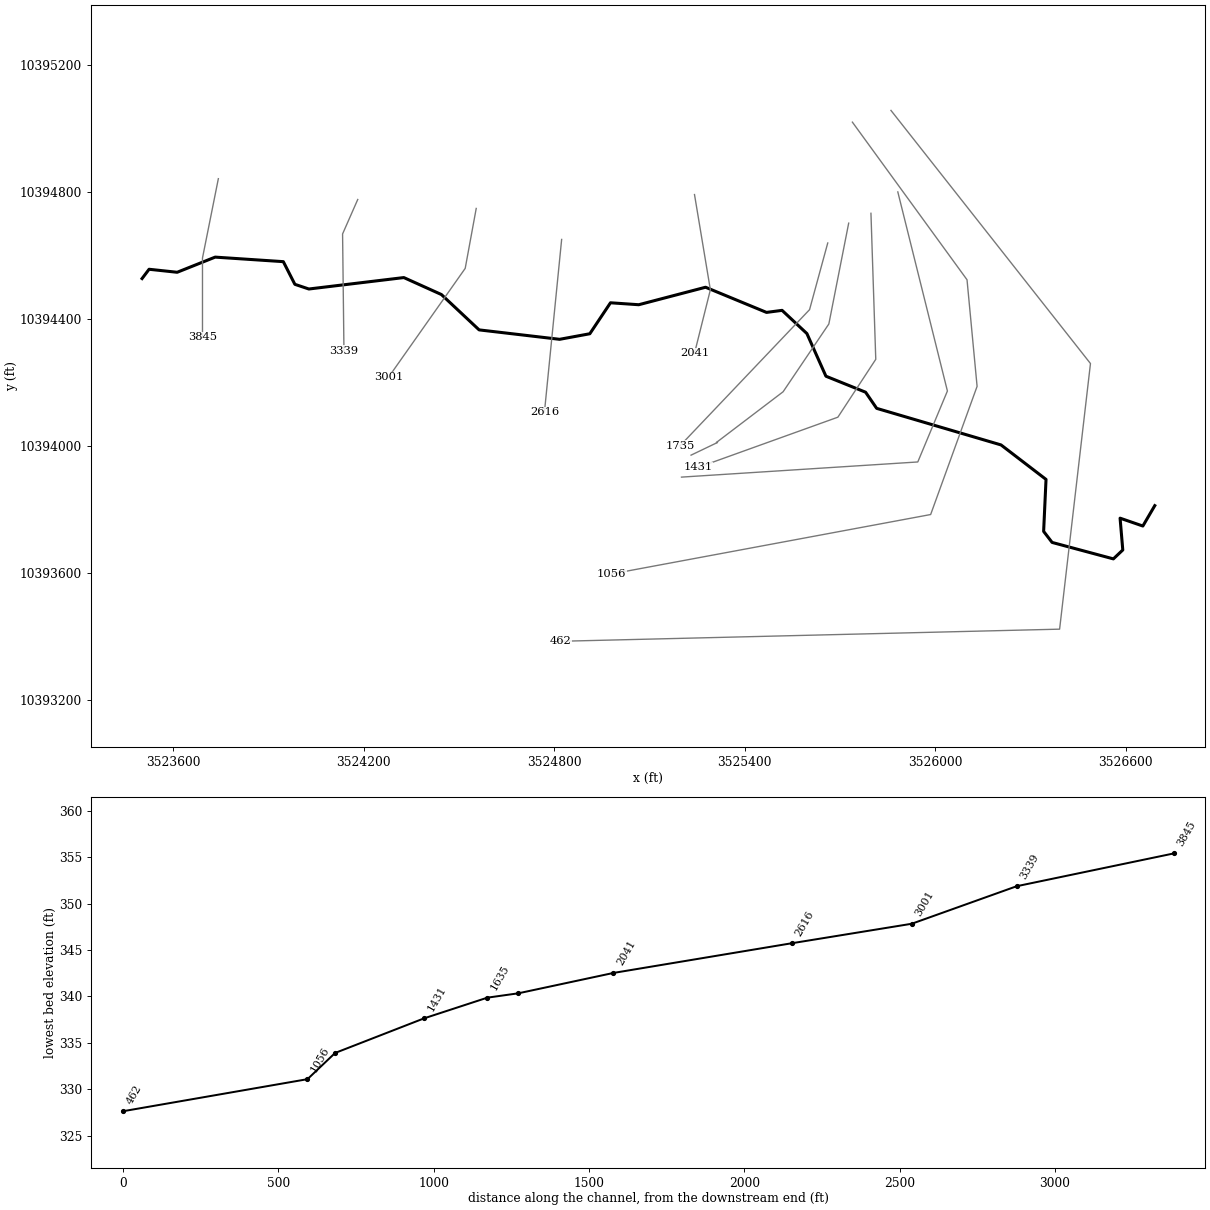
--- MINERAL CR TRIB 4.prj (project) ---

Proj Title=MINERAL CR TRIB 4 Base Level Engineering
Current Plan=p01
Default Exp/Contr=0.3,0.1
English Units
Geom File=g01
Flow File=f01
Plan File=p01
Y Axis Title=Elevation
X Axis Title(PF)=Main Channel Distance
X Axis Title(XS)=Station
BEGIN DESCRIPTION:
MINERAL CR TRIB 4
END DESCRIPTION:
DSS Export Rating Curves= 0
DSS Export Rating Curve Sorted= 0
DSS Export Volume Flow Curves= 0
DXF OffsetX= 0
DXF OffsetY= 0
DXF ScaleX= 1
DXF ScaleY= 10

--- MINERAL CR TRIB 4.p01 (plan) ---

Plan Title=Multiple Run
Short Identifier=Multiple
Geom File=g01
Flow File=f01
Subcritical Flow
K Sum by GR= 0
Std Step Tol= 0.01
Critical Tol= 0.01
Num of Std Step Trials= 20
Max Error Tol= 0.3
Flow Tol Ratio= 0.001
Split Flow NTrial= 30
Split Flow Tol= 0.02
Split Flow Ratio= 0.02
Log Output Level= 0
Friction Slope Method= 1
Unsteady Friction Slope Method= 2
Unsteady Bridges Friction Slope Method= 1
Parabolic Critical Depth
Global Vel Dist=  1 , 1 , 1
Global Log Level= 0
CheckData=True
Encroach Param= -1, 0, 0, 0
BEGIN DESCRIPTION:
Multiple Run
END DESCRIPTION:

--- MINERAL CR TRIB 4.f01 (steady flow) ---

Flow Title=Multiple
Number of Profiles=7
Profile Names=10-year,25-year,50-year,1pct_min,100-year,1pct_plu,500-year
River Rch & RM= MINERAL CR TRIB ,Reach-1,3845
    1204    1699    2120    1931    2612    3532    3954
Boundary for River Rch & Prof#=MINERAL CR TRIB ,Reach-1,1
Up Type=0
Dn Type=3
Dn Slope=0.005
Boundary for River Rch & Prof#=MINERAL CR TRIB ,Reach-1,2
Up Type=0
Dn Type=3
Dn Slope=0.005
Boundary for River Rch & Prof#=MINERAL CR TRIB ,Reach-1,3
Up Type=0
Dn Type=3
Dn Slope=0.005
Boundary for River Rch & Prof#=MINERAL CR TRIB ,Reach-1,4
Up Type=0
Dn Type=3
Dn Slope=0.005
Boundary for River Rch & Prof#=MINERAL CR TRIB ,Reach-1,5
Up Type=0
Dn Type=3
Dn Slope=0.005
Boundary for River Rch & Prof#=MINERAL CR TRIB ,Reach-1,6
Up Type=0
Dn Type=3
Dn Slope=0.005
Boundary for River Rch & Prof#=MINERAL CR TRIB ,Reach-1,7
Up Type=0
Dn Type=3
Dn Slope=0.005

--- MINERAL CR TRIB 4.g01 (geometry) ---

Geom Title=Existing Conditions

River Reach=MINERAL CR TRIB ,Reach-1
Reach XY= 30
      3523501.74     10394526.97      3523523.88     10394556.26
      3523612.34     10394546.78      3523732.08     10394594.51
      3523946.78     10394580.24      3523983.16     10394508.81
      3524027.21     10394494.08      3524326.42     10394530.09
      3524444.87     10394476.60      3524563.58     10394365.28
      3524817.15     10394335.58      3524912.33     10394353.11
      3524977.43     10394450.68      3525066.48     10394444.54
      3525276.93     10394499.62      3525468.92     10394420.35
      3525518.00     10394426.79      3525596.18     10394353.70
      3525656.14     10394219.34      3525781.07     10394168.96
      3525815.95     10394118.11      3526207.83     10394002.83
      3526349.50     10393894.23      3526341.96     10393730.50
      3526368.63     10393695.72      3526561.71     10393643.87
      3526591.32     10393671.96      3526582.80     10393772.15
      3526654.54     10393747.36      3526692.11     10393811.64

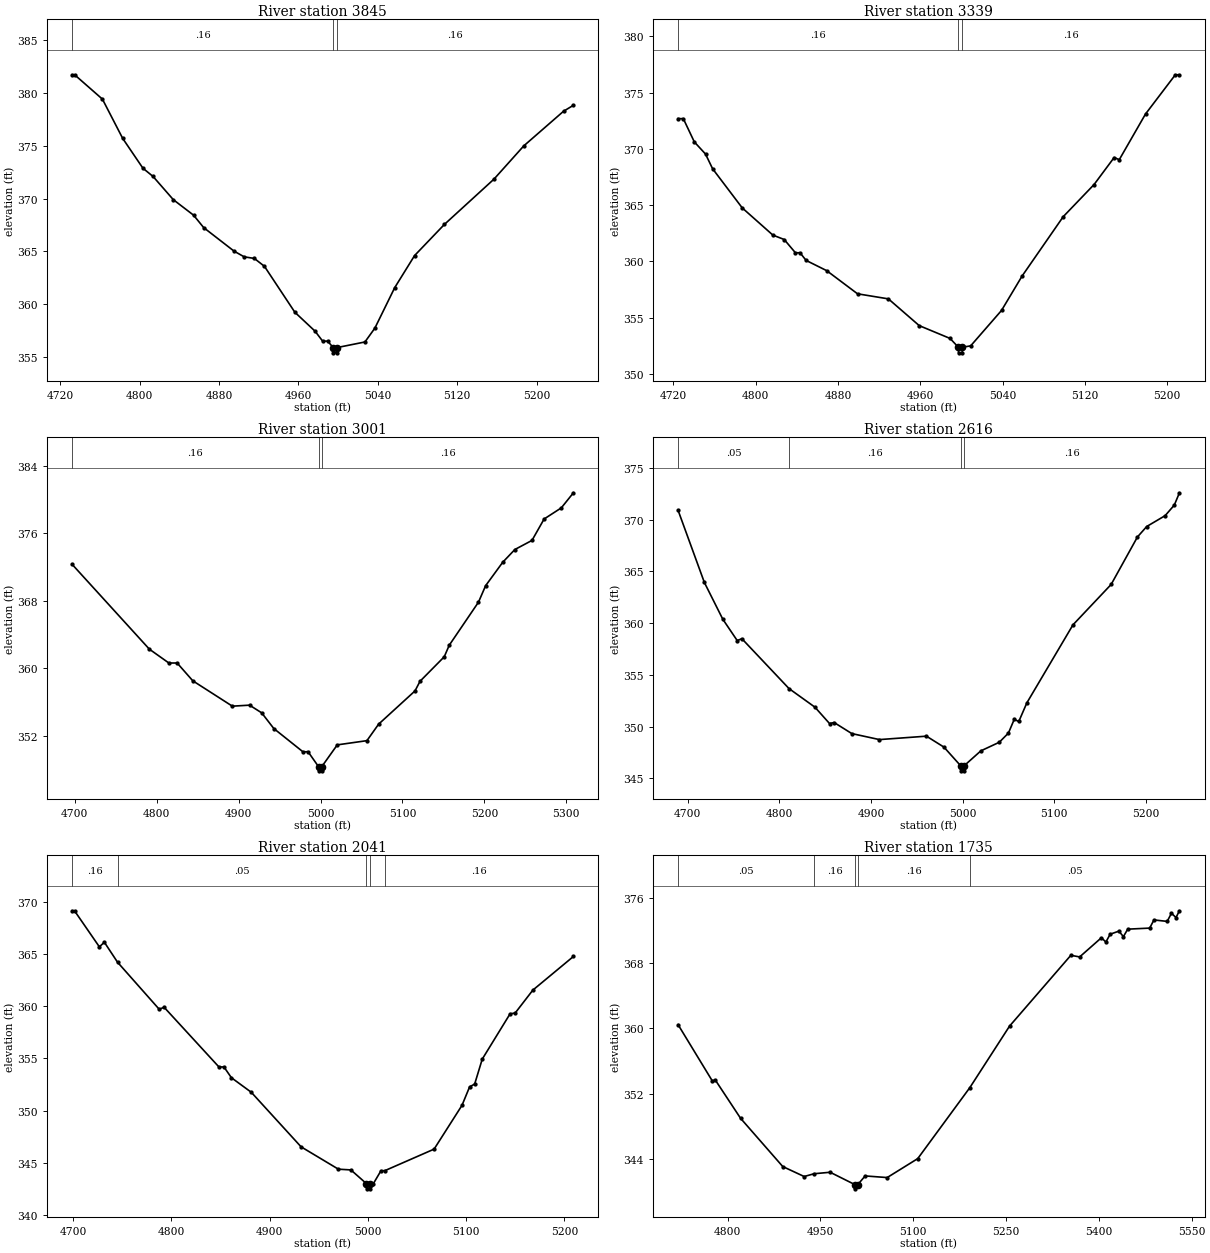
Type RM Length L Ch R = 1,3845,506,506,506
BEGIN DESCRIPTION:
SOUTH MINERAL CR TRIB 14 9 0
END DESCRIPTION:
XS GIS Cut Line= 3
      3523742.11     10394841.65      3523692.11     10394591.64
      3523692.11     10394341.60
#Sta/Elev= 30
  4732.0  381.75  4734.6  381.75  4762.6  379.44  4783.0  375.72  4803.4  372.89
  4813.6  372.11  4834.0  369.91  4854.4  368.44  4864.6  367.26  4895.2  365.03
  4905.4  364.49  4915.6  364.34  4925.8  363.59  4956.4  359.24  4976.8  357.44
  4984.4  356.50  4989.5  356.50  4995.0  355.89  4995.2  355.39  4998.7  355.39
  4999.0  355.89  5027.0  356.42  5037.0  357.73  5057.0  361.57  5077.0  364.61
  5107.0  367.56  5157.0  371.86  5187.0  375.01  5227.0  378.29  5237.0  378.86
#Mann=3,-1,0
  4732.0    0.16       0  4995.0    0.07       0  4999.0    0.16       0
Bank Sta=4995,4999
Exp/Cntr=0.3,0.1

Type RM Length L Ch R = 1,3339,338,338,338
BEGIN DESCRIPTION:
SOUTH MINERAL CR TRIB 14 8 0
END DESCRIPTION:
XS GIS Cut Line= 3
      3524181.22     10394776.06      3524133.46     10394667.53
      3524137.80     10394298.63
#Sta/Elev= 30
  4724.5  372.69  4729.6  372.69  4740.3  370.62  4751.2  369.54  4758.1  368.23
  4786.9  364.75  4816.7  362.33  4827.7  361.94  4838.6  360.76  4843.1  360.76
  4849.0  360.08  4869.0  359.17  4899.0  357.11  4929.0  356.66  4959.0  354.28
  4989.0  353.14  4997.0  352.36  4997.2  351.86  5000.7  351.86  5001.0  352.36
  5009.0  352.48  5039.0  355.63  5059.0  358.69  5099.0  363.97  5129.0  366.83
  5148.5  369.23  5153.5  369.04  5179.0  373.10  5208.0  376.59  5212.0  376.59
#Mann=3,-1,0
  4724.5    0.16       0  4997.0    0.07       0  5001.0    0.16       0
Bank Sta=4997,5001
Exp/Cntr=0.3,0.1

Type RM Length L Ch R = 1,3001,385,385,385
BEGIN DESCRIPTION:
SOUTH MINERAL CR TRIB 14 7 0
END DESCRIPTION:
XS GIS Cut Line= 3
      3524554.47     10394747.85      3524519.75     10394559.02
      3524277.82     10394215.57
#Sta/Elev= 30
  4696.6  372.32  4791.0  362.25  4814.8  360.61  4824.9  360.61  4844.0  358.50
  4892.3  355.49  4913.3  355.61  4928.1  354.70  4942.9  352.84  4978.6  350.07
  4984.7  350.09  4997.5  348.32  4997.7  347.82  5001.2  347.82  5001.5  348.32
  5020.4  350.90  5056.6  351.40  5070.9  353.36  5115.3  357.30  5121.4  358.44
  5151.0  361.35  5157.1  362.72  5192.8  367.83  5201.5  369.78  5222.4  372.56
  5237.2  374.07  5258.1  375.15  5272.9  377.69  5293.9  379.01  5308.7  380.80
#Mann=3,-1,0
  4696.6    0.16       0  4997.5    0.07       0  5001.5    0.16       0
Bank Sta=4997.5,5001.5
Exp/Cntr=0.3,0.1

Type RM Length L Ch R = 1,2616,575,575,575
BEGIN DESCRIPTION:
SOUTH MINERAL CR TRIB 14 4 1
END DESCRIPTION:
XS GIS Cut Line= 2
      3524823.57     10394650.19      3524769.37     10394106.08
#Sta/Elev= 30
  4689.7  370.91  4718.4  363.93  4738.5  360.38  4754.2  358.32  4759.3  358.50
  4810.7  353.68  4839.0  351.88  4854.9  350.30  4859.9  350.40  4879.2  349.33
  4909.3  348.75  4960.6  349.08  4979.7  348.02  4997.8  346.23  4998.0  345.73
  5001.5  345.73  5001.8  346.23  5019.9  347.66  5040.0  348.49  5050.0  349.38
  5056.3  350.70  5061.3  350.50  5070.1  352.30  5120.4  359.84  5162.0  363.74
  5190.7  368.33  5200.8  369.34  5220.9  370.39  5230.9  371.41  5236.5  372.60
#Mann=4,-1,0
  4689.7    0.05       0  4810.7    0.16       0  4997.8    0.07       0
  5001.8    0.16       0
Bank Sta=4997.8,5001.8
Exp/Cntr=0.3,0.1

Type RM Length L Ch R = 1,2041,306,306,306
BEGIN DESCRIPTION:
SOUTH MINERAL CR TRIB 14 4 0
END DESCRIPTION:
XS GIS Cut Line= 3
      3525242.11     10394791.60      3525292.11     10394491.64
      3525242.09     10394291.59
#Sta/Elev= 30
  4698.8  369.13  4701.3  369.13  4726.6  365.68  4731.7  366.12  4745.1  364.21
  4787.5  359.71  4792.5  359.90  4848.3  354.19  4853.4  354.19  4861.0  353.16
  4881.2  351.77  4931.9  346.55  4969.9  344.41  4982.6  344.34  4998.4  343.03
  4998.6  342.53  5002.1  342.53  5002.4  343.03  5005.5  343.03  5013.2  344.26
  5017.2  344.27  5067.3  346.33  5095.7  350.52  5103.4  352.28  5108.6  352.56
  5116.3  354.94  5144.6  359.27  5149.8  359.35  5167.8  361.54  5209.1  364.76
#Mann=5,-1,0
  4698.8    0.16       0  4745.1    0.05       0  4998.4    0.03       0
  5002.4    0.05       0  5017.2    0.16       0
Bank Sta=4998.4,5002.4
Exp/Cntr=0.3,0.1

Type RM Length L Ch R = 1,1735,100,100,100
BEGIN DESCRIPTION:
SOUTH MINERAL CR TRIB 14 6 0
END DESCRIPTION:
XS GIS Cut Line= 3
      3525661.86     10394639.06      3525604.58     10394429.03
      3525195.99     10393999.67
#Sta/Elev= 30
  4719.9  360.44  4775.1  353.57  4780.3  353.64  4820.9  348.98  4889.1  343.07
  4923.7  341.85  4939.9  342.19  4965.7  342.37  5006.2  340.84  5006.4  340.34
  5010.2  340.84  5022.3  341.92  5057.9  341.72  5107.3  344.04  5191.6  352.74
  5255.7  360.26  5354.8  368.93  5369.0  368.73  5404.2  371.08  5411.4  370.55
  5418.3  371.51  5432.5  371.89  5439.7  371.21  5446.7  372.13  5482.2  372.26
  5489.1  373.26  5510.5  373.08  5517.4  374.08  5524.7  373.55  5530.3  374.38
#Mann=5,-1,0
  4719.9    0.05       0  4939.9    0.16       0  5006.2    0.07       0
  5010.2    0.16       0  5191.6    0.05       0
Bank Sta=5006.2,5010.2
Exp/Cntr=0.3,0.1

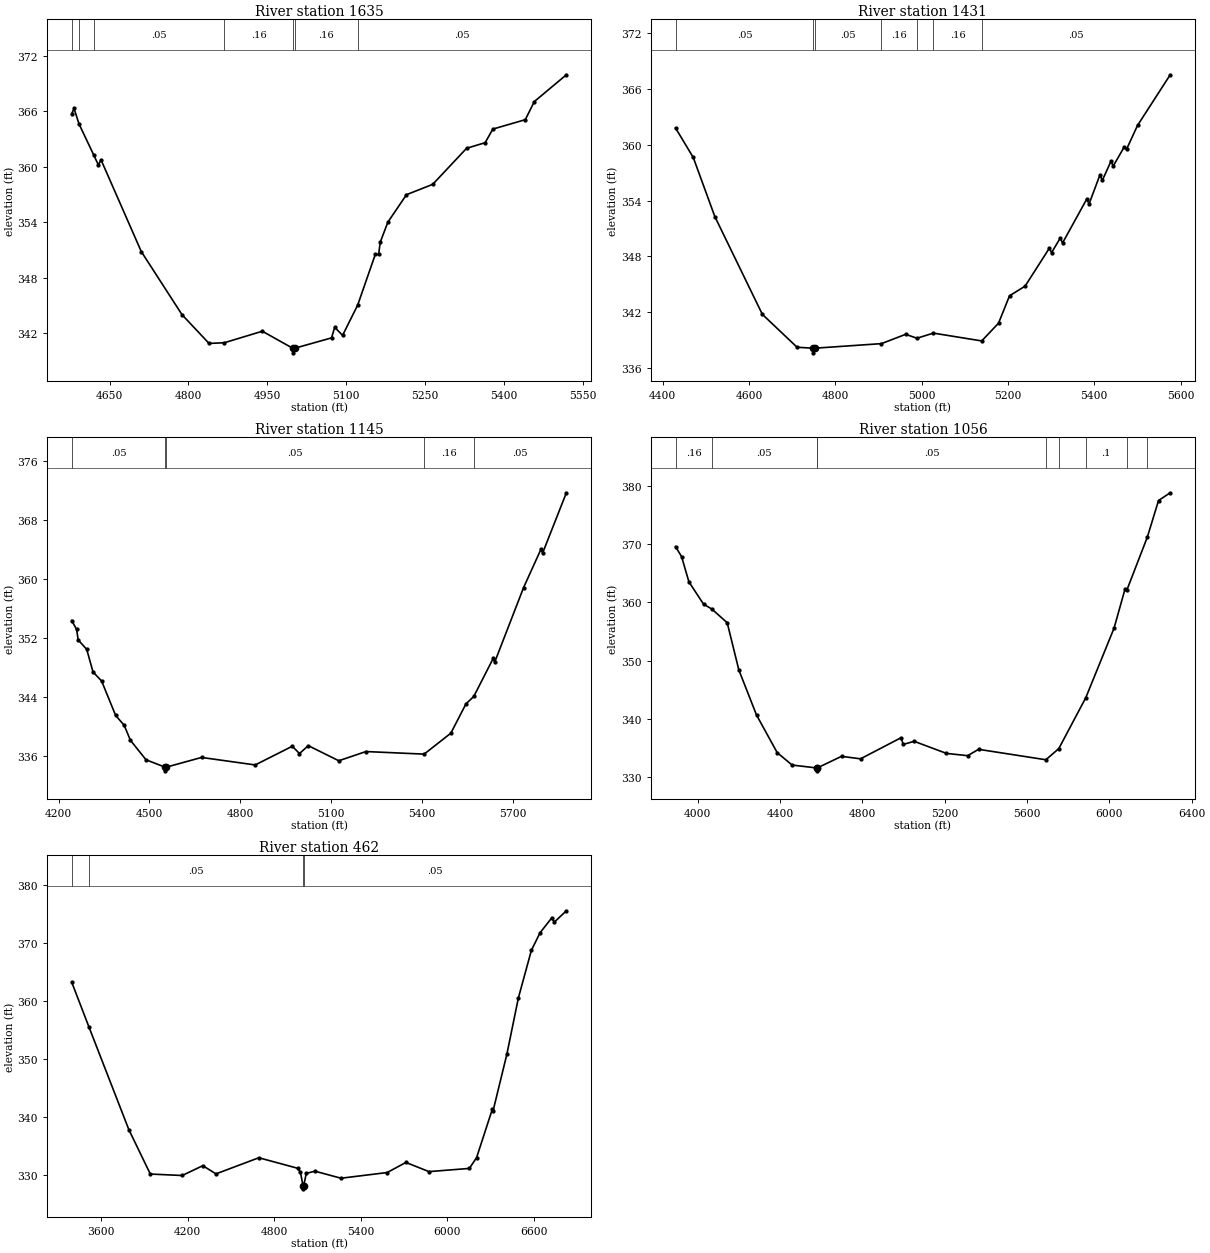
Type RM Length L Ch R = 1,1635,204,204,204
BEGIN DESCRIPTION:
SOUTH MINERAL CR TRIB 14 5 0
END DESCRIPTION:
XS GIS Cut Line= 6
      3525727.84     10394701.58      3525665.34     10394383.89
      3525521.24     10394170.35      3525311.17     10394010.63
      3525314.65     10394010.63      3525231.28     10393970.68
#Sta/Elev= 30
  4578.0  365.75  4582.4  366.32  4591.9  364.65  4620.1  361.26  4628.7  360.21
  4633.8  360.76  4710.4  350.83  4787.9  344.00  4839.3  340.89  4868.2  340.96
  4940.7  342.21  4998.4  340.37  4998.7  339.87  5002.4  340.37  5072.4  341.49
  5078.4  342.63  5093.4  341.76  5122.2  345.05  5155.6  350.52  5162.0  350.52
  5165.0  351.84  5179.6  354.02  5215.0  356.99  5264.9  358.11  5329.3  362.01
  5364.7  362.62  5379.2  364.09  5441.1  365.11  5458.2  367.07  5519.2  369.97
#Mann=7,-1,0
  4578.0    0.05       0  4591.9    0.16       0  4620.1    0.05       0
  4868.2    0.16       0  4998.4    0.07       0  5002.4    0.16       0
  5122.2    0.05       0
Bank Sta=4998.4,5002.4
Exp/Cntr=0.3,0.1

Type RM Length L Ch R = 1,1431,286,286,286
BEGIN DESCRIPTION:
SOUTH MINERAL CR TRIB 14 3 1
END DESCRIPTION:
XS GIS Cut Line= 4
      3525797.96     10394732.60      3525813.15     10394272.56
      3525693.79     10394090.27      3525253.28     10393931.86
#Sta/Elev= 30
  4429.6  361.81  4470.6  358.64  4520.6  352.29  4630.7  341.78  4711.2  338.24
  4748.7  338.14  4749.0  337.64  4752.7  338.14  4906.7  338.63  4962.7  339.63
  4989.1  339.21  5027.1  339.76  5139.1  338.92  5178.1  340.83  5203.5  343.77
  5239.6  344.81  5295.7  348.88  5301.0  348.41  5321.1  349.98  5326.4  349.45
  5382.5  354.17  5387.8  353.64  5413.2  356.78  5418.5  356.17  5438.6  358.23
  5443.9  357.72  5469.3  359.77  5474.7  359.52  5500.1  362.08  5575.9  367.53
#Mann=7,-1,0
  4429.6    0.05       0  4748.7    0.03       0  4752.7    0.05       0
  4906.7    0.16       0  4989.1    0.05       0  5027.1    0.16       0
  5139.1    0.05       0
Bank Sta=4748.7,4752.7
Exp/Cntr=0.3,0.1

Type RM Length L Ch R = 1,1145,89,89,89
BEGIN DESCRIPTION:
Mapping XS 19b34369
END DESCRIPTION:
XS GIS Cut Line= 4
      3525882.59     10394799.91      3526038.84     10394172.74
      3525945.53     10393949.21      3525201.12     10393901.47
#Sta/Elev= 30
  4243.2  354.33  4259.4  353.13  4264.5  351.71  4292.9  350.41  4313.6  347.35
  4342.0  346.12  4388.4  341.44  4416.6  340.11  4437.2  338.07  4488.8  335.42
  4551.6  334.42  4551.8  333.92  4555.6  334.42  4672.3  335.74  4849.5  334.72
  4972.0  337.26  4995.8  336.27  5025.0  337.34  5125.7  335.29  5215.4  336.54
  5407.7  336.19  5495.9  339.03  5546.0  343.02  5571.7  344.02  5635.9  349.19
  5640.9  348.68  5736.4  358.82  5794.2  364.06  5799.2  363.50  5877.7  371.69
#Mann=5,-1,0
  4243.2    0.05       0  4551.6    0.03       0  4555.6    0.05       0
  5407.7    0.16       0  5571.7    0.05       0
Bank Sta=4551.6,4555.6
Exp/Cntr=0.3,0.1

Type RM Length L Ch R = 1,1056,594,594,594
BEGIN DESCRIPTION:
SOUTH MINERAL CR TRIB 14 3 2
END DESCRIPTION:
XS GIS Cut Line= 5
      3525739.49     10395019.73      3526100.62     10394523.18
      3526132.35     10394187.40      3525986.04     10393783.60
      3524980.58     10393596.37
#Sta/Elev= 30
  3892.0  369.55  3921.3  367.84  3956.8  363.52  4027.9  359.69  4067.9  358.86
  4143.0  356.50  4199.5  348.40  4285.3  340.68  4385.7  334.23  4458.4  332.09
  4576.9  331.60  4577.2  331.10  4580.9  331.60  4698.4  333.59  4790.7  333.16
  4987.7  336.78  4998.3  335.63  5051.5  336.16  5208.3  334.09  5311.5  333.70
  5364.3  334.79  5691.3  333.00  5754.1  334.91  5885.1  343.63  6022.6  355.57
  6075.4  362.21  6084.6  362.08  6184.4  371.19  6238.7  377.46  6295.5  378.79
#Mann=9,-1,0
  3892.0    0.16       0  4067.9    0.05       0  4576.9    0.03       0
  4580.9    0.05       0  5691.3    0.16       0  5754.1    0.05       0
  5885.1     0.1       0  6084.6    0.05       0  6184.4     0.1       0
Bank Sta=4576.9,4580.9
Exp/Cntr=0.3,0.1

Type RM Length L Ch R = 1,462,0,0,0
BEGIN DESCRIPTION:
SOUTH MINERAL CR TRIB 14 1 0
END DESCRIPTION:
XS GIS Cut Line= 4
      3525861.04     10395056.64      3526489.51     10394259.29
      3526392.29     10393422.48      3524819.34     10393384.29
#Sta/Elev= 30
  3396.5  363.28  3515.2  355.61  3792.6  337.87  3941.7  330.20  4163.0  329.95
  4305.7  331.64  4397.1  330.23  4694.4  333.01  4963.1  331.20  4983.2  330.48
  5001.4  328.15  5001.6  327.65  5005.4  328.15  5023.5  330.32  5083.9  330.69
  5264.4  329.48  5584.5  330.46  5714.5  332.20  5874.6  330.62  6154.6  331.17
  6204.7  333.02  6314.2  341.38  6319.2  341.10  6414.7  350.84  6494.7  360.56
  6584.8  368.76  6644.8  371.79  6724.8  374.32  6744.8  373.65  6827.6  375.59
#Mann=4,-1,0
  3396.5    0.16       0  3515.2    0.05       0  5001.4   0.035       0
  5005.4    0.05       0
Bank Sta=5001.4,5005.4
Exp/Cntr=0.3,0.1

Chan Stop Cuts=-1