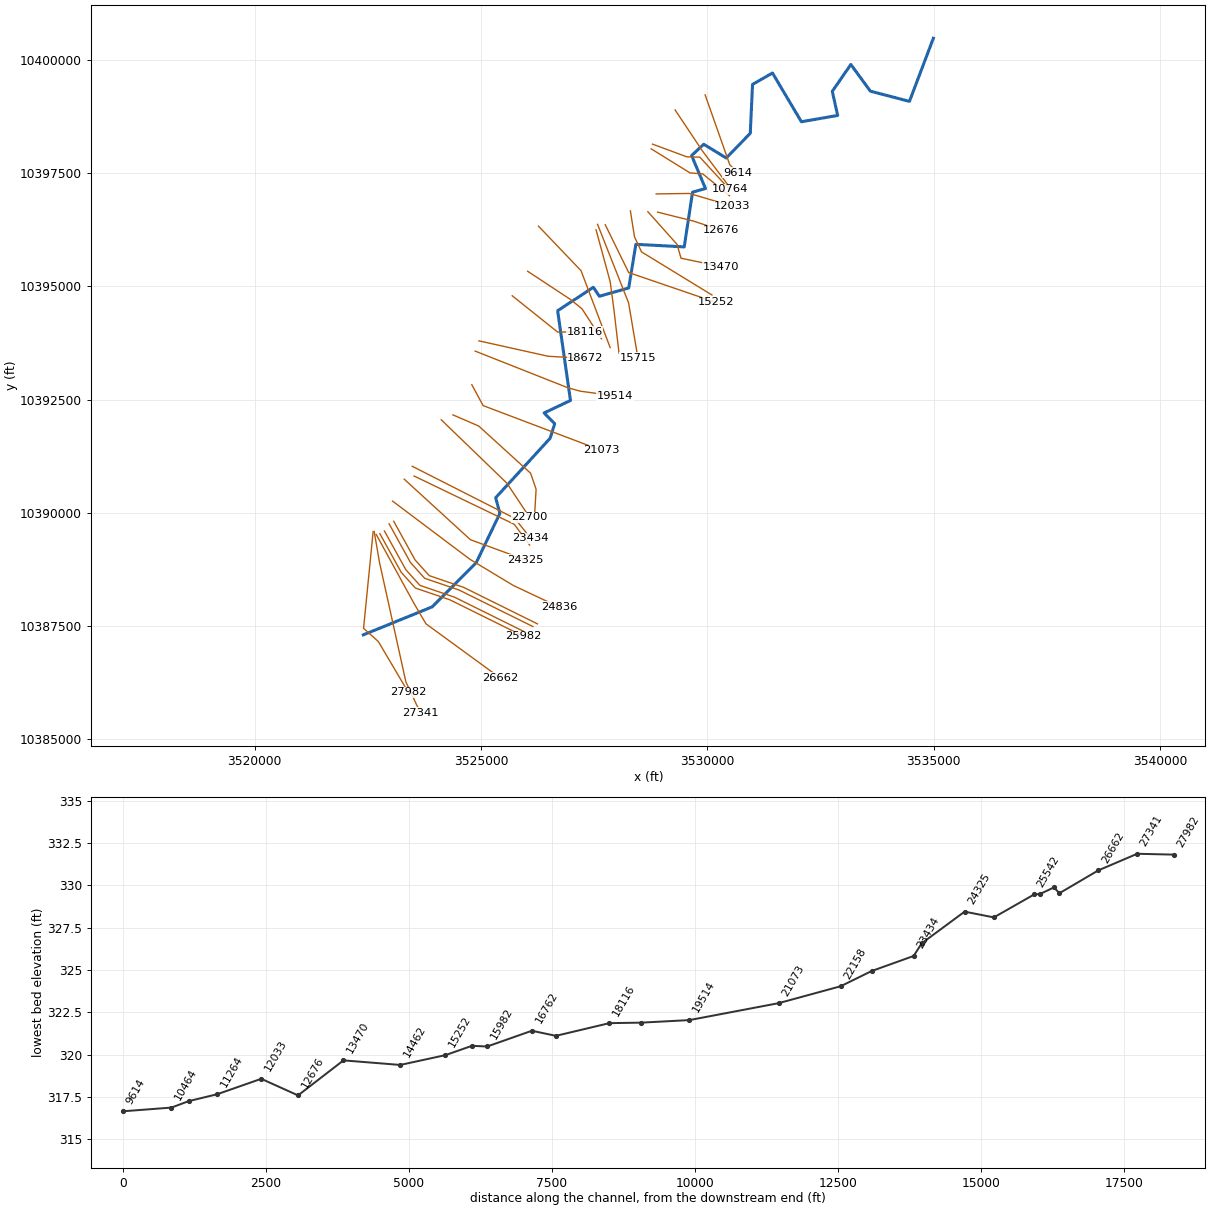
--- MINERAL CREEK.prj (project) ---

Proj Title=MINERAL CREEK Base Level Engineering
Current Plan=p01
Default Exp/Contr=0.3,0.1
English Units
Geom File=g01
Flow File=f01
Plan File=p01
Y Axis Title=Elevation
X Axis Title(PF)=Main Channel Distance
X Axis Title(XS)=Station
BEGIN DESCRIPTION:
MINERAL CREEK
END DESCRIPTION:
DSS Export Rating Curves= 0
DSS Export Rating Curve Sorted= 0
DSS Export Volume Flow Curves= 0
DXF OffsetX= 0
DXF OffsetY= 0
DXF ScaleX= 1
DXF ScaleY= 10

--- MINERAL CREEK.p01 (plan) ---

Plan Title=Multiple Run
Short Identifier=Multiple
Geom File=g01
Flow File=f01
Subcritical Flow
K Sum by GR= 0
Std Step Tol= 0.01
Critical Tol= 0.01
Num of Std Step Trials= 20
Max Error Tol= 0.3
Flow Tol Ratio= 0.001
Split Flow NTrial= 30
Split Flow Tol= 0.02
Split Flow Ratio= 0.02
Log Output Level= 0
Friction Slope Method= 1
Unsteady Friction Slope Method= 2
Unsteady Bridges Friction Slope Method= 1
Parabolic Critical Depth
Global Vel Dist=  1 , 1 , 1
Global Log Level= 0
CheckData=True
Encroach Param= -1, 0, 0, 0
BEGIN DESCRIPTION:
Multiple Run
END DESCRIPTION:

--- MINERAL CREEK.f01 (steady flow) ---

Flow Title=Multiple
Program Version=4.10
Number of Profiles= 7
Profile Names=10-year,25-year,50-year,1pct_min,100-year,1pct_plu,500-year
River Rch & RM=MINERAL CREEK,Reach-1         ,27982
   10393   15520   20084   18814   25444   34410   40767
River Rch & RM=MINERAL CREEK,Reach-1         ,26662
   10929   16340   21163   19840   26832   36287   43054
River Rch & RM=MINERAL CREEK,Reach-1         ,22700
   10929   16340   21163   19840   26832   36287   43054
River Rch & RM=MINERAL CREEK,Reach-1         ,18116
   10842   16174   20918   19580   26479   35810   42354
River Rch & RM=MINERAL CREEK,Reach-1         ,16762
   10859   16184   20916   19564   26458   35781   42257
River Rch & RM=MINERAL CREEK,Reach-1         ,14462
   10859   16184   20916   19564   26458   35781   42257
River Rch & RM=MINERAL CREEK,Reach-1         ,11264
   10923   16274   21027   19663   26592   35963   42450
River Rch & RM=MINERAL CREEK,Reach-1         ,10464
   10591   15708   20233   18859   25504   34492   40447
Boundary for River Rch & Prof#=MINERAL CREEK,Reach-1         , 1
Up Type= 0
Dn Type= 3
Dn Slope=0.001
Boundary for River Rch & Prof#=MINERAL CREEK,Reach-1         , 2
Up Type= 0
Dn Type= 3
Dn Slope=0.001
Boundary for River Rch & Prof#=MINERAL CREEK,Reach-1         , 3
Up Type= 0
Dn Type= 3
Dn Slope=0.001
Boundary for River Rch & Prof#=MINERAL CREEK,Reach-1         , 4
Up Type= 0
Dn Type= 3
Dn Slope=0.001
Boundary for River Rch & Prof#=MINERAL CREEK,Reach-1         , 5
Up Type= 0
Dn Type= 3
Dn Slope=0.001
Boundary for River Rch & Prof#=MINERAL CREEK,Reach-1         , 6
Up Type= 0
Dn Type= 3
Dn Slope=0.001
Boundary for River Rch & Prof#=MINERAL CREEK,Reach-1         , 7
Up Type= 0
Dn Type= 3
Dn Slope=0.001
DSS Import GetInterval= 0
DSS Import GetPeak= 0
DSS Import FillOption= 0

--- MINERAL CREEK.g01 (geometry) ---

Geom Title=Existing Conditions
Program Version=4.10

River Reach=MINERAL CREEK   ,Reach-1
Reach XY= 30
      3522402.11     10387301.64       3523921.9     10387919.18
       3524894.2     10388892.99      3525418.97      10389984.2
      3525325.92     10390330.73       3526528.1     10391643.38
      3526630.31     10391965.74      3526396.15     10392203.42
      3526978.23     10392478.51      3526694.62     10394460.62
      3527483.39     10394979.24      3527616.98     10394781.73
      3528265.55       10394965.      3528423.31     10395928.75
      3529491.63     10395871.84      3529675.51     10397080.36
       3529961.2     10397161.39      3529655.53     10397890.06
      3529922.09     10398139.63      3530420.67     10397835.12
      3530951.19     10398381.32      3531001.05     10399461.18
      3531442.01     10399712.83      3532080.68     10398636.32
      3532882.24     10398775.56      3532763.39     10399307.75
      3533173.32     10399901.66      3533605.38      10399311.4
      3534468.45     10399086.49      3534996.37     10400479.79

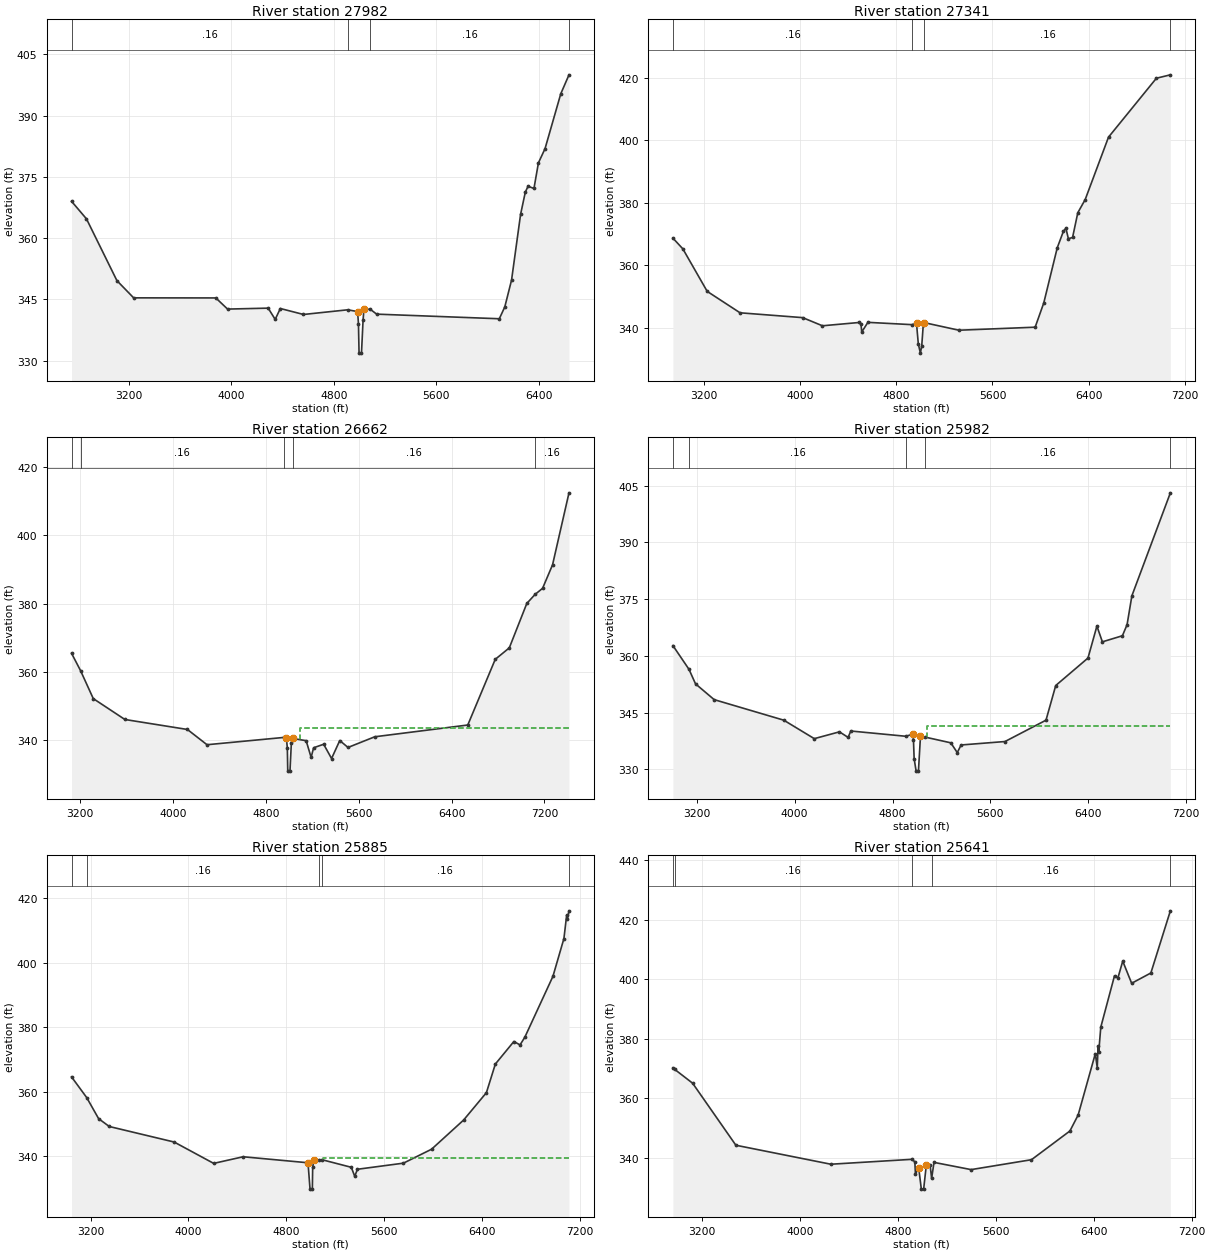
Type RM Length L Ch R = 1 ,27982   ,641,641,641
BEGIN DESCRIPTION:
MINERAL CREEK 3 0
END DESCRIPTION:
XS GIS Cut Line= 4
      3522618.49     10389584.24      3522406.68     10387445.31
      3522733.07     10387153.64      3523392.49      10386036.1
#Sta/Elev= 30
  2752.8  369.01  2869.6   364.7  3107.1  349.58  3237.8  345.36  3879.5  345.34
  3971.3  342.61  4288.4  342.84  4343.1  340.08  4383.3  342.75  4564.2  341.29
    4909  342.43  4986.7     342  4993.4  339.03  4998.1  331.82  5017.1  331.82
  5029.4  339.86  5036.1  342.54  5085.4  342.57  5135.5  341.37  6093.4  340.24
  6136.3  343.15    6189  349.71  6259.5  365.81  6296.3  371.24  6317.7  372.69
    6364  372.16  6398.8  378.42  6450.5  381.91  6573.3  395.34  6637.5  399.99
#Mann= 4 ,-1 , 0
  2752.8     .16       0    4909     .12       0  5085.4     .16       0
  6637.5     .16       0
Bank Sta=4986.7,5036.1
XS Rating Curve= 0 ,0
Exp/Cntr=0.3,0.1

Type RM Length L Ch R = 1 ,27341   ,679,679,679
BEGIN DESCRIPTION:
MINERAL CREEK 30 0
END DESCRIPTION:
XS GIS Cut Line= 4
      3522641.75     10389583.06      3522758.98     10388900.06
      3523342.05      10386260.7       3523658.2      10385585.1
#Sta/Elev= 30
  2939.3  368.71  3021.9  365.28  3224.8  351.65  3498.3  344.79  4019.8  343.24
  4184.3  340.63  4490.9  341.69  4505.3  341.14  4511.4  338.62  4562.6  341.73
  4931.3  340.99  4967.5  341.42  4982.5  334.82  4999.8  331.87  5011.2  334.27
  5023.5  340.84  5033.7  341.62  5320.5  339.21  5955.4  340.18  6027.1  347.95
  6139.7  365.66  6190.9  370.92  6211.4  371.88  6231.9  368.53  6266.9  368.92
  6310.5  376.85  6371.8  381.05  6566.1  401.06  6964.9  419.94  7081.2  421.03
#Mann= 4 ,-1 , 0
  2939.3     .16       0  4931.3     .12       0  5033.7     .16       0
  7081.2     .16       0
Bank Sta=4967.5,5033.7
XS Rating Curve= 0 ,0
Exp/Cntr=0.3,0.1

Type RM Length L Ch R = 1 ,26662   ,680,680,680
BEGIN DESCRIPTION:
MINERAL CREEK 27 0
END DESCRIPTION:
XS GIS Cut Line= 4
      3522686.38     10389519.33       3523519.7     10387998.52
      3523785.32     10387545.39      3525420.71     10386352.71
#Sta/Elev= 30
  3127.7  365.44  3204.9  360.38  3314.9  352.15    3587  346.03  4125.5   343.1
  4294.2  338.63  4956.2  340.77  4977.7   340.6  4985.7   337.8  4989.6  330.89
  5008.6  330.89  5020.6  339.22  5030.5  340.71  5036.3  340.43  5147.8  339.82
  5190.7  334.92  5212.2  337.74  5298.7  338.77  5366.7  334.59  5437.4  339.86
  5508.4  337.83  5738.6  340.96  6539.7  344.41  6776.1  363.66  6897.3  367.03
    7048  380.05    7119  382.69  7183.9  384.49  7269.7  391.38  7411.2  412.48
#Mann= 5 ,-1 , 0
  3127.7     .05       0  3204.9     .16       0  4956.2     .12       0
  5036.3     .16       0    7119     .16       0
#XS Ineff= 2 , 0
       0                 5093.75       0  343.65
Permanent Ineff=
       F       T
Bank Sta=4977.7,5030.5
XS Rating Curve= 0 ,0
Exp/Cntr=0.3,0.1

Type RM Length L Ch R = 1 ,25982   ,97,97,97
BEGIN DESCRIPTION:
MINERAL CREEK 26 6
END DESCRIPTION:
XS GIS Cut Line= 5
      3522766.79     10389536.75      3523239.02     10388682.57
      3523551.52     10388335.34      3524315.41     10388074.93
      3525943.43     10387269.24
#Sta/Elev= 30
  3004.8  362.71  3136.3  356.43  3189.6   352.6    3342  348.43  3911.2     343
  4160.5  338.12  4366.1  339.92  4437.1  338.45  4459.1  340.14  4908.5  338.75
  4965.9  339.31  4971.2  337.85  4976.8  332.86    4993  329.54    5012  329.54
  5028.6  338.73  5065.2  338.54  5276.5  337.02  5329.4  334.43  5360.6  336.45
  5719.5  337.36  6054.7     343  6134.4  352.16    6398  359.42  6470.9  367.86
  6515.7   363.7  6679.5  365.31  6717.6  368.24  6756.9  375.86  7071.5  403.07
#Mann= 5 ,-1 , 0
  3004.8     .05       0  3136.3     .16       0  4908.5     .12       0
  5065.2     .16       0  7071.5     .05       0
#XS Ineff= 2 , 0
       0                 5085.23       0   341.4
Permanent Ineff=
       F       T
Bank Sta=4965.9,5028.6
XS Rating Curve= 0 ,0
Exp/Cntr=0.3,0.1

Type RM Length L Ch R = 1 ,25885   ,244,244,244
BEGIN DESCRIPTION:
MINERAL CREEK 26 2
END DESCRIPTION:
XS GIS Cut Line= 5
      3522867.49     10389595.78      3523339.72     10388741.59
      3523652.22     10388394.37      3524416.11     10388133.96
      3526044.12     10387328.27
#Sta/Elev= 30
  3044.7  364.63  3168.7  358.22    3266   351.7  3353.1  349.27  3883.6  344.46
  4206.7  337.85  4447.4   339.9  4977.9  338.04  4994.4  329.88  5013.4  329.88
    5016  336.65  5026.6  338.83  5069.3  338.88    5090  339.01  5331.7  336.64
  5359.7  333.86  5382.2  336.03  5757.9  337.92  5987.8  342.23    6250  351.27
  6436.4  359.75  6509.3   368.6  6660.7  375.58  6711.2  374.53  6750.4  376.91
  6980.3  395.77    7070  407.47  7092.5  414.71    7098  413.37  7111.4  416.04
#Mann= 5 ,-1 , 0
  3044.7     .05       0  3168.7     .16       0  5069.3     .12       0
    5090     .16       0  7111.4     .05       0
#XS Ineff= 2 , 0
       0                 5099.43       0  339.52
Permanent Ineff=
       F       T
Bank Sta=4977.9,5026.6
XS Rating Curve= 0 ,0
Exp/Cntr=0.3,0.1

Type RM Length L Ch R = 1 ,25641   ,99,99,99
BEGIN DESCRIPTION:
MINERAL CREEK 26 7
END DESCRIPTION:
XS GIS Cut Line= 5
      3522971.64     10389752.05      3523443.88     10388897.84
      3523756.38     10388550.62      3524520.27     10388290.21
      3526147.73      10387484.8
#Sta/Elev= 30
  2959.4  370.24  2973.9  369.74  3120.5  365.09  3474.1  344.24  4250.4  337.86
  4910.6   339.5  4936.7  338.71    4942  334.51    4968  336.75  4989.9  329.49
  5008.9  329.49  5030.7  337.59  5062.1  337.44  5074.2  333.08  5093.4  338.48
  5396.9  336.05  5890.4  339.38  6204.4  349.03  6271.7   354.4  6411.9  374.99
  6427.9  370.32  6434.3  377.48  6439.9  375.42  6456.7  383.92  6568.9  401.21
  6596.9  400.49  6636.2  406.12    6709  398.68  6866.1  402.14  7025.5  423.03
#Mann= 5 ,-1 , 0
  2959.4     .05       0  2973.9     .16       0  4910.6     .12       0
  5074.2     .16       0  7025.5      .1       0
Bank Sta=4968,5030.7
XS Rating Curve= 0 ,0
Exp/Cntr=0.3,0.1

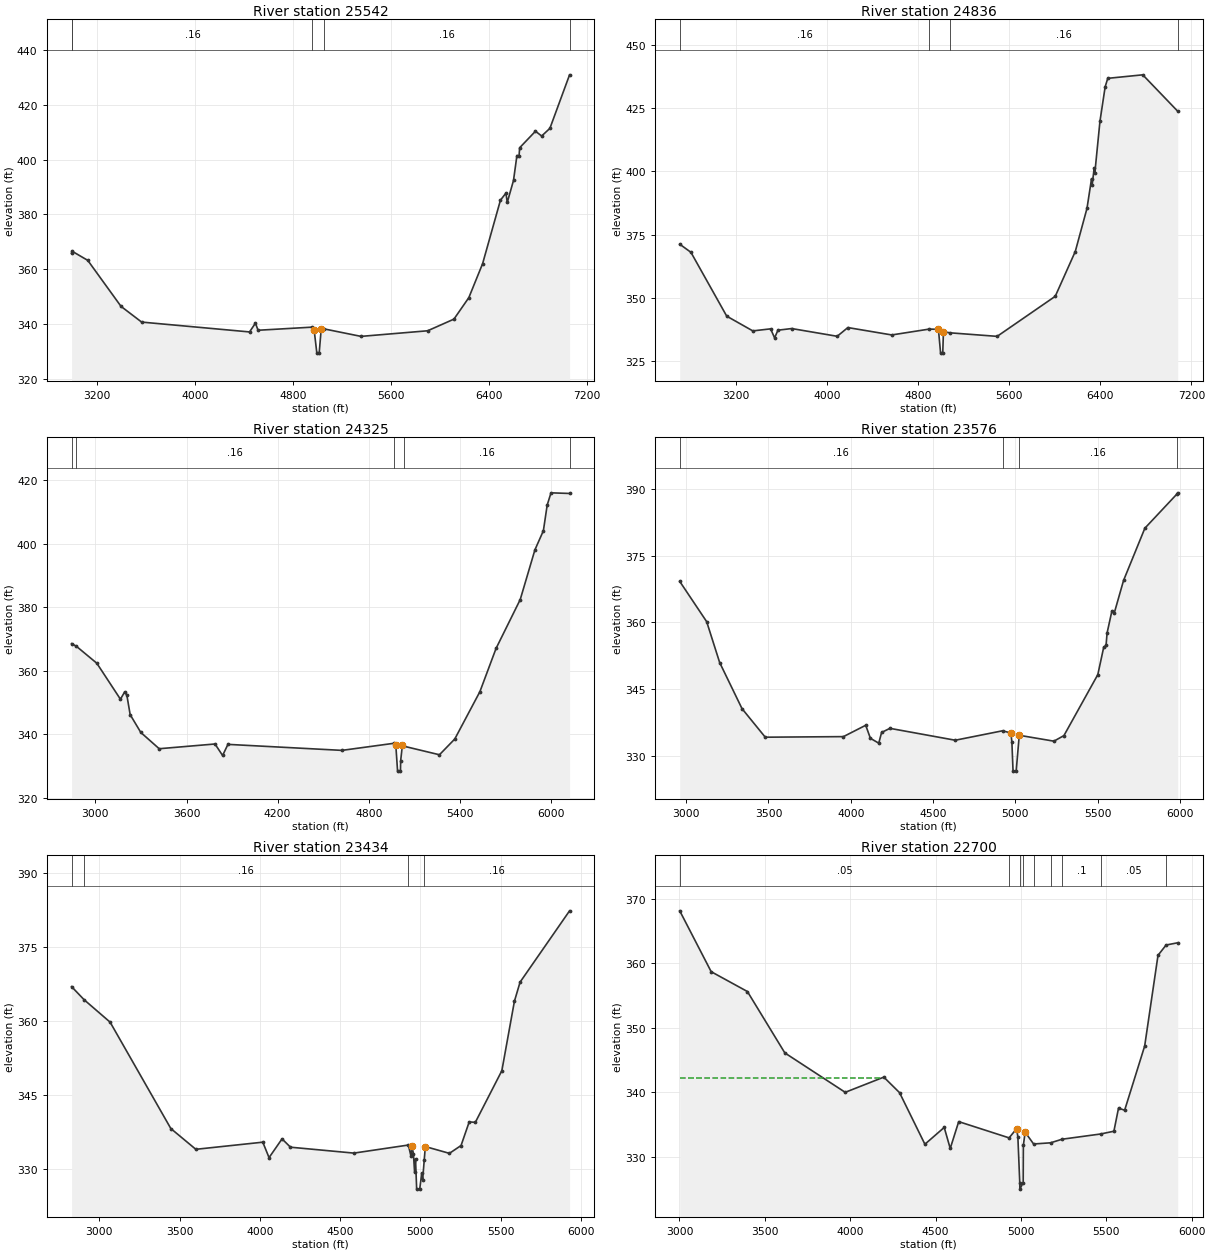
Type RM Length L Ch R = 1 ,25542   ,706,706,706
BEGIN DESCRIPTION:
MINERAL CREEK 26 8
END DESCRIPTION:
XS GIS Cut Line= 5
      3523072.34     10389811.07      3523544.58     10388956.87
      3523857.08     10388609.65      3524620.97     10388349.23
      3526248.07       10387544.
#Sta/Elev= 30
  2992.5   365.9    3000  366.51  3124.8  363.26  3396.3   346.5  3564.6  340.78
  4445.6  337.19  4493.8   340.4    4515   337.8  4958.7  338.94  4973.2  337.82
    4995  329.47    5014  329.47  5030.6  338.23  5053.8   338.3  5355.6  335.57
  5899.6  337.61  6114.3  341.86    6236   349.7  6348.2  362.05  6493.9  385.18
  6538.8  387.77  6549.5  384.35  6600.5  392.37  6628.5  401.46  6645.4  401.11
  6650.9  404.29  6779.9  410.31  6830.4  408.56  6897.7  411.36  7058.2  430.85
#Mann= 5 ,-1 , 0
  2992.5     .05       0    3000     .16       0  4958.7     .12       0
  5053.8     .16       0  7058.2      .1       0
Bank Sta=4973.2,5030.6
XS Rating Curve= 0 ,0
Exp/Cntr=0.3,0.1

Type RM Length L Ch R = 1 ,24836   ,511,511,511
BEGIN DESCRIPTION:
MINERAL CREEK 26 9
END DESCRIPTION:
XS GIS Cut Line= 4
      3523048.03      10390255.5      3524756.38     10388970.76
      3525718.19      10388390.9      3526726.34     10387916.27
#Sta/Elev= 30
  2704.7  371.19  2803.1  367.98  3117.6  342.73  3346.7   336.9  3502.9  337.71
  3538.3  334.14  3567.4  337.18  3688.2  337.83  4088.1  334.77  4181.8  338.22
  4567.1   335.3  4895.6  337.61  4977.4  337.53  4996.4  328.11  5015.4  328.11
  5021.4  336.56  5079.6  336.14  5493.2  334.74  6003.6  350.58  6179.6   368.3
  6282.6  385.39  6322.6  397.12  6328.2  394.78  6345.4  401.16    6351  399.18
  6396.5  419.84  6442.1  433.44  6464.9  436.78  6772.3  438.17  7079.6  423.77
#Mann= 4 ,-1 , 0
  2704.7     .16       0  4895.6      .1       0  5079.6     .16       0
  7079.6     .05       0
Bank Sta=4977.4,5021.4
XS Rating Curve= 0 ,0
Exp/Cntr=0.3,0.1

Type RM Length L Ch R = 1 ,24325   ,749,749,749
BEGIN DESCRIPTION:
MINERAL CREEK 27 1
END DESCRIPTION:
XS GIS Cut Line= 3
      3523305.56     10390740.04      3524767.36     10389403.24
      3525986.58     10388956.42
#Sta/Elev= 30
  2843.1  368.57    2875  367.73  3009.5   362.4  3164.9  351.08  3193.2  353.41
  3207.4   352.3    3229  346.22  3299.3  340.61  3420.2   335.5  3787.7  336.99
  3837.7  333.37  3872.8  336.87  4623.3  334.98  4967.5  337.22  4978.1  336.79
  4989.9  328.45  5008.9  328.45  5010.1  331.67  5021.8  336.69  5032.5  336.28
  5265.7   333.6  5366.6  338.56    5532  353.45  5638.5  367.07  5797.5  382.43
  5894.4  398.09  5950.1   404.1  5975.2  412.19  6000.4  416.03  6122.5  415.83
#Mann= 5 ,-1 , 0
  2843.1     .05       0    2875     .16       0  4967.5      .1       0
  5032.5     .16       0  6122.5     .16       0
Bank Sta=4978.1,5021.8
XS Rating Curve= 0 ,0
Exp/Cntr=0.3,0.1

Type RM Length L Ch R = 1 ,23576   ,142,142,142
BEGIN DESCRIPTION:
MINERAL CREEK 4 0
END DESCRIPTION:
XS GIS Cut Line= 3
      3523524.24     10390809.89      3525736.04     10389743.92
      3526075.95     10389286.07
#Sta/Elev= 30
  2960.8   369.2  3124.5  360.15  3203.4  350.97  3339.1  340.62  3480.4   334.2
  3955.3  334.33  4090.7  336.88  4119.2  333.95    4170  332.86  4187.1  335.26
  4237.8  336.19  4634.7  333.52  4921.9  335.64  4972.7  335.15  4978.8  333.09
  4985.8  326.58  5004.8  326.58  5023.5  334.63  5234.1  333.31  5294.9  334.56
  5500.8  348.26  5536.3  354.35  5550.9  354.83  5557.1   357.6  5586.3  362.53
  5600.9  362.11  5657.2  369.41  5786.6  381.14  5979.4  388.74  5986.3  389.09
#Mann= 4 ,-1 , 0
  2960.8     .16       0  4921.9      .1       0  5023.5     .16       0
  5979.4     .05       0
Bank Sta=4972.7,5023.5
XS Rating Curve= 0 ,0
Exp/Cntr=0.3,0.1

Type RM Length L Ch R = 1 ,23434   ,734,734,734
BEGIN DESCRIPTION:
MINERAL CREEK 27 3
END DESCRIPTION:
XS GIS Cut Line= 3
      3523482.59     10391025.15      3525746.45     10389875.86
      3526099.88      10389435.8
#Sta/Elev= 30
    2827  366.98    2905  364.32  3067.1  359.76  3445.6  338.14  3601.4  333.92
  4018.7  335.37  4057.6  332.23  4138.6  336.04  4191.2  334.35  4586.3  333.15
  4925.8  334.79  4942.4  332.48  4948.1  334.55  4957.3     333  4964.7  329.22
  4970.3  331.99  4977.5  325.83  4996.5  325.83  5009.2  329.05  5014.8  327.76
  5024.6  331.72  5031.5  334.48  5181.6   333.1  5254.1  334.69  5304.9  339.49
  5343.1   339.4  5508.3  349.89  5586.7  364.01  5621.9  367.89  5930.3  382.38
#Mann= 4 ,-1 , 0
    2827     .05       0    2905     .16       0  4925.8      .1       0
  5024.6     .16       0
Bank Sta=4948.1,5031.5
XS Rating Curve= 0 ,0
Exp/Cntr=0.3,0.1

Type RM Length L Ch R = 1 ,22700   ,542,542,542
BEGIN DESCRIPTION:
MINERAL CREEK 26 1
END DESCRIPTION:
XS GIS Cut Line= 3
      3524122.69     10392052.72      3525572.66     10390652.75
      3526072.66     10389902.76
#Sta/Elev= 30
  3001.7  368.15  3185.9   358.7  3398.1  355.62  3617.3  346.09    3971  339.97
  4197.1  342.33  4289.2  339.92  4437.7  331.91  4550.9  334.52  4586.1  331.25
  4635.7  335.42  4930.8   332.9  4975.1  334.33  4982.3  333.03  4993.4  325.94
  4993.9  324.94  5013.4  325.94  5014.4  331.74  5024.9  333.78  5074.4  331.95
  5173.9  332.13  5241.4  332.69  5466.9   333.5  5544.7  333.93  5571.7   337.5
  5607.8   337.2    5725  347.16  5803.1  361.24  5850.5  362.84  5918.6  363.19
#Mann= 9 ,-1 , 0
  3001.7     .05       0  4930.8     .16       0  4993.4     .07       0
  5013.4     .16       0  5074.4      .1       0  5173.9     .05       0
  5241.4      .1       0  5466.9     .05       0  5850.5      .1       0
#XS Ineff= 2 , 0
         4181.39  342.27
Permanent Ineff=
       F       F
Bank Sta=4975.1,5024.9
XS Rating Curve= 0 ,0
Exp/Cntr=0.3,0.1

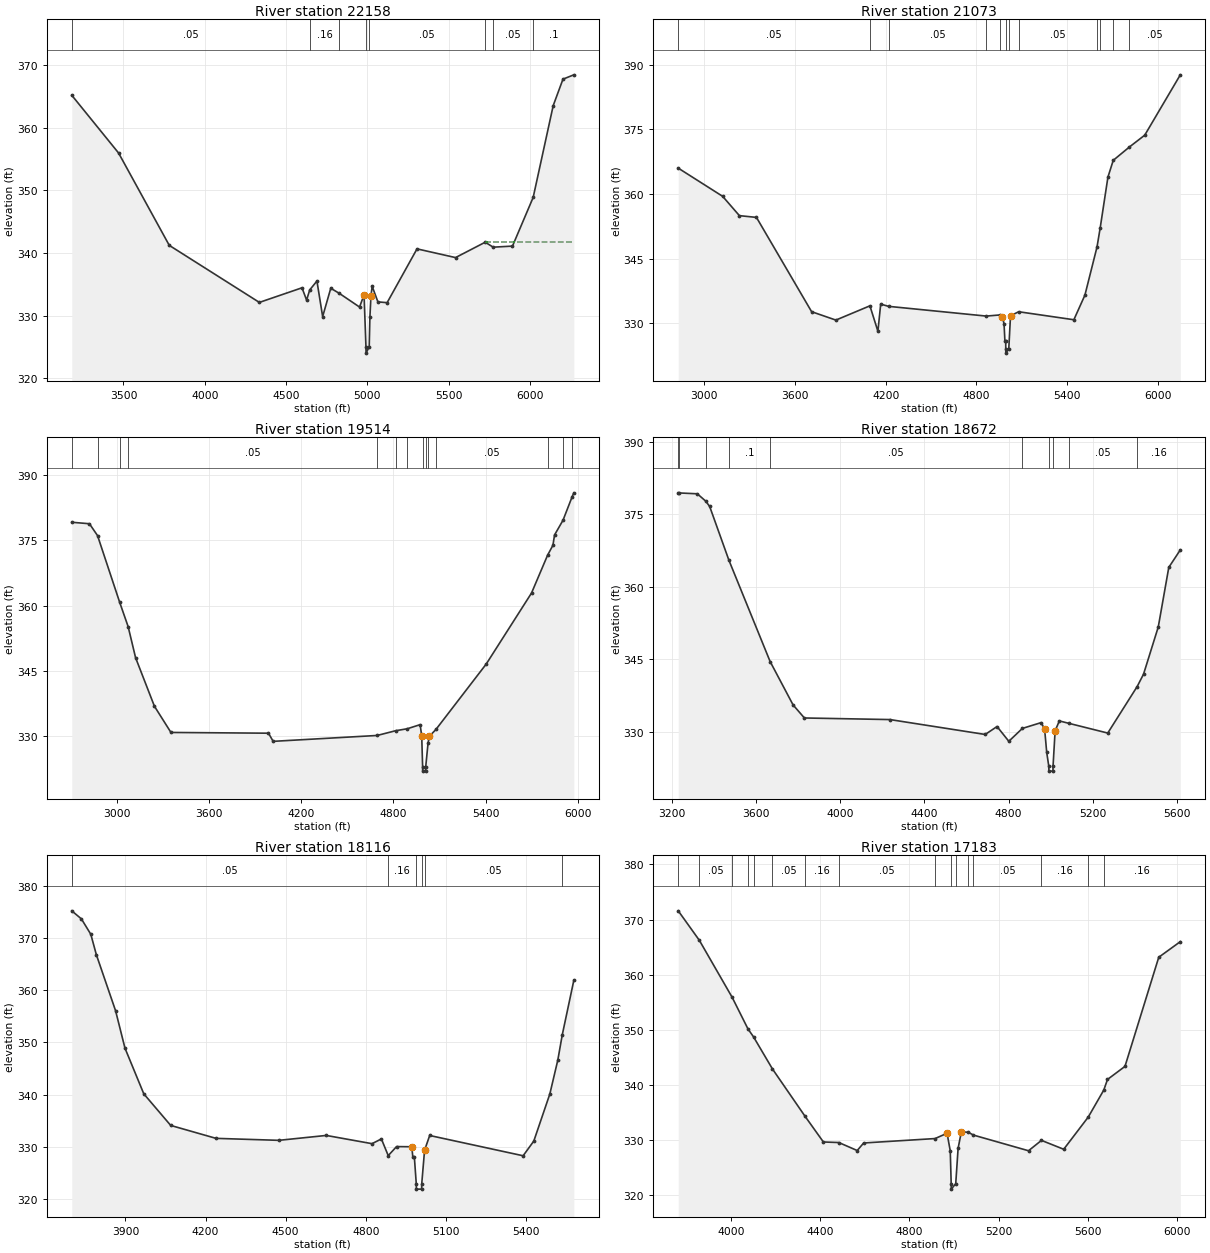
Type RM Length L Ch R = 1 ,22158   ,1085,1085,1085
BEGIN DESCRIPTION:
MINERAL CREEK 26 0
END DESCRIPTION:
XS GIS Cut Line= 5
      3524381.84      10392160.6      3524951.31     10391914.06
      3526097.15     10390872.39      3526218.67     10390518.22
      3526187.53     10389974.85
#Sta/Elev= 30
    3182  365.17  3469.9  355.96  3781.6  341.23  4335.7  332.13  4597.9  334.46
  4626.2   332.5  4645.4  334.12  4689.8  335.54  4724.9  329.87  4774.9  334.39
  4828.2  333.56  4951.9  331.39  4979.6  333.34  4991.3  325.04  4991.8  324.04
  5011.3  325.04  5015.5  329.75  5022.2  333.22  5029.6  334.69  5064.8  332.21
  5121.5  332.09  5305.3  340.67  5542.2  339.28  5724.7  341.73  5773.8  340.94
  5892.4  341.11  6019.7  348.88  6142.8  363.51  6202.9  367.74  6269.8  368.43
#Mann= 8 ,-1 , 0
    3182     .05       0  4645.4     .16       0  4828.2     .05       0
  4991.3     .03       0  5011.3     .05       0  5724.7      .1       0
  5773.8     .05       0  6019.7      .1       0
#XS Ineff= 2 , 0
                         5729.96           341.7
Permanent Ineff=
       F       F
Bank Sta=4979.6,5022.2
XS Rating Curve= 0 ,0
Exp/Cntr=0.3,0.1

Type RM Length L Ch R = 1 ,21073   ,1559,1559,1559
BEGIN DESCRIPTION:
MINERAL CREEK 25 0
END DESCRIPTION:
XS GIS Cut Line= 3
      3524798.55     10392827.23      3525048.54     10392365.45
      3527662.09     10391376.25
#Sta/Elev= 30
  2828.4  365.99  3122.1  359.44  3232.7  354.96  3345.6  354.55  3710.2  332.66
  3870.6  330.71  4095.7  334.02  4148.6  328.11    4167  334.42  4218.8   333.9
  4865.2  331.64  4953.8   331.9  4971.9  331.45  4982.6  329.84  4988.3   325.8
  4993.6  325.84  4993.9  324.04  4994.4  323.04  5013.9  324.04  5025.3  331.69
  5079.1  332.65  5444.2  330.79  5517.2   336.5  5597.3  347.69  5618.4  352.14
  5669.4   363.9  5704.6   367.8  5811.9  370.91  5912.8  373.64    6148  387.65
#Mann= 12 ,-1 , 0
  2828.4     .05       0  4095.7     .16       0  4218.8     .05       0
  4865.2     .16       0  4953.8     .12       0  4993.9     .07       0
  5013.9     .12       0  5079.1     .05       0  5597.3     .16       0
  5618.4     .05       0  5704.6     .16       0  5811.9     .05       0
Bank Sta=4971.9,5025.3
XS Rating Curve= 0 ,0
Exp/Cntr=0.3,0.1

Type RM Length L Ch R = 1 ,19514   ,842,842,842
BEGIN DESCRIPTION:
MINERAL CREEK 22 0
END DESCRIPTION:
XS GIS Cut Line= 5
      3524871.93     10393569.64      3526910.11      10392764.1
      3527194.83     10392684.24      3527934.41     10392583.54
      3527965.62     10392573.14
#Sta/Elev= 30
  2706.8  379.12  2821.8  378.78  2874.6  376.05  3018.4  360.77  3073.6  355.18
    3122  348.05  3244.6  336.92  3352.1  330.91  3986.6  330.74  4017.2  328.87
  4693.6  330.22  4813.2   331.3  4889.8  331.76  4973.2   332.7  4983.6  330.13
  4989.5  323.04    4990  322.04  5009.2  322.04  5009.7  323.04  5025.2  328.59
  5033.7  330.05    5076  331.59  5403.5  346.61  5698.1  362.89  5802.8  371.58
  5837.3  373.84  5847.9  376.21    5903  379.59  5962.5  384.99  5973.4  385.87
#Mann= 14 ,-1 , 0
  2706.8      .1       0  2874.6     .05       0  3018.4      .1       0
  3073.6     .05       0  4693.6     .16       0  4813.2     .05       0
  4889.8     .16       0  4989.5     .07       0  5009.7     .16       0
  5025.2     .12       0    5076     .05       0  5802.8     .16       0
    5903     .05       0  5962.5     .16       0
Bank Sta=4983.6,5033.7
XS Rating Curve= 0 ,0
Exp/Cntr=0.3,0.1

Type RM Length L Ch R = 1 ,18672   ,556,556,556
BEGIN DESCRIPTION:
MINERAL CREEK 20 0
END DESCRIPTION:
XS GIS Cut Line= 3
      3524956.04      10393795.8      3526483.69     10393456.32
      3527306.78     10393406.62
#Sta/Elev= 30
  3228.1  379.43  3230.3  379.41  3318.9  379.23    3359  377.71  3377.7  376.61
  3469.4  365.48  3665.4  344.55  3774.8  335.57  3828.5  332.88  4235.7  332.55
    4689  329.47  4745.4  331.11  4801.4  328.06  4865.9  330.72  4955.2  331.92
  4971.8  330.59  4981.8  325.75  4991.7  322.89  4992.2  321.89  5011.4  321.89
  5011.9  322.89  5021.8  330.23  5041.9  332.27  5086.5  331.78  5272.3  329.76
  5412.3  339.38  5442.6  341.94  5512.7   351.7  5562.8  364.02  5617.6  367.63
#Mann= 10 ,-1 , 0
  3228.1     .16       0  3230.3      .1       0    3359     .05       0
  3469.4      .1       0  3665.4     .05       0  4865.9     .16       0
  4991.7     .07       0  5011.9     .16       0  5086.5     .05       0
  5412.3     .16       0
Bank Sta=4971.8,5021.8
XS Rating Curve= 0 ,0
Exp/Cntr=0.3,0.1

Type RM Length L Ch R = 1 ,18116   ,933,933,933
BEGIN DESCRIPTION:
MINERAL CREEK 2 0
END DESCRIPTION:
XS GIS Cut Line= 3
      3525692.07     10394791.67      3526692.11     10393991.64
      3527292.13     10393991.64
#Sta/Elev= 30
    3699  375.25  3735.1   373.7  3770.3  370.75  3791.1  366.83  3863.1  356.08
  3898.3   348.9  3968.8  340.14  4069.6  334.08  4239.3   331.6  4474.6  331.22
  4652.3  332.16  4823.6  330.58  4858.8  331.49  4884.4  328.29  4915.6  330.02
  4972.5  329.99  4976.5  328.06  4982.2  328.06  4989.5  322.86    4990  321.86
  5009.4  321.86  5009.9  322.86  5020.5   329.3  5039.7  332.15  5389.7  328.26
  5429.7  331.08  5489.7   340.1  5519.7  346.63  5536.4  351.48  5579.7  361.93
#Mann= 6 ,-1 , 0
    3699     .05       0  4884.4     .16       0  4989.5     .07       0
  5009.9     .16       0  5020.5     .05       0  5536.4     .16       0
Bank Sta=4972.5,5020.5
XS Rating Curve= 0 ,0
Exp/Cntr=0.3,0.1

Type RM Length L Ch R = 1 ,17183   ,421,421,421
BEGIN DESCRIPTION:
MINERAL CREEK 19 0
END DESCRIPTION:
XS GIS Cut Line= 4
      3526031.67     10395333.52      3526973.58     10394713.48
      3527233.02     10394503.68      3527663.56     10393840.51
#Sta/Elev= 30
  3763.3  371.58    3858  366.23  4005.2  355.89  4076.4  350.14  4100.9  348.73
  4186.1  342.89  4332.1  334.32  4414.3  329.66  4483.6  329.56    4566  328.11
  4595.1  329.48  4915.3  330.28  4969.1  331.24  4983.4  328.05  4987.6  322.11
  4988.1  321.11    5008  322.11  5018.6   328.5    5033  331.48  5064.1  331.43
  5087.4  330.91  5334.4  328.07  5392.5  329.95  5492.3  328.34  5602.4  334.18
  5672.1  339.08  5688.7     341  5767.1  343.37  5918.6  363.16  6015.3  365.99
#Mann= 16 ,-1 , 0
  3763.3     .16       0    3858     .05       0  4005.2     .16       0
  4076.4     .05       0  4100.9     .16       0  4186.1     .05       0
  4332.1     .16       0  4483.6     .05       0  4915.3     .16       0
  4987.6     .07       0    5008     .16       0  5064.1     .12       0
  5087.4     .05       0  5392.5     .16       0  5602.4     .05       0
  5672.1     .16       0
Bank Sta=4969.1,5033
XS Rating Curve= 0 ,0
Exp/Cntr=0.3,0.1

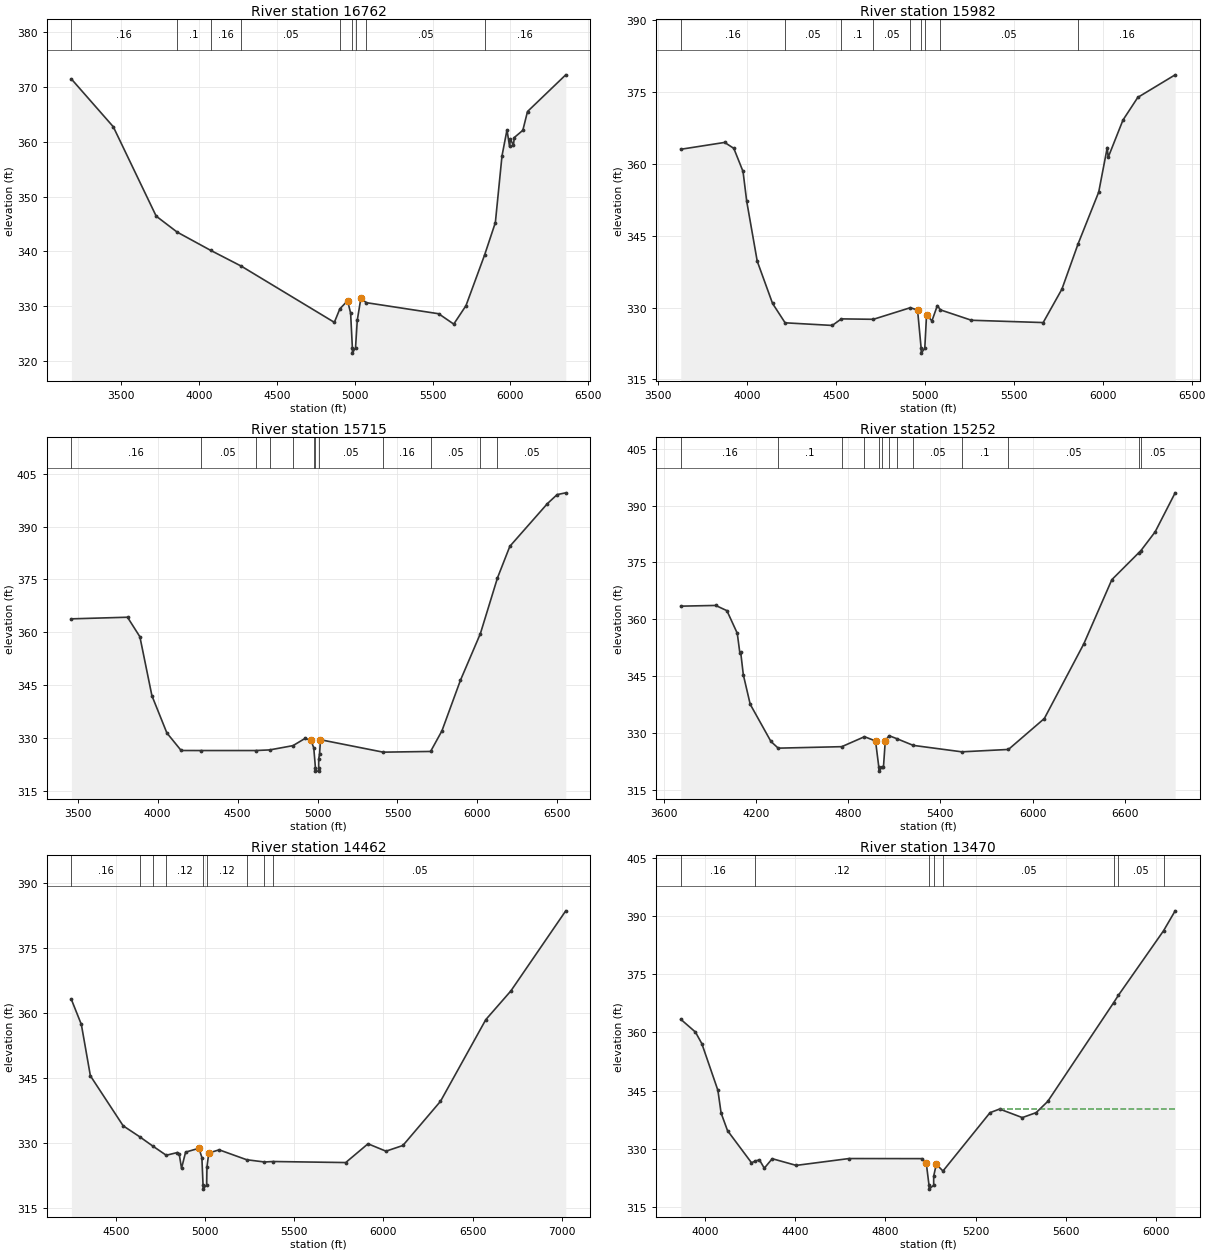
Type RM Length L Ch R = 1 ,16762   ,780,780,780
BEGIN DESCRIPTION:
MINERAL CREEK 37 0
END DESCRIPTION:
XS GIS Cut Line= 3
       3526270.5     10396330.74      3527212.35     10395345.48
      3527854.72      10393648.4
#Sta/Elev= 30
  3178.6  371.46  3447.9  362.74  3723.7  346.42  3858.2  343.51    4074  340.17
  4270.7  337.29  4868.8  327.03  4904.1  329.49    4954  330.98  4973.4  328.71
  4984.6  322.41  4985.1  321.41    5005  322.41  5016.2  327.43  5039.1  331.39
    5075  330.62  5539.3   328.6  5636.3  326.71  5714.9  330.08  5834.8  339.35
  5903.7  345.24  5946.4  357.42  5978.5  362.17  5995.1  359.14  6000.5  360.48
  6019.9  359.34  6025.3  360.77  6080.3  362.09  6110.4  365.52  6356.2  372.22
#Mann= 9 ,-1 , 0
  3178.6     .16       0  3858.2      .1       0    4074     .16       0
  4270.7     .05       0  4904.1     .16       0  4984.6     .07       0
    5005     .16       0    5075     .05       0  5834.8     .16       0
Bank Sta=4954,5039.1
XS Rating Curve= 0 ,0
Exp/Cntr=0.3,0.1

Type RM Length L Ch R = 1 ,15982   ,267,267,267
BEGIN DESCRIPTION:
MINERAL CREEK 29 0
END DESCRIPTION:
XS GIS Cut Line= 4
      3527543.53     10396249.13      3527856.37     10395101.77
      3527938.51     10394486.94      3528051.16     10393525.05
#Sta/Elev= 30
  3629.3  363.03  3875.8  364.46  3927.3  363.22  3979.1   358.4  3999.8  352.16
  4058.9  339.67  4144.9  330.86  4215.5  326.81  4480.5  326.26  4531.6  327.63
  4711.5  327.54    4920  329.97  4959.9  329.45    4980  321.48  4980.5  320.48
  5000.4  321.48  5010.4  328.45  5040.6  327.21  5070.9   330.4  5088.3  329.51
  5262.6  327.34  5665.7  326.86    5771  333.84    5862   343.3  5977.8   354.1
  6025.8   363.4  6030.9  361.34  6114.1  369.13  6197.4  373.86  6407.3  378.57
#Mann= 9 ,-1 , 0
  3629.3     .16       0  4215.5     .05       0  4531.6      .1       0
  4711.5     .05       0    4920     .16       0    4980     .07       0
  5000.4     .16       0  5088.3     .05       0    5862     .16       0
Bank Sta=4959.9,5010.4
XS Rating Curve= 0 ,0
Exp/Cntr=0.3,0.1

Type RM Length L Ch R = 1 ,15715   ,463,463,463
BEGIN DESCRIPTION:
MINERAL CREEK 38 0
END DESCRIPTION:
XS GIS Cut Line= 3
      3527576.92     10396369.83      3528262.58     10394635.07
       3528466.7     10393427.04
#Sta/Elev= 30
  3461.4  363.78  3812.2  364.24  3889.6   358.7  3964.8  341.95  4058.3  331.37
  4147.6  326.38  4270.3  326.37  4612.7  326.37  4701.4  326.55  4846.7  327.76
  4921.8   329.8  4958.8  329.29  4976.7  327.11  4986.9  321.52  4987.4  320.52
  5006.8  320.52  5007.3  321.52  5007.5  324.02  5012.9  325.31  5018.6  329.44
  5410.3  325.91    5707  326.11  5777.8  331.96  5893.6  346.34    6018  359.56
  6125.2  375.43  6202.4  384.39  6437.5  396.53    6498  399.08  6551.9  399.58
#Mann= 12 ,-1 , 0
  3461.4     .16       0  4270.3     .05       0  4612.7      .1       0
  4701.4     .05       0  4846.7     .16       0  4976.7     .05       0
  4986.9     .03       0  5007.3     .05       0  5410.3     .16       0
    5707     .05       0    6018     .16       0  6125.2     .05       0
Bank Sta=4958.8,5018.6
XS Rating Curve= 0 ,0
Exp/Cntr=0.3,0.1

Type RM Length L Ch R = 1 ,15252   ,790,790,790
BEGIN DESCRIPTION:
MINERAL CREEK 28 0
END DESCRIPTION:
XS GIS Cut Line= 3
       3527746.9     10396360.44      3528265.01      10395304.5
      3530198.18     10394643.67
#Sta/Elev= 30
  3709.6  363.48  3936.8  363.67  4009.9  362.29  4077.4  356.33  4094.3  351.12
  4099.8   351.3  4116.8  345.39  4161.7   337.6  4296.7  327.79  4343.9  326.03
  4757.9  326.42  4905.9  329.05  4977.8  327.92  4999.4  320.97  4999.9  319.97
  5019.8  320.97  5029.6  321.16  5041.3     328  5066.2  329.31  5117.6  328.51
  5223.5  326.76  5539.8  325.06  5843.3  325.69  6076.9  333.84    6334  353.54
  6516.6  370.47    6693  377.61  6704.4  378.05  6798.4  383.07  6928.8  393.37
#Mann= 13 ,-1 , 0
  3709.6     .16       0  4343.9      .1       0  4757.9     .05       0
  4905.9     .16       0  4999.4     .07       0  5019.8     .16       0
  5066.2     .05       0  5117.6     .16       0  5223.5     .05       0
  5539.8      .1       0  5843.3     .05       0    6693      .1       0
  6704.4     .05       0
Bank Sta=4977.8,5041.3
XS Rating Curve= 0 ,0
Exp/Cntr=0.3,0.1

Type RM Length L Ch R = 1 ,14462   ,992,992,992
BEGIN DESCRIPTION:
MINERAL CREEK 18 0
END DESCRIPTION:
XS GIS Cut Line= 4
      3528302.47     10396666.87      3528392.74     10396093.96
      3528548.99     10395760.62      3530104.51     10394809.26
#Sta/Elev= 30
  4251.1  363.07    4307  357.31  4357.6  345.49  4541.4  333.97  4633.7  331.46
  4708.7  329.27  4782.9  327.19  4845.8  327.82  4855.7  327.44  4868.6  324.17
  4891.4  327.91  4966.2   328.8  4982.7  326.67  4989.1  320.39  4989.6  319.39
  5009.6  320.39  5011.1  324.48  5021.4  327.71  5079.5  328.44  5233.7  326.16
  5333.7  325.64  5382.2  325.75    5789  325.51    5914  329.83  6014.7  328.13
  6109.5  329.44  6320.4  339.62  6574.3  358.42    6715  365.04  7022.6  383.48
#Mann= 9 ,-1 , 0
  4251.1     .16       0  4633.7     .12       0  4708.7      .1       0
  4782.9     .12       0  4989.1     .07       0  5009.6     .12       0
  5233.7     .05       0  5333.7     .12       0  5382.2     .05       0
Bank Sta=4966.2,5021.4
XS Rating Curve= 0 ,0
Exp/Cntr=0.3,0.1

Type RM Length L Ch R = 1 ,13470   ,794,794,794
BEGIN DESCRIPTION:
MINERAL CREEK 17 0
END DESCRIPTION:
XS GIS Cut Line= 4
      3528687.86     10396649.54      3529333.72     10395927.29
      3529420.52     10395621.74      3530304.65     10395436.37
#Sta/Elev= 30
  3893.2  363.37  3958.1  360.08  3986.5  357.09  4057.6  345.09  4071.8  339.24
  4100.2  334.72  4206.4  326.45  4223.9   326.9  4241.5  327.19  4263.2  325.05
  4298.3  327.49  4404.5  325.77  4638.5  327.53  4961.5  327.51  4980.7  326.33
  4992.8  320.66  4993.3  319.66  5013.4  320.66  5013.5  322.99    5025  326.07
  5054.6  324.32  5263.1  339.34  5305.6  340.27  5406.1  338.07  5467.5  339.35
  5518.5  342.22  5811.1  367.68  5832.1  369.58  6031.8  386.16  6083.1  391.28
#Mann= 8 ,-1 , 0
  3893.2     .16       0  4223.9     .12       0  4992.8     .07       0
  5013.4     .12       0  5054.6     .05       0  5811.1     .16       0
  5832.1     .05       0  6031.8     .16       0
#XS Ineff= 2 , 0
                         5301.05          340.39
Permanent Ineff=
       F       F
Bank Sta=4980.7,5025
XS Rating Curve= 0 ,0
Exp/Cntr=0.3,0.1

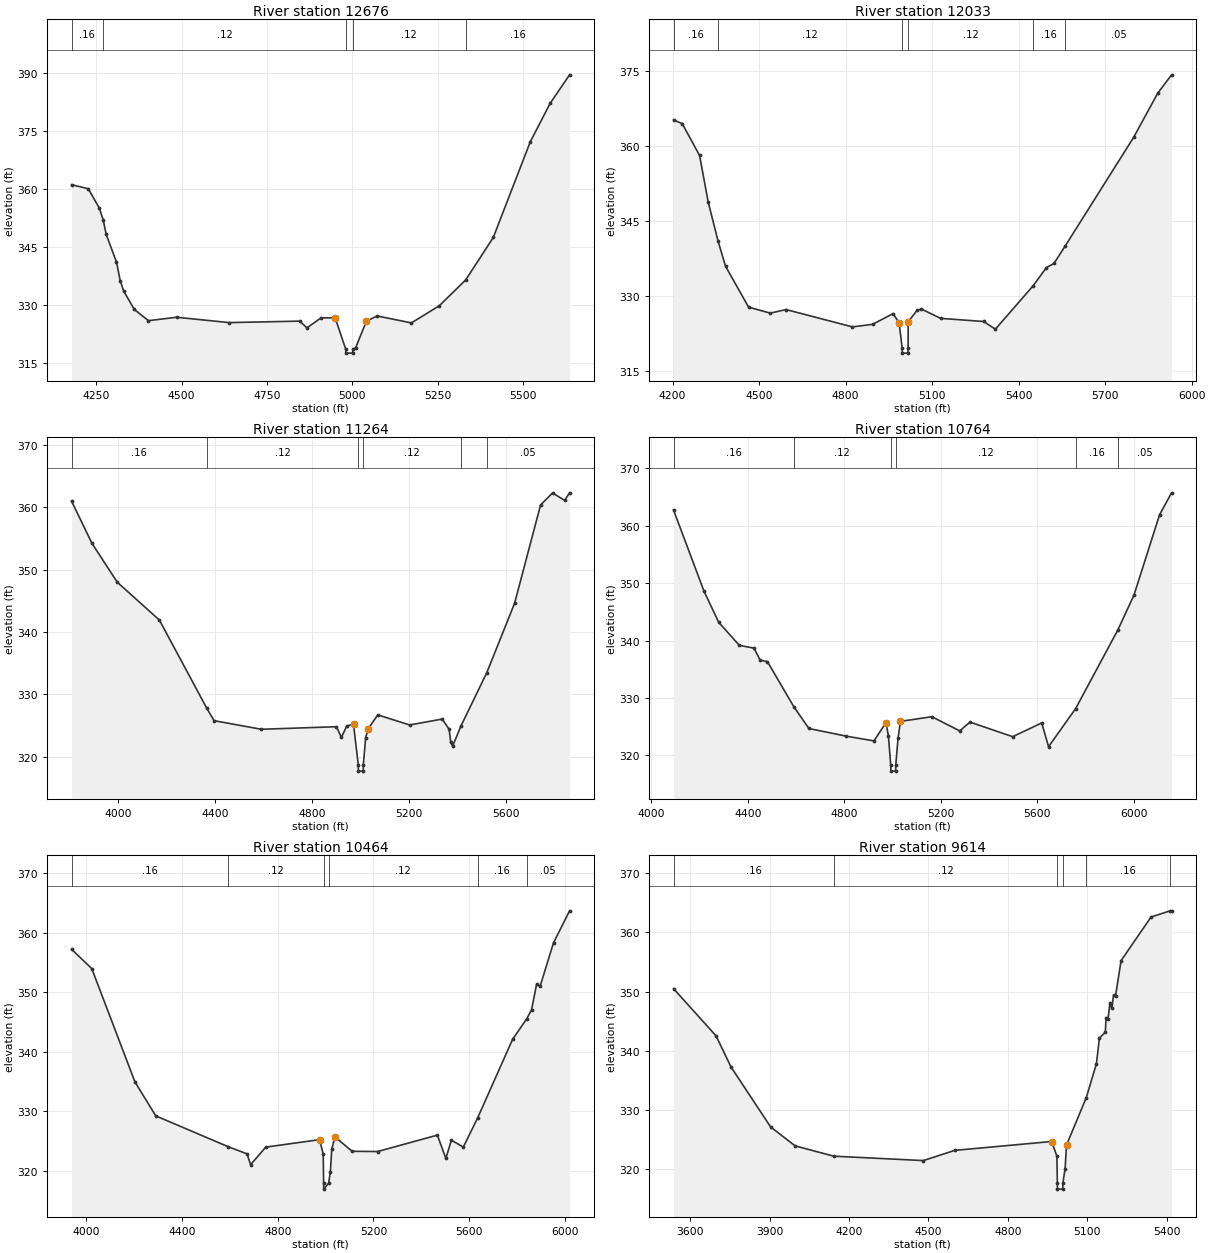
Type RM Length L Ch R = 1 ,12676   ,643,643,643
BEGIN DESCRIPTION:
MINERAL CREEK 16 0
END DESCRIPTION:
XS GIS Cut Line= 3
      3528903.86     10396639.57      3529703.91     10396439.56
      3530303.89     10396239.57
#Sta/Elev= 30
  4178.3  361.17  4227.2  360.12    4259   355.2  4270.5  352.16  4279.6  348.32
  4309.7  341.15  4320.8  336.28  4331.1   333.6    4362  328.88  4403.3  325.99
  4485.7  326.87  4639.6  325.49  4845.7  325.87  4867.1  324.13  4908.3  326.72
  4949.6  326.72  4980.5  318.59    4981  317.59  5000.6  317.59  5001.1  318.59
  5009.3  318.94  5040.9  325.85  5072.5   327.2  5172.7  325.41  5254.1  329.84
  5331.3  336.51  5412.2  347.52  5520.5  372.28  5578.5  382.21  5635.4  389.59
#Mann= 5 ,-1 , 0
  4178.3     .16       0  4270.5     .12       0  4980.5     .07       0
  5001.1     .12       0  5331.3     .16       0
Bank Sta=4949.6,5040.9
XS Rating Curve= 0 ,0
Exp/Cntr=0.3,0.1

Type RM Length L Ch R = 1 ,12033   ,769,769,769
BEGIN DESCRIPTION:
MINERAL CREEK 15 0
END DESCRIPTION:
XS GIS Cut Line= 3
      3528871.92     10397041.87      3529604.55     10397052.29
      3530558.24     10396771.39
#Sta/Elev= 30
  4203.4  365.15  4233.6   364.4  4293.6  358.04  4323.6  348.73    4358  340.89
  4383.6  335.93  4463.6  327.75  4538.7  326.56  4593.6  327.27  4823.6  323.81
  4893.7  324.32  4964.8  326.47  4985.7  324.56  4996.2  319.57  4996.7  318.57
  5016.3  318.57  5016.8  319.57  5016.9  324.81  5048.2  327.15  5063.1  327.36
  5129.7  325.51  5278.7  324.89  5319.3  323.35  5450.3  332.02  5496.5  335.67
  5522.5  336.47  5561.5  339.97  5798.8  361.66  5882.2  370.47  5930.3  374.15
#Mann= 6 ,-1 , 0
  4203.4     .16       0    4358     .12       0  4996.2     .07       0
  5016.8     .12       0  5450.3     .16       0  5561.5     .05       0
Bank Sta=4985.7,5016.9
XS Rating Curve= 0 ,0
Exp/Cntr=0.3,0.1

Type RM Length L Ch R = 1 ,11264   ,500,500,500
BEGIN DESCRIPTION:
MINERAL CREEK 14 0
END DESCRIPTION:
XS GIS Cut Line= 4
      3528760.82     10398038.39      3529618.44     10397507.15
      3529903.16     10397482.85      3530492.09     10397002.76
#Sta/Elev= 30
  3806.5     361    3891  354.21    3995  347.99  4168.7  341.92  4364.8  327.72
  4394.4  325.76  4589.3  324.38  4899.3  324.79  4919.4  323.06  4941.7   324.9
  4969.6  325.19  4989.3  318.66  4989.8  317.66  5009.5  317.66    5010  318.66
  5019.7  323.04  5029.8  324.45  5069.9  326.69  5201.2  325.07  5335.4  326.02
  5364.2  324.38  5370.7  322.29  5378.5  321.67  5412.9  324.92  5519.6  333.48
  5634.2  344.62  5741.2  360.38  5790.7  362.33  5840.2  361.13  5860.9  362.34
#Mann= 6 ,-1 , 0
  3806.5     .16       0  4364.8     .12       0  4989.3     .07       0
    5010     .12       0  5412.9     .16       0  5519.6     .05       0
Bank Sta=4969.6,5029.8
XS Rating Curve= 0 ,0
Exp/Cntr=0.3,0.1

Type RM Length L Ch R = 1 ,10764   ,300,300,300
BEGIN DESCRIPTION:
MINERAL CREEK 13 0
END DESCRIPTION:
XS GIS Cut Line= 4
      3528792.09     10398141.65      3529548.99     10397861.32
      3529837.19     10397854.37      3530492.13     10397141.61
#Sta/Elev= 30
  4092.5  362.74  4218.6  348.61  4279.4  343.19  4365.2  339.16    4426  338.68
  4451.1  336.59  4481.5  336.32  4590.9  328.47  4653.2  324.68    4807  323.35
  4922.8  322.52  4972.8  325.71  4982.8  323.35  4992.4  318.25  4992.9  317.25
  5012.6  317.25  5013.1  318.25  5022.8  323.06  5032.8  325.92  5162.8  326.73
  5278.2  324.26  5320.7  325.79  5497.7  323.25  5617.9  325.65  5646.3  321.51
  5758.5  328.15  5933.3  341.85  6000.2  347.92  6106.2  361.92  6155.9  365.74
#Mann= 6 ,-1 , 0
  4092.5     .16       0  4590.9     .12       0  4992.4     .07       0
  5013.1     .12       0  5758.5     .16       0  5933.3     .05       0
Bank Sta=4972.8,5032.8
XS Rating Curve= 0 ,0
Exp/Cntr=0.3,0.1

Type RM Length L Ch R = 1 ,10464   ,850,850,850
BEGIN DESCRIPTION:
MINERAL CREEK 12 1
END DESCRIPTION:
XS GIS Cut Line= 3
      3529290.32     10398896.87       3529890.3      10397996.9
      3530490.28     10397196.92
#Sta/Elev= 30
    3938   357.2  4022.4  353.95  4202.7  334.92  4289.8  329.19  4591.6  324.02
  4671.4   322.8  4686.4  320.98  4749.5  323.93  4974.8  325.19  4989.9  322.75
  4991.5  317.87    4992  316.87  5012.3  317.87  5019.6  319.68  5025.5  323.55
  5038.7  325.66  5110.9  323.23  5217.1  323.19  5467.1  325.95  5502.5  322.03
  5525.5   325.1  5575.5  323.94  5635.9  328.89  5781.7  342.08  5840.7  345.51
  5860.9  347.06  5881.7   351.3  5896.3  350.96  5952.5  358.28  6019.6  363.66
#Mann= 6 ,-1 , 0
    3938     .16       0  4591.6     .12       0  4991.5     .07       0
  5012.3     .12       0  5635.9     .16       0  5840.7     .05       0
Bank Sta=4974.8,5038.7
XS Rating Curve= 0 ,0
Exp/Cntr=0.3,0.1

Type RM Length L Ch R = 1 ,9614    ,720,720,720
BEGIN DESCRIPTION:
MINERAL CREEK 12 0
END DESCRIPTION:
XS GIS Cut Line= 3
       3529954.2     10399230.03      3530496.66     10397690.41
      3530667.66     10397507.47
#Sta/Elev= 30
  3536.3  350.49  3697.2  342.51  3753.8  337.25  3903.3  327.15  3996.1  323.95
  4142.3  322.21  4480.7  321.47  4599.2  323.19  4965.9  324.69  4985.7  322.19
  4987.3  317.65  4987.8  316.65  5007.6  316.65  5008.1  317.65  5016.6   320.1
  5021.9  324.09  5096.5  332.07  5135.1  337.82  5146.2  342.15  5168.7  343.15
  5171.6   345.6  5178.9  345.32  5185.8     348  5193.1  347.16  5199.9   349.4
  5207.2  349.25  5228.3  355.23  5341.6  362.59  5413.8  363.63  5419.1  363.54
#Mann= 6 ,-1 , 0
  3536.3     .16       0  4142.3     .12       0  4987.3     .07       0
  5008.1     .12       0  5096.5     .16       0  5413.8     .05       0
Bank Sta=4965.9,5021.9
XS Rating Curve= 0 ,0
Exp/Cntr=0.3,0.1