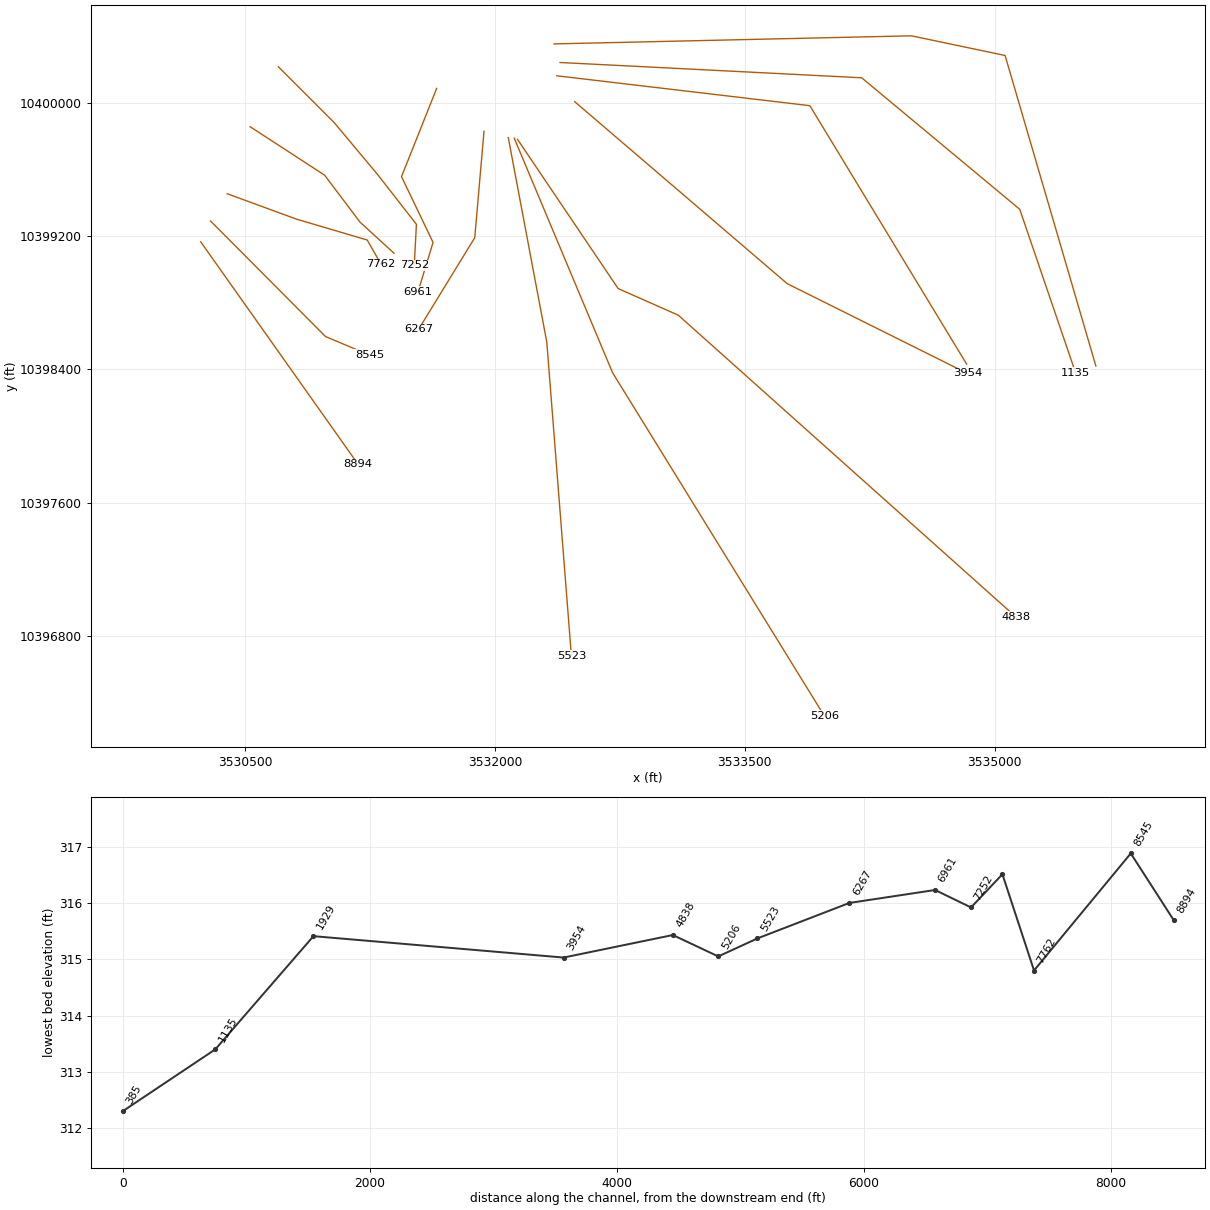
HEC-RAS study MINERAL CREEK.prj: MINERAL CREEK Base Level Engineering

--- MINERAL CREEK.g01 (geometry) --- (continued)

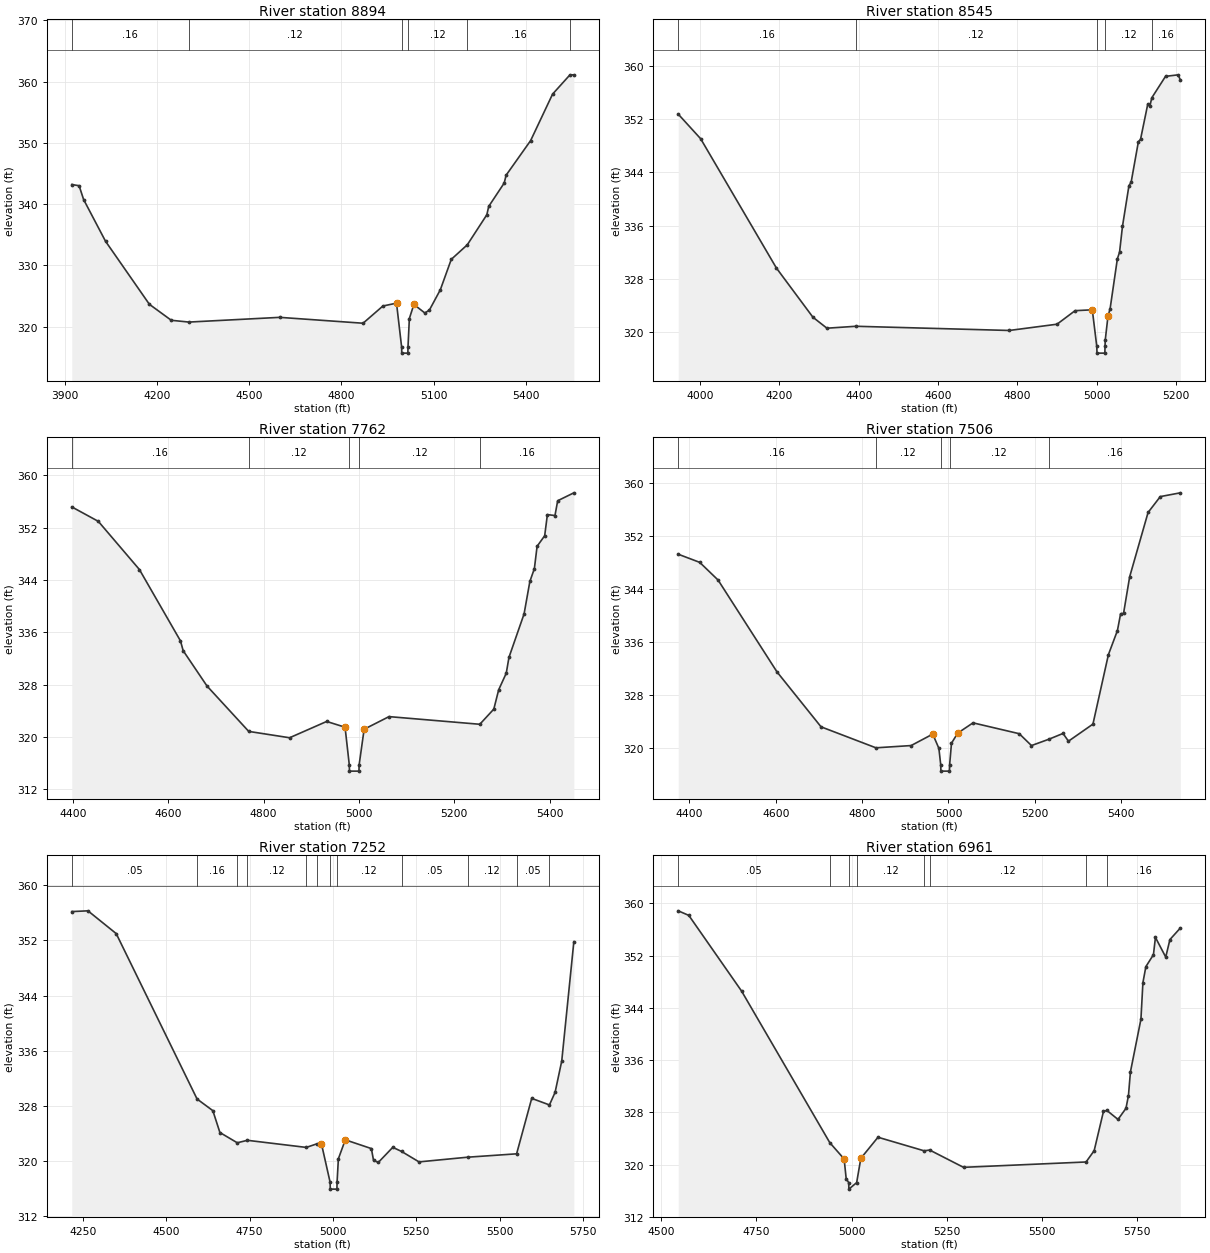
Type RM Length L Ch R = 1 ,8894    ,349,349,349
BEGIN DESCRIPTION:
MINERAL CREEK 10 3
END DESCRIPTION:
XS GIS Cut Line= 2
       3530233.4     10399166.23      3531177.91     10397831.16
#Sta/Elev= 30
  3921.6  343.21  3945.5  343.02  3960.2  340.76  4031.6  333.95  4174.4  323.66
  4245.8  321.05  4303.1  320.76  4599.1  321.53  4870.4  320.57    4935  323.38
  4979.4  323.85    4996  316.69  4996.5  315.69  5016.3  315.69  5016.8  316.69
  5021.2  321.34    5036  323.64  5071.7  322.24  5086.5  322.72  5122.1  326.03
  5157.8     331  5209.9  333.37  5273.6  338.28  5279.7  339.64  5330.2  343.46
  5336.3  344.73  5416.3  350.39  5487.7  357.97  5544.4  361.12    5557  361.11
#Mann= 6 ,-1 , 0
  3921.6     .16       0  4303.1     .12       0    4996     .07       0
  5016.8     .12       0  5209.9     .16       0  5544.4     .05       0
Bank Sta=4979.4,5036
XS Rating Curve= 0 ,0
Exp/Cntr=0.3,0.1

Type RM Length L Ch R = 1 ,8545    ,783,783,783
BEGIN DESCRIPTION:
MINERAL CREEK 9 2
END DESCRIPTION:
XS GIS Cut Line= 3
      3530292.13     10399291.62      3530983.02     10398597.43
      3531246.52     10398486.49
#Sta/Elev= 30
  3945.1  352.74  4001.6  349.05  4192.6  329.64  4284.5  322.27  4319.8  320.62
  4392.7  320.91  4779.4  320.28  4899.7  321.22  4945.2  323.25  4988.6  323.38
  4999.9  317.88  5000.4  316.88  5020.2  316.88  5020.7  317.88  5021.2  318.82
  5028.1  322.41  5033.5  323.55  5051.8  331.04  5057.3  332.03  5064.6  335.89
    5081  342.02  5086.4   342.5  5104.7  348.59  5110.2  348.97  5128.5  354.28
  5133.9  353.99  5138.5  355.19  5173.1  358.41  5205.1  358.64  5210.4  357.87
#Mann= 5 ,-1 , 0
  3945.1     .16       0  4392.7     .12       0  4999.9     .07       0
  5020.7     .12       0  5138.5     .16       0
Bank Sta=4988.6,5028.1
XS Rating Curve= 0 ,0
Exp/Cntr=0.3,0.1

Type RM Length L Ch R = 1 ,7762    ,256,256,256
BEGIN DESCRIPTION:
MINERAL CREEK 10 2
END DESCRIPTION:
XS GIS Cut Line= 4
      3530392.73     10399455.07      3530809.41     10399302.29
      3531233.02     10399177.29      3531316.34     10399031.49
#Sta/Elev= 30
  4397.4  355.18  4453.1  352.97  4539.3  345.61  4625.5   334.7  4631.1  333.21
  4681.2   327.8  4768.7  320.87  4854.4   319.9  4932.2  322.39  4970.8  321.51
  4979.6   315.8  4980.1   314.8  4999.9   314.8  5000.4   315.8  5010.8   321.2
    5063  323.13  5253.5  321.96  5282.9  324.28  5293.1  327.23    5309  329.77
  5314.7  332.19  5346.4  338.83  5358.5  343.78    5368  345.75  5373.7  349.16
  5389.6  350.77  5395.3     354  5411.2  353.86  5416.9  356.12  5450.8  357.33
#Mann= 5 ,-1 , 0
  4397.4     .16       0  4768.7     .12       0  4979.6     .07       0
  5000.4     .12       0  5253.5     .16       0
Bank Sta=4970.8,5010.8
XS Rating Curve= 0 ,0
Exp/Cntr=0.3,0.1

Type RM Length L Ch R = 1 ,7506    ,254,254,254
BEGIN DESCRIPTION:
MINERAL CREEK 11 0
END DESCRIPTION:
XS GIS Cut Line= 4
      3530530.36     10399857.41      3530977.41     10399566.62
      3531190.08      10399284.5      3531394.08     10399097.86
#Sta/Elev= 30
    4374  349.26  4423.8  348.03  4466.3  345.36  4602.7   331.5  4704.8   323.2
    4832  320.03  4913.5  320.37  4963.6   322.1  4977.8  319.95    4982  317.51
  4982.5  316.51  5002.3  316.51  5002.8  317.51    5007  320.73  5021.5  322.25
  5056.9   323.8    5164  322.16  5192.3  320.37  5232.8  321.33  5265.4   322.2
    5278  321.03  5334.7  323.61  5370.5  334.09  5391.4  337.73  5398.8  340.27
  5405.6  340.32  5419.8  345.86  5462.4  355.56  5490.7  357.96  5537.1  358.53
#Mann= 5 ,-1 , 0
    4374     .16       0    4832     .12       0    4982     .07       0
  5002.8     .12       0  5232.8     .16       0
Bank Sta=4963.6,5021.5
XS Rating Curve= 0 ,0
Exp/Cntr=0.3,0.1

Type RM Length L Ch R = 1 ,7252    ,291,291,291
BEGIN DESCRIPTION:
MINERAL CREEK 9 15
END DESCRIPTION:
XS GIS Cut Line= 5
      3530699.61     10400217.68      3531033.83     10399883.46
      3531298.59     10399566.62      3531528.62     10399271.48
      3531515.67     10399025.38
#Sta/Elev= 30
  4216.7  356.17  4265.2  356.28    4350  352.98  4592.6  328.99  4639.9   327.3
  4661.1  324.13  4713.2  322.64  4743.5     323  4920.2  321.97    4951  322.47
  4965.8  322.48  4991.7  316.92  4992.2  315.92  5012.1  315.92  5012.6  316.92
  5016.5  320.32  5037.3  323.07  5115.5   321.8  5121.9  320.11  5136.3  319.79
  5179.7  321.98  5205.9  321.39  5258.4  319.87  5404.1  320.55  5551.2  321.04
  5596.5  329.08  5649.7  328.13  5666.6  329.95  5686.6   334.5  5722.9   351.8
#Mann= 12 ,-1 , 0
  4216.7     .05       0  4592.6     .16       0  4713.2     .05       0
  4743.5     .12       0  4920.2     .05       0    4951     .12       0
  4991.7     .07       0  5012.6     .12       0  5205.9     .05       0
  5404.1     .12       0  5551.2     .05       0  5649.7     .16       0
Bank Sta=4965.8,5037.3
XS Rating Curve= 0 ,0
Exp/Cntr=0.3,0.1

Type RM Length L Ch R = 1 ,6961    ,694,694,694
BEGIN DESCRIPTION:
MINERAL CREEK 9 18
END DESCRIPTION:
XS GIS Cut Line= 4
      3531650.17     10400087.49      3531439.12     10399557.82
      3531628.45     10399162.97      3531537.77     10398865.02
#Sta/Elev= 30
  4544.5  358.87  4572.3  358.17  4710.9  346.58  4942.8  323.35  4980.5  320.85
  4985.9  317.82  4992.5  317.23    4993  316.23  5013.4  317.23  5024.4  320.95
  5069.5  324.18  5190.7   322.1  5205.3  322.22  5294.2  319.57  5616.3  320.39
  5637.6  322.12    5662  328.13  5670.9  328.29  5700.3  326.91  5721.2  328.61
  5727.7  330.56  5732.9  334.19  5760.5  342.26  5765.7  347.86  5773.5  350.32
  5793.4  352.15  5798.6   354.8  5825.7  351.78  5836.7  354.47    5864  356.23
#Mann= 8 ,-1 , 0
  4544.5     .05       0  4942.8     .12       0  4992.5     .07       0
  5013.4     .12       0  5190.7     .05       0  5205.3     .12       0
  5616.3     .05       0  5670.9     .16       0
Bank Sta=4980.5,5024.4
XS Rating Curve= 0 ,0
Exp/Cntr=0.3,0.1

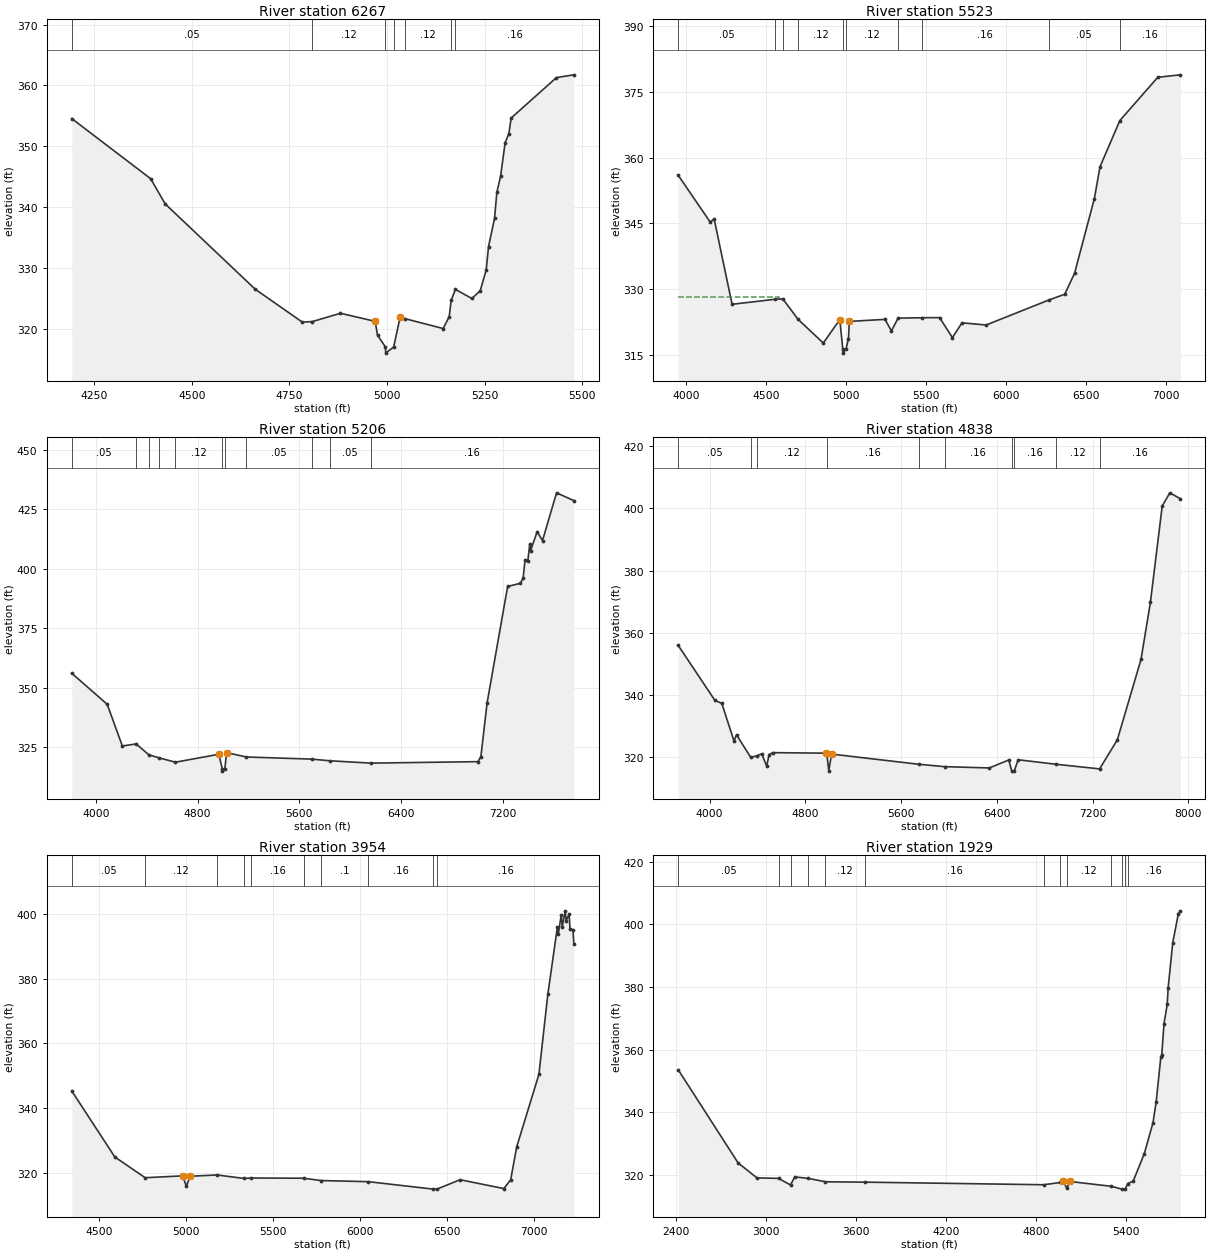
Type RM Length L Ch R = 1 ,6267    ,744,744,744
BEGIN DESCRIPTION:
MINERAL CREEK 9 1
END DESCRIPTION:
XS GIS Cut Line= 3
      3531934.41     10399830.06      3531878.86     10399191.18
       3531542.1     10398641.64
#Sta/Elev= 30
  4192.5  354.55  4394.5  344.67  4431.8  340.52  4662.7  326.48  4783.1  321.09
  4808.8  321.19  4880.7  322.55  4969.6  321.22  4975.5  318.95  4995.9     317
  4996.4     316  5016.8     317  5033.5  321.92  5046.1  321.66  5143.7  320.04
  5159.1     322  5164.1  324.66    5175  326.48  5217.2  324.98  5238.5  326.25
  5253.9  329.68  5259.8  333.52  5275.2  338.13  5281.1   342.4  5290.6  345.04
  5302.4  350.61  5311.9  352.08  5317.8  354.64  5433.8  361.29  5478.3  361.74
#Mann= 7 ,-1 , 0
  4192.5     .05       0  4808.8     .12       0  4995.9     .07       0
  5016.8     .12       0  5046.1     .12       0  5164.1     .05       0
    5175     .16       0
Bank Sta=4969.6,5033.5
XS Rating Curve= 0 ,0
Exp/Cntr=0.3,0.1

Type RM Length L Ch R = 1 ,5523    ,317,317,317
BEGIN DESCRIPTION:
MINERAL CREEK 9 0
END DESCRIPTION:
XS GIS Cut Line= 3
      3532080.18     10399792.43      3532311.52     10398563.93
       3532459.1      10396681.3
#Sta/Elev= 30
  3949.8  355.97  4149.2  345.31  4174.5  345.96  4286.4  326.52    4554  327.66
  4603.1  327.77  4699.3  323.07  4856.6  317.67  4959.9  323.04  4978.1  316.37
  4978.6  315.37    4999  316.37    5014   318.7  5019.1  322.61  5242.3  323.08
  5282.4  320.44    5324  323.36  5474.6  323.45  5583.4  323.48  5663.6  318.92
  5723.8  322.29  5874.2  321.79  6264.6  327.47  6365.7  328.81    6427  333.57
  6551.1  350.66  6586.4  357.93  6710.6  368.48  6947.5  378.35  7088.3  378.91
#Mann= 10 ,-1 , 0
  3949.8     .05       0    4554      .1       0  4603.1     .05       0
  4699.3     .12       0  4978.1     .07       0    4999     .12       0
    5324     .05       0  5474.6     .16       0  6264.6     .05       0
  6710.6     .16       0
#XS Ineff= 2 , 0
         4579.89  328.27
Permanent Ineff=
       F       F
Bank Sta=4959.9,5019.1
XS Rating Curve= 0 ,0
Exp/Cntr=0.3,0.1

Type RM Length L Ch R = 1 ,5206    ,368,368,368
BEGIN DESCRIPTION:
Mapping XS c1c28d5d
END DESCRIPTION:
XS GIS Cut Line= 3
      3532116.08     10399788.44       3532706.4     10398380.45
      3533977.93      10396319.7
#Sta/Elev= 30
    3811  356.14  4089.5  343.12  4208.7  325.61  4317.1  326.48  4417.1  321.91
  4494.1  320.67  4626.5   318.8  4967.8  322.13  4994.1  316.05  4994.6  315.05
    5015  316.05  5028.3  322.86  5181.6  320.99  5698.9  320.09  5839.3   319.4
  6162.9  318.41  7004.9  319.03  7028.2  321.11  7076.7  343.58  7238.7  392.61
  7339.2   393.9  7360.5  396.16  7375.9  403.83  7397.2  403.23  7412.6  410.51
  7418.4  407.49  7470.5  415.58    7513  411.88  7623.1   431.9  7759.2  428.63
#Mann= 11 ,-1 , 0
    3811     .05       0  4317.1      .1       0  4417.1     .05       0
  4494.1      .1       0  4626.5     .12       0  4994.1     .07       0
    5015     .12       0  5181.6     .05       0  5698.9      .1       0
  5839.3     .05       0  6162.9     .16       0
Bank Sta=4967.8,5028.3
XS Rating Curve= 0 ,0
Exp/Cntr=0.3,0.1

Type RM Length L Ch R = 1 ,4838    ,884,884,884
BEGIN DESCRIPTION:
MINERAL CREEK 8 0
END DESCRIPTION:
XS GIS Cut Line= 4
      3532135.81     10399781.44      3532739.97     10398885.62
      3533101.08      10398725.9      3535127.95     10396914.21
#Sta/Elev= 30
  3737.9  355.89  4044.7  338.17  4101.7  337.24  4203.6  325.13  4224.6  327.13
  4343.2  319.87  4396.3  320.38  4434.5     321  4476.5  317.11  4497.5  320.75
  4527.4  321.38  4973.8  321.21  4979.9  320.59  4995.7  315.52  5018.3  320.92
  5746.1  317.64    5963  316.87  6336.1  316.45  6499.1  319.02  6523.7  315.43
  6544.6  315.43  6576.8  319.09  6892.1  317.65  7257.5  316.15  7405.3  325.46
  7603.4  351.36  7681.9  369.72  7780.6  400.75  7844.2     405  7931.8  403.11
#Mann= 10 ,-1 , 0
  3737.9     .05       0  4343.2      .1       0  4396.3     .12       0
  4979.9     .16       0  5746.1      .1       0    5963     .16       0
  6523.7     .07       0  6544.6     .16       0  6892.1     .12       0
  7257.5     .16       0
Bank Sta=4973.8,5018.3
XS Rating Curve= 0 ,0
Exp/Cntr=0.3,0.1

Type RM Length L Ch R = 1 ,3954    ,2025,2025,2025
BEGIN DESCRIPTION:
MINERAL CREEK 6 0
END DESCRIPTION:
XS GIS Cut Line= 3
      3532479.08     10400007.81      3533755.43     10398914.94
      3534836.14     10398376.57
#Sta/Elev= 30
  4343.5  345.31  4591.2  324.95  4765.6  318.55  4980.8  319.12  5002.8  315.89
  5023.6     319  5179.4   319.4  5335.6  318.32  5374.9  318.46  5677.4  318.39
  5778.8  317.67  6049.9  317.33    6423  315.03  6443.9  315.03  6576.9  317.93
  6828.7   315.2  6867.9  317.92  6902.7   328.1  7030.2  350.42  7081.5  375.09
  7136.5  395.86  7142.1  393.86  7158.9   399.7  7164.5   395.9  7181.3  400.89
  7186.9  397.86  7203.7  399.81  7209.3  395.42  7226.1  394.99  7231.2  390.74
#Mann= 10 ,-1 , 0
  4343.5     .05       0  4765.6     .12       0  5179.4     .16       0
  5335.6      .1       0  5374.9     .16       0  5677.4     .05       0
  5778.8      .1       0  6049.9     .16       0    6423     .07       0
  6443.9     .16       0
Bank Sta=4980.8,5023.6
XS Rating Curve= 0 ,0
Exp/Cntr=0.3,0.1

Type RM Length L Ch R = 1 ,1929    ,794,794,794
BEGIN DESCRIPTION:
MINERAL CREEK 2 1
END DESCRIPTION:
XS GIS Cut Line= 3
      3532371.38     10400163.39      3533891.04     10399983.91
      3534832.35     10398432.34
#Sta/Elev= 30
  2417.1  353.54  2815.6  323.81  2941.4     319  3085.6  318.84  3165.4  316.73
  3193.2  319.32    3283  318.85  3398.2  317.76  3662.7  317.64  4851.6  316.81
  4963.8  317.53    4983  317.91  5005.7  315.63    5026  317.86  5300.2  316.32
  5373.8  315.41  5394.7  315.41  5412.3   317.2  5448.2  317.97  5521.9   326.7
    5580  336.61  5601.4  343.31  5632.4  357.67  5638.2   358.2  5653.7  368.32
    5675  374.44    5681  379.72  5711.9   394.2  5748.7  403.34  5762.1  404.33
#Mann= 13 ,-1 , 0
  2417.1     .05       0  3085.6     .16       0  3165.4     .12       0
    3283     .07       0  3398.2     .12       0  3662.7     .16       0
  4851.6     .12       0  4963.8     .16       0  5005.7     .12       0
  5300.2     .05       0  5373.8     .07       0  5394.7     .05       0
  5412.3     .16       0
Bank Sta=4983,5026
XS Rating Curve= 0 ,0
Exp/Cntr=0.3,0.1

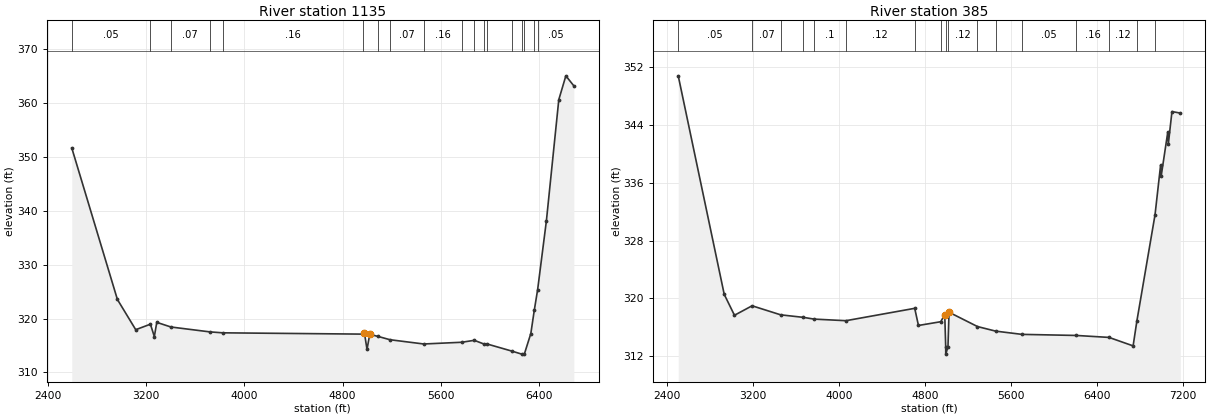
Type RM Length L Ch R = 1 ,1135    ,750,750,750
BEGIN DESCRIPTION:
MINERAL CREEK 1 0
END DESCRIPTION:
XS GIS Cut Line= 4
      3532391.31     10400243.17      3534202.16     10400151.43
      3535151.47     10399361.67      3535486.52     10398380.44
#Sta/Elev= 30
  2596.7  351.63    2968  323.53  3117.1  317.93  3236.5  318.95  3268.4  316.66
  3288.4  319.29  3403.3  318.43  3717.8  317.53  3823.9  317.35  4963.4  317.11
    4978  317.28  4998.8  314.28  5020.9  317.07  5090.7  316.67    5186  316.07
  5460.1  315.28  5769.5   315.6  5871.8  315.96  5947.1   315.3  5974.2  315.29
  6178.9  313.95  6257.7   313.4  6278.7   313.4  6331.6  317.22  6359.8  321.54
  6387.1  325.37  6458.4  338.14  6559.2  360.58  6616.6     365  6681.6  363.14
#Mann= 18 ,-1 , 0
  2596.7     .05       0  3236.5     .12       0  3403.3     .07       0
  3717.8     .12       0  3823.9     .16       0  4963.4     .12       0
  5090.7     .16       0    5186     .07       0  5460.1     .16       0
  5769.5     .05       0  5871.8     .16       0  5947.1     .12       0
  5974.2     .16       0  6178.9     .12       0  6257.7     .07       0
  6278.7     .12       0  6359.8     .16       0  6387.1     .05       0
Bank Sta=4978,5020.9
XS Rating Curve= 0 ,0
Exp/Cntr=0.3,0.1

Type RM Length L Ch R = 1 ,385     ,0,0,0
BEGIN DESCRIPTION:
MINERAL CREEK 10 1
END DESCRIPTION:
XS GIS Cut Line= 4
      3532355.05     10400354.81      3534500.85     10400403.42
      3535063.35     10400285.37      3535608.47     10398420.82
#Sta/Elev= 30
  2508.4  350.76  2935.6  320.56  3030.7  317.67  3194.4  318.98    3460  317.73
  3671.3  317.38    3770  317.14  4066.3  316.92    4705  318.63  4739.7  316.26
  4946.9  316.78    4984  317.77  4992.9   313.3  4993.4   312.3  5013.9   313.3
  5023.7  318.09  5288.2  316.11  5456.4  315.48    5701  315.03  6206.7  314.88
  6509.9  314.61  6733.7  313.44    6769  316.91  6937.3  331.56    6989  338.41
  6994.2  336.88  7055.9  343.01  7061.1  341.37  7094.5  345.82  7172.1  345.61
#Mann= 17 ,-1 , 0
  2508.4     .05       0  3194.4     .07       0    3460     .12       0
  3671.3     .16       0    3770      .1       0  4066.3     .12       0
    4705     .16       0  4946.9     .12       0  4992.9     .07       0
  5013.9     .12       0  5288.2      .1       0  5456.4     .12       0
    5701     .05       0  6206.7     .16       0  6509.9     .12       0
    6769     .16       0  6937.3     .05       0
Bank Sta=4984,5023.7
XS Rating Curve= 0 ,0
Exp/Cntr=0.3,0.1

Chan Stop Cuts=-1
Use User Specified Reach Order=0
Composite Channel Slope=5