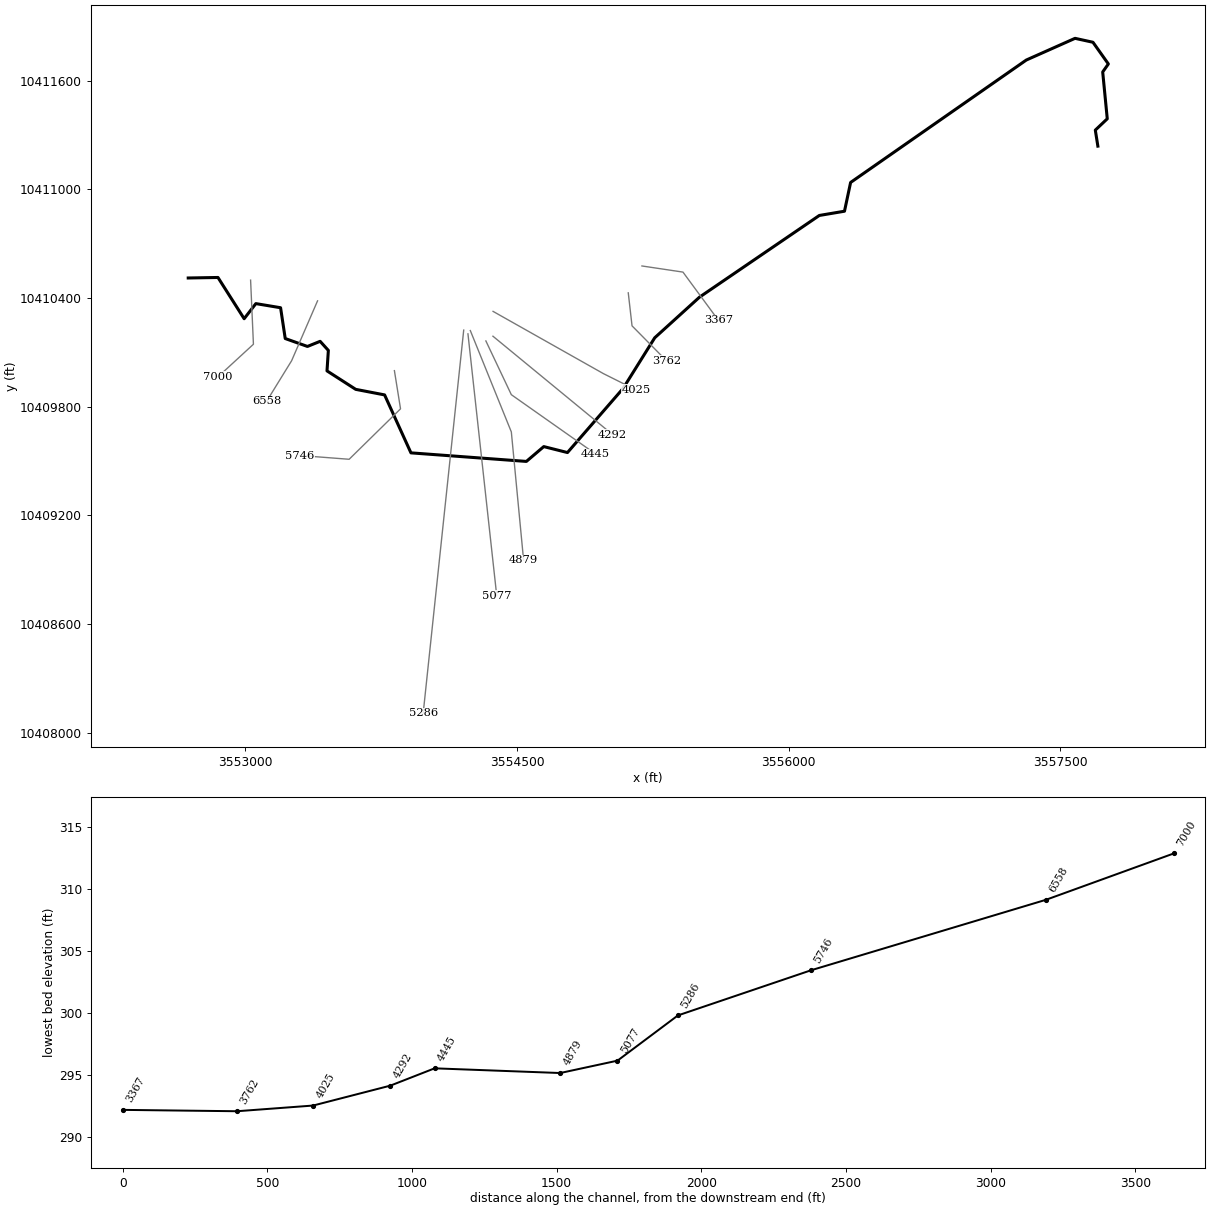
--- NAVASOTA RV TRIB 5.prj (project) ---

Proj Title=NAVASOTA RV TRIB 5 Base Level Engineering
Current Plan=p01
Default Exp/Contr=0.3,0.1
English Units
Geom File=g01
Flow File=f01
Plan File=p01
Y Axis Title=Elevation
X Axis Title(PF)=Main Channel Distance
X Axis Title(XS)=Station
BEGIN DESCRIPTION:
NAVASOTA RV TRIB 5
END DESCRIPTION:
DSS Export Rating Curves= 0
DSS Export Rating Curve Sorted= 0
DSS Export Volume Flow Curves= 0
DXF OffsetX= 0
DXF OffsetY= 0
DXF ScaleX= 1
DXF ScaleY= 10

--- NAVASOTA RV TRIB 5.p01 (plan) ---

Plan Title=Multiple Run
Short Identifier=Multiple
Geom File=g01
Flow File=f01
Subcritical Flow
K Sum by GR= 0
Std Step Tol= 0.01
Critical Tol= 0.01
Num of Std Step Trials= 20
Max Error Tol= 0.3
Flow Tol Ratio= 0.001
Split Flow NTrial= 30
Split Flow Tol= 0.02
Split Flow Ratio= 0.02
Log Output Level= 0
Friction Slope Method= 1
Unsteady Friction Slope Method= 2
Unsteady Bridges Friction Slope Method= 1
Parabolic Critical Depth
Global Vel Dist=  1 , 1 , 1
Global Log Level= 0
CheckData=True
Encroach Param= -1, 0, 0, 0
BEGIN DESCRIPTION:
Multiple Run
END DESCRIPTION:

--- NAVASOTA RV TRIB 5.f01 (steady flow) ---

Flow Title=Multiple
Number of Profiles=7
Profile Names=10-year,25-year,50-year,1pct_min,100-year,1pct_plu,500-year
River Rch & RM= NAVASOTA RV TRIB,Reach-1,7000
     857    1172    1431    1276    1725    2333    2500
Boundary for River Rch & Prof#=NAVASOTA RV TRIB,Reach-1,1
Up Type=0
Dn Type=3
Dn Slope=0.005
Boundary for River Rch & Prof#=NAVASOTA RV TRIB,Reach-1,2
Up Type=0
Dn Type=3
Dn Slope=0.005
Boundary for River Rch & Prof#=NAVASOTA RV TRIB,Reach-1,3
Up Type=0
Dn Type=3
Dn Slope=0.005
Boundary for River Rch & Prof#=NAVASOTA RV TRIB,Reach-1,4
Up Type=0
Dn Type=3
Dn Slope=0.005
Boundary for River Rch & Prof#=NAVASOTA RV TRIB,Reach-1,5
Up Type=0
Dn Type=3
Dn Slope=0.005
Boundary for River Rch & Prof#=NAVASOTA RV TRIB,Reach-1,6
Up Type=0
Dn Type=3
Dn Slope=0.005
Boundary for River Rch & Prof#=NAVASOTA RV TRIB,Reach-1,7
Up Type=0
Dn Type=3
Dn Slope=0.005

--- NAVASOTA RV TRIB 5.g01 (geometry) ---

Geom Title=Existing Conditions
Program Version=4.10

River Reach=NAVASOTA RV TRIB,Reach-1
Reach XY= 30
      3552684.19     10410511.22      3552848.48     10410514.09
      3552993.09     10410286.28      3553057.71     10410369.71
      3553194.34     10410346.97      3553219.99     10410176.81
      3553342.65     10410133.12      3553412.75     10410161.41
      3553458.17      10410111.2      3553450.69     10409998.13
      3553609.29     10409896.15      3553768.77      10409865.5
      3553914.32     10409545.39      3554551.89      10409498.1
      3554648.04     10409579.98      3554778.83     10409547.07
      3555085.99     10409901.15      3555260.87     10410181.05
      3555508.04     10410405.33      3556169.96     10410856.61
      3556308.85     10410880.04       3556342.7      10411038.9
      3557313.19     10411715.11      3557582.28      10411834.9
      3557681.24      10411813.2      3557766.31     10411693.41
      3557735.06     10411649.14      3557760.24     10411390.46
      3557694.26     10411327.96      3557708.36     10411239.41

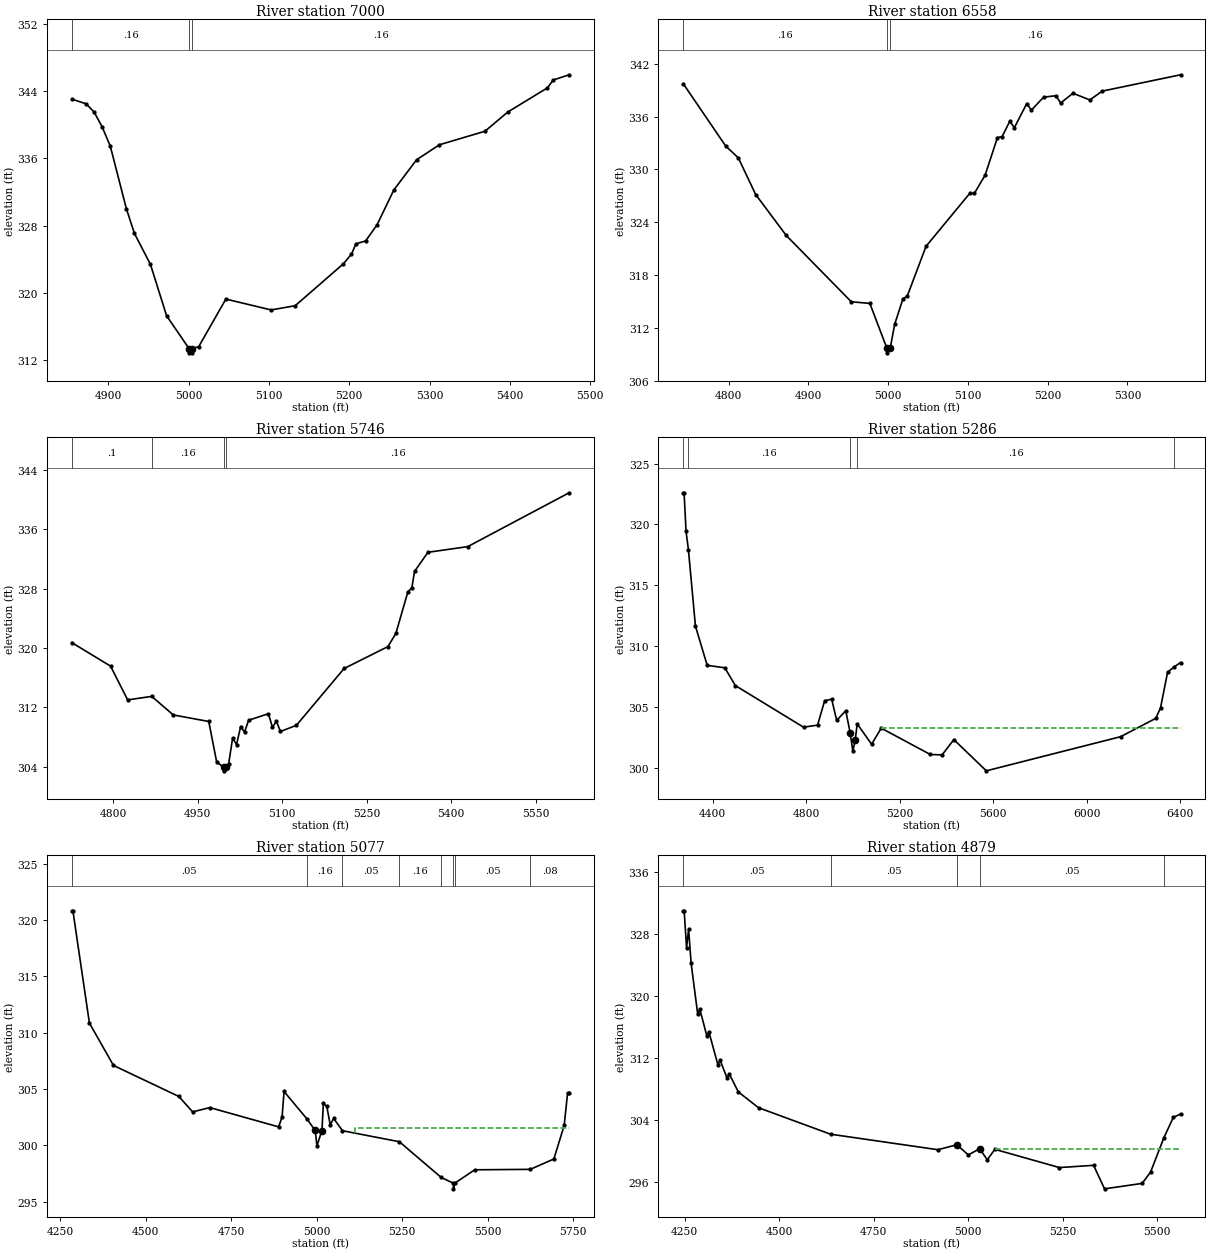
Type RM Length L Ch R = 1 ,7000    ,442,442,442
BEGIN DESCRIPTION:
NAVASOTA RV TRIB 5 11 0
END DESCRIPTION:
XS GIS Cut Line= 3
      3553028.71     10410499.49      3553044.33     10410145.36
      3552849.51     10409966.13
#Sta/Elev= 30
  4854.6  343.06  4872.5  342.49  4882.5   341.5  4892.5  339.72  4902.5  337.46
  4922.5  330.03  4932.5   327.1  4952.5  323.41  4972.6   317.3  5000.6   313.4
  5000.8   312.9  5004.3   312.9  5004.6   313.4  5012.6  313.64  5046.4  319.29
  5102.7     318  5132.7   318.5  5192.8  323.49  5202.8  324.63  5208.4  325.86
  5220.4   326.2  5234.6  328.11  5255.6  332.27  5283.9  335.85  5312.3  337.63
    5369  339.24  5397.4  341.52  5446.7  344.39  5454.1  345.33  5473.8  345.95
#Mann= 3 ,-1 , 0
  4854.6     .16       0  5000.6     .07       0  5004.6     .16       0
Bank Sta=5000.6,5004.6
XS Rating Curve= 0 ,0
Exp/Cntr=0.3,0.1

Type RM Length L Ch R = 1 ,6558    ,812,812,812
BEGIN DESCRIPTION:
NAVASOTA RV TRIB 5 10 0
END DESCRIPTION:
XS GIS Cut Line= 3
       3553398.5     10410384.95      3553255.27     10410054.22
      3553117.24     10409830.25
#Sta/Elev= 30
  4743.1  339.73  4796.3  332.65  4812.1  331.31  4833.9  327.14  4872.2  322.49
  4953.8  314.95    4977  314.77  4998.5  309.65  4998.8  309.15  5002.5  309.65
  5008.2  312.41  5018.5  315.28    5024  315.61  5047.5  321.26  5102.2  327.26
    5108  327.26  5121.6  329.35    5137  333.61  5142.9  333.73  5152.4  335.45
  5158.3  334.75  5173.7  337.47  5179.6  336.74    5195  338.21  5210.4  338.37
  5216.2  337.54  5231.7  338.65  5252.9  337.89  5268.3  338.89  5366.6  340.75
#Mann= 3 ,-1 , 0
  4743.1     .16       0  4998.5     .07       0  5002.5     .16       0
Bank Sta=4998.5,5002.5
XS Rating Curve= 0 ,0
Exp/Cntr=0.3,0.1

Type RM Length L Ch R = 1 ,5746    ,460,460,460
BEGIN DESCRIPTION:
NAVASOTA RV TRIB 5 9 0
END DESCRIPTION:
XS GIS Cut Line= 4
      3553822.98     10409999.49      3553856.83     10409788.59
      3553572.97     10409509.95      3553302.14     10409530.78
#Sta/Elev= 30
  4726.6  320.72  4795.3  317.56  4825.7  313.01  4868.5  313.48  4906.7  310.98
  4969.7   310.1  4983.8  304.63    4996  303.95  4996.2  303.45    5000  303.95
    5005  304.38  5012.1  307.87  5019.1  306.99  5026.3  309.41  5033.3  308.66
  5040.4  310.26  5075.7  311.15  5082.8  309.32  5089.8  310.13    5097  308.75
  5125.3  309.58  5210.1  317.24  5287.9  320.19    5302  321.97  5323.3  327.57
  5330.3  328.09  5335.1  330.32  5358.9  332.89  5429.7  333.66  5609.6  340.91
#Mann= 4 ,-1 , 0
  4726.6      .1       0  4868.5     .16       0    4996     .07       0
    5000     .16       0
Bank Sta=4996,5000
XS Rating Curve= 0 ,0
Exp/Cntr=0.3,0.1

Type RM Length L Ch R = 1 ,5286    ,209,209,209
BEGIN DESCRIPTION:
NAVASOTA RV TRIB 5 6 1
END DESCRIPTION:
XS GIS Cut Line= 2
      3554205.79     10410223.49      3553981.85      10408106.5
#Sta/Elev= 30
  4273.7   322.6  4277.1   322.6  4285.6  319.43  4295.7  317.94  4325.8  311.67
  4376.1  308.45  4451.4  308.25  4496.8  306.79  4788.4  303.38  4848.7  303.55
  4878.9  305.55  4909.1  305.67  4930.4  303.94  4969.4  304.73    4988  302.92
  4999.6  301.42  5009.6  302.29  5018.2  303.65    5080  301.98    5121   303.3
  5331.4  301.14  5381.7  301.11    5432  302.36    5571   299.8  6145.9   302.6
  6296.8  304.11  6316.9  304.98  6347.1  307.89  6375.7  308.33  6402.5  308.68
#Mann= 5 ,-1 , 0
  4273.7     .05       0  4295.7     .16       0    4988     .07       0
  5018.2     .16       0  6375.7     .08       0
#XS Ineff= 2 , 0
       0                 5120.54       0  303.32
Permanent Ineff=
       F       T
Bank Sta=4988,5009.6
XS Rating Curve= 0 ,0
Exp/Cntr=0.3,0.1

Type RM Length L Ch R = 1 ,5077    ,198,198,198
BEGIN DESCRIPTION:
Mapping XS e4b73dd4
END DESCRIPTION:
XS GIS Cut Line= 2
      3554229.22     10410202.69      3554388.08      10408757.3
#Sta/Elev= 30
  4284.3  320.82  4287.4  320.82  4335.7  310.85  4406.1  307.09  4597.2  304.34
  4637.5  302.97  4687.8  303.35    4889  301.64    4899  302.51  4904.9  304.78
  4971.1  302.37  4995.9  301.32  5000.9  299.97 5015.61   301.3  5019.8  303.72
  5029.8  303.45  5039.9  301.82  5049.9  302.39  5075.6   301.3  5242.1  300.32
  5364.4  297.15    5400  296.64  5400.3  296.14    5404  296.64  5462.4  297.83
  5624.7  297.87  5693.8  298.79    5724  301.77  5733.9  304.64  5738.4  304.64
#Mann= 8 ,-1 , 0
  4284.3     .05       0  4971.1     .16       0  5075.6     .05       0
  5242.1     .16       0  5364.4     .05       0    5400     .07       0
    5404     .05       0  5624.7     .08       0
#XS Ineff= 2 , 0
       0                 5111.46       0  301.53
Permanent Ineff=
       F       T
Bank Sta=4995.9,5015.61
XS Rating Curve= 0 ,0
Exp/Cntr=0.3,0.1

Type RM Length L Ch R = 1 ,4879    ,434,434,434
BEGIN DESCRIPTION:
NAVASOTA RV TRIB 5 8 0
END DESCRIPTION:
XS GIS Cut Line= 3
      3554242.25     10410220.87      3554468.81     10409660.99
      3554536.51      10408952.7
#Sta/Elev= 30
  4246.3  330.96  4248.6  330.96    4255  326.22  4260.4  328.58    4267  324.22
  4284.6  317.61    4290  318.31  4308.7  314.82  4314.1  315.37  4338.2  311.06
  4343.6  311.73  4362.3  309.39  4367.7  309.98  4391.8  307.63  4445.4  305.59
  4635.8  302.18  4919.9  300.18  4970.2  300.82  5000.3  299.51  5030.4  300.31
  5050.5  298.88  5070.6  300.23  5241.4  297.88  5331.8  298.17  5360.7  295.14
  5460.2  295.84  5482.5   297.3  5517.4  301.69  5542.8  304.36  5561.8  304.77
#Mann= 5 ,-1 , 0
  4246.3     .05       0  4635.8     .05       0  4970.2     .07       0
  5030.4     .05       0  5517.4     .08       0
#XS Ineff= 2 , 0
       0                 5070.35       0  300.27
Permanent Ineff=
       F       T
Bank Sta=4970.2,5030.4
XS Rating Curve= 0 ,0
Exp/Cntr=0.3,0.1

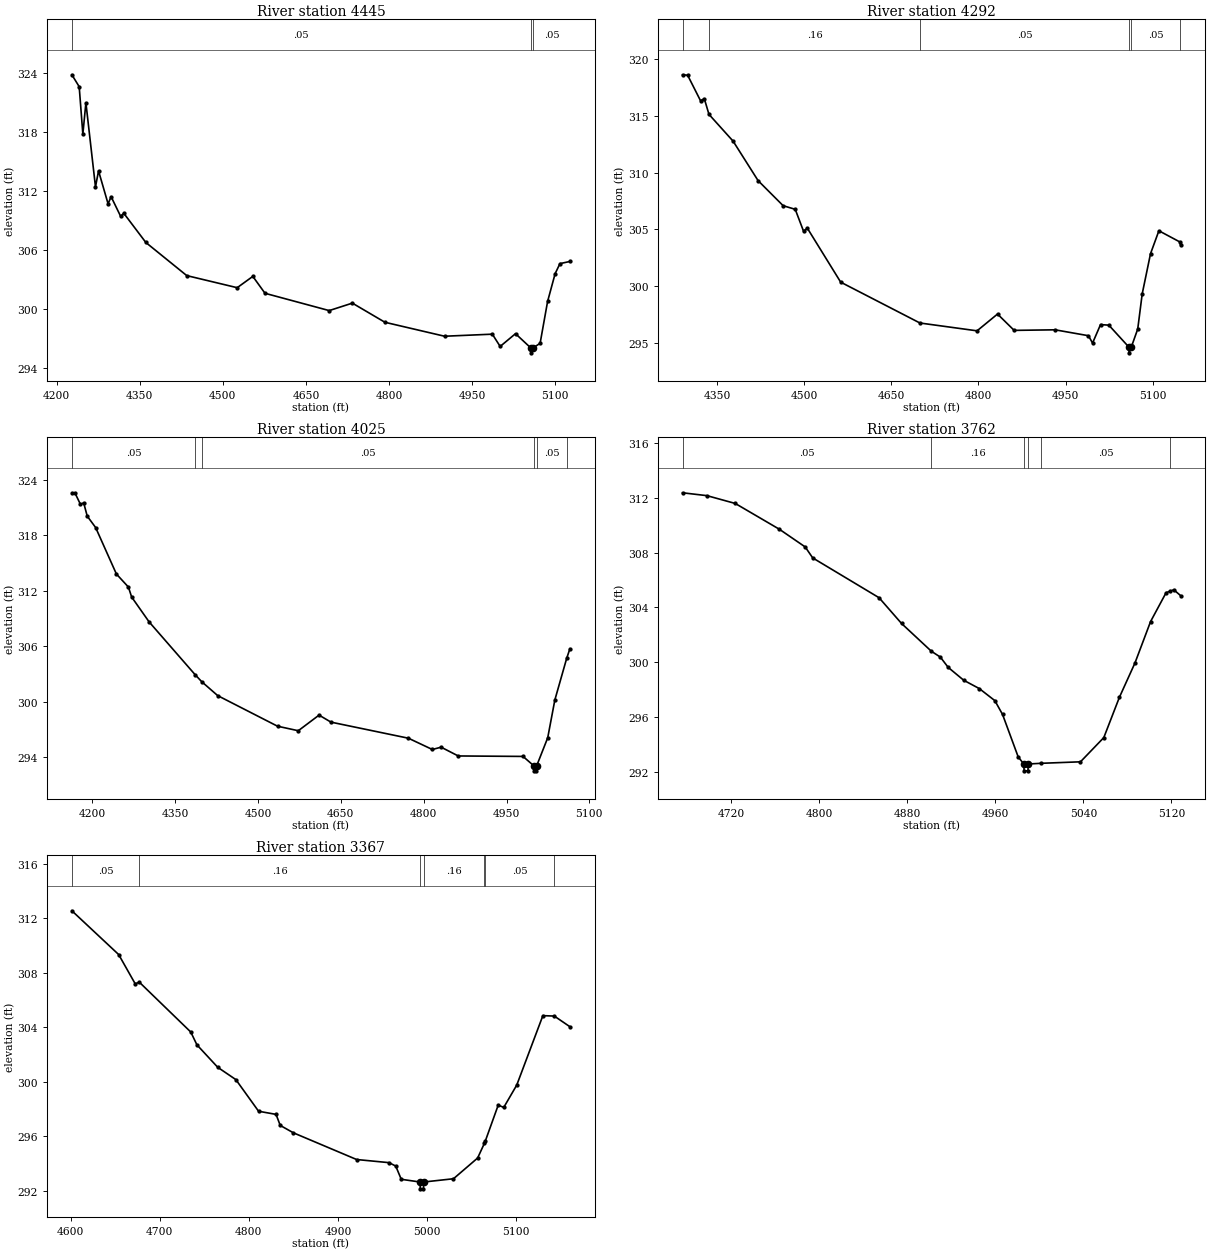
Type RM Length L Ch R = 1 ,4445    ,153,153,153
BEGIN DESCRIPTION:
NAVASOTA RV TRIB 5 7 0
END DESCRIPTION:
XS GIS Cut Line= 3
      3554328.18     10410163.61      3554468.81     10409866.72
      3554934.98     10409538.57
#Sta/Elev= 30
  4227.6  323.82  4240.8  322.61  4247.4  317.78  4252.9  320.97  4270.2  312.41
  4275.7  314.04  4292.9  310.69  4298.4  311.41  4315.7   309.4  4321.2  309.73
  4361.1  306.75  4434.9  303.38  4525.9  302.15  4554.1   303.3  4576.1  301.58
  4691.9  299.82  4733.7  300.58  4792.5  298.63  4900.1  297.21  4986.3  297.42
  5000.4  296.17  5028.1  297.47  5055.7  296.02    5056  295.52  5059.7  296.02
  5072.5  296.49    5086  300.75  5099.6  303.58  5108.3   304.6  5126.2  304.82
#Mann= 3 ,-1 , 0
  4227.6     .05       0  5055.7     .04       0  5059.7     .05       0
Bank Sta=5055.7,5059.7
XS Rating Curve= 0 ,0
Exp/Cntr=0.3,0.1

Type RM Length L Ch R = 1 ,4292    ,267,267,267
BEGIN DESCRIPTION:
NAVASOTA RV TRIB 5 6 0
END DESCRIPTION:
XS GIS Cut Line= 2
      3554367.21     10410189.66      3555028.94     10409645.56
#Sta/Elev= 30
  4290.9  318.63  4299.7  318.59  4321.9  316.34  4328.4  316.52  4336.4  315.14
  4377.9  312.78  4420.9   309.3    4464  307.09  4484.8  306.77  4499.1  304.84
  4505.6  305.11    4563  300.35  4699.3  296.75  4797.6  296.06  4832.8  297.54
  4861.4   296.1  4931.8  296.15  4989.2  295.63  4996.3  294.98    5010  296.61
  5024.3  296.56  5058.9  294.62  5059.1  294.12  5062.9  294.62    5074  296.22
  5081.7  299.32    5096  302.86  5110.4  304.88  5145.9  303.91  5147.6  303.65
#Mann= 6 ,-1 , 0
  4290.9     .05       0  4336.4     .16       0  4699.3     .05       0
  5058.9     .04       0  5062.9     .05       0  5145.9     .08       0
Bank Sta=5058.9,5062.9
XS Rating Curve= 0 ,0
Exp/Cntr=0.3,0.1

Type RM Length L Ch R = 1 ,4025    ,263,263,263
BEGIN DESCRIPTION:
NAVASOTA RV TRIB 5 6 2
END DESCRIPTION:
XS GIS Cut Line= 3
       3554367.9     10410326.79      3554977.27     10409983.09
      3555157.93     10409892.76
#Sta/Elev= 30
  4163.1  322.59  4168.5   322.6  4178.7  321.34  4184.5  321.51  4190.9  320.07
  4206.1  318.84  4243.7  313.81  4265.4   312.4  4271.3  311.32  4302.9  308.63
    4386  302.93  4398.3  302.15  4427.1  300.65  4535.4  297.34    4573  296.85
  4610.6  298.54  4632.2  297.78  4772.4  296.04  4815.7  294.82  4831.6  295.07
  4862.6  294.12  4979.9  294.07  5000.3  293.01  5000.5  292.51    5004  292.51
  5004.3  293.01  5024.6  296.09  5037.5  300.18  5058.9  304.68  5064.7  305.71
#Mann= 6 ,-1 , 0
  4163.1     .05       0    4386     .16       0  4398.3     .05       0
  5000.3     .04       0  5004.3     .05       0  5058.9     .08       0
Bank Sta=5000.3,5004.3
XS Rating Curve= 0 ,0
Exp/Cntr=0.3,0.1

Type RM Length L Ch R = 1 ,3762    ,395,395,395
BEGIN DESCRIPTION:
NAVASOTA RV TRIB 5 5 0
END DESCRIPTION:
XS GIS Cut Line= 3
      3555114.64      10410429.2      3555135.47     10410246.93
      3555324.41      10410055.4
#Sta/Elev= 30
  4675.7  312.37  4697.9  312.16  4723.6  311.59  4763.8   309.7  4787.2  308.41
    4794  307.61  4854.3   304.7  4874.7  302.82  4901.8  300.79    4910  300.36
  4917.1  299.61  4931.2  298.67  4945.4  298.06  4959.5  297.18  4966.5  296.17
  4980.7  293.07  4985.8  292.55  4986.1  292.05  4989.6  292.05  4989.8  292.55
  5001.4   292.6  5037.3  292.71  5058.5  294.48  5072.7  297.43  5086.8  299.93
    5101  302.96  5115.1  305.07  5118.9  305.18  5122.1  305.28  5128.2  304.86
#Mann= 6 ,-1 , 0
  4675.7     .05       0  4901.8     .16       0  4985.8     .07       0
  4989.8     .16       0  5001.4     .05       0  5118.9     .08       0
Bank Sta=4985.8,4989.8
XS Rating Curve= 0 ,0
Exp/Cntr=0.3,0.1

Type RM Length L Ch R = 1 ,3367    ,0,0,0
BEGIN DESCRIPTION:
NAVASOTA RV TRIB 5 5 1
END DESCRIPTION:
XS GIS Cut Line= 3
      3555190.17     10410577.65      3555416.72      10410543.8
      3555612.05     10410278.15
#Sta/Elev= 30
  4601.5  312.55    4654  309.34  4672.6  307.19  4677.1  307.32  4734.9  303.66
  4741.8  302.72  4765.2  301.07  4785.5  300.17    4811  297.85  4830.6  297.62
  4835.3  296.81    4850  296.27    4921  294.31  4957.4  294.08  4964.9  293.83
  4971.1  292.86  4992.2  292.66  4992.5  292.16    4996  292.16  4996.2  292.66
  5029.7   292.9  5056.8  294.42  5064.4   295.5  5065.4  295.66  5079.9   298.3
  5086.1  298.13  5100.7  299.77    5130  304.86  5142.8  304.83  5160.3  304.05
#Mann= 7 ,-1 , 0
  4601.5     .05       0  4677.1     .16       0  4992.2     .07       0
  4996.2     .16       0  5064.4      .1       0  5065.4     .05       0
  5142.8     .08       0
Bank Sta=4992.2,4996.2
XS Rating Curve= 0 ,0
Exp/Cntr=0.3,0.1

Chan Stop Cuts=-1
Use User Specified Reach Order=0
Composite Channel Slope=5