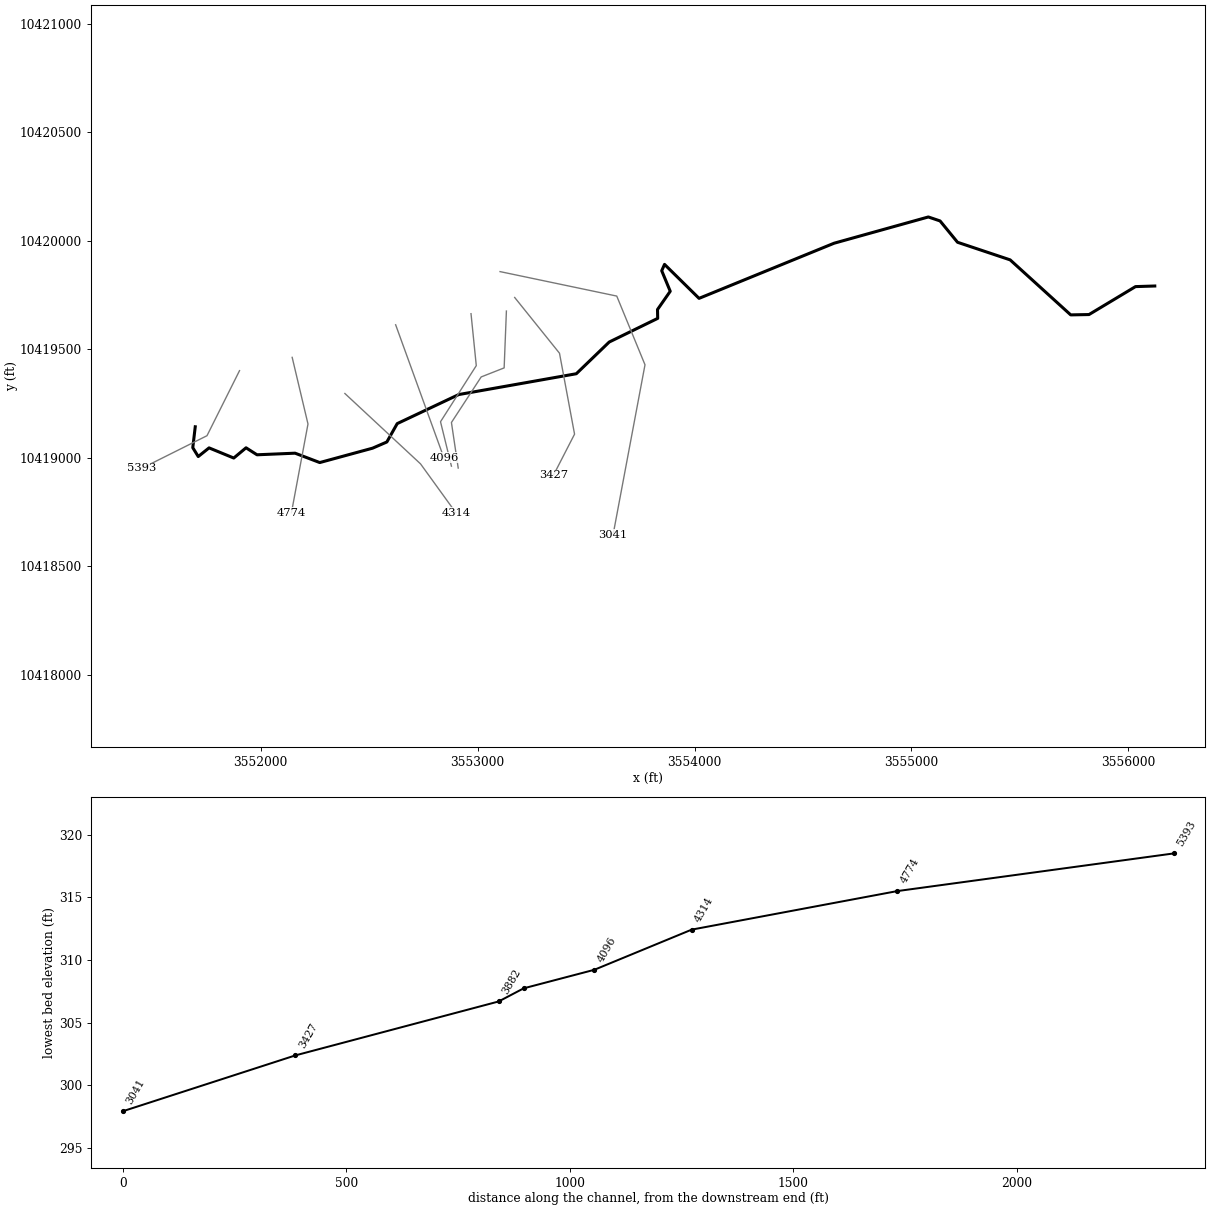
--- NAVASOTA RV TRIB 6.prj (project) ---

Proj Title=NAVASOTA RV TRIB 6 Base Level Engineering
Current Plan=p01
Default Exp/Contr=0.3,0.1
English Units
Geom File=g01
Flow File=f01
Plan File=p01
BEGIN DESCRIPTION:
NAVASOTA RV TRIB 6
END DESCRIPTION:

--- NAVASOTA RV TRIB 6.p01 (plan) ---

Plan Title=Multiple Run
Short Identifier=Multiple
Geom File=g01
Flow File=f01
Subcritical Flow
K Sum by GR= 0
Std Step Tol= 0.01
Critical Tol= 0.01
Num of Std Step Trials= 20
Max Error Tol= 0.3
Flow Tol Ratio= 0.001
Split Flow NTrial= 30
Split Flow Tol= 0.02
Split Flow Ratio= 0.02
Log Output Level= 0
Friction Slope Method= 1
Unsteady Friction Slope Method= 2
Unsteady Bridges Friction Slope Method= 1
Parabolic Critical Depth
Global Vel Dist=  1 , 1 , 1
Global Log Level= 0
CheckData=True
Encroach Param= -1, 0, 0, 0
BEGIN DESCRIPTION:
Multiple Run
END DESCRIPTION:

--- NAVASOTA RV TRIB 6.f01 (steady flow) ---

Flow Title=Multiple
Number of Profiles=7
Profile Names=10-year,25-year,50-year,1pct_min,100-year,1pct_plu,500-year
River Rch & RM= NAVASOTA RV TRIB,Reach-1,5393
     841    1159    1423    1278    1728    2337    2539
Boundary for River Rch & Prof#=NAVASOTA RV TRIB,Reach-1,1
Up Type=0
Dn Type=3
Dn Slope=0.005
Boundary for River Rch & Prof#=NAVASOTA RV TRIB,Reach-1,2
Up Type=0
Dn Type=3
Dn Slope=0.005
Boundary for River Rch & Prof#=NAVASOTA RV TRIB,Reach-1,3
Up Type=0
Dn Type=3
Dn Slope=0.005
Boundary for River Rch & Prof#=NAVASOTA RV TRIB,Reach-1,4
Up Type=0
Dn Type=3
Dn Slope=0.005
Boundary for River Rch & Prof#=NAVASOTA RV TRIB,Reach-1,5
Up Type=0
Dn Type=3
Dn Slope=0.005
Boundary for River Rch & Prof#=NAVASOTA RV TRIB,Reach-1,6
Up Type=0
Dn Type=3
Dn Slope=0.005
Boundary for River Rch & Prof#=NAVASOTA RV TRIB,Reach-1,7
Up Type=0
Dn Type=3
Dn Slope=0.005

--- NAVASOTA RV TRIB 6.g01 (geometry) ---

Geom Title=Existing Conditions

River Reach=NAVASOTA RV TRIB,Reach-1
Reach XY= 30
      3551697.66     10419142.49      3551686.30     10419046.05
      3551711.48     10419005.30      3551761.37     10419045.20
      3551875.30     10418998.38      3551931.87     10419045.59
      3551982.48     10419013.35      3552158.03     10419020.75
      3552271.80     10418977.52      3552515.35     10419043.84
      3552581.21     10419072.44      3552628.97     10419157.11
      3552912.76     10419291.11      3553454.82     10419387.09
      3553606.51     10419533.28      3553830.04     10419642.33
      3553829.16     10419683.10      3553887.89     10419767.33
      3553848.63     10419861.98      3553861.57     10419891.33
      3554020.73     10419734.63      3554643.27     10419988.84
      3555078.03     10420109.95      3555132.12     10420091.63
      3555212.60     10419993.26      3555455.23     10419912.13
      3555734.48     10419658.45      3555818.86     10419660.01
      3556033.26     10419788.85      3556122.11     10419791.64

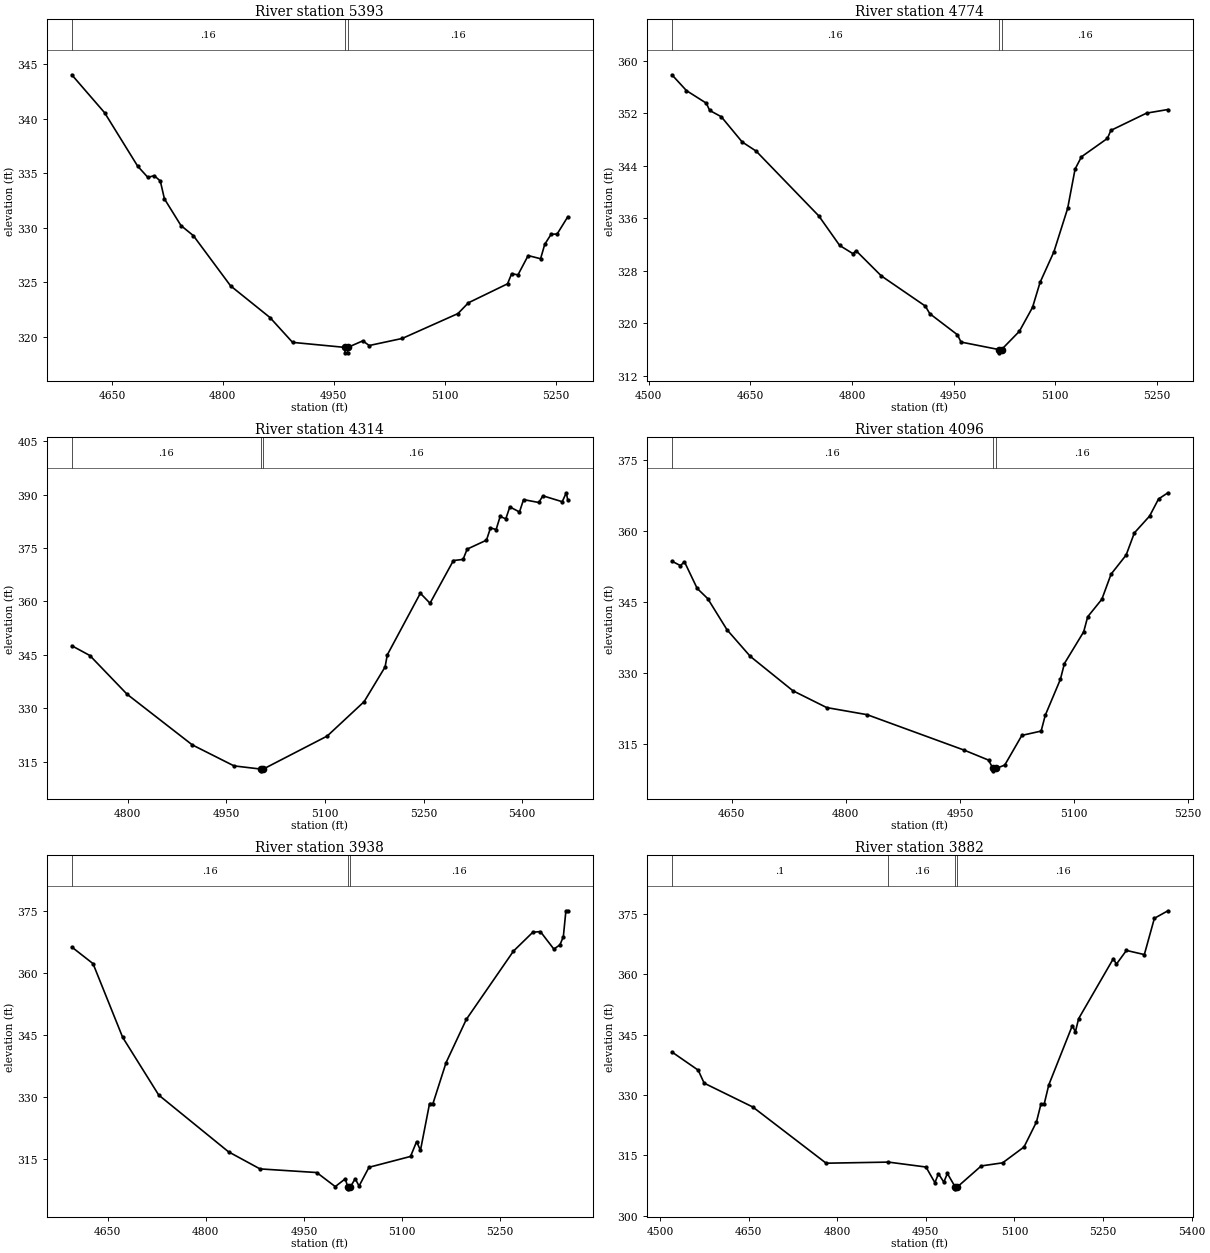
Type RM Length L Ch R = 1,5393,619,619,619
BEGIN DESCRIPTION:
NAVASOTA RV TRIB 6 5 0
END DESCRIPTION:
XS GIS Cut Line= 3
      3551901.83     10419401.35      3551751.83     10419101.34
      3551451.85     10418951.35
#Sta/Elev= 30
  4595.7  344.02  4640.1  340.54  4684.8  335.64  4698.6  334.61  4707.2  334.77
  4715.4  334.28  4721.0  332.64  4743.4  330.19  4760.1  329.27  4810.5  324.66
  4863.7  321.76  4894.3  319.48  4965.0  319.02  4965.2  318.52  4968.7  318.52
  4969.0  319.02  4989.3  319.62  4997.9  319.19  5042.6  319.84  5117.9  322.12
  5132.1  323.11  5185.0  324.85  5190.6  325.78  5199.1  325.67  5212.9  327.44
  5229.7  327.15  5235.3  328.47  5243.9  329.39  5252.1  329.42  5266.5  331.00
#Mann=3,-1,0
  4595.7    0.16       0  4965.0    0.07       0  4969.0    0.16       0
Bank Sta=4965,4969
Exp/Cntr=0.3,0.1

Type RM Length L Ch R = 1,4774,460,460,460
BEGIN DESCRIPTION:
NAVASOTA RV TRIB 6 9 0
END DESCRIPTION:
XS GIS Cut Line= 3
      3552144.61     10419462.59      3552217.51     10419155.34
      3552141.23     10418746.17
#Sta/Elev= 30
  4534.3  357.85  4555.8  355.44  4585.0  353.53  4590.1  352.42  4607.2  351.46
  4638.0  347.62  4658.6  346.23  4751.1  336.36  4781.9  331.86  4801.2  330.63
  4806.3  331.04  4843.4  327.22  4908.3  322.63  4914.9  321.47  4955.6  318.27
  4961.0  317.15  5016.8  316.01  5017.1  315.51  5020.8  316.01  5047.1  318.79
  5066.5  322.43  5077.6  326.23  5098.0  330.88  5118.3  337.49  5129.3  343.49
  5138.7  345.36  5177.0  348.16  5182.1  349.38  5234.8  352.01  5266.3  352.56
#Mann=3,-1,0
  4534.3    0.16       0  5016.8    0.07       0  5020.8    0.16       0
Bank Sta=5016.8,5020.8
Exp/Cntr=0.3,0.1

Type RM Length L Ch R = 1,4314,218,218,218
BEGIN DESCRIPTION:
NAVASOTA RV TRIB 6 49 0
END DESCRIPTION:
XS GIS Cut Line= 3
      3552387.66     10419295.96      3552736.61     10418971.31
      3552899.44     10418746.13
#Sta/Elev= 30
  4714.9  347.57  4742.4  344.82  4799.0  333.95  4898.2  319.72  4961.7  313.82
  5002.2  312.93  5002.5  312.43  5006.2  312.93  5103.4  322.20  5159.6  331.86
  5191.5  341.62  5194.8  344.99  5245.1  362.31  5259.8  359.51  5295.4  371.50
  5310.1  371.81  5316.3  374.70  5345.7  377.22  5351.8  380.66  5360.4  380.21
  5366.5  383.88  5375.1  383.21  5381.2  386.56  5395.9  385.14  5402.1  388.61
  5425.3  387.80  5431.5  389.68  5460.9  388.02  5467.1  390.53  5469.4  388.43
#Mann=3,-1,0
  4714.9    0.16       0  5002.2    0.07       0  5006.2    0.16       0
Bank Sta=5002.2,5006.2
Exp/Cntr=0.3,0.1

Type RM Length L Ch R = 1,4096,158,158,158
BEGIN DESCRIPTION:
NAVASOTA RV TRIB 6 39 0
END DESCRIPTION:
XS GIS Cut Line= 2
      3552621.73     10419612.82      3552843.92     10419000.06
#Sta/Elev= 30
  4571.5  353.56  4582.7  352.63  4588.0  353.43  4604.7  347.81  4618.6  345.64
  4643.9  339.06  4674.5  333.43  4730.5  326.16  4774.9  322.60  4828.0  321.10
  4955.7  313.59  4987.6  311.49  4993.4  309.72  4993.7  309.22  4997.4  309.72
  5008.9  310.44  5031.4  316.72  5056.7  317.63  5062.1  320.96  5082.0  328.57
  5087.3  331.92  5112.6  338.62  5117.9  341.81  5136.5  345.51  5148.6  350.82
  5168.4  354.86  5179.2  359.54  5199.2  363.10  5211.0  366.72  5223.3  368.03
#Mann=3,-1,0
  4571.5    0.16       0  4993.4    0.07       0  4997.4    0.16       0
Bank Sta=4993.4,4997.4
Exp/Cntr=0.3,0.1

Type RM Length L Ch R = 1,3938,56,56,56
BEGIN DESCRIPTION:
NAVASOTA RV TRIB 6 29 0
END DESCRIPTION:
XS GIS Cut Line= 4
      3552969.25     10419664.00      3552993.56     10419424.44
      3552828.63     10419165.76      3552878.96     10418960.93
#Sta/Elev= 30
  4595.0  366.19  4627.5  362.17  4672.8  344.36  4728.0  330.40  4834.7  316.69
  4882.8  312.56  4969.6  311.68  4997.9  308.28  5013.1  310.15  5017.1  308.24
  5017.3  307.74  5021.1  308.24  5028.4  310.18  5034.3  308.42  5049.5  312.95
  5113.0  315.57  5122.3  319.15  5128.2  317.05  5142.1  328.35  5147.3  328.35
  5167.4  338.26  5198.3  348.69  5270.4  365.20  5300.0  369.76  5311.6  369.92
  5332.2  365.69  5341.5  366.72  5346.7  368.70  5350.6  374.95  5353.5  374.95
#Mann=3,-1,0
  4595.0    0.16       0  5017.1    0.07       0  5021.1    0.16       0
Bank Sta=5017.1,5021.1
Exp/Cntr=0.3,0.1

Type RM Length L Ch R = 1,3882,455,455,455
BEGIN DESCRIPTION:
NAVASOTA RV TRIB 6 8 0
END DESCRIPTION:
XS GIS Cut Line= 5
      3553132.44     10419676.15      3553122.03     10419414.02
      3553016.13     10419372.35      3552878.97     10419162.28
      3552910.22     10418952.22
#Sta/Elev= 30
  4520.3  340.69  4564.8  336.17  4574.9  332.94  4657.3  327.01  4781.3  313.06
  4886.8  313.33  4950.3  312.11  4965.4  308.21  4971.4  310.44  4980.5  308.35
  4986.5  310.51  4999.6  307.19  4999.9  306.69  5003.6  307.19  5043.8  312.38
  5080.0  313.15  5116.2  317.09  5137.3  323.32  5144.7  327.68  5150.2  327.68
  5158.1  332.51  5198.0  347.25  5203.1  345.67  5208.6  348.96  5267.4  363.88
  5272.5  362.49  5289.5  365.91  5319.8  364.88  5336.8  373.89  5359.7  375.76
#Mann=4,-1,0
  4520.3     0.1       0  4886.8    0.16       0  4999.6    0.07       0
  5003.6    0.16       0
Bank Sta=4999.6,5003.6
Exp/Cntr=0.3,0.1

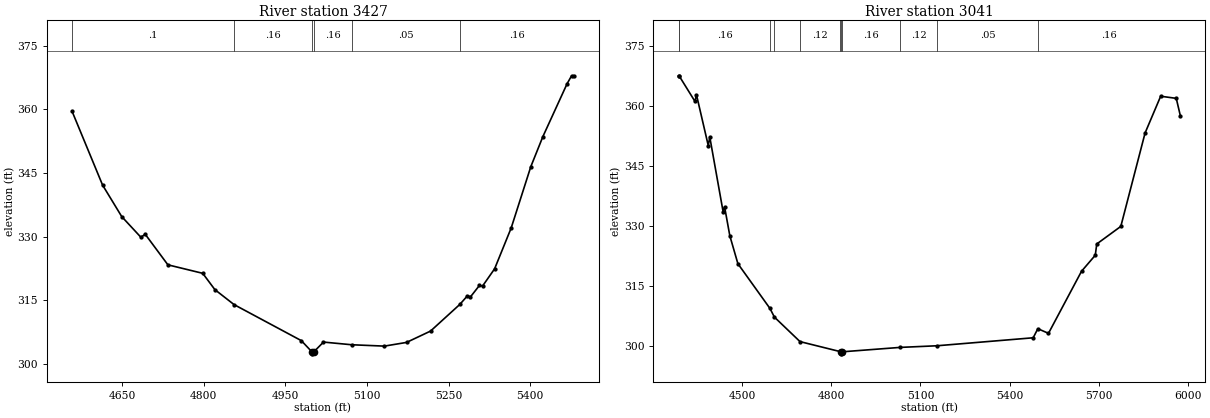
Type RM Length L Ch R = 1,3427,386,386,386
BEGIN DESCRIPTION:
NAVASOTA RV TRIB 6 28 0
END DESCRIPTION:
XS GIS Cut Line= 4
      3553170.65     10419738.66      3553377.24     10419481.73
      3553446.68     10419108.46      3553349.46     10418919.24
#Sta/Elev= 30
  4558.2  359.52  4614.3  342.13  4649.5  334.71  4684.7  329.84  4692.6  330.56
  4734.3  323.35  4798.3  321.35  4820.6  317.51  4855.9  313.98  4979.5  305.49
  4998.7  302.88  4999.0  302.38  5002.7  302.88  5020.2  305.15  5072.1  304.52
  5132.1  304.20  5172.8  305.07  5216.9  307.74  5270.7  314.02  5284.7  316.05
  5290.3  315.80  5306.9  318.51  5312.5  318.35  5334.7  322.42  5365.2  332.06
  5401.2  346.48  5423.4  353.57  5467.8  366.00  5476.1  367.89  5480.3  367.89
#Mann=6,-1,0
  4558.2     0.1       0  4855.9    0.16       0  4998.7    0.07       0
  5002.7    0.16       0  5072.1    0.05       0  5270.7    0.16       0
Bank Sta=4998.7,5002.7
Exp/Cntr=0.3,0.1

Type RM Length L Ch R = 1,3041,0,0,0
BEGIN DESCRIPTION:
NAVASOTA RV TRIB 6 7 0
END DESCRIPTION:
XS GIS Cut Line= 4
      3553103.12     10419858.02      3553641.30     10419745.18
      3553771.51     10419428.34      3553624.31     10418644.68
#Sta/Elev= 30
  4285.4  367.52  4287.2  367.52  4340.7  361.11  4345.8  362.77  4385.5  350.05
  4390.6  352.20  4435.4  333.54  4440.5  334.70  4458.1  327.48  4485.3  320.48
  4593.2  309.29  4608.3  307.11  4694.5  300.98  4828.7  298.50  4831.1  298.42
  4831.4  297.92  4835.1  298.42  5031.2  299.53  5155.7  299.94  5479.7  301.94
  5495.4  304.21  5531.2  303.05  5642.5  318.59  5688.8  322.60  5693.8  325.42
  5774.8  329.82  5856.5  353.20  5909.0  362.40  5961.5  361.87  5975.2  357.54
#Mann=11,-1,0
  4285.4     0.1       0  4287.2    0.16       0  4593.2    0.12       0
  4608.3    0.16       0  4694.5    0.12       0  4828.7    0.16       0
  4831.1    0.07       0  4835.1    0.16       0  5031.2    0.12       0
  5155.7    0.05       0  5495.4    0.16       0
Bank Sta=4831.1,4835.1
Exp/Cntr=0.3,0.1

Chan Stop Cuts=-1