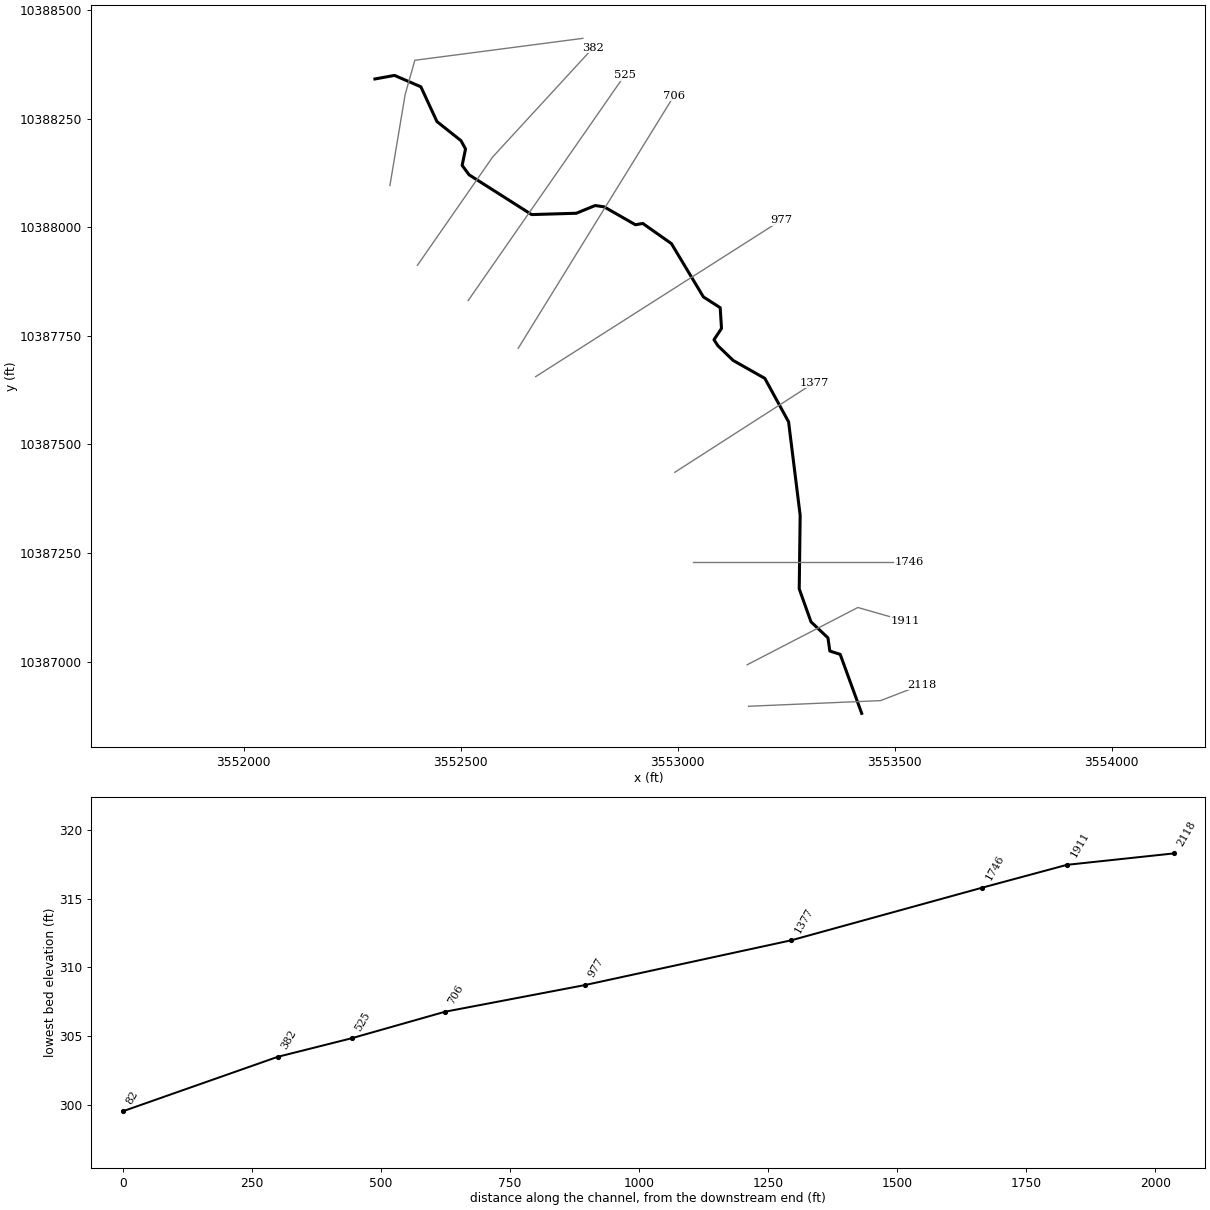
--- NED BRANCH TRIB 1.prj (project) ---

Proj Title=NED BRANCH TRIB 1 Base Level Engineering
Current Plan=p01
Default Exp/Contr=0.3,0.1
English Units
Geom File=g01
Flow File=f01
Plan File=p01
BEGIN DESCRIPTION:
NED BRANCH TRIB 1
END DESCRIPTION:

--- NED BRANCH TRIB 1.p01 (plan) ---

Plan Title=Multiple Run
Short Identifier=Multiple
Geom File=g01
Flow File=f01
Subcritical Flow
K Sum by GR= 0
Std Step Tol= 0.01
Critical Tol= 0.01
Num of Std Step Trials= 20
Max Error Tol= 0.3
Flow Tol Ratio= 0.001
Split Flow NTrial= 30
Split Flow Tol= 0.02
Split Flow Ratio= 0.02
Log Output Level= 0
Friction Slope Method= 1
Unsteady Friction Slope Method= 2
Unsteady Bridges Friction Slope Method= 1
Parabolic Critical Depth
Global Vel Dist=  1 , 1 , 1
Global Log Level= 0
CheckData=True
Encroach Param= -1, 0, 0, 0
BEGIN DESCRIPTION:
Multiple Run
END DESCRIPTION:

--- NED BRANCH TRIB 1.f01 (steady flow) ---

Flow Title=Multiple
Number of Profiles=7
Profile Names=10-year,25-year,50-year,1pct_min,100-year,1pct_plu,500-year
River Rch & RM= NED BRANCH TRIB ,Reach-1,2118
     204     253     290     244     331     447     425
Boundary for River Rch & Prof#=NED BRANCH TRIB ,Reach-1,1
Up Type=0
Dn Type=3
Dn Slope=0.005
Boundary for River Rch & Prof#=NED BRANCH TRIB ,Reach-1,2
Up Type=0
Dn Type=3
Dn Slope=0.005
Boundary for River Rch & Prof#=NED BRANCH TRIB ,Reach-1,3
Up Type=0
Dn Type=3
Dn Slope=0.005
Boundary for River Rch & Prof#=NED BRANCH TRIB ,Reach-1,4
Up Type=0
Dn Type=3
Dn Slope=0.005
Boundary for River Rch & Prof#=NED BRANCH TRIB ,Reach-1,5
Up Type=0
Dn Type=3
Dn Slope=0.005
Boundary for River Rch & Prof#=NED BRANCH TRIB ,Reach-1,6
Up Type=0
Dn Type=3
Dn Slope=0.005
Boundary for River Rch & Prof#=NED BRANCH TRIB ,Reach-1,7
Up Type=0
Dn Type=3
Dn Slope=0.005

--- NED BRANCH TRIB 1.g01 (geometry) ---

Geom Title=Existing Conditions

River Reach=NED BRANCH TRIB ,Reach-1
Reach XY= 30
      3553423.78     10386880.76      3553374.25     10387016.68
      3553350.38     10387024.27      3553346.04     10387054.65
      3553306.98     10387091.55      3553279.85     10387167.50
      3553282.02     10387336.77      3553255.30     10387552.17
      3553200.60     10387652.20      3553127.68     10387693.43
      3553092.52     10387727.28      3553083.41     10387741.17
      3553100.77     10387767.21      3553097.73     10387814.96
      3553059.10     10387839.70      3552985.32     10387962.53
      3552919.35     10388008.97      3552902.42     10388005.93
      3552830.37     10388047.16      3552809.54     10388050.20
      3552766.13     10388032.41      3552663.27     10388029.37
      3552519.17     10388120.95      3552503.11     10388142.65
      3552510.93     10388180.41      3552500.51     10388199.51
      3552445.06     10388243.58      3552408.00     10388323.66
      3552347.24     10388349.86      3552302.11     10388341.64

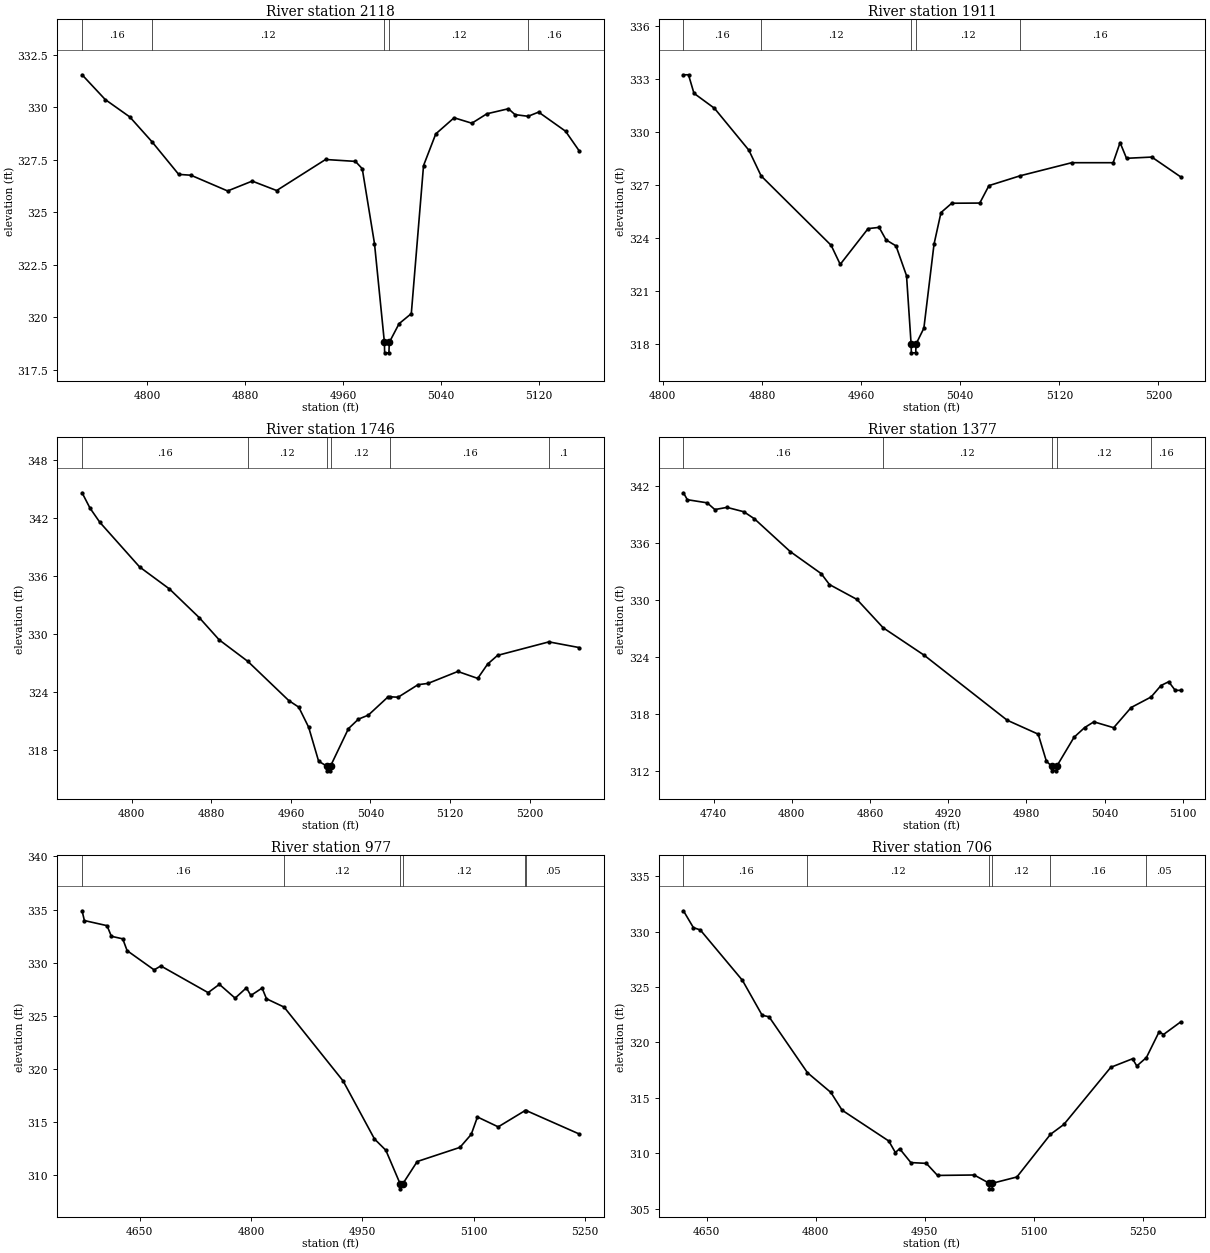
Type RM Length L Ch R = 1,2118,207,207,207
BEGIN DESCRIPTION:
NED BRANCH TRIB 1 2 0
END DESCRIPTION:
XS GIS Cut Line= 3
      3553163.18     10386897.11      3553467.14     10386910.12
      3553562.57     10386946.87
#Sta/Elev= 30
  4746.6  331.56  4765.5  330.38  4785.6  329.55  4803.7  328.37  4825.6  326.81
  4835.6  326.77  4865.6  326.02  4885.7  326.49  4905.7  326.04  4945.7  327.52
  4970.1  327.43  4975.7  327.08  4985.7  323.51  4993.8  318.80  4994.0  318.30
  4997.5  318.30  4997.8  318.80  5005.8  319.69  5015.8  320.17  5025.8  327.23
  5035.8  328.74  5050.8  329.51  5065.3  329.25  5077.6  329.70  5095.2  329.94
  5100.6  329.66  5111.3  329.58  5119.9  329.78  5141.9  328.87  5153.1  327.93
#Mann=5,-1,0
  4746.6    0.16       0  4803.7    0.12       0  4993.8    0.07       0
  4997.8    0.12       0  5111.3    0.16       0
Bank Sta=4993.8,4997.8
Exp/Cntr=0.3,0.1

Type RM Length L Ch R = 1,1911,165,165,165
BEGIN DESCRIPTION:
Mapping XS 06cd7a4e
END DESCRIPTION:
XS GIS Cut Line= 3
      3553159.75     10386992.63      3553414.97     10387124.58
      3553524.38     10387093.32
#Sta/Elev= 30
  4816.7  333.25  4820.8  333.25  4825.2  332.20  4841.7  331.35  4869.5  328.97
  4879.4  327.51  4935.9  323.57  4943.2  322.49  4965.7  324.52  4974.6  324.59
  4980.2  323.88  4988.2  323.54  4996.7  321.85  5000.4  317.97  5000.6  317.47
  5004.1  317.47  5004.4  317.97  5010.7  318.87  5018.9  323.64  5024.5  325.43
  5033.2  325.96  5055.8  325.97  5063.2  326.96  5088.5  327.52  5130.0  328.26
  5163.4  328.26  5169.0  329.40  5174.2  328.51  5194.6  328.58  5217.8  327.46
#Mann=5,-1,0
  4816.7    0.16       0  4879.4    0.12       0  5000.4    0.07       0
  5004.4    0.12       0  5088.5    0.16       0
Bank Sta=5000.4,5004.4
Exp/Cntr=0.3,0.1

Type RM Length L Ch R = 1,1746,369,369,369
BEGIN DESCRIPTION:
NED BRANCH TRIB 1 3 0
END DESCRIPTION:
XS GIS Cut Line= 2
      3553034.19     10387229.35      3553534.19     10387229.35
#Sta/Elev= 30
  4750.0  344.65  4757.9  343.07  4767.9  341.58  4807.9  336.95  4837.9  334.67
  4867.9  331.69  4887.9  329.39  4916.8  327.15  4957.9  323.09  4967.9  322.41
  4977.9  320.32  4987.9  316.80  4995.9  316.30  4996.2  315.80  4999.7  315.80
  4999.9  316.30  5017.9  320.18  5027.9  321.16  5037.9  321.58  5057.9  323.49
  5060.1  323.48  5067.9  323.44  5087.9  324.74  5097.9  324.87  5127.9  326.11
  5147.9  325.39  5157.9  326.88  5167.9  327.78  5219.5  329.18  5250.0  328.59
#Mann=6,-1,0
  4750.0    0.16       0  4916.8    0.12       0  4995.9    0.07       0
  4999.9    0.12       0  5060.1    0.16       0  5219.5     0.1       0
Bank Sta=4995.9,4999.9
Exp/Cntr=0.3,0.1

Type RM Length L Ch R = 1,1377,400,400,400
BEGIN DESCRIPTION:
NED BRANCH TRIB 1 4 0
END DESCRIPTION:
XS GIS Cut Line= 2
      3552993.18     10387435.95      3553314.02     10387641.98
#Sta/Elev= 30
  4716.9  341.31  4719.9  340.58  4735.1  340.25  4741.0  339.54  4750.3  339.77
  4763.2  339.31  4771.4  338.56  4798.8  335.11  4822.6  332.78  4828.9  331.63
  4850.0  330.06  4870.1  327.07  4901.5  324.18  4965.2  317.32  4989.0  315.85
  4995.3  312.99  4999.3  312.48  4999.5  311.98  5003.0  311.98  5003.3  312.48
  5016.5  315.52  5024.6  316.54  5031.7  317.15  5046.9  316.53  5060.3  318.66
  5075.6  319.77  5083.2  320.98  5089.1  321.38  5094.1  320.47  5098.2  320.47
#Mann=5,-1,0
  4716.9    0.16       0  4870.1    0.12       0  4999.3    0.07       0
  5003.3    0.12       0  5075.6    0.16       0
Bank Sta=4999.3,5003.3
Exp/Cntr=0.3,0.1

Type RM Length L Ch R = 1,977,271,271,271
BEGIN DESCRIPTION:
NED BRANCH TRIB 1 5 0
END DESCRIPTION:
XS GIS Cut Line= 2
      3552672.54     10387656.18      3553237.85     10388016.16
#Sta/Elev= 30
  4572.3  334.88  4575.4  333.96  4605.9  333.48  4611.8  332.48  4627.1  332.24
  4633.0  331.13  4669.4  329.32  4678.5  329.69  4742.2  327.18  4757.4  327.96
  4778.6  326.66  4793.8  327.63  4799.8  326.91  4815.0  327.61  4820.9  326.60
  4844.6  325.82  4924.2  318.87  4966.5  313.41  4981.8  312.35  5000.9  309.22
  5001.2  308.72  5004.9  309.22  5024.1  311.29  5081.7  312.62  5096.9  313.84
  5105.3  315.48  5133.3  314.55  5169.7  316.09  5171.2  316.08  5242.5  313.88
#Mann=6,-1,0
  4572.3    0.16       0  4844.6    0.12       0  5000.9    0.07       0
  5004.9    0.12       0  5169.7     0.1       0  5171.2    0.05       0
Bank Sta=5000.9,5004.9
Exp/Cntr=0.3,0.1

Type RM Length L Ch R = 1,706,181,181,181
BEGIN DESCRIPTION:
NED BRANCH TRIB 1 6 0
END DESCRIPTION:
XS GIS Cut Line= 2
      3552632.18     10387721.29      3552991.53     10388303.29
#Sta/Elev= 30
  4618.1  331.88  4631.8  330.36  4641.3  330.15  4699.3  325.60  4726.4  322.45
  4735.9  322.31  4788.8  317.26  4821.0  315.48  4836.4  313.88  4900.6  311.10
  4909.7  310.06  4915.6  310.40  4931.0  309.15  4952.3  309.08  4967.7  307.99
  5018.1  308.03  5039.0  307.28  5039.2  306.78  5042.7  306.78  5043.0  307.28
  5076.9  307.85  5123.1  311.70  5141.5  312.59  5206.1  317.75  5236.0  318.52
  5241.9  317.87  5255.1  318.63  5272.7  320.97  5278.6  320.71  5302.1  321.84
#Mann=6,-1,0
  4618.1    0.16       0  4788.8    0.12       0  5039.0    0.07       0
  5043.0    0.12       0  5123.1    0.16       0  5255.1    0.05       0
Bank Sta=5039,5043
Exp/Cntr=0.3,0.1

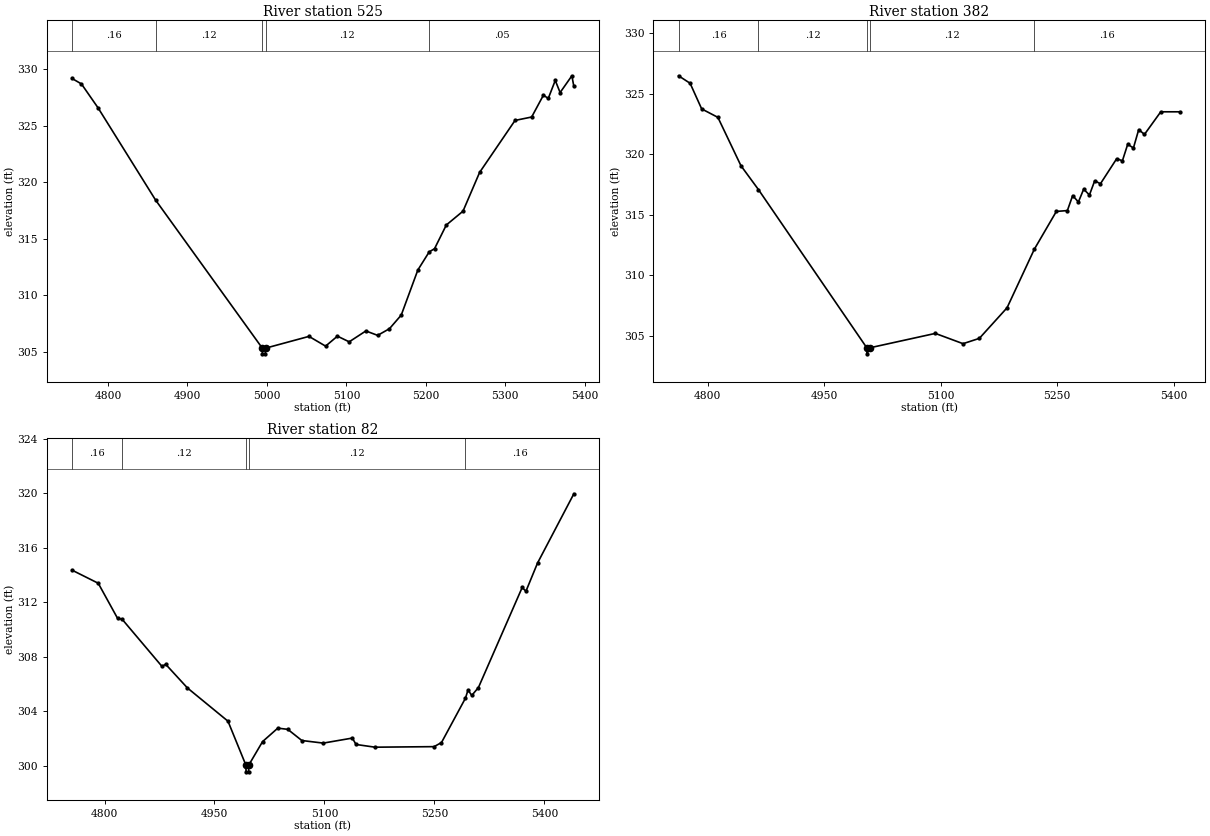
Type RM Length L Ch R = 1,525,143,143,143
BEGIN DESCRIPTION:
NED BRANCH TRIB 1 8 0
END DESCRIPTION:
XS GIS Cut Line= 2
      3552517.14     10387831.60      3552877.58     10388350.01
#Sta/Elev= 30
  4754.8  329.15  4766.6  328.67  4787.5  326.56  4859.9  318.42  4994.2  305.35
  4994.4  304.85  4997.9  304.85  4998.2  305.35  5052.9  306.39  5073.8  305.53
  5088.7  306.41  5103.5  305.91  5124.5  306.87  5139.3  306.48  5154.2  307.07
  5169.0  308.27  5189.9  312.25  5204.2  313.85  5210.9  314.13  5225.7  316.22
  5246.7  317.44  5267.6  320.86  5312.2  325.45  5333.1  325.75  5347.9  327.68
  5354.0  327.39  5362.8  328.98  5368.9  327.91  5383.7  329.39  5386.2  328.45
#Mann=5,-1,0
  4754.8    0.16       0  4859.9    0.12       0  4994.2    0.07       0
  4998.2    0.12       0  5204.2    0.05       0
Bank Sta=4994.2,4998.2
Exp/Cntr=0.3,0.1

Type RM Length L Ch R = 1,382,300,300,300
BEGIN DESCRIPTION:
NED BRANCH TRIB 1 7 0
END DESCRIPTION:
XS GIS Cut Line= 3
      3552399.95     10387912.42      3552573.51     10388162.05
      3552805.38     10388413.94
#Sta/Elev= 30
  4762.3  326.50  4777.2  325.88  4792.1  323.76  4813.0  323.06  4842.7  319.06
  4865.2  317.09  5004.8  304.00  5005.0  303.50  5008.8  304.00  5093.1  305.19
  5128.8  304.34  5149.8  304.78  5185.5  307.31  5220.6  312.15  5249.0  315.28
  5263.2  315.35  5270.0  316.59  5277.4  316.06  5284.2  317.12  5291.6  316.64
  5298.4  317.81  5305.8  317.57  5326.7  319.64  5334.1  319.47  5340.9  320.83
  5348.3  320.53  5355.1  322.05  5362.5  321.65  5383.5  323.52  5408.7  323.52
#Mann=5,-1,0
  4762.3    0.16       0  4865.2    0.12       0  5004.8    0.07       0
  5008.8    0.12       0  5220.6    0.16       0
Bank Sta=5004.8,5008.8
Exp/Cntr=0.3,0.1

Type RM Length L Ch R = 1,82,0,0,0
BEGIN DESCRIPTION:
NED BRANCH TRIB 1 1 0
END DESCRIPTION:
XS GIS Cut Line= 4
      3552336.70     10388096.42      3552371.85     10388306.16
      3552394.11     10388384.66      3552781.16     10388435.22
#Sta/Elev= 30
  4755.7  314.35  4791.4  313.39  4817.7  310.82  4824.1  310.74  4878.4  307.28
  4883.4  307.44  4913.1  305.70  4968.4  303.26  4992.8  300.04  4993.1  299.54
  4996.6  299.54  4996.8  300.04  5015.6  301.76  5036.4  302.75  5050.0  302.66
  5069.2  301.84  5098.4  301.65  5138.1  302.02  5143.1  301.55  5169.0  301.35
  5249.6  301.39  5259.7  301.69  5292.4  304.95  5295.9  305.55  5301.0  305.15
  5310.1  305.73  5369.8  313.08  5374.9  312.80  5390.8  314.88  5440.3  319.96
#Mann=5,-1,0
  4755.7    0.16       0  4824.1    0.12       0  4992.8    0.07       0
  4996.8    0.12       0  5292.4    0.16       0
Bank Sta=4992.8,4996.8
Exp/Cntr=0.3,0.1

Chan Stop Cuts=-1