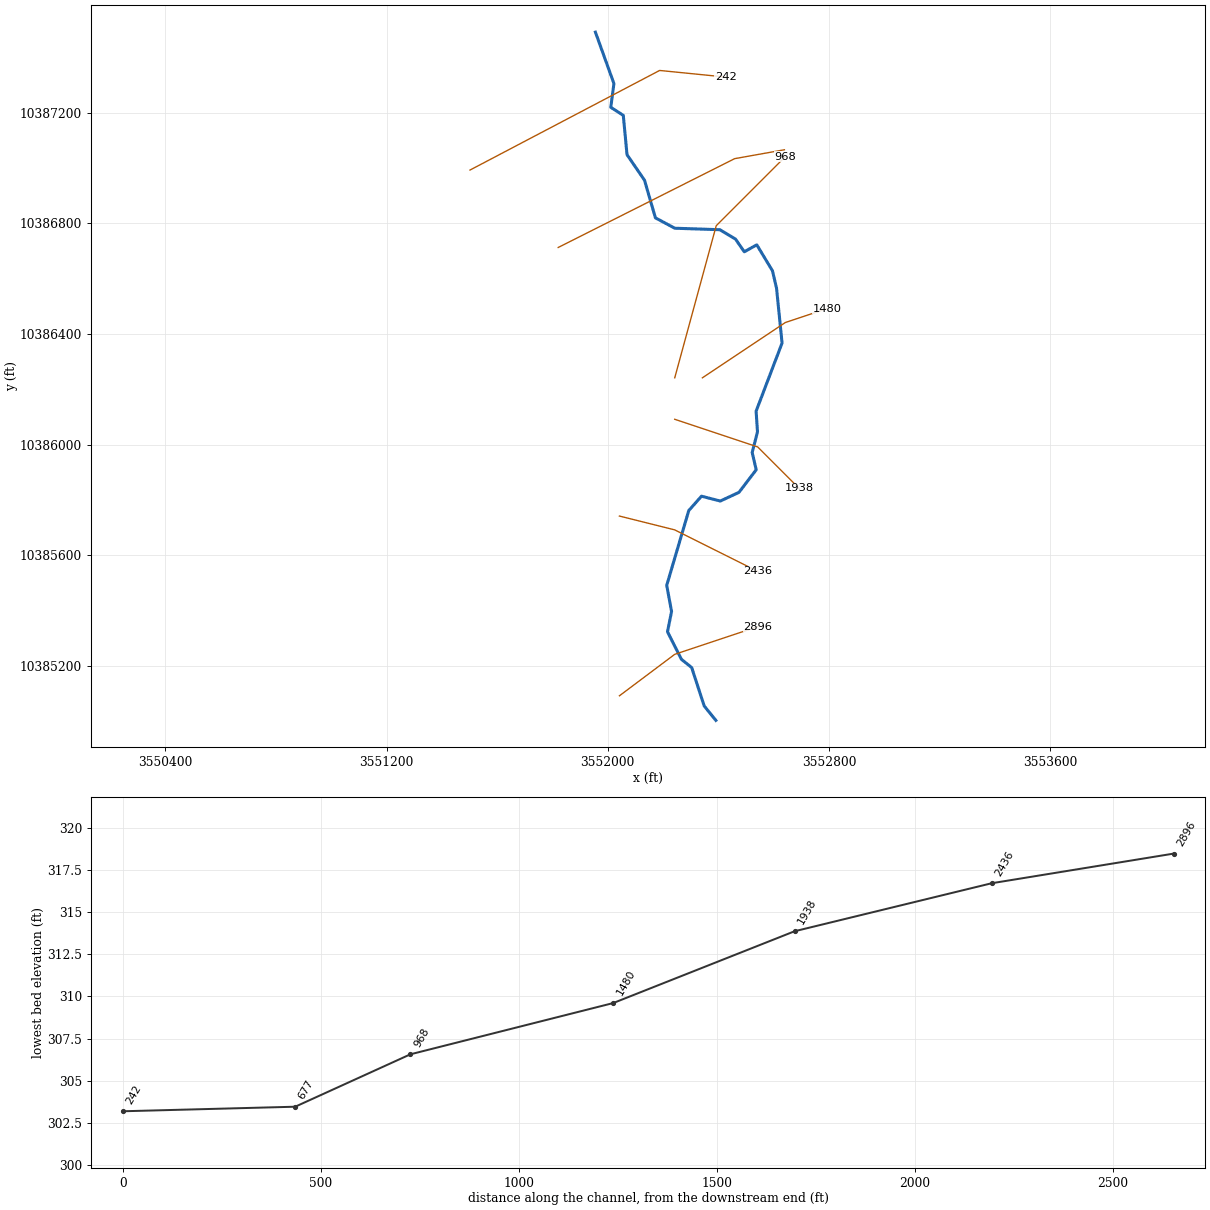
--- NED BRANCH TRIB 2.prj (project) ---

Proj Title=NED BRANCH TRIB 2 Base Level Engineering
Current Plan=p01
Default Exp/Contr=0.3,0.1
English Units
Geom File=g01
Flow File=f01
Plan File=p01
Y Axis Title=Elevation
X Axis Title(PF)=Main Channel Distance
X Axis Title(XS)=Station
BEGIN DESCRIPTION:
NED BRANCH TRIB 2
END DESCRIPTION:
DSS Export Rating Curves= 0
DSS Export Rating Curve Sorted= 0
DSS Export Volume Flow Curves= 0
DXF OffsetX= 0
DXF OffsetY= 0
DXF ScaleX= 1
DXF ScaleY= 10

--- NED BRANCH TRIB 2.p01 (plan) ---

Plan Title=Multiple Run
Short Identifier=Multiple
Geom File=g01
Flow File=f01
Subcritical Flow
K Sum by GR= 0
Std Step Tol= 0.01
Critical Tol= 0.01
Num of Std Step Trials= 20
Max Error Tol= 0.3
Flow Tol Ratio= 0.001
Split Flow NTrial= 30
Split Flow Tol= 0.02
Split Flow Ratio= 0.02
Log Output Level= 0
Friction Slope Method= 1
Unsteady Friction Slope Method= 2
Unsteady Bridges Friction Slope Method= 1
Parabolic Critical Depth
Global Vel Dist=  1 , 1 , 1
Global Log Level= 0
CheckData=True
Encroach Param= -1, 0, 0, 0
BEGIN DESCRIPTION:
Multiple Run
END DESCRIPTION:

--- NED BRANCH TRIB 2.f01 (steady flow) ---

Flow Title=Multiple
Program Version=4.10
Number of Profiles= 7
Profile Names=10-year,25-year,50-year,1pct_min,100-year,1pct_plu,500-year
River Rch & RM=NED BRANCH TRIB,Reach-1         ,2896
     617     831    1005     889    1203    1627    1716
Boundary for River Rch & Prof#=NED BRANCH TRIB,Reach-1         , 1
Up Type= 0
Dn Type= 3
Dn Slope=0.0067
Boundary for River Rch & Prof#=NED BRANCH TRIB,Reach-1         , 2
Up Type= 0
Dn Type= 3
Dn Slope=0.0067
Boundary for River Rch & Prof#=NED BRANCH TRIB,Reach-1         , 3
Up Type= 0
Dn Type= 3
Dn Slope=0.0067
Boundary for River Rch & Prof#=NED BRANCH TRIB,Reach-1         , 4
Up Type= 0
Dn Type= 3
Dn Slope=0.0067
Boundary for River Rch & Prof#=NED BRANCH TRIB,Reach-1         , 5
Up Type= 0
Dn Type= 3
Dn Slope=0.0067
Boundary for River Rch & Prof#=NED BRANCH TRIB,Reach-1         , 6
Up Type= 0
Dn Type= 3
Dn Slope=0.0067
Boundary for River Rch & Prof#=NED BRANCH TRIB,Reach-1         , 7
Up Type= 0
Dn Type= 3
Dn Slope=0.0067
DSS Import GetInterval= 0
DSS Import GetPeak= 0
DSS Import FillOption= 0

--- NED BRANCH TRIB 2.g01 (geometry) ---

Geom Title=Existing Conditions
Program Version=4.10

River Reach=NED BRANCH TRIB ,Reach-1
Reach XY= 30
      3552390.78     10385002.76      3552348.56     10385054.93
       3552303.5     10385193.51      3552266.16     10385223.79
      3552215.87     10385323.26      3552230.58     10385396.61
      3552213.09     10385491.08      3552292.84     10385761.62
      3552338.83     10385813.52      3552406.81     10385795.94
      3552474.36     10385827.41      3552536.74     10385909.04
      3552522.15     10385971.48      3552541.31     10386046.05
      3552536.35     10386120.97      3552630.22      10386367.3
       3552610.2     10386565.82      3552595.61     10386628.42
      3552538.78     10386722.57      3552493.57     10386697.34
      3552461.84     10386743.31      3552405.08     10386777.24
      3552242.37     10386782.58      3552172.23     10386820.13
      3552132.76     10386956.21      3552069.52     10387048.42
      3552055.98     10387190.78      3552010.84     10387219.86
      3552022.13      10387305.8      3551955.13     10387491.89

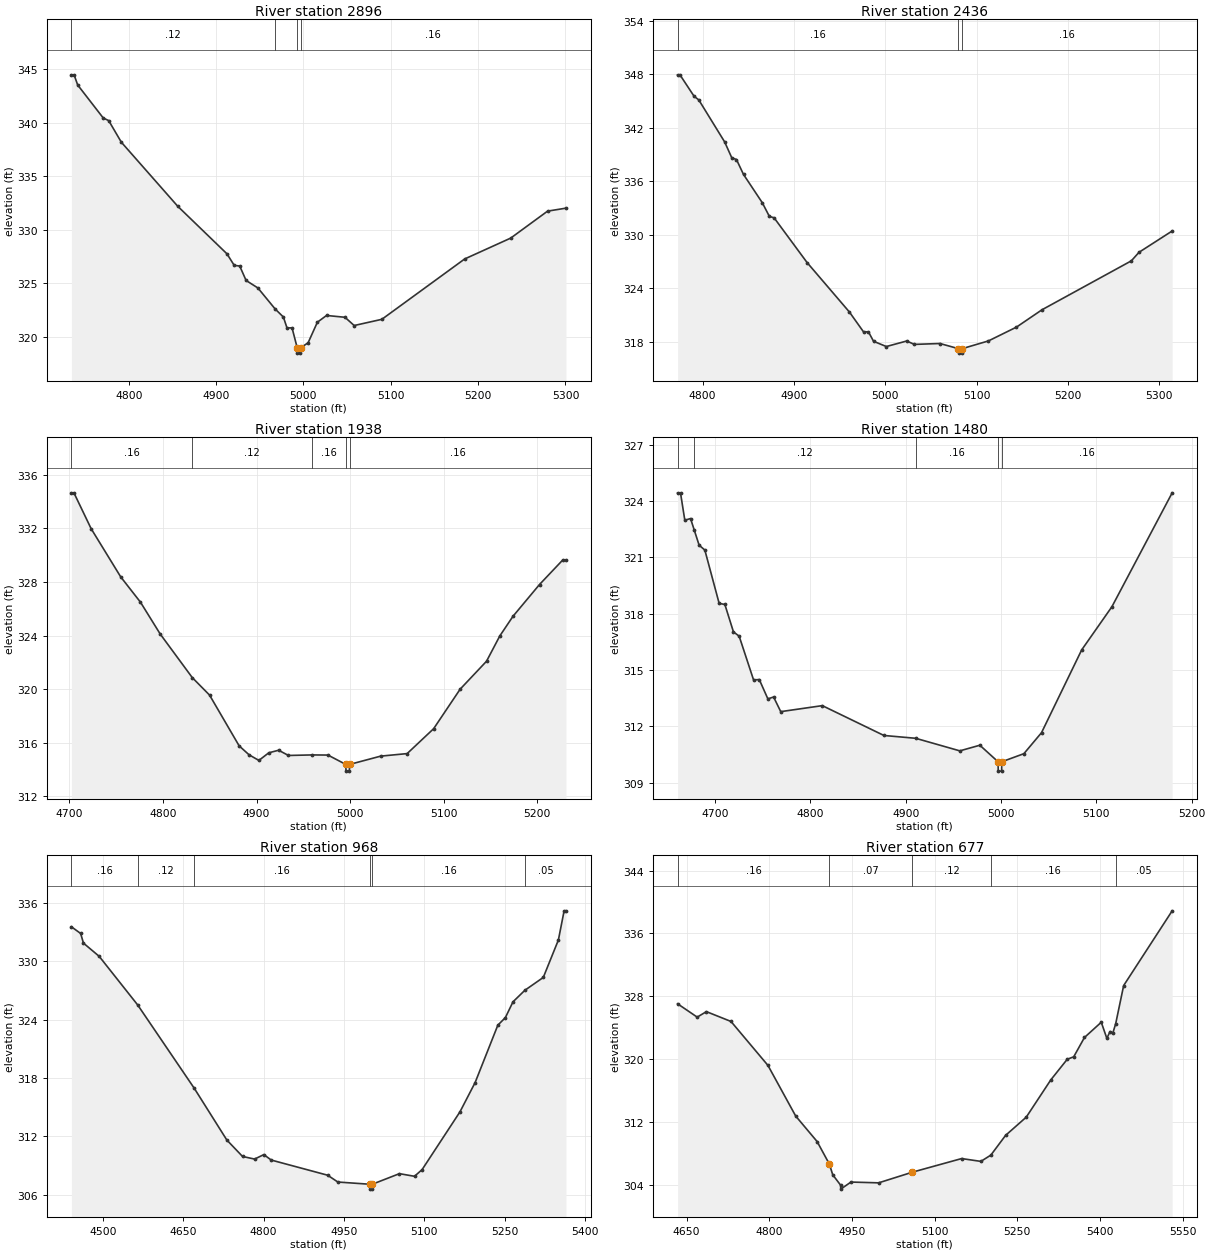
Type RM Length L Ch R = 1 ,2896    ,460,460,460
BEGIN DESCRIPTION:
NED BRANCH TRIB 2 8 0
END DESCRIPTION:
XS GIS Cut Line= 3
      3552042.14     10385091.67      3552242.11     10385241.64
      3552542.12     10385341.65
#Sta/Elev= 30
  4734.4  344.49  4737.5  344.49  4741.6  343.54  4770.8  340.46  4777.1  340.21
  4791.6  338.19  4856.2   332.2  4912.5  327.76  4920.8  326.68  4927.1  326.62
  4934.4  325.27  4947.9  324.57  4967.5  322.62  4977.1  321.85  4981.2  320.84
    4987  320.84  4992.9  318.98  4993.1  318.48  4996.6  318.48  4996.9  318.98
  5005.4  319.45    5016  321.37  5026.5     322  5047.6  321.83  5058.1  321.06
  5089.8  321.64  5184.6  327.28  5237.3  329.23  5279.5  331.75  5300.6  332.03
#Mann= 4 ,-1 , 0
  4734.4     .12       0  4967.5     .16       0  4992.9     .07       0
  4996.9     .16       0
Bank Sta=4992.9,4996.9
XS Rating Curve= 0 ,0
Exp/Cntr=0.3,0.1

Type RM Length L Ch R = 1 ,2436    ,498,498,498
BEGIN DESCRIPTION:
NED BRANCH TRIB 2 7 0
END DESCRIPTION:
XS GIS Cut Line= 3
      3552042.06     10385741.65      3552242.11     10385691.64
       3552542.1     10385541.65
#Sta/Elev= 30
  4772.6  347.96  4775.2  347.96  4790.7  345.55  4795.8  345.15  4824.2  340.42
  4831.9  338.66  4837.1  338.45  4844.8  336.78  4865.4   333.6  4873.1  332.07
  4878.3  331.91  4914.4  326.89  4960.8  321.33  4976.2  319.11  4981.6  319.11
  4987.2  318.05  5001.2  317.46  5023.5  318.08  5031.9   317.7  5059.9   317.8
  5080.2  317.22  5080.5  316.72    5084  316.72  5084.2  317.22    5113  318.09
  5143.7  319.64  5171.7  321.59  5269.5  327.08  5277.9  328.04  5314.2  330.43
#Mann= 3 ,-1 , 0
  4772.6     .16       0  5080.2     .07       0  5084.2     .16       0
Bank Sta=5080.2,5084.2
XS Rating Curve= 0 ,0
Exp/Cntr=0.3,0.1

Type RM Length L Ch R = 1 ,1938    ,458,458,458
BEGIN DESCRIPTION:
NED BRANCH TRIB 2 6 0
END DESCRIPTION:
XS GIS Cut Line= 3
      3552242.07     10386091.65      3552542.11     10385991.64
      3552692.11     10385841.64
#Sta/Elev= 30
  4702.2  334.66  4704.9  334.66  4723.3  331.98  4754.9  328.38    4776  326.49
  4797.1  324.11  4831.3  320.86  4849.8  319.55  4881.4  315.76    4892  315.09
  4902.5  314.67  4913.1  315.24  4923.6  315.43  4934.1  315.04  4959.2  315.08
  4976.3  315.07  4995.4  314.37  4995.6  313.87  4999.1  313.87  4999.4  314.37
  5032.6  314.99  5060.9  315.18  5089.2  317.04  5117.5  319.99  5145.7  322.08
  5159.9  323.97    5174  325.44  5202.3  327.81  5227.1  329.64  5230.6  329.64
#Mann= 5 ,-1 , 0
  4702.2     .16       0  4831.3     .12       0  4959.2     .16       0
  4995.4     .07       0  4999.4     .16       0
Bank Sta=4995.4,4999.4
XS Rating Curve= 0 ,0
Exp/Cntr=0.3,0.1

Type RM Length L Ch R = 1 ,1480    ,512,512,512
BEGIN DESCRIPTION:
NED BRANCH TRIB 2 5 0
END DESCRIPTION:
XS GIS Cut Line= 3
      3552342.06     10386241.62      3552642.11     10386441.64
      3552792.09     10386491.64
#Sta/Elev= 30
  4660.8  324.43  4663.9  324.43  4668.4  322.98  4674.4  323.07  4678.2  322.47
  4683.4  321.65  4689.4  321.39  4704.4  318.55  4710.4  318.49  4719.4  317.03
  4725.4   316.8  4740.5  314.47  4746.5  314.49  4755.5  313.46  4761.5  313.56
    4769  312.78  4812.6   313.1  4877.2  311.51  4910.5  311.36  4956.8  310.69
  4977.8  310.99  4996.9  310.11  4997.1  309.61  5000.6  309.61  5000.9  310.11
    5024  310.54  5042.5  311.66  5084.6  316.07  5116.3  318.37  5179.5  324.44
#Mann= 5 ,-1 , 0
  4660.8     .16       0  4678.2     .12       0  4910.5     .16       0
  4996.9     .07       0  5000.9     .16       0
Bank Sta=4996.9,5000.9
XS Rating Curve= 0 ,0
Exp/Cntr=0.3,0.1

Type RM Length L Ch R = 1 ,968     ,291,291,291
BEGIN DESCRIPTION:
NED BRANCH TRIB 2 4 0
END DESCRIPTION:
XS GIS Cut Line= 3
      3552242.09      10386241.6      3552392.11     10386791.64
      3552642.12     10387041.65
#Sta/Elev= 30
    4441  333.55  4458.3  332.86  4463.5  331.87  4492.9  330.51  4564.8  325.51
  4670.7  316.92  4731.3  311.62  4760.6  309.93  4783.1  309.66  4800.4  310.12
  4814.2  309.56  4919.6     308  4938.6   307.3  4998.8  307.07    4999  306.57
  5002.5  306.57  5002.8  307.07  5053.6  308.16  5081.8  307.89    5096  308.58
  5166.7  314.52    5195  317.53  5237.4  323.43  5251.5  324.21  5265.7  325.83
  5287.9  327.02  5322.3  328.34  5350.5  332.19  5361.2  335.19  5364.7  335.19
#Mann= 6 ,-1 , 0
    4441     .16       0  4564.8     .12       0  4670.7     .16       0
  4998.8     .07       0  5002.8     .16       0  5287.9     .05       0
Bank Sta=4998.8,5002.8
XS Rating Curve= 0 ,0
Exp/Cntr=0.3,0.1

Type RM Length L Ch R = 1 ,677     ,435,435,435
BEGIN DESCRIPTION:
Mapping XS 0f47952c
END DESCRIPTION:
XS GIS Cut Line= 3
      3551820.67     10386712.99      3552458.72     10387034.19
      3552638.74     10387066.33
#Sta/Elev= 30
  4633.7  327.05  4669.3  325.35    4686  326.05  4730.6   324.8  4797.6  319.21
    4848  312.76  4886.8  309.52  4909.1  306.64  4915.2  305.28  4929.5  303.96
  4929.7  303.46  4948.2  304.36  4998.4  304.26  5059.8  305.62    5149  307.35
  5183.9  306.99    5202  307.79  5228.7   310.3  5266.2  312.62  5310.8  317.37
  5340.6  319.99  5352.3   320.3  5371.8  322.76  5402.3   324.7  5412.4  322.65
  5418.2  323.52  5423.3  323.33  5428.4   324.5  5442.9  329.37  5530.9  338.88
#Mann= 5 ,-1 , 0
  4633.7     .16       0  4909.1     .07       0  5059.8     .12       0
    5202     .16       0  5428.4     .05       0
Bank Sta=4909.1,5059.8
XS Rating Curve= 0 ,0
Exp/Cntr=0.3,0.1

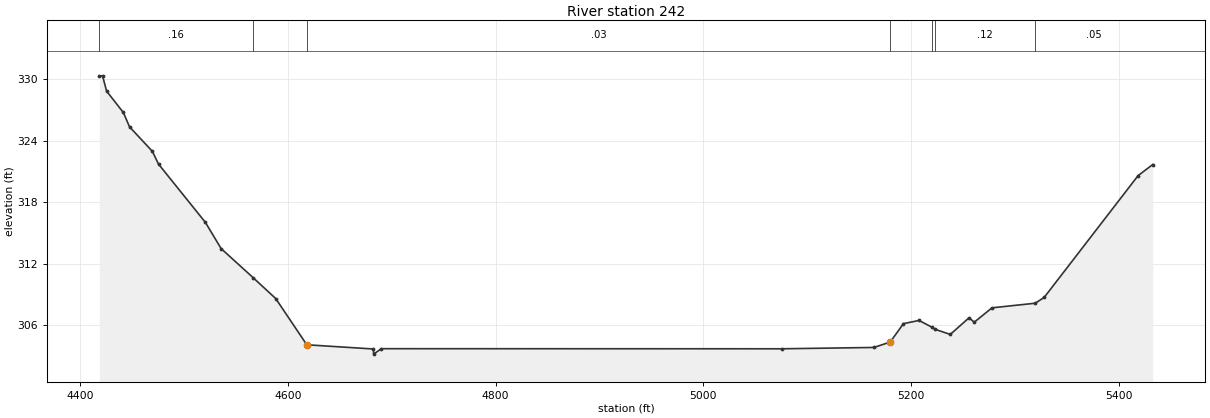
Type RM Length L Ch R = 1 ,242     ,0,0,0
BEGIN DESCRIPTION:
NED BRANCH TRIB 2 1 0
END DESCRIPTION:
XS GIS Cut Line= 3
      3551501.68     10386992.95      3552187.46      10387353.2
      3552426.13     10387329.33
#Sta/Elev= 30
  4418.4   330.3  4421.5   330.3  4425.4  328.81  4441.5  326.73  4447.5  325.33
  4469.5  322.94  4475.4   321.7  4520.5  316.03  4535.7  313.47  4566.6  310.63
  4588.3   308.6  4618.2   304.1  4682.4  303.69  4682.6  303.19    4690  303.72
  5075.6  303.71  5164.4  303.84  5180.1  304.37  5192.8  306.16  5207.8  306.47
  5220.1  305.82  5223.2  305.61  5237.9  305.11    5256  306.73    5261   306.3
  5278.1   307.7  5319.8  308.15  5328.4  308.72  5418.8  320.58  5432.9  321.66
#Mann= 7 ,-1 , 0
  4418.4     .16       0  4566.6     .07       0  4618.2     .03       0
  5180.1     .12       0  5220.1     .05       0  5223.2     .12       0
  5319.8     .05       0
#XS Ineff= 2 , 0
                         5208.21          306.44
Permanent Ineff=
       F       F
Bank Sta=4618.2,5180.1
XS Rating Curve= 0 ,0
Exp/Cntr=0.3,0.1

Chan Stop Cuts=-1
Use User Specified Reach Order=0
Composite Channel Slope=5