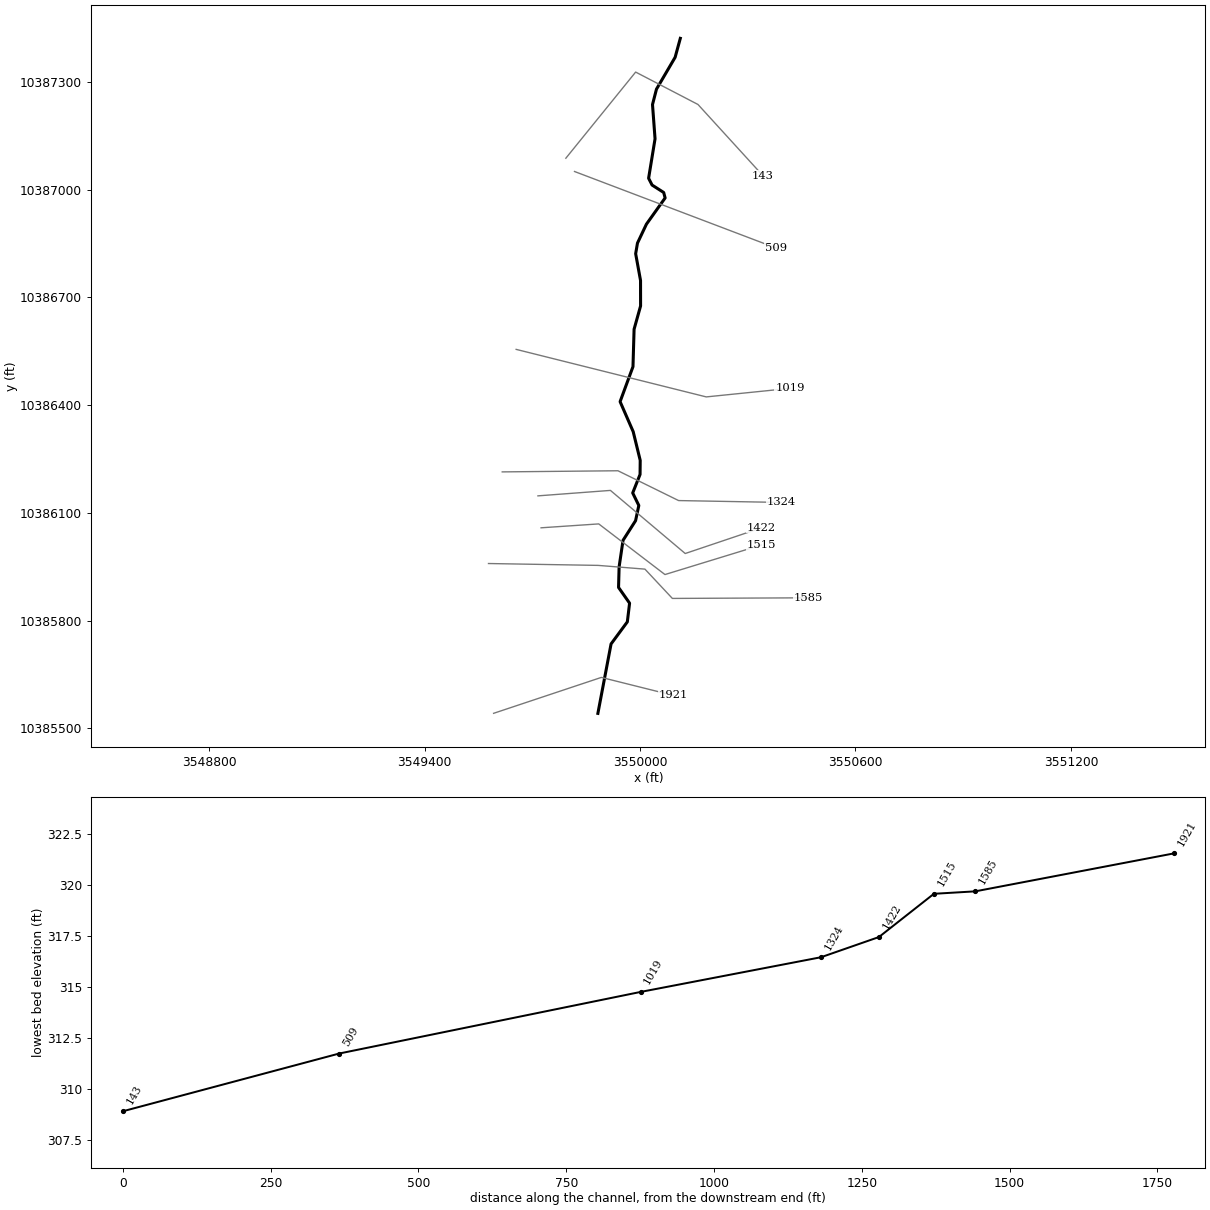
--- NED BRANCH TRIB 3.prj (project) ---

Proj Title=NED BRANCH TRIB 3 Base Level Engineering
Current Plan=p01
Default Exp/Contr=0.3,0.1
English Units
Geom File=g01
Flow File=f01
Plan File=p01
BEGIN DESCRIPTION:
NED BRANCH TRIB 3
END DESCRIPTION:

--- NED BRANCH TRIB 3.p01 (plan) ---

Plan Title=Multiple Run
Short Identifier=Multiple
Geom File=g01
Flow File=f01
Subcritical Flow
K Sum by GR= 0
Std Step Tol= 0.01
Critical Tol= 0.01
Num of Std Step Trials= 20
Max Error Tol= 0.3
Flow Tol Ratio= 0.001
Split Flow NTrial= 30
Split Flow Tol= 0.02
Split Flow Ratio= 0.02
Log Output Level= 0
Friction Slope Method= 1
Unsteady Friction Slope Method= 2
Unsteady Bridges Friction Slope Method= 1
Parabolic Critical Depth
Global Vel Dist=  1 , 1 , 1
Global Log Level= 0
CheckData=True
Encroach Param= -1, 0, 0, 0
BEGIN DESCRIPTION:
Multiple Run
END DESCRIPTION:

--- NED BRANCH TRIB 3.f01 (steady flow) ---

Flow Title=Multiple
Number of Profiles=7
Profile Names=10-year,25-year,50-year,1pct_min,100-year,1pct_plu,500-year
River Rch & RM= NED BRANCH TRIB ,Reach-1,1921
     505     673     807     711     961    1300    1354
Boundary for River Rch & Prof#=NED BRANCH TRIB ,Reach-1,1
Up Type=0
Dn Type=3
Dn Slope=0.005
Boundary for River Rch & Prof#=NED BRANCH TRIB ,Reach-1,2
Up Type=0
Dn Type=3
Dn Slope=0.005
Boundary for River Rch & Prof#=NED BRANCH TRIB ,Reach-1,3
Up Type=0
Dn Type=3
Dn Slope=0.005
Boundary for River Rch & Prof#=NED BRANCH TRIB ,Reach-1,4
Up Type=0
Dn Type=3
Dn Slope=0.005
Boundary for River Rch & Prof#=NED BRANCH TRIB ,Reach-1,5
Up Type=0
Dn Type=3
Dn Slope=0.005
Boundary for River Rch & Prof#=NED BRANCH TRIB ,Reach-1,6
Up Type=0
Dn Type=3
Dn Slope=0.005
Boundary for River Rch & Prof#=NED BRANCH TRIB ,Reach-1,7
Up Type=0
Dn Type=3
Dn Slope=0.005

--- NED BRANCH TRIB 3.g01 (geometry) ---

Geom Title=Existing Conditions

River Reach=NED BRANCH TRIB ,Reach-1
Reach XY= 30
      3549882.51     10385541.48      3549919.25     10385734.91
      3549964.56     10385796.37      3549970.81     10385848.45
      3549940.08     10385892.20      3549941.64     10385949.49
      3549952.58     10386023.45      3549987.48     10386078.14
      3549996.55     10386120.51      3549979.50     10386155.42
      3550000.00     10386207.02      3550000.42     10386246.17
      3549980.86     10386326.15      3549944.40     10386409.71
      3549980.27     10386507.18      3549983.37     10386611.52
      3550001.45     10386676.26      3550001.34     10386747.05
      3549987.73     10386821.73      3549992.78     10386851.29
      3550017.72     10386904.05      3550069.81     10386977.08
      3550065.77     10386992.33      3550033.45     10387013.02
      3550023.79     10387031.93      3550041.74     10387141.76
      3550034.66     10387237.17      3550045.69     10387280.06
      3550097.65     10387368.77      3550112.11     10387421.64

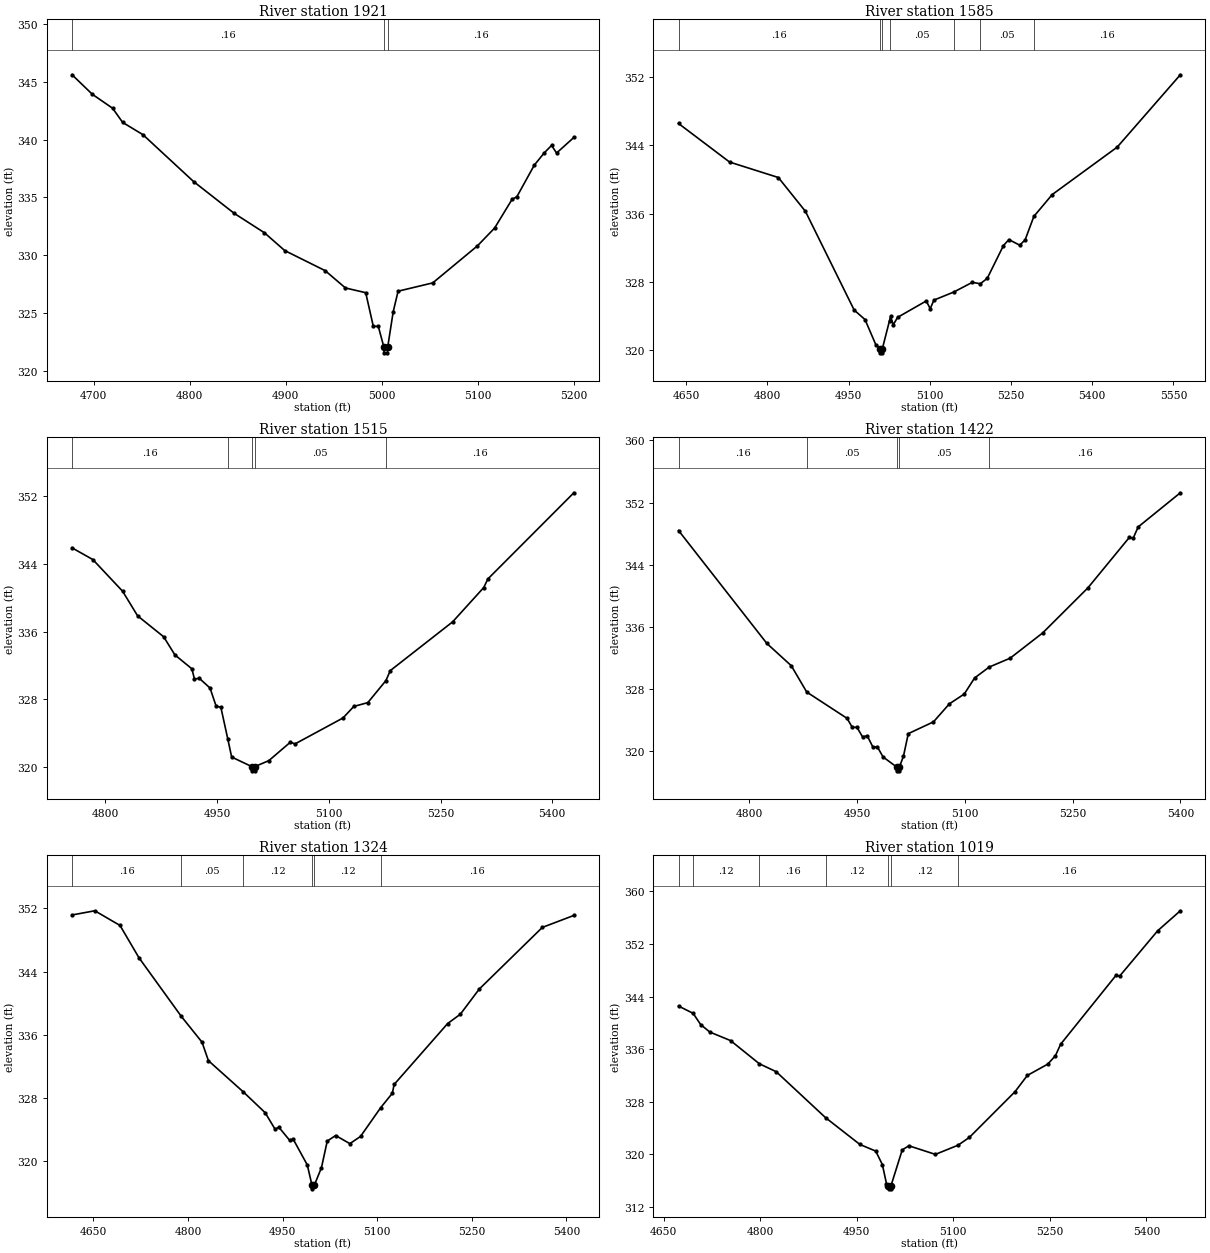
Type RM Length L Ch R = 1,1921,336,336,336
BEGIN DESCRIPTION:
NED BRANCH TRIB 3 2 0
END DESCRIPTION:
XS GIS Cut Line= 3
      3549592.09     10385541.64      3549892.11     10385641.64
      3550092.10     10385591.64
#Sta/Elev= 30
  4677.5  345.63  4698.6  343.94  4719.7  342.73  4730.2  341.50  4751.3  340.44
  4804.0  336.38  4846.2  333.63  4877.8  331.94  4898.9  330.40  4941.0  328.66
  4962.1  327.16  4983.2  326.75  4991.1  323.84  4996.3  323.84  5002.1  322.04
  5002.3  321.54  5005.8  321.54  5006.1  322.04  5011.8  325.09  5016.9  326.88
  5053.0  327.60  5099.4  330.80  5117.4  332.35  5135.5  334.83  5140.6  335.07
  5158.7  337.80  5169.0  338.86  5176.7  339.51  5181.9  338.85  5199.9  340.20
#Mann=3,-1,0
  4677.5    0.16       0  5002.1    0.07       0  5006.1    0.16       0
Bank Sta=5002.1,5006.1
Exp/Cntr=0.3,0.1

Type RM Length L Ch R = 1,1585,70,70,70
BEGIN DESCRIPTION:
NED BRANCH TRIB 3 3 0
END DESCRIPTION:
XS GIS Cut Line= 5
      3549577.84     10385958.86      3549883.38     10385953.65
      3550013.59     10385943.24      3550089.98     10385861.64
      3550468.69     10385863.37
#Sta/Elev= 30
  4636.0  346.56  4730.3  342.04  4820.3  340.23  4870.3  336.27  4960.4  324.69
  4980.4  323.58  5000.5  320.61  5008.5  320.18  5008.8  319.68  5012.3  319.68
  5012.5  320.18  5025.7  323.47  5027.5  323.95  5032.6  322.98  5040.6  323.84
  5093.5  325.76  5100.8  324.85  5107.6  325.86  5144.1  326.80  5178.5  327.94
  5193.4  327.78  5206.1  328.41  5236.1  332.26  5246.1  332.95  5266.1  332.30
  5276.1  332.92  5292.2  335.67  5326.1  338.23  5446.1  343.79  5562.7  352.27
#Mann=7,-1,0
  4636.0    0.16       0  5008.5    0.07       0  5012.5    0.16       0
  5025.7    0.05       0  5144.1    0.16       0  5193.4    0.05       0
  5292.2    0.16       0
Bank Sta=5008.5,5012.5
Exp/Cntr=0.3,0.1

Type RM Length L Ch R = 1,1515,93,93,93
BEGIN DESCRIPTION:
NED BRANCH TRIB 3 7 0
END DESCRIPTION:
XS GIS Cut Line= 4
      3549724.31     10386058.35      3549884.88     10386069.20
      3550069.35     10385928.14      3550337.77     10386010.40
#Sta/Elev= 30
  4755.2  345.87  4783.1  344.49  4823.1  340.75  4843.2  337.85  4878.2  335.38
  4893.3  333.24  4916.1  331.60  4919.6  330.38  4925.9  330.49  4940.5  329.33
  4948.7  327.18  4955.0  327.07  4964.3  323.33  4969.5  321.19  4996.6  320.06
  4996.8  319.56  5000.3  319.56  5000.6  320.06  5019.4  320.76  5048.4  322.94
  5054.7  322.74  5119.1  325.80  5133.6  327.16  5152.4  327.61  5176.7  330.21
  5182.6  331.39  5266.3  337.14  5308.1  341.19  5313.6  342.20  5429.1  352.37
#Mann=5,-1,0
  4755.2    0.16       0  4964.3    0.05       0  4996.6   0.035       0
  5000.6    0.05       0  5176.7    0.16       0
Bank Sta=4996.6,5000.6
Exp/Cntr=0.3,0.1

Type RM Length L Ch R = 1,1422,98,98,98
BEGIN DESCRIPTION:
NED BRANCH TRIB 3 6 0
END DESCRIPTION:
XS GIS Cut Line= 4
      3549715.58     10386147.32      3549917.44     10386162.51
      3550125.77     10385986.73      3550337.76     10386058.12
#Sta/Elev= 30
  4701.2  348.40  4824.2  333.85  4858.2  330.98  4879.7  327.59  4935.9  324.20
  4943.1  323.04  4949.6  323.05  4957.4  321.82  4963.9  321.96  4971.7  320.53
  4978.2  320.50  4986.0  319.23  5004.8  317.94  5005.1  317.44  5008.6  317.44
  5008.8  317.94  5014.4  319.33  5021.1  322.23  5056.2  323.75  5078.3  326.07
  5099.1  327.34  5113.4  329.40  5133.8  330.81  5162.9  331.95  5208.3  335.21
  5271.3  341.02  5329.0  347.52  5334.2  347.40  5341.2  348.86  5399.9  353.26
#Mann=5,-1,0
  4701.2    0.16       0  4879.7    0.05       0  5004.8   0.035       0
  5008.8    0.05       0  5133.8    0.16       0
Bank Sta=5004.8,5008.8
Exp/Cntr=0.3,0.1

Type RM Length L Ch R = 1,1324,305,305,305
BEGIN DESCRIPTION:
NED BRANCH TRIB 3 8 0
END DESCRIPTION:
XS GIS Cut Line= 4
      3549616.07     10386214.07      3549938.42     10386217.24
      3550107.34     10386134.21      3550392.10     10386129.00
#Sta/Elev= 30
  4616.3  351.17  4652.3  351.70  4692.3  349.84  4722.3  345.75  4789.2  338.34
  4822.3  335.04  4832.4  332.70  4888.0  328.72  4922.4  326.10  4938.0  324.02
  4944.2  324.25  4961.1  322.61  4966.7  322.76  4989.1  319.49  4996.5  316.95
  4996.7  316.45  5000.5  316.95  5011.6  319.13  5020.8  322.51  5034.1  323.21
  5056.6  322.18  5073.5  323.09  5105.6  326.75  5124.0  328.57  5126.8  329.68
  5211.7  337.41  5231.7  338.58  5261.7  341.77  5361.7  349.59  5411.7  351.11
#Mann=6,-1,0
  4616.3    0.16       0  4789.2    0.05       0  4888.0    0.12       0
  4996.5    0.07       0  5000.5    0.12       0  5105.6    0.16       0
Bank Sta=4996.5,5000.5
Exp/Cntr=0.3,0.1

Type RM Length L Ch R = 1,1019,510,510,510
BEGIN DESCRIPTION:
NED BRANCH TRIB 3 4 0
END DESCRIPTION:
XS GIS Cut Line= 3
      3549654.90     10386555.30      3550184.36     10386422.93
      3550417.10     10386446.64
#Sta/Elev= 30
  4673.0  342.55  4695.7  341.44  4707.4  339.73  4721.7  338.59  4753.8  337.30
  4798.6  333.77  4824.7  332.57  4901.5  325.57  4954.8  321.50  4979.4  320.49
  4989.7  318.44  4996.1  315.55  4999.2  315.25  4999.5  314.75  5003.0  314.75
  5003.2  315.25  5020.6  320.67  5030.9  321.30  5072.1  319.99  5107.2  321.38
  5124.9  322.57  5195.8  329.52  5215.0  332.00  5246.6  333.71  5258.6  334.99
  5266.7  336.74  5353.1  347.26  5358.2  347.08  5417.5  354.00  5452.7  357.04
#Mann=7,-1,0
  4673.0    0.05       0  4695.7    0.12       0  4798.6    0.16       0
  4901.5    0.12       0  4999.2    0.07       0  5003.2    0.12       0
  5107.2    0.16       0
Bank Sta=4999.2,5003.2
Exp/Cntr=0.3,0.1

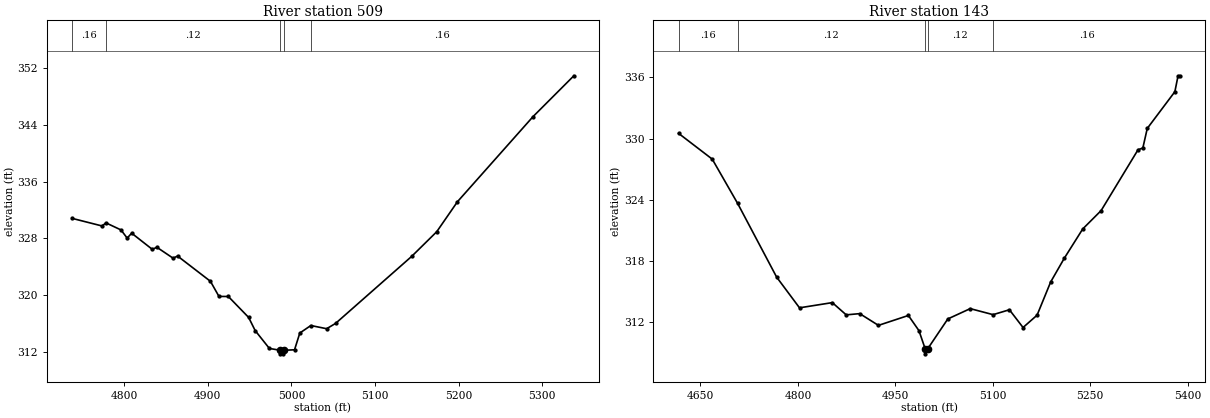
Type RM Length L Ch R = 1,509,366,366,366
BEGIN DESCRIPTION:
NED BRANCH TRIB 3 5 0
END DESCRIPTION:
XS GIS Cut Line= 2
      3549817.40     10387050.76      3550378.52     10386837.74
#Sta/Elev= 30
  4737.6  330.82  4773.4  329.75  4778.2  330.18  4796.1  329.19  4803.5  328.04
  4808.9  328.73  4833.6  326.45  4839.0  326.75  4858.4  325.21  4863.8  325.51
  4903.1  321.95  4913.3  319.82  4924.5  319.81  4948.8  316.86  4956.6  315.01
  4973.6  312.49  4986.7  312.23  4986.9  311.73  4990.4  311.73  4990.7  312.23
  5003.7  312.30  5010.0  314.66  5023.2  315.72  5042.1  315.27  5052.8  316.02
  5143.7  325.45  5173.8  328.94  5198.6  333.17  5289.0  345.16  5337.8  350.91
#Mann=5,-1,0
  4737.6    0.16       0  4778.2    0.12       0  4986.7    0.07       0
  4990.7    0.12       0  5023.2    0.16       0
Bank Sta=4986.7,4990.7
Exp/Cntr=0.3,0.1

Type RM Length L Ch R = 1,143,0,0,0
BEGIN DESCRIPTION:
NED BRANCH TRIB 3 1 0
END DESCRIPTION:
XS GIS Cut Line= 4
      3549793.30     10387087.74      3549987.71     10387327.69
      3550161.32     10387237.41      3550341.88     10387039.50
#Sta/Elev= 30
  4616.3  330.51  4668.2  327.98  4707.2  323.65  4767.3  316.42  4802.5  313.41
  4853.0  313.92  4874.4  312.72  4895.2  312.84  4924.0  311.69  4970.1  312.66
  4986.4  311.17  4995.9  309.40  4996.1  308.90  4999.9  309.40  5030.8  312.32
  5065.3  313.33  5100.5  312.74  5125.6  313.22  5146.6  311.48  5168.2  312.69
  5189.1  315.94  5210.1  318.27  5238.5  321.14  5266.8  322.94  5323.6  328.90
  5331.0  329.07  5337.8  330.99  5380.3  334.59  5385.2  336.15  5388.7  336.15
#Mann=5,-1,0
  4616.3    0.16       0  4707.2    0.12       0  4995.9    0.07       0
  4999.9    0.12       0  5100.5    0.16       0
Bank Sta=4995.9,4999.9
Exp/Cntr=0.3,0.1

Chan Stop Cuts=-1