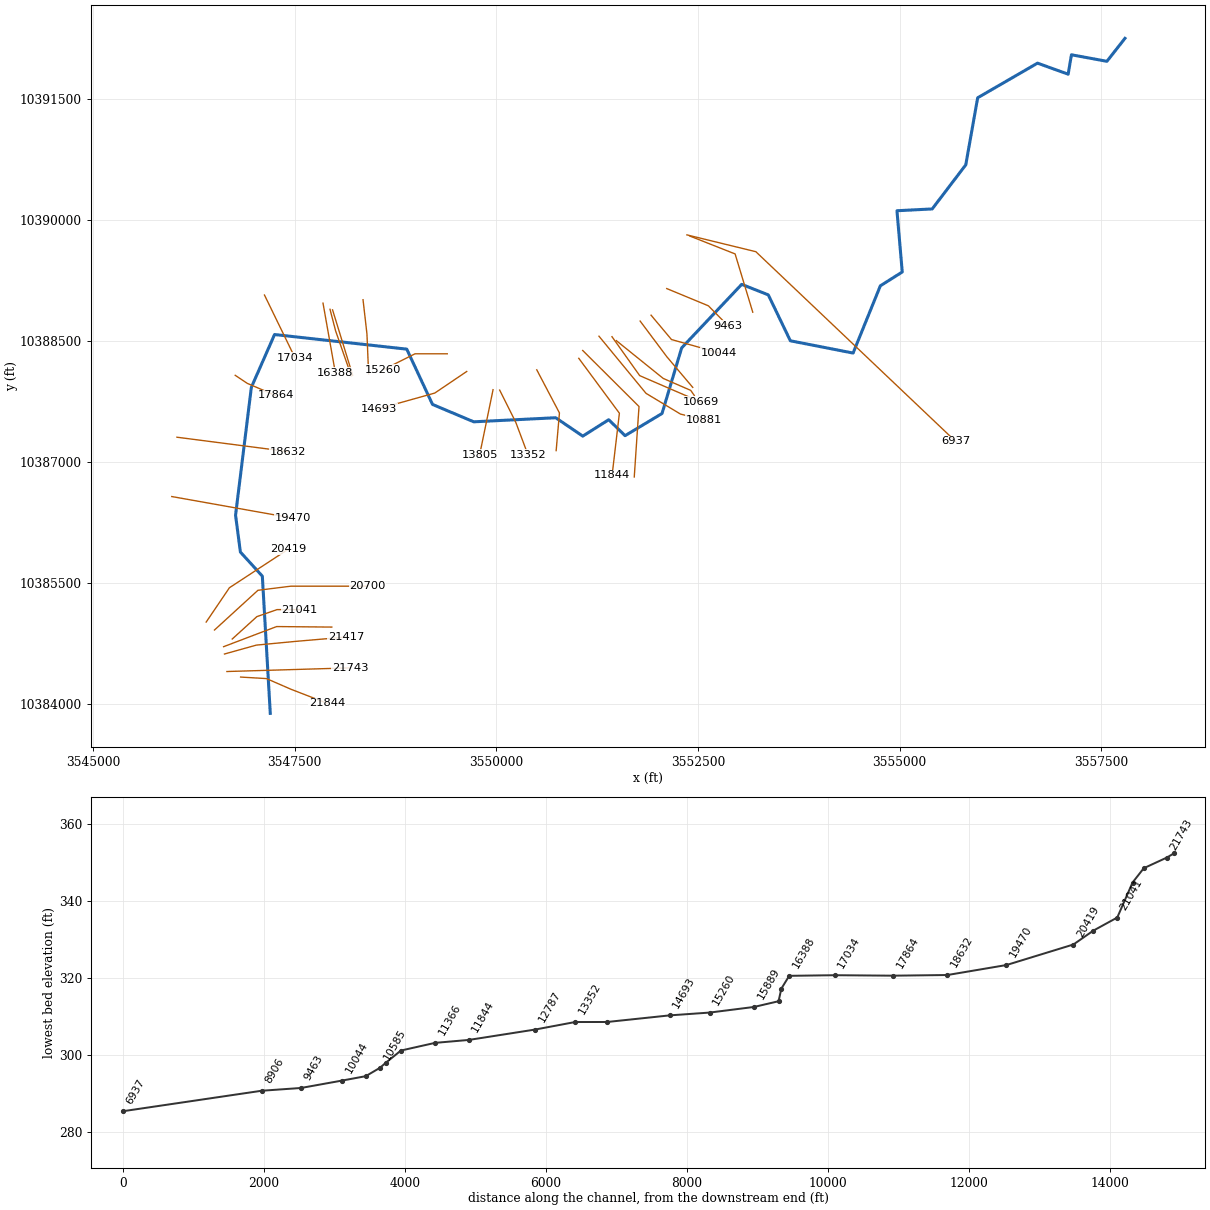
--- NED BRANCH.prj (project) ---

Proj Title=NED BRANCH Base Level Engineering
Current Plan=p01
Default Exp/Contr=0.3,0.1
English Units
Geom File=g01
Flow File=f01
Plan File=p01
Y Axis Title=Elevation
X Axis Title(PF)=Main Channel Distance
X Axis Title(XS)=Station
BEGIN DESCRIPTION:
NED BRANCH
END DESCRIPTION:
DSS Export Rating Curves= 0
DSS Export Rating Curve Sorted= 0
DSS Export Volume Flow Curves= 0
DXF OffsetX= 0
DXF OffsetY= 0
DXF ScaleX= 1
DXF ScaleY= 10

--- NED BRANCH.p01 (plan) ---

Plan Title=Multiple Run
Short Identifier=Multiple
Geom File=g01
Flow File=f01
Subcritical Flow
K Sum by GR= 0
Std Step Tol= 0.01
Critical Tol= 0.01
Num of Std Step Trials= 20
Max Error Tol= 0.3
Flow Tol Ratio= 0.001
Split Flow NTrial= 30
Split Flow Tol= 0.02
Split Flow Ratio= 0.02
Log Output Level= 0
Friction Slope Method= 1
Unsteady Friction Slope Method= 2
Unsteady Bridges Friction Slope Method= 1
Parabolic Critical Depth
Global Vel Dist=  1 , 1 , 1
Global Log Level= 0
CheckData=True
Encroach Param= -1, 0, 0, 0
BEGIN DESCRIPTION:
Multiple Run
END DESCRIPTION:

--- NED BRANCH.f01 (steady flow) ---

Flow Title=Multiple
Number of Profiles=7
Profile Names=10-year,25-year,50-year,1pct_min,100-year,1pct_plu,500-year
River Rch & RM= NED BRANCH,Reach-1,21844
     232     289     333     281     380     514     491
River Rch & RM= NED BRANCH,Reach-1,21743
    1171    1638    2029    1834    2480    3354    3698
River Rch & RM= NED BRANCH,Reach-1,17864
    1497    2106    2620    2374    3211    4342    4812
River Rch & RM= NED BRANCH,Reach-1,13352
    1670    2360    2942    2672    3613    4886    5438
River Rch & RM= NED BRANCH,Reach-1,10881
    1896    2693    3371    3071    4153    5616    6292
River Rch & RM= NED BRANCH,Reach-1,10044
    2244    3206    4026    3678    4974    6727    7579
River Rch & RM= NED BRANCH,Reach-1,4266
    2473    3536    4443    4059    5489    7423    8364
Boundary for River Rch & Prof#=NED BRANCH,Reach-1,1
Up Type=0
Dn Type=3
Dn Slope=0.005
Boundary for River Rch & Prof#=NED BRANCH,Reach-1,2
Up Type=0
Dn Type=3
Dn Slope=0.005
Boundary for River Rch & Prof#=NED BRANCH,Reach-1,3
Up Type=0
Dn Type=3
Dn Slope=0.005
Boundary for River Rch & Prof#=NED BRANCH,Reach-1,4
Up Type=0
Dn Type=3
Dn Slope=0.005
Boundary for River Rch & Prof#=NED BRANCH,Reach-1,5
Up Type=0
Dn Type=3
Dn Slope=0.005
Boundary for River Rch & Prof#=NED BRANCH,Reach-1,6
Up Type=0
Dn Type=3
Dn Slope=0.005
Boundary for River Rch & Prof#=NED BRANCH,Reach-1,7
Up Type=0
Dn Type=3
Dn Slope=0.005

--- NED BRANCH.g01 (geometry) ---

Geom Title=Existing Conditions
Program Version=4.10

River Reach=NED BRANCH      ,Reach-1
Reach XY= 30
      3547198.79     10383884.92      3547100.31     10385585.78
      3546828.31      10385884.6      3546768.45     10386341.74
      3546964.14     10387925.95      3547251.94     10388580.44
      3548890.32      10388399.3       3549209.8     10387713.92
      3549720.89     10387498.73      3550736.68     10387549.15
       3551071.9     10387321.22      3551393.54     10387524.72
      3551596.11      10387326.9      3552054.13     10387601.48
      3552297.39     10388414.16      3553041.71     10389202.38
      3553371.26     10389072.05      3553644.85     10388502.96
      3554422.45     10388350.87      3554760.31     10389184.24
      3555031.67     10389355.48      3554966.16     10390114.76
      3555403.09     10390137.18      3555819.06     10390683.82
      3555966.48     10391514.85      3556708.14     10391944.01
        3557088.     10391807.21      3557128.83     10392047.79
      3557568.56     10391966.93      3557792.11     10392251.64

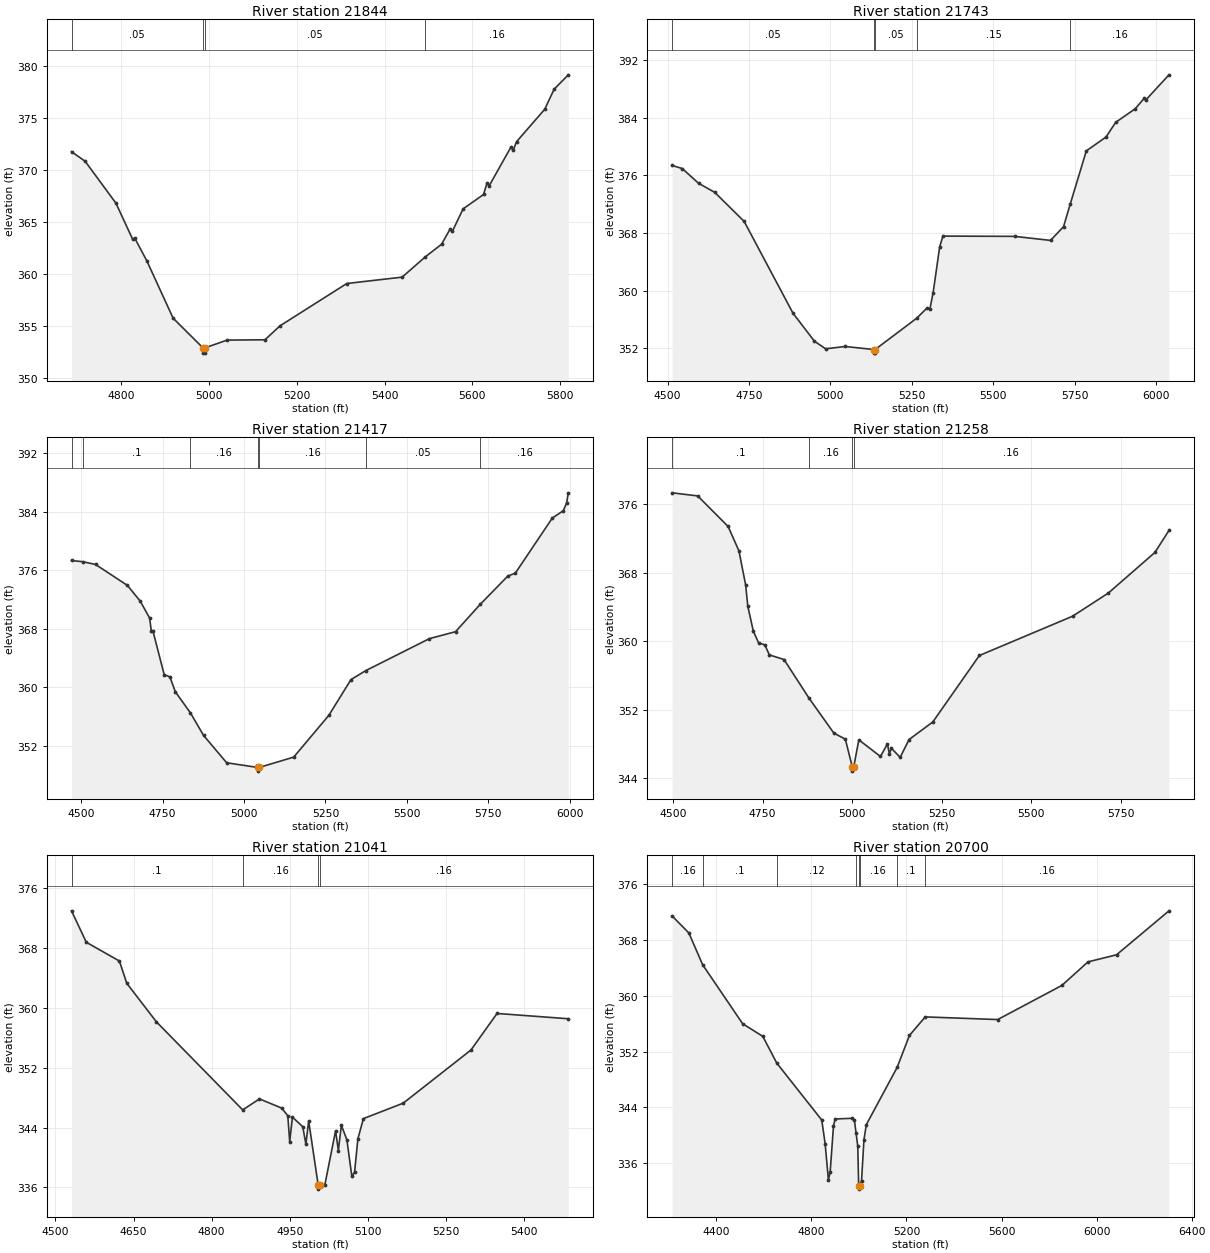
Type RM Length L Ch R = 1 ,21844   ,101,101,101
BEGIN DESCRIPTION:
Mapping XS 8e30ada5
END DESCRIPTION:
XS GIS Cut Line= 4
      3546831.01      10384335.1      3547152.14       10384316.
      3547450.75     10384185.79      3547902.12     10384010.45
#Sta/Elev= 30
  4686.8  371.76    4718  370.83  4788.1  366.81  4826.2  363.34  4831.2  363.43
  4858.2   361.3  4918.3  355.78  4986.4  352.93  4986.7  352.43  4990.2  352.43
  4990.4  352.93  5041.2  353.68  5127.5  353.71  5161.8  355.05  5313.9  359.11
    5440  359.72  5493.1  361.68  5529.7  362.87  5548.9  364.31  5554.3  364.11
  5578.8  366.27  5625.4  367.65  5633.2  368.73  5638.6  368.51  5687.7  372.19
    5693  371.89  5700.5  372.71  5764.8  375.83  5786.3  377.76  5818.5  379.13
#Mann= 4 ,-1 , 0
  4686.8     .05       0  4986.4     .03       0  4990.4     .05       0
  5493.1     .16       0
Bank Sta=4986.4,4990.4
XS Rating Curve= 0 ,0
Exp/Cntr=0.3,0.1

Type RM Length L Ch R = 1 ,21743   ,326,326,326
BEGIN DESCRIPTION:
NED BRANCH 41 0
END DESCRIPTION:
XS GIS Cut Line= 2
      3546661.34     10384403.69      3548185.67     10384448.83
#Sta/Elev= 30
  4514.3  377.36  4545.1  376.94  4595.1   374.9  4645.1  373.63  4735.2  369.61
  4885.2  356.87    4951  352.99  4985.3  351.94  5045.3  352.26  5133.3  351.84
  5133.6  351.34  5137.1  351.34  5137.3  351.84  5264.3  356.16  5295.4  357.54
  5305.4  357.46  5315.4  359.74  5335.4  366.08  5345.4  367.57  5565.5  367.53
  5675.6  366.97  5715.6  368.87  5736.4  372.04  5785.6  379.39  5845.7  381.29
  5875.7  383.34  5935.7  385.23    5963  386.66    5968  386.44  6039.3  389.93
#Mann= 5 ,-1 , 0
  4514.3     .05       0  5133.3     .03       0  5137.3     .05       0
  5264.3     .15       0  5736.4     .16       0
Bank Sta=5133.3,5137.3
XS Rating Curve= 0 ,0
Exp/Cntr=0.3,0.1

Type RM Length L Ch R = 1 ,21417   ,159,159,159
BEGIN DESCRIPTION:
NED BRANCH 37 0
END DESCRIPTION:
XS GIS Cut Line= 4
      3546630.98     10384620.72      3547026.09     10384730.94
      3547524.68     10384778.26      3548137.11     10384830.75
#Sta/Elev= 30
  4470.2  377.34  4505.2  377.17    4544   376.8  4641.9  373.94  4681.3  371.79
  4710.1  369.48  4715.4  367.69  4720.6  367.66  4754.8  361.76  4772.4  361.45
    4789  359.42  4835.3  356.54  4875.7  353.46  4946.7  349.72  5042.4  349.08
  5042.6  348.58  5046.4  349.08  5152.5  350.49  5260.7  356.21  5328.4  361.08
  5373.7   362.3  5569.3  366.67  5649.6  367.62  5726.2  371.39  5810.2  375.22
    5833   375.6  5946.7  383.13  5980.8  384.15  5990.9  385.23  5995.9  386.58
#Mann= 7 ,-1 , 0
  4470.2     .05       0  4505.2      .1       0  4835.3     .16       0
  5042.4     .07       0  5046.4     .16       0  5373.7     .05       0
  5726.2     .16       0
Bank Sta=5042.4,5046.4
XS Rating Curve= 0 ,0
Exp/Cntr=0.3,0.1

Type RM Length L Ch R = 1 ,21258   ,217,217,217
BEGIN DESCRIPTION:
NED BRANCH 443 0
END DESCRIPTION:
XS GIS Cut Line= 4
      3546620.28     10384711.41      3547019.58     10384863.31
      3547277.83     10384960.97      3547961.38     10384954.46
#Sta/Elev= 30
  4497.5  377.35  4568.7  376.99  4653.7  373.42  4683.8  370.58  4702.7  366.57
  4708.6  364.11  4724.1  361.19  4738.7  359.84  4756.2   359.6  4768.8  358.43
  4809.7  357.89  4879.8  353.36  4948.8   349.3  4980.9  348.59  5000.3  345.36
  5000.5  344.86  5004.3  345.36  5018.6  348.51    5079  346.57  5098.4  348.04
  5103.8  346.87  5109.2  347.54    5134  346.47  5158.8  348.55  5225.1   350.6
  5355.1  358.36  5615.1  362.94  5715.1  365.65  5845.1  370.39  5884.4  372.96
#Mann= 4 ,-1 , 0
  4497.5      .1       0  4879.8     .16       0  5000.3     .07       0
  5004.3     .16       0
Bank Sta=5000.3,5004.3
XS Rating Curve= 0 ,0
Exp/Cntr=0.3,0.1

Type RM Length L Ch R = 1 ,21041   ,341,341,341
BEGIN DESCRIPTION:
NED BRANCH 36 0
END DESCRIPTION:
XS GIS Cut Line= 4
      3546727.32     10384806.48      3547032.86     10385084.25
      3547282.86     10385171.06      3547558.89     10385171.06
#Sta/Elev= 30
    4531  373.01  4559.4   368.8  4622.9  366.29  4637.1  363.31  4693.8  358.16
  4859.6  346.36  4891.8  347.83  4934.4   346.6  4946.2  345.57  4949.8   342.1
  4955.1  345.39  4974.9   344.1  4980.9  341.77  4986.2  344.88  5004.6  336.25
  5004.9  335.75  5008.6  336.25  5017.4  336.36  5037.9  343.57  5043.2  340.92
    5049   344.3  5059.6  342.35    5069   337.5  5074.3  338.01  5080.7  342.48
  5091.3  345.19  5167.7  347.26  5297.8  354.38  5347.8  359.27  5484.6  358.56
#Mann= 4 ,-1 , 0
    4531      .1       0  4859.6     .16       0  5004.6     .07       0
  5008.6     .16       0
Bank Sta=5004.6,5008.6
XS Rating Curve= 0 ,0
Exp/Cntr=0.3,0.1

Type RM Length L Ch R = 1 ,20700   ,281,281,281
BEGIN DESCRIPTION:
NED BRANCH 42 0
END DESCRIPTION:
XS GIS Cut Line= 4
      3546507.02     10384918.02      3547045.79     10385410.43
      3547453.17      10385461.4      3548402.83      10385461.4
#Sta/Elev= 30
  4214.5  371.38  4284.5  368.96  4342.7  364.41  4510.8  355.98  4595.9  354.16
  4654.6  350.34  4843.8   342.2    4858  338.82  4871.7  333.66    4879   334.7
  4893.1  341.33  4899.9  342.35  4970.9  342.45    4981  342.19  4988.2  340.34
  4995.3  338.46  4999.1  332.82  4999.4  332.32  5003.1  332.82  5011.2  333.52
  5021.3   339.4  5031.4  341.55  5160.8  349.72  5212.8  354.31  5279.2  356.95
  5583.9  356.57  5853.9  361.45  5963.9  364.82  6083.9  365.83  6304.6  372.12
#Mann= 8 ,-1 , 0
  4214.5     .16       0  4342.7      .1       0  4654.6     .12       0
  4988.2     .16       0  4999.1     .07       0  5003.1     .16       0
  5160.8      .1       0  5279.2     .16       0
Bank Sta=4999.1,5003.1
XS Rating Curve= 0 ,0
Exp/Cntr=0.3,0.1

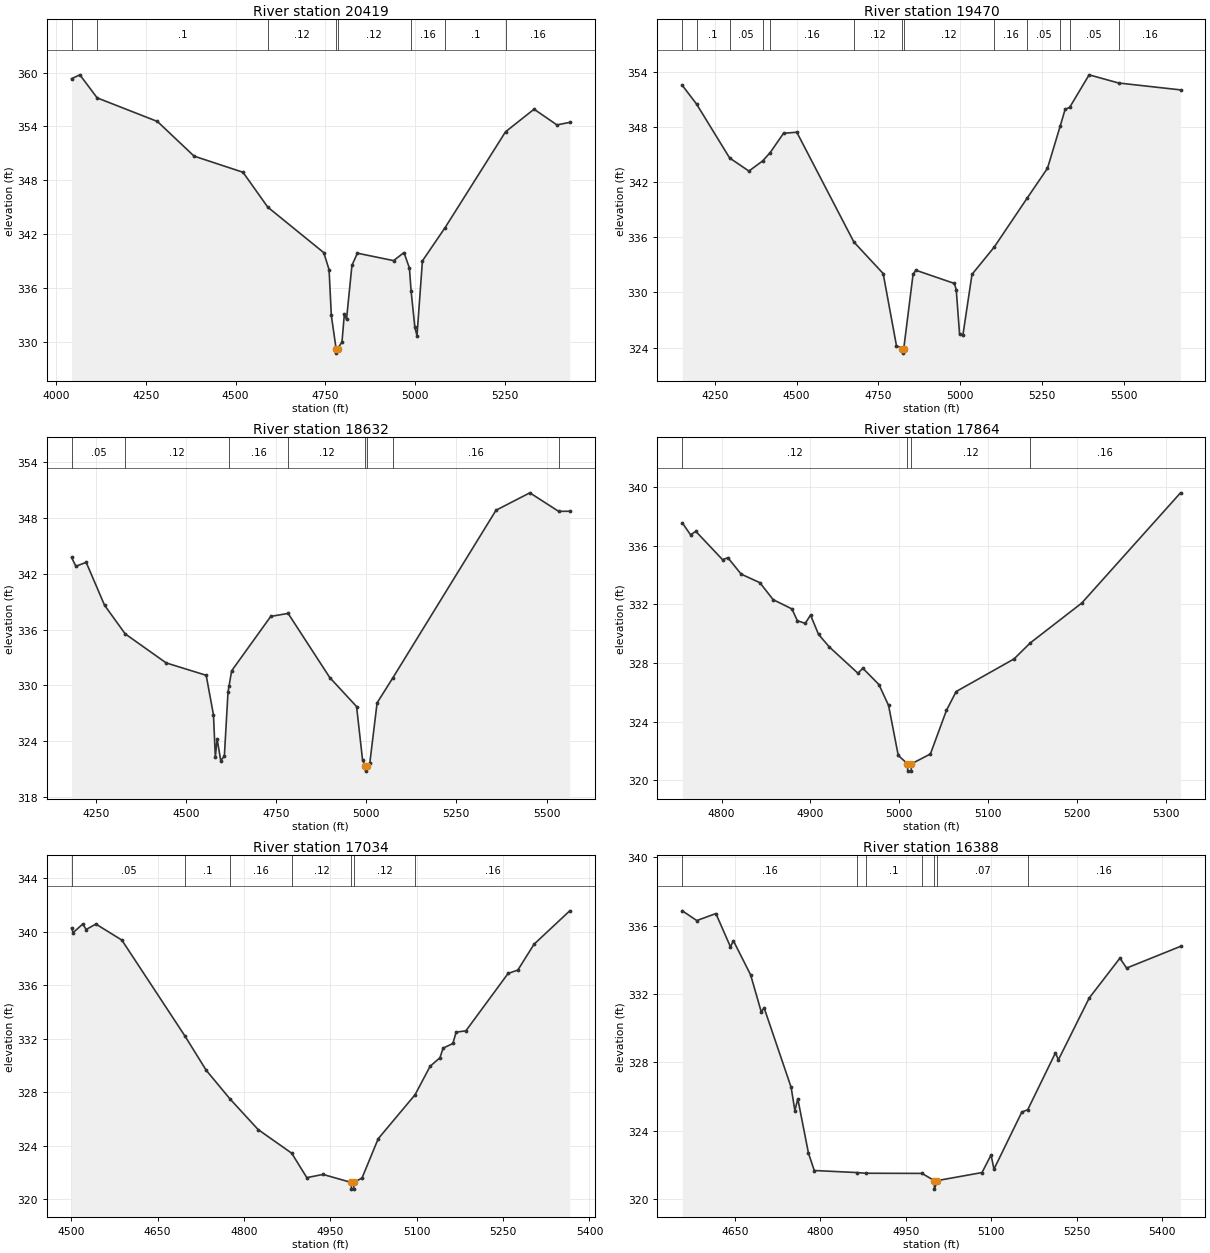
Type RM Length L Ch R = 1 ,20419   ,949,949,949
BEGIN DESCRIPTION:
NED BRANCH 35 0
END DESCRIPTION:
XS GIS Cut Line= 3
      3546404.54     10385016.92      3546692.11     10385441.64
      3547421.93     10385919.74
#Sta/Elev= 30
    4044  359.32  4067.1  359.75  4115.2  357.18  4282.8  354.55  4384.6  350.69
  4520.7  348.89  4589.7     345  4745.4  339.93  4760.1  338.03  4766.4  332.93
  4779.6  329.23  4779.8  328.73  4783.6  329.23    4796  329.96  4802.6  333.07
  4808.6  332.49  4823.7  338.51  4838.8  339.87  4939.5  339.04  4968.4  339.94
  4983.5  338.22  4988.2  335.67  4998.6  331.62  5004.6  330.67  5019.7  339.01
  5082.6  342.71  5250.8   353.4  5330.2  355.92  5393.7  354.17  5429.4  354.45
#Mann= 8 ,-1 , 0
    4044     .16       0  4115.2      .1       0  4589.7     .12       0
  4779.6     .07       0  4783.6     .12       0  4988.2     .16       0
  5082.6      .1       0  5250.8     .16       0
Bank Sta=4779.6,4783.6
XS Rating Curve= 0 ,0
Exp/Cntr=0.3,0.1

Type RM Length L Ch R = 1 ,19470   ,838,838,838
BEGIN DESCRIPTION:
NED BRANCH 33 0
END DESCRIPTION:
XS GIS Cut Line= 2
      3545977.49     10386572.51      3547477.26     10386305.19
#Sta/Elev= 30
  4150.4  352.55    4194  350.51  4295.1  344.64    4354  343.22  4396.2  344.33
    4419  345.23  4459.8  347.33  4500.4  347.45    4675  335.49  4764.5  332.06
  4805.2   324.2  4823.5  323.89  4823.7  323.39  4827.5  323.89    4856  331.98
  4864.4  332.42  4982.3  330.98    4988  330.31  4998.2  325.45  5008.3  325.34
  5036.2  331.97  5103.7  334.92  5204.8  340.27    5267  343.52  5305.9  348.12
  5320.9  349.93  5335.1  350.17  5394.3   353.7  5484.4  352.81  5673.8  352.06
#Mann= 13 ,-1 , 0
  4150.4     .16       0    4194      .1       0  4295.1     .05       0
  4396.2      .1       0    4419     .16       0    4675     .12       0
  4823.5     .07       0  4827.5     .12       0  5103.7     .16       0
  5204.8     .05       0  5305.9     .16       0  5335.1     .05       0
  5484.4     .16       0
Bank Sta=4823.5,4827.5
XS Rating Curve= 0 ,0
Exp/Cntr=0.3,0.1

Type RM Length L Ch R = 1 ,18632   ,768,768,768
BEGIN DESCRIPTION:
NED BRANCH 31 0
END DESCRIPTION:
XS GIS Cut Line= 2
      3546041.98     10387307.77      3547411.78     10387130.69
#Sta/Elev= 30
  4183.2  343.75  4195.2  342.81  4223.7  343.23  4274.6  338.62  4331.9  335.54
  4445.5  332.42  4556.4  331.09  4576.6  326.84  4581.8  322.32  4586.8  324.25
  4596.7  321.93  4606.8  322.39  4616.9  329.27    4620  329.98    4627  331.57
  4735.4  337.42  4783.6  337.74  4899.2  330.84  4973.4  327.73    4990  321.98
  4998.1  321.29  4998.3  320.79  5002.1  321.29  5010.2   321.7  5030.3  328.13
  5073.4  330.78    5360  348.83  5453.8   350.7  5533.6  348.71  5564.4  348.72
#Mann= 8 ,-1 , 0
  4183.2     .05       0  4331.9     .12       0    4620     .16       0
  4783.6     .12       0  4998.1     .07       0  5002.1     .12       0
  5073.4     .16       0  5533.6     .05       0
Bank Sta=4998.1,5002.1
XS Rating Curve= 0 ,0
Exp/Cntr=0.3,0.1

Type RM Length L Ch R = 1 ,17864   ,830,830,830
BEGIN DESCRIPTION:
NED BRANCH 3 0
END DESCRIPTION:
XS GIS Cut Line= 3
      3546764.32     10388074.98      3546914.33     10387974.98
      3547264.35     10387824.97
#Sta/Elev= 30
  4755.7  337.56  4764.9  336.75  4770.9  336.98    4801  335.05    4807  335.18
    4822  334.06    4843  333.48    4858  332.32  4879.1  331.69  4885.2  330.89
  4894.1   330.7  4900.1  331.27  4909.1  329.95  4921.3  329.09  4953.5   327.3
    4959  327.64  4977.1  326.53    4988   325.1  4998.9  321.69  5009.3  321.12
  5009.6  320.62  5013.4  320.62  5013.8  321.12  5035.1  321.79  5053.2  324.77
  5064.1  326.05  5129.4  328.28  5147.4  329.36  5205.6  332.09  5316.8  339.61
#Mann= 4 ,-1 , 0
  4755.7     .12       0  5009.3     .07       0  5013.8     .12       0
  5147.4     .16       0
Bank Sta=5009.3,5013.8
XS Rating Curve= 0 ,0
Exp/Cntr=0.3,0.1

Type RM Length L Ch R = 1 ,17034   ,646,646,646
BEGIN DESCRIPTION:
NED BRANCH 39 0
END DESCRIPTION:
XS GIS Cut Line= 2
       3547126.6     10389070.38      3547505.09     10388292.58
#Sta/Elev= 30
  4500.7  340.27  4503.4  339.94  4520.3  340.59  4525.9  340.17  4542.9  340.58
    4588  339.38    4698  332.17  4734.4  329.64  4775.8  327.49  4824.6   325.2
  4882.9  323.43  4909.2   321.6  4937.3  321.84  4986.3  321.24  4986.7  320.74
  4990.6  320.74  4990.9  321.24    5005  321.57  5033.1  324.51  5097.2  327.81
  5123.3  329.94  5140.3  330.57  5145.8  331.29  5162.8  331.64  5168.4  332.49
  5185.4  332.59  5258.6  336.88  5275.6  337.14  5303.7  339.07  5365.7  341.57
#Mann= 7 ,-1 , 0
  4500.7     .05       0    4698      .1       0  4775.8     .16       0
  4882.9     .12       0  4986.3     .07       0  4990.9     .12       0
  5097.2     .16       0
Bank Sta=4986.3,4990.9
XS Rating Curve= 0 ,0
Exp/Cntr=0.3,0.1

Type RM Length L Ch R = 1 ,16388   ,111,111,111
BEGIN DESCRIPTION:
NED BRANCH 27 0
END DESCRIPTION:
XS GIS Cut Line= 2
      3547852.31     10388969.66      3548005.09     10388108.51
#Sta/Elev= 30
  4557.6  336.87    4583   336.3  4616.5  336.71  4642.1  334.76  4647.2  335.12
  4677.5  333.12  4696.1  330.96  4701.2  331.19  4748.6  326.54  4755.2  325.17
  4760.3  325.87    4779  322.69  4789.2  321.67  4864.3  321.55  4879.4  321.51
  4978.4   321.5  4999.8  321.08  5000.2  320.58  5005.2  321.08  5083.7  321.55
  5099.6  322.58  5104.7  321.75  5153.6  325.09    5164  325.23  5212.7  328.56
  5217.8  328.15  5271.8  331.76  5325.8   334.1  5337.6  333.52  5432.2  334.79
#Mann= 7 ,-1 , 0
  4557.6     .16       0  4864.3     .12       0  4879.4      .1       0
  4978.4     .07       0  4999.8     .07       0  5005.2     .07       0
    5164     .16       0
Bank Sta=4999.8,5005.2
XS Rating Curve= 0 ,0
Exp/Cntr=0.3,0.1

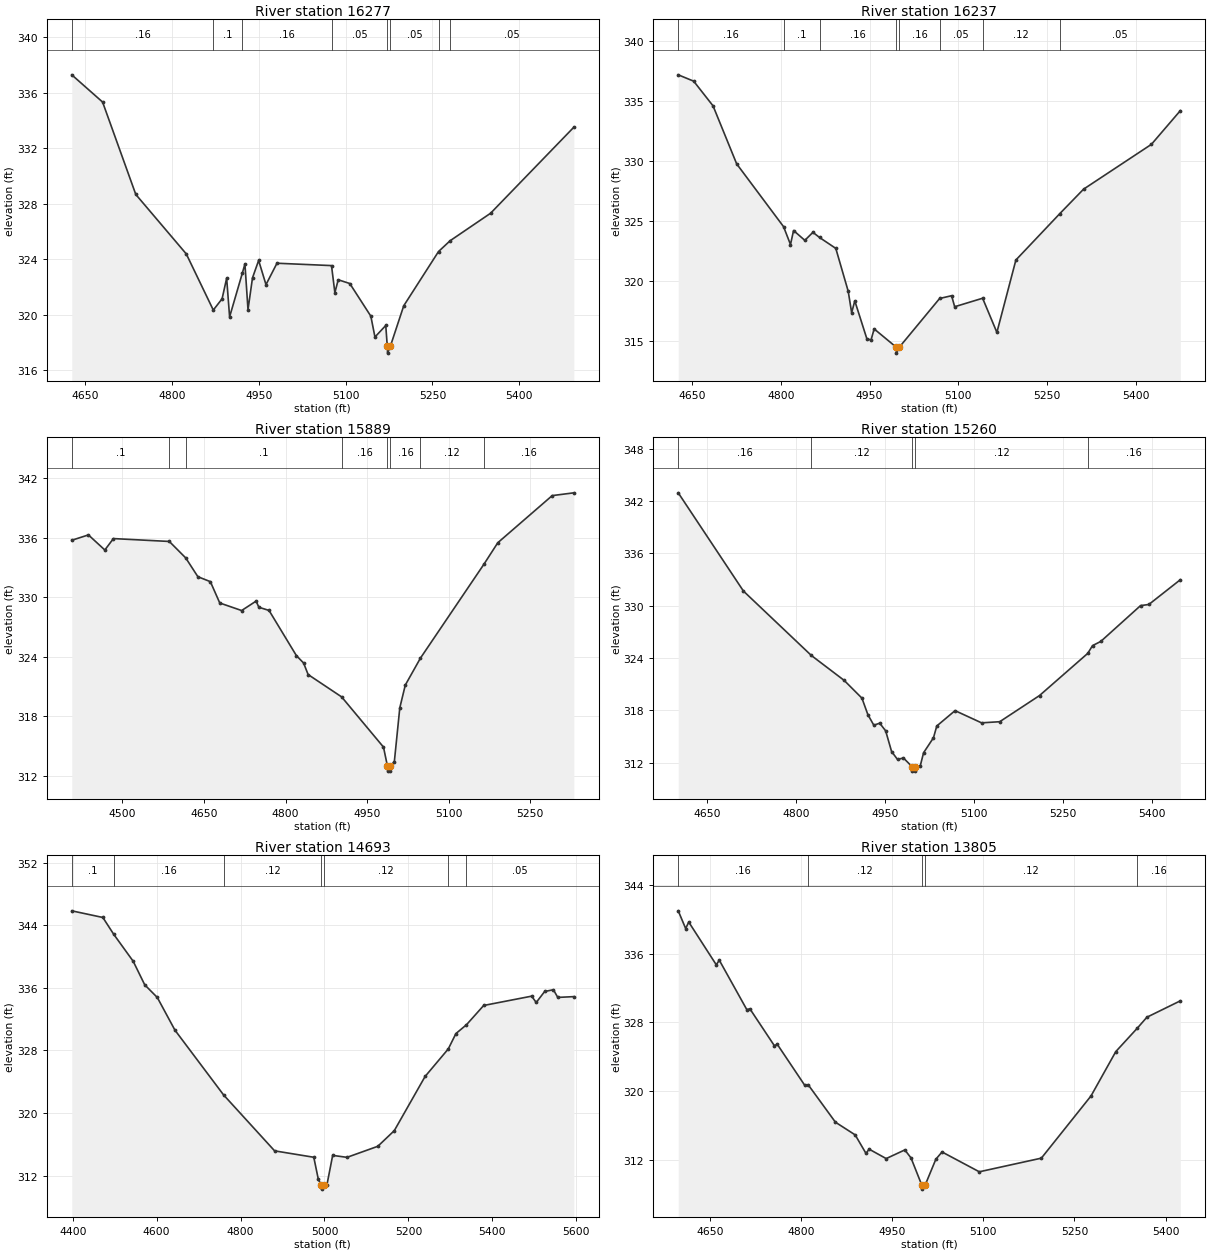
Type RM Length L Ch R = 1 ,16277   ,40,40,40
BEGIN DESCRIPTION:
NED BRANCH 45 0
END DESCRIPTION:
XS GIS Cut Line= 3
      3547939.12     10388893.24      3548008.56     10388625.92
      3548203.01     10388066.87
#Sta/Elev= 30
  4626.4  337.28  4679.7  335.32  4737.1  328.67  4824.4  324.39  4871.1  320.35
  4886.3  321.16  4894.2  322.64  4899.3  319.86  4921.2  322.99  4925.8  323.67
  4931.1  320.38  4938.9  322.67  4949.5  323.92  4962.2  322.18  4981.2  323.72
  5075.5  323.55  5081.3   321.6  5087.1  322.53  5107.1  322.26  5143.5  319.91
  5150.6  318.41  5169.3  319.24  5171.9  317.75  5172.4  317.25  5177.3  317.75
  5200.4  320.66  5260.5  324.56  5280.6  325.34  5350.6  327.32  5494.5  333.51
#Mann= 8 ,-1 , 0
  4626.4     .16       0  4871.1      .1       0  4921.2     .16       0
  5075.5     .05       0  5171.9     .07       0  5177.3     .05       0
  5260.5     .12       0  5280.6     .05       0
Bank Sta=5171.9,5177.3
XS Rating Curve= 0 ,0
Exp/Cntr=0.3,0.1

Type RM Length L Ch R = 1 ,16237   ,348,348,348
BEGIN DESCRIPTION:
NED BRANCH 25 0
END DESCRIPTION:
XS GIS Cut Line= 2
      3547970.83     10388886.03      3548220.06     10388075.48
#Sta/Elev= 30
  4626.9  337.19    4653  336.66  4685.7   334.6  4725.6  329.76  4804.8  324.52
  4816.5  323.03  4821.7   324.2  4840.7  323.38  4854.4  324.05  4865.5  323.62
    4893  322.71    4914  319.13  4919.8  317.34  4925.1  318.33  4945.4  315.18
  4952.5  315.06  4957.8  315.99    4995  314.47  4995.4  313.97  5000.4  314.47
  5068.4  318.53  5088.6  318.76  5093.8  317.84    5141  318.55  5165.1   315.7
  5197.2  321.74  5271.4  325.61  5311.5  327.65  5426.1  331.39  5474.9   334.2
#Mann= 8 ,-1 , 0
  4626.9     .16       0  4804.8      .1       0  4865.5     .16       0
    4995     .07       0  5000.4     .16       0  5068.4     .05       0
    5141     .12       0  5271.4     .05       0
Bank Sta=4995,5000.4
XS Rating Curve= 0 ,0
Exp/Cntr=0.3,0.1

Type RM Length L Ch R = 1 ,15889   ,629,629,629
BEGIN DESCRIPTION:
NED BRANCH 24 0
END DESCRIPTION:
XS GIS Cut Line= 3
      3548348.29     10389012.05       3548396.9     10388588.42
      3548417.74     10388091.87
#Sta/Elev= 30
  4406.8  335.74  4437.4  336.28  4467.6  334.76  4483.4  335.91  4586.2  335.62
  4616.4  333.96  4638.7  332.07  4661.7  331.57    4679  329.42  4719.2  328.66
  4745.8  329.61  4750.9  328.99  4769.6  328.67  4819.9  324.12  4833.2  323.37
  4841.5  322.21  4903.1  319.96  4980.1   314.9  4987.4  312.98  4987.8  312.48
  4992.4  312.48  4992.9  312.98  5000.1  313.45  5010.1  318.86  5020.2  321.15
  5048.1  323.87    5165  333.34  5190.3  335.49  5290.4  340.24  5330.2  340.52
#Mann= 8 ,-1 , 0
  4406.8      .1       0  4586.2     .16       0  4616.4      .1       0
  4903.1     .16       0  4987.4     .07       0  4992.9     .16       0
  5048.1     .12       0    5165     .16       0
Bank Sta=4987.4,4992.9
XS Rating Curve= 0 ,0
Exp/Cntr=0.3,0.1

Type RM Length L Ch R = 1 ,15260   ,567,567,567
BEGIN DESCRIPTION:
NED BRANCH 23 0
END DESCRIPTION:
XS GIS Cut Line= 3
      3549392.09     10388341.64      3548992.11     10388341.64
       3548592.1     10388141.64
#Sta/Elev= 30
  4601.1  342.95  4711.1  331.68  4825.7  324.29  4881.1  321.43  4911.1  319.39
  4921.1   317.5  4931.1  316.29  4941.1  316.52  4951.1  315.64  4961.1  313.27
  4971.1  312.36  4981.1  312.53  4995.8  311.52  4996.2  311.02  5000.9  311.02
  5001.4  311.52  5009.5  311.63  5015.1  313.13  5031.8  314.85  5037.4   316.2
  5068.2  317.96  5112.9  316.56  5143.6  316.69  5210.7  319.69  5292.1  324.53
  5300.2  325.42  5314.1   325.9  5381.2  330.01  5395.2  330.14  5448.3  332.98
#Mann= 5 ,-1 , 0
  4601.1     .16       0  4825.7     .12       0  4995.8     .07       0
  5001.4     .12       0  5292.1     .16       0
Bank Sta=4995.8,5001.4
XS Rating Curve= 0 ,0
Exp/Cntr=0.3,0.1

Type RM Length L Ch R = 1 ,14693   ,888,888,888
BEGIN DESCRIPTION:
NED BRANCH 22 0
END DESCRIPTION:
XS GIS Cut Line= 3
      3549633.54     10388122.43      3549237.72     10387855.08
      3548545.21     10387661.18
#Sta/Elev= 30
  4397.6  345.84  4471.7  344.99  4497.5  342.85  4544.1  339.39  4571.5  336.39
  4601.5  334.77  4643.5   330.6  4759.4  322.33  4881.1  315.18  4974.5  314.36
  4985.4  311.52  4992.5  310.79    4993  310.29  4998.1  310.79  5005.7   310.8
  5019.5   314.6  5053.7  314.35  5127.1  315.76  5166.4  317.76  5239.8  324.68
  5295.1   328.2  5313.3  330.16  5338.5  331.29  5379.5  333.75  5493.8  334.94
  5504.7  334.13  5524.9  335.54  5545.7  335.76  5556.1  334.78  5594.4  334.88
#Mann= 7 ,-1 , 0
  4397.6      .1       0  4497.5     .16       0  4759.4     .12       0
  4992.5     .07       0  4998.1     .12       0  5295.1     .16       0
  5338.5     .05       0
Bank Sta=4992.5,4998.1
XS Rating Curve= 0 ,0
Exp/Cntr=0.3,0.1

Type RM Length L Ch R = 1 ,13805   ,453,453,453
BEGIN DESCRIPTION:
NED BRANCH 21 0
END DESCRIPTION:
XS GIS Cut Line= 2
      3549959.95     10387896.75      3549793.28     10387087.74
#Sta/Elev= 30
  4598.2     341  4610.4  338.94  4615.5  339.69  4660.7  334.72  4665.8  335.24
    4711  329.49  4716.1  329.58  4756.2   325.3  4761.3  325.43  4806.5  320.65
  4811.9  320.74  4856.8  316.37  4889.3  314.89  4907.1  312.73  4912.2  313.23
  4940.3  312.13    4971  313.14  4981.2   312.2  4998.7  309.07  4999.2  308.57
  5004.6  309.07    5022  312.05  5032.2   312.9  5093.5  310.59  5195.6  312.18
  5277.3  319.43  5318.1   324.6  5353.5  327.33  5369.2   328.6  5424.2  330.51
#Mann= 5 ,-1 , 0
  4598.2     .16       0  4811.9     .12       0  4998.7     .07       0
  5004.6     .12       0  5353.5     .16       0
Bank Sta=4998.7,5004.6
XS Rating Curve= 0 ,0
Exp/Cntr=0.3,0.1

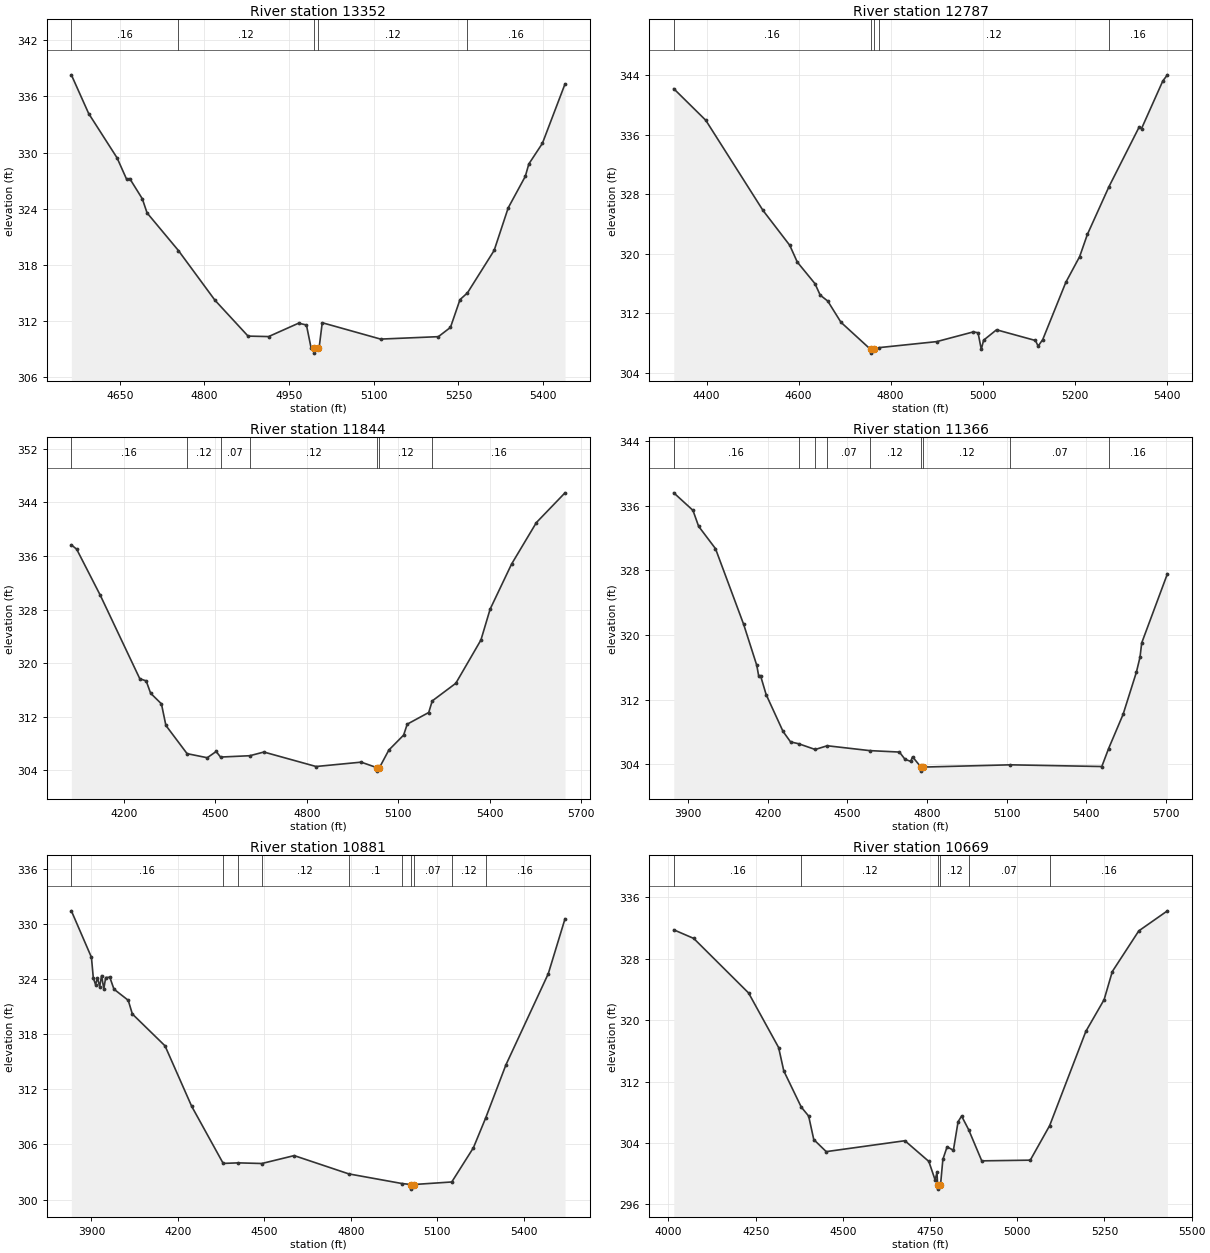
Type RM Length L Ch R = 1 ,13352   ,565,565,565
BEGIN DESCRIPTION:
NED BRANCH 20 0
END DESCRIPTION:
XS GIS Cut Line= 3
      3550042.12     10387891.61      3550242.11     10387491.64
      3550392.11     10387091.63
#Sta/Elev= 30
  4564.3  338.31    4595  334.17  4645.3  329.43  4662.1  327.16  4667.7  327.22
    4690  325.06  4698.4  323.55  4753.9  319.53  4818.6  314.22  4877.3  310.38
  4913.7  310.33  4966.8  311.76  4980.7  311.57  4989.1  309.07  4994.1  309.06
  4994.6  308.56  5000.9  309.06  5003.1   309.1  5008.7  311.81  5112.1  310.06
  5214.4  310.32  5235.8  311.31  5252.7  314.28  5265.9     315  5313.2  319.54
  5338.1  324.09  5368.4  327.46  5374.6  328.78  5398.6  330.98  5438.7  337.33
#Mann= 5 ,-1 , 0
  4564.3     .16       0  4753.9     .12       0  4994.1     .07       0
  5000.9     .12       0  5265.9     .16       0
Bank Sta=4994.1,5000.9
XS Rating Curve= 0 ,0
Exp/Cntr=0.3,0.1

Type RM Length L Ch R = 1 ,12787   ,943,943,943
BEGIN DESCRIPTION:
NED BRANCH 18 0
END DESCRIPTION:
XS GIS Cut Line= 3
      3550501.63     10388143.25      3550782.86     10387608.56
      3550742.11     10387141.68
#Sta/Elev= 30
  4328.8   342.2  4398.4  337.95  4522.7  325.82  4580.9  321.12  4597.2  318.87
  4635.7  315.96    4647  314.42  4663.4  313.62  4692.2  310.76  4756.6  307.11
  4757.1  306.61  4763.4  307.11  4774.8  307.35  4900.2  308.16    4980  309.47
  4990.1  309.35  4997.1  307.11  5002.1  308.35  5030.2  309.75  5114.8  308.31
  5120.6  307.55  5130.6  308.43  5180.8  316.14  5210.9  319.61  5227.6  322.58
  5274.6  329.02  5340.3  337.06  5345.3  336.83  5391.6  343.25  5401.6  344.07
#Mann= 5 ,-1 , 0
  4328.8     .16       0  4756.6     .07       0  4763.4     .16       0
  4774.8     .12       0  5274.6     .16       0
Bank Sta=4756.6,4763.4
XS Rating Curve= 0 ,0
Exp/Cntr=0.3,0.1

Type RM Length L Ch R = 1 ,11844   ,478,478,478
BEGIN DESCRIPTION:
NED BRANCH 17 0
END DESCRIPTION:
XS GIS Cut Line= 3
      3551022.46     10388285.62      3551525.92     10387605.08
      3551435.64     10386837.69
#Sta/Elev= 30
  4027.9  337.67  4045.3  337.03    4123  330.13  4252.4  317.69  4273.3  317.37
  4287.9  315.53  4323.4  313.94    4338  310.72  4407.5  306.51  4473.7   305.9
  4502.9  306.83  4517.2     306  4613.4   306.2  4659.4  306.75  4830.6  304.59
  4978.6  305.24  5031.2   304.4  5031.7   303.9  5038.2   304.4  5069.2  307.04
  5117.8  309.28  5129.6  310.91  5200.1  312.65  5211.6  314.38  5288.9  317.01
  5371.3  323.47  5401.5  328.08    5472  334.82  5553.2     341  5647.1  345.44
#Mann= 7 ,-1 , 0
  4027.9     .16       0  4407.5     .12       0  4517.2     .07       0
  4613.4     .12       0  5031.2     .07       0  5038.2     .12       0
  5211.6     .16       0
Bank Sta=5031.2,5038.2
XS Rating Curve= 0 ,0
Exp/Cntr=0.3,0.1

Type RM Length L Ch R = 1 ,11366   ,485,485,485
BEGIN DESCRIPTION:
NED BRANCH 16 0
END DESCRIPTION:
XS GIS Cut Line= 3
      3551071.03     10388382.89      3551768.97     10387688.42
      3551710.05       10386815.
#Sta/Elev= 30
  3845.7  337.59    3918  335.42  3939.3  333.45  4002.9  330.68    4109  321.31
  4158.5  316.23  4165.5  314.95  4172.6  314.96  4193.8  312.61  4257.5  308.05
  4285.7  306.76  4316.3  306.53  4378.5  305.82  4424.1  306.28  4583.7  305.68
  4695.9   305.5  4717.1   304.6  4738.3  304.35  4745.4  304.91  4777.2  303.64
  4777.7  303.14  4784.2  303.64  5113.9  303.92  5458.5  303.71  5483.9  305.92
  5538.7  310.17  5588.8  315.39  5602.4  317.24  5608.8  319.01  5705.7  327.57
#Mann= 9 ,-1 , 0
  3845.7     .16       0  4316.3     .07       0  4378.5     .12       0
  4424.1     .07       0  4583.7     .12       0  4777.2     .07       0
  4784.2     .12       0  5113.9     .07       0  5483.9     .16       0
Bank Sta=4777.2,4784.2
XS Rating Curve= 0 ,0
Exp/Cntr=0.3,0.1

Type RM Length L Ch R = 1 ,10881   ,212,212,212
BEGIN DESCRIPTION:
NED BRANCH 13 0
END DESCRIPTION:
XS GIS Cut Line= 4
      3551272.42     10388559.97      3551855.78     10387851.61
      3552282.86     10387594.67      3552571.02     10387521.76
#Sta/Elev= 30
  3830.1  331.44  3899.8  326.38  3906.3  324.14  3914.1   323.4  3920.6  324.14
  3928.5  323.19  3934.9  324.39  3942.8  322.95  3949.3  324.18  3963.6  324.21
    3978  322.91  4027.5   321.7  4041.8  320.21  4155.2  316.74  4247.7  310.16
  4357.1  303.94  4409.4     304  4491.2  303.93  4603.5  304.79  4792.9   302.8
  4977.5  301.75  5009.6  301.64  5010.1  301.14  5017.7  301.64  5150.4  301.92
  5225.4  305.64  5267.7  308.86  5338.2  314.66  5485.3  324.59  5543.4  330.57
#Mann= 10 ,-1 , 0
  3830.1     .16       0  4357.1     .12       0  4409.4     .16       0
  4491.2     .12       0  4792.9      .1       0  4977.5     .07       0
  5009.6     .07       0  5017.7     .07       0  5150.4     .12       0
  5267.7     .16       0
Bank Sta=5009.6,5017.7
XS Rating Curve= 0 ,0
Exp/Cntr=0.3,0.1

Type RM Length L Ch R = 1 ,10669   ,84,84,84
BEGIN DESCRIPTION:
NED BRANCH 14 0
END DESCRIPTION:
XS GIS Cut Line= 3
      3551434.07      10388553.4      3551777.82     10388070.76
      3552533.07     10387744.36
#Sta/Elev= 30
  4015.2  331.75  4072.4  330.63  4229.7  323.53  4315.8  316.43  4330.6  313.39
  4380.7  308.68  4401.9  307.51  4416.6  304.45  4452.3  302.88  4677.8   304.3
  4746.4  301.61  4764.4  299.21  4769.9  300.17  4771.7   298.5  4772.2     298
  4779.9   298.5  4786.7  301.87  4798.8   303.5  4816.9  303.06  4830.3  306.77
  4840.4  307.51  4860.4  305.76  4898.2  301.68  5037.3  301.77  5092.9  306.27
  5196.6  318.53    5249  322.66  5272.5  326.32  5348.4  331.61  5430.5  334.22
#Mann= 6 ,-1 , 0
  4015.2     .16       0  4380.7     .12       0  4771.7     .07       0
  4779.9     .12       0  4860.4     .07       0  5092.9     .16       0
Bank Sta=4771.7,4779.9
XS Rating Curve= 0 ,0
Exp/Cntr=0.3,0.1

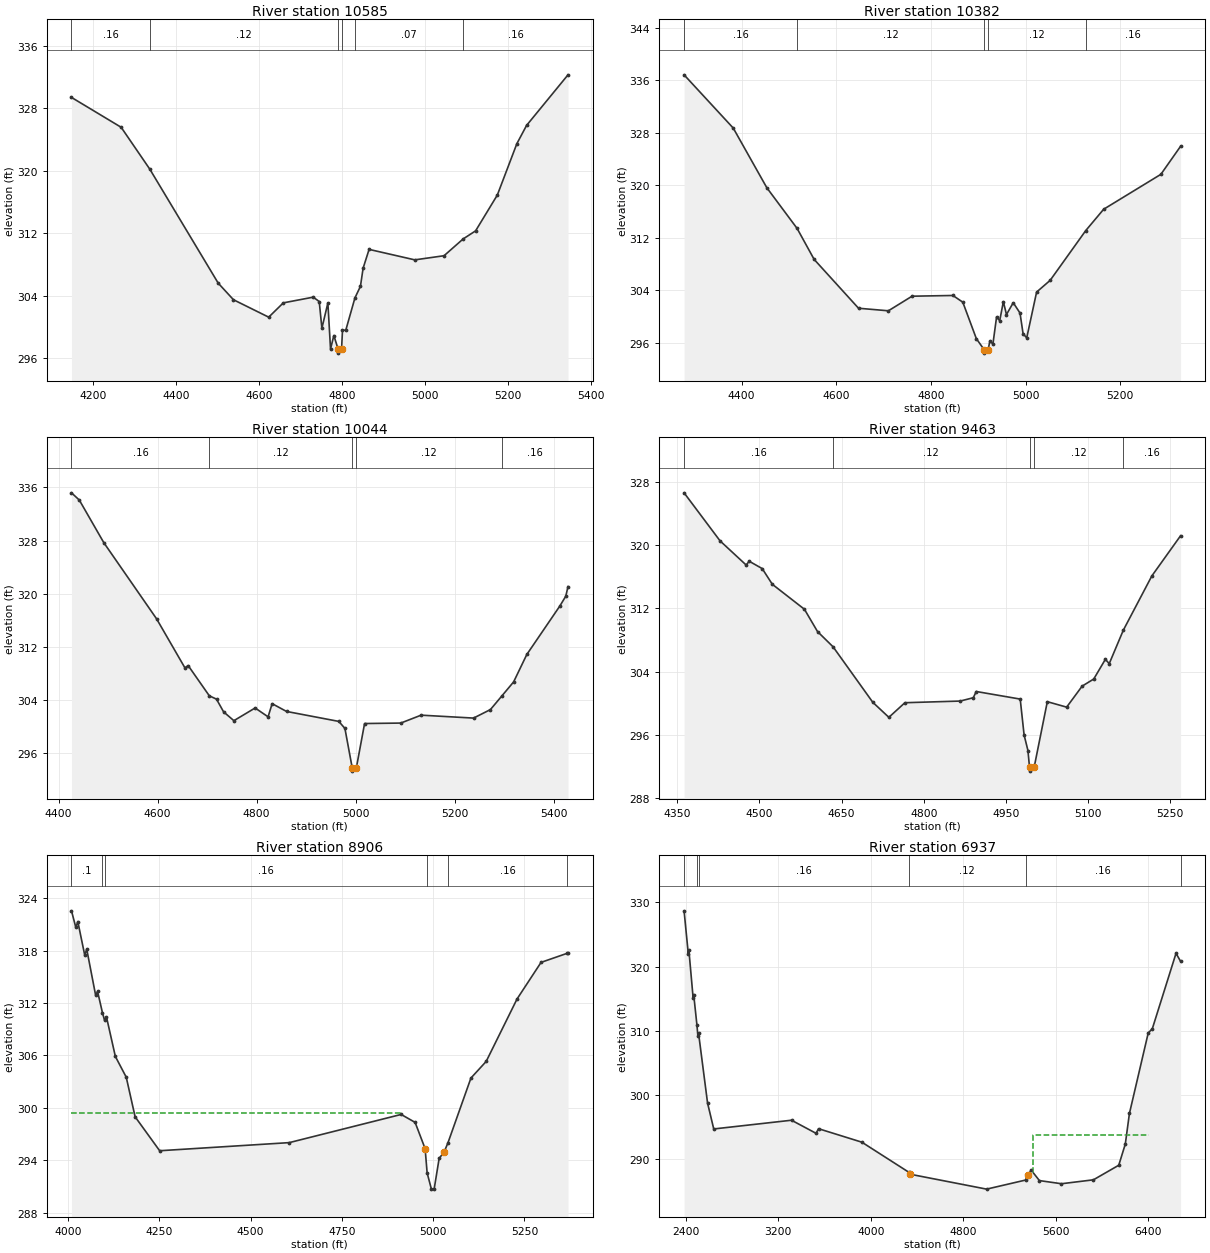
Type RM Length L Ch R = 1 ,10585   ,203,203,203
BEGIN DESCRIPTION:
Mapping XS 2e716018
END DESCRIPTION:
XS GIS Cut Line= 4
      3551487.91     10388504.78      3552069.49     10388036.04
      3552409.77     10387888.47      3552454.06     10387825.44
#Sta/Elev= 30
    4149  329.37  4268.5  325.55  4337.5  320.19  4502.1  305.61  4538.8  303.49
  4623.6  301.26  4658.8  303.09  4730.8  303.82  4745.2  303.26  4751.6  299.84
    4766  303.08  4772.4  297.19  4780.4  298.91  4790.7  297.16  4791.2  296.66
  4798.9  297.16  4801.2  299.57  4809.2  299.61  4831.1  303.72  4844.4  305.21
  4850.8  307.52  4865.2  309.93  4975.2  308.59  5045.6  309.12  5091.6  311.27
  5121.5   312.3  5173.8  316.88  5220.8  323.45  5244.2  325.79  5343.9  332.26
#Mann= 6 ,-1 , 0
    4149     .16       0  4337.5     .12       0  4790.7     .07       0
  4798.9     .12       0  4831.1     .07       0  5091.6     .16       0
Bank Sta=4790.7,4798.9
XS Rating Curve= 0 ,0
Exp/Cntr=0.3,0.1

Type RM Length L Ch R = 1 ,10382   ,338,338,338
BEGIN DESCRIPTION:
NED BRANCH 12 1
END DESCRIPTION:
XS GIS Cut Line= 3
      3551782.88     10388747.42      3552112.72     10388306.47
      3552434.73     10387925.61
#Sta/Elev= 30
  4278.3  336.81  4382.3   328.7  4453.2  319.63  4517.2  313.44  4553.2  308.73
    4647   301.3  4710.1  300.91  4760.1  303.13  4846.5  303.24  4867.4  302.22
    4896  296.68  4912.7  294.97  4913.2  294.47  4920.9  294.97  4924.5  296.27
  4931.1  295.88  4938.8  299.98  4945.4   299.4  4953.1   302.3  4959.7  300.34
    4974  302.14  4988.3  300.57  4994.8  297.43  5002.5  296.79  5023.4  303.76
    5052  305.54  5127.2  313.11  5165.1  316.36    5286  321.67  5327.7  325.94
#Mann= 5 ,-1 , 0
  4278.3     .16       0  4517.2     .12       0  4912.7     .07       0
  4920.9     .12       0  5127.2     .16       0
Bank Sta=4912.7,4920.9
XS Rating Curve= 0 ,0
Exp/Cntr=0.3,0.1

Type RM Length L Ch R = 1 ,10044   ,581,581,581
BEGIN DESCRIPTION:
NED BRANCH 12 0
END DESCRIPTION:
XS GIS Cut Line= 3
       3551918.3     10388820.34      3552171.75     10388518.28
      3552757.87     10388354.41
#Sta/Elev= 30
  4426.1  335.19  4441.9   334.1  4491.3   327.7    4598  316.23  4655.2  308.86
  4661.8   309.2  4704.5  304.65    4719  304.15  4733.3  302.24  4754.1  300.91
    4797  302.82  4823.2  301.49  4831.4  303.47  4860.4   302.3  4966.1   300.8
  4978.4  299.74  4993.1  293.82  4993.6  293.32  5001.5  293.82  5018.1  300.48
  5091.2  300.55  5132.3  301.74  5238.2   301.3  5272.3  302.58  5295.5  304.64
  5319.2  306.75  5345.8  310.87  5412.6  318.17  5424.5  319.64    5429  321.08
#Mann= 5 ,-1 , 0
  4426.1     .16       0  4704.5     .12       0  4993.1     .07       0
  5001.5     .12       0  5295.5     .16       0
Bank Sta=4993.1,5001.5
XS Rating Curve= 0 ,0
Exp/Cntr=0.3,0.1

Type RM Length L Ch R = 1 ,9463    ,557,557,557
BEGIN DESCRIPTION:
NED BRANCH 29 0
END DESCRIPTION:
XS GIS Cut Line= 3
      3552112.72     10389150.22      3552628.91     10388936.44
      3552873.14     10388688.41
#Sta/Elev= 30
  4362.3  326.63    4428  320.55  4475.7  317.49  4481.2  317.97    4505  317.04
  4523.5  315.05  4582.1  311.89    4606  309.07  4634.5  307.13    4707  300.11
  4736.3  298.21  4765.6  300.06  4866.6  300.27  4890.5  300.69  4895.9  301.48
  4976.2  300.52  4983.3  295.98  4990.3  294.01  4993.2   291.9  4993.7   291.4
  5001.7   291.9  5025.7  300.19    5061   299.5  5089.3  302.16  5110.5  303.06
  5131.7  305.55  5138.8  305.01  5164.5  309.24  5216.6  316.11  5269.1   321.2
#Mann= 5 ,-1 , 0
  4362.3     .16       0  4634.5     .12       0  4993.2     .07       0
  5001.7     .12       0  5164.5     .16       0
Bank Sta=4993.2,5001.7
XS Rating Curve= 0 ,0
Exp/Cntr=0.3,0.1

Type RM Length L Ch R = 1 ,8906    ,1969,1969,1969
BEGIN DESCRIPTION:
NED BRANCH 19 0
END DESCRIPTION:
XS GIS Cut Line= 3
      3552397.61     10389801.67      3552960.11     10389579.44
      3553178.85     10388857.25
#Sta/Elev= 30
  4009.8  322.58  4021.7  320.67  4027.1  321.35  4046.1  317.49  4051.5  318.19
  4075.8  312.92  4081.2  313.34  4094.5  310.91  4100.2  310.05  4105.6  310.41
  4129.9  305.89  4159.7  303.51    4184  298.97  4251.2  295.08    4606  296.01
  4912.4  299.24  4950.6  298.33    4978  295.32  4983.5  292.54  4995.2  290.68
  5002.7  290.68  5016.4   294.2  5030.3  294.96  5040.7  296.01  5103.4  303.41
  5145.2  305.32  5229.6  312.47  5295.4  316.67  5366.2   317.7  5369.2   317.7
#Mann= 6 ,-1 , 0
  4009.8      .1       0  4094.5     .12       0  4100.2     .16       0
  4983.5     .12       0  5040.7     .16       0  5366.2     .05       0
#XS Ineff= 2 , 0
       0  4912.5  299.44               0
Permanent Ineff=
       T       F
Bank Sta=4978,5030.3
XS Rating Curve= 0 ,0
Exp/Cntr=0.3,0.1

Type RM Length L Ch R = 1 ,6937    ,693,693,693
BEGIN DESCRIPTION:
NED BRANCH 7 3
END DESCRIPTION:
XS GIS Cut Line= 3
      3552362.93     10389815.54      3553217.06     10389607.22
      3555692.69     10387256.58
#Sta/Elev= 30
  2385.2  328.69  2421.6  322.01  2426.7  322.58  2463.3  315.16  2468.4  315.64
  2496.5  310.88  2504.9  309.14  2510.1  309.67  2588.3  298.75  2641.7  294.72
  3314.2  296.08  3526.5  294.04  3547.6  294.76  3922.5  292.66  4325.8  288.01
    4340  287.67  5001.1  285.35  5337.4  286.76  5358.5  287.58  5386.8   288.3
  5457.6  286.68  5648.5  286.19  5924.4   286.8  6143.6  289.07  6200.2  292.37
  6235.8  297.13  6398.4  309.67  6433.6  310.32  6638.7  322.07  6678.2  320.82
#Mann= 6 ,-1 , 0
  2385.2      .1       0  2496.5     .12       0  2510.1     .16       0
  4325.8     .12       0  5337.4     .16       0  6678.2     .05       0
#XS Ineff= 1 ,-1
 5403.21 6403.21293.8257
Permanent Ineff=
       T
Bank Sta=4340,5358.5
XS Rating Curve= 0 ,0
Exp/Cntr=0.3,0.1