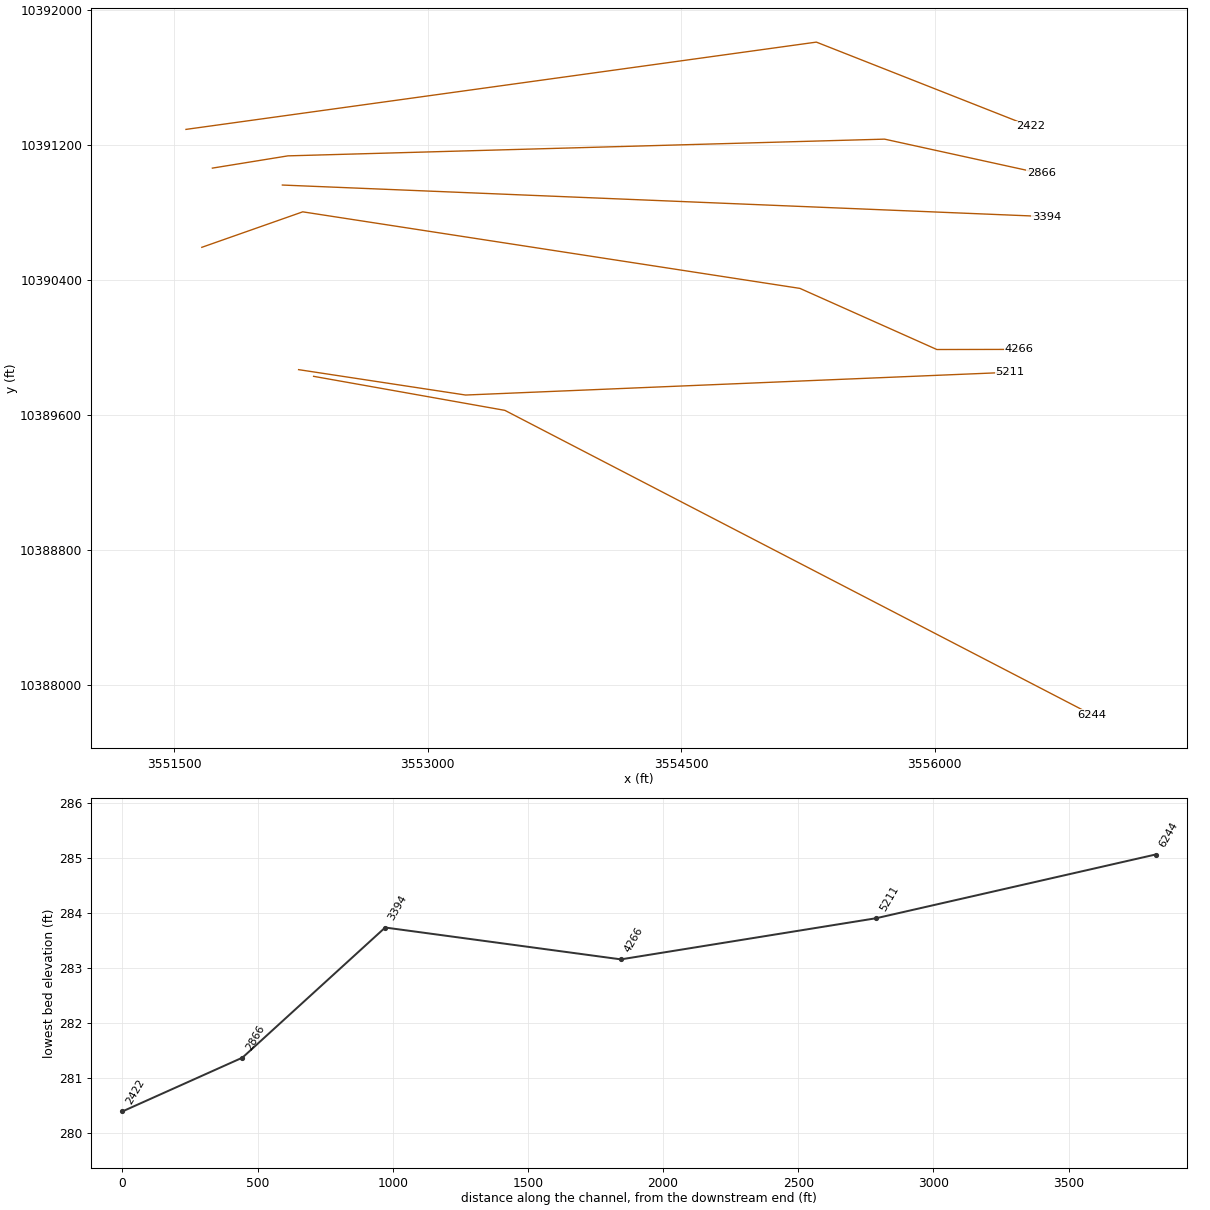
HEC-RAS study NED BRANCH.prj: NED BRANCH Base Level Engineering

--- NED BRANCH.g01 (geometry) --- (continued)

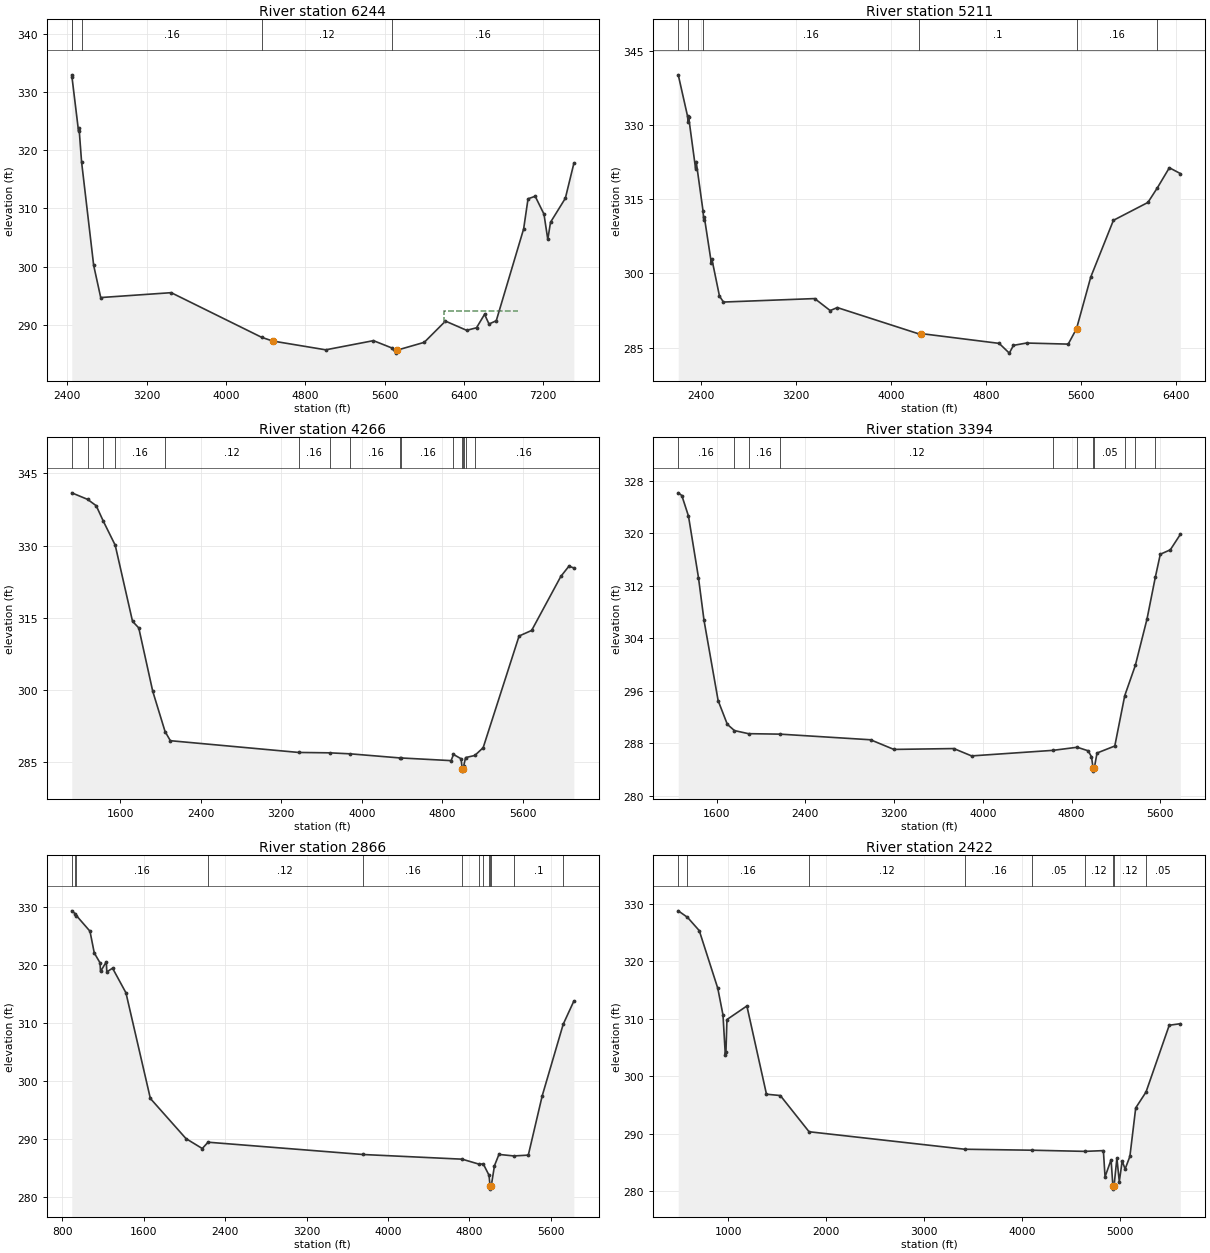
Type RM Length L Ch R = 1 ,6244    ,1033,1033,1033
BEGIN DESCRIPTION:
NED BRANCH 7 2
END DESCRIPTION:
XS GIS Cut Line= 3
      3552324.66     10389829.45      3553456.64     10389628.05
      3556931.67     10387826.31
#Sta/Elev= 30
    2445  333.04  2446.8   332.7  2513.3  323.33  2518.3  323.88    2544  318.02
  2665.9   300.2    2737  294.65  3447.9  295.49  4359.7   287.8  4470.4  287.16
  5006.6  285.64  5487.8  287.22  5673.5  285.96  5713.9  285.07  5723.7  285.57
  6000.2  286.93  6214.2  290.59  6428.2     289  6527.4  289.44  6608.5  291.76
  6653.5  290.09  6726.5  290.65  7002.7  306.48  7047.1  311.67  7119.2  312.11
  7207.7  309.03  7246.3  304.68    7274  307.63  7423.3  311.76  7509.1  317.77
#Mann= 5 ,-1 , 0
    2445     .16       0  2446.8      .1       0    2544     .16       0
  4359.7     .12       0  5673.5     .16       0
#XS Ineff= 1 ,-1
 6194.64 6944.64  292.37
Permanent Ineff=
       T
Bank Sta=4470.4,5723.7
XS Rating Curve= 0 ,0
Exp/Cntr=0.3,0.1

Type RM Length L Ch R = 1 ,5211    ,945,945,945
BEGIN DESCRIPTION:
NED BRANCH 7 1
END DESCRIPTION:
XS GIS Cut Line= 3
       3552235.9     10389869.04      3553224.27     10389718.77
      3556444.23     10389853.41
#Sta/Elev= 30
  2209.6  340.13  2288.4  331.73  2291.9  330.56    2297  331.61  2355.5  321.19
  2360.6  322.61  2418.2  312.62  2424.2  310.75  2429.2  311.36  2487.8  302.17
  2492.8  302.88  2556.5  295.42  2590.1  294.23  3357.3  294.93  3487.4  292.51
  3547.5  293.11  4238.1  287.76  4248.1  287.87  4908.6  285.88    4994  283.91
  5028.8  285.48  5138.9  285.95  5489.2  285.73  5559.2  288.84  5679.3   299.3
  5869.5  310.74  6159.7  314.35  6239.8  317.33  6339.9  321.36  6432.1  320.19
#Mann= 6 ,-1 , 0
  2209.6     .16       0  2288.4      .1       0  2418.2     .16       0
  4238.1      .1       0  5559.2     .16       0  6239.8     .16       0
Bank Sta=4248.1,5559.2
XS Rating Curve= 0 ,0
Exp/Cntr=0.3,0.1

Type RM Length L Ch R = 1 ,4266    ,872,872,872
BEGIN DESCRIPTION:
NED BRANCH 7 0
END DESCRIPTION:
XS GIS Cut Line= 5
      3551663.03     10390593.01      3552260.29       10390803.
        3555203.     10390349.88      3556013.31     10389988.13
      3556501.13     10389988.89
#Sta/Elev= 30
  1120.1  340.96  1277.1   339.6  1362.9  338.28  1434.4  335.03  1551.5  330.08
  1723.3  314.28  1785.4   312.9  1924.2  299.74  2046.4  291.39    2099  289.48
  3372.9  287.04    3680  286.96  3886.4  286.75  4384.1  285.89  4394.1  285.89
  4887.1  285.34  4910.7  286.62  4985.4  285.74  4997.6  283.66  4998.1  283.16
  5008.7  283.66  5012.1  284.24  5030.7  285.97  5122.2  286.41  5205.3  288.03
  5561.9  311.22  5686.8  312.38  5976.8  323.61  6056.8  325.72  6105.8  325.36
#Mann= 16 ,-1 , 0
  1120.1     .05       0  1277.1      .1       0  1434.4     .05       0
  1551.5     .16       0  2046.4     .12       0  3372.9     .16       0
    3680     .12       0  3886.4     .16       0  4384.1     .12       0
  4394.1     .16       0  4910.7     .12       0  4997.6     .07       0
  5008.7     .12       0  5012.1     .07       0  5030.7     .12       0
  5122.2     .16       0
Bank Sta=4997.6,5008.7
XS Rating Curve= 0 ,0
Exp/Cntr=0.3,0.1

Type RM Length L Ch R = 1 ,3394    ,528,528,528
BEGIN DESCRIPTION:
NED BRANCH 32 0
END DESCRIPTION:
XS GIS Cut Line= 2
      3552139.82     10390961.56      3556662.27     10390774.89
#Sta/Elev= 30
  1254.1  326.17  1286.4  325.76  1346.5  322.62  1436.5  313.25  1486.6  306.72
  1613.8  294.49  1696.8  290.87  1761.1  289.92  1887.7  289.45    2172  289.38
  2987.9  288.52    3198  287.05  3738.5  287.18  3898.6  286.06  4633.7  286.91
    4851  287.38  4949.5  286.84  4979.6  285.93    4994  284.24  4994.5  283.74
  5005.2  284.24  5029.6   286.5  5189.7  287.57  5279.5  295.25  5374.7  299.85
    5480  306.92  5555.2  313.31  5600.1  316.81  5690.2  317.48  5780.4  319.83
#Mann= 11 ,-1 , 0
  1254.1     .16       0  1761.1     .12       0  1887.7     .16       0
    2172     .12       0  4633.7     .05       0    4851     .12       0
    4994    .035       0  5005.2     .05       0  5279.5     .16       0
  5374.7      .1       0  5555.2     .05       0
Bank Sta=4994,5005.2
XS Rating Curve= 0 ,0
Exp/Cntr=0.3,0.1

Type RM Length L Ch R = 1 ,2866    ,444,444,444
BEGIN DESCRIPTION:
NED BRANCH 44 0
END DESCRIPTION:
XS GIS Cut Line= 4
      3551725.53     10391061.75      3552172.69     10391134.27
      3555703.94     10391233.23      3556631.01      10391030.1
#Sta/Elev= 30
   891.2  329.41   925.4  328.91   937.4  328.57  1070.1  325.89  1112.4  322.14
    1169  320.43    1174  318.94  1230.6  320.61  1235.7  318.87  1292.2  319.51
  1423.6  315.26  1663.7  297.02  2013.9  290.09  2173.9  288.38  2230.5  289.47
    3750  287.35    4728  286.54  4890.4   285.7  4936.4   285.7  4992.4  283.76
  5002.4  281.87  5002.9  281.37  5013.6  281.87  5045.8  285.42  5089.7  287.36
  5235.9   287.1  5378.3  287.24  5514.9  297.47  5721.5  309.84  5825.9  313.83
#Mann= 13 ,-1 , 0
   891.2     .05       0   925.4      .1       0   937.4     .16       0
  2230.5     .12       0    3750     .16       0    4728     .05       0
  4890.4     .16       0  4936.4     .05       0  4992.4     .16       0
  5002.4     .07       0  5013.6     .16       0  5235.9      .1       0
  5721.5     .05       0
Bank Sta=5002.4,5013.6
XS Rating Curve= 0 ,0
Exp/Cntr=0.3,0.1

Type RM Length L Ch R = 1 ,2422    ,0,0,0
BEGIN DESCRIPTION:
NED BRANCH 1 0
END DESCRIPTION:
XS GIS Cut Line= 3
      3551569.29     10391290.92      3555300.17     10391807.47
      3556567.33     10391308.31
#Sta/Elev= 30
   489.9  328.74   584.5  327.61   704.7   325.3   893.9  315.28     947  310.65
   970.7  303.76   977.3  304.25   987.4  309.85  1191.1  312.21  1391.2  296.88
  1532.6  296.65  1826.3  290.36  3416.8  287.32  4105.7  287.15    4644  286.95
  4832.5  287.08  4849.6  282.52  4911.1   285.5  4929.9  280.89  4930.4  280.39
  4941.1  280.89  4970.6  285.77    4995  281.71  5024.8  285.27  5054.5  283.88
  5103.3  286.08  5162.8   294.5    5268  297.26  5505.2  308.86  5618.3  309.13
#Mann= 9 ,-1 , 0
   489.9     .05       0   584.5     .16       0  1826.3     .12       0
  3416.8     .16       0  4105.7     .05       0    4644     .12       0
  4929.9     .07       0  4941.1     .12       0    5268     .05       0
Bank Sta=4929.9,4941.1
XS Rating Curve= 0 ,0
Exp/Cntr=0.3,0.1

Chan Stop Cuts=-1
Use User Specified Reach Order=0
Composite Channel Slope=5