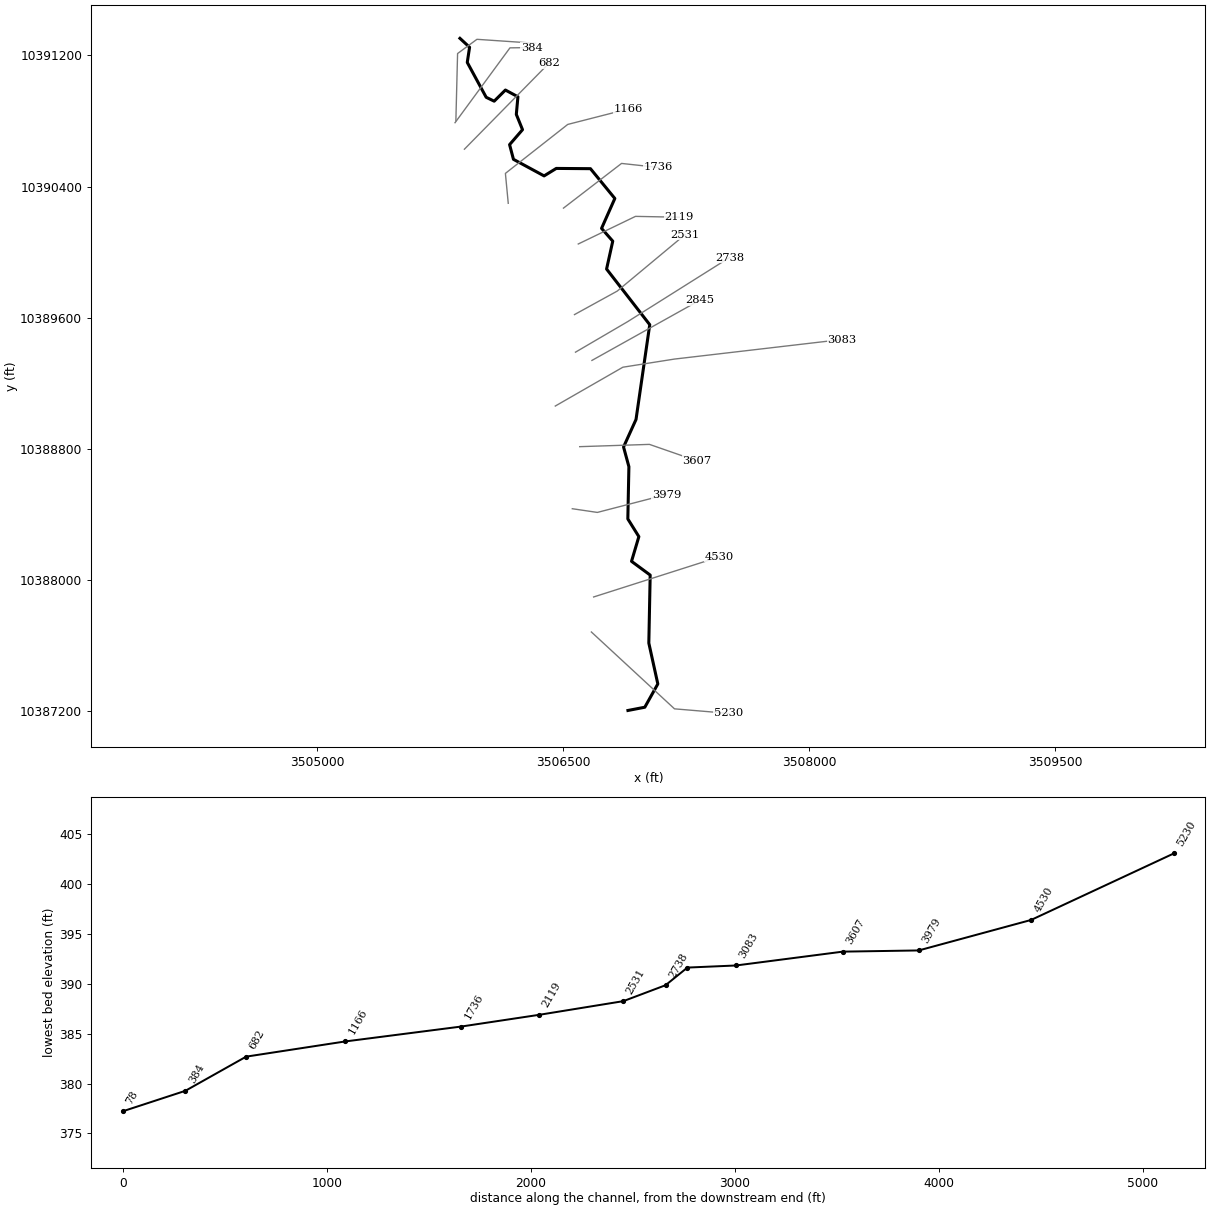
--- NORTH MINERAL CR TRIB 10.prj (project) ---

Proj Title=NORTH MINERAL CR TRIB 10 Base Level Engineering
Current Plan=p01
Default Exp/Contr=0.3,0.1
English Units
Geom File=g01
Flow File=f01
Plan File=p01
BEGIN DESCRIPTION:
NORTH MINERAL CR TRIB 10
END DESCRIPTION:

--- NORTH MINERAL CR TRIB 10.p01 (plan) ---

Plan Title=Multiple Run
Short Identifier=Multiple
Geom File=g01
Flow File=f01
Subcritical Flow
K Sum by GR= 0
Std Step Tol= 0.01
Critical Tol= 0.01
Num of Std Step Trials= 20
Max Error Tol= 0.3
Flow Tol Ratio= 0.001
Split Flow NTrial= 30
Split Flow Tol= 0.02
Split Flow Ratio= 0.02
Log Output Level= 0
Friction Slope Method= 1
Unsteady Friction Slope Method= 2
Unsteady Bridges Friction Slope Method= 1
Parabolic Critical Depth
Global Vel Dist=  1 , 1 , 1
Global Log Level= 0
CheckData=True
Encroach Param= -1, 0, 0, 0
BEGIN DESCRIPTION:
Multiple Run
END DESCRIPTION:

--- NORTH MINERAL CR TRIB 10.f01 (steady flow) ---

Flow Title=Multiple
Number of Profiles=7
Profile Names=10-year,25-year,50-year,1pct_min,100-year,1pct_plu,500-year
River Rch & RM= NORTH MINERAL CR,Reach-1,5230
    1332    1881    2345    2132    2883    3899    4351
Boundary for River Rch & Prof#=NORTH MINERAL CR,Reach-1,1
Up Type=0
Dn Type=3
Dn Slope=0.005
Boundary for River Rch & Prof#=NORTH MINERAL CR,Reach-1,2
Up Type=0
Dn Type=3
Dn Slope=0.005
Boundary for River Rch & Prof#=NORTH MINERAL CR,Reach-1,3
Up Type=0
Dn Type=3
Dn Slope=0.005
Boundary for River Rch & Prof#=NORTH MINERAL CR,Reach-1,4
Up Type=0
Dn Type=3
Dn Slope=0.005
Boundary for River Rch & Prof#=NORTH MINERAL CR,Reach-1,5
Up Type=0
Dn Type=3
Dn Slope=0.005
Boundary for River Rch & Prof#=NORTH MINERAL CR,Reach-1,6
Up Type=0
Dn Type=3
Dn Slope=0.005
Boundary for River Rch & Prof#=NORTH MINERAL CR,Reach-1,7
Up Type=0
Dn Type=3
Dn Slope=0.005

--- NORTH MINERAL CR TRIB 10.g01 (geometry) ---

Geom Title=Existing Conditions

River Reach=NORTH MINERAL CR,Reach-1
Reach XY= 30
      3506894.50     10387205.26      3506997.32     10387225.10
      3507076.70     10387367.07      3507021.81     10387616.33
      3507030.09     10388031.06      3506916.28     10388114.92
      3506961.06     10388265.51      3506893.78     10388373.46
      3506900.29     10388692.13      3506867.65     10388812.26
      3506943.69     10388979.97      3507027.37     10389558.10
      3506764.15     10389897.49      3506801.83     10390067.57
      3506733.52     10390145.57      3506814.53     10390327.89
      3506665.88     10390509.59      3506457.29     10390511.16
      3506383.05     10390465.57      3506196.24     10390566.59
      3506172.61     10390656.27      3506251.49     10390747.44
      3506213.68     10390840.65      3506223.45     10390948.08
      3506147.15     10390989.23      3506078.66     10390921.26
      3506029.90     10390944.96      3505914.51     10391157.62
      3505928.61     10391250.16      3505869.85     10391304.53

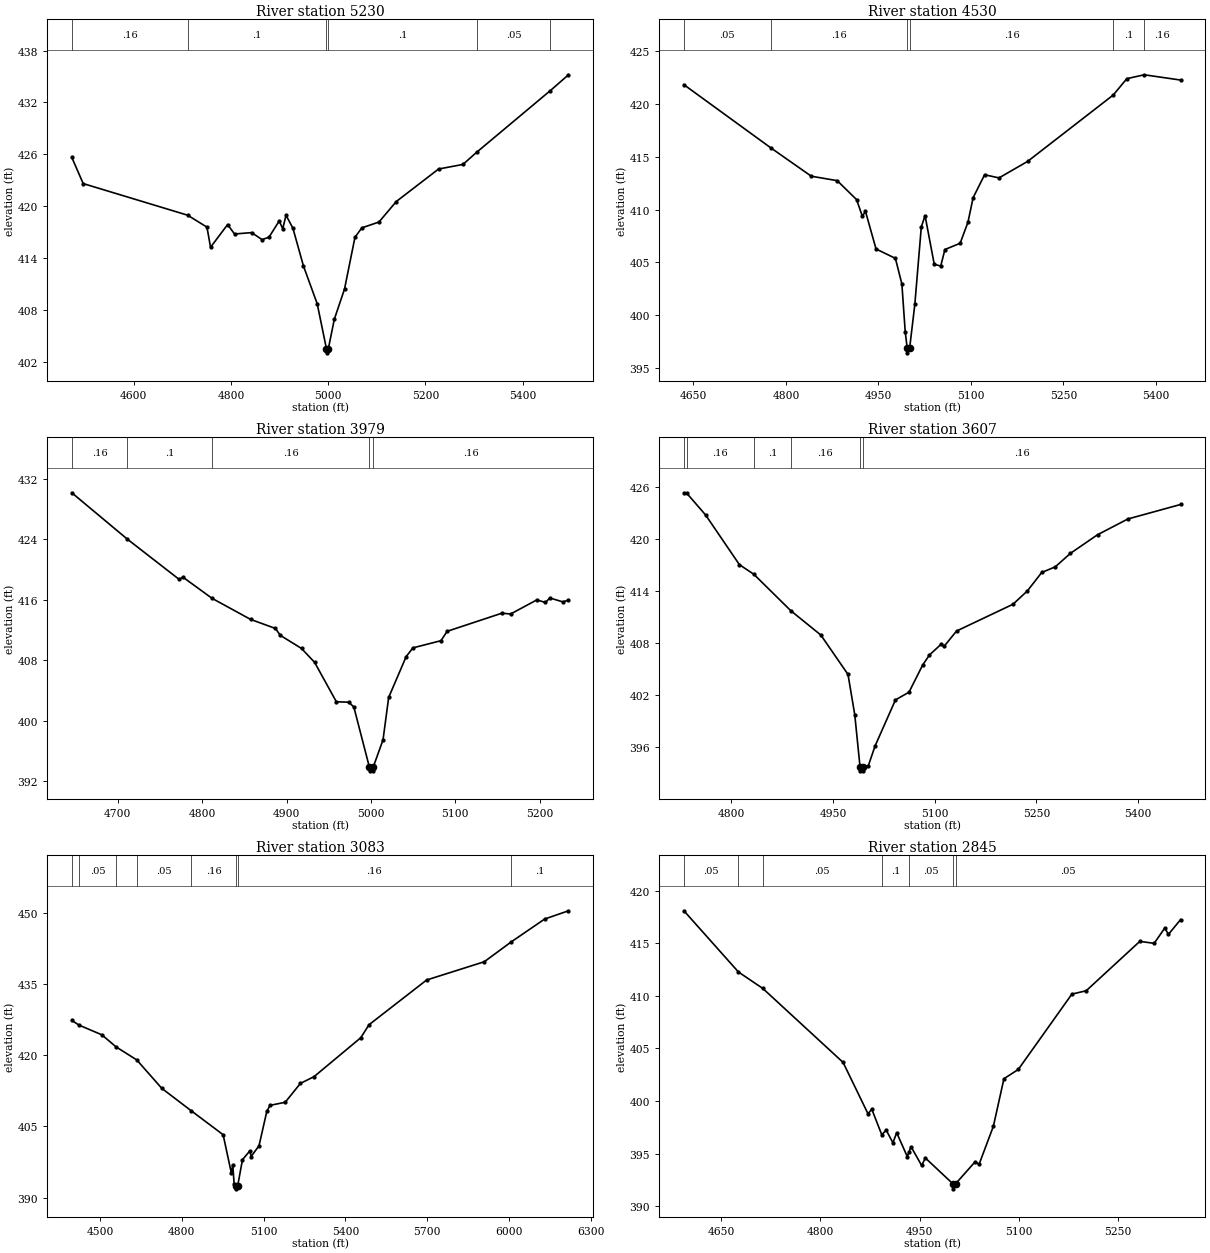
Type RM Length L Ch R = 1,5230,700,700,700
BEGIN DESCRIPTION:
NORTH MINERAL CR TRIB 10 3 0
END DESCRIPTION:
XS GIS Cut Line= 3
      3506671.45     10387683.97      3507178.36     10387215.25
      3507508.50     10387187.59
#Sta/Elev= 30
  4472.7  425.66  4496.1  422.64  4710.9  418.99  4750.7  417.61  4758.1  415.29
  4793.2  417.91  4807.4  416.82  4842.6  416.98  4864.1  416.17  4878.3  416.45
  4899.3  418.32  4906.6  417.43  4913.4  418.99  4927.6  417.47  4949.2  413.13
  4977.5  408.76  4996.4  403.60  4996.7  403.10  5000.5  403.60  5012.7  406.98
  5033.7  410.47  5055.2  416.45  5069.4  417.53  5104.5  418.20  5140.2  420.57
  5227.1  424.32  5277.3  424.85  5305.2  426.24  5457.2  433.38  5494.4  435.20
#Mann=6,-1,0
  4472.7    0.16       0  4710.9     0.1       0  4996.4    0.07       0
  5000.5     0.1       0  5305.2    0.05       0  5457.2     0.1       0
Bank Sta=4996.4,5000.5
Exp/Cntr=0.3,0.1

Type RM Length L Ch R = 1,4530,551,551,551
BEGIN DESCRIPTION:
NORTH MINERAL CR TRIB 10 2 0
END DESCRIPTION:
XS GIS Cut Line= 2
      3506685.29     10387897.53      3507452.69     10388142.34
#Sta/Elev= 30
  4634.5  421.85  4775.2  415.87  4841.1  413.17  4883.1  412.75  4914.6  410.95
  4923.8  409.38  4929.0  409.83  4946.1  406.27  4977.5  405.38  4988.0  402.95
  4993.4  398.44  4996.5  396.92  4996.8  396.42  5000.7  396.92  5009.0  401.01
  5019.5  408.36  5025.6  409.43  5040.5  404.82  5051.0  404.65  5057.8  406.22
  5082.5  406.81  5095.2  408.81  5103.5  411.13  5122.2  413.31  5145.5  413.01
  5191.8  414.57  5330.8  420.87  5352.8  422.42  5381.0  422.79  5440.0  422.29
#Mann=6,-1,0
  4634.5    0.05       0  4775.2    0.16       0  4996.5    0.07       0
  5000.7    0.16       0  5330.8     0.1       0  5381.0    0.16       0
Bank Sta=4996.5,5000.7
Exp/Cntr=0.3,0.1

Type RM Length L Ch R = 1,3979,372,372,372
BEGIN DESCRIPTION:
NORTH MINERAL CR TRIB 10 10 0
END DESCRIPTION:
XS GIS Cut Line= 3
      3506555.13     10388435.73      3506707.88     10388413.16
      3507128.47     10388522.21
#Sta/Elev= 30
  4645.4  430.13  4711.1  424.01  4772.4  418.70  4777.4  418.95  4811.7  416.17
  4857.3  413.39  4886.8  412.19  4892.7  411.27  4917.8  409.54  4933.3  407.70
  4959.1  402.49  4973.8  402.44  4979.8  401.80  4998.2  393.86  4998.5  393.36
  5002.4  393.36  5002.8  393.86  5014.4  397.46  5021.1  403.07  5041.8  408.46
  5049.8  409.62  5083.1  410.57  5090.4  411.81  5155.4  414.21  5165.7  414.10
  5196.7  415.96  5207.0  415.63  5212.2  416.22  5227.7  415.70  5234.3  415.95
#Mann=5,-1,0
  4645.4    0.16       0  4711.1     0.1       0  4811.7    0.16       0
  4998.2    0.07       0  5002.8    0.16       0
Bank Sta=4998.2,5002.8
Exp/Cntr=0.3,0.1

Type RM Length L Ch R = 1,3607,524,524,524
BEGIN DESCRIPTION:
NORTH MINERAL CR TRIB 10 9 0
END DESCRIPTION:
XS GIS Cut Line= 3
      3506600.26     10388814.21      3507025.58     10388828.10
      3507315.55     10388727.39
#Sta/Elev= 30
  4730.1  425.30  4734.6  425.22  4762.0  422.75  4812.0  417.01  4833.3  415.90
  4887.8  411.70  4932.0  408.90  4972.1  404.36  4982.1  399.70  4989.8  393.74
  4990.1  393.24  4994.1  393.24  4994.4  393.74  5002.1  393.84  5012.1  396.12
  5042.1  401.42  5062.1  402.31  5082.1  405.42  5092.1  406.59  5109.1  407.81
  5114.1  407.62  5132.2  409.36  5215.5  412.45  5236.7  413.99  5257.8  416.11
  5277.8  416.76  5300.2  418.32  5340.1  420.46  5384.9  422.28  5462.6  423.95
#Mann=6,-1,0
  4730.1     0.1       0  4734.6    0.16       0  4833.3     0.1       0
  4887.8    0.16       0  4989.8    0.07       0  4994.4    0.16       0
Bank Sta=4989.8,4994.4
Exp/Cntr=0.3,0.1

Type RM Length L Ch R = 1,3083,238,238,238
BEGIN DESCRIPTION:
NORTH MINERAL CR TRIB 10 11
END DESCRIPTION:
XS GIS Cut Line= 4
      3506451.31     10389061.97      3506863.55     10389298.79
      3507178.31     10389348.44      3508198.81     10389467.60
#Sta/Elev= 30
  4396.6  427.38  4423.1  426.38  4506.7  424.34  4558.5  421.81  4634.8  419.04
  4726.7  413.04  4834.5  408.32  4951.5  403.27  4981.7  395.18  4986.8  396.95
  4992.0  392.80  4999.8  392.35  5000.2  391.85  5004.5  392.35  5022.4  397.99
  5049.3  399.84  5054.3  398.67  5083.2  400.95  5111.7  408.18  5123.6  409.46
  5179.2  410.11  5234.8  414.08  5285.1  415.52  5456.3  423.72  5486.5  426.46
  5697.9  435.90  5909.3  439.75  6008.2  443.94  6130.8  448.76  6218.1  450.50
#Mann=8,-1,0
  4396.6    0.16       0  4423.1    0.05       0  4558.5     0.1       0
  4634.8    0.05       0  4834.5    0.16       0  4999.8    0.07       0
  5004.5    0.16       0  6008.2     0.1       0
Bank Sta=4999.8,5004.5
Exp/Cntr=0.3,0.1

Type RM Length L Ch R = 1,2845,107,107,107
BEGIN DESCRIPTION:
NORTH MINERAL CR TRIB 10 8 0
END DESCRIPTION:
XS GIS Cut Line= 2
      3506674.89     10389340.25      3507331.17     10389706.58
#Sta/Elev= 30
  4593.3  418.10  4675.9  412.27  4712.7  410.71  4834.2  403.67  4871.9  398.78
  4877.6  399.22  4892.7  396.79  4899.4  397.23  4909.6  396.02  4915.3  396.98
  4931.3  394.71  4934.1  395.17  4937.0  395.65  4953.0  393.87  4958.8  394.57
  5000.0  392.14  5000.4  391.64  5004.7  392.14  5034.2  394.23  5039.9  393.96
  5061.6  397.59  5077.6  402.12  5099.3  403.00  5180.4  410.17  5202.1  410.49
  5283.2  415.19  5304.9  415.00  5320.9  416.45  5326.6  415.86  5344.9  417.26
#Mann=7,-1,0
  4593.3    0.05       0  4675.9     0.1       0  4712.7    0.05       0
  4892.7     0.1       0  4934.1    0.05       0  5000.0    0.03       0
  5004.7    0.05       0
Bank Sta=5000,5004.7
Exp/Cntr=0.3,0.1

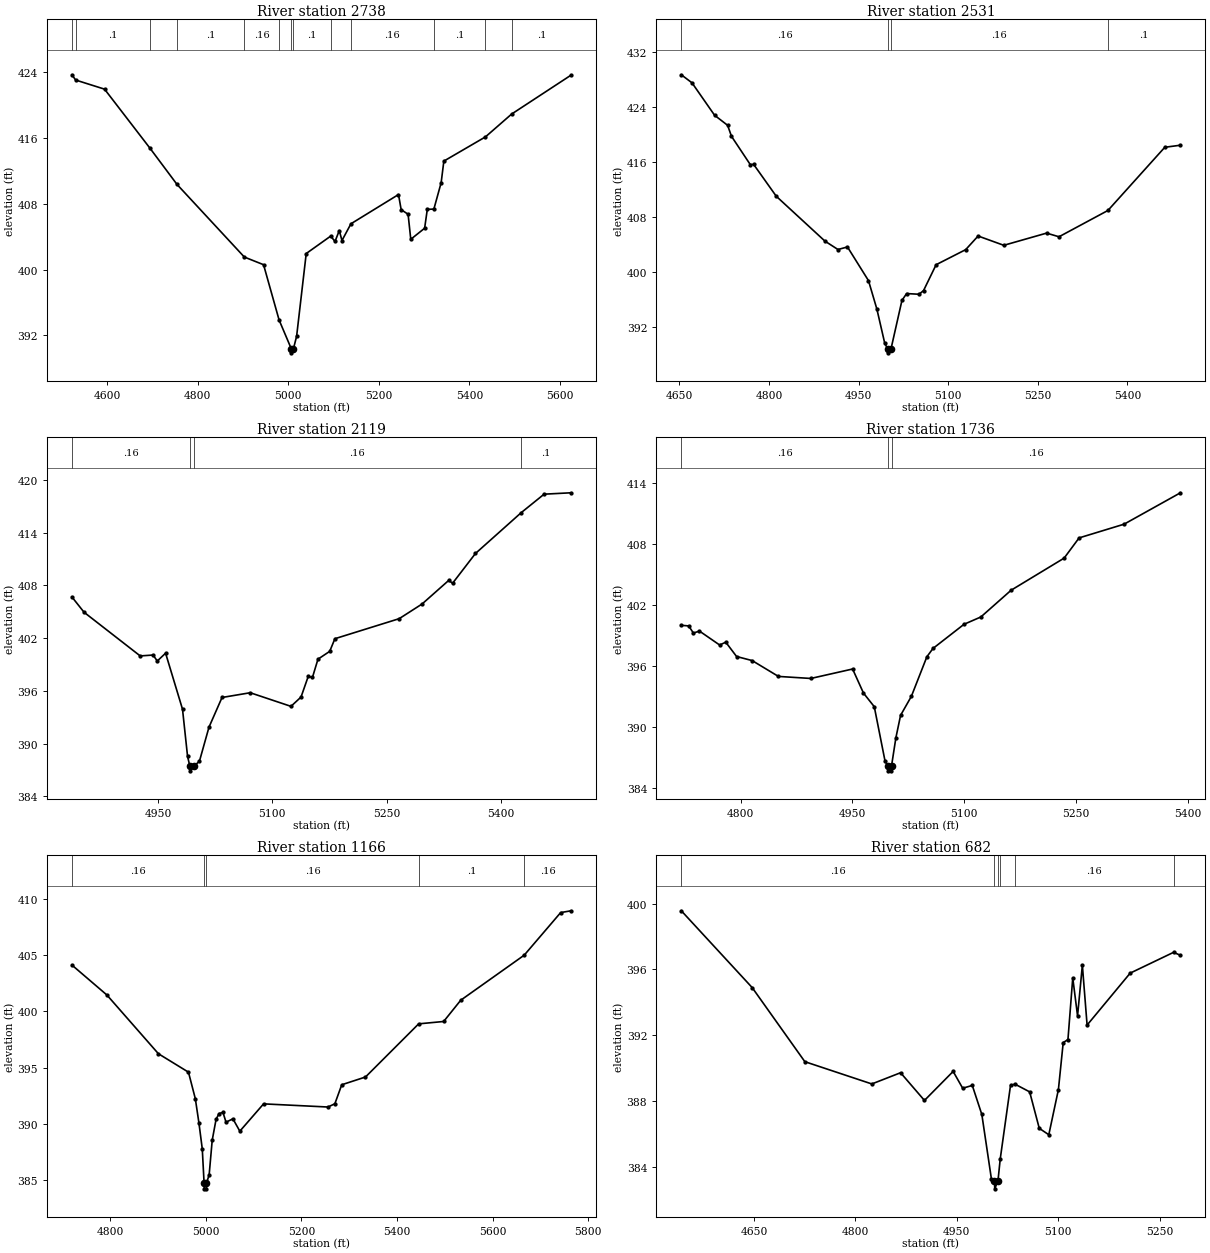
Type RM Length L Ch R = 1,2738,207,207,207
BEGIN DESCRIPTION:
NORTH MINERAL CR TRIB 10 6 0
END DESCRIPTION:
XS GIS Cut Line= 3
      3506574.56     10389390.52      3506893.59     10389577.17
      3507513.34     10389967.22
#Sta/Elev= 30
  4522.6  423.72  4530.8  423.08  4594.6  421.97  4695.3  414.75  4754.6  410.37
  4903.2  401.53  4945.6  400.60  4979.9  393.87  5006.8  390.37  5007.1  389.87
  5011.6  390.37  5018.6  391.89  5039.8  401.96  5093.8  404.08  5103.4  403.43
  5112.8  404.76  5118.7  403.54  5138.5  405.58  5243.5  409.14  5249.4  407.30
  5264.7  406.74  5270.6  403.69  5301.2  405.04  5307.1  407.34  5321.6  407.37
  5337.7  410.59  5343.6  413.21  5435.5  416.16  5493.3  418.94  5624.5  423.68
#Mann=13,-1,0
  4522.6    0.16       0  4530.8     0.1       0  4695.3    0.16       0
  4754.6     0.1       0  4903.2    0.16       0  4979.9     0.1       0
  5006.8    0.07       0  5011.6     0.1       0  5093.8    0.05       0
  5138.5    0.16       0  5321.6     0.1       0  5435.5    0.05       0
  5493.3     0.1       0
Bank Sta=5006.8,5011.6
Exp/Cntr=0.3,0.1

Type RM Length L Ch R = 1,2531,412,412,412
BEGIN DESCRIPTION:
NORTH MINERAL CR TRIB 10 7 0
END DESCRIPTION:
XS GIS Cut Line= 3
      3506568.47     10389619.69      3506828.92     10389762.93
      3507242.60     10390107.30
#Sta/Elev= 30
  4653.2  428.66  4671.1  427.49  4708.9  422.78  4730.7  421.32  4737.2  419.72
  4768.6  415.62  4774.3  415.64  4812.2  411.01  4893.6  404.50  4915.4  403.28
  4931.3  403.65  4966.5  398.76  4980.6  394.61  4993.8  389.63  4999.2  388.77
  4999.6  388.27  5004.0  388.77  5022.5  395.88  5030.3  396.88  5051.1  396.78
  5058.7  397.32  5079.7  401.07  5129.2  403.26  5150.0  405.24  5193.0  403.89
  5264.6  405.66  5285.4  405.13  5367.3  408.95  5462.5  418.13  5488.7  418.43
#Mann=4,-1,0
  4653.2    0.16       0  4999.2    0.07       0  5004.0    0.16       0
  5367.3     0.1       0
Bank Sta=4999.2,5004
Exp/Cntr=0.3,0.1

Type RM Length L Ch R = 1,2119,383,383,383
BEGIN DESCRIPTION:
NORTH MINERAL CR TRIB 10 12
END DESCRIPTION:
XS GIS Cut Line= 3
      3506591.53     10390050.31      3506940.52     10390218.72
      3507207.47     10390213.52
#Sta/Elev= 30
  4837.2  406.69  4853.1  404.95  4926.7  399.98  4943.6  400.08  4949.1  399.40
  4960.0  400.29  4982.2  393.91  4988.8  388.55  4991.9  387.40  4992.2  386.90
  4996.8  387.40  5004.4  388.00  5016.9  391.87  5034.0  395.25  5071.0  395.79
  5124.4  394.24  5137.6  395.30  5147.0  397.64  5152.6  397.54  5159.8  399.61
  5175.2  400.50  5182.0  401.94  5266.3  404.22  5296.3  405.89  5331.3  408.58
  5336.3  408.25  5366.3  411.64  5426.2  416.28  5456.3  418.39  5491.7  418.55
#Mann=4,-1,0
  4837.2    0.16       0  4991.9    0.07       0  4996.8    0.16       0
  5426.2     0.1       0
Bank Sta=4991.9,4996.8
Exp/Cntr=0.3,0.1

Type RM Length L Ch R = 1,1736,570,570,570
BEGIN DESCRIPTION:
NORTH MINERAL CR TRIB 10 5 0
END DESCRIPTION:
XS GIS Cut Line= 3
      3506501.26     10390269.06      3506855.45     10390541.64
      3507077.39     10390517.36
#Sta/Elev= 30
  4720.3  400.04  4730.2  399.98  4736.5  399.28  4744.7  399.47  4771.8  398.10
  4780.0  398.38  4794.5  396.97  4815.4  396.57  4850.7  395.01  4894.2  394.81
  4950.3  395.74  4964.9  393.37  4979.4  392.03  4993.9  386.66  4997.7  386.22
  4998.1  385.72  5002.3  385.72  5002.6  386.22  5008.4  388.97  5014.7  391.18
  5029.2  393.05  5050.0  396.94  5058.2  397.76  5099.9  400.14  5122.5  400.86
  5163.1  403.49  5234.3  406.65  5254.4  408.64  5314.8  409.99  5390.5  413.08
#Mann=3,-1,0
  4720.3    0.16       0  4997.7    0.07       0  5002.6    0.16       0
Bank Sta=4997.7,5002.6
Exp/Cntr=0.3,0.1

Type RM Length L Ch R = 1,1166,484,484,484
BEGIN DESCRIPTION:
NORTH MINERAL CR TRIB 10 4 0
END DESCRIPTION:
XS GIS Cut Line= 4
      3506164.48     10390298.56      3506147.11     10390480.87
      3506527.32     10390779.48      3506893.63     10390873.23
#Sta/Elev= 30
  4719.7  404.13  4792.8  401.47  4900.7  396.24  4963.6  394.60  4978.0  392.23
  4985.5  390.08  4992.5  387.77  4996.3  384.72  4996.7  384.22  5001.0  384.22
  5001.3  384.72  5006.9  385.47  5013.3  388.55  5021.4  390.41  5027.7  390.92
  5035.8  391.02  5042.2  390.15  5056.6  390.45  5071.1  389.35  5120.8  391.78
  5255.5  391.50  5270.0  391.79  5284.4  393.48  5334.1  394.17  5445.4  398.90
  5497.7  399.11  5533.4  401.00  5666.3  405.01  5742.6  408.80  5764.4  408.96
#Mann=5,-1,0
  4719.7    0.16       0  4996.3    0.07       0  5001.3    0.16       0
  5445.4     0.1       0  5666.3    0.16       0
Bank Sta=4996.3,5001.3
Exp/Cntr=0.3,0.1

Type RM Length L Ch R = 1,682,298,298,298
BEGIN DESCRIPTION:
Mapping XS 351bfffa
END DESCRIPTION:
XS GIS Cut Line= 2
      3505897.10     10390628.43      3506414.44     10391154.45
#Sta/Elev= 30
  4542.7  399.56  4647.5  394.90  4725.3  390.41  4824.3  389.06  4866.8  389.74
  4902.1  388.06  4944.5  389.82  4958.6  388.80  4972.8  388.97  4986.9  387.21
  5001.1  383.29  5005.6  383.20  5006.0  382.70  5010.8  383.20  5014.1  384.51
  5029.3  388.97  5035.8  389.05  5057.6  388.58  5071.8  386.37  5085.9  385.98
  5100.1  388.72  5107.2  391.57  5114.2  391.75  5121.3  395.49  5128.4  393.19
  5135.5  396.26  5142.5  392.63  5206.2  395.78  5270.3  397.04  5280.5  396.86
#Mann=6,-1,0
  4542.7    0.16       0  5005.6    0.07       0  5010.8    0.16       0
  5014.1    0.12       0  5035.8    0.16       0  5270.3     0.1       0
Bank Sta=5005.6,5010.8
Exp/Cntr=0.3,0.1

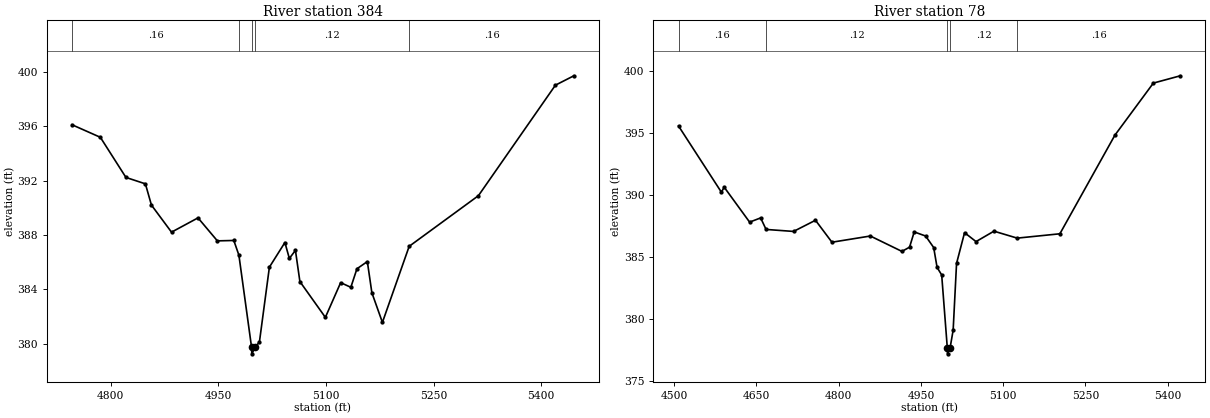
Type RM Length L Ch R = 1,384,306,306,306
BEGIN DESCRIPTION:
Mapping XS 71a5983f
END DESCRIPTION:
XS GIS Cut Line= 3
      3505839.83     10390789.91      3506174.89     10391246.50
      3506307.84     10391248.22
#Sta/Elev= 30
  4746.2  396.10  4785.6  395.18  4821.3  392.23  4848.4  391.76  4856.8  390.20
  4884.8  388.21  4921.7  389.26  4948.7  387.57  4971.6  387.60  4978.7  386.52
  4996.3  379.77  4996.7  379.27  5001.5  379.77  5007.3  380.14  5021.2  385.64
  5042.8  387.45  5049.0  386.28  5057.5  386.87  5063.7  384.58  5099.2  381.95
  5120.5  384.50  5134.7  384.16  5143.2  385.52  5157.7  386.05  5164.0  383.76
  5178.7  381.58  5216.0  387.17  5312.5  390.89  5419.8  399.01  5445.5  399.70
#Mann=5,-1,0
  4746.2    0.16       0  4978.7    0.12       0  4996.3    0.07       0
  5001.5    0.12       0  5216.0    0.16       0
Bank Sta=4996.3,5001.5
Exp/Cntr=0.3,0.1

Type RM Length L Ch R = 1,78,0,0,0
BEGIN DESCRIPTION:
NORTH MINERAL CR TRIB 10 1 0
END DESCRIPTION:
XS GIS Cut Line= 4
      3505845.03     10390802.03      3505855.45     10391211.78
      3505973.50     10391298.58      3506331.17     10391274.27
#Sta/Elev= 30
  4508.1  395.59  4586.3  390.25  4591.3  390.66  4637.7  387.84  4657.8  388.18
  4667.7  387.25  4717.8  387.09  4757.8  387.99  4787.8  386.22  4857.8  386.72
  4915.4  385.48  4929.3  385.82  4937.8  387.05  4958.6  386.72  4973.3  385.79
  4979.5  384.19  4987.9  383.58  4998.1  377.72  4998.5  377.22  5003.3  377.72
  5008.8  379.13  5015.0  384.51  5029.6  386.99  5050.5  386.27  5083.2  387.11
  5125.6  386.55  5203.4  386.90  5303.7  394.85  5373.8  399.05  5423.0  399.64
#Mann=5,-1,0
  4508.1    0.16       0  4667.7    0.12       0  4998.1    0.07       0
  5003.3    0.12       0  5125.6    0.16       0
Bank Sta=4998.1,5003.3
Exp/Cntr=0.3,0.1

Chan Stop Cuts=-1