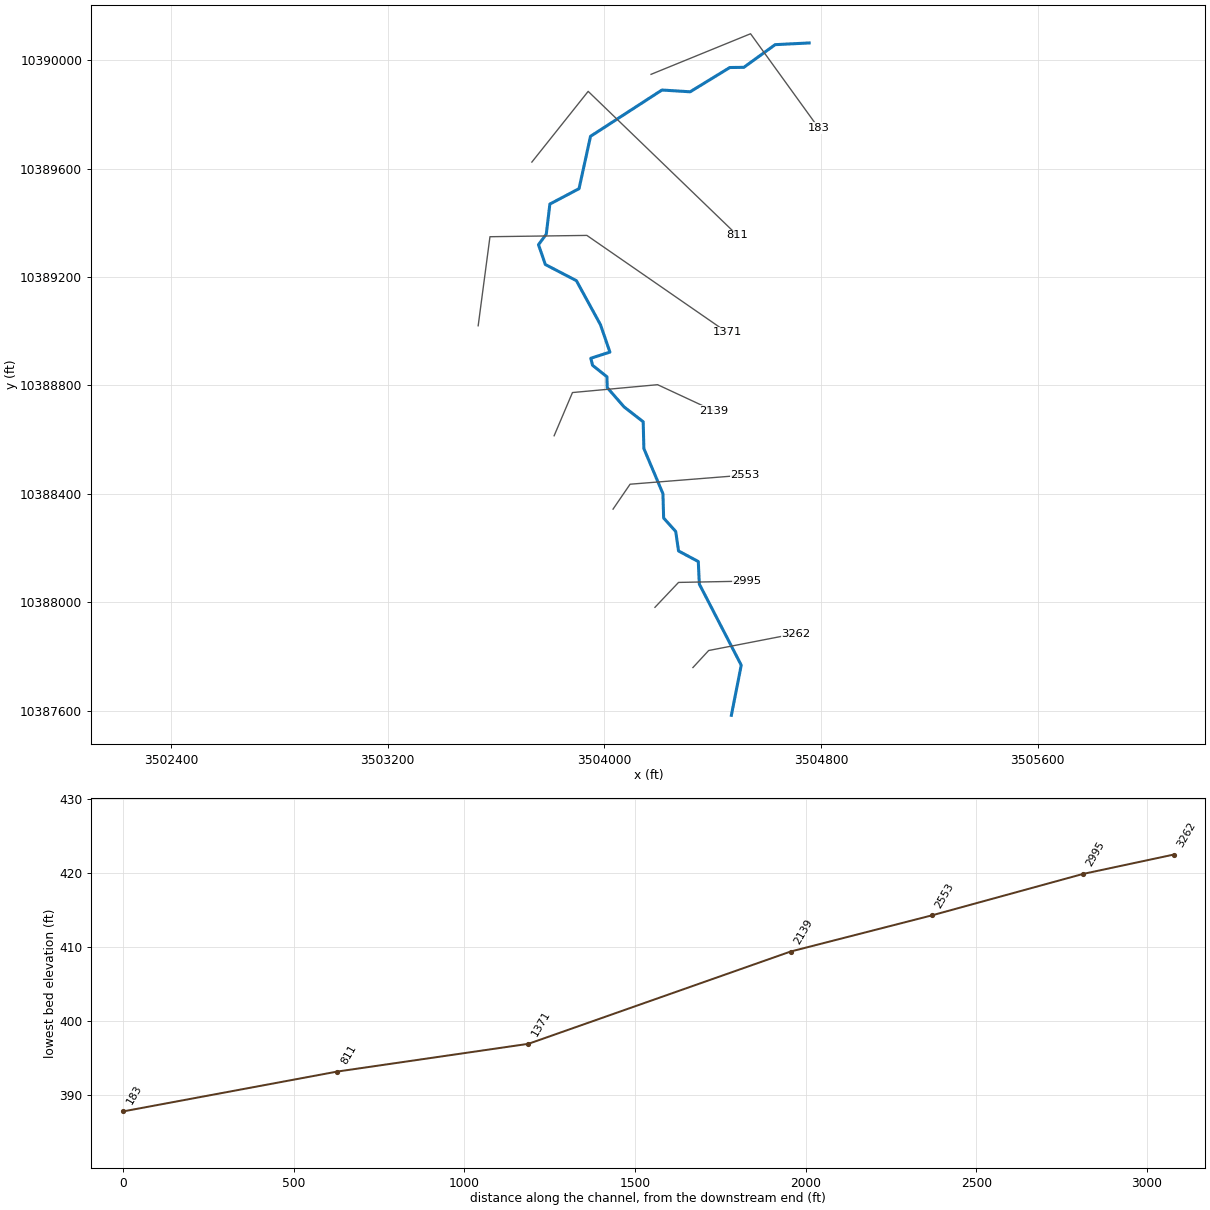
--- NORTH MINERAL CR TRIB 11.prj (project) ---

Proj Title=NORTH MINERAL CR TRIB 11 Base Level Engineering
Current Plan=p01
Default Exp/Contr=0.3,0.1
English Units
Geom File=g01
Flow File=f01
Plan File=p01
Y Axis Title=Elevation
X Axis Title(PF)=Main Channel Distance
X Axis Title(XS)=Station
BEGIN DESCRIPTION:
NORTH MINERAL CR TRIB 11
END DESCRIPTION:
DSS Export Rating Curves= 0
DSS Export Rating Curve Sorted= 0
DSS Export Volume Flow Curves= 0
DXF OffsetX= 0
DXF OffsetY= 0
DXF ScaleX= 1
DXF ScaleY= 10

--- NORTH MINERAL CR TRIB 11.p01 (plan) ---

Plan Title=Multiple Run
Short Identifier=Multiple
Geom File=g01
Flow File=f01
Subcritical Flow
K Sum by GR= 0
Std Step Tol= 0.01
Critical Tol= 0.01
Num of Std Step Trials= 20
Max Error Tol= 0.3
Flow Tol Ratio= 0.001
Split Flow NTrial= 30
Split Flow Tol= 0.02
Split Flow Ratio= 0.02
Log Output Level= 0
Friction Slope Method= 1
Unsteady Friction Slope Method= 2
Unsteady Bridges Friction Slope Method= 1
Parabolic Critical Depth
Global Vel Dist=  1 , 1 , 1
Global Log Level= 0
CheckData=True
Encroach Param= -1, 0, 0, 0
BEGIN DESCRIPTION:
Multiple Run
END DESCRIPTION:

--- NORTH MINERAL CR TRIB 11.f01 (steady flow) ---

Flow Title=Multiple
Number of Profiles=7
Profile Names=10-year,25-year,50-year,1pct_min,100-year,1pct_plu,500-year
River Rch & RM= NORTH MINERAL CR,Reach-1,3262
     119     155     183     125     212     299     282
Boundary for River Rch & Prof#=NORTH MINERAL CR,Reach-1,1
Up Type=0
Dn Type=3
Dn Slope=0.005
Boundary for River Rch & Prof#=NORTH MINERAL CR,Reach-1,2
Up Type=0
Dn Type=3
Dn Slope=0.005
Boundary for River Rch & Prof#=NORTH MINERAL CR,Reach-1,3
Up Type=0
Dn Type=3
Dn Slope=0.005
Boundary for River Rch & Prof#=NORTH MINERAL CR,Reach-1,4
Up Type=0
Dn Type=3
Dn Slope=0.005
Boundary for River Rch & Prof#=NORTH MINERAL CR,Reach-1,5
Up Type=0
Dn Type=3
Dn Slope=0.005
Boundary for River Rch & Prof#=NORTH MINERAL CR,Reach-1,6
Up Type=0
Dn Type=3
Dn Slope=0.005
Boundary for River Rch & Prof#=NORTH MINERAL CR,Reach-1,7
Up Type=0
Dn Type=3
Dn Slope=0.005

--- NORTH MINERAL CR TRIB 11.g01 (geometry) ---

Geom Title=Existing Conditions
Program Version=4.10

River Reach=NORTH MINERAL CR,Reach-1
Reach XY= 30
      3504469.09     10387582.58      3504505.54     10387767.48
      3504350.89     10388066.64      3504346.98     10388149.98
      3504274.06     10388189.04      3504263.65     10388261.03
      3504219.09     10388310.45      3504216.48     10388400.29
      3504146.17     10388566.96      3504143.57     10388665.91
      3504073.25      10388720.6      3504010.75     10388792.22
      3504009.89     10388831.93      3503956.72     10388874.25
      3503950.21     10388900.29      3504020.74     10388923.08
      3503986.01     10389023.99      3503897.04     10389186.75
      3503782.43     10389246.38       3503757.1     10389319.65
      3503785.91     10389358.36      3503799.13     10389469.46
       3503906.8     10389526.37      3503949.12     10389719.52
      3504212.78     10389890.46      3504316.95     10389883.94
      3504463.27     10389973.52      3504515.14     10389974.22
      3504630.69     10390057.89      3504756.28     10390064.23

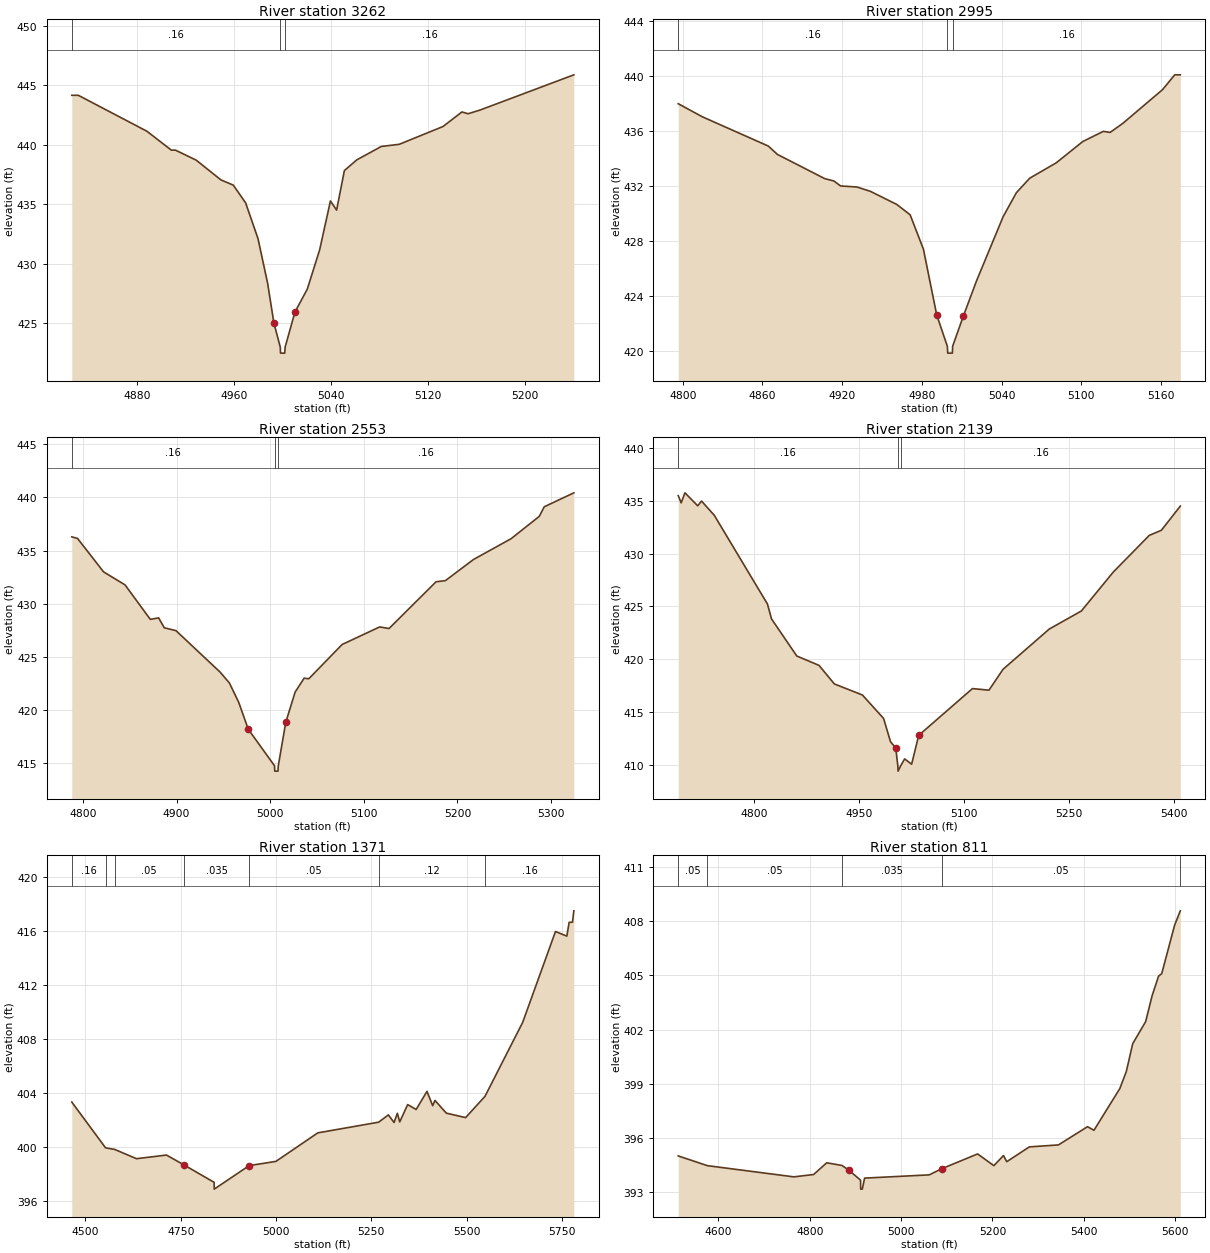
Type RM Length L Ch R = 1 ,3262    ,267,267,267
BEGIN DESCRIPTION:
NORTH MINERAL CR TRIB 11 3.0
END DESCRIPTION:
XS GIS Cut Line= 3
       3504327.2      10387758.7      3504385.23     10387821.57
      3504708.05      10387884.2
#Sta/Elev= 30
  4826.2  444.16  4831.6  444.16  4888.2  441.14  4908.4  439.55  4911.8  439.55
  4928.9  438.71  4949.3  437.05  4959.5  436.61  4969.7  435.12  4979.9  432.12
  4987.9  428.34    4993  425.04  4998.3  422.99  4998.5  422.49    5002  422.49
  5002.3  422.99  5010.4  425.94  5020.6  427.87  5030.8  431.17  5039.7  435.28
  5044.8  434.51  5051.2  437.83  5061.4  438.73  5081.7  439.86  5096.5  440.04
  5132.7  441.54  5148.2  442.76  5153.3  442.61  5163.2  442.92  5240.6  445.88
#Mann= 3 ,-1 , 0
  4826.2     .16       0  4998.3     .07       0  5002.3     .16       0
Bank Sta=4993,5010.4
XS Rating Curve= 0 ,0
Exp/Cntr=0.3,0.1

Type RM Length L Ch R = 1 ,2995    ,442,442,442
BEGIN DESCRIPTION:
Mapping XS 29c98c51
END DESCRIPTION:
XS GIS Cut Line= 3
      3504187.02     10387981.04      3504274.06     10388072.91
      3504525.45     10388077.75
#Sta/Elev= 30
  4796.6     438  4814.7  437.05  4864.4  434.92  4871.3  434.31  4906.9  432.55
  4913.8  432.38  4918.8  432.02  4931.2  431.94  4941.2  431.63  4961.2  430.67
  4971.2  429.92  4981.2  427.42  4991.2  422.64  4999.2  420.36  4999.5  419.86
    5003  419.86  5003.2  420.36  5011.2  422.54  5021.2  425.12  5041.2  429.78
  5051.2  431.53  5061.2  432.58  5081.2   433.7  5101.2  435.25  5116.7  435.99
  5121.7  435.91  5131.2  436.56  5161.2  439.02  5170.4   440.1  5174.6   440.1
#Mann= 3 ,-1 , 0
  4796.6     .16       0  4999.2     .07       0  5003.2     .16       0
Bank Sta=4991.2,5011.2
XS Rating Curve= 0 ,0
Exp/Cntr=0.3,0.1

Type RM Length L Ch R = 1 ,2553    ,414,414,414
BEGIN DESCRIPTION:
Mapping XS 4dba7808
END DESCRIPTION:
XS GIS Cut Line= 3
      3504032.35     10388343.55      3504095.21     10388435.43
      3504518.85     10388469.13
#Sta/Elev= 30
    4788  436.28  4794.1  436.14    4822  432.99  4844.9  431.77  4871.9  428.53
  4880.8  428.67  4886.8  427.74  4899.3  427.47  4946.4  423.58  4956.4  422.55
  4966.4  420.72  4976.5  418.21  5004.6  414.77  5004.8  414.27  5008.3  414.27
  5008.6  414.77  5016.6  418.86  5026.6   421.7  5036.2     423  5041.2  422.95
  5076.8  426.17  5116.9  427.82  5126.9  427.67  5177.1  432.06  5187.1  432.17
  5217.2  434.16  5257.3  436.11  5287.4  438.21  5292.7  439.11  5324.3  440.42
#Mann= 3 ,-1 , 0
    4788     .16       0  5004.6     .07       0  5008.6     .16       0
Bank Sta=4976.5,5016.6
XS Rating Curve= 0 ,0
Exp/Cntr=0.3,0.1

Type RM Length L Ch R = 1 ,2139    ,768,768,768
BEGIN DESCRIPTION:
Mapping XS f9b1b568
END DESCRIPTION:
XS GIS Cut Line= 4
      3503814.86     10388614.27      3503882.54     10388773.78
      3504196.72     10388802.79        3504404.     10388706.38
#Sta/Elev= 30
  4691.9  435.51  4696.1  434.83  4701.5  435.78  4719.7  434.55  4725.2     435
  4743.4  433.65  4819.4  425.23  4825.2  423.82  4861.3   420.3  4893.1  419.41
    4915  417.65  4955.1   416.6  4985.3  414.38  4995.3  412.16  5002.7  411.58
  5005.7  409.88    5006  409.38  5009.7  409.88  5015.4  410.54  5025.4  410.04
  5035.5  412.77  5112.3  417.21  5135.9  417.06    5156  419.04  5222.1  422.86
  5267.9  424.57  5313.6  428.27  5364.9  431.74  5382.3  432.23  5409.3  434.52
#Mann= 3 ,-1 , 0
  4691.9     .16       0  5005.7     .07       0  5009.7     .16       0
Bank Sta=5002.7,5035.5
XS Rating Curve= 0 ,0
Exp/Cntr=0.3,0.1

Type RM Length L Ch R = 1 ,1371    ,560,560,560
BEGIN DESCRIPTION:
Mapping XS 0f8b231a
END DESCRIPTION:
XS GIS Cut Line= 4
      3503534.51     10389020.27      3503578.02     10389348.98
      3503935.71     10389353.82      3504452.55     10388996.38
#Sta/Elev= 30
    4464  403.35  4552.8  399.96  4576.3  399.85    4634  399.16  4712.5  399.43
  4757.9  398.71  4837.7  397.41  4837.9  396.91  4929.7  398.65  4999.7  398.96
  5109.7  401.07  5269.4  401.86  5294.9   402.4  5309.8  401.84  5318.6  402.52
  5324.7  401.88  5345.6  403.16  5367.8   402.8  5396.3  404.14  5411.2  403.08
  5417.3  403.47    5447  402.53  5497.7   402.2  5548.5  403.77  5647.4  409.24
  5733.5  415.96  5763.3  415.62  5769.4  416.64  5778.2  416.65  5781.7  417.49
#Mann= 7 ,-1 , 0
    4464     .16       0  4552.8     .12       0  4576.3     .05       0
  4757.9    .035       0  4929.7     .05       0  5269.4     .12       0
  5548.5     .16       0
Bank Sta=4757.9,4929.7
XS Rating Curve= 0 ,0
Exp/Cntr=0.3,0.1

Type RM Length L Ch R = 1 ,811     ,628,628,628
BEGIN DESCRIPTION:
NORTH MINERAL CR TRIB 11 2.0
END DESCRIPTION:
XS GIS Cut Line= 3
       3503732.7      10389624.5      3503940.54     10389885.51
      3504491.58      10389353.8
#Sta/Elev= 30
  4512.1     395  4575.9  394.46  4765.2  393.84  4808.5  393.97  4837.3  394.62
  4870.9  394.47    4885  394.22  4911.3  393.66  4911.6  393.16  4915.1  393.16
  4920.2  393.77  5061.7  393.95    5090   394.3  5167.7  395.11  5203.2  394.46
  5224.3  395.02  5231.5  394.68  5280.9   395.5  5344.7  395.61  5408.3  396.62
  5422.4  396.42    5479  398.73  5493.2  399.67  5507.3  401.22  5535.6  402.44
  5549.7  403.87  5563.9  404.96  5570.8   405.1  5599.1  407.79  5611.5  408.58
#Mann= 5 ,-1 , 0
  4512.1     .05       0  4575.9     .05       0  4870.9    .035       0
    5090     .05       0  5611.5     .16       0
Bank Sta=4885,5090
XS Rating Curve= 0 ,0
Exp/Cntr=0.3,0.1

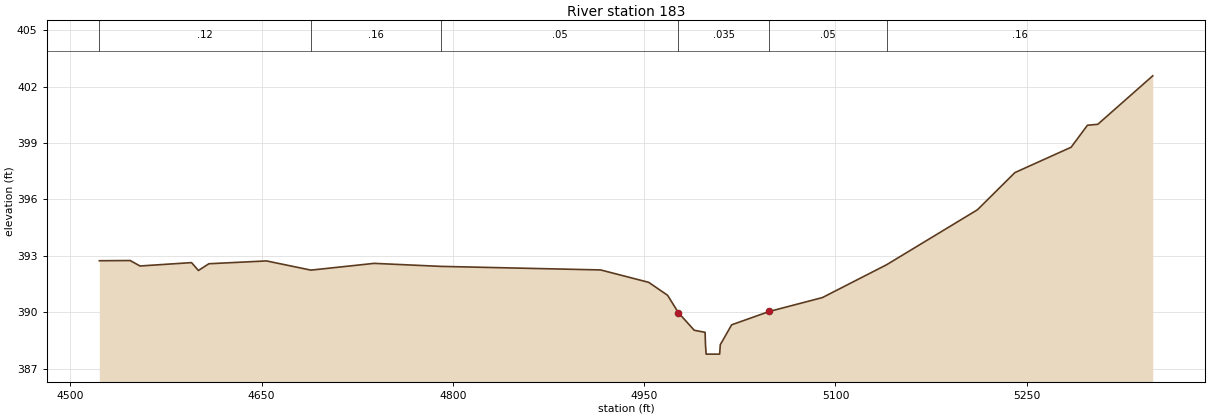
Type RM Length L Ch R = 1 ,183     ,0,0,0
BEGIN DESCRIPTION:
NORTH MINERAL CR TRIB 11 1.0
END DESCRIPTION:
XS GIS Cut Line= 3
      3504172.59     10389948.37      3504539.91     10390098.19
      3504791.26     10389750.16
#Sta/Elev= 30
  4522.8  392.74    4547  392.75  4554.7  392.46  4595.1  392.64  4600.5  392.22
  4608.7  392.58  4653.9  392.73  4688.7  392.24  4738.3   392.6  4790.4  392.44
  4915.9  392.25  4953.6  391.59  4968.4   390.9  4976.9  389.97  4989.3  389.04
  4997.8  388.93  4998.1  388.27  4998.6  387.77  5009.2  387.77  5009.7  388.27
  5018.6  389.33  5048.1  390.04  5089.8  390.78  5140.2  392.53  5211.3  395.45
  5240.7  397.43  5284.8  398.78  5297.6  399.95  5305.7     400  5348.8  402.58
#Mann= 6 ,-1 , 0
  4522.8     .12       0  4688.7     .16       0  4790.4     .05       0
  4976.9    .035       0  5048.1     .05       0  5140.2     .16       0
Bank Sta=4976.9,5048.1
XS Rating Curve= 0 ,0
Exp/Cntr=0.3,0.1

Chan Stop Cuts=-1
Use User Specified Reach Order=0
Composite Channel Slope=5