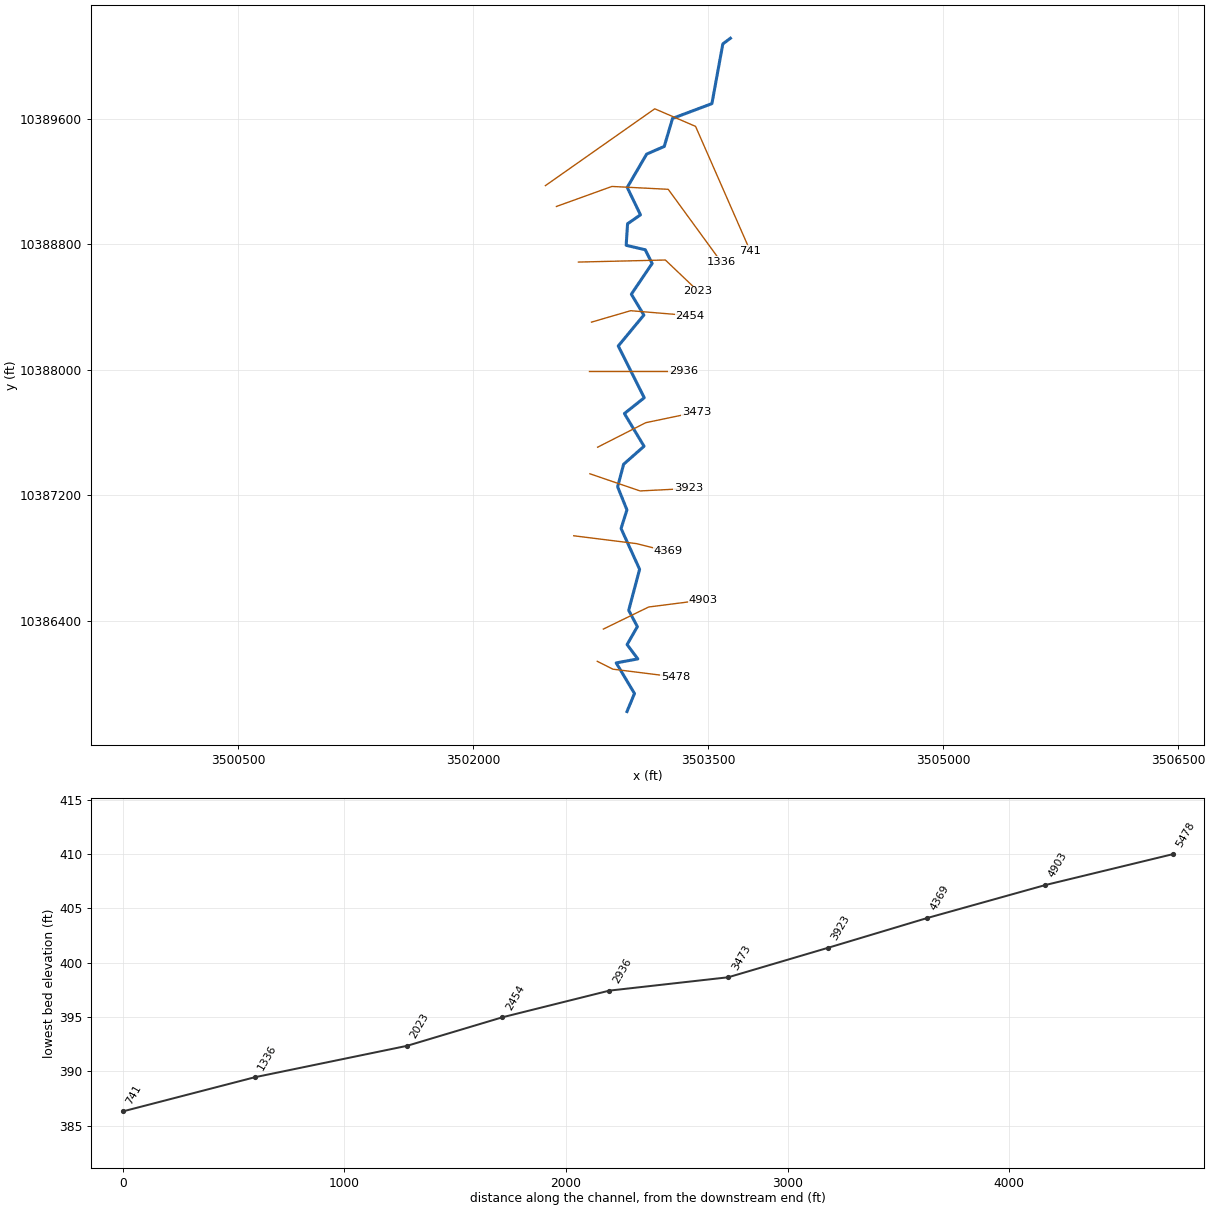
--- NORTH MINERAL CR TRIB 12.prj (project) ---

Proj Title=NORTH MINERAL CR TRIB 12 Base Level Engineering
Current Plan=p01
Default Exp/Contr=0.3,0.1
English Units
Geom File=g01
Flow File=f01
Plan File=p01
BEGIN DESCRIPTION:
NORTH MINERAL CR TRIB 12
END DESCRIPTION:

--- NORTH MINERAL CR TRIB 12.p01 (plan) ---

Plan Title=Multiple Run
Short Identifier=Multiple
Geom File=g01
Flow File=f01
Subcritical Flow
K Sum by GR= 0
Std Step Tol= 0.01
Critical Tol= 0.01
Num of Std Step Trials= 20
Max Error Tol= 0.3
Flow Tol Ratio= 0.001
Split Flow NTrial= 30
Split Flow Tol= 0.02
Split Flow Ratio= 0.02
Log Output Level= 0
Friction Slope Method= 1
Unsteady Friction Slope Method= 2
Unsteady Bridges Friction Slope Method= 1
Parabolic Critical Depth
Global Vel Dist=  1 , 1 , 1
Global Log Level= 0
CheckData=True
Encroach Param= -1, 0, 0, 0
BEGIN DESCRIPTION:
Multiple Run
END DESCRIPTION:

--- NORTH MINERAL CR TRIB 12.f01 (steady flow) ---

Flow Title=Multiple
Number of Profiles=7
Profile Names=10-year,25-year,50-year,1pct_min,100-year,1pct_plu,500-year
River Rch & RM= NORTH MINERAL CR,Reach-1,5478
    1222    1716    2130    1928    2607    3526    3901
Boundary for River Rch & Prof#=NORTH MINERAL CR,Reach-1,1
Up Type=0
Dn Type=3
Dn Slope=0.005
Boundary for River Rch & Prof#=NORTH MINERAL CR,Reach-1,2
Up Type=0
Dn Type=3
Dn Slope=0.005
Boundary for River Rch & Prof#=NORTH MINERAL CR,Reach-1,3
Up Type=0
Dn Type=3
Dn Slope=0.005
Boundary for River Rch & Prof#=NORTH MINERAL CR,Reach-1,4
Up Type=0
Dn Type=3
Dn Slope=0.005
Boundary for River Rch & Prof#=NORTH MINERAL CR,Reach-1,5
Up Type=0
Dn Type=3
Dn Slope=0.005
Boundary for River Rch & Prof#=NORTH MINERAL CR,Reach-1,6
Up Type=0
Dn Type=3
Dn Slope=0.005
Boundary for River Rch & Prof#=NORTH MINERAL CR,Reach-1,7
Up Type=0
Dn Type=3
Dn Slope=0.005

--- NORTH MINERAL CR TRIB 12.g01 (geometry) ---

Geom Title=Existing Conditions

River Reach=NORTH MINERAL CR,Reach-1
Reach XY= 30
      3502982.11     10385821.64      3503029.83     10385936.46
      3502913.25     10386131.59      3503051.04     10386156.96
      3502982.79     10386248.33      3503048.31     10386362.46
      3502993.04     10386466.66      3503062.59     10386727.98
      3502944.32     10386987.90      3502981.62     10387106.31
      3502922.35     10387253.61      3502960.65     10387397.42
      3503090.86     10387511.98      3502965.64     10387720.29
      3503092.19     10387821.17      3502926.36     10388151.07
      3503089.81     10388347.72      3503009.87     10388480.84
      3503142.44     10388676.55      3503098.58     10388763.98
      3502976.87     10388792.38      3502985.73     10388929.48
      3503068.13     10388986.56      3502983.58     10389161.03
      3503107.51     10389373.48      3503219.84     10389422.23
      3503272.92     10389600.98      3503523.99     10389695.05
      3503593.84     10390075.87      3503642.11     10390111.64

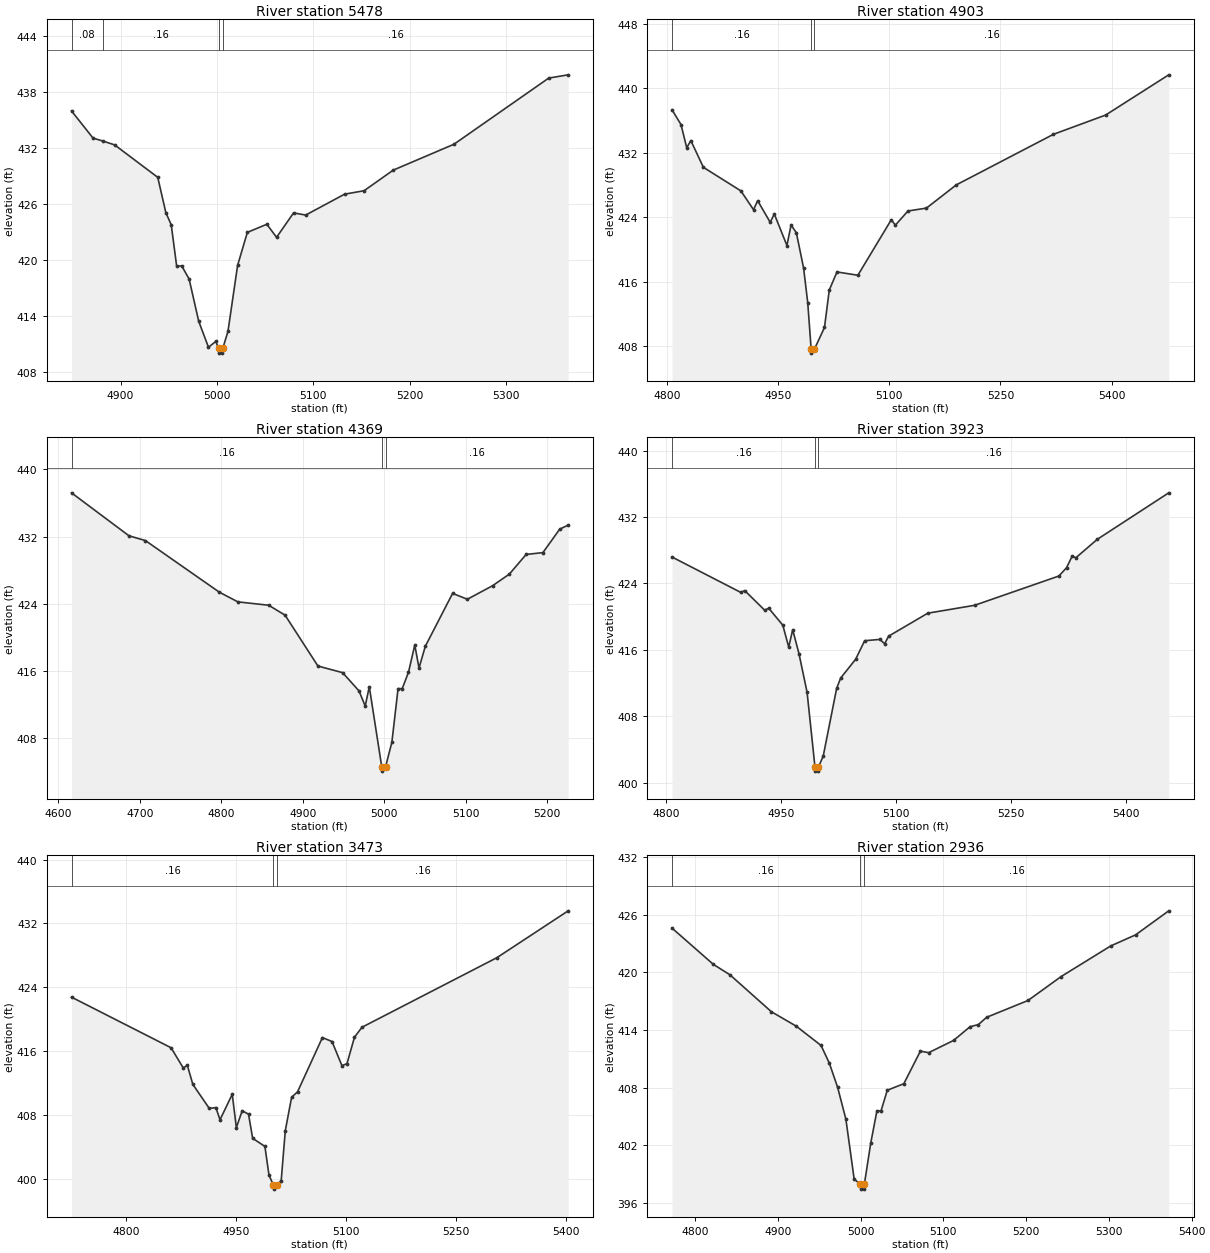
Type RM Length L Ch R = 1,5478,575,575,575
BEGIN DESCRIPTION:
NORTH MINERAL CR TRIB 12 3 0
END DESCRIPTION:
XS GIS Cut Line= 3
      3502792.13     10386141.63      3502892.11     10386091.64
      3503292.12     10386041.64
#Sta/Elev= 30
  4849.2  435.99  4871.5  433.07  4881.5  432.76  4893.9  432.34  4938.6  428.86
  4947.0  425.07  4952.6  423.76  4958.2  419.34  4963.5  419.34  4971.1  417.95
  4981.1  413.40  4991.2  410.62  4998.8  411.25  5001.6  410.49  5001.9  409.99
  5005.7  409.99  5006.0  410.49  5011.4  412.32  5021.4  419.41  5031.5  422.95
  5051.7  423.82  5061.8  422.42  5079.4  425.04  5092.0  424.81  5132.3  427.05
  5152.5  427.42  5182.7  429.63  5245.7  432.41  5343.9  439.51  5364.1  439.86
#Mann=4,-1,0
  4849.2    0.08       0  4881.5    0.16       0  5001.6    0.07       0
  5006.0    0.16       0
Bank Sta=5001.6,5006
Exp/Cntr=0.3,0.1

Type RM Length L Ch R = 1,4903,534,534,534
BEGIN DESCRIPTION:
NORTH MINERAL CR TRIB 12 2 0
END DESCRIPTION:
XS GIS Cut Line= 3
      3502831.18     10386347.07      3503120.20     10386487.67
      3503466.58     10386531.95
#Sta/Elev= 30
  4806.6  437.33  4818.7  435.50  4826.4  432.63  4832.0  433.51  4848.9  430.20
  4899.6  427.27  4916.6  424.94  4922.2  426.06  4939.1  423.38  4944.7  424.40
  4961.7  420.50  4967.3  423.04  4974.4  422.09  4984.2  417.71  4989.8  413.41
  4994.4  407.65  4994.7  407.15  4998.9  407.65  5012.4  410.33  5018.9  414.98
  5029.3  417.22  5057.5  416.81  5102.6  423.69  5108.1  423.02  5125.1  424.78
  5150.1  425.14  5190.4  428.02  5321.5  434.29  5392.0  436.68  5477.2  441.67
#Mann=3,-1,0
  4806.6    0.16       0  4994.4    0.07       0  4998.9    0.16       0
Bank Sta=4994.4,4998.9
Exp/Cntr=0.3,0.1

Type RM Length L Ch R = 1,4369,446,446,446
BEGIN DESCRIPTION:
NORTH MINERAL CR TRIB 12 9 0
END DESCRIPTION:
XS GIS Cut Line= 3
      3502642.12     10386941.64      3503042.11     10386891.64
      3503242.15     10386841.63
#Sta/Elev= 30
  4616.3  437.21  4686.8  432.10  4707.0  431.53  4797.7  425.39  4820.4  424.24
  4858.2  423.84  4878.3  422.66  4918.6  416.61  4948.9  415.82  4969.0  413.65
  4976.6  411.85  4981.6  414.15  4996.9  404.61  4997.3  404.11  5001.5  404.61
  5009.3  407.54  5016.9  413.92  5022.0  413.92  5029.7  415.87  5037.4  419.11
  5042.6  416.37  5050.3  418.95  5083.8  425.25  5101.9  424.55  5132.8  426.16
  5153.4  427.54  5174.0  429.88  5194.6  430.10  5215.2  432.89  5225.6  433.37
#Mann=3,-1,0
  4616.3    0.16       0  4996.9    0.07       0  5001.5    0.16       0
Bank Sta=4996.9,5001.5
Exp/Cntr=0.3,0.1

Type RM Length L Ch R = 1,3923,450,450,450
BEGIN DESCRIPTION:
NORTH MINERAL CR TRIB 12 8 0
END DESCRIPTION:
XS GIS Cut Line= 3
      3502745.16     10387336.64      3503065.52     10387227.26
      3503375.41     10387242.88
#Sta/Elev= 30
  4807.4  427.19  4897.1  422.93  4902.4  423.14  4928.4  420.78  4933.7  421.02
  4952.1  418.97  4959.8  416.34  4965.0  418.43  4973.2  415.54  4983.8  410.88
  4994.1  401.88  4994.4  401.38  4998.4  401.38  4998.7  401.88  5004.9  403.20
  5022.4  411.35  5027.7  412.61  5047.2  414.86  5059.0  417.10  5078.9  417.26
  5085.1  416.74  5090.3  417.65  5141.5  420.42  5202.6  421.37  5312.7  424.90
  5322.7  425.90  5330.0  427.29  5335.0  427.11  5362.8  429.32  5456.2  434.93
#Mann=3,-1,0
  4807.4    0.16       0  4994.1    0.07       0  4998.7    0.16       0
Bank Sta=4994.1,4998.7
Exp/Cntr=0.3,0.1

Type RM Length L Ch R = 1,3473,537,537,537
BEGIN DESCRIPTION:
NORTH MINERAL CR TRIB 12 7 0
END DESCRIPTION:
XS GIS Cut Line= 3
      3502794.70     10387505.91      3503101.97     10387662.15
      3503427.29     10387729.82
#Sta/Elev= 30
  4726.0  422.76  4861.7  416.41  4878.3  413.88  4883.9  414.20  4891.4  411.81
  4913.8  408.80  4922.8  408.90  4928.4  407.37  4945.1  410.57  4950.7  406.39
  4958.7  408.51  4967.3  408.07  4972.9  405.05  4989.6  404.03  4995.2  400.42
  5001.2  399.17  5001.6  398.67  5005.9  399.17  5011.8  399.73  5017.4  406.00
  5026.0  410.19  5034.1  410.88  5068.0  417.69  5081.1  417.19  5094.6  414.16
  5101.5  414.42  5111.7  417.73  5121.9  418.98  5305.8  427.71  5403.0  433.59
#Mann=3,-1,0
  4726.0    0.16       0  5001.2    0.07       0  5005.9    0.16       0
Bank Sta=5001.2,5005.9
Exp/Cntr=0.3,0.1

Type RM Length L Ch R = 1,2936,482,482,482
BEGIN DESCRIPTION:
NORTH MINERAL CR TRIB 12 6 0
END DESCRIPTION:
XS GIS Cut Line= 3
      3502742.11     10387991.64      3502992.11     10387991.64
      3503342.11     10387991.64
#Sta/Elev= 30
  4772.3  424.60  4822.3  420.82  4842.3  419.74  4892.3  415.90  4922.3  414.40
  4952.3  412.39  4962.3  410.55  4972.3  408.04  4982.3  404.72  4992.3  398.48
  4999.9  397.94  5000.3  397.44  5004.3  397.44  5004.6  397.94  5012.3  402.22
  5019.8  405.59  5024.8  405.59  5032.3  407.73  5052.3  408.41  5072.3  411.80
  5082.3  411.64  5112.3  412.91  5132.3  414.34  5142.3  414.56  5152.3  415.32
  5202.3  417.07  5242.3  419.56  5302.3  422.75  5332.3  423.90  5372.3  426.40
#Mann=3,-1,0
  4772.3    0.16       0  4999.9    0.07       0  5004.6    0.16       0
Bank Sta=4999.9,5004.6
Exp/Cntr=0.3,0.1

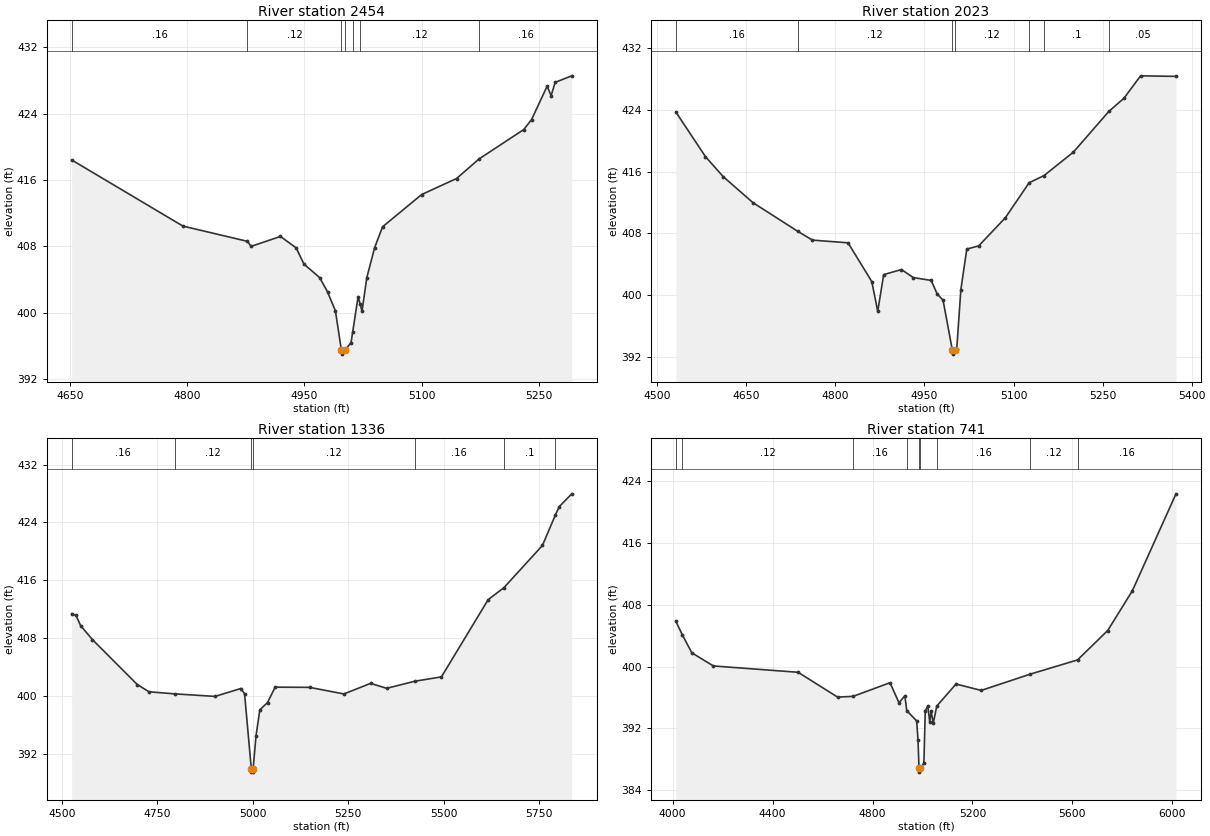
Type RM Length L Ch R = 1,2454,431,431,431
BEGIN DESCRIPTION:
NORTH MINERAL CR TRIB 12 5 0
END DESCRIPTION:
XS GIS Cut Line= 3
      3502755.62     10388302.78      3503005.62     10388375.69
      3503383.21     10388344.44
#Sta/Elev= 30
  4652.4  418.42  4794.6  410.44  4877.1  408.60  4881.8  407.99  4919.3  409.19
  4939.4  407.81  4949.4  405.85  4969.5  404.22  4979.5  402.50  4989.6  400.21
  4997.2  395.49  4997.6  394.99  5002.0  395.49  5009.6  396.39  5011.6  397.62
  5018.6  401.92  5021.3  400.98  5023.6  400.18  5029.7  404.21  5039.7  407.83
  5049.8  410.35  5099.9  414.25  5144.5  416.18  5173.2  418.54  5230.4  422.09
  5240.4  423.30  5260.3  427.33  5265.3  426.17  5270.5  427.78  5291.7  428.57
#Mann=7,-1,0
  4652.4    0.16       0  4877.1    0.12       0  4997.2    0.07       0
  5002.0    0.12       0  5011.6    0.16       0  5021.3    0.12       0
  5173.2    0.16       0
Bank Sta=4997.2,5002
Exp/Cntr=0.3,0.1

Type RM Length L Ch R = 1,2023,687,687,687
BEGIN DESCRIPTION:
NORTH MINERAL CR TRIB 12 4 0
END DESCRIPTION:
XS GIS Cut Line= 3
      3502672.30     10388685.59      3503226.97     10388698.61
      3503435.32     10388500.68
#Sta/Elev= 30
  4531.4  423.71  4581.2  417.94  4611.2  415.34  4661.2  411.98  4736.8  408.26
  4761.3  407.13  4821.3  406.78  4861.3  401.76  4871.3  397.90  4881.3  402.66
  4911.3  403.32  4931.3  402.27  4961.3  401.91  4971.3  400.17  4981.3  399.35
  4997.0  392.86  4997.3  392.36  5001.8  392.86  5004.4  393.05  5011.3  400.72
  5021.3  405.97  5041.3  406.38  5086.2  410.02  5126.3  414.56  5151.4  415.49
  5201.0  418.54  5260.5  423.80  5285.9  425.50  5314.0  428.41  5373.6  428.34
#Mann=7,-1,0
  4531.4    0.16       0  4736.8    0.12       0  4997.0    0.07       0
  5001.8    0.12       0  5126.3    0.16       0  5151.4     0.1       0
  5260.5    0.05       0
Bank Sta=4997,5001.8
Exp/Cntr=0.3,0.1

Type RM Length L Ch R = 1,1336,595,595,595
BEGIN DESCRIPTION:
Mapping XS 9ca67121
END DESCRIPTION:
XS GIS Cut Line= 4
      3502531.69     10389039.77      3502885.83     10389167.36
      3503245.20     10389149.13      3503583.35     10388686.13
#Sta/Elev= 30
  4525.4  411.38  4536.5  411.15  4549.1  409.71  4579.7  407.80  4697.2  401.58
  4727.9  400.58  4795.6  400.29  4900.8  399.94  4968.2  401.03  4978.2  400.31
  4995.8  389.97  4996.1  389.47  5000.3  389.47  5000.7  389.97  5008.2  394.51
  5018.2  398.08  5038.3  399.09  5058.3  401.22  5148.4  401.19  5238.5  400.28
  5308.1  401.74  5350.5  401.06  5424.2  402.04  5493.8  402.64  5616.2  413.32
  5657.3  414.97  5758.3  420.81  5792.4  425.05  5802.3  426.18  5835.0  427.95
#Mann=7,-1,0
  4525.4    0.16       0  4795.6    0.12       0  4995.8    0.07       0
  5000.7    0.12       0  5424.2    0.16       0  5657.3     0.1       0
  5792.4    0.16       0
Bank Sta=4995.8,5000.7
Exp/Cntr=0.3,0.1

Type RM Length L Ch R = 1,741,0,0,0
BEGIN DESCRIPTION:
NORTH MINERAL CR TRIB 12 1 0
END DESCRIPTION:
XS GIS Cut Line= 4
      3502461.35     10389172.57      3503159.27     10389662.15
      3503419.68     10389550.17      3503767.70     10388758.04
#Sta/Elev= 30
  4013.2  405.84  4039.1  404.10  4076.9  401.78  4163.2  400.08  4502.2  399.26
  4660.0  396.05  4722.2  396.14  4870.0  397.91  4905.9  395.31  4929.5  396.23
  4937.1  394.29  4976.6  392.97  4982.0  390.55  4986.1  386.83  4986.4  386.33
  4991.0  386.83  5005.6  387.48  5011.0  394.24  5021.2  394.91  5029.1  392.80
  5034.5  394.28  5043.0  392.65  5057.2  394.89  5134.2  397.74  5235.0  396.91
  5431.4  399.02  5620.5  400.86  5741.2  404.67  5840.0  409.82  6014.4  422.37
#Mann=9,-1,0
  4013.2    0.16       0  4039.1    0.12       0  4722.2    0.16       0
  4937.1    0.12       0  4986.1    0.07       0  4991.0    0.12       0
  5057.2    0.16       0  5431.4    0.12       0  5620.5    0.16       0
Bank Sta=4986.1,4991
Exp/Cntr=0.3,0.1

Chan Stop Cuts=-1