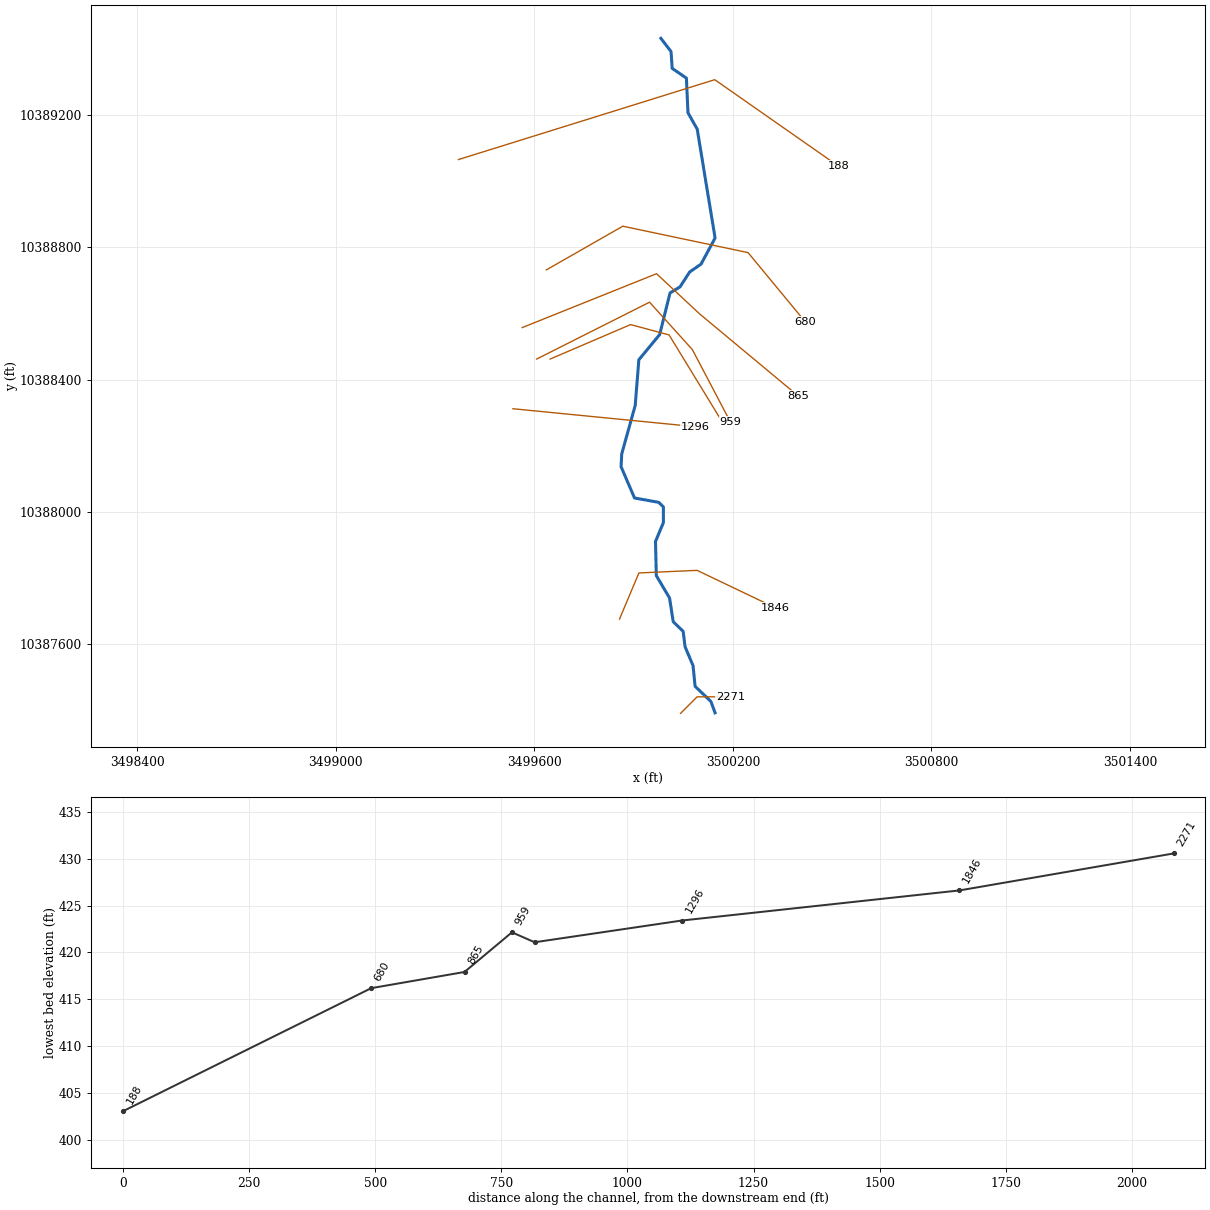
--- NORTH MINERAL CR TRIB 13.prj (project) ---

Proj Title=NORTH MINERAL CR TRIB 13 Base Level Engineering
Current Plan=p01
Default Exp/Contr=0.3,0.1
English Units
Geom File=g01
Flow File=f01
Plan File=p01
BEGIN DESCRIPTION:
NORTH MINERAL CR TRIB 13
END DESCRIPTION:

--- NORTH MINERAL CR TRIB 13.p01 (plan) ---

Plan Title=Multiple Run
Short Identifier=Multiple
Geom File=g01
Flow File=f01
Subcritical Flow
K Sum by GR= 0
Std Step Tol= 0.01
Critical Tol= 0.01
Num of Std Step Trials= 20
Max Error Tol= 0.3
Flow Tol Ratio= 0.001
Split Flow NTrial= 30
Split Flow Tol= 0.02
Split Flow Ratio= 0.02
Log Output Level= 0
Friction Slope Method= 1
Unsteady Friction Slope Method= 2
Unsteady Bridges Friction Slope Method= 1
Parabolic Critical Depth
Global Vel Dist=  1 , 1 , 1
Global Log Level= 0
CheckData=True
Encroach Param= -1, 0, 0, 0
BEGIN DESCRIPTION:
Multiple Run
END DESCRIPTION:

--- NORTH MINERAL CR TRIB 13.f01 (steady flow) ---

Flow Title=Multiple
Number of Profiles=7
Profile Names=10-year,25-year,50-year,1pct_min,100-year,1pct_plu,500-year
River Rch & RM= NORTH MINERAL CR,Reach-1,2271
     325     421     497     430     581     786     790
Boundary for River Rch & Prof#=NORTH MINERAL CR,Reach-1,1
Up Type=0
Dn Type=3
Dn Slope=0.005
Boundary for River Rch & Prof#=NORTH MINERAL CR,Reach-1,2
Up Type=0
Dn Type=3
Dn Slope=0.005
Boundary for River Rch & Prof#=NORTH MINERAL CR,Reach-1,3
Up Type=0
Dn Type=3
Dn Slope=0.005
Boundary for River Rch & Prof#=NORTH MINERAL CR,Reach-1,4
Up Type=0
Dn Type=3
Dn Slope=0.005
Boundary for River Rch & Prof#=NORTH MINERAL CR,Reach-1,5
Up Type=0
Dn Type=3
Dn Slope=0.005
Boundary for River Rch & Prof#=NORTH MINERAL CR,Reach-1,6
Up Type=0
Dn Type=3
Dn Slope=0.005
Boundary for River Rch & Prof#=NORTH MINERAL CR,Reach-1,7
Up Type=0
Dn Type=3
Dn Slope=0.005

--- NORTH MINERAL CR TRIB 13.g01 (geometry) ---

Geom Title=Existing Conditions

River Reach=NORTH MINERAL CR,Reach-1
Reach XY= 30
      3500146.23     10387393.40      3500133.75     10387427.60
      3500085.98     10387473.34      3500079.85     10387535.69
      3500055.60     10387593.25      3500049.79     10387639.57
      3500019.81     10387668.59      3500008.86     10387740.22
      3499968.76     10387807.97      3499966.35     10387910.98
      3499990.12     10387968.01      3499990.23     10388015.53
      3499976.18     10388029.20      3499902.88     10388042.48
      3499862.32     10388136.96      3499864.25     10388175.55
      3499905.02     10388322.04      3499916.08     10388460.06
      3499978.95     10388536.35      3500010.20     10388661.87
      3500040.67     10388680.62      3500069.32     10388725.15
      3500103.95     10388749.11      3500146.40     10388828.01
      3500092.35     10389157.07      3500064.48     10389206.44
      3500059.70     10389311.16      3500016.74     10389340.67
      3500013.26     10389391.46      3499982.54     10389431.36

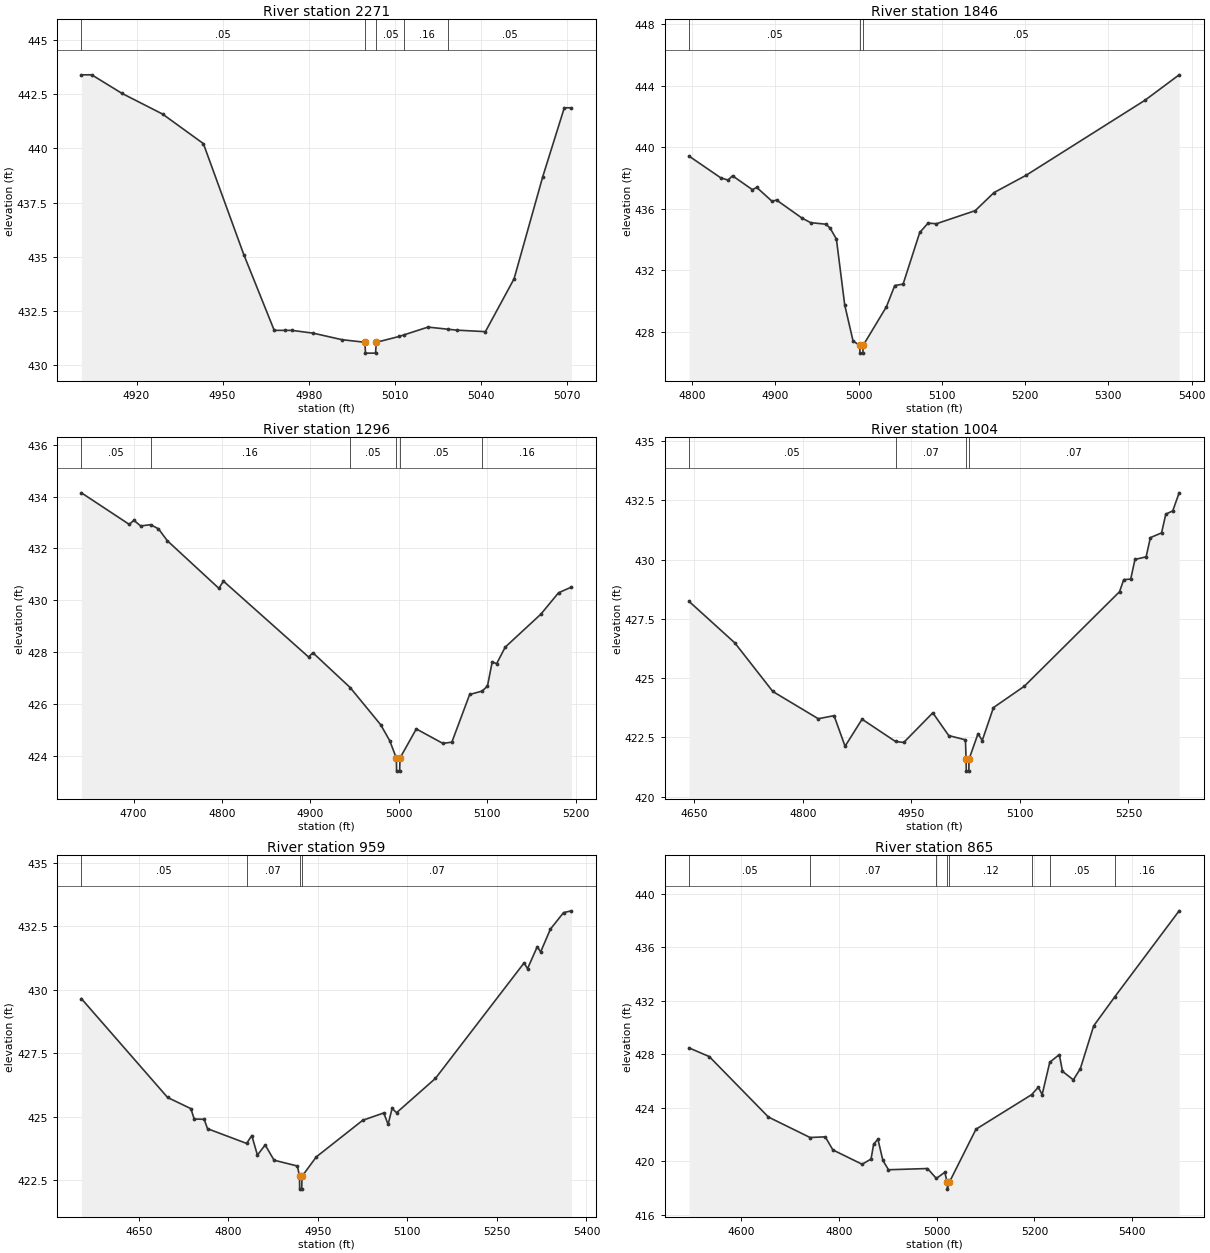
Type RM Length L Ch R = 1,2271,425,425,425
BEGIN DESCRIPTION:
NORTH MINERAL CR TRIB 13 7 0
END DESCRIPTION:
XS GIS Cut Line= 3
      3500042.08     10387391.61      3500092.11     10387441.64
      3500192.15     10387441.64
#Sta/Elev= 25
  4900.8  443.39  4904.4  443.39  4915.0  442.53  4929.1  441.58  4943.3  440.22
  4957.4  435.10  4968.0  431.61  4971.6  431.61  4974.1  431.61  4981.6  431.48
  4991.6  431.18  4999.6  431.06  4999.8  430.56  5003.3  430.56  5003.6  431.06
  5011.6  431.33  5013.4  431.41  5021.6  431.76  5028.7  431.66  5031.6  431.62
  5041.6  431.55  5051.6  433.99  5061.6  438.70  5069.1  441.87  5071.6  441.87
#Mann=5,-1,0
  4900.8    0.05       0  4999.6    0.03       0  5003.6    0.05       0
  5013.4    0.16       0  5028.7    0.05       0
Bank Sta=4999.6,5003.6
Exp/Cntr=0.3,0.1

Type RM Length L Ch R = 1,1846,550,550,550
BEGIN DESCRIPTION:
NORTH MINERAL CR TRIB 13 6 0
END DESCRIPTION:
XS GIS Cut Line= 4
      3499857.63     10387676.66      3499916.21     10387815.94
      3500091.99     10387823.76      3500328.05     10387710.91
#Sta/Elev= 30
  4796.3  439.43  4834.3  438.02  4843.1  437.87  4848.5  438.15  4872.3  437.25
  4877.7  437.39  4896.0  436.49  4901.4  436.57  4931.9  435.40  4942.4  435.10
  4960.7  435.00  4965.7  434.75  4973.3  434.03  4983.3  429.74  4993.3  427.40
  5001.4  427.11  5001.6  426.61  5005.1  426.61  5005.4  427.11  5033.4  429.63
  5043.4  431.01  5053.4  431.10  5073.4  434.46  5083.4  435.07  5093.4  435.03
  5140.0  435.88  5162.7  437.06  5201.1  438.18  5344.1  443.07  5385.0  444.72
#Mann=3,-1,0
  4796.3    0.05       0  5001.4    0.03       0  5005.4    0.05       0
Bank Sta=5001.4,5005.4
Exp/Cntr=0.3,0.1

Type RM Length L Ch R = 1,1296,292,292,292
BEGIN DESCRIPTION:
NORTH MINERAL CR TRIB 13 2 0
END DESCRIPTION:
XS GIS Cut Line= 2
      3499535.43     10388312.16      3500086.66     10388257.91
#Sta/Elev= 30
  4641.1  434.15  4695.2  432.93  4700.3  433.09  4708.1  432.87  4719.2  432.92
  4728.2  432.76  4738.2  432.30  4796.5  430.46  4801.6  430.74  4897.8  427.81
  4902.8  427.97  4944.8  426.63  4979.4  425.19  4989.5  424.58  4997.1  423.90
  4997.3  423.40  5000.8  423.40  5001.1  423.90  5019.6  425.03  5049.7  424.47
  5059.8  424.52  5079.9  426.36  5093.8  426.49  5100.0  426.68  5105.4  427.62
  5110.4  427.55  5120.1  428.19  5160.3  429.46  5180.4  430.29  5195.0  430.51
#Mann=6,-1,0
  4641.1    0.05       0  4719.2    0.16       0  4944.8    0.05       0
  4997.1    0.03       0  5001.1    0.05       0  5093.8    0.16       0
Bank Sta=4997.1,5001.1
Exp/Cntr=0.3,0.1

Type RM Length L Ch R = 1,1004,45,45,45
BEGIN DESCRIPTION:
NORTH MINERAL CR TRIB 13 5 0
END DESCRIPTION:
XS GIS Cut Line= 4
      3499648.00     10388462.22      3499891.04     10388566.38
      3500007.36     10388535.13      3500159.69     10388285.85
#Sta/Elev= 30
  4643.0  428.24  4706.2  426.49  4758.7  424.44  4821.5  423.29  4843.3  423.42
  4858.5  422.13  4882.0  423.27  4928.2  422.33  4939.6  422.29  4979.7  423.54
  5001.7  422.58  5024.8  422.40  5025.7  421.58  5026.0  421.08  5029.5  421.08
  5029.7  421.58  5042.2  422.66  5048.0  422.37  5063.5  423.76  5106.1  424.66
  5237.7  428.65  5243.5  429.16  5253.1  429.18  5259.0  430.01  5274.4  430.12
  5280.3  430.93  5295.7  431.13  5301.6  431.92  5311.2  432.06  5320.0  432.82
#Mann=4,-1,0
  4643.0    0.05       0  4928.2    0.07       0  5025.7    0.07       0
  5029.7    0.07       0
Bank Sta=5025.7,5029.7
Exp/Cntr=0.3,0.1

Type RM Length L Ch R = 1,959,94,94,94
BEGIN DESCRIPTION:
Mapping XS 0569a1db
END DESCRIPTION:
XS GIS Cut Line= 4
      3499607.16     10388462.20      3499948.33     10388634.08
      3500077.67     10388490.86      3500192.26     10388272.96
#Sta/Elev= 30
  4553.7  429.64  4698.1  425.75  4737.1  425.31  4742.7  424.90  4759.4  424.89
  4765.0  424.52  4830.5  423.94  4839.2  424.25  4848.6  423.48  4861.6  423.88
  4876.5  423.28  4915.6  423.05  4919.2  422.64  4919.4  422.14  4922.9  422.14
  4923.2  422.64  4947.3  423.41  5025.0  424.85  5060.3  425.14  5067.6  424.69
  5074.3  425.32  5081.8  425.15  5146.9  426.50  5295.5  431.05  5301.2  430.82
  5317.6  431.69  5323.2  431.48  5339.6  432.38  5361.6  433.03  5374.9  433.10
#Mann=4,-1,0
  4553.7    0.05       0  4830.5    0.07       0  4919.2    0.07       0
  4923.2    0.07       0
Bank Sta=4919.2,4923.2
Exp/Cntr=0.3,0.1

Type RM Length L Ch R = 1,865,185,185,185
BEGIN DESCRIPTION:
NORTH MINERAL CR TRIB 13 3 0
END DESCRIPTION:
XS GIS Cut Line= 4
      3499563.66     10388557.38      3499969.49     10388720.14
      3500099.70     10388598.62      3500396.97     10388351.25
#Sta/Elev= 30
  4493.8  428.47  4535.2  427.82  4656.1  423.30  4741.2  421.77  4772.3  421.82
  4787.9  420.84  4847.7  419.77  4865.9  420.16  4871.3  421.28  4880.0  421.64
  4890.1  420.06  4901.6  419.36  4981.3  419.45  4999.5  418.71  5016.7  419.17
  5021.8  418.41  5022.1  417.91  5025.8  418.41  5080.5  422.39  5194.1  424.97
  5208.0  425.53  5215.8  424.98  5231.4  427.40  5250.9  427.97  5257.4  426.72
  5279.6  426.08  5293.9  426.92  5321.2  430.12  5364.3  432.29  5495.9  438.72
#Mann=8,-1,0
  4493.8    0.05       0  4741.2    0.07       0  4999.5    0.12       0
  5021.8    0.07       0  5025.8    0.12       0  5194.1    0.07       0
  5231.4    0.05       0  5364.3    0.16       0
Bank Sta=5021.8,5025.8
Exp/Cntr=0.3,0.1

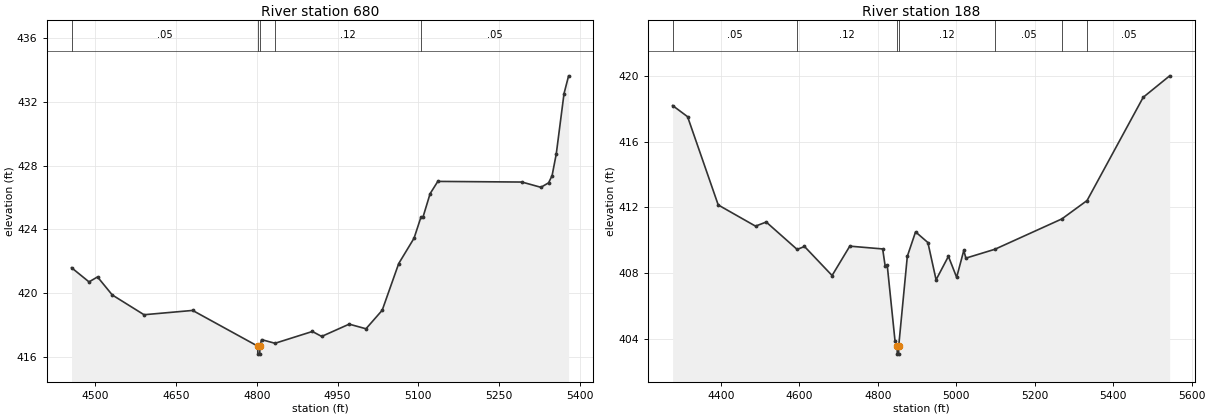
Type RM Length L Ch R = 1,680,492,492,492
BEGIN DESCRIPTION:
NORTH MINERAL CR TRIB 13 4 0
END DESCRIPTION:
XS GIS Cut Line= 4
      3499636.72     10388731.78      3499867.60     10388863.71
      3500246.07     10388783.85      3500418.51     10388575.21
#Sta/Elev= 30
  4455.9  421.60  4488.4  420.71  4504.2  421.02  4531.6  419.89  4590.6  418.65
  4680.9  418.92  4801.8  416.68  4802.0  416.18  4805.5  416.18  4805.8  416.68
  4808.9  417.09  4833.9  416.86  4903.3  417.60  4920.6  417.29  4971.7  418.06
  5002.9  417.77  5033.0  418.93  5063.7  421.86  5092.2  423.45  5104.8  424.75
  5108.6  424.75  5122.0  426.24  5136.3  427.01  5292.6  426.97  5327.8  426.64
  5342.1  426.92  5348.6  427.37  5356.4  428.74  5370.8  432.52  5379.3  433.63
#Mann=5,-1,0
  4455.9    0.05       0  4801.8    0.07       0  4805.8    0.05       0
  4833.9    0.12       0  5104.8    0.05       0
Bank Sta=4801.8,4805.8
Exp/Cntr=0.3,0.1

Type RM Length L Ch R = 1,188,0,0,0
BEGIN DESCRIPTION:
NORTH MINERAL CR TRIB 13 1 0
END DESCRIPTION:
XS GIS Cut Line= 3
      3499371.09     10389065.11      3500145.38     10389306.42
      3500518.77     10389045.40
#Sta/Elev= 30
  4277.4  418.20  4315.6  417.52  4393.7  412.14  4488.7  410.85  4516.0  411.10
  4594.8  409.43  4613.5  409.61  4683.8  407.84  4728.9  409.63  4812.7  409.46
  4819.1  408.41  4824.3  408.47  4844.1  403.87  4849.6  403.55  4849.9  403.05
  4853.4  403.05  4853.6  403.55  4875.5  409.01  4896.5  410.50  4927.9  409.85
  4948.8  407.58  4980.2  409.01  5001.2  407.73  5019.4  409.37  5024.7  408.90
  5098.6  409.44  5269.3  411.29  5333.5  412.41  5476.5  418.70  5544.0  420.01
#Mann=7,-1,0
  4277.4    0.05       0  4594.8    0.12       0  4849.6    0.07       0
  4853.6    0.12       0  5098.6    0.05       0  5269.3    0.12       0
  5333.5    0.05       0
Bank Sta=4849.6,4853.6
Exp/Cntr=0.3,0.1

Chan Stop Cuts=-1