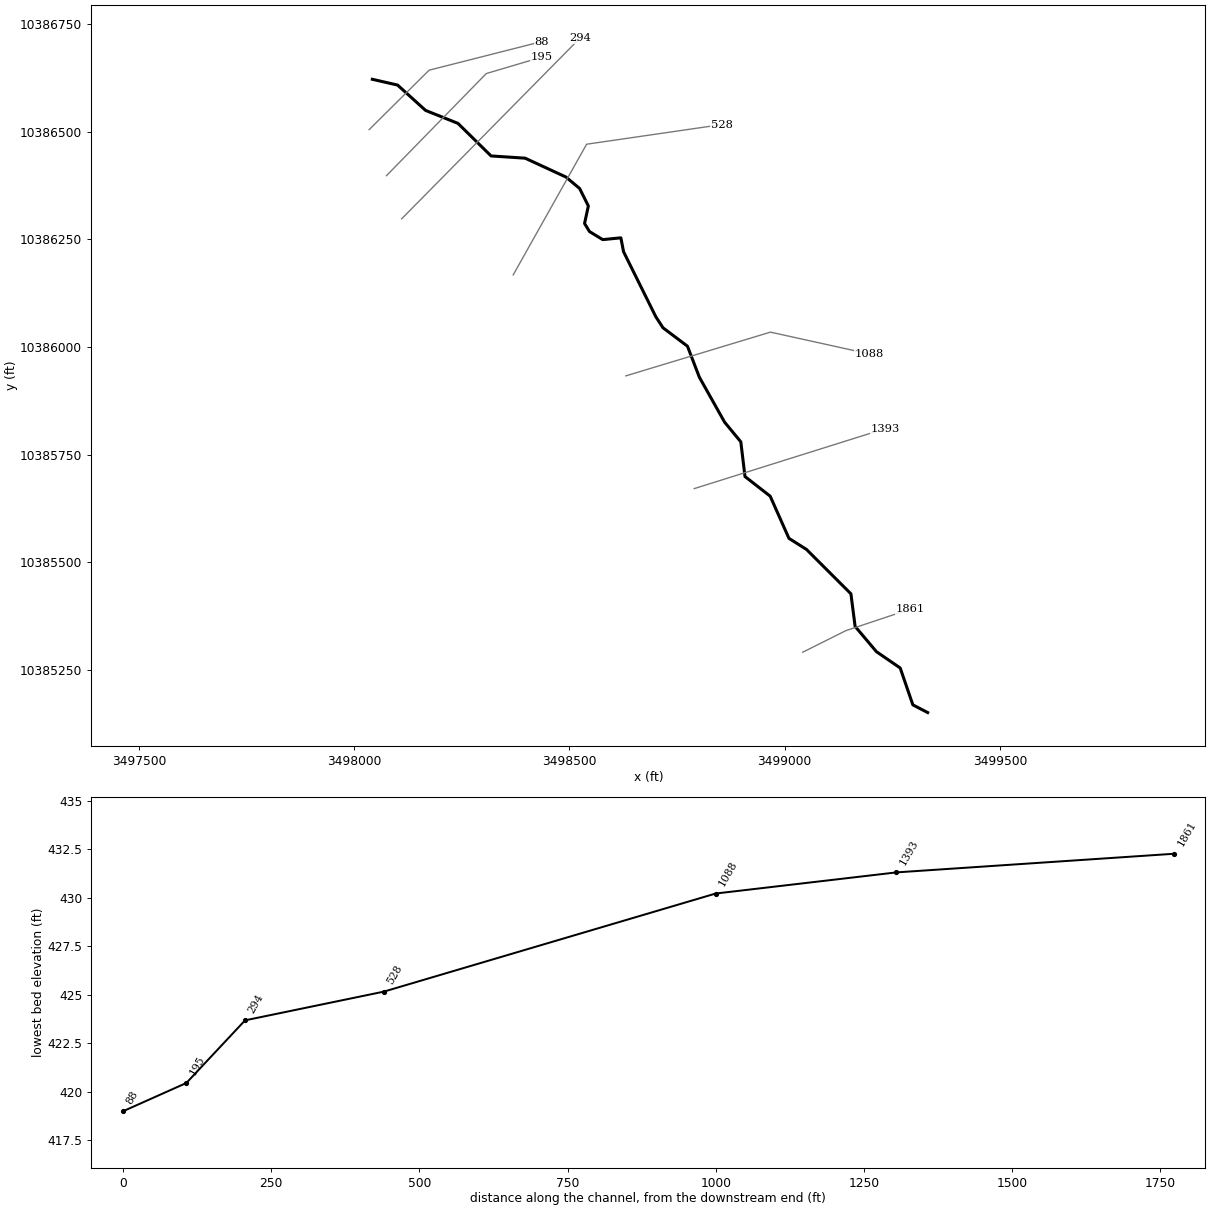
--- NORTH MINERAL CR TRIB 14 1.prj (project) ---

Proj Title=NORTH MINERAL CR TRIB 14 1 Base Level Engineering
Current Plan=p01
Default Exp/Contr=0.3,0.1
English Units
Geom File=g01
Flow File=f01
Plan File=p01
BEGIN DESCRIPTION:
NORTH MINERAL CR TRIB 14 1
END DESCRIPTION:

--- NORTH MINERAL CR TRIB 14 1.p01 (plan) ---

Plan Title=Multiple Run
Short Identifier=Multiple
Geom File=g01
Flow File=f01
Subcritical Flow
K Sum by GR= 0
Std Step Tol= 0.01
Critical Tol= 0.01
Num of Std Step Trials= 20
Max Error Tol= 0.3
Flow Tol Ratio= 0.001
Split Flow NTrial= 30
Split Flow Tol= 0.02
Split Flow Ratio= 0.02
Log Output Level= 0
Friction Slope Method= 1
Unsteady Friction Slope Method= 2
Unsteady Bridges Friction Slope Method= 1
Parabolic Critical Depth
Global Vel Dist=  1 , 1 , 1
Global Log Level= 0
CheckData=True
Encroach Param= -1, 0, 0, 0
BEGIN DESCRIPTION:
Multiple Run
END DESCRIPTION:

--- NORTH MINERAL CR TRIB 14 1.f01 (steady flow) ---

Flow Title=Multiple
Number of Profiles=7
Profile Names=10-year,25-year,50-year,1pct_min,100-year,1pct_plu,500-year
River Rch & RM= NORTH MINERAL CR,Reach-1,1861
     615     833    1010     897    1213    1641    1742
Boundary for River Rch & Prof#=NORTH MINERAL CR,Reach-1,1
Up Type=0
Dn Type=3
Dn Slope=0.005
Boundary for River Rch & Prof#=NORTH MINERAL CR,Reach-1,2
Up Type=0
Dn Type=3
Dn Slope=0.005
Boundary for River Rch & Prof#=NORTH MINERAL CR,Reach-1,3
Up Type=0
Dn Type=3
Dn Slope=0.005
Boundary for River Rch & Prof#=NORTH MINERAL CR,Reach-1,4
Up Type=0
Dn Type=3
Dn Slope=0.005
Boundary for River Rch & Prof#=NORTH MINERAL CR,Reach-1,5
Up Type=0
Dn Type=3
Dn Slope=0.005
Boundary for River Rch & Prof#=NORTH MINERAL CR,Reach-1,6
Up Type=0
Dn Type=3
Dn Slope=0.005
Boundary for River Rch & Prof#=NORTH MINERAL CR,Reach-1,7
Up Type=0
Dn Type=3
Dn Slope=0.005

--- NORTH MINERAL CR TRIB 14 1.g01 (geometry) ---

Geom Title=Existing Conditions

River Reach=NORTH MINERAL CR,Reach-1
Reach XY= 30
      3499332.30     10385151.55      3499297.88     10385169.39
      3499268.49     10385254.95      3499213.20     10385292.93
      3499163.72     10385351.56      3499153.95     10385427.24
      3499050.77     10385530.20      3499010.00     10385555.92
      3498966.40     10385653.86      3498907.87     10385699.44
      3498898.17     10385779.99      3498860.49     10385825.69
      3498801.80     10385930.15      3498774.19     10386002.02
      3498717.42     10386044.73      3498700.75     10386070.25
      3498625.75     10386221.30      3498619.50     10386253.59
      3498577.32     10386249.42      3498546.59     10386268.17
      3498535.13     10386286.92      3498543.98     10386327.55
      3498523.67     10386368.17      3498491.90     10386394.73
      3498397.11     10386438.48      3498317.94     10386443.69
      3498241.10     10386519.22      3498165.82     10386549.38
      3498100.79     10386608.19      3498042.11     10386621.64

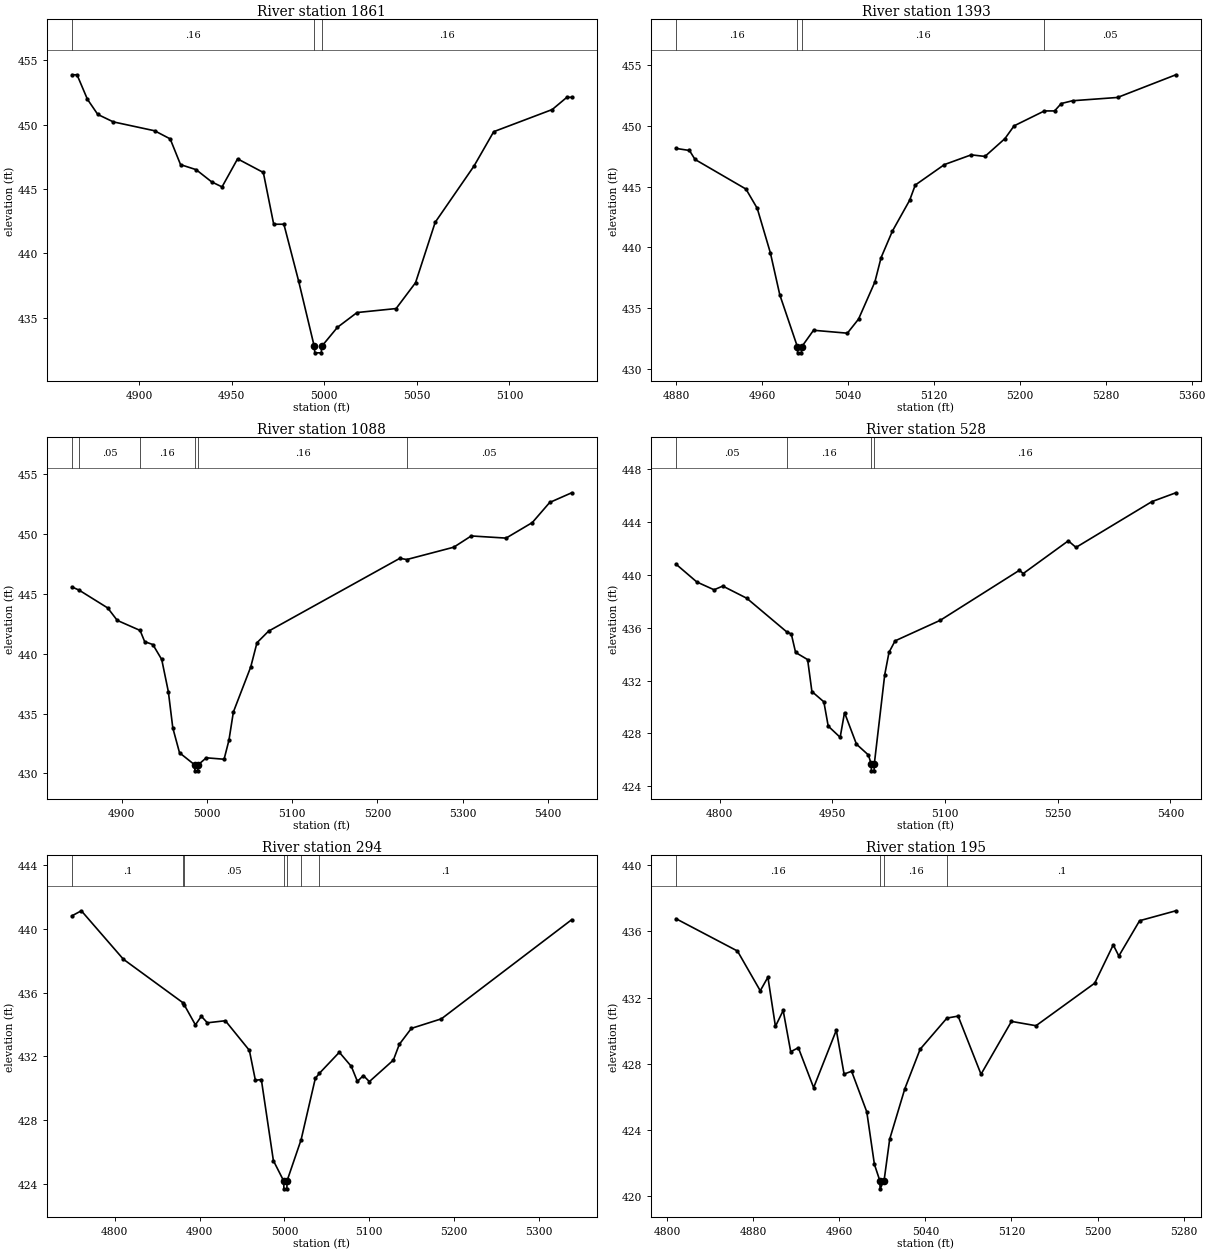
Type RM Length L Ch R = 1,1861,468,468,468
BEGIN DESCRIPTION:
NORTH MINERAL CR TRIB 14 1 8 0
END DESCRIPTION:
XS GIS Cut Line= 3
      3499042.08     10385291.63      3499142.11     10385341.64
      3499292.07     10385391.63
#Sta/Elev= 30
  4863.7  453.87  4866.5  453.87  4872.1  451.97  4877.7  450.79  4886.1  450.21
  4908.4  449.52  4916.8  448.89  4922.4  446.89  4930.8  446.50  4939.2  445.55
  4944.8  445.16  4953.2  447.34  4967.1  446.28  4972.7  442.26  4978.2  442.26
  4986.1  437.88  4994.6  432.77  4994.9  432.27  4998.4  432.27  4998.6  432.77
  5007.1  434.25  5017.7  435.40  5038.8  435.71  5049.3  437.72  5059.9  442.41
  5080.9  446.79  5091.5  449.45  5123.1  451.17  5131.0  452.12  5133.6  452.12
#Mann=3,-1,0
  4863.7    0.16       0  4994.6    0.07       0  4998.6    0.16       0
Bank Sta=4994.6,4998.6
Exp/Cntr=0.3,0.1

Type RM Length L Ch R = 1,1393,305,305,305
BEGIN DESCRIPTION:
NORTH MINERAL CR TRIB 14 1 3 0
END DESCRIPTION:
XS GIS Cut Line= 2
      3498789.95     10385671.42      3499233.91     10385810.73
#Sta/Elev= 30
  4880.0  448.16  4892.5  447.99  4897.7  447.25  4945.1  444.81  4955.6  443.22
  4967.8  439.56  4976.6  436.09  4993.0  431.81  4993.2  431.31  4996.7  431.31
  4997.0  431.81  5008.0  433.17  5039.5  432.93  5049.9  434.09  5065.1  437.15
  5070.9  439.16  5081.4  441.34  5097.5  443.89  5102.7  445.14  5129.9  446.83
  5154.8  447.63  5167.6  447.50  5186.2  448.97  5194.7  450.02  5222.9  451.25
  5232.4  451.25  5238.6  451.86  5249.1  452.09  5291.0  452.36  5345.3  454.23
#Mann=4,-1,0
  4880.0    0.16       0  4993.0    0.07       0  4997.0    0.16       0
  5222.9    0.05       0
Bank Sta=4993,4997
Exp/Cntr=0.3,0.1

Type RM Length L Ch R = 1,1088,560,560,560
BEGIN DESCRIPTION:
NORTH MINERAL CR TRIB 14 1 2 0
END DESCRIPTION:
XS GIS Cut Line= 3
      3498631.10     10385933.14      3498966.99     10386034.69
      3499197.26     10385983.96
#Sta/Elev= 30
  4841.3  445.60  4849.8  445.33  4883.4  443.84  4894.6  442.80  4921.4  441.96
  4926.8  441.02  4936.4  440.78  4946.8  439.53  4954.6  436.83  4959.8  433.81
  4967.7  431.73  4985.5  430.72  4985.7  430.22  4989.2  430.22  4989.5  430.72
  4999.1  431.31  5020.0  431.19  5025.7  432.78  5030.9  435.14  5051.3  438.91
  5058.6  440.93  5072.2  441.90  5226.3  447.99  5234.5  447.89  5289.6  448.92
  5310.1  449.86  5351.0  449.68  5381.8  450.98  5402.2  452.66  5428.0  453.47
#Mann=6,-1,0
  4841.3    0.16       0  4849.8    0.05       0  4921.4    0.16       0
  4985.5    0.07       0  4989.5    0.16       0  5234.5    0.05       0
Bank Sta=4985.5,4989.5
Exp/Cntr=0.3,0.1

Type RM Length L Ch R = 1,528,234,234,234
BEGIN DESCRIPTION:
NORTH MINERAL CR TRIB 14 1 7 0
END DESCRIPTION:
XS GIS Cut Line= 3
      3498369.35     10386167.53      3498539.91     10386470.89
      3498853.69     10386516.46
#Sta/Elev= 30
  4742.1  440.82  4769.8  439.47  4792.7  438.88  4804.3  439.16  4836.2  438.24
  4889.6  435.68  4895.5  435.53  4901.2  434.13  4917.2  433.59  4922.9  431.17
  4938.8  430.39  4944.6  428.55  4960.5  427.70  4966.3  429.57  4982.2  427.18
  4998.1  426.36  5001.9  425.66  5002.1  425.16  5005.6  425.16  5005.9  425.66
  5019.8  432.44  5025.5  434.14  5033.6  435.01  5093.8  436.57  5199.1  440.36
  5204.1  440.11  5264.1  442.59  5274.3  442.09  5375.3  445.56  5407.2  446.23
#Mann=4,-1,0
  4742.1    0.05       0  4889.6    0.16       0  5001.9    0.07       0
  5005.9    0.16       0
Bank Sta=5001.9,5005.9
Exp/Cntr=0.3,0.1

Type RM Length L Ch R = 1,294,99,99,99
BEGIN DESCRIPTION:
NORTH MINERAL CR TRIB 14 1 6 0
END DESCRIPTION:
XS GIS Cut Line= 2
      3498110.22     10386297.71      3498524.09     10386716.79
#Sta/Elev= 30
  4749.5  440.81  4760.7  441.13  4810.2  438.09  4880.4  435.36  4881.9  435.23
  4895.1  433.97  4902.1  434.51  4909.2  434.10  4930.4  434.23  4958.7  432.37
  4965.8  430.49  4972.8  430.54  4987.0  425.45  4999.1  424.18  4999.4  423.68
  5002.9  423.68  5003.1  424.18  5019.7  426.77  5036.4  430.61  5041.2  430.93
  5064.7  432.25  5078.9  431.36  5086.0  430.42  5093.0  430.79  5100.1  430.41
  5128.4  431.76  5135.4  432.75  5149.6  433.75  5185.0  434.35  5338.5  440.57
#Mann=7,-1,0
  4749.5     0.1       0  4880.4    0.16       0  4881.9    0.05       0
  4999.1   0.035       0  5003.1    0.05       0  5019.7    0.16       0
  5041.2     0.1       0
Bank Sta=4999.1,5003.1
Exp/Cntr=0.3,0.1

Type RM Length L Ch R = 1,195,107,107,107
BEGIN DESCRIPTION:
NORTH MINERAL CR TRIB 14 1 4 0
END DESCRIPTION:
XS GIS Cut Line= 3
      3498075.04     10386397.95      3498306.83     10386634.95
      3498434.45     10386672.72
#Sta/Elev= 30
  4808.2  436.76  4865.3  434.81  4886.5  432.41  4893.6  433.23  4900.6  430.26
  4907.8  431.22  4914.8  428.73  4921.9  428.97  4936.1  426.56  4957.2  430.03
  4964.4  427.38  4971.4  427.55  4985.5  425.10  4992.6  421.93  4997.6  420.95
  4997.9  420.45  5001.6  420.95  5006.8  423.45  5020.9  426.50  5035.1  428.88
  5060.0  430.76  5070.4  430.88  5091.7  427.37  5120.0  430.56  5142.8  430.30
  5197.4  432.87  5214.6  435.18  5219.8  434.51  5239.1  436.64  5272.8  437.24
#Mann=4,-1,0
  4808.2    0.16       0  4997.6    0.07       0  5001.6    0.16       0
  5060.0     0.1       0
Bank Sta=4997.6,5001.6
Exp/Cntr=0.3,0.1

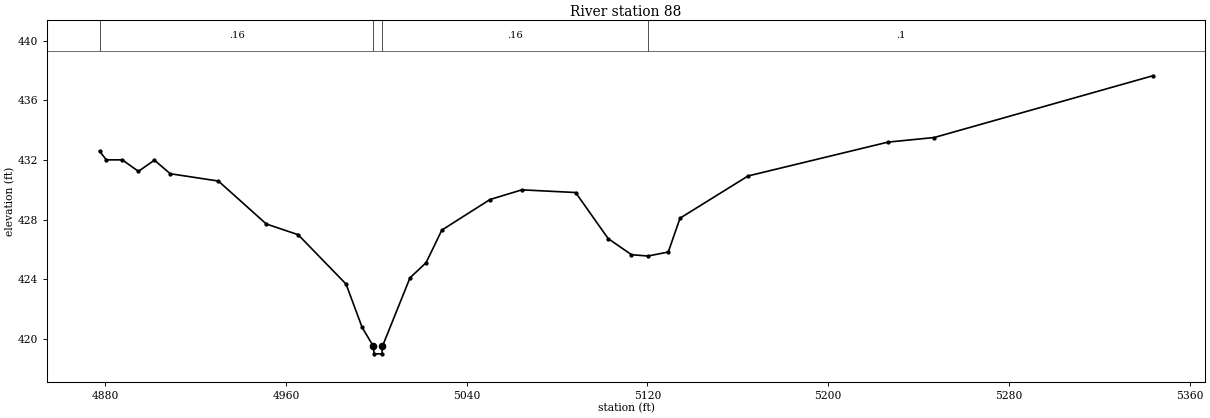
Type RM Length L Ch R = 1,88,0,0,0
BEGIN DESCRIPTION:
NORTH MINERAL CR TRIB 14 1 1 0
END DESCRIPTION:
XS GIS Cut Line= 3
      3498034.70     10386504.75      3498174.02     10386642.77
      3498435.72     10386709.17
#Sta/Elev= 30
  4877.5  432.59  4880.5  432.00  4887.6  432.00  4894.7  431.23  4901.8  431.98
  4908.8  431.07  4930.1  430.58  4951.3  427.70  4965.4  426.98  4986.6  423.67
  4993.7  420.77  4998.7  419.49  4999.0  418.99  5002.5  418.99  5002.7  419.49
  5014.9  424.09  5022.0  425.10  5029.0  427.29  5050.3  429.34  5064.4  429.99
  5088.2  429.81  5102.6  426.72  5112.9  425.64  5120.2  425.55  5129.2  425.82
  5134.4  428.09  5164.5  430.92  5226.4  433.19  5246.9  433.50  5343.6  437.64
#Mann=4,-1,0
  4877.5    0.16       0  4998.7    0.07       0  5002.7    0.16       0
  5120.2     0.1       0
Bank Sta=4998.7,5002.7
Exp/Cntr=0.3,0.1

Chan Stop Cuts=-1