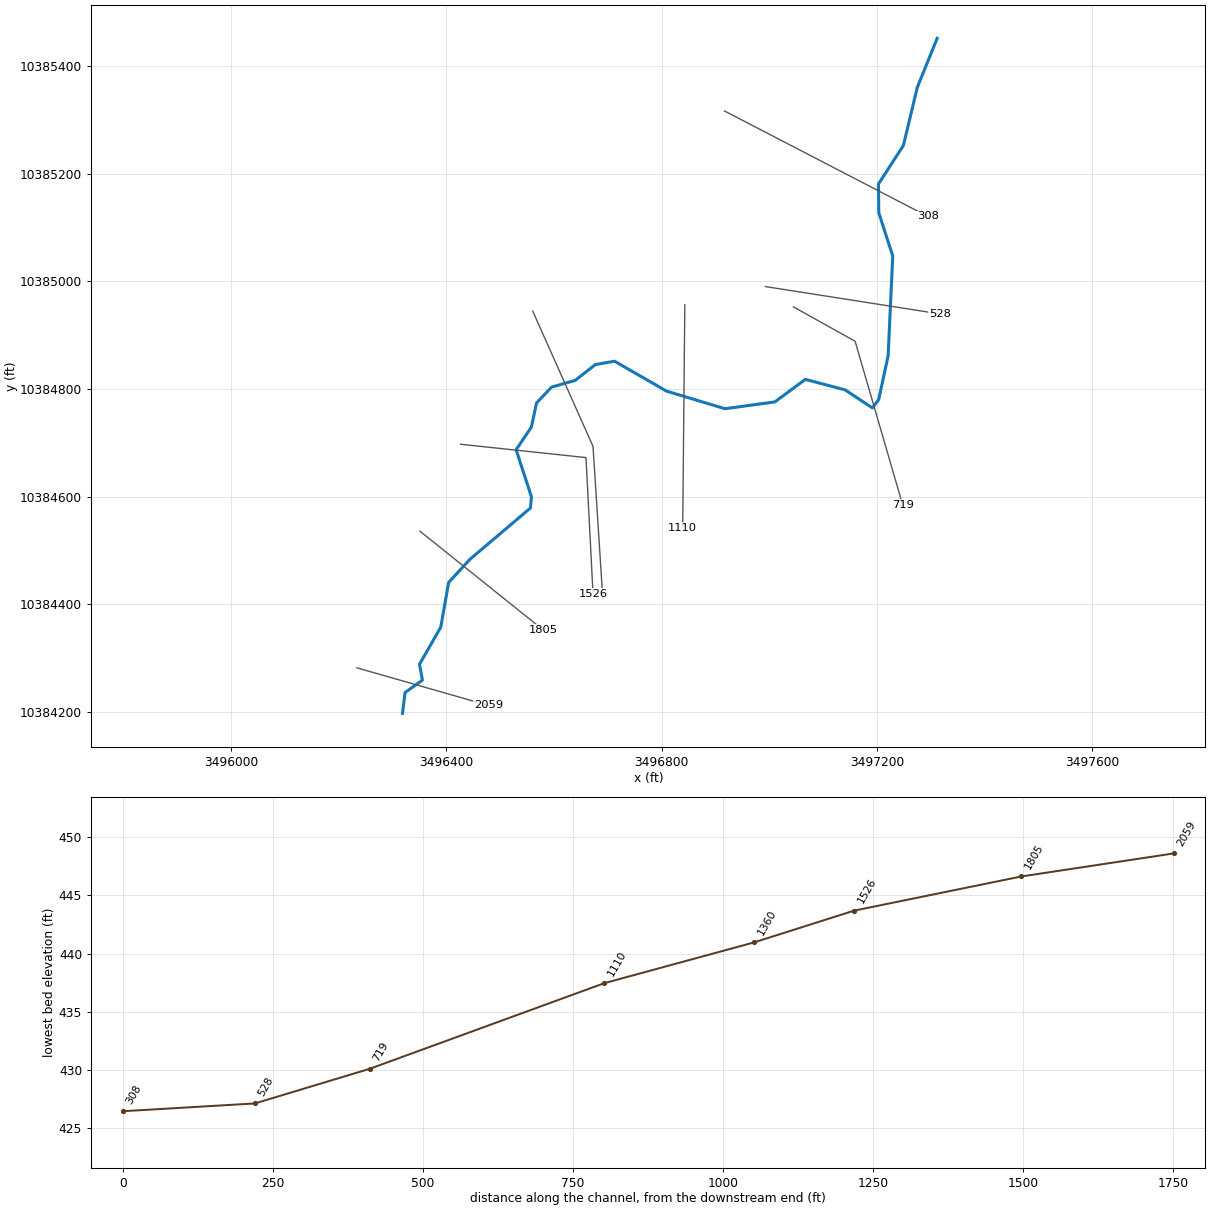
--- NORTH MINERAL CR TRIB 14 2.prj (project) ---

Proj Title=NORTH MINERAL CR TRIB 14 2 Base Level Engineering
Current Plan=p01
Default Exp/Contr=0.3,0.1
English Units
Geom File=g01
Flow File=f01
Plan File=p01
BEGIN DESCRIPTION:
NORTH MINERAL CR TRIB 14 2
END DESCRIPTION:

--- NORTH MINERAL CR TRIB 14 2.p01 (plan) ---

Plan Title=Multiple Run
Short Identifier=Multiple
Geom File=g01
Flow File=f01
Subcritical Flow
K Sum by GR= 0
Std Step Tol= 0.01
Critical Tol= 0.01
Num of Std Step Trials= 20
Max Error Tol= 0.3
Flow Tol Ratio= 0.001
Split Flow NTrial= 30
Split Flow Tol= 0.02
Split Flow Ratio= 0.02
Log Output Level= 0
Friction Slope Method= 1
Unsteady Friction Slope Method= 2
Unsteady Bridges Friction Slope Method= 1
Parabolic Critical Depth
Global Vel Dist=  1 , 1 , 1
Global Log Level= 0
CheckData=True
Encroach Param= -1, 0, 0, 0
BEGIN DESCRIPTION:
Multiple Run
END DESCRIPTION:

--- NORTH MINERAL CR TRIB 14 2.f01 (steady flow) ---

Flow Title=Multiple
Number of Profiles=7
Profile Names=10-year,25-year,50-year,1pct_min,100-year,1pct_plu,500-year
River Rch & RM= NORTH MINERAL CR,Reach-1,2059
     633     864    1054     942    1273    1722    1850
Boundary for River Rch & Prof#=NORTH MINERAL CR,Reach-1,1
Up Type=0
Dn Type=3
Dn Slope=0.005
Boundary for River Rch & Prof#=NORTH MINERAL CR,Reach-1,2
Up Type=0
Dn Type=3
Dn Slope=0.005
Boundary for River Rch & Prof#=NORTH MINERAL CR,Reach-1,3
Up Type=0
Dn Type=3
Dn Slope=0.005
Boundary for River Rch & Prof#=NORTH MINERAL CR,Reach-1,4
Up Type=0
Dn Type=3
Dn Slope=0.005
Boundary for River Rch & Prof#=NORTH MINERAL CR,Reach-1,5
Up Type=0
Dn Type=3
Dn Slope=0.005
Boundary for River Rch & Prof#=NORTH MINERAL CR,Reach-1,6
Up Type=0
Dn Type=3
Dn Slope=0.005
Boundary for River Rch & Prof#=NORTH MINERAL CR,Reach-1,7
Up Type=0
Dn Type=3
Dn Slope=0.005

--- NORTH MINERAL CR TRIB 14 2.g01 (geometry) ---

Geom Title=Existing Conditions

River Reach=NORTH MINERAL CR,Reach-1
Reach XY= 30
      3496318.81     10384197.45      3496323.58     10384236.22
      3496355.79     10384259.19      3496350.38     10384288.77
      3496389.90     10384357.60      3496404.48     10384440.68
      3496444.31     10384483.91      3496556.54     10384579.07
      3496558.32     10384599.98      3496529.83     10384687.24
      3496558.30     10384729.42      3496567.77     10384774.16
      3496595.73     10384803.61      3496639.63     10384816.14
      3496677.02     10384845.43      3496712.61     10384851.83
      3496809.28     10384796.20      3496918.07     10384763.49
      3497010.69     10384776.18      3497067.18     10384817.99
      3497141.14     10384798.47      3497191.84     10384765.00
      3497203.56     10384780.63      3497221.03     10384861.66
      3497229.64     10385047.22      3497203.69     10385127.49
      3497203.14     10385181.06      3497249.46     10385252.73
      3497275.20     10385360.36      3497312.11     10385451.64

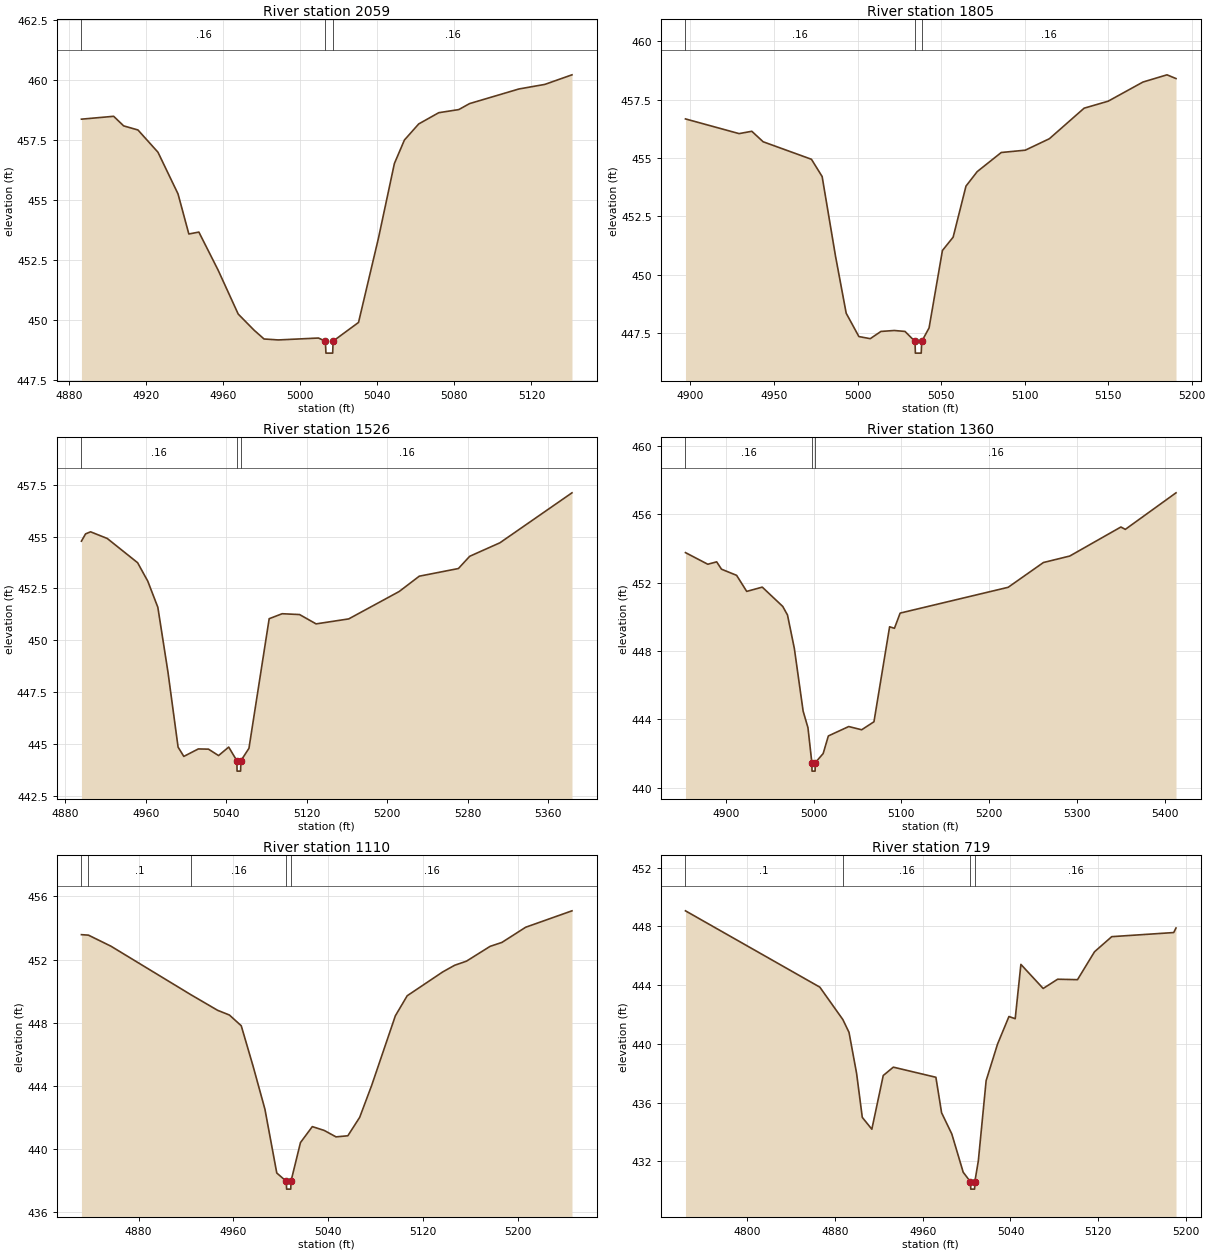
Type RM Length L Ch R = 1,2059,254,254,254
BEGIN DESCRIPTION:
NORTH MINERAL CR TRIB 14 2 5 0
END DESCRIPTION:
XS GIS Cut Line= 2
      3496233.97     10384282.07      3496478.58     10384212.19
#Sta/Elev= 29
  4886.6  458.37  4903.3  458.49  4908.5  458.09  4915.9  457.92  4926.3  456.99
  4936.7  455.25  4942.3  453.58  4947.5  453.66  4957.5  452.07  4967.9  450.24
  4976.1  449.57  4981.3  449.20  4988.7  449.16  5009.5  449.24  5013.1  449.11
  5013.4  448.61  5016.9  448.61  5017.1  449.11  5030.3  449.89  5040.7  453.43
  5048.9  456.52  5054.1  457.50  5061.5  458.17  5071.9  458.64  5082.3  458.77
  5087.9  459.02  5113.5  459.63  5126.9  459.82  5141.0  460.22
#Mann=3,-1,0
  4886.6    0.16       0  5013.1    0.07       0  5017.1    0.16       0
Bank Sta=5013.1,5017.1
Exp/Cntr=0.3,0.1

Type RM Length L Ch R = 1,1805,279,279,279
BEGIN DESCRIPTION:
Mapping XS 0bebf195
END DESCRIPTION:
XS GIS Cut Line= 2
      3496351.10     10384536.00      3496580.24     10384352.43
#Sta/Elev= 30
  4897.0  456.67  4929.1  456.04  4936.7  456.14  4943.5  455.69  4972.4  454.94
  4978.8  454.20  4986.8  450.79  4993.2  448.34  5000.8  447.34  5007.6  447.25
  5014.0  447.56  5022.0  447.60  5028.4  447.56  5034.4  447.13  5034.6  446.63
  5038.1  446.63  5038.4  447.13  5042.8  447.71  5050.8  451.03  5057.2  451.60
  5064.9  453.79  5071.6  454.41  5086.0  455.23  5100.4  455.33  5114.8  455.82
  5135.6  457.13  5150.0  457.43  5170.8  458.25  5185.2  458.56  5190.6  458.40
#Mann=3,-1,0
  4897.0    0.16       0  5034.4    0.07       0  5038.4    0.16       0
Bank Sta=5034.4,5038.4
Exp/Cntr=0.3,0.1

Type RM Length L Ch R = 1,1526,166,166,166
BEGIN DESCRIPTION:
NORTH MINERAL CR TRIB 14 2 3 0
END DESCRIPTION:
XS GIS Cut Line= 3
      3496426.62     10384697.45      3496659.70     10384672.71
      3496672.72     10384420.14
#Sta/Elev= 30
  4896.2  454.78  4900.3  455.13  4905.3  455.23  4921.8  454.91  4952.0  453.74
  4962.1  452.85  4972.1  451.59  4982.2  448.45  4992.2  444.85  4997.9  444.40
  5012.3  444.76  5022.4  444.75  5032.4  444.44  5042.5  444.85  5050.6  444.19
  5050.8  443.69  5054.3  443.69  5054.6  444.19  5062.6  444.79  5082.7  451.04
  5095.6  451.28  5112.9  451.24  5129.3  450.79  5161.7  451.03  5211.8  452.35
  5231.8  453.09  5270.7  453.46  5281.9  454.05  5311.9  454.70  5383.5  457.11
#Mann=3,-1,0
  4896.2    0.16       0  5050.6    0.07       0  5054.6    0.16       0
Bank Sta=5050.6,5054.6
Exp/Cntr=0.3,0.1

Type RM Length L Ch R = 1,1360,250,250,250
BEGIN DESCRIPTION:
Mapping XS e54518ee
END DESCRIPTION:
XS GIS Cut Line= 3
      3496560.76     10384944.80      3496672.72     10384693.55
      3496690.95     10384411.01
#Sta/Elev= 30
  4854.3  453.76  4879.7  453.08  4889.8  453.22  4895.3  452.79  4912.5  452.43
  4924.0  451.49  4941.7  451.74  4965.0  450.61  4970.4  450.11  4978.2  448.15
  4988.2  444.48  4993.7  443.51  4998.1  441.47  4998.3  440.97  5001.8  440.97
  5002.1  441.47  5011.0  442.00  5016.9  443.03  5040.1  443.58  5054.8  443.39
  5068.8  443.86  5086.6  449.42  5092.1  449.33  5098.6  450.22  5221.5  451.73
  5261.6  453.18  5291.6  453.56  5349.8  455.26  5354.8  455.12  5412.5  457.26
#Mann=3,-1,0
  4854.3    0.16       0  4998.1    0.07       0  5002.1    0.16       0
Bank Sta=4998.1,5002.1
Exp/Cntr=0.3,0.1

Type RM Length L Ch R = 1,1110,391,391,391
BEGIN DESCRIPTION:
NORTH MINERAL CR TRIB 14 2 4 0
END DESCRIPTION:
XS GIS Cut Line= 2
      3496843.29     10384956.58      3496839.39     10384542.50
#Sta/Elev= 30
  4831.7  453.58  4837.6  453.55  4856.6  452.85  4924.0  449.78  4946.6  448.79
  4956.6  448.49  4966.6  447.81  4976.6  445.25  4986.6  442.52  4996.6  438.48
  5004.6  437.96  5004.9  437.46  5008.4  437.46  5008.6  437.96  5016.6  440.41
  5026.6  441.42  5036.6  441.18  5046.6  440.77  5056.6  440.84  5066.6  442.01
  5076.7  444.03  5096.7  448.44  5106.7  449.71  5136.7  451.22  5146.7  451.64
  5156.7  451.90  5176.7  452.84  5186.7  453.09  5206.7  454.05  5245.8  455.09
#Mann=5,-1,0
  4831.7    0.16       0  4837.6     0.1       0  4924.0    0.16       0
  5004.6    0.07       0  5008.6    0.16       0
Bank Sta=5004.6,5008.6
Exp/Cntr=0.3,0.1

Type RM Length L Ch R = 1,719,191,191,191
BEGIN DESCRIPTION:
NORTH MINERAL CR TRIB 14 2 2 0
END DESCRIPTION:
XS GIS Cut Line= 3
      3497045.10     10384952.67      3497159.70     10384888.86
      3497247.89     10384585.39
#Sta/Elev= 30
  4743.7  449.06  4866.2  443.86  4887.2  441.65  4892.8  440.78  4899.7  437.99
  4904.9  434.99  4913.6  434.18  4924.0  437.84  4933.2  438.41  4972.0  437.72
  4977.2  435.30  4986.5  433.86  4996.9  431.25  5003.5  430.60  5003.8  430.10
  5007.3  430.10  5007.5  430.60  5010.7  432.03  5017.8  437.49  5028.2  439.98
  5038.6  441.86  5044.3  441.71  5049.5  445.41  5069.8  443.77  5083.0  444.40
  5101.1  444.37  5116.6  446.27  5132.3  447.30  5188.8  447.58  5190.9  447.89
#Mann=4,-1,0
  4743.7     0.1       0  4887.2    0.16       0  5003.5    0.07       0
  5007.5    0.16       0
Bank Sta=5003.5,5007.5
Exp/Cntr=0.3,0.1

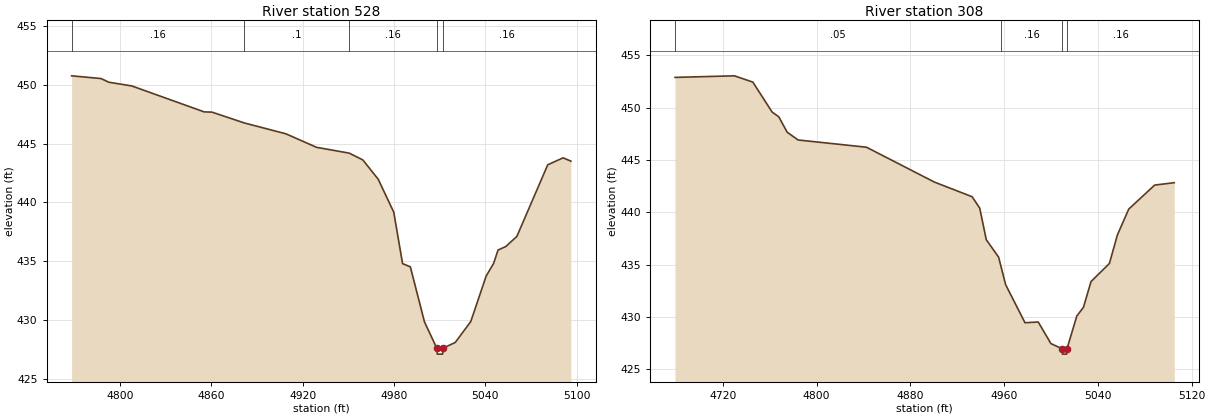
Type RM Length L Ch R = 1,528,220,220,220
BEGIN DESCRIPTION:
Mapping XS bcc18cb8
END DESCRIPTION:
XS GIS Cut Line= 2
      3496993.00     10384990.43      3497317.15     10384939.66
#Sta/Elev= 30
  4768.1  450.75  4787.4  450.52  4792.5  450.21  4807.7  449.89  4855.2  447.69
  4860.3  447.67  4881.6  446.75  4908.9  445.83  4929.1  444.68  4950.5  444.19
  4959.5  443.61  4969.6  441.97  4979.8  439.18  4985.6  434.81  4990.7  434.54
  5000.0  429.86  5008.1  427.63  5008.4  427.13  5011.9  427.13  5012.1  427.63
  5020.2  428.12  5030.4  429.89  5040.5  433.75  5045.5  434.85  5048.3  435.96
  5053.4  436.26  5060.7  437.12  5081.0  443.20  5091.1  443.79  5096.2  443.51
#Mann=5,-1,0
  4768.1    0.16       0  4881.6     0.1       0  4950.5    0.16       0
  5008.1    0.07       0  5012.1    0.16       0
Bank Sta=5008.1,5012.1
Exp/Cntr=0.3,0.1

Type RM Length L Ch R = 1,308,0,0,0
BEGIN DESCRIPTION:
NORTH MINERAL CR TRIB 14 2 1 0
END DESCRIPTION:
XS GIS Cut Line= 2
      3496917.12     10385316.64      3497295.12     10385120.63
#Sta/Elev= 30
  4679.3  452.90  4730.0  453.05  4745.7  452.45  4762.2  449.58  4767.8  449.14
  4775.0  447.66  4784.3  446.92  4842.6  446.23  4900.5  442.90  4932.7  441.50
  4939.2  440.41  4944.8  437.39  4955.3  435.73  4957.6  434.72  4961.3  433.10
  4977.8  429.46  4989.1  429.53  4999.9  427.47  5009.6  426.96  5009.8  426.46
  5013.3  426.46  5013.6  426.96  5022.0  430.10  5027.7  430.94  5034.1  433.39
  5049.8  435.12  5056.6  437.84  5066.3  440.32  5088.4  442.61  5105.1  442.84
#Mann=4,-1,0
  4679.3    0.05       0  4957.6    0.16       0  5009.6    0.07       0
  5013.6    0.16       0
Bank Sta=5009.6,5013.6
Exp/Cntr=0.3,0.1

Chan Stop Cuts=-1