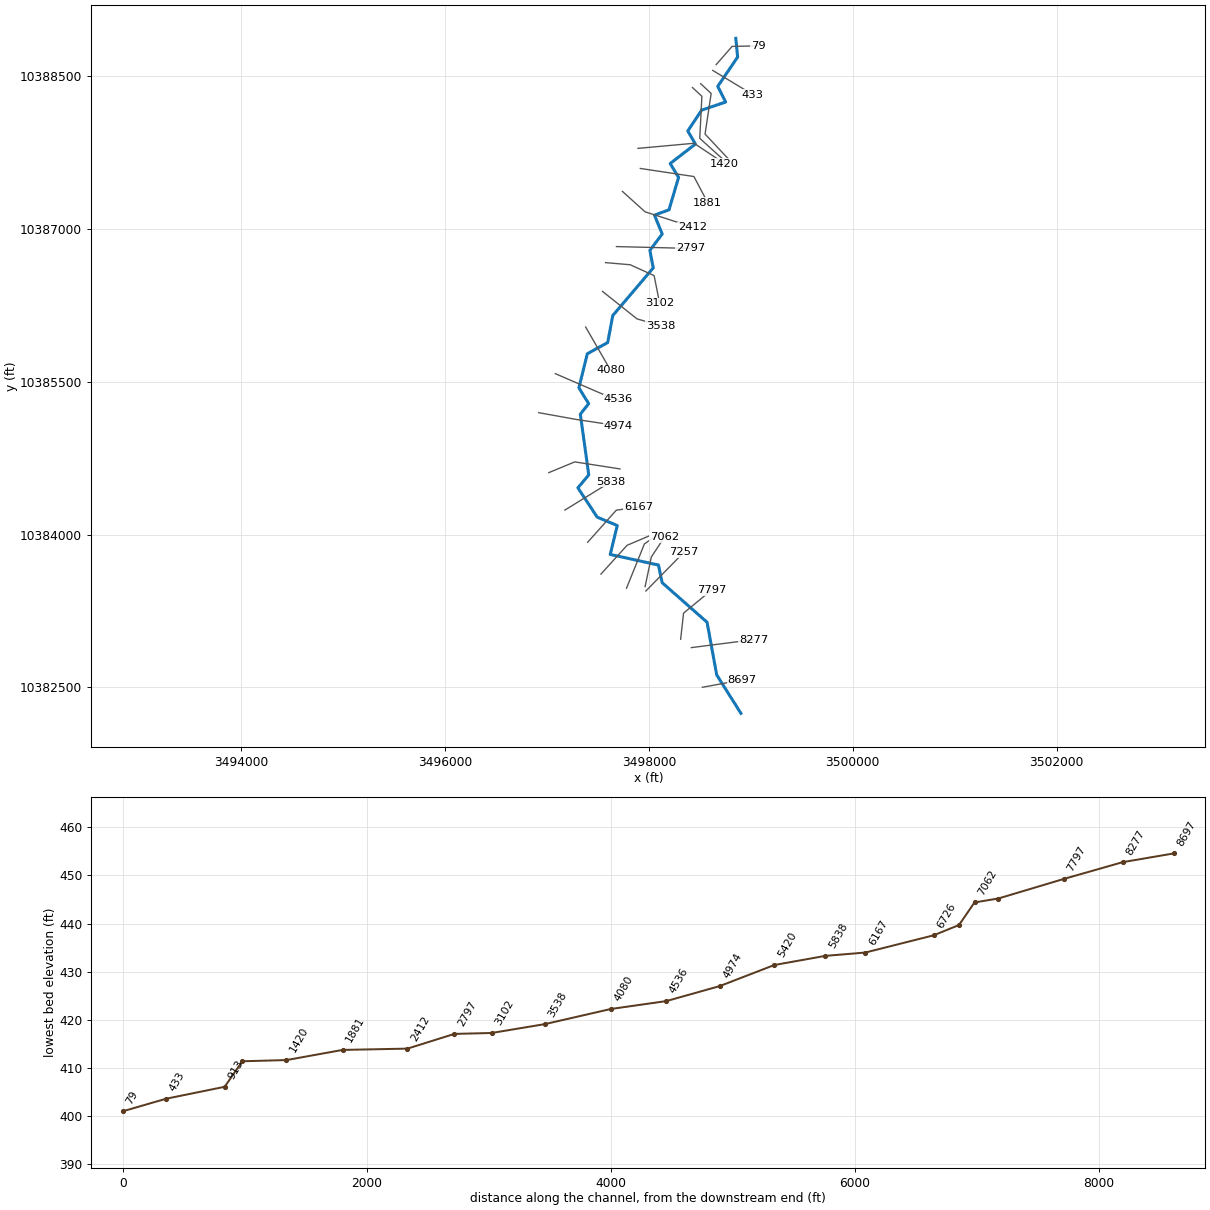
--- NORTH MINERAL CR TRIB 14.prj (project) ---

Proj Title=NORTH MINERAL CR TRIB 14 Base Level Engineering
Current Plan=p01
Default Exp/Contr=0.3,0.1
English Units
Geom File=g01
Flow File=f01
Plan File=p01
Y Axis Title=Elevation
X Axis Title(PF)=Main Channel Distance
X Axis Title(XS)=Station
BEGIN DESCRIPTION:
NORTH MINERAL CR TRIB 14
END DESCRIPTION:
DSS Export Rating Curves= 0
DSS Export Rating Curve Sorted= 0
DSS Export Volume Flow Curves= 0
DXF OffsetX= 0
DXF OffsetY= 0
DXF ScaleX= 1
DXF ScaleY= 10

--- NORTH MINERAL CR TRIB 14.p01 (plan) ---

Plan Title=Multiple Run
Short Identifier=Multiple
Geom File=g01
Flow File=f01
Subcritical Flow
K Sum by GR= 0
Std Step Tol= 0.01
Critical Tol= 0.01
Num of Std Step Trials= 20
Max Error Tol= 0.3
Flow Tol Ratio= 0.001
Split Flow NTrial= 30
Split Flow Tol= 0.02
Split Flow Ratio= 0.02
Log Output Level= 0
Friction Slope Method= 1
Unsteady Friction Slope Method= 2
Unsteady Bridges Friction Slope Method= 1
Parabolic Critical Depth
Global Vel Dist=  1 , 1 , 1
Global Log Level= 0
CheckData=True
Encroach Param= -1, 0, 0, 0
BEGIN DESCRIPTION:
Multiple Run
END DESCRIPTION:

--- NORTH MINERAL CR TRIB 14.f01 (steady flow) ---

Flow Title=Multiple
Program Version=4.10
Number of Profiles= 7
Profile Names=10-year,25-year,50-year,1pct_min,100-year,1pct_plu,500-year
River Rch & RM=NORTH MINERAL CR,Reach-1         ,8697
     907    1256    1545    1388    1878    2539    2766
River Rch & RM=NORTH MINERAL CR,Reach-1         ,4974
    1266    1786    2225    2022    2735    3699    4123
River Rch & RM=NORTH MINERAL CR,Reach-1         ,4536
    1266    1786    2225    2022    2735    3699    4123
River Rch & RM=NORTH MINERAL CR,Reach-1         ,2797
    1597    2277    2856    2611    3531    4775    5389
Boundary for River Rch & Prof#=NORTH MINERAL CR,Reach-1         , 1
Up Type= 0
Dn Type= 3
Dn Slope=0.005
Boundary for River Rch & Prof#=NORTH MINERAL CR,Reach-1         , 2
Up Type= 0
Dn Type= 3
Dn Slope=0.005
Boundary for River Rch & Prof#=NORTH MINERAL CR,Reach-1         , 3
Up Type= 0
Dn Type= 3
Dn Slope=0.005
Boundary for River Rch & Prof#=NORTH MINERAL CR,Reach-1         , 4
Up Type= 0
Dn Type= 3
Dn Slope=0.005
Boundary for River Rch & Prof#=NORTH MINERAL CR,Reach-1         , 5
Up Type= 0
Dn Type= 3
Dn Slope=0.005
Boundary for River Rch & Prof#=NORTH MINERAL CR,Reach-1         , 6
Up Type= 0
Dn Type= 3
Dn Slope=0.005
Boundary for River Rch & Prof#=NORTH MINERAL CR,Reach-1         , 7
Up Type= 0
Dn Type= 3
Dn Slope=0.005
DSS Import GetInterval= 0
DSS Import GetPeak= 0
DSS Import FillOption= 0

--- NORTH MINERAL CR TRIB 14.g01 (geometry) ---

Geom Title=Existing Conditions
Program Version=4.10

River Reach=NORTH MINERAL CR,Reach-1
Reach XY= 30
      3498902.41     10382245.97      3498664.81     10382622.91
      3498569.97     10383140.48      3498129.43     10383528.44
      3498092.84      10383701.8      3497619.59     10383805.97
      3497688.47      10384089.6      3497492.14      10384171.5
      3497302.16     10384459.82      3497408.75     10384586.53
      3497326.15     10385182.36      3497407.82     10385286.06
      3497311.82     10385441.07      3497394.65     10385775.72
      3497594.62     10385885.78      3497644.43     10386150.72
      3498041.53     10386618.19      3498008.91     10386790.48
      3498130.01     10386951.52       3498053.8     10387136.05
      3498196.44     10387188.73      3498290.59     10387507.59
      3498207.77     10387642.95      3498455.69     10387833.92
      3498380.69     10387962.39      3498516.53     10388166.94
      3498752.62     10388246.45      3498674.82      10388400.5
      3498869.94     10388687.55      3498852.11     10388871.64

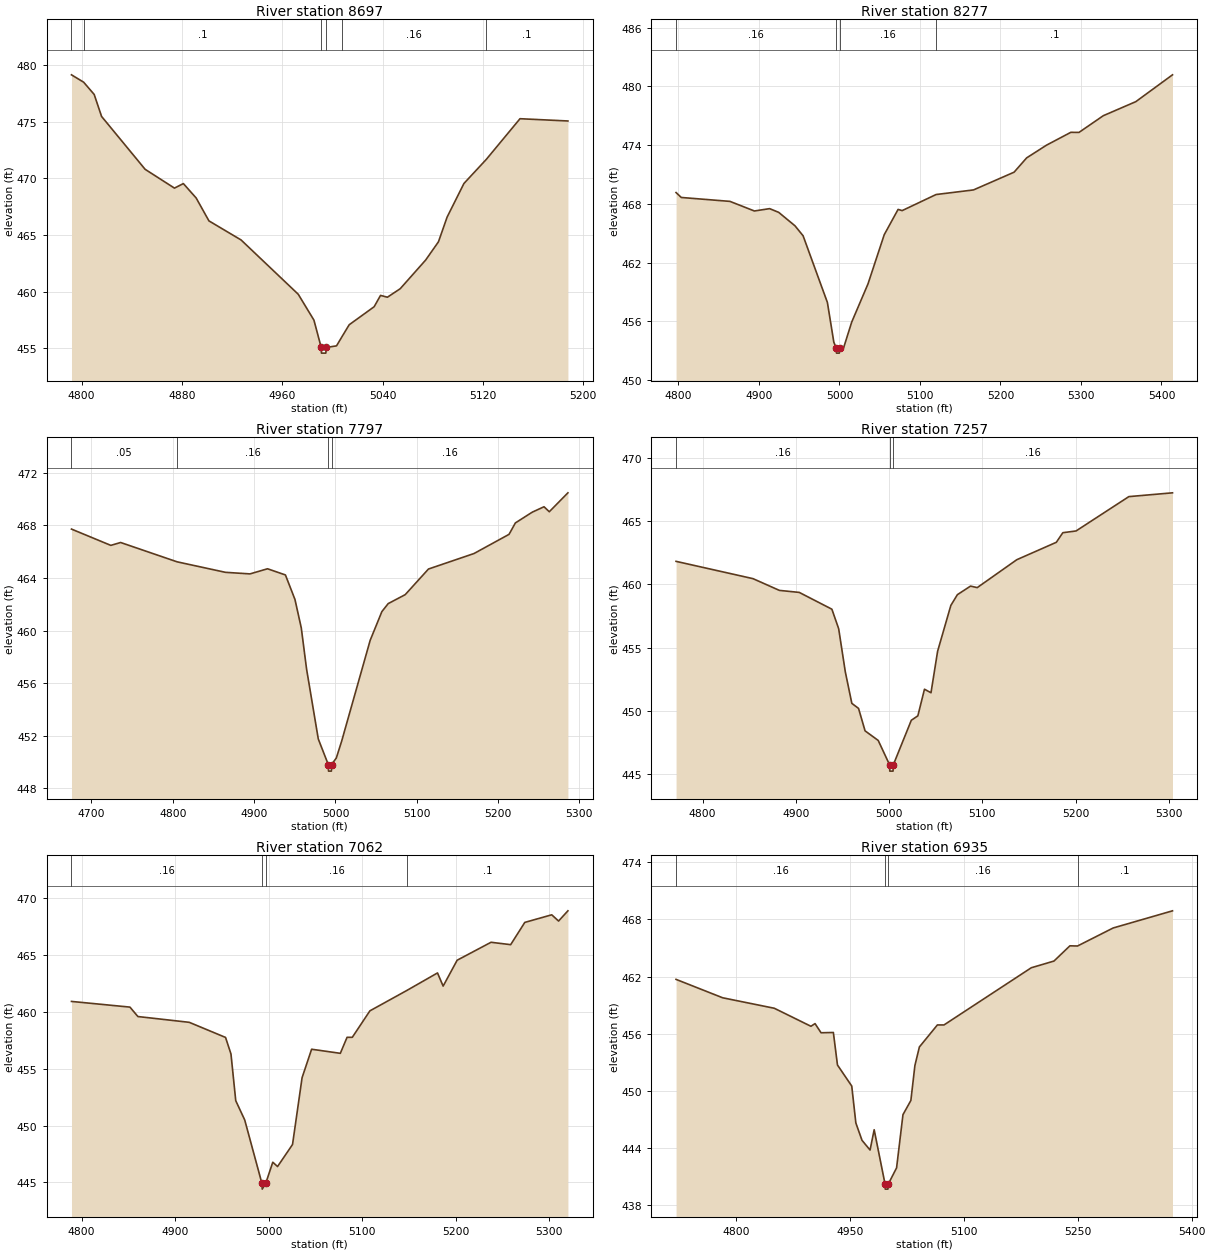
Type RM Length L Ch R = 1 ,8697    ,420,420,420
BEGIN DESCRIPTION:
NORTH MINERAL CR TRIB 14 21 0
END DESCRIPTION:
XS GIS Cut Line= 2
      3498524.33     10382502.15       3498913.6     10382573.75
#Sta/Elev= 30
  4791.9  479.13  4801.6  478.48    4810   477.4  4815.9  475.46  4850.6   470.8
    4874  469.14  4881.1  469.54  4891.3  468.27  4901.5  466.25  4927.1  464.57
  4972.7  459.78  4985.2   457.5    4991  455.09  4991.2  454.59  4994.7  454.59
    4995  455.09  5003.2  455.23  5007.9   456.1  5013.3  457.09  5033.2  458.68
  5038.3  459.68  5043.8  459.52    5054  460.27  5074.3   462.8  5084.5  464.41
  5091.4  466.59  5104.8  469.55  5122.6  471.67  5149.5  475.26  5187.7  475.06
#Mann= 6 ,-1 , 0
  4791.9     .05       0  4801.6      .1       0    4991     .07       0
    4995      .1       0  5007.9     .16       0  5122.6      .1       0
Bank Sta=4991,4995
XS Rating Curve= 0 ,0
Exp/Cntr=0.3,0.1

Type RM Length L Ch R = 1 ,8277    ,480,480,480
BEGIN DESCRIPTION:
NORTH MINERAL CR TRIB 14 2 0
END DESCRIPTION:
XS GIS Cut Line= 2
      3498415.61     10382891.44      3499027.35     10382969.54
#Sta/Elev= 30
    4797  469.16  4803.5  468.66    4864  468.26  4894.3  467.28  4913.2  467.52
  4924.5  467.14  4944.7  465.77  4954.8  464.75    4985  457.94    4993  453.88
  4996.1  453.27  4996.3  452.77  4999.8  452.77  5000.1  453.27  5005.2  453.33
  5015.2  455.94  5035.4  459.83  5055.6  464.86  5072.8  467.44  5077.9  467.32
    5120  468.96  5166.5  469.43  5216.9  471.24  5232.5   472.7  5257.2     474
  5287.4  475.31  5297.5   475.3  5327.8  477.01  5368.1  478.44  5413.7  481.18
#Mann= 4 ,-1 , 0
    4797     .16       0  4996.1     .07       0  5000.1     .16       0
    5120      .1       0
Bank Sta=4996.1,5000.1
XS Rating Curve= 0 ,0
Exp/Cntr=0.3,0.1

Type RM Length L Ch R = 1 ,7797    ,540,540,540
BEGIN DESCRIPTION:
NORTH MINERAL CR TRIB 14 18 0
END DESCRIPTION:
XS GIS Cut Line= 3
      3498310.74     10382973.51      3498339.39     10383230.01
       3498611.5     10383453.95
#Sta/Elev= 30
  4675.4  467.72  4723.8  466.48  4735.8   466.7  4805.2  465.23  4864.7  464.43
  4894.9  464.31  4916.5   464.7  4938.5  464.23  4950.2  462.37    4958   460.2
  4964.5  457.07  4978.9  451.75  4991.2   449.8  4991.5   449.3    4995   449.3
  4995.2   449.8  5001.1   450.3  5007.6  451.57  5042.7  459.25  5057.1  461.44
  5064.9  462.05  5085.8  462.73  5114.4  464.68  5170.4  465.86  5213.5  467.32
  5221.3  468.19  5242.1  469.01  5256.5  469.42    5263  469.04  5285.9  470.48
#Mann= 4 ,-1 , 0
  4675.4     .05       0  4805.2     .16       0  4991.2     .07       0
  4995.2     .16       0
Bank Sta=4991.2,4995.2
XS Rating Curve= 0 ,0
Exp/Cntr=0.3,0.1

Type RM Length L Ch R = 1 ,7257    ,195,195,195
BEGIN DESCRIPTION:
NORTH MINERAL CR TRIB 14 15 1
END DESCRIPTION:
XS GIS Cut Line= 2
      3497969.59     10383447.44      3498342.78     10383827.14
#Sta/Elev= 30
  4771.6  461.83  4854.1  460.46  4882.4  459.53  4903.7  459.37  4938.7  458.04
    4946  456.49  4953.1  453.08  4960.1  450.58  4967.3  450.18  4974.3   448.4
  4988.4  447.64  5000.6  445.71  5000.8  445.21  5004.3  445.21  5004.6  445.71
  5023.9  449.24  5030.9  449.59    5038   451.7    5045  451.42  5052.1  454.71
  5066.3  458.34  5073.3  459.19  5087.4  459.87  5094.6  459.75    5137  461.96
  5179.4  463.34  5186.4   464.1  5200.6  464.24  5257.2  466.96    5304  467.26
#Mann= 3 ,-1 , 0
  4771.6     .16       0  5000.6     .07       0  5004.6     .16       0
Bank Sta=5000.6,5004.6
XS Rating Curve= 0 ,0
Exp/Cntr=0.3,0.1

Type RM Length L Ch R = 1 ,7062    ,127,127,127
BEGIN DESCRIPTION:
NORTH MINERAL CR TRIB 14 17 0
END DESCRIPTION:
XS GIS Cut Line= 3
      3497961.79     10383490.46      3498022.98     10383780.79
      3498151.87     10383976.08
#Sta/Elev= 30
  4789.2  460.93  4851.7  460.43  4860.2   459.6  4915.1  459.09  4953.9  457.76
  4959.7   456.3  4964.8  452.19  4974.4  450.49  4992.8   444.9  4993.1   444.4
  4996.8   444.9  5004.4  446.77  5009.5  446.39  5025.5  448.33  5035.7  454.21
  5045.9  456.72  5076.6  456.36  5083.8  457.77  5089.4  457.77  5108.2   460.1
    5148  461.91  5180.5  463.44  5186.5  462.28  5201.5  464.56  5237.7  466.14
  5258.7  465.93  5273.8  467.89  5302.6  468.56  5309.9  468.01  5319.9  468.91
#Mann= 4 ,-1 , 0
  4789.2     .16       0  4992.8     .07       0  4996.8     .16       0
    5148      .1       0
Bank Sta=4992.8,4996.8
XS Rating Curve= 0 ,0
Exp/Cntr=0.3,0.1

Type RM Length L Ch R = 1 ,6935    ,209,209,209
BEGIN DESCRIPTION:
NORTH MINERAL CR TRIB 14 15 0
END DESCRIPTION:
XS GIS Cut Line= 3
      3497779.48     10383474.78      3497955.27     10383909.69
      3498107.33     10384013.66
#Sta/Elev= 30
  4721.5   461.7  4782.8  459.77  4850.8  458.67    4899  456.78  4904.4  457.06
  4912.3   456.1  4928.5  456.13  4933.9  452.72  4952.7  450.51  4958.1  446.64
  4966.2  444.82  4976.8   443.8  4982.2  445.93  4996.6   440.2  4996.8   439.7
  5000.3   439.7  5000.6   440.2  5011.7  441.93  5020.1  447.51  5030.5     449
  5035.8  452.66  5041.7  454.61  5065.4  456.92  5074.1  456.92    5189  462.92
  5218.8  463.62  5239.8  465.22  5249.8   465.2  5296.7  467.09  5374.8  468.89
#Mann= 4 ,-1 , 0
  4721.5     .16       0  4996.6     .07       0  5000.6     .16       0
  5249.8      .1       0
Bank Sta=4996.6,5000.6
XS Rating Curve= 0 ,0
Exp/Cntr=0.3,0.1

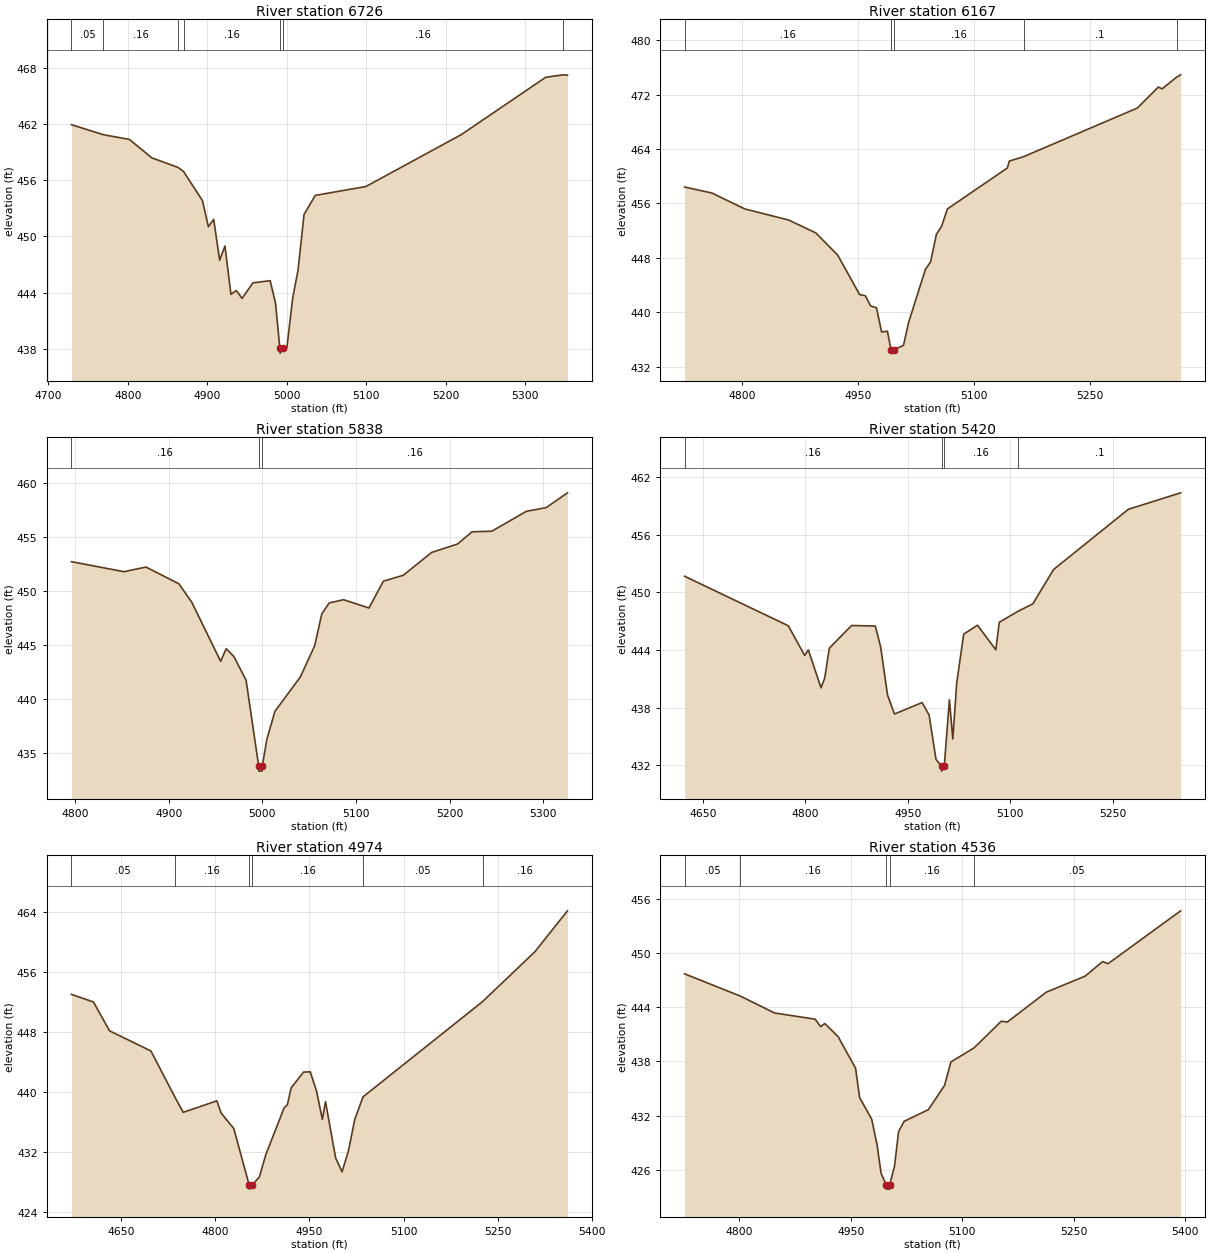
Type RM Length L Ch R = 1 ,6726    ,559,559,559
BEGIN DESCRIPTION:
NORTH MINERAL CR TRIB 14 16 0
END DESCRIPTION:
XS GIS Cut Line= 3
      3497528.18      10383612.8       3497784.7     10383895.37
      3498007.23     10383990.37
#Sta/Elev= 30
  4729.3  461.92  4769.5  460.85  4802.1  460.35  4830.4  458.38  4863.1  457.37
  4870.3  456.92    4894  453.82  4901.4  451.04  4908.1  451.82  4915.6  447.47
  4922.3  448.98  4929.8  443.82  4936.5  444.23  4943.8  443.39  4957.5  445.05
  4979.1  445.28  4985.9  442.86  4991.3  438.05  4991.6  437.55  4995.3  438.05
  5000.1  438.12  5007.5  443.45  5014.2  446.42  5021.7  452.34  5035.9  454.38
  5099.4  455.32  5219.2  460.85  5325.6  466.98  5347.6  467.24  5352.9   467.2
#Mann= 7 ,-1 , 0
  4729.3     .05       0  4769.5     .16       0  4863.1     .05       0
  4870.3     .16       0  4991.3     .07       0  4995.3     .16       0
  5347.6      .1       0
Bank Sta=4991.3,4995.3
XS Rating Curve= 0 ,0
Exp/Cntr=0.3,0.1

Type RM Length L Ch R = 1 ,6167    ,329,329,329
BEGIN DESCRIPTION:
NORTH MINERAL CR TRIB 14 14 1
END DESCRIPTION:
XS GIS Cut Line= 3
      3497397.95     10383925.28      3497679.23     10384240.42
      3497897.58     10384270.32
#Sta/Elev= 30
    4725   458.4  4760.4  457.52    4803  455.18  4859.9  453.55    4895  451.66
  4923.4  448.39  4951.8  442.59  4959.3  442.41  4966.1  440.91  4973.6  440.66
  4980.3  437.09  4987.8   437.2  4992.5  434.48  4992.7  433.98  4996.5  434.48
  5008.7  435.13  5015.4  438.53  5037.1   446.3  5043.8   447.4  5051.3  451.45
    5058  452.61  5065.5  455.17  5143.3  461.21  5145.8  462.22  5164.2  462.86
  5311.8  470.02  5338.9   473.1  5343.9  472.84  5362.5  474.55  5367.8   474.9
#Mann= 5 ,-1 , 0
    4725     .16       0  4992.5     .07       0  4996.5     .16       0
  5164.2      .1       0  5362.5     .15       0
Bank Sta=4992.5,4996.5
XS Rating Curve= 0 ,0
Exp/Cntr=0.3,0.1

Type RM Length L Ch R = 1 ,5838    ,418,418,418
BEGIN DESCRIPTION:
NORTH MINERAL CR TRIB 14 14 0
END DESCRIPTION:
XS GIS Cut Line= 2
       3497174.3     10384241.29      3497625.67     10384519.06
#Sta/Elev= 30
    4796  452.72  4852.1  451.79  4875.6  452.22  4910.8  450.67  4924.6  448.95
  4955.4  443.47  4961.3  444.64  4969.6  443.91  4982.6  441.71    4996  433.78
  4996.2  433.28  4999.7  433.28    5000  433.78  5004.8  436.24  5013.4  438.83
  5040.5  442.01  5055.9  444.92  5063.5  447.88  5071.4  448.89  5086.8  449.19
  5113.9  448.42  5129.3  450.91  5150.6  451.46  5180.9  453.58  5208.6  454.36
    5224  455.49  5245.3  455.55    5282  457.39  5303.3  457.74    5326  459.11
#Mann= 3 ,-1 , 0
    4796     .16       0    4996     .07       0    5000     .16       0
Bank Sta=4996,5000
XS Rating Curve= 0 ,0
Exp/Cntr=0.3,0.1

Type RM Length L Ch R = 1 ,5420    ,446,446,446
BEGIN DESCRIPTION:
NORTH MINERAL CR TRIB 14 12 0
END DESCRIPTION:
XS GIS Cut Line= 3
      3497016.46     10384608.91      3497271.68     10384714.38
      3497715.69     10384645.37
#Sta/Elev= 30
  4623.5  451.68  4775.2  446.52  4799.1  443.42  4804.5     444    4823  440.06
  4828.4  441.06  4835.2  444.19  4867.7  446.55  4902.4  446.49  4910.2  444.34
  4920.3   439.3  4930.5  437.33  4970.9  438.52  4981.1  437.23  4991.2  432.61
  4999.3  431.88  4999.5  431.38  5003.3  431.88  5010.8  438.82  5015.8  434.73
  5021.5  440.55  5031.7  445.65  5051.9  446.58  5078.7  444.02  5083.8  446.89
  5111.2  448.03  5132.9  448.81  5163.2  452.38  5272.5  458.65    5349  460.37
#Mann= 4 ,-1 , 0
  4623.5     .16       0  4999.3     .07       0  5003.3     .16       0
  5111.2      .1       0
Bank Sta=4999.3,5003.3
XS Rating Curve= 0 ,0
Exp/Cntr=0.3,0.1

Type RM Length L Ch R = 1 ,4974    ,438,438,438
BEGIN DESCRIPTION:
NORTH MINERAL CR TRIB 14 13 0
END DESCRIPTION:
XS GIS Cut Line= 3
      3496917.52     10385197.45        3497286.     10385131.05
      3497697.27     10385068.58
#Sta/Elev= 30
  4570.7  452.96  4605.8  451.94  4631.4   448.1  4697.3  445.42  4735.6  439.26
  4748.8  437.24  4802.4  438.77  4809.1  437.16  4829.4  435.08    4854  427.51
  4854.2  427.01    4858  427.51    4870  428.61  4880.2  431.55  4909.6  437.84
  4914.7  438.23  4920.8   440.5  4940.6  442.61  4951.3  442.63  4961.4  440.02
  4970.5  436.29  4975.5  438.66  4991.7  431.16  5001.9  429.31    5012  432.09
  5022.1  436.27  5035.3   439.3  5225.7  451.99  5308.9  458.61  5361.1  464.09
#Mann= 6 ,-1 , 0
  4570.7     .05       0  4735.6     .16       0    4854     .07       0
    4858     .16       0  5035.3     .05       0  5225.7     .16       0
Bank Sta=4854,4858
XS Rating Curve= 0 ,0
Exp/Cntr=0.3,0.1

Type RM Length L Ch R = 1 ,4536    ,456,456,456
BEGIN DESCRIPTION:
NORTH MINERAL CR TRIB 14 11 1
END DESCRIPTION:
XS GIS Cut Line= 4
      3497080.98     10385580.23      3497597.44     10385356.72
      3497601.78     10385356.72      3497697.75     10385326.86
#Sta/Elev= 30
  4726.3  447.68  4801.3  445.22  4847.4  443.35  4901.9  442.67  4909.4  441.85
  4914.9  442.19  4932.9  440.74  4956.4  437.25  4961.9     434  4978.1  431.62
  4985.3   428.8  4990.8  425.61  4997.6  424.39  4997.9  423.89    5002  423.89
  5002.3  424.39  5008.8  426.42  5014.3  430.23  5021.7  431.38  5054.4  432.67
  5076.2  435.35  5084.7  437.94  5115.8  439.49  5152.5  442.44  5160.6  442.35
  5213.1  445.65  5265.5  447.43  5288.9  449.03  5296.3   448.8  5393.9  454.64
#Mann= 5 ,-1 , 0
  4726.3     .05       0  4801.3     .16       0  4997.6     .07       0
  5002.3     .16       0  5115.8     .05       0
Bank Sta=4997.6,5002.3
XS Rating Curve= 0 ,0
Exp/Cntr=0.3,0.1

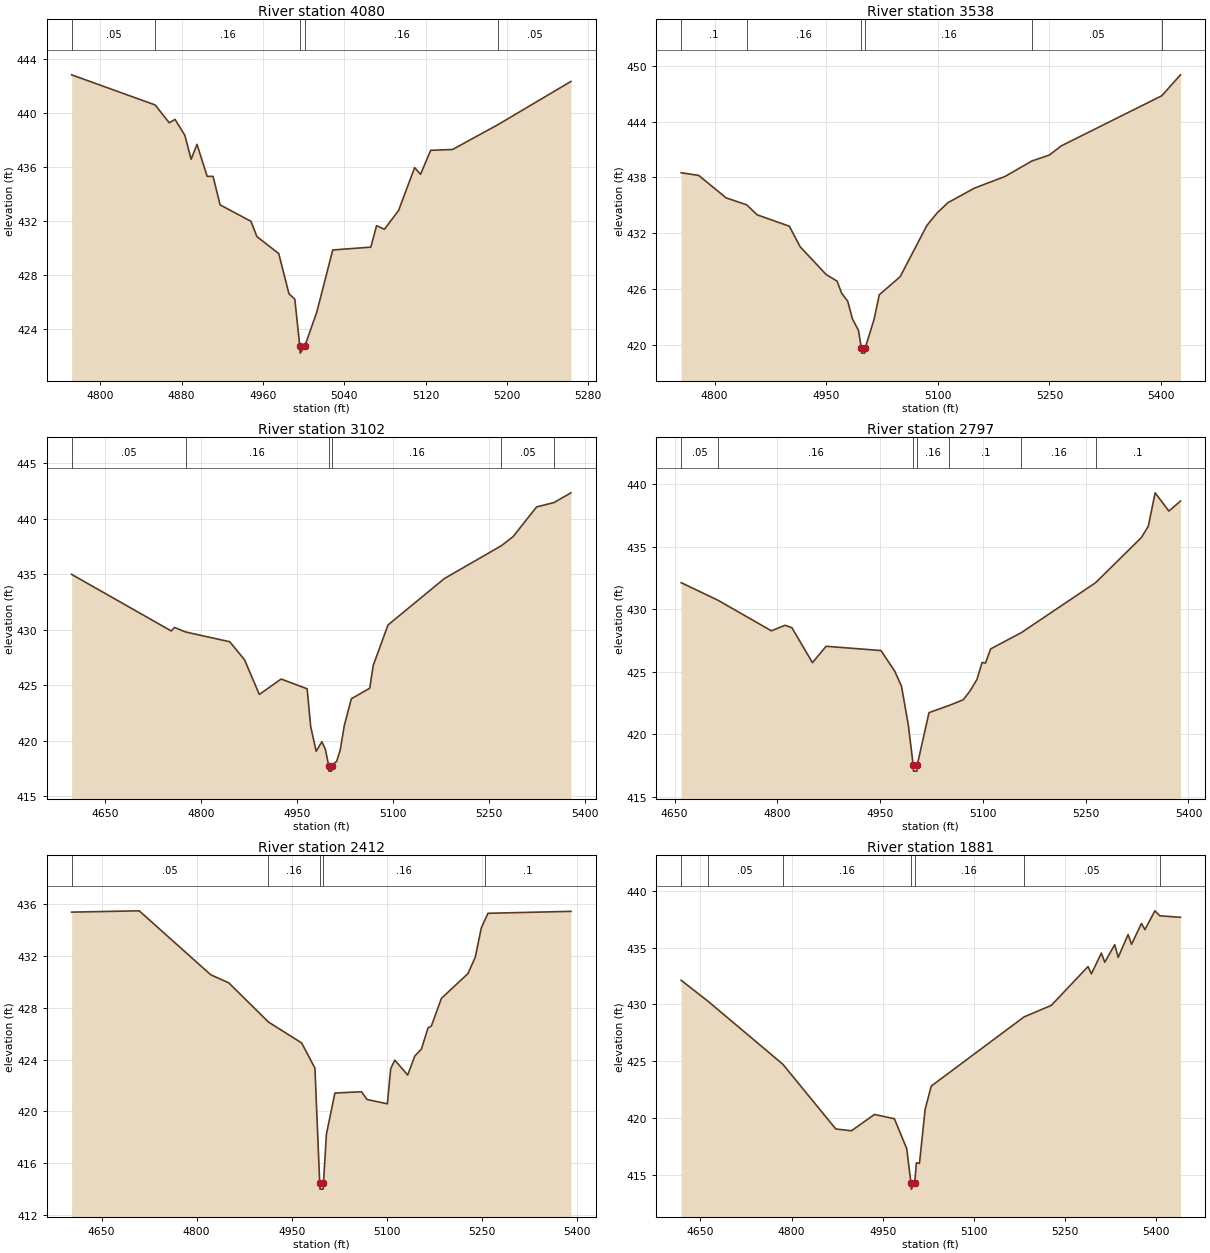
Type RM Length L Ch R = 1 ,4080    ,542,542,542
BEGIN DESCRIPTION:
NORTH MINERAL CR TRIB 14 29 0
END DESCRIPTION:
XS GIS Cut Line= 2
      3497378.25     10386038.15      3497623.49     10385612.78
#Sta/Elev= 30
  4771.9  442.85    4854  440.62  4867.9   439.3  4873.6  439.55  4883.3  438.36
  4889.4   436.6  4895.2   437.7  4905.2  435.33    4911  435.33  4917.9  433.22
  4948.3     432  4954.1  430.87  4975.6  429.61  4985.6  426.64  4991.4  426.23
  4996.3  422.74  4996.7  422.24  5001.1  422.74    5013  425.28  5028.7  429.88
  5066.1  430.09  5071.8  431.68  5079.5  431.41  5093.4   432.8  5109.2  435.98
    5115  435.48    5125  437.26  5146.5  437.32  5191.4  439.17  5262.9  442.36
#Mann= 5 ,-1 , 0
  4771.9     .05       0    4854     .16       0  4996.3     .07       0
  5001.1     .16       0  5191.4     .05       0
Bank Sta=4996.3,5001.1
XS Rating Curve= 0 ,0
Exp/Cntr=0.3,0.1

Type RM Length L Ch R = 1 ,3538    ,436,436,436
BEGIN DESCRIPTION:
NORTH MINERAL CR TRIB 14 19 0
END DESCRIPTION:
XS GIS Cut Line= 3
      3497543.84     10386387.54      3497882.36     10386118.03
      3498111.49     10386052.93
#Sta/Elev= 30
  4755.1  438.51  4778.7  438.22  4815.6   435.8  4843.1  435.06  4857.2  433.98
  4900.5  432.75  4914.9  430.55  4950.1  427.54  4964.5  426.85  4970.9  425.52
  4978.9  424.68  4985.3  422.77  4993.4  421.53  4997.3  419.59  4997.6  419.09
  5001.8  419.09  5002.2  419.59  5014.2  422.69  5021.3  425.37  5049.4  427.32
  5085.2  432.82    5099  434.18  5113.5  435.28  5149.1  436.85  5190.3  438.11
  5226.3  439.77  5249.9  440.42  5265.8   441.4    5401   446.8    5426  449.05
#Mann= 6 ,-1 , 0
  4755.1      .1       0  4843.1     .16       0  4997.3     .07       0
  5002.2     .16       0  5226.3     .05       0    5401      .1       0
Bank Sta=4997.3,5002.2
XS Rating Curve= 0 ,0
Exp/Cntr=0.3,0.1

Type RM Length L Ch R = 1 ,3102    ,305,305,305
BEGIN DESCRIPTION:
NORTH MINERAL CR TRIB 14 9 0
END DESCRIPTION:
XS GIS Cut Line= 4
      3497573.71     10386670.11      3497815.95     10386649.28
      3498050.32     10386542.51      3498105.01      10386269.1
#Sta/Elev= 30
  4598.2  434.98  4753.8  429.88  4758.8   430.2  4776.1  429.79  4845.1  428.91
  4868.2  427.28  4891.2  424.16  4925.3  425.55  4965.9  424.67  4971.4  421.28
    4980  419.04  4988.9   419.9  4994.4  419.21  4999.5  417.75  4999.8  417.25
    5004  417.25  5004.4  417.75    5012  418.14  5017.5  419.14  5023.9  421.35
  5034.9  423.77  5063.6  424.72  5069.1  426.78  5092.1  430.42  5180.3  434.61
  5269.3  437.57  5287.4  438.38  5324.1  441.06  5351.2  441.45  5377.7  442.33
#Mann= 6 ,-1 , 0
  4598.2     .05       0  4776.1     .16       0  4999.5     .07       0
  5004.4     .16       0  5269.3     .05       0  5351.2      .1       0
Bank Sta=4999.5,5004.4
XS Rating Curve= 0 ,0
Exp/Cntr=0.3,0.1

Type RM Length L Ch R = 1 ,2797    ,385,385,385
BEGIN DESCRIPTION:
NORTH MINERAL CR TRIB 14 8 0
END DESCRIPTION:
XS GIS Cut Line= 2
      3497680.56     10386827.66      3498409.04     10386809.48
#Sta/Elev= 30
  4659.6  432.14  4713.5  430.73  4791.2  428.29  4811.2  428.73  4821.2  428.54
  4851.2  425.74  4871.2  427.05  4951.2  426.71  4971.2  425.07  4981.2  423.85
  4991.2  420.73  4998.2  417.56  4998.7  417.06  5003.7  417.06  5004.2  417.56
  5021.3  421.74  5050.9  422.32  5071.3  422.77  5081.3  423.48  5091.3   424.4
  5098.8  425.75  5103.8  425.71  5111.3  426.84  5156.3  428.15  5264.5  432.14
  5331.4  435.76  5341.4  436.66  5351.4  439.33  5371.4  437.87  5388.3  438.67
#Mann= 7 ,-1 , 0
  4659.6     .05       0  4713.5     .16       0  4998.2     .07       0
  5004.2     .16       0  5050.9      .1       0  5156.3     .16       0
  5264.5      .1       0
Bank Sta=4998.2,5004.2
XS Rating Curve= 0 ,0
Exp/Cntr=0.3,0.1

Type RM Length L Ch R = 1 ,2412    ,531,531,531
BEGIN DESCRIPTION:
NORTH MINERAL CR TRIB 14 7 0
END DESCRIPTION:
XS GIS Cut Line= 3
      3497739.15      10387369.3      3497961.78     10387168.81
      3498426.65     10387019.06
#Sta/Elev= 30
  4602.7  435.39  4709.4  435.49  4822.3  430.55  4850.7  429.93  4913.4   426.9
  4965.7  425.29  4986.7  423.34  4994.2   414.5  4994.7     414  4999.7     414
  5000.2   414.5  5004.8  418.24  5018.2  421.42  5060.2  421.52    5069  420.92
    5101  420.59  5106.3  423.32  5112.8  423.96  5133.1  422.81  5144.3  424.28
  5154.8  424.82  5165.2  426.45  5170.4  426.59  5186.3  428.73  5228.3  430.65
  5239.8  431.92  5249.3  434.18    5255  434.79  5259.8   435.3  5390.7  435.45
#Mann= 5 ,-1 , 0
  4602.7     .05       0  4913.4     .16       0  4994.2     .07       0
  5000.2     .16       0    5255      .1       0
Bank Sta=4994.2,5000.2
XS Rating Curve= 0 ,0
Exp/Cntr=0.3,0.1

Type RM Length L Ch R = 1 ,1881    ,461,461,461
BEGIN DESCRIPTION:
NORTH MINERAL CR TRIB 14 6 0
END DESCRIPTION:
XS GIS Cut Line= 3
       3497914.9     10387594.59      3498440.95     10387515.16
      3498576.38     10387258.63
#Sta/Elev= 30
  4618.2  432.13  4661.8  430.31  4785.7  424.73  4872.8  419.03  4898.5  418.87
  4936.6  420.31  4969.3  419.93  4989.6   417.3  4996.7  414.23  4997.2  413.73
  5002.7  414.23  5005.5  416.05  5010.6     416  5019.9  420.76    5030  422.81
  5182.7   428.9  5227.7  429.92  5288.1  433.34  5293.7   432.7  5310.1  434.53
  5315.7  433.72  5332.1  435.27  5337.8  434.15  5354.1  436.16  5359.8   435.3
  5376.1  437.14  5381.8  436.59  5398.2  438.25  5406.4  437.81  5440.3  437.68
#Mann= 7 ,-1 , 0
  4618.2      .1       0  4661.8     .05       0  4785.7     .16       0
  4996.7     .07       0  5002.7     .16       0  5182.7     .05       0
  5406.4      .1       0
Bank Sta=4996.7,5002.7
XS Rating Curve= 0 ,0
Exp/Cntr=0.3,0.1

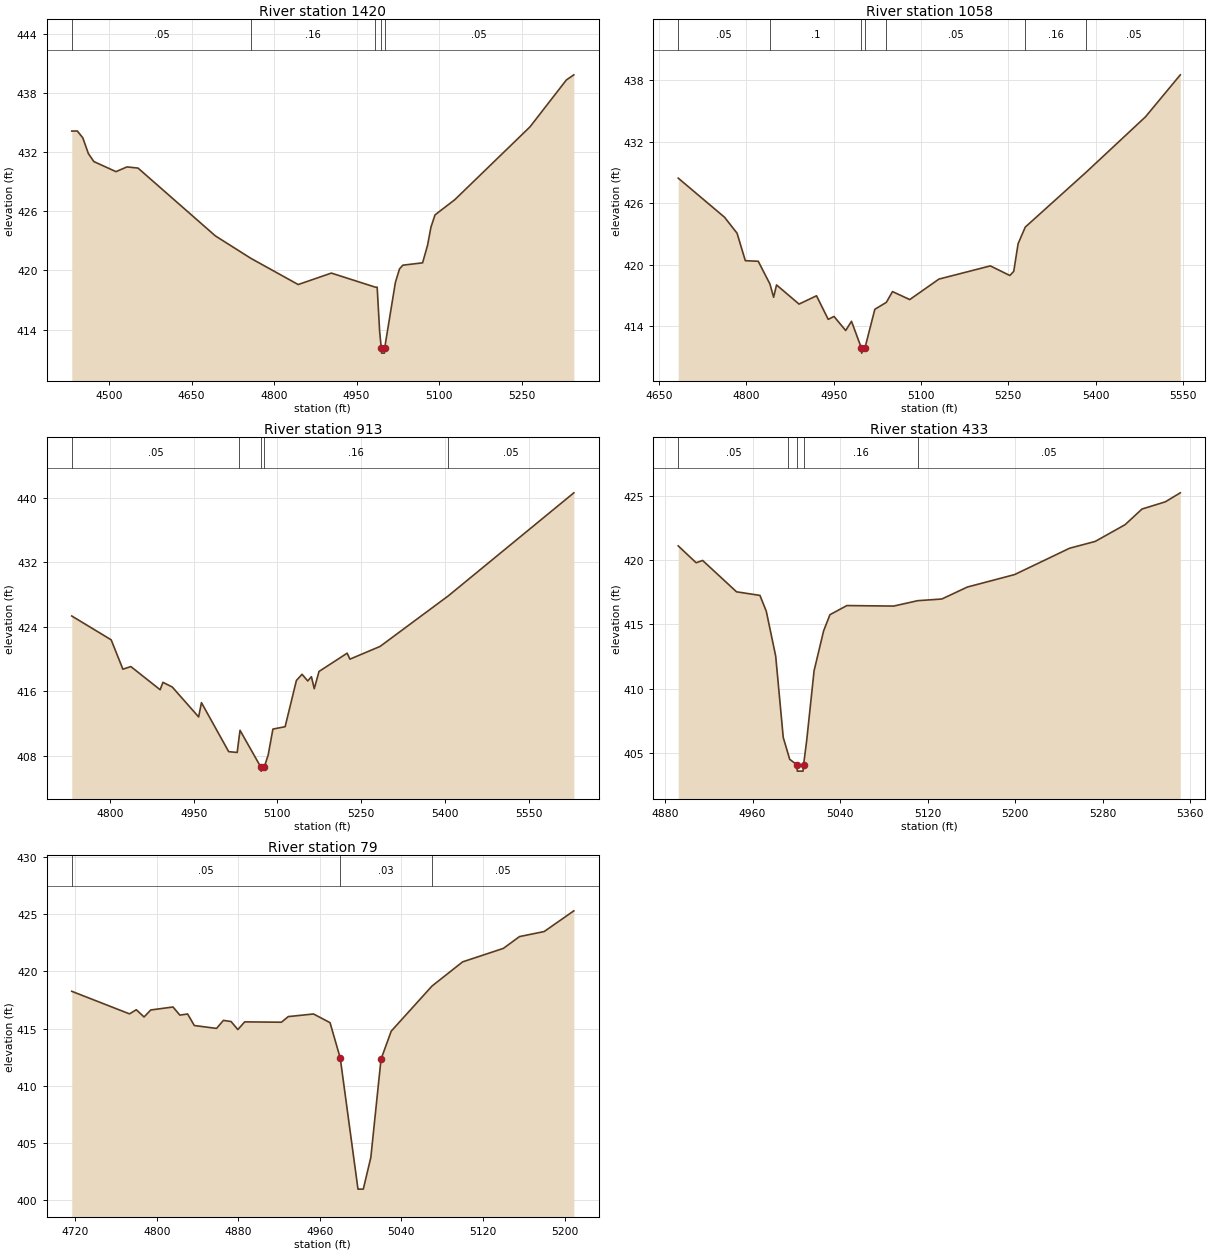
Type RM Length L Ch R = 1 ,1420    ,362,362,362
BEGIN DESCRIPTION:
NORTH MINERAL CR TRIB 14 5 0
END DESCRIPTION:
XS GIS Cut Line= 3
      3497892.07     10387791.64      3498442.11     10387841.64
      3498742.14     10387641.62
#Sta/Elev= 30
  4432.2  434.12  4442.3  434.13  4452.3  433.43  4462.4  431.84  4472.4  431.03
  4512.6  430.01  4532.6  430.49  4552.7  430.37  4693.3   423.5    4758  421.22
  4843.9  418.57  4904.2  419.73  4984.4   418.3  4987.5   418.3    4992  413.82
    4995  412.12  4995.5  411.62  5000.6  411.62  5001.1  412.12  5020.6  418.78
  5028.1  420.15  5034.1  420.53  5070.1  420.77  5079.2  422.57  5085.2  424.37
  5092.7  425.63  5128.7  427.17  5265.4  434.55  5331.5   439.3  5345.1  439.82
#Mann= 5 ,-1 , 0
  4432.2     .05       0    4758     .16       0  4984.4     .05       0
    4995     .04       0  5001.1     .05       0
Bank Sta=4995,5001.1
XS Rating Curve= 0 ,0
Exp/Cntr=0.3,0.1

Type RM Length L Ch R = 1 ,1058    ,145,145,145
BEGIN DESCRIPTION:
NORTH MINERAL CR TRIB 14 2 2 1
END DESCRIPTION:
XS GIS Cut Line= 4
      3498426.63     10388388.86      3498519.07     10388302.92
      3498498.24     10387890.16      3498738.15      10387673.6
#Sta/Elev= 30
  4682.9  428.46  4762.5  424.64    4784  423.08  4798.2   420.4  4820.4  420.34
  4840.4  418.13  4846.8  416.83  4851.8  418.03  4890.5  416.16  4920.5  416.97
  4940.6  414.67  4950.6  414.95  4970.6  413.58  4980.6  414.48  4997.6  411.87
  4998.1  411.37  5003.7  411.87  5020.7  415.65  5040.5  416.33  5051.1  417.38
  5080.7   416.6  5130.8   418.6  5219.2  419.89  5252.7  418.95  5259.4  419.36
  5266.9  422.06  5279.2  423.68  5384.2  429.06  5485.8  434.45  5545.6  438.55
#Mann= 7 ,-1 , 0
  4682.9     .05       0  4840.4      .1       0  4997.6     .07       0
  5003.7      .1       0  5040.5     .05       0  5279.2     .16       0
  5384.2     .05       0
Bank Sta=4997.6,5003.7
XS Rating Curve= 0 ,0
Exp/Cntr=0.3,0.1

Type RM Length L Ch R = 1 ,913     ,480,480,480
BEGIN DESCRIPTION:
Mapping XS ddd7e301
END DESCRIPTION:
XS GIS Cut Line= 4
      3498507.39     10388426.59      3498610.22     10388330.27
      3498550.32     10387931.83      3498793.83      10387672.7
#Sta/Elev= 30
  4731.7  425.33  4802.3  422.37  4823.3  418.72  4837.5  419.05    4890  416.17
    4895  417.09  4911.7  416.51    4959  412.79    4964  414.57  5012.8  408.48
    5028  408.38  5031.4  410.21  5033.1  411.13  5070.4  406.56  5070.9  406.06
  5076.5  406.56  5083.6  408.08    5092  411.28  5113.9  411.58  5134.1  417.32
  5144.2  418.09  5154.4  417.26    5161  417.79  5166.1   416.3  5174.6  418.44
    5225  420.71    5230  419.97    5284  421.55  5406.2  427.83  5631.1  440.63
#Mann= 5 ,-1 , 0
  4731.7     .05       0  5031.4     .16       0  5070.4     .04       0
  5076.5     .16       0  5406.2     .05       0
Bank Sta=5070.4,5076.5
XS Rating Curve= 0 ,0
Exp/Cntr=0.3,0.1

Type RM Length L Ch R = 1 ,433     ,354,354,354
BEGIN DESCRIPTION:
Mapping XS f44ad0ad
END DESCRIPTION:
XS GIS Cut Line= 2
      3498625.83     10388556.84      3499018.73     10388319.54
#Sta/Elev= 30
    4892   421.1  4908.4  419.79  4914.3  419.97  4945.3  417.53  4966.7  417.25
  4972.5  416.02  4981.1  412.53    4988   406.2  4992.8  404.82  4993.9   404.5
  5000.4  404.08  5000.9  403.58  5006.1  403.58  5006.6  404.08  5009.4  405.94
  5016.2  411.39  5024.9  414.49  5030.7  415.75  5046.2  416.46  5088.9  416.42
    5111  416.84    5133  416.97  5156.3   417.9  5199.5  418.87  5249.8  420.92
  5273.2  421.45  5300.5  422.75    5316  423.97  5337.3  424.53    5351  425.23
#Mann= 5 ,-1 , 0
    4892     .05       0  4992.8     .16       0  5000.4     .07       0
  5006.6     .16       0    5111     .05       0
Bank Sta=5000.4,5006.6
XS Rating Curve= 0 ,0
Exp/Cntr=0.3,0.1

Type RM Length L Ch R = 1 ,79      ,0,0,0
BEGIN DESCRIPTION:
NORTH MINERAL CR TRIB 14 1 0
END DESCRIPTION:
XS GIS Cut Line= 3
      3498659.71     10388614.13      3498815.95     10388792.51
      3499071.17     10388797.71
#Sta/Elev= 30
  4716.7  418.26  4773.3  416.29    4780  416.65  4787.6  416.02  4794.2  416.63
    4816  416.89  4822.7  416.18  4830.3  416.28  4836.9  415.27  4858.7  415.02
  4865.4  415.72  4872.9  415.62  4879.6  414.92  4886.3  415.59  4922.3  415.56
    4929  416.05  4953.8  416.28    4970  415.52    4980  412.43  4997.4  400.98
  5002.6  400.98    5010  403.75    5020  412.33    5030  414.78    5070  418.72
    5100  420.83    5140  422.01  5155.8  423.04    5180  423.48  5209.1  425.29
#Mann= 3 ,-1 , 0
  4716.7     .05       0    4980     .03       0    5070     .05       0
Bank Sta=4980,5020
XS Rating Curve= 0 ,0
Exp/Cntr=0.3,0.1

Chan Stop Cuts=-1
Use User Specified Reach Order=0
Composite Channel Slope=5