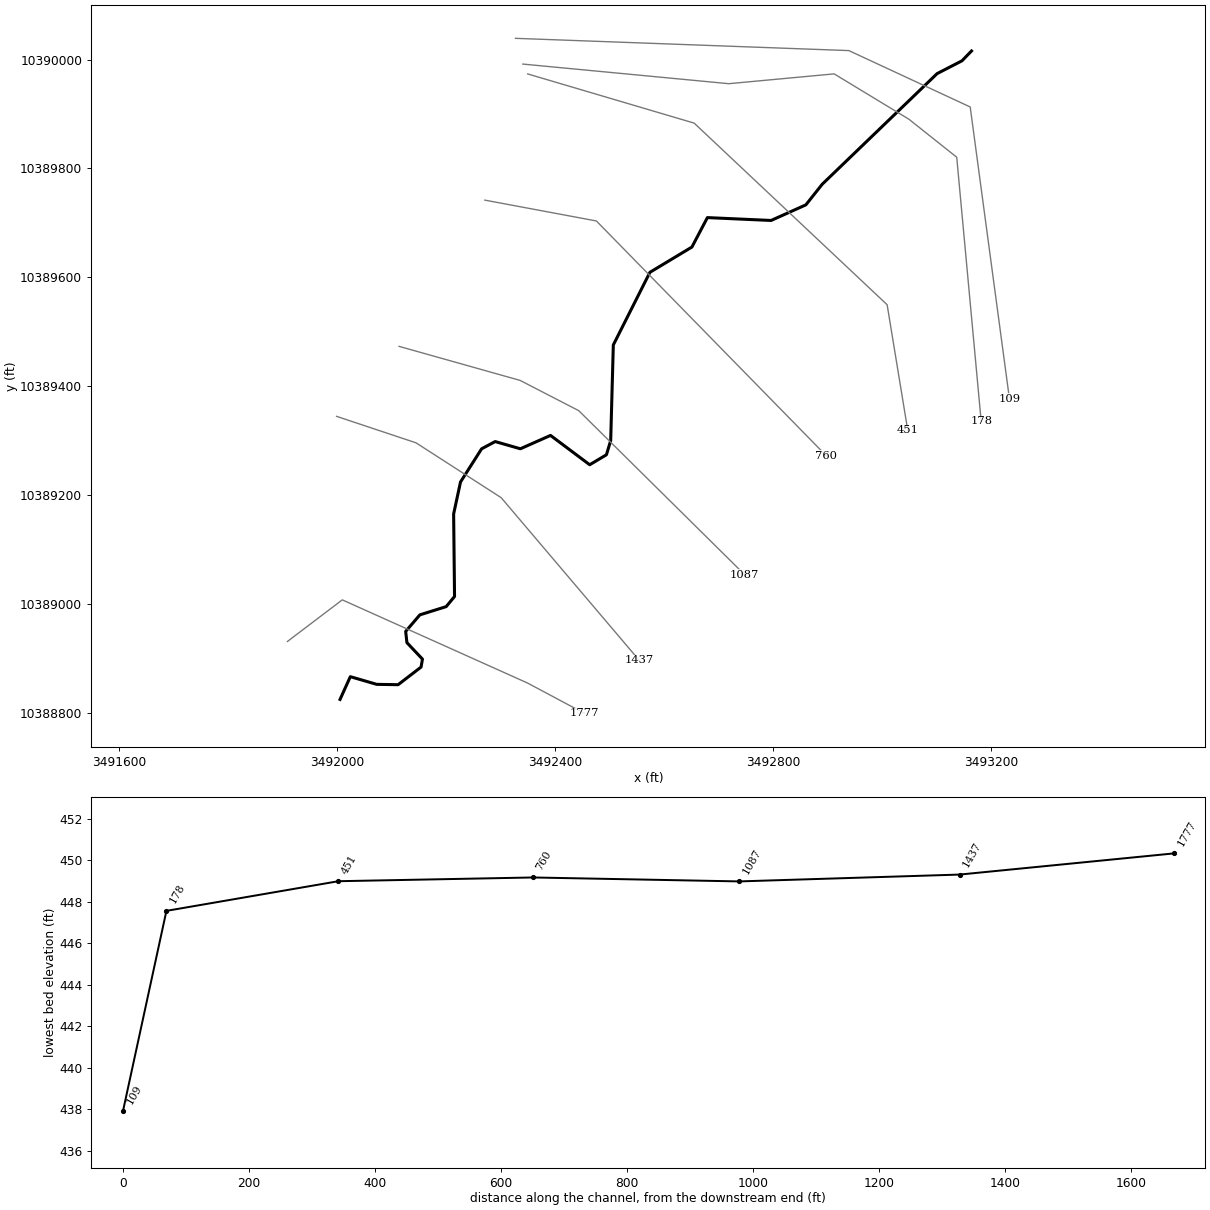
--- NORTH MINERAL CR TRIB 15 1.prj (project) ---

Proj Title=NORTH MINERAL CR TRIB 15 1 Base Level Engineering
Current Plan=p01
Default Exp/Contr=0.3,0.1
English Units
Geom File=g01
Flow File=f01
Plan File=p01
Y Axis Title=Elevation
X Axis Title(PF)=Main Channel Distance
X Axis Title(XS)=Station
BEGIN DESCRIPTION:
NORTH MINERAL CR TRIB 15 1
END DESCRIPTION:
DSS Export Rating Curves= 0
DSS Export Rating Curve Sorted= 0
DSS Export Volume Flow Curves= 0
DXF OffsetX= 0
DXF OffsetY= 0
DXF ScaleX= 1
DXF ScaleY= 10

--- NORTH MINERAL CR TRIB 15 1.p01 (plan) ---

Plan Title=Multiple Run
Short Identifier=Multiple
Geom File=g01
Flow File=f01
Subcritical Flow
K Sum by GR= 0
Std Step Tol= 0.01
Critical Tol= 0.01
Num of Std Step Trials= 20
Max Error Tol= 0.3
Flow Tol Ratio= 0.001
Split Flow NTrial= 30
Split Flow Tol= 0.02
Split Flow Ratio= 0.02
Log Output Level= 0
Friction Slope Method= 1
Unsteady Friction Slope Method= 2
Unsteady Bridges Friction Slope Method= 1
Parabolic Critical Depth
Global Vel Dist=  1 , 1 , 1
Global Log Level= 0
CheckData=True
Encroach Param= -1, 0, 0, 0
BEGIN DESCRIPTION:
Multiple Run
END DESCRIPTION:

--- NORTH MINERAL CR TRIB 15 1.f01 (steady flow) ---

Flow Title=Multiple
Program Version=4.10
Number of Profiles= 7
Profile Names=10-year,25-year,50-year,1pct_min,100-year,1pct_plu,500-year
River Rch & RM=NORTH MINERAL CR,Reach-1         ,1777
     613     824     994     876    1185    1602    1680
Boundary for River Rch & Prof#=NORTH MINERAL CR,Reach-1         , 1
Up Type= 0
Dn Type= 3
Dn Slope=0.005
Boundary for River Rch & Prof#=NORTH MINERAL CR,Reach-1         , 2
Up Type= 0
Dn Type= 3
Dn Slope=0.005
Boundary for River Rch & Prof#=NORTH MINERAL CR,Reach-1         , 3
Up Type= 0
Dn Type= 3
Dn Slope=0.005
Boundary for River Rch & Prof#=NORTH MINERAL CR,Reach-1         , 4
Up Type= 0
Dn Type= 3
Dn Slope=0.005
Boundary for River Rch & Prof#=NORTH MINERAL CR,Reach-1         , 5
Up Type= 0
Dn Type= 3
Dn Slope=0.005
Boundary for River Rch & Prof#=NORTH MINERAL CR,Reach-1         , 6
Up Type= 0
Dn Type= 3
Dn Slope=0.005
Boundary for River Rch & Prof#=NORTH MINERAL CR,Reach-1         , 7
Up Type= 0
Dn Type= 3
Dn Slope=0.005
DSS Import GetInterval= 0
DSS Import GetPeak= 0
DSS Import FillOption= 0

--- NORTH MINERAL CR TRIB 15 1.g01 (geometry) ---

Geom Title=Existing Conditions
Program Version=4.10

River Reach=NORTH MINERAL CR,Reach-1
Reach XY= 30
       3492005.4      10388825.5      3492024.29     10388867.28
       3492072.7     10388853.18      3492111.96     10388852.54
      3492154.12      10388884.9      3492156.67     10388899.52
      3492128.18     10388929.68      3492125.88     10388950.36
      3492151.93     10388980.74      3492200.21     10388995.85
      3492215.56      10389014.4      3492213.89      10389165.9
      3492226.51     10389224.62      3492265.25     10389285.47
      3492290.12     10389298.81      3492336.35     10389285.54
      3492391.73     10389310.06       3492463.6     10389256.23
      3492494.29     10389274.51      3492502.14     10389300.48
      3492506.97     10389476.11      3492574.16     10389609.45
      3492651.24      10389655.8      3492679.63     10389709.84
      3492796.56     10389704.59      3492860.37     10389733.23
      3492890.31     10389770.99      3493101.25     10389974.12
      3493146.82     10389997.56      3493164.41     10390015.67

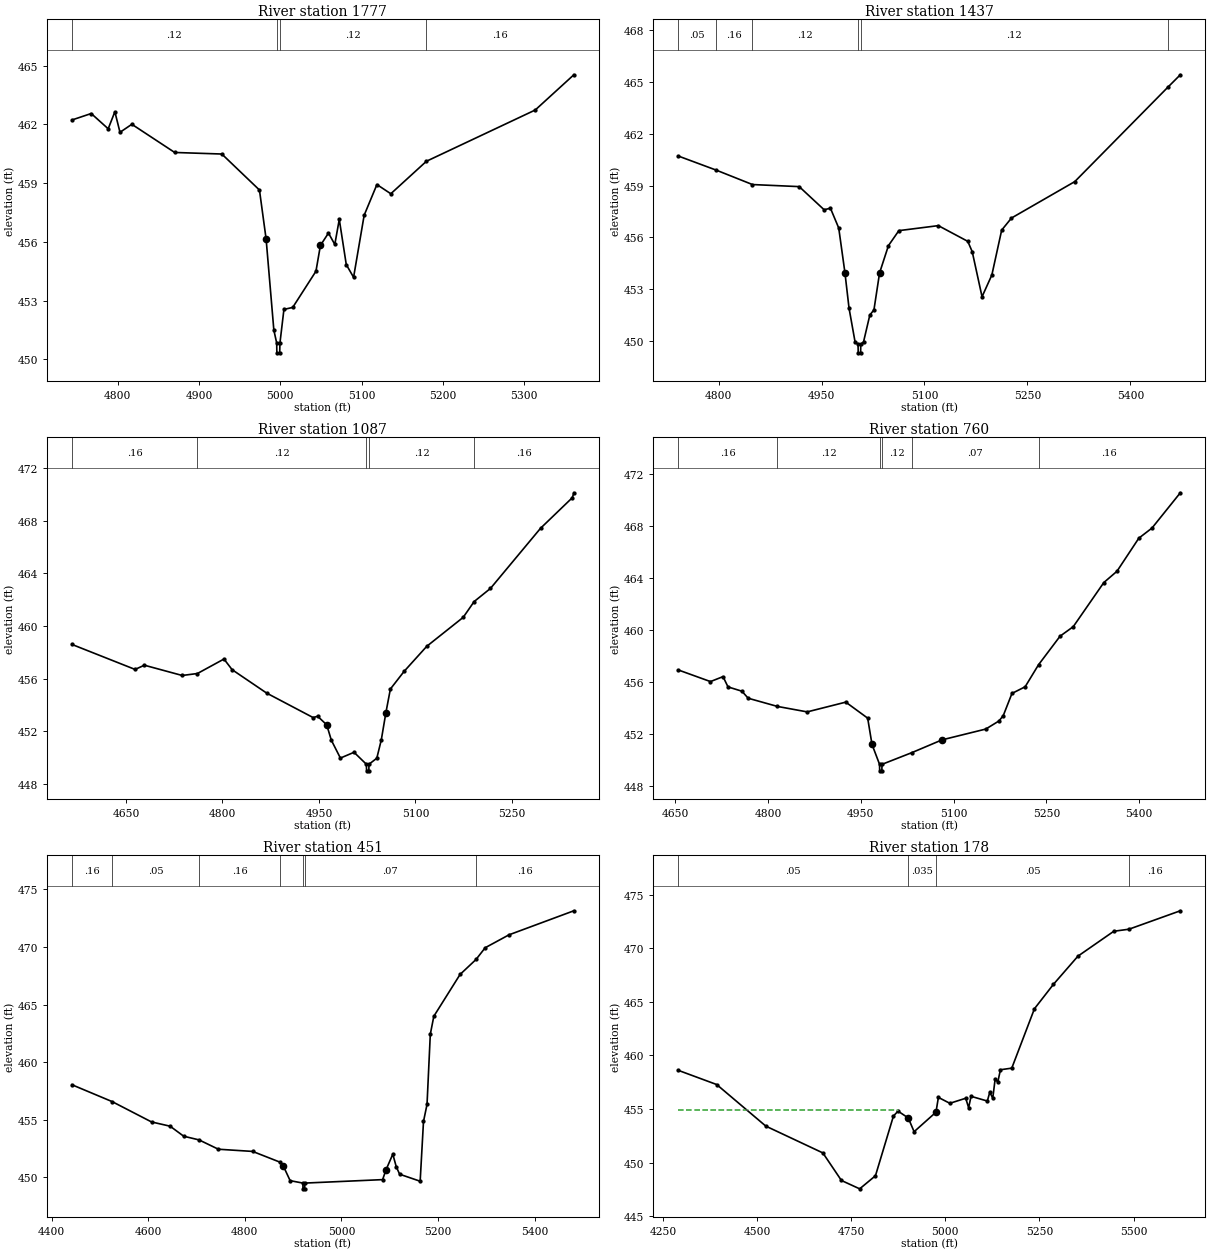
Type RM Length L Ch R = 1 ,1777    ,340,340,340
BEGIN DESCRIPTION:
NORTH MINERAL CR TRIB 15 1 4.0
END DESCRIPTION:
XS GIS Cut Line= 4
      3491908.79     10388931.84      3492009.52     10389008.25
       3492349.8     10388855.47      3492453.98     10388799.91
#Sta/Elev= 30
  4743.7  462.23  4767.4  462.56  4788.3  461.78  4796.5  462.65  4802.8   461.6
  4817.4  462.01  4870.1  460.57  4928.1  460.49  4974.4  458.65  4982.6  456.14
  4992.1  451.49  4995.6  450.83  4995.8  450.33  4999.3  450.33  4999.6  450.83
  5004.5  452.55  5015.3  452.65  5043.9   454.5  5049.4  455.82  5059.3  456.45
  5067.1  455.87  5072.6  457.15  5081.2  454.84  5090.2  454.19  5103.2  457.36
  5118.9  458.93    5136  458.46  5179.8  460.12  5313.7  462.74  5361.2  464.54
#Mann= 4 ,-1 , 0
  4743.7     .12       0  4995.6     .07       0  4999.6     .12       0
  5179.8     .16       0
Bank Sta=4982.6,5049.4
XS Rating Curve= 0 ,0
Exp/Cntr=0.3,0.1

Type RM Length L Ch R = 1 ,1437    ,350,350,350
BEGIN DESCRIPTION:
Mapping XS 142d69e4
END DESCRIPTION:
XS GIS Cut Line= 4
      3491999.11     10389345.05      3492144.94     10389296.44
      3492301.19     10389195.75      3492554.67     10388897.13
#Sta/Elev= 30
  4741.5  460.71  4796.3   459.9  4849.4  459.06  4917.5  458.94  4953.8   457.6
    4963  457.69  4975.1  456.54  4984.1  453.96  4990.1   451.9  4998.9  449.94
  5003.2  449.81  5003.5  449.31    5007  449.31  5007.2  449.81  5011.2  449.94
  5020.4   451.5  5026.4   451.8  5034.6  453.94  5047.5  455.52  5062.7  456.39
  5120.2  456.68  5163.1  455.77  5169.6  455.17  5183.9  452.56  5198.2  453.82
  5212.5  456.42  5226.8  457.12    5319  459.23  5454.4  464.69  5472.8  465.42
#Mann= 6 ,-1 , 0
  4741.5     .05       0  4796.3     .16       0  4849.4     .12       0
  5003.2     .07       0  5007.2     .12       0  5454.4     .16       0
Bank Sta=4984.1,5034.6
XS Rating Curve= 0 ,0
Exp/Cntr=0.3,0.1

Type RM Length L Ch R = 1 ,1087    ,327,327,327
BEGIN DESCRIPTION:
Mapping XS 4792d7b7
END DESCRIPTION:
XS GIS Cut Line= 4
      3492113.71     10389473.52      3492335.91     10389411.03
      3492443.55     10389355.47      3492748.09     10389054.39
#Sta/Elev= 30
    4566  458.59  4664.1  456.69  4678.6  457.01  4737.4  456.23  4761.1  456.38
  4802.3  457.48    4815  456.67  4868.7  454.89  4940.9  453.03  4947.9  453.13
    4962  452.48  4969.2  451.31  4983.3  449.95  5004.5  450.39  5023.7  449.48
    5024  448.98  5027.5  448.98  5027.7  449.48  5039.9  449.94  5046.9  451.34
    5054   453.4    5061   455.2  5082.3  456.54  5117.6  458.45  5174.2  460.65
  5191.2  461.85  5216.6  462.85  5294.4  467.42  5343.9  469.75  5346.2  470.12
#Mann= 5 ,-1 , 0
    4566     .16       0  4761.1     .12       0  5023.7     .07       0
  5027.7     .12       0  5191.2     .16       0
Bank Sta=4962,5054
XS Rating Curve= 0 ,0
Exp/Cntr=0.3,0.1

Type RM Length L Ch R = 1 ,760     ,309,309,309
BEGIN DESCRIPTION:
NORTH MINERAL CR TRIB 15 1 3.0
END DESCRIPTION:
XS GIS Cut Line= 3
      3492271.19     10389741.91      3492475.88     10389703.67
      3492897.94     10389272.62
#Sta/Elev= 30
  4655.1  456.92  4706.9  456.03  4727.2  456.41  4735.3  455.62  4757.8  455.29
  4767.9  454.75  4815.2  454.12  4863.3   453.7  4925.7  454.45  4961.1  453.22
  4968.1   451.2  4980.3  449.67  4980.5  449.17    4984  449.17  4984.3  449.67
  5032.6  450.57  5081.3  451.55    5152  452.38  5173.3     453  5180.3  453.41
  5194.4  455.12  5215.7  455.63  5237.3  457.32  5272.2  459.52  5293.5  460.25
  5342.9  463.64  5364.2  464.51  5399.5  467.05  5420.8  467.83  5466.6  470.54
#Mann= 6 ,-1 , 0
  4655.1     .16       0  4815.2     .12       0  4980.3     .07       0
  4984.3     .12       0  5032.6     .07       0  5237.3     .16       0
Bank Sta=4968.1,5081.3
XS Rating Curve= 0 ,0
Exp/Cntr=0.3,0.1

Type RM Length L Ch R = 1 ,451     ,273,273,273
BEGIN DESCRIPTION:
Mapping XS 5a1b3874
END DESCRIPTION:
XS GIS Cut Line= 4
      3492349.83     10389973.52      3492655.35     10389883.25
      3493009.52     10389549.92      3493047.41     10389319.14
#Sta/Elev= 30
  4442.3  458.03  4525.3  456.57    4607   454.8  4645.5  454.43  4673.6  453.56
  4705.4  453.24  4745.4  452.43  4816.3  452.24  4873.3   451.3    4880  450.95
  4893.9   449.7  4920.3  449.49  4920.5  448.99    4924  448.99  4924.3  449.49
  5085.3  449.79  5092.2  450.63  5106.4     452  5113.5  450.91  5120.5  450.26
    5163  449.65  5169.9  454.84  5177.2  456.32    5184  462.42  5191.3  463.98
  5245.6  467.61  5278.6  468.91  5297.6  469.93  5346.8  471.05  5481.1  473.14
#Mann= 7 ,-1 , 0
  4442.3     .16       0  4525.3     .05       0  4705.4     .16       0
  4873.3     .07       0  4920.3     .07       0  4924.3     .07       0
  5278.6     .16       0
Bank Sta=4880,5092.2
XS Rating Curve= 0 ,0
Exp/Cntr=0.3,0.1

Type RM Length L Ch R = 1 ,178     ,69,69,69
BEGIN DESCRIPTION:
NORTH MINERAL CR TRIB 15 1 2.0
END DESCRIPTION:
XS GIS Cut Line= 6
       3492340.9     10389991.62      3492718.83     10389955.62
       3492912.3     10389973.62      3493049.52     10389890.38
      3493137.25     10389820.65      3493182.15     10389335.73
#Sta/Elev= 30
  4290.8  458.61  4392.5  457.29  4523.1  453.41  4674.6  450.91  4723.9  448.34
  4772.4  447.56  4814.3  448.78  4862.1  454.35  4874.3  454.81  4901.5  454.17
    4917  452.89  4975.1  454.71  4981.5  456.09  5011.9  455.54  5054.1  456.01
  5061.9  455.13  5068.3  456.19  5111.6  455.75    5118  456.57    5126  456.02
  5132.4  457.83  5139.3  457.52  5146.4  458.67  5176.5  458.82  5236.7  464.36
    5287  466.63  5352.4  469.27  5447.6  471.59  5487.8  471.78  5624.3   473.5
#Mann= 4 ,-1 , 0
  4290.8     .05       0  4901.5    .035       0  4975.1     .05       0
  5487.8     .16       0
#XS Ineff= 2 , 0
         4875.08   454.9
Permanent Ineff=
       T       T
Bank Sta=4901.5,4975.1
XS Rating Curve= 0 ,0
Exp/Cntr=0.3,0.1

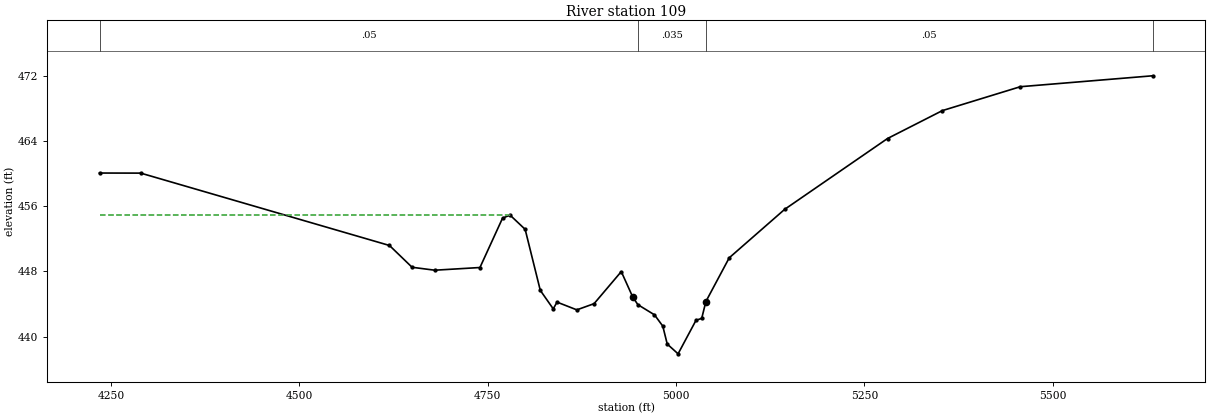
Type RM Length L Ch R = 1 ,109     ,0,0,0
BEGIN DESCRIPTION:
NORTH MINERAL CR TRIB 15 1 1.0
END DESCRIPTION:
XS GIS Cut Line= 4
      3492327.44     10390038.86      3492939.29     10390016.36
        3493162.     10389912.88      3493233.99     10389377.43
#Sta/Elev= 30
  4234.7  460.06  4289.4  460.05  4619.6  451.18  4649.6  448.51  4679.7  448.15
  4739.7  448.48  4769.7  454.53  4779.7   454.9  4799.7  453.16  4819.8  445.68
    4837  443.41    4842  444.24  4868.3  443.29  4891.2  444.05  4927.3  447.98
  4942.5  444.87  4949.3  443.93  4971.4  442.68  4982.4   441.3  4988.3   439.1
  5002.7   437.9  5026.5  442.01  5034.1  442.25  5039.6  444.31  5070.6  449.67
  5144.2  455.61  5280.7  464.29  5353.5  467.71    5457  470.64  5632.8  471.98
#Mann= 4 ,-1 , 0
  4234.7     .05       0  4949.3    .035       0  5039.6     .05       0
  5632.8     .16       0
#XS Ineff= 2 , 0
         4780.23   454.9
Permanent Ineff=
       T       T
Bank Sta=4942.5,5039.6
XS Rating Curve= 0 ,0
Exp/Cntr=0.3,0.1

Chan Stop Cuts=-1
Use User Specified Reach Order=0
Composite Channel Slope=5