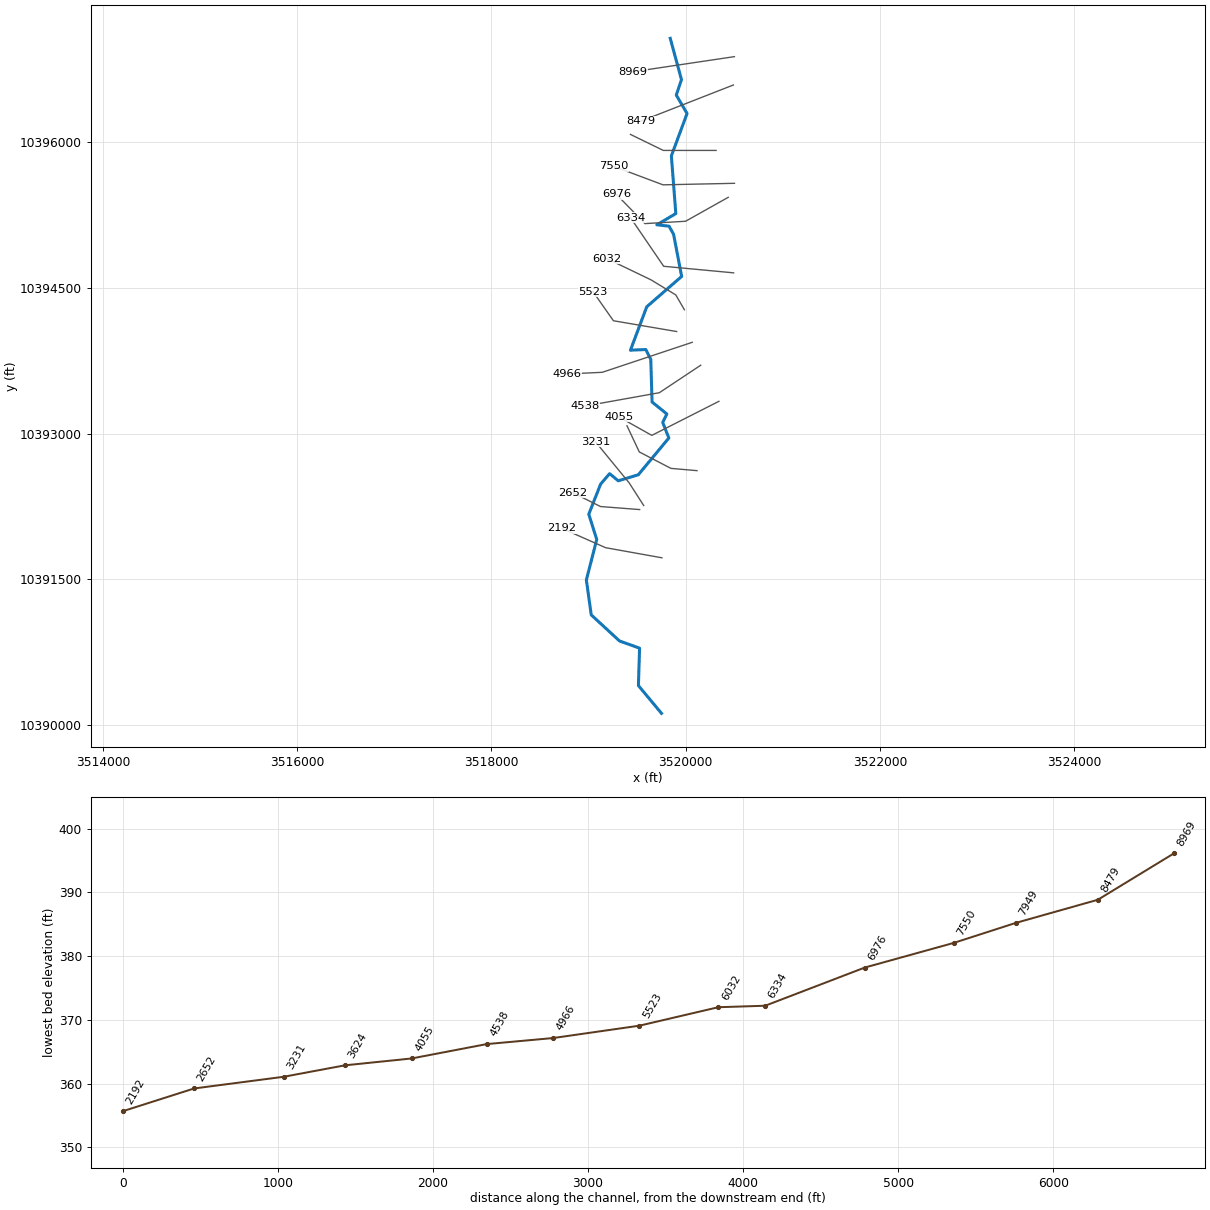
--- NORTH MINERAL CR TRIB 2.prj (project) ---

Proj Title=NORTH MINERAL CR TRIB 2 Base Level Engineering
Current Plan=p01
Default Exp/Contr=0.3,0.1
English Units
Geom File=g01
Flow File=f01
Plan File=p01
BEGIN DESCRIPTION:
NORTH MINERAL CR TRIB 2
END DESCRIPTION:

--- NORTH MINERAL CR TRIB 2.p01 (plan) ---

Plan Title=Multiple Run
Short Identifier=Multiple
Geom File=g01
Flow File=f01
Subcritical Flow
K Sum by GR= 0
Std Step Tol= 0.01
Critical Tol= 0.01
Num of Std Step Trials= 20
Max Error Tol= 0.3
Flow Tol Ratio= 0.001
Split Flow NTrial= 30
Split Flow Tol= 0.02
Split Flow Ratio= 0.02
Log Output Level= 0
Friction Slope Method= 1
Unsteady Friction Slope Method= 2
Unsteady Bridges Friction Slope Method= 1
Parabolic Critical Depth
Global Vel Dist=  1 , 1 , 1
Global Log Level= 0
CheckData=True
Encroach Param= -1, 0, 0, 0
BEGIN DESCRIPTION:
Multiple Run
END DESCRIPTION:

--- NORTH MINERAL CR TRIB 2.f01 (steady flow) ---

Flow Title=Multiple
Number of Profiles=7
Profile Names=10-year,25-year,50-year,1pct_min,100-year,1pct_plu,500-year
River Rch & RM= NORTH MINERAL CR,Reach-1,8969
     970    1347    1661    1497    2024    2737    2996
Boundary for River Rch & Prof#=NORTH MINERAL CR,Reach-1,1
Up Type=0
Dn Type=3
Dn Slope=0.005
Boundary for River Rch & Prof#=NORTH MINERAL CR,Reach-1,2
Up Type=0
Dn Type=3
Dn Slope=0.005
Boundary for River Rch & Prof#=NORTH MINERAL CR,Reach-1,3
Up Type=0
Dn Type=3
Dn Slope=0.005
Boundary for River Rch & Prof#=NORTH MINERAL CR,Reach-1,4
Up Type=0
Dn Type=3
Dn Slope=0.005
Boundary for River Rch & Prof#=NORTH MINERAL CR,Reach-1,5
Up Type=0
Dn Type=3
Dn Slope=0.005
Boundary for River Rch & Prof#=NORTH MINERAL CR,Reach-1,6
Up Type=0
Dn Type=3
Dn Slope=0.005
Boundary for River Rch & Prof#=NORTH MINERAL CR,Reach-1,7
Up Type=0
Dn Type=3
Dn Slope=0.005

--- NORTH MINERAL CR TRIB 2.g01 (geometry) ---

Geom Title=Existing Conditions

River Reach=NORTH MINERAL CR,Reach-1
Reach XY= 30
      3519842.06     10397071.49      3519957.63     10396645.98
      3519904.08     10396487.44      3520015.25     10396297.64
      3519853.70     10395861.20      3519899.55     10395267.31
      3519704.00     10395151.64      3519829.89     10395137.69
      3519876.40     10395054.02      3519959.54     10394620.22
      3519600.24     10394307.88      3519432.30     10393860.87
      3519589.98     10393867.52      3519641.69     10393766.57
      3519654.92     10393327.35      3519807.18     10393203.88
      3519764.45     10393117.25      3519827.82     10392956.97
      3519513.05     10392578.11      3519307.00     10392516.00
      3519217.70     10392589.97      3519124.64     10392480.77
      3519003.28     10392171.90      3519085.45     10391912.12
      3518978.54     10391495.59      3519028.58     10391135.59
      3519319.86     10390867.11      3519526.37     10390793.11
      3519514.38     10390407.63      3519752.11     10390121.64

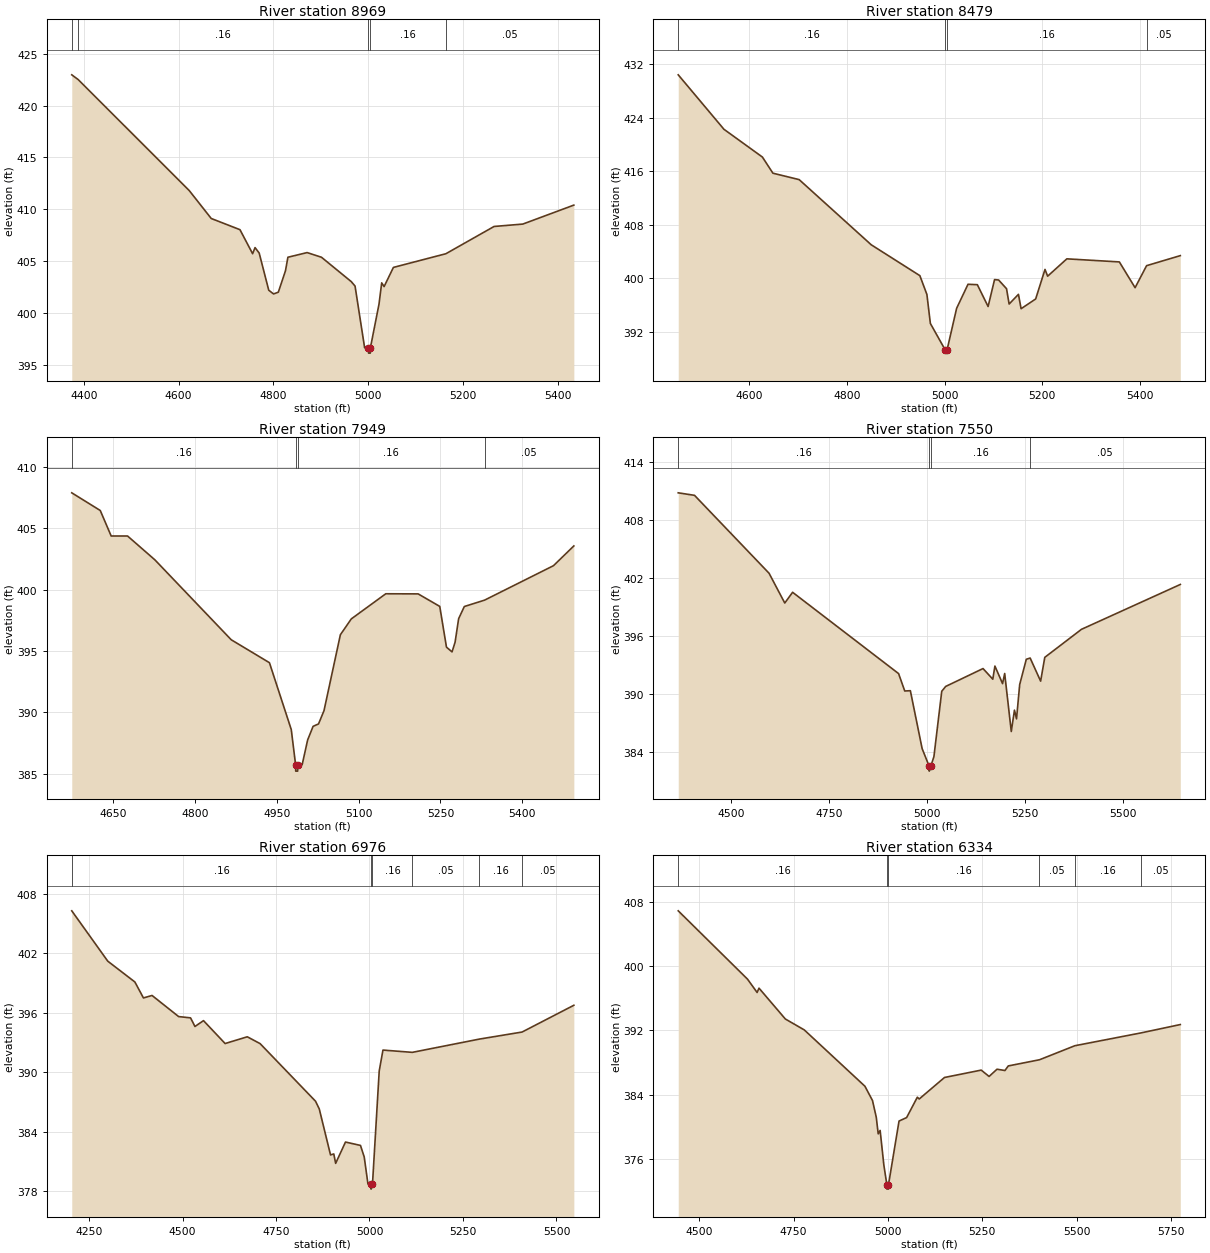
Type RM Length L Ch R = 1,8969,490,490,490
BEGIN DESCRIPTION:
NORTH MINERAL CR TRIB 2 3 0
END DESCRIPTION:
XS GIS Cut Line= 2
      3520502.96     10396883.06      3519455.72     10396727.02
#Sta/Elev= 30
  4374.6  422.96  4388.2  422.50  4622.4  411.79  4668.7  409.10  4729.3  408.02
  4756.0  405.70  4761.1  406.29  4769.8  405.77  4790.0  402.18  4800.1  401.82
  4810.2  401.99  4825.3  404.06  4830.4  405.36  4870.9  405.81  4901.2  405.36
  4964.0  403.01  4972.0  402.58  4992.2  396.63  5000.3  396.61  5000.6  396.11
  5004.1  396.11  5004.3  396.61  5022.5  400.83  5028.2  402.89  5033.3  402.53
  5052.9  404.38  5163.6  405.70  5265.2  408.33  5325.8  408.56  5433.4  410.39
#Mann=5,-1,0
  4374.6    0.05       0  4388.2    0.16       0  5000.3    0.07       0
  5004.3    0.16       0  5163.6    0.05       0
Bank Sta=5000.3,5004.3
Exp/Cntr=0.3,0.1

Type RM Length L Ch R = 1,8479,530,530,530
BEGIN DESCRIPTION:
NORTH MINERAL CR TRIB 2 2 0
END DESCRIPTION:
XS GIS Cut Line= 2
      3520492.46     10396591.37      3519535.98     10396217.10
#Sta/Elev= 30
  4455.2  430.40  4548.7  422.27  4627.4  418.12  4648.9  415.71  4702.6  414.75
  4850.0  405.02  4949.5  400.41  4963.9  397.60  4971.0  393.27  5001.2  389.34
  5001.5  388.84  5005.2  389.34  5024.7  395.53  5048.0  399.12  5067.1  399.06
  5089.1  395.80  5102.3  399.82  5110.6  399.76  5126.8  398.46  5132.1  396.17
  5151.2  397.62  5156.6  395.47  5186.4  396.93  5205.5  401.34  5210.9  400.33
  5250.2  402.92  5357.6  402.46  5389.8  398.61  5413.3  401.90  5482.3  403.40
#Mann=4,-1,0
  4455.2    0.16       0  5001.2    0.07       0  5005.2    0.16       0
  5413.3    0.05       0
Bank Sta=5001.2,5005.2
Exp/Cntr=0.3,0.1

Type RM Length L Ch R = 1,7949,399,399,399
BEGIN DESCRIPTION:
NORTH MINERAL CR TRIB 2 15 0
END DESCRIPTION:
XS GIS Cut Line= 3
      3520314.28     10395917.45      3519770.90     10395917.45
      3519432.33     10396082.39
#Sta/Elev= 30
  4574.4  407.89  4626.6  406.45  4646.6  404.37  4676.6  404.37  4726.6  402.43
  4866.6  395.91  4936.6  394.04  4976.6  388.59  4984.6  385.70  4984.8  385.20
  4988.3  385.20  4988.6  385.70  4996.6  385.73  5006.6  387.74  5016.6  388.85
  5026.6  389.05  5036.6  390.13  5066.6  396.32  5086.6  397.61  5149.8  399.66
  5209.1  399.65  5248.7  398.63  5261.0  395.31  5271.2  394.92  5276.8  395.71
  5283.3  397.63  5293.7  398.62  5330.8  399.14  5457.1  401.95  5494.4  403.56
#Mann=4,-1,0
  4574.4    0.16       0  4984.6    0.07       0  4988.6    0.16       0
  5330.8    0.05       0
Bank Sta=4984.6,4988.6
Exp/Cntr=0.3,0.1

Type RM Length L Ch R = 1,7550,574,574,574
BEGIN DESCRIPTION:
NORTH MINERAL CR TRIB 2 14 0
END DESCRIPTION:
XS GIS Cut Line= 3
      3520503.55     10395578.91      3519767.42     10395563.28
      3519258.78     10395754.24
#Sta/Elev= 30
  4365.5  410.86  4407.0  410.60  4597.0  402.54  4637.0  399.46  4657.0  400.57
  4927.1  392.16  4942.8  390.36  4957.1  390.39  4987.1  384.40  5005.1  382.57
  5005.3  382.07  5009.1  382.57  5017.1  383.56  5037.1  390.33  5047.1  390.83
  5142.3  392.68  5167.2  391.58  5172.6  392.94  5192.1  391.12  5197.5  392.17
  5214.3  386.17  5222.4  388.38  5227.7  387.48  5235.7  391.02  5252.6  393.64
  5262.4  393.77  5289.1  391.38  5299.7  393.84  5393.2  396.74  5645.1  401.38
#Mann=4,-1,0
  4365.5    0.16       0  5005.1    0.07       0  5009.1    0.16       0
  5262.4    0.05       0
Bank Sta=5005.1,5009.1
Exp/Cntr=0.3,0.1

Type RM Length L Ch R = 1,6976,642,642,642
BEGIN DESCRIPTION:
NORTH MINERAL CR TRIB 2 13 0
END DESCRIPTION:
XS GIS Cut Line= 4
      3520439.31     10395434.82      3520000.06     10395188.28
      3519581.66     10395163.98      3519288.25     10395464.33
#Sta/Elev= 30
  4203.8  406.28  4300.1  401.20  4372.6  399.10  4395.5  397.49  4418.5  397.74
  4489.6  395.61  4521.5  395.48  4533.2  394.61  4556.1  395.20  4613.9  392.89
  4673.2  393.57  4707.5  392.88  4855.7  387.07  4865.7  386.29  4895.8  381.65
  4904.5  381.75  4909.5  380.80  4935.8  382.95  4975.9  382.61  4985.9  381.45
  4995.9  378.72  5004.0  378.70  5004.2  378.20  5008.0  378.70  5026.0  390.11
  5036.0  392.23  5114.6  392.00  5294.1  393.34  5408.1  394.05  5546.5  396.75
#Mann=6,-1,0
  4203.8    0.16       0  5004.0    0.07       0  5008.0    0.16       0
  5114.6    0.05       0  5294.1    0.16       0  5408.1    0.05       0
Bank Sta=5004,5008
Exp/Cntr=0.3,0.1

Type RM Length L Ch R = 1,6334,302,302,302
BEGIN DESCRIPTION:
NORTH MINERAL CR TRIB 2 12 0
END DESCRIPTION:
XS GIS Cut Line= 3
      3520494.84     10394657.03      3519774.37     10394724.74
      3519432.34     10395226.51
#Sta/Elev= 30
  4444.2  406.91  4627.7  398.40  4653.3  396.73  4658.3  397.27  4728.2  393.42
  4778.4  392.06  4939.1  385.04  4959.2  383.25  4969.2  381.16  4974.3  379.10
  4979.4  379.53  4989.3  375.20  4997.4  372.71  4997.6  372.21  5001.1  372.21
  5001.4  372.71  5029.5  380.70  5049.6  381.13  5078.0  383.67  5083.0  383.45
  5150.0  386.13  5247.3  387.05  5268.2  386.26  5289.2  387.16  5310.2  387.00
  5319.1  387.57  5401.8  388.34  5495.6  390.09  5670.1  391.68  5775.1  392.73
#Mann=6,-1,0
  4444.2    0.16       0  4997.4    0.07       0  5001.4    0.16       0
  5401.8    0.05       0  5495.6    0.16       0  5670.1    0.05       0
Bank Sta=4997.4,5001.4
Exp/Cntr=0.3,0.1

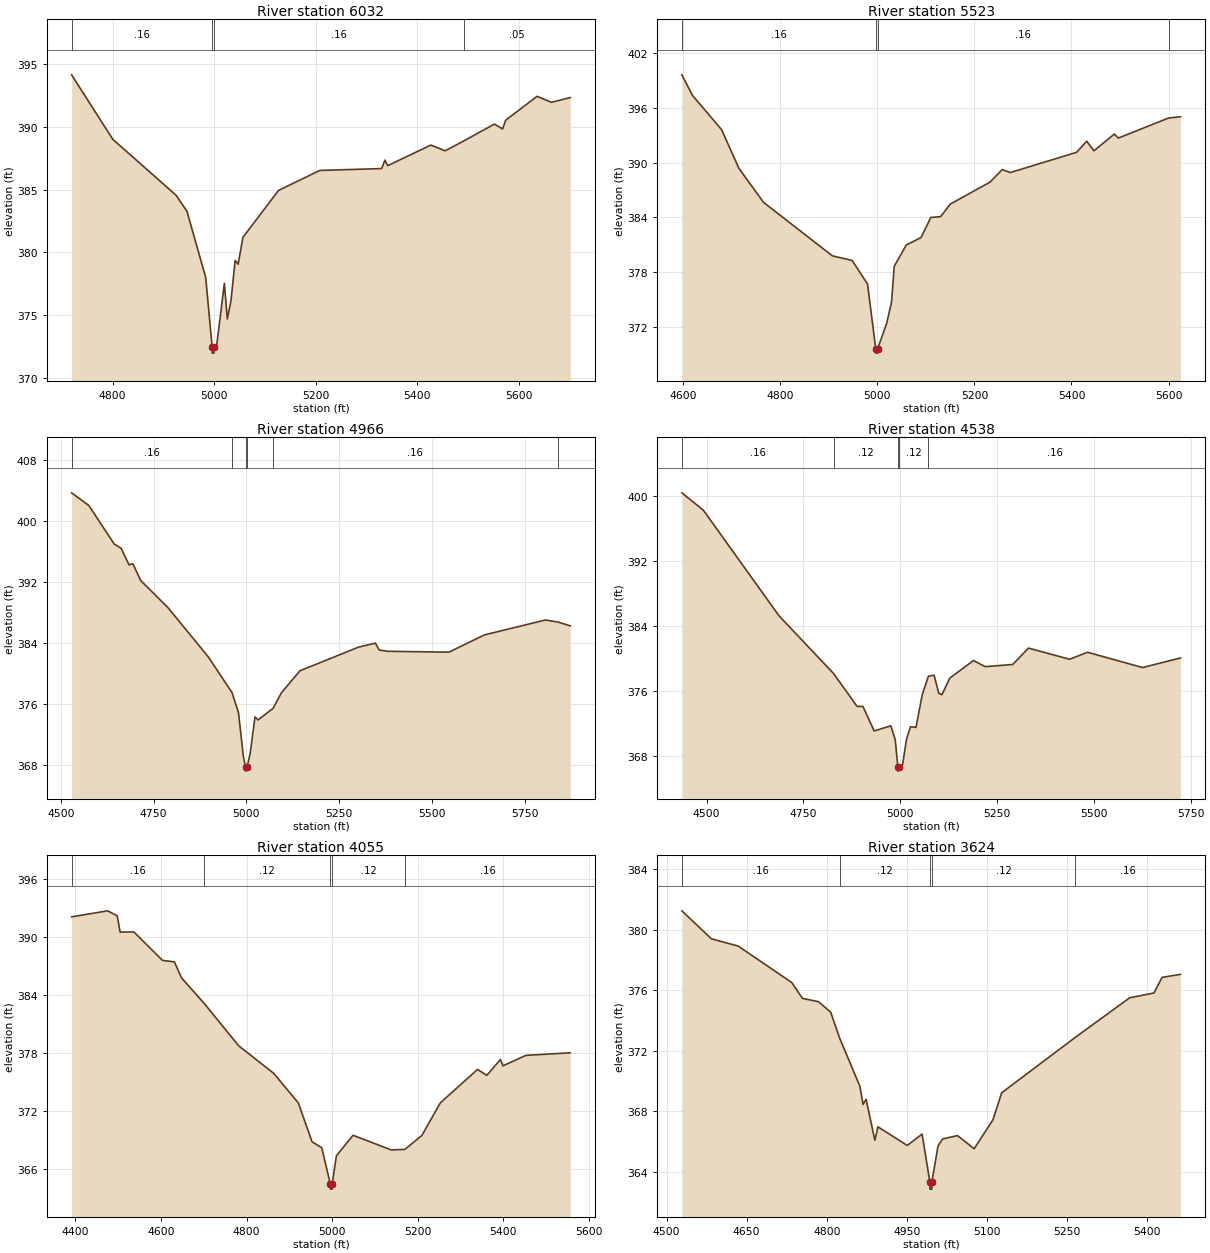
Type RM Length L Ch R = 1,6032,509,509,509
BEGIN DESCRIPTION:
NORTH MINERAL CR TRIB 2 11 0
END DESCRIPTION:
XS GIS Cut Line= 4
      3519987.92     10394276.81      3519899.37     10394429.60
      3519645.90     10394584.12      3519187.53     10394804.62
#Sta/Elev= 30
  4719.2  394.13  4800.3  389.00  4925.2  384.54  4946.5  383.26  4983.3  378.01
  4996.0  372.48  4996.2  371.98  4999.7  371.98  5000.0  372.48  5004.6  372.48
  5020.1  377.54  5025.9  374.70  5033.1  376.16  5041.4  379.36  5047.3  379.06
  5056.6  381.19  5126.8  384.93  5208.0  386.52  5330.0  386.67  5336.2  387.34
  5341.8  386.90  5426.8  388.54  5454.9  388.08  5492.6  388.89  5552.0  390.21
  5568.1  389.82  5574.2  390.52  5636.0  392.42  5664.2  391.94  5701.3  392.32
#Mann=4,-1,0
  4719.2    0.16       0  4996.0    0.07       0  5000.0    0.16       0
  5492.6    0.05       0
Bank Sta=4996,5000
Exp/Cntr=0.3,0.1

Type RM Length L Ch R = 1,5523,557,557,557
BEGIN DESCRIPTION:
NORTH MINERAL CR TRIB 2 10 0
END DESCRIPTION:
XS GIS Cut Line= 3
      3519908.00     10394052.87      3519257.01     10394163.98
      3519046.15     10394464.71
#Sta/Elev= 30
  4597.0  399.64  4618.8  397.39  4679.0  393.61  4714.6  389.37  4765.3  385.64
  4907.3  379.76  4947.9  379.26  4979.7  376.67  4996.6  369.58  4996.9  369.08
  5000.4  369.08  5000.6  369.58  5018.9  372.30  5029.1  374.66  5034.8  378.62
  5059.5  380.95  5089.9  381.77  5110.2  383.98  5130.5  384.07  5150.0  385.44
  5231.9  387.85  5257.4  389.24  5273.8  388.91  5410.6  391.13  5431.5  392.35
  5446.4  391.30  5488.2  393.13  5496.9  392.70  5600.3  394.90  5624.7  395.04
#Mann=4,-1,0
  4597.0    0.16       0  4996.6    0.07       0  5000.6    0.16       0
  5600.3    0.05       0
Bank Sta=4996.6,5000.6
Exp/Cntr=0.3,0.1

Type RM Length L Ch R = 1,4966,428,428,428
BEGIN DESCRIPTION:
NORTH MINERAL CR TRIB 2 9 0
END DESCRIPTION:
XS GIS Cut Line= 3
      3520068.88     10393942.08      3519141.81     10393633.06
      3518775.44     10393615.77
#Sta/Elev= 30
  4529.2  403.71  4575.6  402.05  4644.1  396.98  4662.8  396.42  4683.9  394.26
  4694.5  394.37  4715.5  392.19  4789.3  388.60  4897.1  382.19  4961.4  377.48
  4979.1  374.83  4992.0  369.12  4998.1  367.64  4998.4  367.14  5002.1  367.64
  5010.7  369.53  5023.6  374.26  5031.8  373.87  5072.2  375.38  5095.0  377.46
  5144.8  380.33  5303.0  383.44  5348.0  383.96  5358.5  383.06  5379.6  382.89
  5546.2  382.77  5641.9  385.04  5806.5  387.00  5839.2  386.74  5873.2  386.23
#Mann=6,-1,0
  4529.2    0.16       0  4961.4    0.12       0  4998.1    0.07       0
  5002.1    0.12       0  5072.2    0.16       0  5839.2    0.05       0
Bank Sta=4998.1,5002.1
Exp/Cntr=0.3,0.1

Type RM Length L Ch R = 1,4538,483,483,483
BEGIN DESCRIPTION:
NORTH MINERAL CR TRIB 2 8 0
END DESCRIPTION:
XS GIS Cut Line= 3
      3520155.65     10393705.95      3519729.58     10393422.87
      3518965.88     10393286.04
#Sta/Elev= 30
  4436.3  400.42  4491.9  398.28  4687.4  385.28  4827.9  378.20  4888.8  374.15
  4903.8  374.15  4932.8  371.13  4975.8  371.76  4987.1  370.09  4994.1  366.69
  4994.3  366.19  4998.1  366.69  5006.2  366.99  5016.4  370.11  5026.5  371.65
  5040.8  371.57  5057.0  375.60  5072.9  377.86  5087.5  378.00  5099.6  375.77
  5107.8  375.59  5128.1  377.63  5189.1  379.79  5219.6  379.04  5290.7  379.31
  5331.3  381.32  5437.4  379.95  5483.7  380.81  5625.9  378.93  5723.7  380.11
#Mann=5,-1,0
  4436.3    0.16       0  4827.9    0.12       0  4994.1    0.07       0
  4998.1    0.12       0  5072.9    0.16       0
Bank Sta=4994.1,4998.1
Exp/Cntr=0.3,0.1

Type RM Length L Ch R = 1,4055,431,431,431
BEGIN DESCRIPTION:
NORTH MINERAL CR TRIB 2 7 0
END DESCRIPTION:
XS GIS Cut Line= 3
      3520343.19     10393334.44      3519652.22     10392983.75
      3519311.92     10393174.73
#Sta/Elev= 30
  4391.1  392.06  4475.5  392.68  4497.8  392.16  4504.5  390.48  4536.7  390.50
  4603.5  387.56  4631.4  387.41  4648.0  385.75  4700.8  383.13  4781.6  378.74
  4863.3  375.90  4920.8  372.85  4953.0  368.83  4975.5  368.22  4995.9  364.44
  4996.1  363.94  4999.6  363.94  4999.9  364.44  5009.8  367.38  5048.7  369.50
  5137.8  367.99  5169.6  368.04  5209.5  369.48  5252.9  372.86  5339.6  376.30
  5361.3  375.69  5393.2  377.33  5398.9  376.67  5452.5  377.75  5556.2  378.02
#Mann=5,-1,0
  4391.1    0.16       0  4700.8    0.12       0  4995.9    0.07       0
  4999.9    0.12       0  5169.6    0.16       0
Bank Sta=4995.9,4999.9
Exp/Cntr=0.3,0.1

Type RM Length L Ch R = 1,3624,393,393,393
BEGIN DESCRIPTION:
NORTH MINERAL CR TRIB 2 6 0
END DESCRIPTION:
XS GIS Cut Line= 4
      3520117.25     10392620.58      3519849.02     10392644.01
      3519523.50     10392813.28      3519396.51     10393082.81
#Sta/Elev= 30
  4528.6  381.26  4584.0  379.41  4634.1  378.93  4734.5  376.52  4754.6  375.47
  4784.7  375.25  4807.4  374.56  4824.5  372.82  4862.0  369.67  4868.1  368.46
  4873.7  368.80  4890.2  366.09  4895.9  366.98  4950.9  365.75  4978.7  366.50
  4993.1  363.36  4993.4  362.86  4996.9  362.86  4997.1  363.36  5008.5  365.72
  5017.2  366.18  5045.0  366.40  5076.2  365.53  5111.3  367.44  5127.8  369.23
  5265.9  372.90  5367.5  375.51  5413.0  375.83  5428.2  376.86  5462.7  377.06
#Mann=5,-1,0
  4528.6    0.16       0  4824.5    0.12       0  4993.1    0.07       0
  4997.1    0.12       0  5265.9    0.16       0
Bank Sta=4993.1,4997.1
Exp/Cntr=0.3,0.1

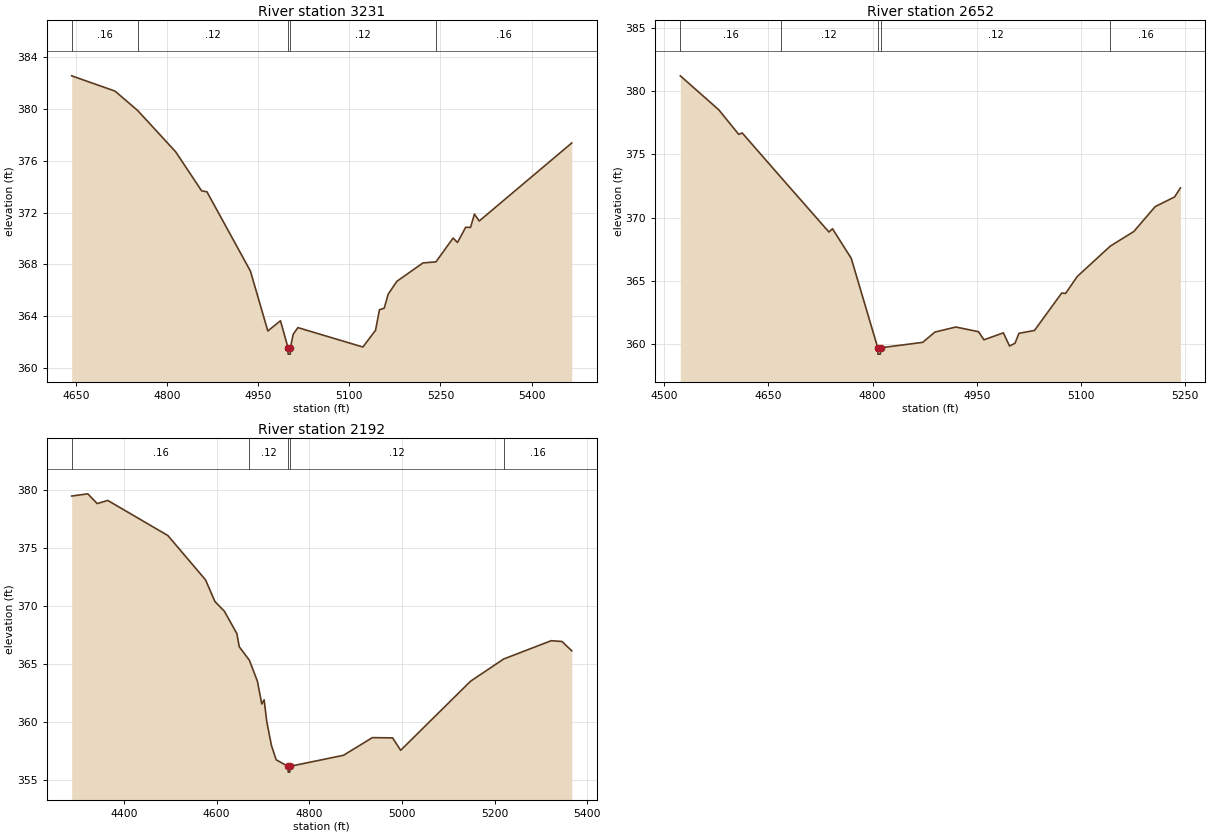
Type RM Length L Ch R = 1,3231,579,579,579
BEGIN DESCRIPTION:
NORTH MINERAL CR TRIB 2 5 0
END DESCRIPTION:
XS GIS Cut Line= 3
      3519568.88     10392261.55      3519419.58     10392494.17
      3519072.83     10392917.21
#Sta/Elev= 30
  4642.8  382.58  4714.2  381.40  4751.7  379.89  4814.0  376.71  4856.8  373.69
  4865.5  373.62  4937.1  367.49  4965.8  362.86  4986.6  363.65  4999.0  361.57
  4999.2  361.07  5002.7  361.07  5003.0  361.57  5007.5  362.60  5015.3  363.12
  5122.3  361.62  5143.1  362.91  5149.6  364.50  5157.4  364.62  5163.9  365.70
  5178.3  366.70  5221.3  368.12  5242.6  368.20  5270.8  370.04  5278.0  369.70
  5291.7  370.88  5299.5  370.86  5306.0  371.89  5313.9  371.36  5466.2  377.39
#Mann=5,-1,0
  4642.8    0.16       0  4751.7    0.12       0  4999.0    0.07       0
  5003.0    0.12       0  5242.6    0.16       0
Bank Sta=4999,5003
Exp/Cntr=0.3,0.1

Type RM Length L Ch R = 1,2652,460,460,460
BEGIN DESCRIPTION:
NORTH MINERAL CR TRIB 2 4 0
END DESCRIPTION:
XS GIS Cut Line= 3
      3519527.23     10392219.86      3519124.44     10392251.11
      3518842.08     10392391.65
#Sta/Elev= 30
  4523.5  381.20  4578.8  378.52  4607.5  376.58  4612.5  376.69  4668.2  373.19
  4737.3  368.87  4742.4  369.13  4769.4  366.79  4807.5  359.73  4807.7  359.23
  4811.2  359.23  4811.5  359.73  4872.2  360.16  4889.7  360.97  4919.8  361.37
  4952.5  361.00  4960.2  360.36  4988.2  360.91  4997.1  359.87  5005.0  360.09
  5010.6  360.87  5033.0  361.10  5072.1  364.05  5077.7  364.02  5094.5  365.36
  5142.1  367.76  5175.9  368.91  5206.5  370.87  5234.5  371.64  5242.9  372.35
#Mann=5,-1,0
  4523.5    0.16       0  4668.2    0.12       0  4807.5    0.07       0
  4811.5    0.12       0  5142.1    0.16       0
Bank Sta=4807.5,4811.5
Exp/Cntr=0.3,0.1

Type RM Length L Ch R = 1,2192,0,0,0
BEGIN DESCRIPTION:
NORTH MINERAL CR TRIB 2 1 0
END DESCRIPTION:
XS GIS Cut Line= 3
      3519756.35     10391723.34      3519176.53     10391827.50
      3518728.60     10392025.42
#Sta/Elev= 30
  4287.5  379.44  4322.3  379.63  4342.6  378.79  4365.4  379.06  4495.0  376.04
  4576.3  372.22  4596.6  370.35  4616.9  369.52  4643.9  367.59  4649.0  366.46
  4671.0  365.29  4688.1  363.50  4697.6  361.53  4702.7  361.89  4708.4  360.00
  4718.5  357.95  4728.7  356.72  4754.4  356.16  4754.6  355.66  4758.1  355.66
  4758.4  356.16  4873.9  357.11  4936.1  358.63  4979.8  358.61  4997.2  357.54
  5148.0  363.49  5219.3  365.40  5322.0  366.98  5345.3  366.91  5366.3  366.11
#Mann=5,-1,0
  4287.5    0.16       0  4671.0    0.12       0  4754.4    0.07       0
  4758.4    0.12       0  5219.3    0.16       0
Bank Sta=4754.4,4758.4
Exp/Cntr=0.3,0.1

Chan Stop Cuts=-1