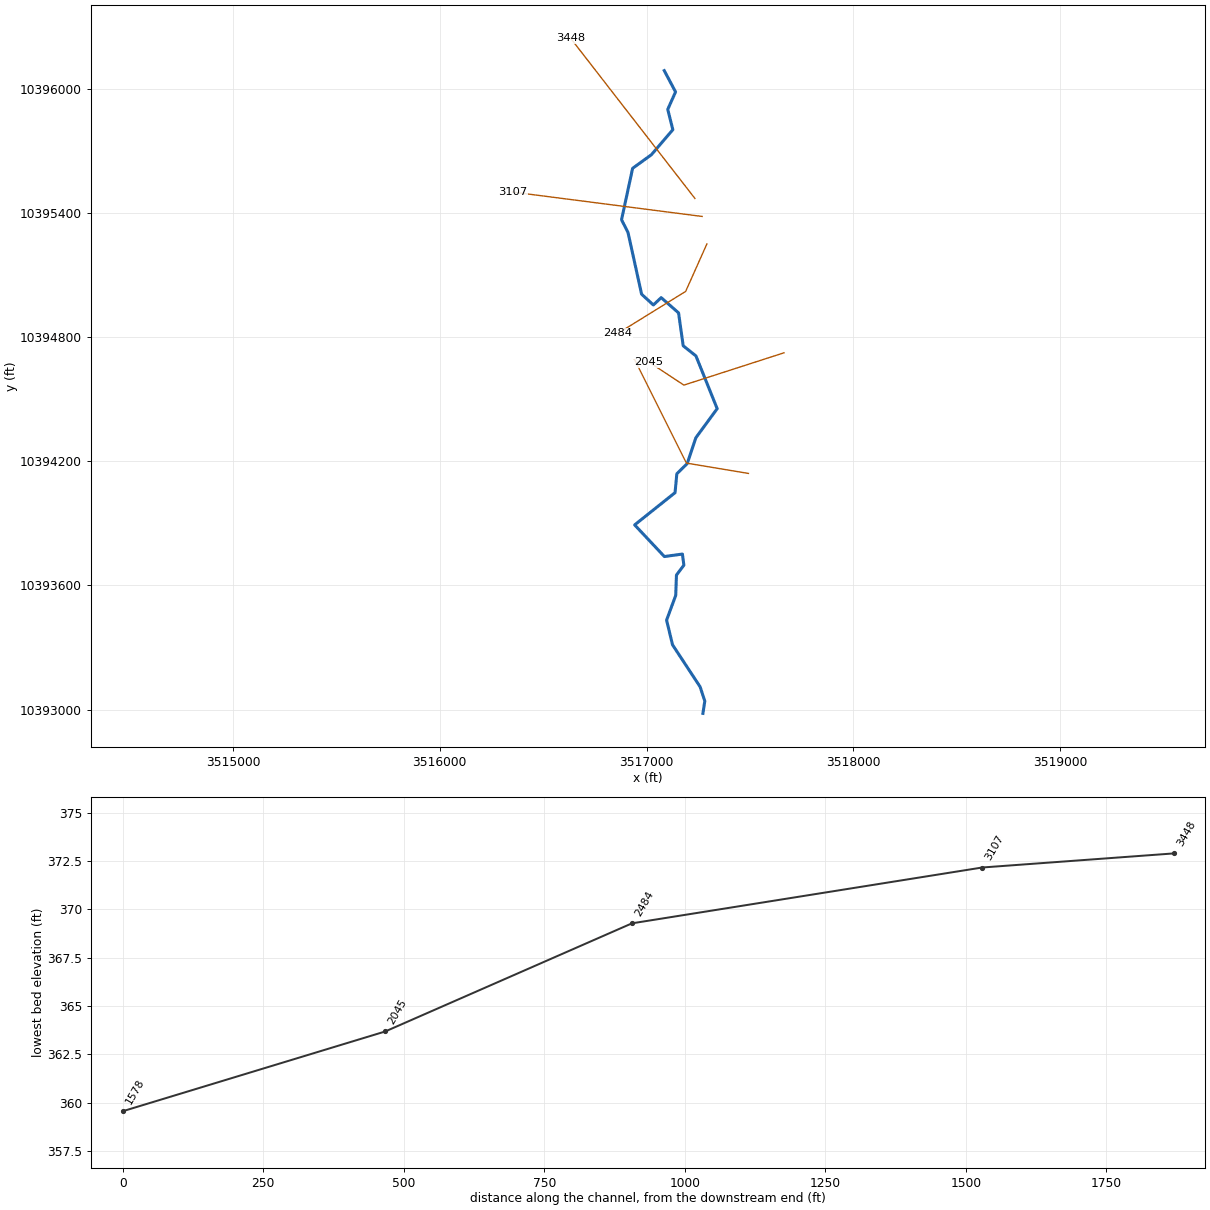
--- NORTH MINERAL CR TRIB 3.prj (project) ---

Proj Title=NORTH MINERAL CR TRIB 3 Base Level Engineering
Current Plan=p01
Default Exp/Contr=0.3,0.1
English Units
Geom File=g01
Flow File=f01
Plan File=p01
BEGIN DESCRIPTION:
NORTH MINERAL CR TRIB 3
END DESCRIPTION:

--- NORTH MINERAL CR TRIB 3.p01 (plan) ---

Plan Title=Multiple Run
Short Identifier=Multiple
Geom File=g01
Flow File=f01
Subcritical Flow
K Sum by GR= 0
Std Step Tol= 0.01
Critical Tol= 0.01
Num of Std Step Trials= 20
Max Error Tol= 0.3
Flow Tol Ratio= 0.001
Split Flow NTrial= 30
Split Flow Tol= 0.02
Split Flow Ratio= 0.02
Log Output Level= 0
Friction Slope Method= 1
Unsteady Friction Slope Method= 2
Unsteady Bridges Friction Slope Method= 1
Parabolic Critical Depth
Global Vel Dist=  1 , 1 , 1
Global Log Level= 0
CheckData=True
Encroach Param= -1, 0, 0, 0
BEGIN DESCRIPTION:
Multiple Run
END DESCRIPTION:

--- NORTH MINERAL CR TRIB 3.f01 (steady flow) ---

Flow Title=Multiple
Number of Profiles=7
Profile Names=10-year,25-year,50-year,1pct_min,100-year,1pct_plu,500-year
River Rch & RM= NORTH MINERAL CR,Reach-1,3448
     612     830    1009     898    1214    1642    1751
Boundary for River Rch & Prof#=NORTH MINERAL CR,Reach-1,1
Up Type=0
Dn Type=3
Dn Slope=0.005
Boundary for River Rch & Prof#=NORTH MINERAL CR,Reach-1,2
Up Type=0
Dn Type=3
Dn Slope=0.005
Boundary for River Rch & Prof#=NORTH MINERAL CR,Reach-1,3
Up Type=0
Dn Type=3
Dn Slope=0.005
Boundary for River Rch & Prof#=NORTH MINERAL CR,Reach-1,4
Up Type=0
Dn Type=3
Dn Slope=0.005
Boundary for River Rch & Prof#=NORTH MINERAL CR,Reach-1,5
Up Type=0
Dn Type=3
Dn Slope=0.005
Boundary for River Rch & Prof#=NORTH MINERAL CR,Reach-1,6
Up Type=0
Dn Type=3
Dn Slope=0.005
Boundary for River Rch & Prof#=NORTH MINERAL CR,Reach-1,7
Up Type=0
Dn Type=3
Dn Slope=0.005

--- NORTH MINERAL CR TRIB 3.g01 (geometry) ---

Geom Title=Existing Conditions

River Reach=NORTH MINERAL CR,Reach-1
Reach XY= 30
      3517085.11     10396089.02      3517139.74     10395986.21
      3517102.01     10395901.47      3517126.61     10395803.54
      3517023.05     10395682.44      3516932.19     10395616.71
      3516878.66     10395368.11      3516909.91     10395306.34
      3516975.68     10395008.09      3517032.54     10394956.00
      3517070.21     10394991.59      3517154.32     10394917.81
      3517176.68     10394758.71      3517238.40     10394709.61
      3517341.01     10394454.70      3517237.96     10394314.14
      3517196.20     10394189.33      3517145.87     10394139.89
      3517137.38     10394048.71      3516942.00     10393892.78
      3517085.71     10393739.86      3517172.93     10393751.83
      3517179.99     10393697.96      3517144.10     10393650.33
      3517140.56     10393551.89      3517096.43     10393432.24
      3517125.25     10393312.92      3517258.45     10393110.11
      3517281.18     10393041.23      3517272.11     10392981.64

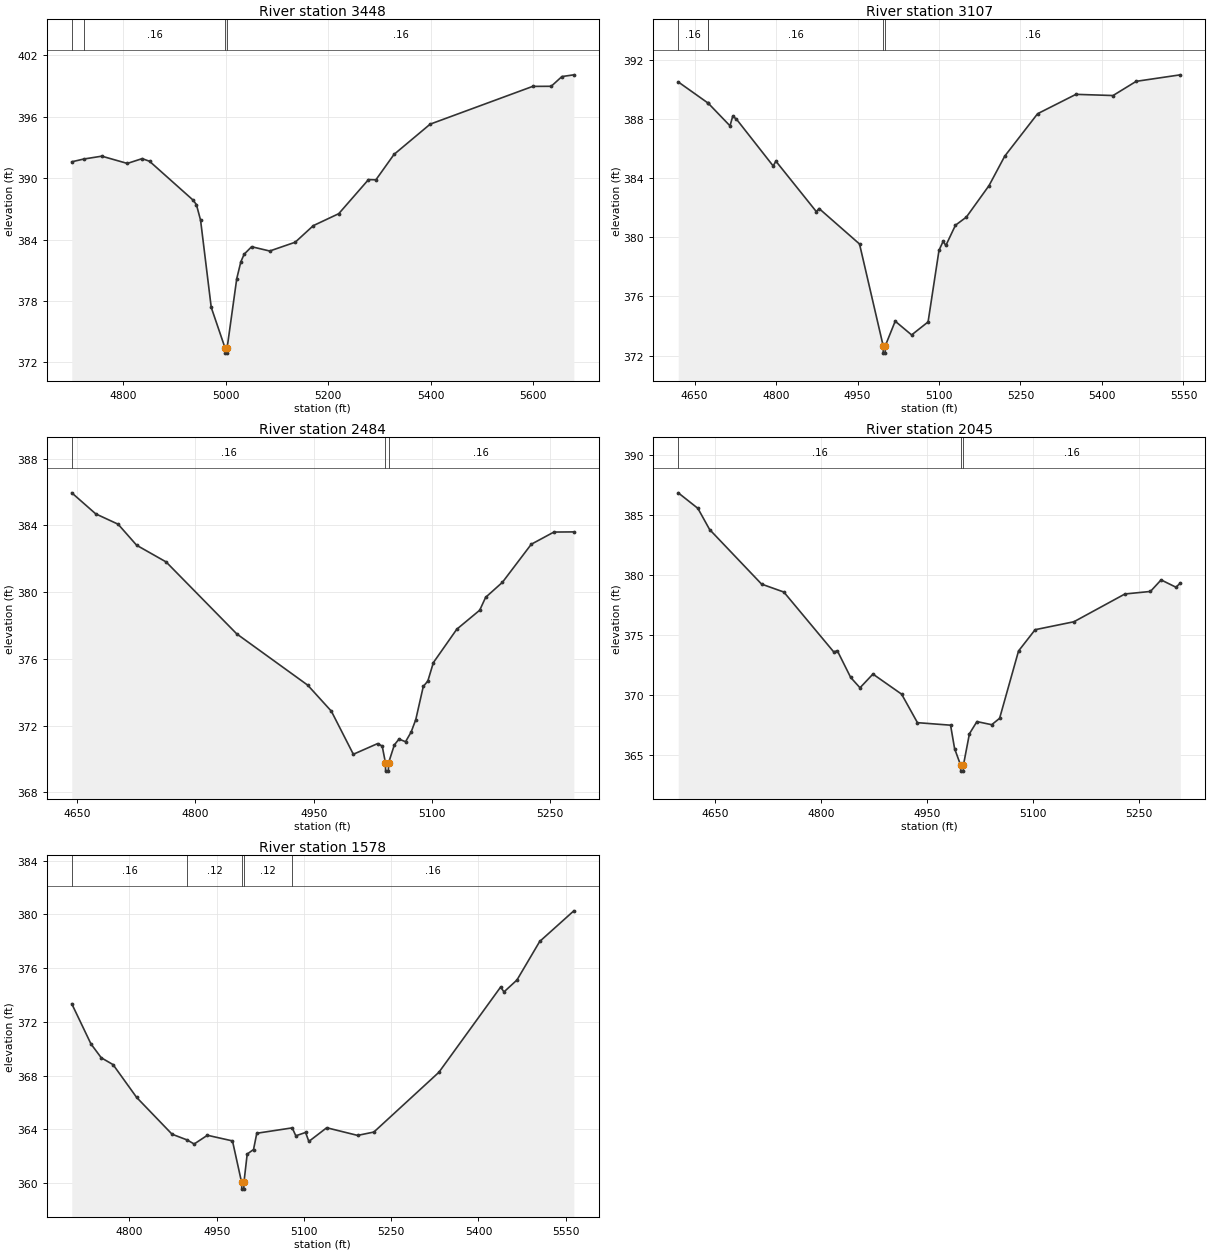
Type RM Length L Ch R = 1,3448,341,341,341
BEGIN DESCRIPTION:
NORTH MINERAL CR TRIB 3 26 0
END DESCRIPTION:
XS GIS Cut Line= 2
      3517233.45     10395470.88      3516632.81     10396245.11
#Sta/Elev= 30
  4699.4  391.60  4722.8  391.87  4758.0  392.15  4807.8  391.44  4836.8  391.91
  4851.2  391.65  4936.3  387.85  4942.7  387.41  4950.8  385.89  4971.6  377.37
  4998.6  373.40  4998.8  372.90  5002.3  372.90  5002.6  373.40  5021.4  380.18
  5029.4  381.83  5035.9  382.57  5050.4  383.30  5085.7  382.88  5135.5  383.74
  5170.8  385.36  5220.5  386.53  5278.5  389.86  5293.0  389.84  5328.3  392.32
  5398.9  395.28  5599.0  398.97  5635.1  398.98  5656.0  399.93  5679.3  400.10
#Mann=4,-1,0
  4699.4    0.05       0  4722.8    0.16       0  4998.6    0.07       0
  5002.6    0.16       0
Bank Sta=4998.6,5002.6
Exp/Cntr=0.3,0.1

Type RM Length L Ch R = 1,3107,623,623,623
BEGIN DESCRIPTION:
NORTH MINERAL CR TRIB 3 16 0
END DESCRIPTION:
XS GIS Cut Line= 2
      3517268.19     10395384.04      3516351.56     10395502.09
#Sta/Elev= 30
  4620.0  390.51  4674.5  389.09  4675.5  389.06  4715.3  387.54  4720.3  388.19
  4727.0  388.00  4794.7  384.83  4799.8  385.15  4874.2  381.74  4879.2  381.95
  4953.7  379.55  4997.2  372.67  4997.4  372.17  5000.9  372.17  5001.2  372.67
  5019.4  374.33  5049.6  373.40  5079.9  374.28  5100.0  379.12  5107.6  379.73
  5112.6  379.45  5130.3  380.82  5150.4  381.37  5192.1  383.50  5221.0  385.49
  5281.5  388.36  5352.1  389.67  5420.4  389.59  5463.0  390.55  5544.2  390.99
#Mann=5,-1,0
  4620.0    0.16       0  4674.5    0.05       0  4675.5    0.16       0
  4997.2    0.07       0  5001.2    0.16       0
Bank Sta=4997.2,5001.2
Exp/Cntr=0.3,0.1

Type RM Length L Ch R = 1,2484,439,439,439
BEGIN DESCRIPTION:
NORTH MINERAL CR TRIB 3 6 0
END DESCRIPTION:
XS GIS Cut Line= 3
      3517291.11     10395250.90      3517188.69     10395021.77
      3516860.56     10394818.64
#Sta/Elev= 30
  4643.1  385.95  4673.5  384.69  4701.9  384.07  4725.4  382.81  4762.8  381.81
  4852.4  377.50  4942.4  374.43  4972.4  372.87  5000.3  370.29  5031.1  370.93
  5036.9  370.78  5041.0  369.78  5041.2  369.28  5044.7  369.28  5045.0  369.78
  5052.3  370.85  5058.2  371.20  5066.5  371.04  5073.6  371.62  5079.5  372.37
  5089.0  374.35  5094.8  374.68  5101.8  375.78  5131.5  377.78  5160.6  378.92
  5168.1  379.69  5189.4  380.59  5226.0  382.87  5254.7  383.60  5280.0  383.61
#Mann=3,-1,0
  4643.1    0.16       0  5041.0    0.07       0  5045.0    0.16       0
Bank Sta=5041,5045
Exp/Cntr=0.3,0.1

Type RM Length L Ch R = 1,2045,467,467,467
BEGIN DESCRIPTION:
NORTH MINERAL CR TRIB 3 5 0
END DESCRIPTION:
XS GIS Cut Line= 3
      3517664.37     10394724.89      3517180.01     10394568.64
      3517011.60     10394679.76
#Sta/Elev= 30
  4598.1  386.82  4625.9  385.53  4642.5  383.77  4716.1  379.23  4747.6  378.57
  4818.1  373.60  4823.4  373.68  4842.2  371.47  4855.4  370.61  4873.7  371.75
  4914.3  370.08  4936.7  367.71  4983.6  367.50  4989.3  365.55  4997.8  364.18
  4998.0  363.68  5001.5  363.68  5001.8  364.18  5010.3  366.79  5020.9  367.80
  5041.8  367.54  5053.0  368.07  5079.8  373.67  5103.3  375.44  5158.2  376.10
  5230.4  378.41  5266.5  378.62  5281.6  379.58  5302.7  378.97  5308.8  379.32
#Mann=3,-1,0
  4598.1    0.16       0  4997.8    0.07       0  5001.8    0.16       0
Bank Sta=4997.8,5001.8
Exp/Cntr=0.3,0.1

Type RM Length L Ch R = 1,1578,0,0,0
BEGIN DESCRIPTION:
NORTH MINERAL CR TRIB 3 2 1
END DESCRIPTION:
XS GIS Cut Line= 3
      3517492.13     10394141.64      3517192.11     10394191.64
      3516942.10     10394691.66
#Sta/Elev= 30
  4700.8  373.35  4733.8  370.36  4751.5  369.33  4771.8  368.82  4812.3  366.38
  4873.2  363.64  4899.2  363.21  4911.2  362.91  4934.0  363.56  4977.1  363.14
  4992.8  360.05  4993.1  359.55  4996.6  359.55  4996.8  360.05  5002.4  362.16
  5013.3  362.50  5018.9  363.71  5079.8  364.11  5086.0  363.52  5102.8  363.77
  5108.4  363.10  5139.1  364.12  5192.2  363.55  5220.2  363.80  5332.0  368.25
  5438.2  374.60  5443.8  374.23  5466.2  375.12  5505.3  377.99  5564.0  380.27
#Mann=5,-1,0
  4700.8    0.16       0  4899.2    0.12       0  4992.8    0.07       0
  4996.8    0.12       0  5079.8    0.16       0
Bank Sta=4992.8,4996.8
Exp/Cntr=0.3,0.1

Chan Stop Cuts=-1