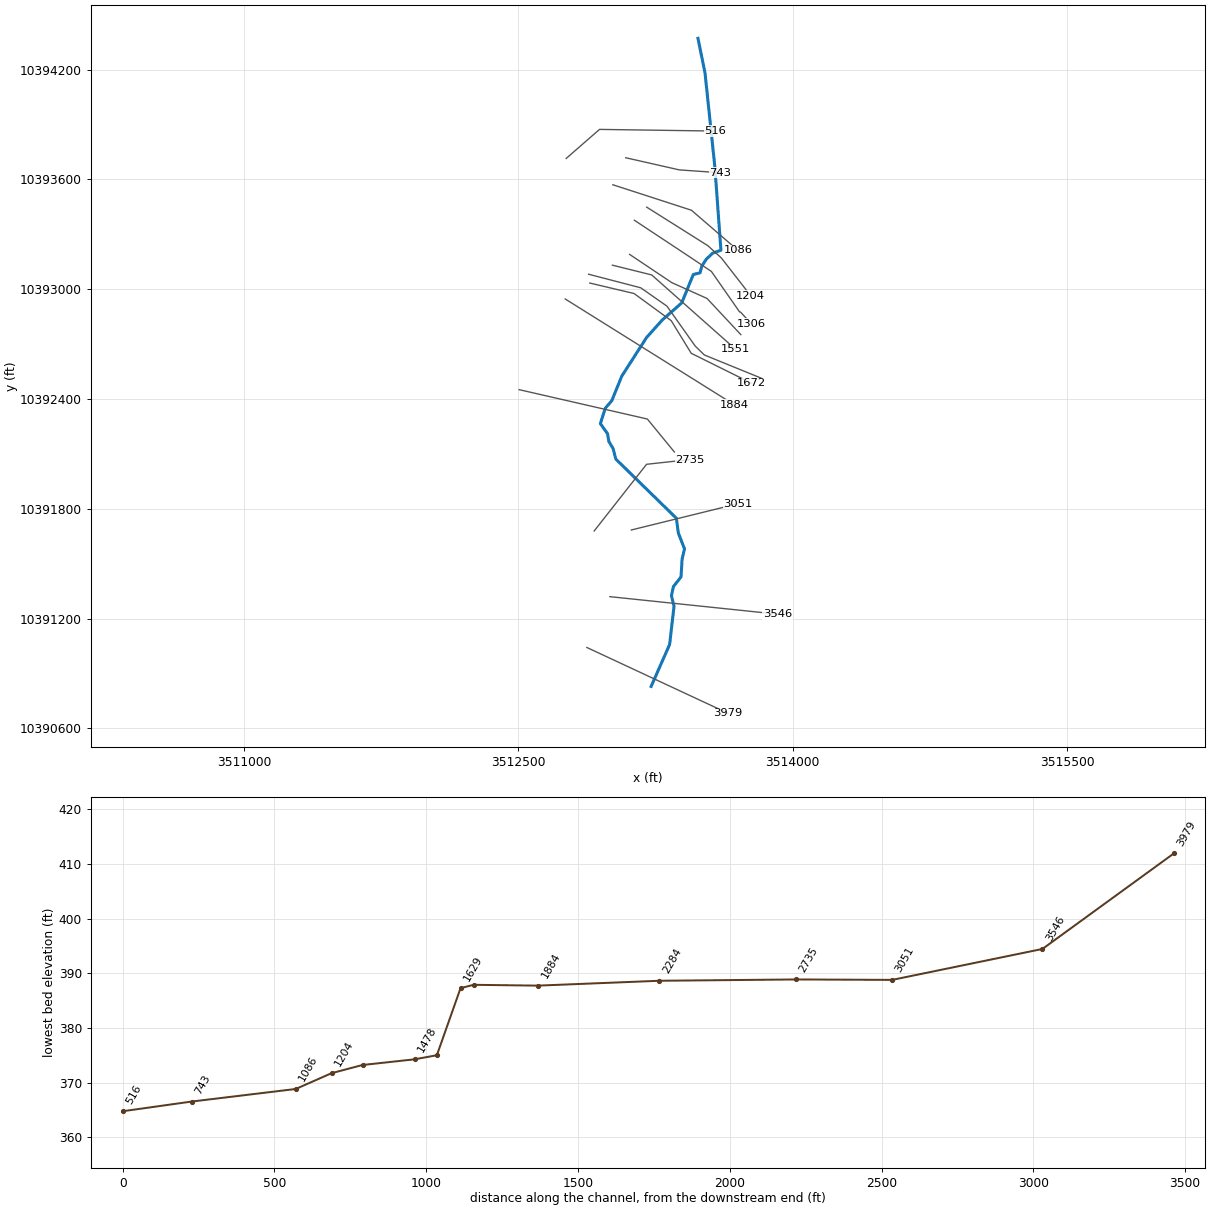
--- NORTH MINERAL CR TRIB 4.prj (project) ---

Proj Title=NORTH MINERAL CR TRIB 4 Base Level Engineering
Current Plan=p01
Default Exp/Contr=0.3,0.1
English Units
Geom File=g01
Flow File=f01
Plan File=p01
BEGIN DESCRIPTION:
NORTH MINERAL CR TRIB 4
END DESCRIPTION:

--- NORTH MINERAL CR TRIB 4.p01 (plan) ---

Plan Title=Multiple Run
Short Identifier=Multiple
Geom File=g01
Flow File=f01
Subcritical Flow
K Sum by GR= 0
Std Step Tol= 0.01
Critical Tol= 0.01
Num of Std Step Trials= 20
Max Error Tol= 0.3
Flow Tol Ratio= 0.001
Split Flow NTrial= 30
Split Flow Tol= 0.02
Split Flow Ratio= 0.02
Log Output Level= 0
Friction Slope Method= 1
Unsteady Friction Slope Method= 2
Unsteady Bridges Friction Slope Method= 1
Parabolic Critical Depth
Global Vel Dist=  1 , 1 , 1
Global Log Level= 0
CheckData=True
Encroach Param= -1, 0, 0, 0
BEGIN DESCRIPTION:
Multiple Run
END DESCRIPTION:

--- NORTH MINERAL CR TRIB 4.f01 (steady flow) ---

Flow Title=Multiple
Number of Profiles=7
Profile Names=10-year,25-year,50-year,1pct_min,100-year,1pct_plu,500-year
River Rch & RM= NORTH MINERAL CR,Reach-1,3979
     696     952    1163    1040    1406    1902    2048
Boundary for River Rch & Prof#=NORTH MINERAL CR,Reach-1,1
Up Type=0
Dn Type=3
Dn Slope=0.005
Boundary for River Rch & Prof#=NORTH MINERAL CR,Reach-1,2
Up Type=0
Dn Type=3
Dn Slope=0.005
Boundary for River Rch & Prof#=NORTH MINERAL CR,Reach-1,3
Up Type=0
Dn Type=3
Dn Slope=0.005
Boundary for River Rch & Prof#=NORTH MINERAL CR,Reach-1,4
Up Type=0
Dn Type=3
Dn Slope=0.005
Boundary for River Rch & Prof#=NORTH MINERAL CR,Reach-1,5
Up Type=0
Dn Type=3
Dn Slope=0.005
Boundary for River Rch & Prof#=NORTH MINERAL CR,Reach-1,6
Up Type=0
Dn Type=3
Dn Slope=0.005
Boundary for River Rch & Prof#=NORTH MINERAL CR,Reach-1,7
Up Type=0
Dn Type=3
Dn Slope=0.005

--- NORTH MINERAL CR TRIB 4.g01 (geometry) ---

Geom Title=Existing Conditions

River Reach=NORTH MINERAL CR,Reach-1
Reach XY= 30
      3513226.03     10390828.99      3513327.02     10391057.88
      3513351.11     10391266.90      3513337.02     10391325.10
      3513347.53     10391373.99      3513389.41     10391427.64
      3513395.41     10391526.02      3513408.61     10391580.43
      3513374.76     10391667.43      3513363.93     10391748.29
      3513033.25     10392071.41      3513017.74     10392129.84
      3512994.95     10392167.84      3512987.85     10392209.99
      3512948.42     10392265.66      3512975.77     10392350.07
      3513010.83     10392390.59      3513065.51     10392524.90
      3513201.15     10392736.48      3513287.95     10392833.06
      3513393.21     10392925.29      3513456.52     10393080.54
      3513493.65     10393089.94      3513502.83     10393126.21
      3513527.28     10393163.95      3513562.17     10393197.25
      3513607.50     10393213.61      3513574.51     10393667.61
      3513520.73     10394181.60      3513482.11     10394371.64

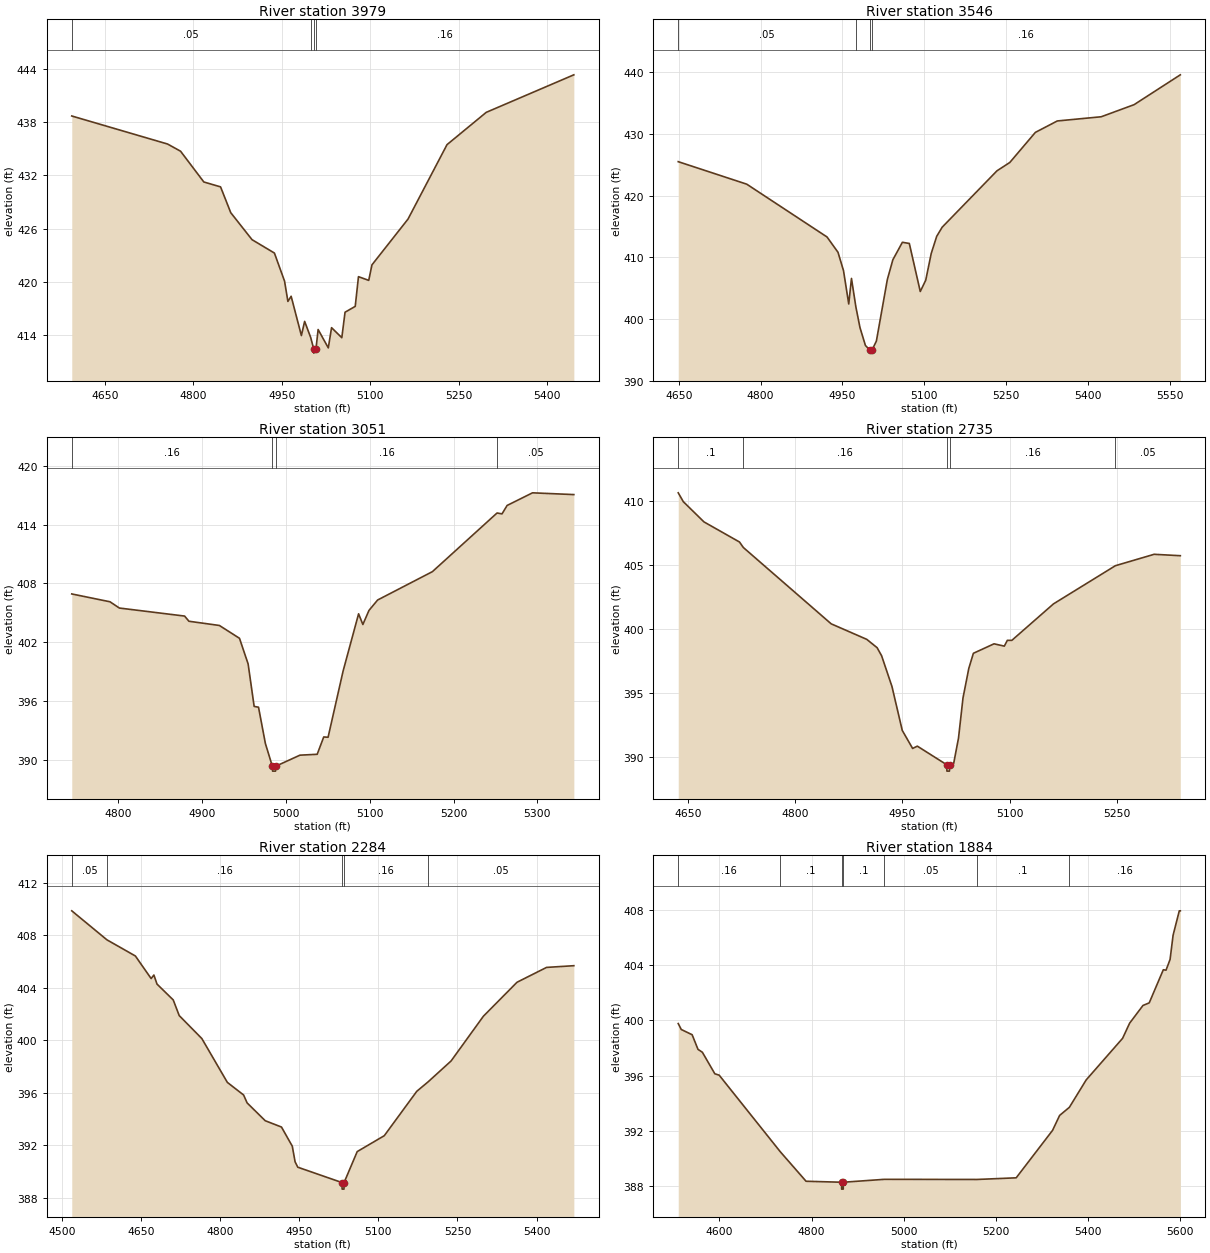
Type RM Length L Ch R = 1,3979,433,433,433
BEGIN DESCRIPTION:
NORTH MINERAL CR TRIB 4 11
END DESCRIPTION:
XS GIS Cut Line= 2
      3512874.74     10391041.78      3513647.19     10390681.59
#Sta/Elev= 30
  4593.4  438.69  4756.0  435.53  4778.1  434.72  4817.6  431.25  4846.0  430.70
  4863.3  427.79  4899.4  424.75  4937.4  423.24  4954.6  420.08  4960.3  417.79
  4965.8  418.37  4983.2  413.94  4988.7  415.54  4999.0  413.72  5004.0  412.46
  5004.3  411.96  5008.0  412.46  5011.6  414.62  5028.9  412.55  5034.4  414.83
  5051.8  413.70  5057.3  416.57  5074.6  417.23  5080.1  420.58  5097.5  420.16
  5103.0  421.91  5164.2  427.07  5230.4  435.46  5297.0  439.10  5445.7  443.33
#Mann=4,-1,0
  4593.4    0.05       0  4999.0    0.16       0  5004.0    0.07       0
  5008.0    0.16       0
Bank Sta=5004,5008
Exp/Cntr=0.3,0.1

Type RM Length L Ch R = 1,3546,495,495,495
BEGIN DESCRIPTION:
NORTH MINERAL CR TRIB 4 10
END DESCRIPTION:
XS GIS Cut Line= 2
      3513000.64     10391319.54      3513916.47     10391224.05
#Sta/Elev= 30
  4648.8  425.52  4774.5  421.87  4921.7  413.31  4941.8  410.83  4951.9  407.86
  4961.5  402.45  4966.5  406.59  4974.6  401.97  4982.1  398.63  4992.1  395.72
  5000.2  394.98  5000.4  394.48  5004.2  394.98  5012.2  396.43  5032.3  406.41
  5042.4  409.61  5059.9  412.45  5072.6  412.26  5092.7  404.47  5102.7  406.30
  5112.8  410.64  5122.8  413.41  5132.9  414.90  5233.4  424.04  5256.9  425.39
  5303.8  430.27  5344.0  432.12  5424.5  432.80  5484.8  434.76  5569.6  439.60
#Mann=4,-1,0
  4648.8    0.05       0  4974.6    0.16       0  5000.2    0.07       0
  5004.2    0.16       0
Bank Sta=5000.2,5004.2
Exp/Cntr=0.3,0.1

Type RM Length L Ch R = 1,3051,316,316,316
BEGIN DESCRIPTION:
NORTH MINERAL CR TRIB 4 9 0
END DESCRIPTION:
XS GIS Cut Line= 2
      3513117.80     10391684.11      3513699.42     10391827.34
#Sta/Elev= 30
  4744.5  406.92  4790.1  406.12  4801.3  405.48  4879.1  404.66  4884.3  404.13
  4920.6  403.70  4944.6  402.39  4954.9  399.77  4962.1  395.43  4967.3  395.35
  4975.5  391.64  4983.8  389.32  4984.1  388.82  4987.6  388.82  4987.8  389.32
  5016.7  390.45  5037.3  390.54  5045.1  392.31  5050.3  392.28  5068.2  399.04
  5086.7  404.89  5091.8  403.80  5099.1  405.24  5109.4  406.30  5174.8  409.20
  5251.9  415.19  5257.8  415.10  5263.9  415.96  5294.2  417.25  5343.5  417.07
#Mann=4,-1,0
  4744.5    0.16       0  4983.8    0.07       0  4987.8    0.16       0
  5251.9    0.05       0
Bank Sta=4983.8,4987.8
Exp/Cntr=0.3,0.1

Type RM Length L Ch R = 1,2735,451,451,451
BEGIN DESCRIPTION:
NORTH MINERAL CR TRIB 4 8 0
END DESCRIPTION:
XS GIS Cut Line= 3
      3512914.66     10391678.65      3513201.12     10392043.23
      3513438.45     10392069.12
#Sta/Elev= 30
  4636.5  410.63  4643.6  409.94  4672.5  408.36  4722.2  406.79  4727.6  406.36
  4850.5  400.40  4900.2  399.19  4914.7  398.54  4921.0  397.91  4935.5  395.51
  4949.9  392.08  4964.4  390.67  4971.0  390.85  5012.1  389.40  5012.4  388.90
  5015.9  388.90  5016.1  389.40  5021.8  389.49  5028.6  391.48  5034.9  394.62
  5043.0  396.92  5049.4  398.10  5078.3  398.84  5092.7  398.66  5096.9  399.11
  5103.2  399.11  5161.5  401.96  5248.1  404.94  5302.3  405.83  5338.9  405.72
#Mann=5,-1,0
  4636.5     0.1       0  4727.6    0.16       0  5012.1    0.07       0
  5016.1    0.16       0  5248.1    0.05       0
Bank Sta=5012.1,5016.1
Exp/Cntr=0.3,0.1

Type RM Length L Ch R = 1,2284,400,400,400
BEGIN DESCRIPTION:
NORTH MINERAL CR TRIB 4 7 0
END DESCRIPTION:
XS GIS Cut Line= 3
      3512504.55     10392451.21      3513205.46     10392290.63
      3513353.02     10392110.52
#Sta/Elev= 30
  4518.9  409.86  4585.6  407.65  4639.5  406.42  4669.4  404.70  4674.6  404.97
  4680.5  404.28  4711.3  403.07  4722.6  401.88  4765.5  400.13  4813.9  396.79
  4844.7  395.83  4851.3  395.23  4885.7  393.87  4916.5  393.39  4937.0  391.93
  4942.3  390.74  4947.4  390.33  5031.2  389.16  5031.5  388.66  5035.0  388.66
  5035.2  389.16  5060.1  391.52  5111.4  392.73  5173.0  396.11  5195.0  396.85
  5238.0  398.42  5299.3  401.83  5363.1  404.42  5419.1  405.55  5470.8  405.68
#Mann=5,-1,0
  4518.9    0.05       0  4585.6    0.16       0  5031.2    0.07       0
  5035.2    0.16       0  5195.0    0.05       0
Bank Sta=5031.2,5035.2
Exp/Cntr=0.3,0.1

Type RM Length L Ch R = 1,1884,212,212,212
BEGIN DESCRIPTION:
Mapping XS f87b57a8
END DESCRIPTION:
XS GIS Cut Line= 2
      3512756.47     10392946.76      3513680.90     10392368.67
#Sta/Elev= 30
  4510.6  399.77  4517.2  399.34  4540.8  398.96  4553.5  397.90  4563.0  397.69
  4590.1  396.13  4599.5  396.03  4732.2  390.48  4788.2  388.34  4865.2  388.27
  4865.4  387.77  4868.9  387.77  4869.2  388.27  4958.3  388.48  5159.3  388.47
  5244.5  388.59  5323.5  392.03  5338.8  393.11  5360.0  393.70  5396.6  395.69
  5475.6  398.70  5490.9  399.80  5519.8  401.08  5533.4  401.27  5564.0  403.67
  5569.9  403.64  5578.7  404.42  5585.2  406.17  5598.7  407.94  5600.9  407.94
#Mann=7,-1,0
  4510.6    0.16       0  4732.2     0.1       0  4865.2   0.033       0
  4869.2     0.1       0  4958.3    0.05       0  5159.3     0.1       0
  5360.0    0.16       0
Bank Sta=4865.2,4869.2
Exp/Cntr=0.3,0.1

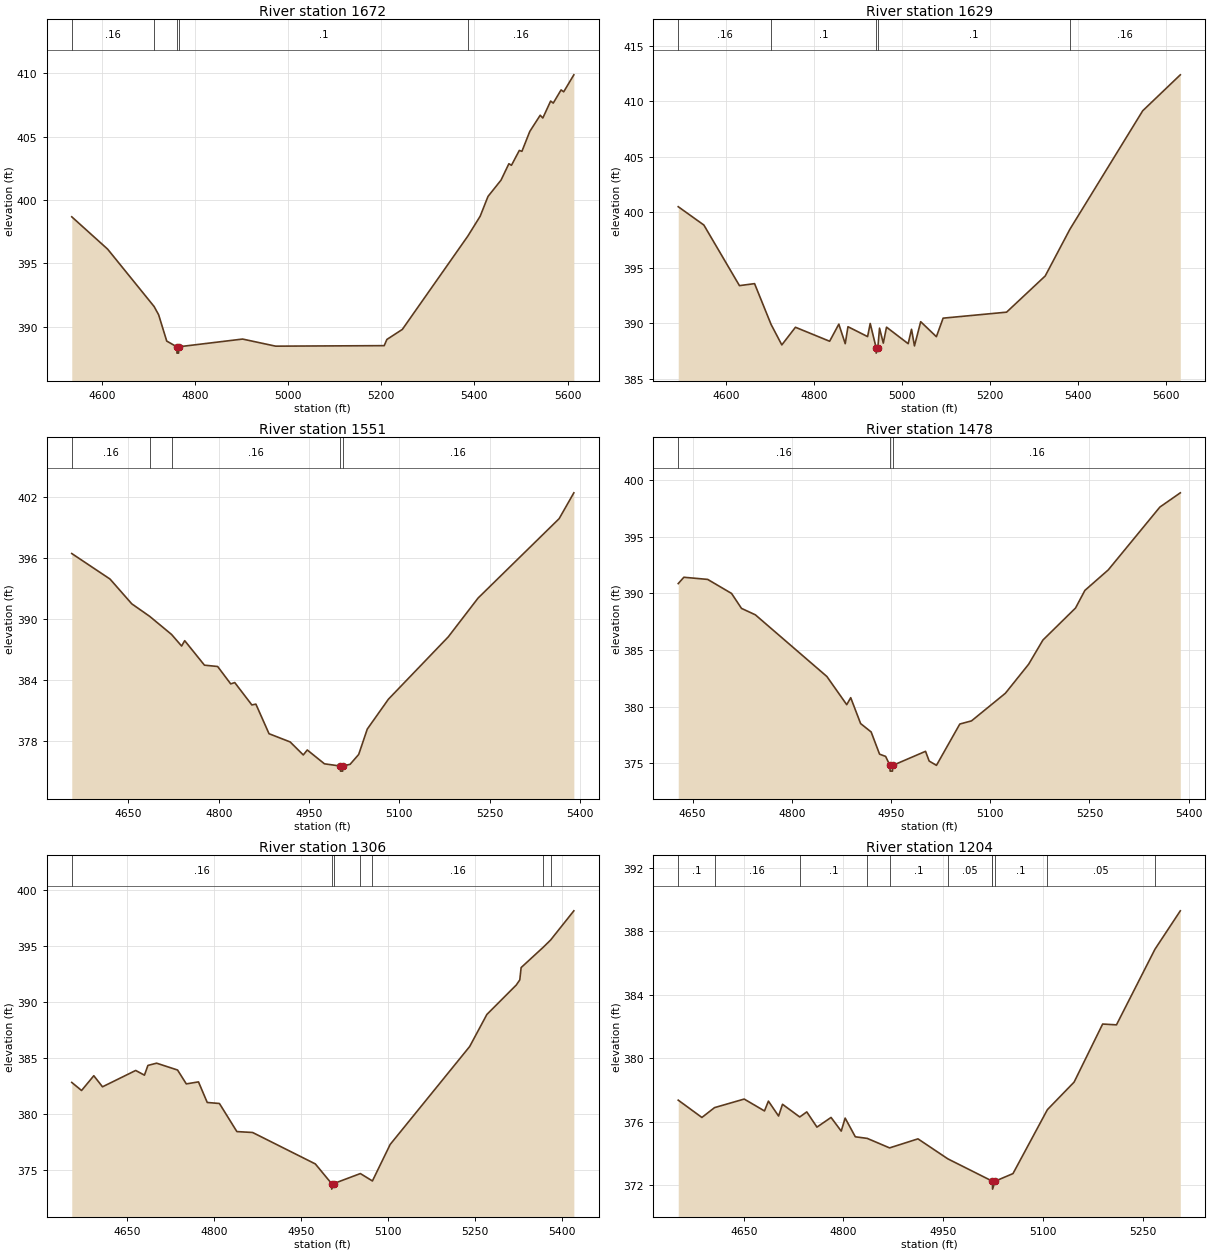
Type RM Length L Ch R = 1,1672,43,43,43
BEGIN DESCRIPTION:
NORTH MINERAL CR TRIB 4 6 0
END DESCRIPTION:
XS GIS Cut Line= 5
      3512890.58     10393034.01      3513132.76     10392976.72
      3513335.88     10392828.28      3513445.26     10392649.90
      3513775.20     10392486.23
#Sta/Elev= 30
  4535.6  398.68  4612.6  396.13  4712.4  391.60  4722.1  390.95  4739.5  388.87
  4761.2  388.42  4761.5  387.92  4765.0  387.92  4765.2  388.42  4902.3  389.03
  4973.3  388.47  5206.4  388.51  5212.2  389.00  5245.3  389.79  5386.0  397.16
  5412.5  398.73  5429.3  400.29  5457.3  401.58  5474.1  402.87  5479.7  402.75
  5496.5  403.92  5502.1  403.85  5519.0  405.42  5541.4  406.70  5547.0  406.48
  5563.8  407.82  5569.4  407.66  5586.2  408.70  5591.8  408.55  5613.6  409.89
#Mann=5,-1,0
  4535.6    0.16       0  4712.4     0.1       0  4761.2    0.07       0
  4765.2     0.1       0  5386.0    0.16       0
Bank Sta=4761.2,4765.2
Exp/Cntr=0.3,0.1

Type RM Length L Ch R = 1,1629,78,78,78
BEGIN DESCRIPTION:
NORTH MINERAL CR TRIB 4 3 2
END DESCRIPTION:
XS GIS Cut Line= 6
      3512884.02     10393082.20      3513169.22     10393007.97
      3513312.45     10392907.71      3513467.40     10392688.96
      3513516.87     10392640.78      3513826.78     10392514.48
#Sta/Elev= 30
  4490.3  400.50  4548.6  398.85  4629.6  393.39  4664.0  393.57  4701.5  389.90
  4726.0  388.05  4757.0  389.64  4834.8  388.38  4855.7  389.92  4870.3  388.16
  4876.5  389.69  4921.2  388.80  4927.1  389.98  4940.5  387.81  4940.7  387.31
  4944.5  387.81  4948.3  389.56  4956.9  388.21  4964.2  389.65  5013.5  388.16
  5021.1  389.46  5027.8  387.96  5042.0  390.14  5077.7  388.79  5093.0  390.46
  5237.4  391.00  5325.3  394.26  5381.5  398.47  5547.1  409.14  5632.7  412.38
#Mann=5,-1,0
  4490.3    0.16       0  4701.5     0.1       0  4940.5    0.07       0
  4944.5     0.1       0  5381.5    0.16       0
Bank Sta=4940.5,4944.5
Exp/Cntr=0.3,0.1

Type RM Length L Ch R = 1,1551,73,73,73
BEGIN DESCRIPTION:
Mapping XS 0130e7d0
END DESCRIPTION:
XS GIS Cut Line= 3
      3513014.28     10393131.67      3513229.11     10393078.28
      3513687.28     10392672.18
#Sta/Elev= 30
  4556.0  396.44  4619.5  393.93  4655.7  391.49  4685.4  390.26  4721.7  388.48
  4738.4  387.34  4743.5  387.87  4776.3  385.46  4798.2  385.33  4819.9  383.62
  4826.6  383.75  4855.0  381.55  4861.7  381.63  4883.5  378.72  4918.6  377.91
  4940.4  376.63  4947.0  377.12  4975.5  375.76  5001.9  375.54  5002.2  375.04
  5005.7  375.04  5005.9  375.54  5018.1  375.71  5032.4  376.68  5046.6  379.17
  5081.7  382.11  5181.2  388.25  5230.6  392.06  5365.2  399.87  5389.6  402.41
#Mann=5,-1,0
  4556.0    0.16       0  4685.4     0.1       0  4721.7    0.16       0
  5001.9    0.07       0  5005.9    0.16       0
Bank Sta=5001.9,5005.9
Exp/Cntr=0.3,0.1

Type RM Length L Ch R = 1,1478,172,172,172
BEGIN DESCRIPTION:
NORTH MINERAL CR TRIB 4 5 0
END DESCRIPTION:
XS GIS Cut Line= 4
      3513108.64     10393190.46      3513338.69     10393036.37
      3513531.83     10392949.56      3513716.31     10392752.06
#Sta/Elev= 30
  4628.4  390.86  4636.9  391.42  4672.9  391.23  4709.0  389.99  4724.0  388.67
  4745.0  388.10  4853.1  382.65  4883.1  380.16  4889.1  380.78  4904.1  378.49
  4920.0  377.75  4932.7  375.79  4941.9  375.59  4948.4  374.79  4948.7  374.29
  4952.2  374.29  4952.4  374.79  5002.2  376.04  5007.7  375.18  5018.7  374.80
  5054.0  378.45  5071.7  378.73  5122.9  381.17  5158.1  383.74  5179.6  385.87
  5228.9  388.70  5243.1  390.26  5278.4  392.07  5356.4  397.62  5387.3  398.88
#Mann=3,-1,0
  4628.4    0.16       0  4948.4    0.07       0  4952.4    0.16       0
Bank Sta=4948.4,4952.4
Exp/Cntr=0.3,0.1

Type RM Length L Ch R = 1,1306,102,102,102
BEGIN DESCRIPTION:
NORTH MINERAL CR TRIB 4 3 1
END DESCRIPTION:
XS GIS Cut Line= 6
      3513134.66     10393377.10      3513442.85     10393173.09
      3513555.70     10393097.13      3513709.78     10392875.78
      3513714.12     10392875.78      3513772.74     10392812.81
#Sta/Elev= 30
  4555.2  382.78  4572.1  382.06  4593.2  383.38  4608.2  382.39  4665.4  383.85
  4680.5  383.43  4686.5  384.30  4701.5  384.50  4737.6  383.89  4752.7  382.65
  4773.7  382.83  4788.8  380.99  4809.8  380.90  4839.9  378.39  4867.0  378.31
  4975.2  375.50  5003.1  373.75  5003.4  373.25  5007.1  373.75  5052.8  374.64
  5073.6  373.98  5104.2  377.24  5241.3  385.99  5270.9  388.85  5321.6  391.48
  5327.7  391.94  5330.0  393.04  5368.4  394.87  5380.8  395.50  5420.9  398.11
#Mann=7,-1,0
  4555.2    0.16       0  5003.1    0.07       0  5007.1    0.16       0
  5052.8     0.1       0  5073.6    0.16       0  5368.4     0.1       0
  5380.8    0.16       0
Bank Sta=5003.1,5007.1
Exp/Cntr=0.3,0.1

Type RM Length L Ch R = 1,1204,118,118,118
BEGIN DESCRIPTION:
NORTH MINERAL CR TRIB 4 4 0
END DESCRIPTION:
XS GIS Cut Line= 4
      3513201.96     10393448.70      3513536.17     10393238.19
      3513609.95     10393170.92      3513769.83     10392965.67
#Sta/Elev= 30
  4551.5  377.36  4587.1  376.27  4606.1  376.89  4650.7  377.43  4681.2  376.68
  4687.1  377.30  4702.4  376.36  4708.3  377.10  4734.2  376.30  4744.8  376.62
  4760.1  375.66  4781.3  376.27  4796.6  375.41  4802.5  376.23  4817.8  375.05
  4835.7  374.95  4869.3  374.35  4912.0  374.92  4956.9  373.66  5023.9  372.25
  5024.0  372.25  5024.2  371.75  5028.0  372.25  5054.9  372.73  5106.6  376.76
  5146.8  378.50  5189.7  382.16  5210.5  382.11  5268.4  386.88  5306.5  389.30
#Mann=11,-1,0
  4551.5     0.1       0  4606.1    0.16       0  4734.2     0.1       0
  4835.7    0.16       0  4869.3     0.1       0  4956.9    0.05       0
  5023.9     0.1       0  5024.0   0.035       0  5028.0     0.1       0
  5106.6    0.05       0  5268.4    0.16       0
Bank Sta=5024,5028
Exp/Cntr=0.3,0.1

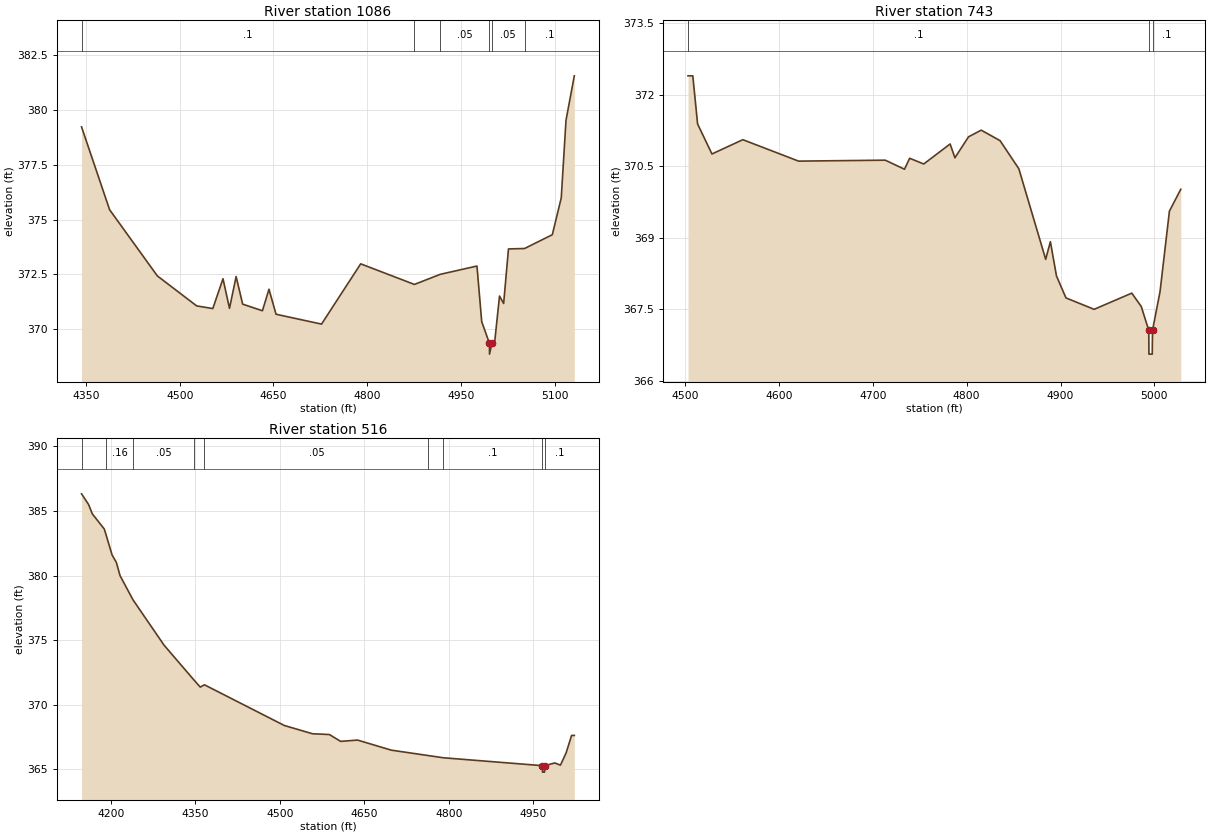
Type RM Length L Ch R = 1,1086,343,343,343
BEGIN DESCRIPTION:
NORTH MINERAL CR TRIB 4 3 0
END DESCRIPTION:
XS GIS Cut Line= 3
      3513016.76     10393571.26      3513446.47     10393431.93
      3513701.67     10393211.89
#Sta/Elev= 30
  4342.8  379.23  4387.7  375.45  4464.1  372.43  4527.1  371.06  4552.9  370.94
  4569.2  372.30  4579.6  370.95  4590.2  372.40  4600.7  371.14  4632.3  370.84
  4642.8  371.82  4654.1  370.68  4726.9  370.23  4789.6  372.98  4875.6  372.04
  4916.8  372.50  4975.7  372.88  4983.3  370.34  4995.6  369.36  4995.8  368.86
  4999.6  369.36  5004.2  369.46  5011.8  371.51  5018.4  371.17  5026.1  373.66
  5051.9  373.68  5096.3  374.31  5110.6  375.99  5118.2  379.53  5131.5  381.56
#Mann=6,-1,0
  4342.8     0.1       0  4875.6    0.16       0  4916.8    0.05       0
  4995.6   0.035       0  4999.6    0.05       0  5051.9     0.1       0
Bank Sta=4995.6,4999.6
Exp/Cntr=0.3,0.1

Type RM Length L Ch R = 1,743,227,227,227
BEGIN DESCRIPTION:
NORTH MINERAL CR TRIB 4 3 3
END DESCRIPTION:
XS GIS Cut Line= 3
      3513087.22     10393718.90      3513380.16     10393652.50
      3513604.14     10393636.87
#Sta/Elev= 30
  4503.2  372.40  4508.3  372.40  4513.4  371.39  4528.7  370.76  4561.6  371.06
  4621.0  370.61  4713.3  370.63  4733.8  370.44  4739.3  370.67  4754.3  370.55
  4782.4  370.97  4787.5  370.68  4802.0  371.12  4815.5  371.26  4835.6  371.04
  4855.6  370.45  4884.2  368.55  4889.2  368.92  4895.7  368.20  4905.8  367.74
  4935.8  367.50  4975.9  367.84  4986.0  367.56  4994.0  367.06  4994.2  366.56
  4997.7  366.56  4998.0  367.06  5006.0  367.87  5016.0  369.56  5028.1  370.02
#Mann=3,-1,0
  4503.2     0.1       0  4994.0    0.07       0  4998.0     0.1       0
Bank Sta=4994,4998
Exp/Cntr=0.3,0.1

Type RM Length L Ch R = 1,516,0,0,0
BEGIN DESCRIPTION:
NORTH MINERAL CR TRIB 4 1 0
END DESCRIPTION:
XS GIS Cut Line= 3
      3512761.70     10393715.03      3512943.96     10393873.86
      3513576.74     10393864.74
#Sta/Elev= 30
  4148.2  386.33  4160.6  385.51  4167.3  384.78  4188.5  383.61  4191.3  383.22
  4202.4  381.60  4210.0  381.02  4216.6  379.99  4239.6  378.12  4294.6  374.62
  4347.9  371.91  4359.0  371.37  4366.3  371.55  4508.1  368.40  4558.1  367.76
  4588.1  367.70  4608.1  367.17  4638.1  367.27  4698.1  366.49  4763.9  366.07
  4790.6  365.90  4966.2  365.29  4966.4  364.79  4969.9  364.79  4970.2  365.29
  4988.2  365.50  4998.2  365.33  5008.2  366.27  5018.0  367.63  5022.8  367.63
#Mann=9,-1,0
  4148.2    0.05       0  4191.3    0.16       0  4239.6    0.05       0
  4347.9    0.12       0  4366.3    0.05       0  4763.9    0.12       0
  4790.6     0.1       0  4966.2    0.07       0  4970.2     0.1       0
Bank Sta=4966.2,4970.2
Exp/Cntr=0.3,0.1

Chan Stop Cuts=-1