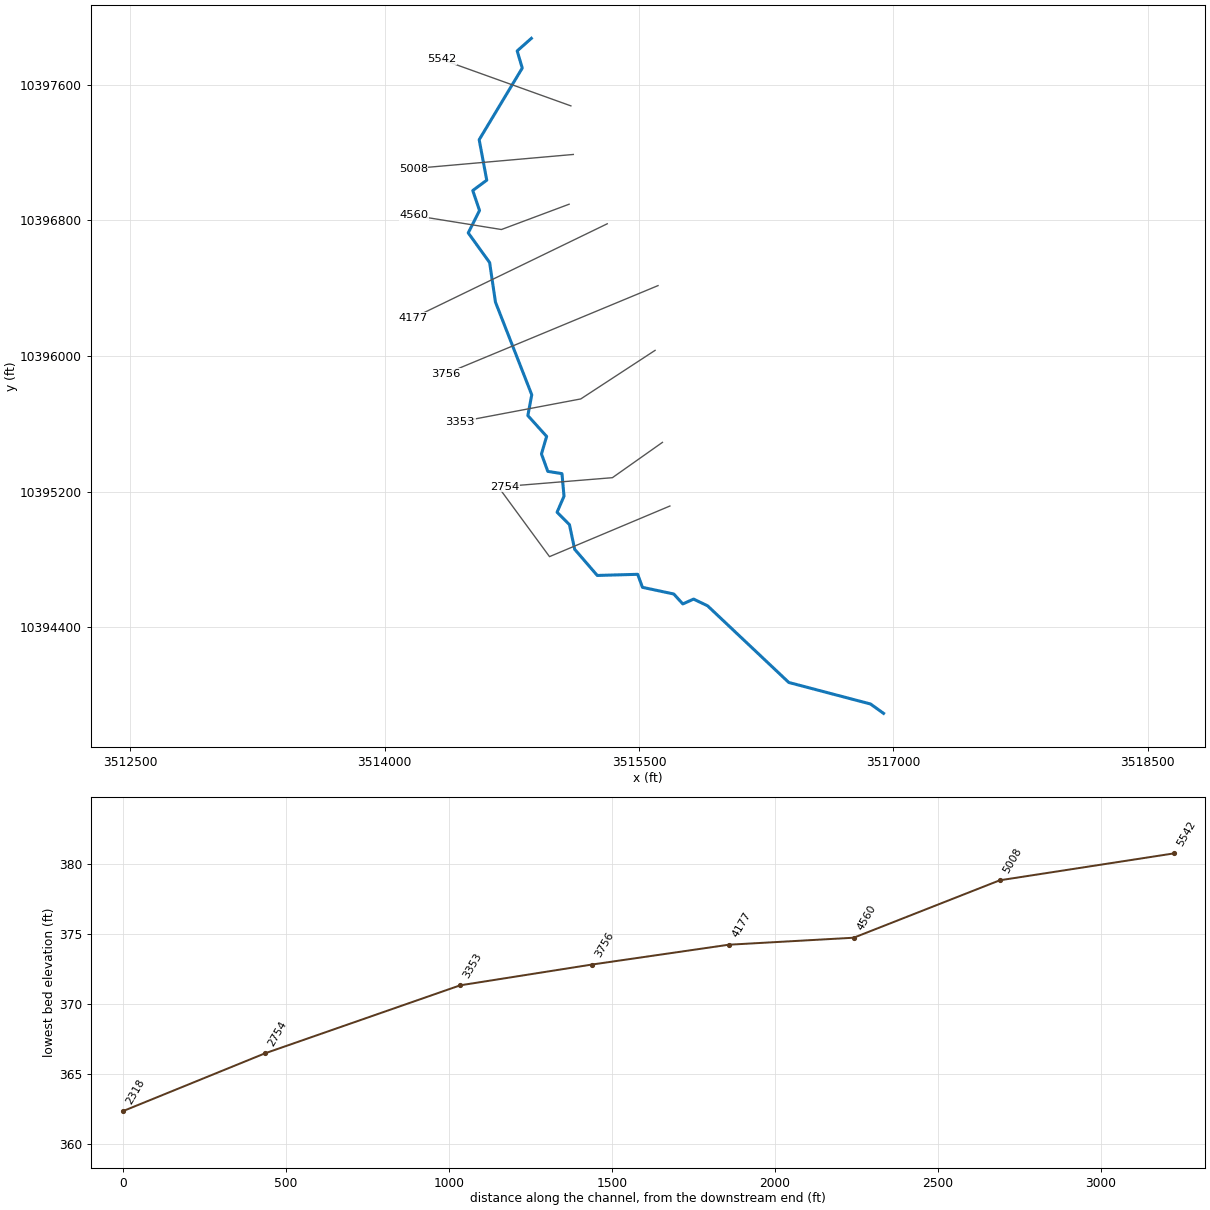
--- NORTH MINERAL CR TRIB 5.prj (project) ---

Proj Title=NORTH MINERAL CR TRIB 5 Base Level Engineering
Current Plan=p01
Default Exp/Contr=0.3,0.1
English Units
Geom File=g01
Flow File=f01
Plan File=p01
BEGIN DESCRIPTION:
NORTH MINERAL CR TRIB 5
END DESCRIPTION:

--- NORTH MINERAL CR TRIB 5.p01 (plan) ---

Plan Title=Multiple Run
Short Identifier=Multiple
Geom File=g01
Flow File=f01
Subcritical Flow
K Sum by GR= 0
Std Step Tol= 0.01
Critical Tol= 0.01
Num of Std Step Trials= 20
Max Error Tol= 0.3
Flow Tol Ratio= 0.001
Split Flow NTrial= 30
Split Flow Tol= 0.02
Split Flow Ratio= 0.02
Log Output Level= 0
Friction Slope Method= 1
Unsteady Friction Slope Method= 2
Unsteady Bridges Friction Slope Method= 1
Parabolic Critical Depth
Global Vel Dist=  1 , 1 , 1
Global Log Level= 0
CheckData=True
Encroach Param= -1, 0, 0, 0
BEGIN DESCRIPTION:
Multiple Run
END DESCRIPTION:

--- NORTH MINERAL CR TRIB 5.f01 (steady flow) ---

Flow Title=Multiple
Number of Profiles=7
Profile Names=10-year,25-year,50-year,1pct_min,100-year,1pct_plu,500-year
River Rch & RM= NORTH MINERAL CR,Reach-1,5542
     919    1276    1574    1419    1919    2595    2843
Boundary for River Rch & Prof#=NORTH MINERAL CR,Reach-1,1
Up Type=0
Dn Type=3
Dn Slope=0.005
Boundary for River Rch & Prof#=NORTH MINERAL CR,Reach-1,2
Up Type=0
Dn Type=3
Dn Slope=0.005
Boundary for River Rch & Prof#=NORTH MINERAL CR,Reach-1,3
Up Type=0
Dn Type=3
Dn Slope=0.005
Boundary for River Rch & Prof#=NORTH MINERAL CR,Reach-1,4
Up Type=0
Dn Type=3
Dn Slope=0.005
Boundary for River Rch & Prof#=NORTH MINERAL CR,Reach-1,5
Up Type=0
Dn Type=3
Dn Slope=0.005
Boundary for River Rch & Prof#=NORTH MINERAL CR,Reach-1,6
Up Type=0
Dn Type=3
Dn Slope=0.005
Boundary for River Rch & Prof#=NORTH MINERAL CR,Reach-1,7
Up Type=0
Dn Type=3
Dn Slope=0.005

--- NORTH MINERAL CR TRIB 5.g01 (geometry) ---

Geom Title=Existing Conditions

River Reach=NORTH MINERAL CR,Reach-1
Reach XY= 30
      3514864.99     10397872.68      3514781.29     10397798.41
      3514811.16     10397697.38      3514557.17     10397274.80
      3514601.78     10397036.01      3514519.33     10396975.13
      3514559.18     10396857.32      3514492.61     10396725.26
      3514618.79     10396550.28      3514653.16     10396317.08
      3514867.25     10395770.57      3514844.20     10395647.99
      3514954.97     10395524.87      3514924.40     10395421.75
      3514961.90     10395318.72      3515045.45     10395305.56
      3515057.43     10395172.32      3515016.51     10395077.95
      3515089.59     10395004.48      3515120.27     10394859.44
      3515253.54     10394705.02      3515491.91     10394711.75
      3515520.09     10394634.96      3515704.71     10394595.67
      3515758.10     10394537.12      3515821.65     10394565.59
      3515904.27     10394525.87      3516383.04     10394073.95
      3516865.02     10393946.95      3516942.11     10393891.64

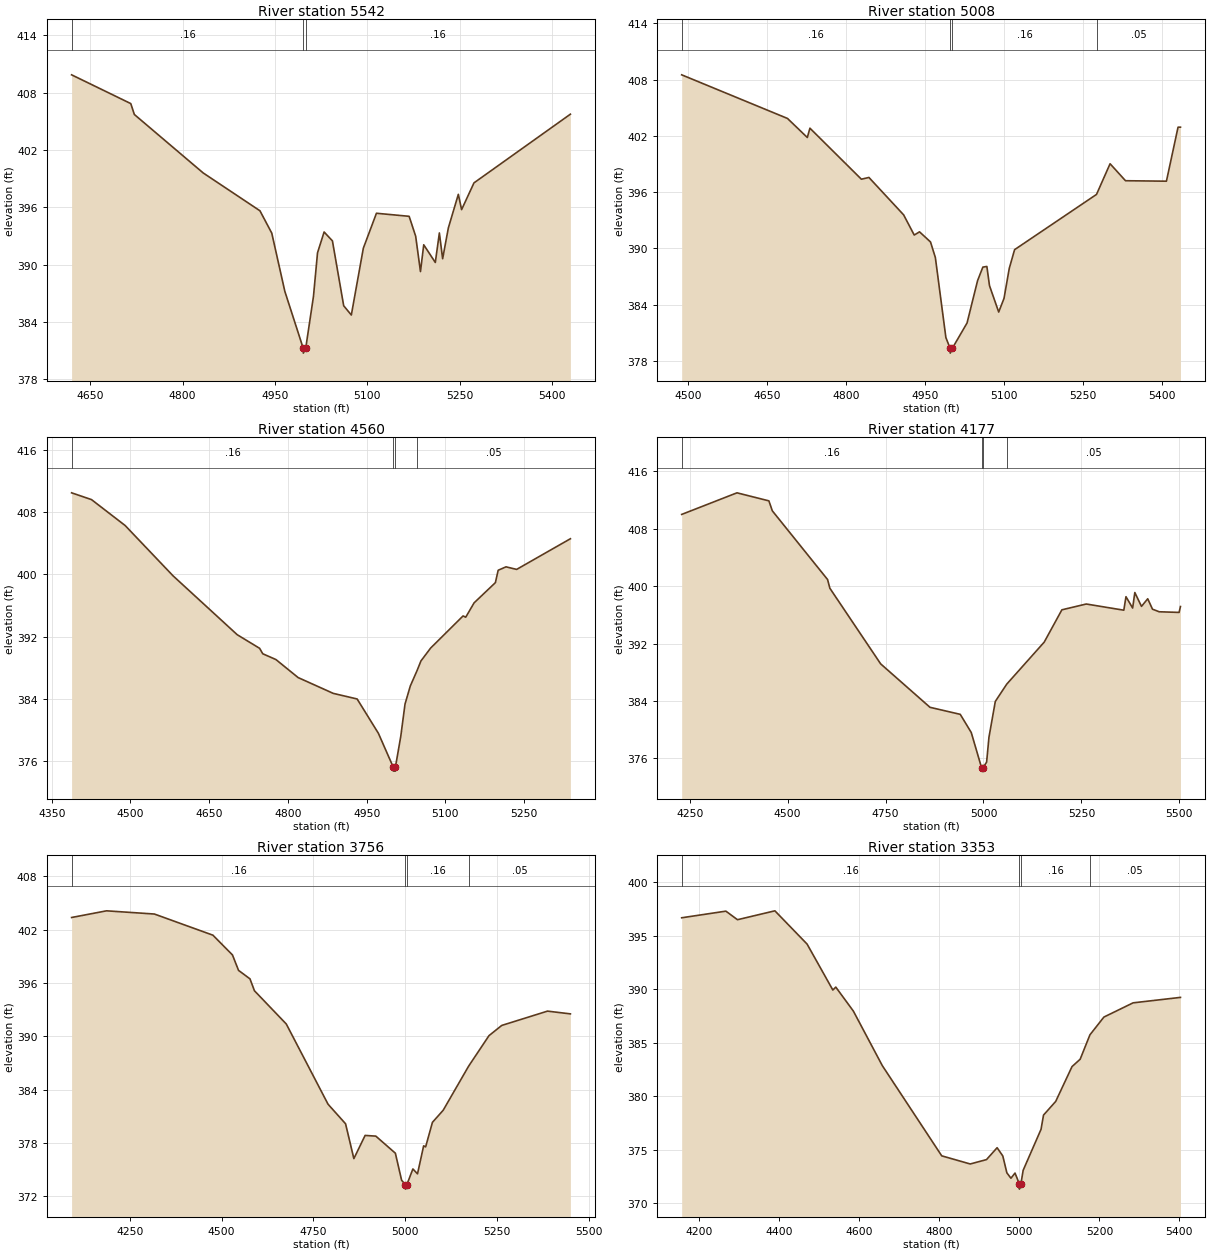
Type RM Length L Ch R = 1,5542,534,534,534
BEGIN DESCRIPTION:
NORTH MINERAL CR TRIB 5 28 0
END DESCRIPTION:
XS GIS Cut Line= 2
      3515098.04     10397474.32      3514335.61     10397748.11
#Sta/Elev= 30
  4619.8  409.88  4715.9  406.87  4721.7  405.73  4833.5  399.61  4925.7  395.65
  4944.9  393.31  4966.1  387.22  4996.0  381.25  4996.2  380.75  5000.0  381.25
  5012.6  386.68  5019.2  391.25  5029.9  393.43  5043.4  392.50  5061.7  385.71
  5074.1  384.74  5093.6  391.73  5114.9  395.39  5168.0  395.07  5178.6  392.99
  5186.4  389.29  5191.7  392.09  5210.5  390.24  5217.1  393.33  5222.4  390.63
  5231.7  393.86  5247.9  397.37  5253.2  395.77  5273.3  398.57  5429.9  405.76
#Mann=3,-1,0
  4619.8    0.16       0  4996.0    0.07       0  5000.0    0.16       0
Bank Sta=4996,5000
Exp/Cntr=0.3,0.1

Type RM Length L Ch R = 1,5008,448,448,448
BEGIN DESCRIPTION:
NORTH MINERAL CR TRIB 5 18 0
END DESCRIPTION:
XS GIS Cut Line= 2
      3515112.41     10397187.85      3514167.98     10397104.52
#Sta/Elev= 30
  4487.8  408.50  4688.9  403.85  4726.6  401.82  4731.6  402.81  4829.4  397.37
  4843.7  397.56  4909.7  393.57  4929.8  391.42  4939.9  391.76  4960.8  390.68
  4970.0  389.02  4990.0  380.49  4998.1  379.33  4998.3  378.83  5002.1  379.33
  5030.2  382.04  5050.3  386.57  5060.3  388.00  5067.9  388.07  5072.9  386.02
  5090.4  383.21  5100.5  384.67  5110.5  387.87  5120.6  389.86  5276.3  395.75
  5302.1  399.02  5331.4  397.21  5409.2  397.16  5431.3  402.92  5435.9  402.92
#Mann=4,-1,0
  4487.8    0.16       0  4998.1    0.07       0  5002.1    0.16       0
  5276.3    0.05       0
Bank Sta=4998.1,5002.1
Exp/Cntr=0.3,0.1

Type RM Length L Ch R = 1,4560,383,383,383
BEGIN DESCRIPTION:
NORTH MINERAL CR TRIB 5 8 0
END DESCRIPTION:
XS GIS Cut Line= 3
      3515087.62     10396894.45      3514688.33     10396745.15
      3514170.99     10396828.48
#Sta/Elev= 30
  4387.8  410.49  4425.7  409.62  4489.8  406.29  4581.0  399.83  4703.3  392.26
  4746.0  390.51  4752.0  389.81  4777.0  389.07  4819.4  386.75  4886.3  384.72
  4931.8  384.00  4972.3  379.59  5000.7  375.23  5001.0  374.73  5004.5  374.73
  5004.7  375.23  5015.0  379.23  5023.0  383.34  5033.1  385.67  5046.1  387.67
  5053.4  388.89  5071.8  390.54  5133.6  394.67  5138.7  394.51  5154.6  396.35
  5195.2  398.95  5200.5  400.54  5215.4  400.98  5235.7  400.65  5338.1  404.59
#Mann=4,-1,0
  4387.8    0.16       0  5000.7    0.07       0  5004.7    0.16       0
  5046.1    0.05       0
Bank Sta=5000.7,5004.7
Exp/Cntr=0.3,0.1

Type RM Length L Ch R = 1,4177,421,421,421
BEGIN DESCRIPTION:
NORTH MINERAL CR TRIB 5 7 0
END DESCRIPTION:
XS GIS Cut Line= 2
      3515312.45     10396779.00      3514166.89     10396223.58
#Sta/Elev= 30
  4229.7  409.99  4370.8  413.00  4452.3  411.88  4461.1  410.49  4602.1  400.92
  4607.9  399.71  4737.6  389.17  4863.5  383.12  4940.7  382.14  4968.8  379.61
  4995.0  374.73  4995.2  374.23  4999.0  374.73  5008.0  375.48  5014.0  378.95
  5030.2  383.94  5059.4  386.35  5155.0  392.20  5200.1  396.70  5262.3  397.51
  5358.2  396.65  5363.7  398.53  5380.7  396.95  5386.3  399.11  5403.3  397.18
  5419.2  398.24  5431.4  396.79  5448.5  396.43  5499.2  396.34  5502.8  397.16
#Mann=4,-1,0
  4229.7    0.16       0  4995.0    0.07       0  4999.0    0.16       0
  5059.4    0.05       0
Bank Sta=4995,4999
Exp/Cntr=0.3,0.1

Type RM Length L Ch R = 1,3756,403,403,403
BEGIN DESCRIPTION:
NORTH MINERAL CR TRIB 5 6 0
END DESCRIPTION:
XS GIS Cut Line= 2
      3515611.98     10396414.44      3514357.61     10395893.59
#Sta/Elev= 30
  4091.7  403.36  4186.9  404.11  4317.1  403.75  4476.5  401.37  4529.7  399.15
  4546.3  397.41  4577.4  396.46  4589.6  395.12  4676.3  391.38  4790.0  382.36
  4837.7  380.16  4860.3  376.24  4890.9  378.85  4920.1  378.77  4973.3  376.85
  4990.3  373.81  5000.6  373.31  5000.8  372.81  5004.6  373.31  5021.0  375.08
  5033.6  374.53  5050.3  377.68  5055.7  377.56  5074.2  380.32  5103.5  381.68
  5172.8  386.64  5228.2  390.07  5262.9  391.22  5387.6  392.83  5449.9  392.52
#Mann=4,-1,0
  4091.7    0.16       0  5000.6    0.07       0  5004.6    0.16       0
  5172.8    0.05       0
Bank Sta=5000.6,5004.6
Exp/Cntr=0.3,0.1

Type RM Length L Ch R = 1,3353,599,599,599
BEGIN DESCRIPTION:
NORTH MINERAL CR TRIB 5 3 1
END DESCRIPTION:
XS GIS Cut Line= 3
      3515594.58     10396032.47      3515156.22     10395746.02
      3514445.76     10395611.72
#Sta/Elev= 30
  4155.9  396.69  4266.4  397.31  4295.4  396.51  4388.9  397.34  4469.4  394.23
  4533.7  389.94  4541.1  390.21  4585.0  387.97  4657.4  382.87  4805.9  374.44
  4877.1  373.68  4917.8  374.09  4944.3  375.20  4958.5  374.43  4968.7  372.85
  4978.9  372.35  4989.1  372.83  4999.8  371.83  5000.0  371.33  5003.8  371.83
  5009.4  373.09  5054.1  376.92  5060.3  378.25  5090.8  379.53  5131.5  382.78
  5151.9  383.47  5176.3  385.75  5211.2  387.41  5284.2  388.74  5402.6  389.25
#Mann=4,-1,0
  4155.9    0.16       0  4999.8    0.07       0  5003.8    0.16       0
  5176.3    0.05       0
Bank Sta=4999.8,5003.8
Exp/Cntr=0.3,0.1

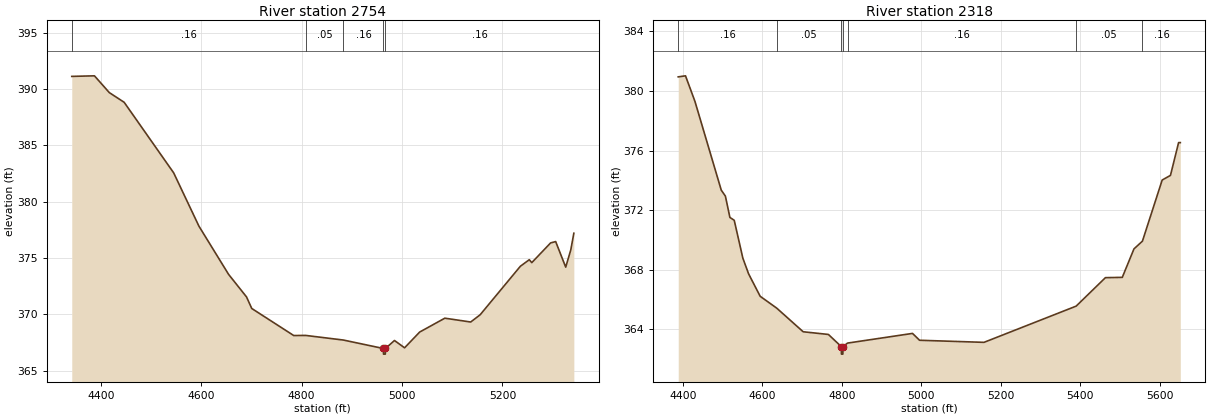
Type RM Length L Ch R = 1,2754,436,436,436
BEGIN DESCRIPTION:
NORTH MINERAL CR TRIB 5 3 0
END DESCRIPTION:
XS GIS Cut Line= 3
      3515637.97     10395489.93      3515342.85     10395281.61
      3514706.00     10395229.62
#Sta/Elev= 30
  4342.1  391.12  4387.3  391.17  4416.9  389.68  4446.5  388.82  4545.1  382.56
  4595.4  377.83  4654.5  373.55  4690.2  371.55  4700.7  370.52  4784.3  368.12
  4808.0  368.13  4883.2  367.72  4962.9  366.97  4963.2  366.47  4966.7  366.47
  4966.9  366.97  4985.0  367.68  5005.1  367.03  5035.2  368.43  5085.3  369.66
  5136.8  369.32  5155.6  369.96  5235.8  374.27  5253.5  374.85  5258.5  374.59
  5296.0  376.34  5306.1  376.46  5326.1  374.19  5336.2  375.72  5342.3  377.20
#Mann=5,-1,0
  4342.1    0.16       0  4808.0    0.05       0  4883.2    0.16       0
  4962.9    0.07       0  4966.9    0.16       0
Bank Sta=4962.9,4966.9
Exp/Cntr=0.3,0.1

Type RM Length L Ch R = 1,2318,0,0,0
BEGIN DESCRIPTION:
NORTH MINERAL CR TRIB 5 5 0
END DESCRIPTION:
XS GIS Cut Line= 3
      3515681.96     10395114.58      3514971.91     10394815.98
      3514680.22     10395213.58
#Sta/Elev= 30
  4388.4  380.94  4406.7  381.01  4430.4  379.30  4496.7  373.34  4507.1  372.94
  4518.4  371.51  4529.3  371.32  4551.0  368.78  4565.4  367.73  4594.6  366.22
  4636.0  365.43  4702.8  363.84  4766.3  363.66  4798.9  362.84  4799.1  362.34
  4802.6  362.34  4802.9  362.84  4814.4  363.08  4977.9  363.73  4995.7  363.27
  5157.8  363.13  5389.7  365.56  5463.4  367.47  5505.8  367.49  5535.2  369.40
  5556.5  369.92  5606.2  374.02  5627.0  374.33  5647.5  376.53  5651.8  376.53
#Mann=7,-1,0
  4388.4    0.16       0  4636.0    0.05       0  4798.9    0.07       0
  4802.9    0.05       0  4814.4    0.16       0  5389.7    0.05       0
  5556.5    0.16       0
Bank Sta=4798.9,4802.9
Exp/Cntr=0.3,0.1

Chan Stop Cuts=-1