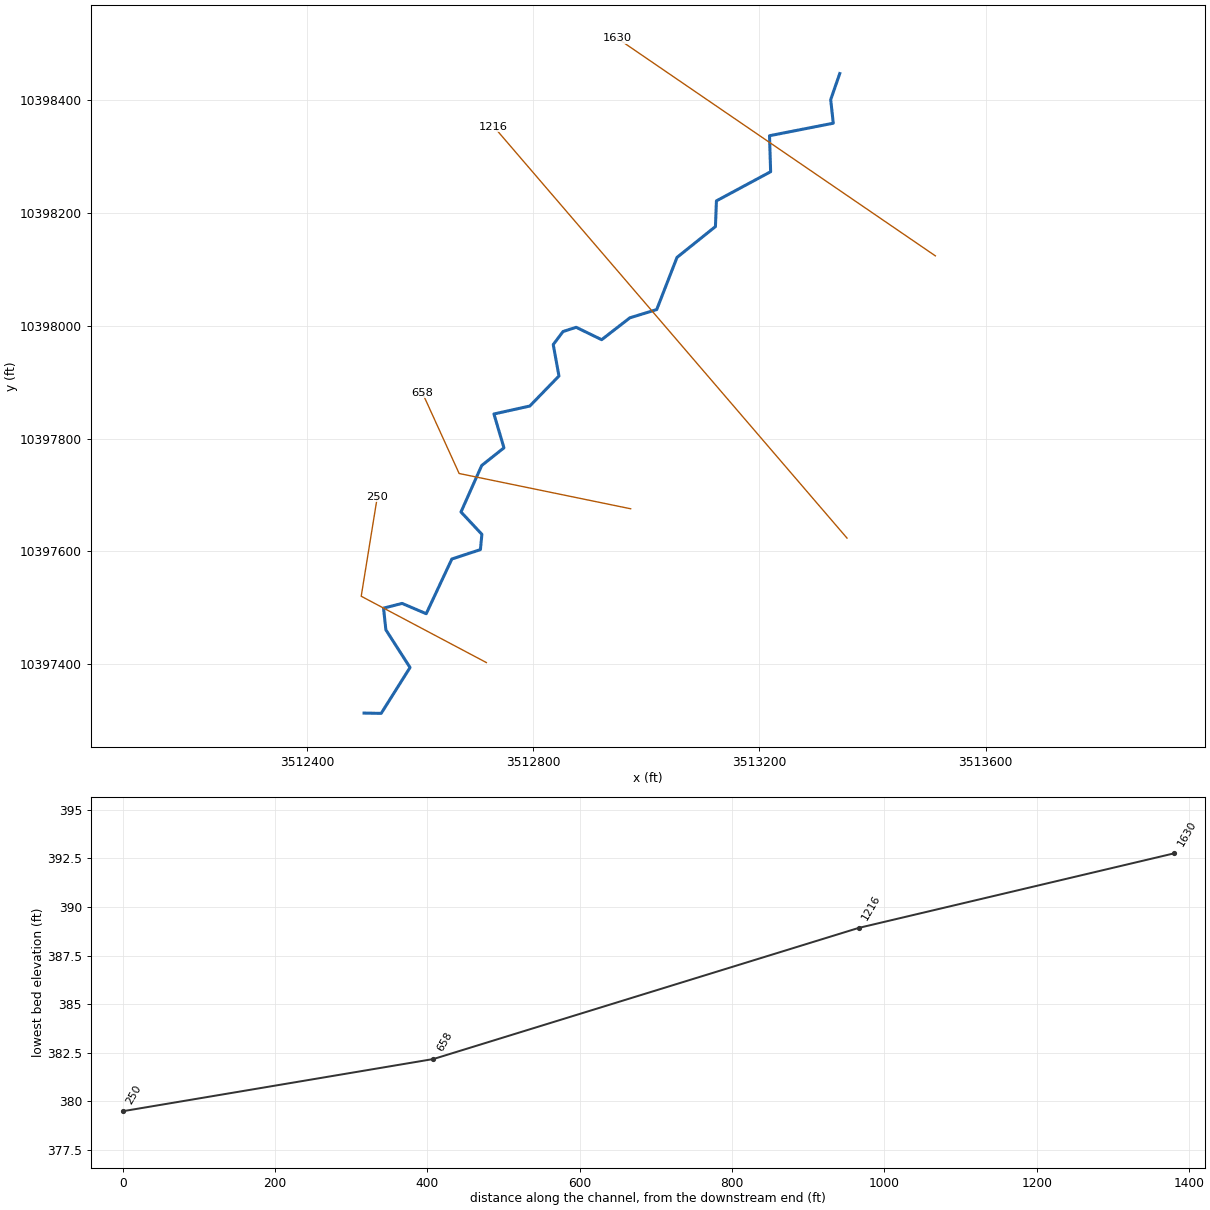
--- NORTH MINERAL CR TRIB 6 1.prj (project) ---

Proj Title=NORTH MINERAL CR TRIB 6 1 Base Level Engineering
Current Plan=p01
Default Exp/Contr=0.3,0.1
English Units
Geom File=g01
Flow File=f01
Plan File=p01
Y Axis Title=Elevation
X Axis Title(PF)=Main Channel Distance
X Axis Title(XS)=Station
BEGIN DESCRIPTION:
NORTH MINERAL CR TRIB 6 1
END DESCRIPTION:
DSS Export Rating Curves= 0
DSS Export Rating Curve Sorted= 0
DSS Export Volume Flow Curves= 0
DXF OffsetX= 0
DXF OffsetY= 0
DXF ScaleX= 1
DXF ScaleY= 10

--- NORTH MINERAL CR TRIB 6 1.p01 (plan) ---

Plan Title=Multiple Run
Short Identifier=Multiple
Geom File=g01
Flow File=f01
Subcritical Flow
K Sum by GR= 0
Std Step Tol= 0.01
Critical Tol= 0.01
Num of Std Step Trials= 20
Max Error Tol= 0.3
Flow Tol Ratio= 0.001
Split Flow NTrial= 30
Split Flow Tol= 0.02
Split Flow Ratio= 0.02
Log Output Level= 0
Friction Slope Method= 1
Unsteady Friction Slope Method= 2
Unsteady Bridges Friction Slope Method= 1
Parabolic Critical Depth
Global Vel Dist=  1 , 1 , 1
Global Log Level= 0
CheckData=True
Encroach Param= -1, 0, 0, 0
BEGIN DESCRIPTION:
Multiple Run
END DESCRIPTION:

--- NORTH MINERAL CR TRIB 6 1.f01 (steady flow) ---

Flow Title=Multiple
Program Version=4.10
Number of Profiles= 7
Profile Names=10-year,25-year,50-year,1pct_min,100-year,1pct_plu,500-year
River Rch & RM=NORTH MINERAL CR,Reach-1         ,1630
     303     391     460     397     537     726     726
Boundary for River Rch & Prof#=NORTH MINERAL CR,Reach-1         , 1
Up Type= 0
Dn Type= 3
Dn Slope=0.0103
Boundary for River Rch & Prof#=NORTH MINERAL CR,Reach-1         , 2
Up Type= 0
Dn Type= 3
Dn Slope=0.0103
Boundary for River Rch & Prof#=NORTH MINERAL CR,Reach-1         , 3
Up Type= 0
Dn Type= 3
Dn Slope=0.0103
Boundary for River Rch & Prof#=NORTH MINERAL CR,Reach-1         , 4
Up Type= 0
Dn Type= 3
Dn Slope=0.0103
Boundary for River Rch & Prof#=NORTH MINERAL CR,Reach-1         , 5
Up Type= 0
Dn Type= 3
Dn Slope=0.0103
Boundary for River Rch & Prof#=NORTH MINERAL CR,Reach-1         , 6
Up Type= 0
Dn Type= 3
Dn Slope=0.0103
Boundary for River Rch & Prof#=NORTH MINERAL CR,Reach-1         , 7
Up Type= 0
Dn Type= 3
Dn Slope=0.0103
DSS Import GetInterval= 0
DSS Import GetPeak= 0
DSS Import FillOption= 0

--- NORTH MINERAL CR TRIB 6 1.g01 (geometry) ---

Geom Title=Existing Conditions
Program Version=4.10

River Reach=NORTH MINERAL CR,Reach-1
Reach XY= 30
      3513342.11     10398446.64       3513326.1     10398400.32
      3513330.67     10398358.66      3513217.91     10398336.49
      3513219.86     10398272.69      3513124.02     10398221.09
      3513122.23     10398175.56      3513054.25      10398120.9
      3513018.38     10398028.52      3512970.89     10398013.91
      3512921.02     10397975.15      3512875.93     10397997.13
      3512852.71     10397989.62      3512835.36      10397966.5
      3512845.49     10397910.83      3512793.94     10397857.65
      3512730.49     10397843.55      3512748.21      10397783.6
       3512708.9     10397752.32      3512672.19     10397669.95
      3512709.17     10397630.37      3512706.57     10397603.28
      3512656.05     10397586.62      3512610.74     10397489.74
      3512568.03     10397507.97      3512535.22     10397499.64
      3512539.38      10397461.1      3512582.09     10397394.43
      3512531.05     10397313.18      3512500.84      10397313.7

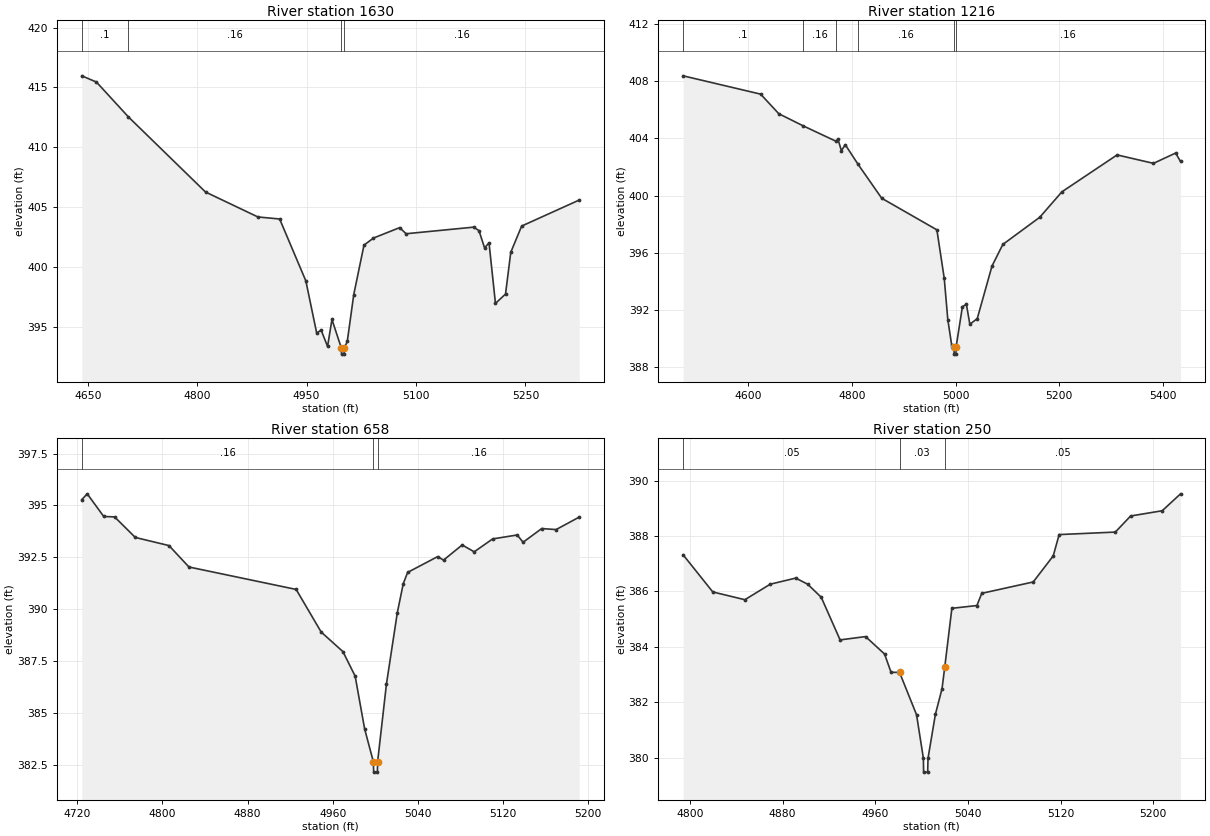
Type RM Length L Ch R = 1 ,1630    ,414,414,414
BEGIN DESCRIPTION:
NORTH MINERAL CR TRIB 6 10 1
END DESCRIPTION:
XS GIS Cut Line= 2
      3513511.23     10398123.64      3512948.79     10398509.01
#Sta/Elev= 30
  4641.9  415.97    4662  415.45  4705.7  412.55  4811.5  406.28  4883.3   404.2
  4913.1  404.03    4949  398.87  4963.9  394.51  4969.9  394.77  4978.8   393.4
  4984.8  395.65  4997.7  393.26    4998  392.76  5001.5  392.76  5001.7  393.26
  5005.8  393.82  5014.7  397.73  5028.7  401.85  5041.7  402.44  5077.6  403.31
  5086.4   402.8  5179.1  403.35  5186.3  403.06    5194  401.62  5200.1  402.04
  5208.9  396.99  5222.7  397.77  5229.9  401.25  5244.8  403.44  5323.7  405.61
#Mann= 4 ,-1 , 0
  4641.9      .1       0  4705.7     .16       0  4997.7     .07       0
  5001.7     .16       0
Bank Sta=4997.7,5001.7
XS Rating Curve= 0 ,0
Exp/Cntr=0.3,0.1

Type RM Length L Ch R = 1 ,1216    ,558,558,558
BEGIN DESCRIPTION:
NORTH MINERAL CR TRIB 6 10 0
END DESCRIPTION:
XS GIS Cut Line= 2
      3513354.98     10397623.65      3512730.03     10398352.76
#Sta/Elev= 30
  4473.8  408.38  4623.4   407.1  4658.5  405.73  4705.7  404.88  4768.7  403.81
  4772.7  403.95  4779.3  403.15  4786.9  403.56  4811.4   402.2  4857.2  399.82
  4963.7  397.61  4977.9  394.22  4984.8  391.33  4992.2  389.57  4996.8  389.42
    4997  388.92  5000.5  388.92  5000.8  389.42    5013  392.24  5020.7   392.4
  5027.3  391.01  5041.6   391.4  5070.1  395.08    5091  396.59  5162.3  398.49
  5205.1  400.27  5311.6  402.85  5381.8  402.26  5424.6  402.98  5434.1  402.39
#Mann= 6 ,-1 , 0
  4473.8      .1       0  4705.7     .16       0  4768.7      .1       0
  4811.4     .16       0  4996.8     .07       0  5000.8     .16       0
Bank Sta=4996.8,5000.8
XS Rating Curve= 0 ,0
Exp/Cntr=0.3,0.1

Type RM Length L Ch R = 1 ,658     ,408,408,408
BEGIN DESCRIPTION:
NORTH MINERAL CR TRIB 6 1 2 0
END DESCRIPTION:
XS GIS Cut Line= 3
      3512972.28     10397675.63      3512668.93     10397738.13
       3512603.8      10397881.4
#Sta/Elev= 30
  4724.3  395.28  4729.4  395.56  4744.9  394.47  4755.1  394.45  4774.6  393.46
  4806.2  393.07  4824.9  392.04  4925.6  390.96  4949.1  388.91  4969.5  387.97
    4981  386.79  4989.9  384.25  4998.1  382.67  4998.4  382.17  5001.9  382.17
  5002.1  382.67  5010.4  386.41  5020.6  389.84  5026.2  391.24  5030.3  391.78
  5058.5  392.54    5064  392.37  5081.5   393.1  5092.8  392.77  5110.1  393.39
  5133.2  393.58  5138.7  393.23  5156.2  393.89  5169.7  393.84  5191.4  394.44
#Mann= 3 ,-1 , 0
  4724.3     .16       0  4998.1     .07       0  5002.1     .16       0
Bank Sta=4998.1,5002.1
XS Rating Curve= 0 ,0
Exp/Cntr=0.3,0.1

Type RM Length L Ch R = 1 ,250     ,0,0,0
BEGIN DESCRIPTION:
NORTH MINERAL CR TRIB 6 1 1 0
END DESCRIPTION:
XS GIS Cut Line= 3
      3512717.07     10397403.23      3512495.75     10397520.68
      3512524.31     10397697.23
#Sta/Elev= 30
  4794.2  387.32  4819.8  385.98  4847.5   385.7  4869.4  386.26  4891.4  386.48
  4901.7  386.26  4913.4  385.79  4929.7  384.25  4951.7  384.37  4968.1  383.74
  4973.7  383.08    4981  383.08  4995.7  381.55  5001.6  379.98  5001.8  379.48
  5005.3  379.48  5005.6  379.98    5012  381.57  5017.7  382.49 5020.11  383.29
  5026.2  385.39  5047.8  385.49    5052  385.93  5096.4  386.34  5113.7  387.28
  5118.8  388.05  5167.3  388.14  5180.5  388.72  5207.8  388.91  5223.6  389.52
#Mann= 3 , 0 , 0
  4794.2     .05       0    4981     .03       0 5020.11     .05       0
Bank Sta=4981,5020.11
XS Rating Curve= 0 ,0
Exp/Cntr=0.3,0.1

Chan Stop Cuts=-1
Use User Specified Reach Order=0
Composite Channel Slope=5