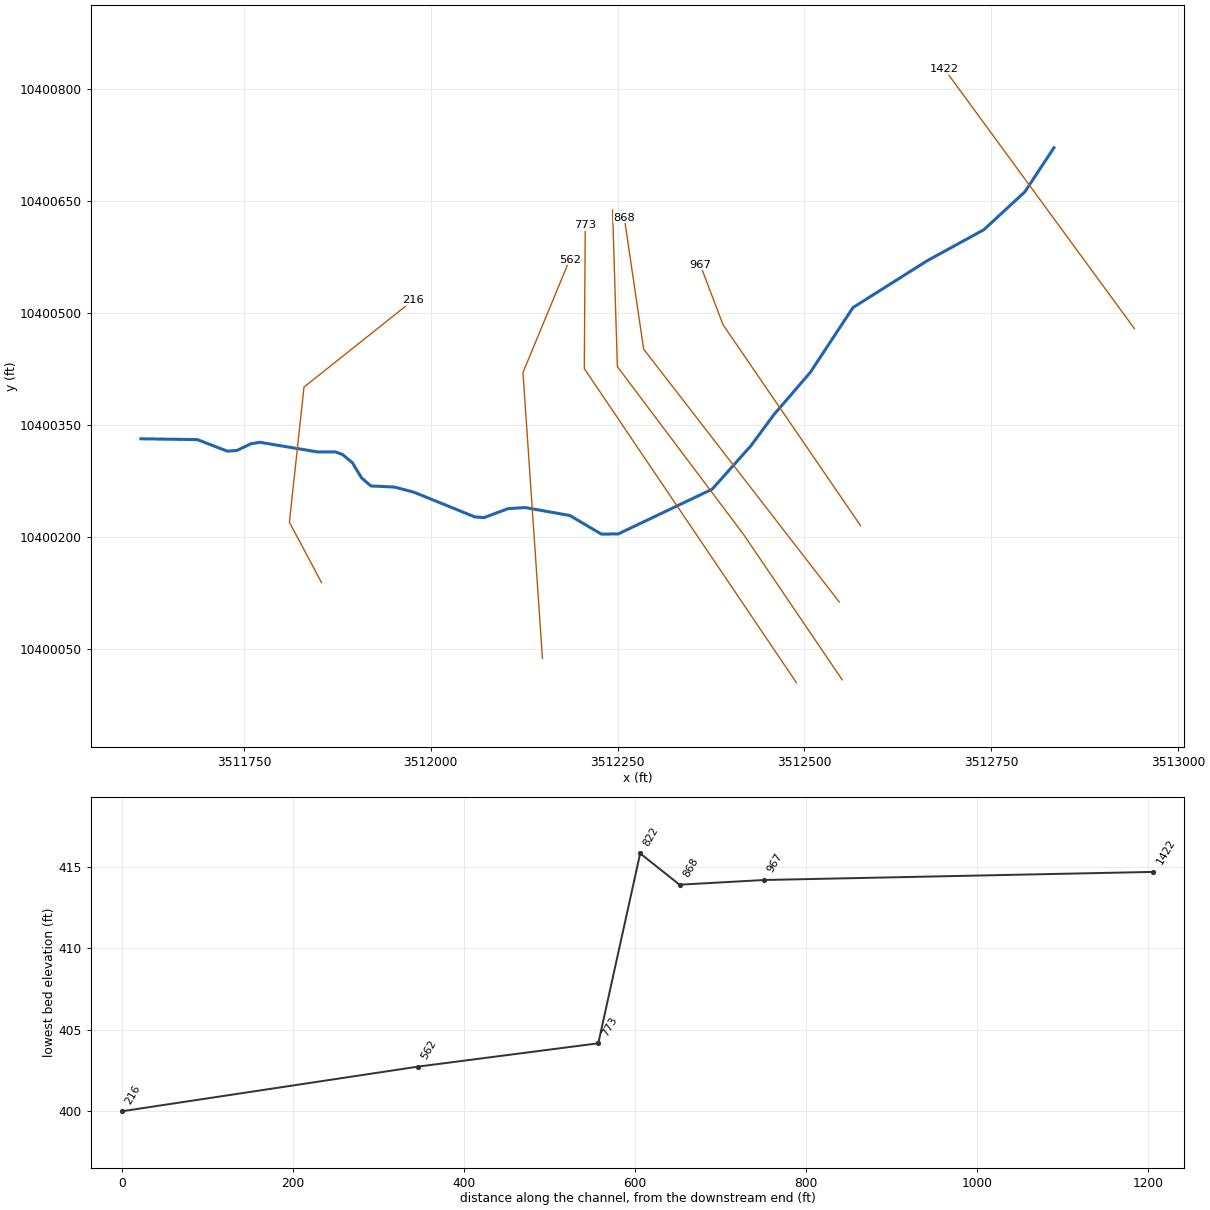
--- NORTH MINERAL CR TRIB 6 2.prj (project) ---

Proj Title=NORTH MINERAL CR TRIB 6 2 Base Level Engineering
Current Plan=p01
Default Exp/Contr=0.3,0.1
English Units
Geom File=g01
Flow File=f01
Plan File=p01
Y Axis Title=Elevation
X Axis Title(PF)=Main Channel Distance
X Axis Title(XS)=Station
BEGIN DESCRIPTION:
NORTH MINERAL CR TRIB 6 2
END DESCRIPTION:
DSS Export Rating Curves= 0
DSS Export Rating Curve Sorted= 0
DSS Export Volume Flow Curves= 0
DXF OffsetX= 0
DXF OffsetY= 0
DXF ScaleX= 1
DXF ScaleY= 10

--- NORTH MINERAL CR TRIB 6 2.p01 (plan) ---

Plan Title=Multiple Run
Short Identifier=Multiple
Geom File=g01
Flow File=f01
Subcritical Flow
K Sum by GR= 0
Std Step Tol= 0.01
Critical Tol= 0.01
Num of Std Step Trials= 20
Max Error Tol= 0.3
Flow Tol Ratio= 0.001
Split Flow NTrial= 30
Split Flow Tol= 0.02
Split Flow Ratio= 0.02
Log Output Level= 0
Friction Slope Method= 1
Unsteady Friction Slope Method= 2
Unsteady Bridges Friction Slope Method= 1
Parabolic Critical Depth
Global Vel Dist=  1 , 1 , 1
Global Log Level= 0
CheckData=True
Encroach Param= -1, 0, 0, 0
BEGIN DESCRIPTION:
Multiple Run
END DESCRIPTION:

--- NORTH MINERAL CR TRIB 6 2.f01 (steady flow) ---

Flow Title=Multiple
Program Version=4.10
Number of Profiles= 7
Profile Names=10-year,25-year,50-year,1pct_min,100-year,1pct_plu,500-year
River Rch & RM=NORTH MINERAL CR,Reach-1         ,1422
     367     481     570     497     672     909     927
Boundary for River Rch & Prof#=NORTH MINERAL CR,Reach-1         , 1
Up Type= 0
Dn Type= 3
Dn Slope=0.0078
Boundary for River Rch & Prof#=NORTH MINERAL CR,Reach-1         , 2
Up Type= 0
Dn Type= 3
Dn Slope=0.0078
Boundary for River Rch & Prof#=NORTH MINERAL CR,Reach-1         , 3
Up Type= 0
Dn Type= 3
Dn Slope=0.0078
Boundary for River Rch & Prof#=NORTH MINERAL CR,Reach-1         , 4
Up Type= 0
Dn Type= 3
Dn Slope=0.0078
Boundary for River Rch & Prof#=NORTH MINERAL CR,Reach-1         , 5
Up Type= 0
Dn Type= 3
Dn Slope=0.0078
Boundary for River Rch & Prof#=NORTH MINERAL CR,Reach-1         , 6
Up Type= 0
Dn Type= 3
Dn Slope=0.0078
Boundary for River Rch & Prof#=NORTH MINERAL CR,Reach-1         , 7
Up Type= 0
Dn Type= 3
Dn Slope=0.0078
DSS Import GetInterval= 0
DSS Import GetPeak= 0
DSS Import FillOption= 0

--- NORTH MINERAL CR TRIB 6 2.g01 (geometry) ---

Geom Title=Existing Conditions
Program Version=4.10

River Reach=NORTH MINERAL CR,Reach-1
Reach XY= 30
      3512833.74     10400721.36      3512794.61     10400662.06
      3512739.92     10400611.54      3512663.88     10400569.87
      3512564.92     10400507.37      3512507.63     10400420.39
      3512459.19     10400364.14      3512428.47     10400322.47
      3512376.38     10400264.14      3512251.01     10400204.34
      3512228.25     10400204.01      3512186.04     10400228.93
      3512126.32     10400239.58      3512103.37     10400238.09
      3512071.24     10400226.15      3512059.01     10400227.02
      3511977.41     10400260.17      3511951.21     10400267.02
      3511919.77     10400268.54      3511907.32     10400279.38
      3511895.13     10400299.56      3511882.11     10400310.49
      3511872.21     10400314.14      3511848.15     10400314.08
      3511771.45     10400326.98      3511759.34     10400324.99
      3511740.69     10400316.07      3511727.84     10400315.07
      3511687.68     10400330.57      3511612.11     10400331.64

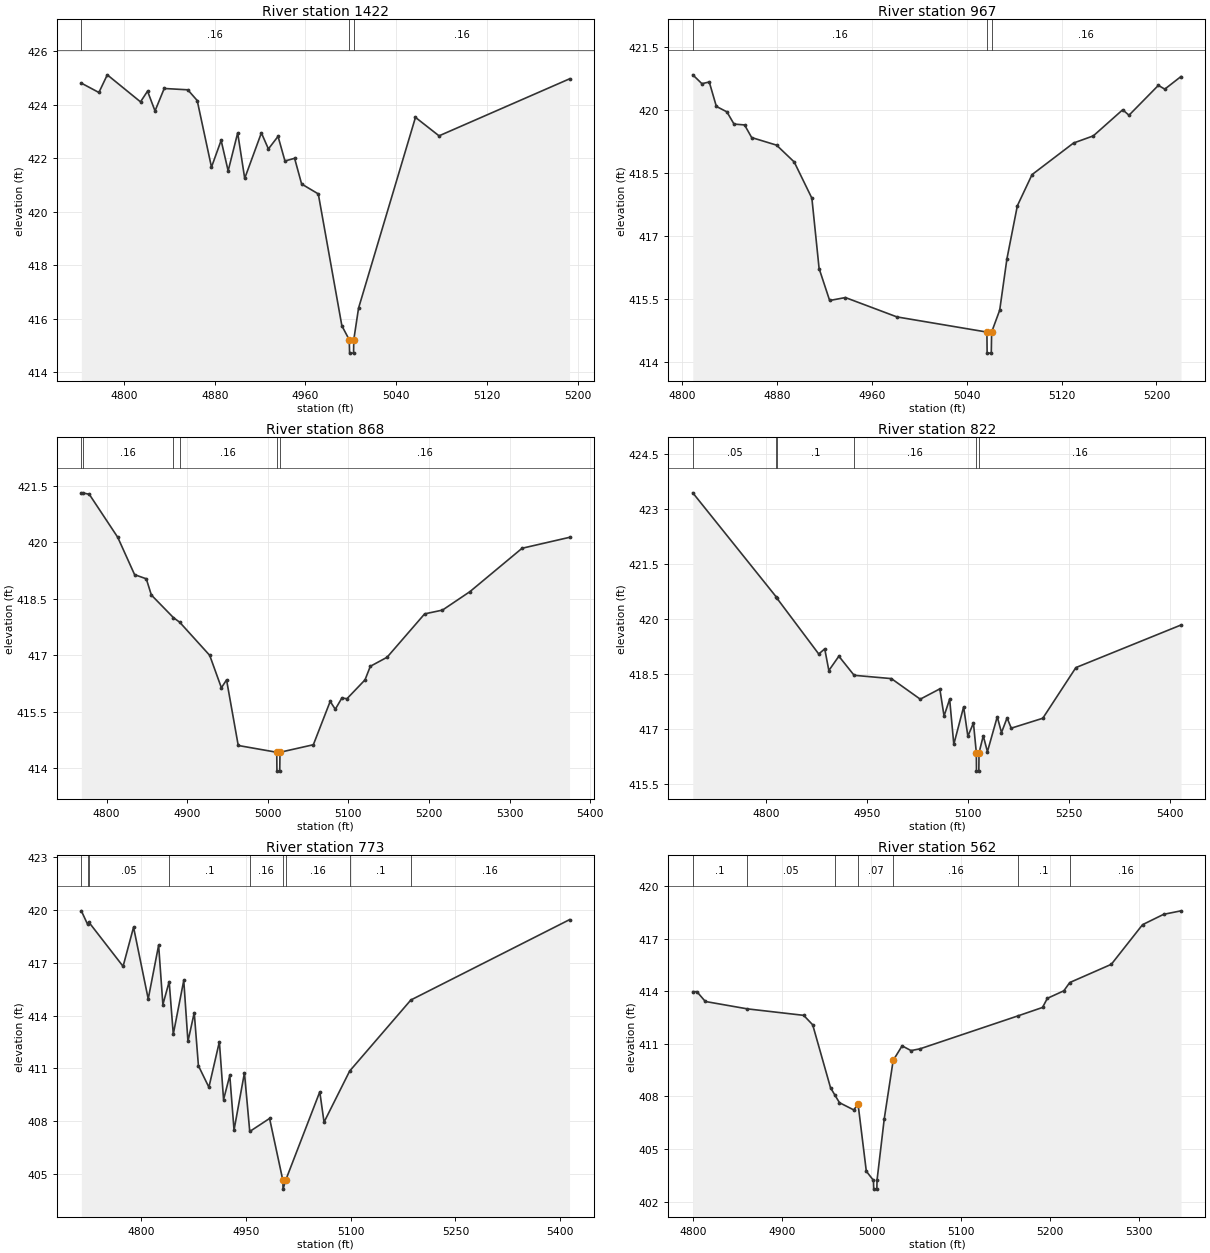
Type RM Length L Ch R = 1 ,1422    ,455,455,455
BEGIN DESCRIPTION:
NORTH MINERAL CR TRIB 6 2 6 0
END DESCRIPTION:
XS GIS Cut Line= 2
      3512941.35     10400479.17      3512687.16     10400826.74
#Sta/Elev= 30
  4762.3  424.81  4777.8  424.46  4785.2  425.12  4814.5  424.11  4820.7  424.51
  4827.3  423.77  4835.4  424.61  4856.2  424.56  4864.5  424.16  4877.1  421.67
  4885.6  422.67  4891.8  421.53  4900.2  422.95  4906.4  421.25  4921.1  422.95
  4927.3  422.35  4935.8  422.82  4941.9   421.9  4950.4     422  4956.6  421.04
  4971.3  420.67  4992.1  415.74  4998.6  415.22  4998.9  414.72  5002.4  414.72
  5002.6  415.22  5006.8   416.4    5057  423.53  5077.8  422.84  5192.9  424.97
#Mann= 3 ,-1 , 0
  4762.3     .16       0  4998.6     .07       0  5002.6     .16       0
Bank Sta=4998.6,5002.6
XS Rating Curve= 0 ,0
Exp/Cntr=0.3,0.1

Type RM Length L Ch R = 1 ,967     ,99,99,99
BEGIN DESCRIPTION:
NORTH MINERAL CR TRIB 6 2 3 0
END DESCRIPTION:
XS GIS Cut Line= 3
        3512575.     10400215.32        3512391.     10400484.38
      3512360.44     10400564.81
#Sta/Elev= 30
  4808.7  420.83  4816.4  420.62  4822.6  420.66  4828.6  420.08  4837.5  419.95
  4843.5  419.66  4852.4  419.64  4858.4  419.34  4879.4  419.16  4894.3  418.76
  4909.2   417.9  4915.3  416.23  4924.2  415.47  4937.5  415.54    4981  415.08
  5056.9  414.72  5057.1  414.22  5060.6  414.22  5060.9  414.72  5067.7  415.24
  5073.8  416.46  5082.6  417.72    5095  418.46    5130  419.21  5146.7  419.38
  5171.5     420  5176.8  419.87  5201.6  420.58    5207  420.49  5220.7  420.79
#Mann= 3 ,-1 , 0
  4808.7     .16       0  5056.9     .07       0  5060.9     .16       0
Bank Sta=5056.9,5060.9
XS Rating Curve= 0 ,0
Exp/Cntr=0.3,0.1

Type RM Length L Ch R = 1 ,868     ,46,46,46
BEGIN DESCRIPTION:
NORTH MINERAL CR TRIB 6 2 5 0
END DESCRIPTION:
XS GIS Cut Line= 3
      3512546.53     10400113.13      3512284.81     10400451.67
      3512258.93     10400627.66
#Sta/Elev= 30
  4768.6  421.31  4770.2  421.31  4778.5  421.27  4813.8  420.13  4834.7  419.14
  4849.2  419.03  4855.5   418.6  4882.9     418  4890.6  417.88  4927.9     417
  4942.4  416.14  4948.8  416.35  4963.3  414.61  5011.1  414.43  5011.3  413.93
  5014.8  413.93  5015.1  414.43  5056.5  414.63  5077.4  415.78  5083.7  415.57
  5091.9  415.87  5098.2  415.85  5120.6  416.35  5127.2  416.71    5148  416.95
  5194.6   418.1  5216.7   418.2  5250.8  418.69  5315.5  419.84  5374.4  420.13
#Mann= 6 ,-1 , 0
  4768.6     .05       0  4770.2     .16       0  4882.9      .1       0
  4890.6     .16       0  5011.1     .07       0  5015.1     .16       0
Bank Sta=5011.1,5015.1
XS Rating Curve= 0 ,0
Exp/Cntr=0.3,0.1

Type RM Length L Ch R = 1 ,822     ,49,49,49
BEGIN DESCRIPTION:
Mapping XS b3fe2a91
END DESCRIPTION:
XS GIS Cut Line= 4
      3512550.43     10400008.97      3512418.93     10400202.97
      3512249.66     10400428.23      3512243.19     10400637.89
#Sta/Elev= 30
  4690.6  423.44  4814.9   420.6  4815.7  420.57  4877.9  419.05  4886.8  419.19
  4892.9   418.6  4907.8  418.99  4930.5  418.47  4985.9  418.38  5028.8  417.82
  5057.9   418.1  5064.2  417.36  5072.5  417.82  5078.7  416.59  5093.3  417.61
  5099.6  416.81  5107.9  417.17  5112.2  416.36  5112.4  415.86  5115.9  415.86
  5116.2  416.36  5122.5  416.82  5128.7  416.39  5143.3  417.34  5149.6  416.91
  5157.9  417.31  5164.1  417.03    5211   417.3  5260.2  418.68  5416.5  419.84
#Mann= 6 ,-1 , 0
  4690.6     .05       0  4814.9     .16       0  4815.7      .1       0
  4930.5     .16       0  5112.2     .07       0  5116.2     .16       0
Bank Sta=5112.2,5116.2
XS Rating Curve= 0 ,0
Exp/Cntr=0.3,0.1

Type RM Length L Ch R = 1 ,773     ,211,211,211
BEGIN DESCRIPTION:
NORTH MINERAL CR TRIB 6 2 4 0
END DESCRIPTION:
XS GIS Cut Line= 3
      3512489.22     10400005.09      3512205.39     10400425.63
      3512206.68     10400617.46
#Sta/Elev= 30
  4714.2  419.94  4723.1  419.18  4724.7  419.31    4774  416.79    4789  419.01
    4810  414.94  4824.9  417.99    4831  414.62    4840  415.92  4845.9  412.94
  4860.9  415.99  4866.9  412.53  4875.9  414.16  4881.9  411.15  4896.9  409.93
  4911.9  412.51  4917.9  409.23  4926.8   410.6  4932.9   407.5  4947.8  410.75
  4955.4  407.42  4983.8  408.16  5002.8  404.65  5003.1  404.15  5006.8  404.65
  5055.7  409.67  5061.8  407.95  5098.5  410.85  5186.1  414.88  5413.4  419.44
#Mann= 9 ,-1 , 0
  4714.2     .05       0  4723.1      .1       0  4724.7     .05       0
    4840      .1       0  4955.4     .16       0  5002.8     .07       0
  5006.8     .16       0  5098.5      .1       0  5186.1     .16       0
Bank Sta=5002.8,5006.8
XS Rating Curve= 0 ,0
Exp/Cntr=0.3,0.1

Type RM Length L Ch R = 1 ,562     ,346,346,346
BEGIN DESCRIPTION:
Mapping XS 2335e301
END DESCRIPTION:
XS GIS Cut Line= 3
       3512149.4     10400037.58      3512123.36     10400420.42
      3512185.86     10400571.48
#Sta/Elev= 30
  4799.7  413.97  4804.3  413.97  4813.8  413.41  4860.8  412.99    4924  412.62
  4934.1  412.08  4954.1  408.49  4958.9  408.08  4964.1  407.64    4980  407.23
    4985  407.54  4994.2  403.73  5002.2  403.21  5002.5  402.71    5006  402.71
  5006.2  403.21  5014.3  406.72  5024.3  410.05  5034.3  410.88  5044.3  410.61
  5054.3  410.71  5164.2  412.59  5191.7  413.07  5197.1  413.59  5215.6  414.02
  5222.2  414.49  5268.8  415.53  5303.8  417.79  5327.4  418.38  5346.9  418.58
#Mann= 7 ,-1 , 0
  4799.7      .1       0  4860.8     .05       0  4958.9     .16       0
    4985     .07       0  5024.3     .16       0  5164.2      .1       0
  5222.2     .16       0
Bank Sta=4985,5024.3
XS Rating Curve= 0 ,0
Exp/Cntr=0.3,0.1

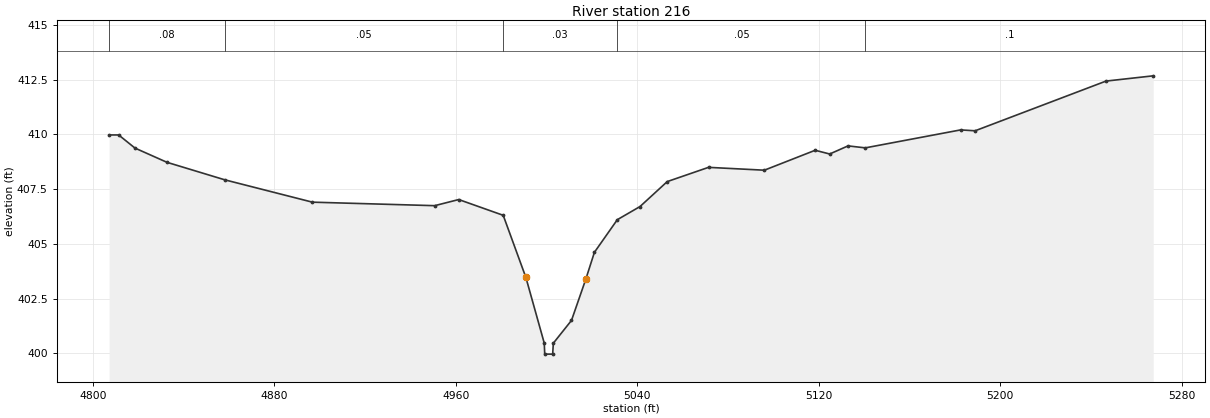
Type RM Length L Ch R = 1 ,216     ,0,0,0
BEGIN DESCRIPTION:
NORTH MINERAL CR TRIB 6 2 1 0
END DESCRIPTION:
XS GIS Cut Line= 4
      3511853.82     10400139.17      3511810.86      10400219.9
      3511830.39     10400400.89      3511976.43     10400517.21
#Sta/Elev= 30
  4807.2  409.97  4811.4  409.97  4818.6  409.37  4832.7  408.72  4858.2  407.92
  4896.8   406.9  4950.7  406.74  4961.3  407.02  4980.9   406.3  4990.9  403.46
    4999  400.46  4999.2  399.96  5002.7  399.96    5003  400.46    5011   401.5
 5017.33  403.39  5021.1  404.61  5031.2   406.1  5041.2   406.7  5053.2  407.84
  5071.4  408.49    5096  408.36  5118.4  409.27  5124.8   409.1  5132.9  409.47
  5140.5  409.38  5182.5   410.2  5188.9  410.16  5246.6  412.43  5267.4  412.67
#Mann= 5 ,-1 , 0
  4807.2     .08       0  4858.2     .05       0  4980.9     .03       0
  5031.2     .05       0  5140.5      .1       0
Bank Sta=4990.9,5017.33
XS Rating Curve= 0 ,0
Exp/Cntr=0.3,0.1

Chan Stop Cuts=-1
Use User Specified Reach Order=0
Composite Channel Slope=5