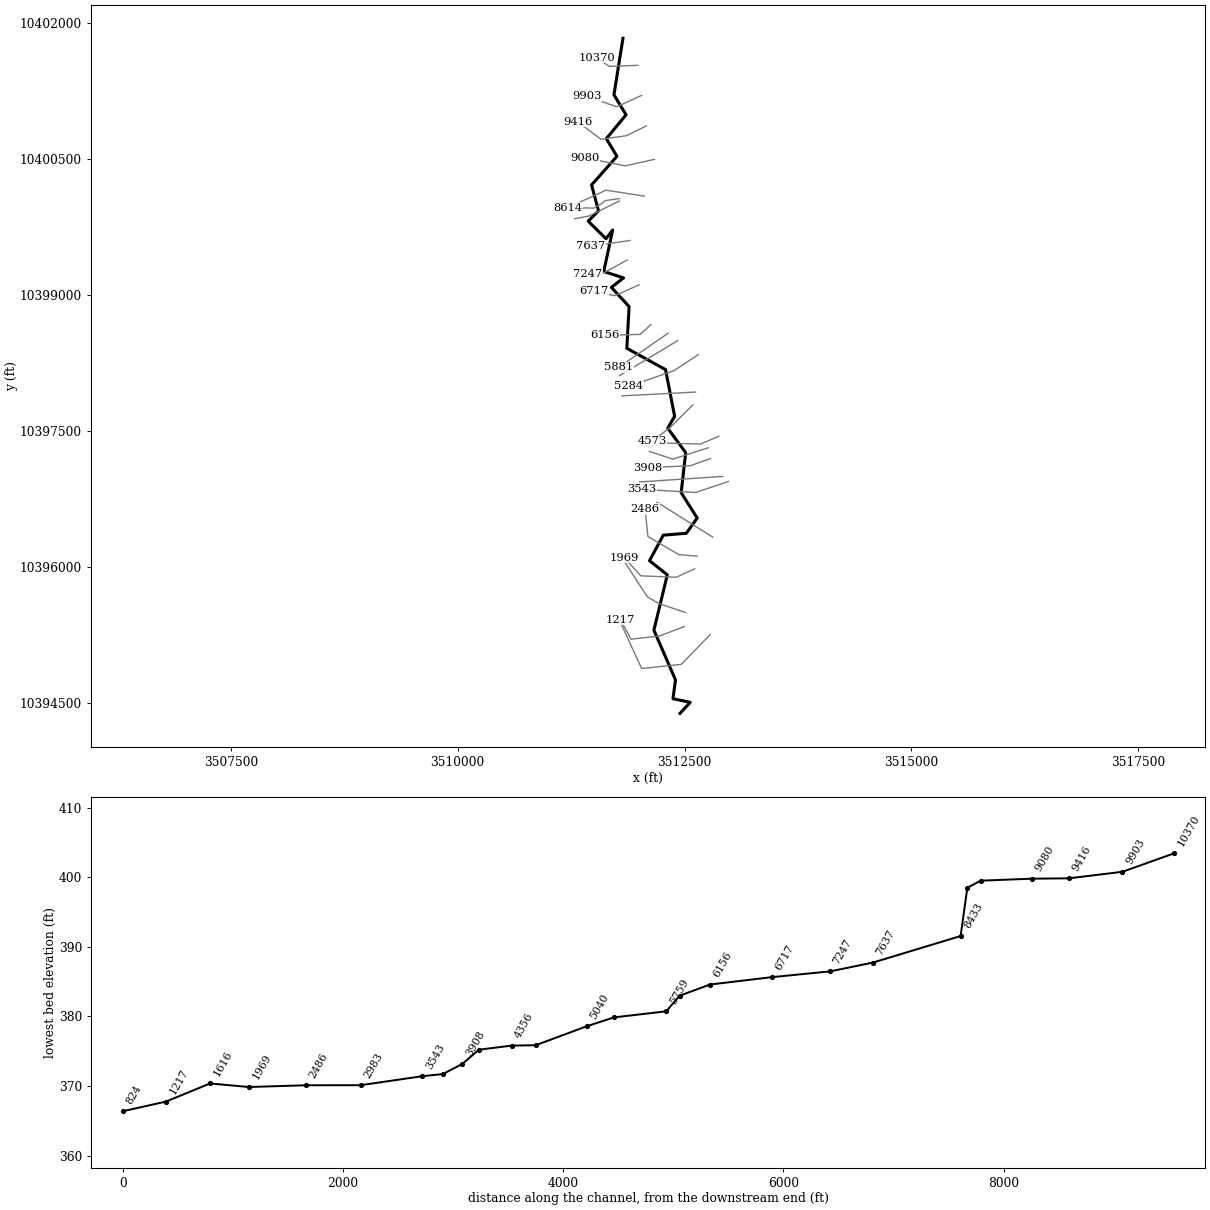
--- NORTH MINERAL CR TRIB 6.prj (project) ---

Proj Title=NORTH MINERAL CR TRIB 6 Base Level Engineering
Current Plan=p01
Default Exp/Contr=0.3,0.1
English Units
Geom File=g01
Flow File=f01
Plan File=p01
Y Axis Title=Elevation
X Axis Title(PF)=Main Channel Distance
X Axis Title(XS)=Station
BEGIN DESCRIPTION:
NORTH MINERAL CR TRIB 6
END DESCRIPTION:
DSS Export Rating Curves= 0
DSS Export Rating Curve Sorted= 0
DSS Export Volume Flow Curves= 0
DXF OffsetX= 0
DXF OffsetY= 0
DXF ScaleX= 1
DXF ScaleY= 10

--- NORTH MINERAL CR TRIB 6.p01 (plan) ---

Plan Title=Multiple Run
Short Identifier=Multiple
Geom File=g01
Flow File=f01
Subcritical Flow
K Sum by GR= 0
Std Step Tol= 0.01
Critical Tol= 0.01
Num of Std Step Trials= 20
Max Error Tol= 0.3
Flow Tol Ratio= 0.001
Split Flow NTrial= 30
Split Flow Tol= 0.02
Split Flow Ratio= 0.02
Log Output Level= 0
Friction Slope Method= 1
Unsteady Friction Slope Method= 2
Unsteady Bridges Friction Slope Method= 1
Parabolic Critical Depth
Global Vel Dist=  1 , 1 , 1
Global Log Level= 0
CheckData=True
Encroach Param= -1, 0, 0, 0
BEGIN DESCRIPTION:
Multiple Run
END DESCRIPTION:

--- NORTH MINERAL CR TRIB 6.f01 (steady flow) ---

Flow Title=Multiple
Program Version=4.10
Number of Profiles= 7
Profile Names=10-year,25-year,50-year,1pct_min,100-year,1pct_plu,500-year
River Rch & RM=NORTH MINERAL CR,Reach-1         ,10370
     443     583     694     605     818    1107    1132
River Rch & RM=NORTH MINERAL CR,Reach-1         ,8614
     732     993    1205    1069    1445    1954    2072
River Rch & RM=NORTH MINERAL CR,Reach-1         ,4356
     872    1192    1454    1294    1750    2367    2529
River Rch & RM=NORTH MINERAL CR,Reach-1         ,4058
     872    1192    1454    1294    1750    2367    2529
Boundary for River Rch & Prof#=NORTH MINERAL CR,Reach-1         , 1
Up Type= 0
Dn Type= 3
Dn Slope=0.005
Boundary for River Rch & Prof#=NORTH MINERAL CR,Reach-1         , 2
Up Type= 0
Dn Type= 3
Dn Slope=0.005
Boundary for River Rch & Prof#=NORTH MINERAL CR,Reach-1         , 3
Up Type= 0
Dn Type= 3
Dn Slope=0.005
Boundary for River Rch & Prof#=NORTH MINERAL CR,Reach-1         , 4
Up Type= 0
Dn Type= 3
Dn Slope=0.005
Boundary for River Rch & Prof#=NORTH MINERAL CR,Reach-1         , 5
Up Type= 0
Dn Type= 3
Dn Slope=0.005
Boundary for River Rch & Prof#=NORTH MINERAL CR,Reach-1         , 6
Up Type= 0
Dn Type= 3
Dn Slope=0.005
Boundary for River Rch & Prof#=NORTH MINERAL CR,Reach-1         , 7
Up Type= 0
Dn Type= 3
Dn Slope=0.005
DSS Import GetInterval= 0
DSS Import GetPeak= 0
DSS Import FillOption= 0

--- NORTH MINERAL CR TRIB 6.g01 (geometry) ---

Geom Title=Existing Conditions

River Reach=NORTH MINERAL CR,Reach-1
Reach XY= 30
      3511821.41     10401835.39      3511722.04     10401211.71
      3511855.72     10400992.07      3511638.26     10400728.46
      3511754.92     10400533.35      3511475.17     10400217.66
      3511552.25     10399932.76      3511438.43     10399817.97
      3511634.16     10399624.53      3511708.23     10399720.97
      3511609.49     10399262.50      3511828.07     10399192.45
      3511693.52     10399087.85      3511889.26     10398876.04
      3511864.09     10398415.54      3512290.74     10398180.73
      3512391.23     10397665.62      3512314.84     10397533.68
      3512513.22     10397264.73      3512463.22     10396822.39
      3512639.82     10396543.19      3512520.56     10396375.03
      3512266.16     10396353.71      3512114.01     10396071.68
      3512310.54     10395916.41      3512162.54     10395305.93
      3512400.61     10394756.97      3512372.84     10394549.33
      3512563.46     10394509.40      3512450.45     10394387.65

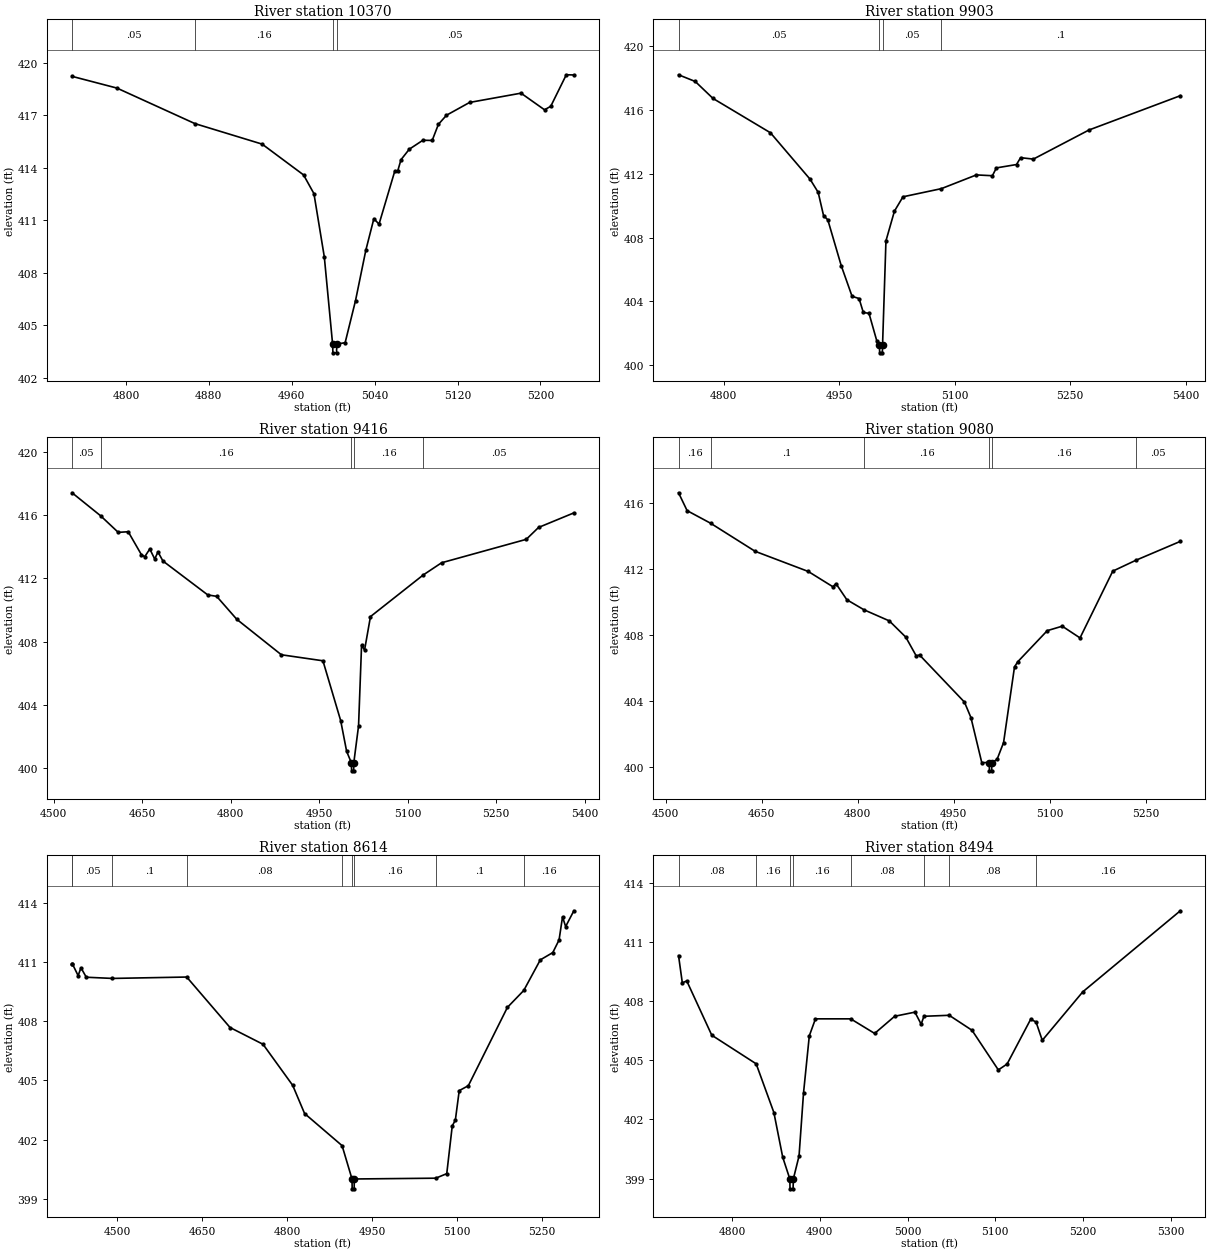
Type RM Length L Ch R = 1,10370,467,467,467
BEGIN DESCRIPTION:
NORTH MINERAL CR TRIB 6 25 0
END DESCRIPTION:
XS GIS Cut Line= 3
      3511985.38     10401537.61      3511671.53     10401525.89
      3511529.57     10401619.66
#Sta/Elev= 30
  4748.0  419.21  4791.3  418.54  4866.6  416.51  4931.4  415.34  4971.4  413.58
  4981.4  412.51  4991.4  408.90  4999.4  403.92  4999.7  403.42  5003.2  403.42
  5003.4  403.92  5011.5  404.00  5021.5  406.40  5031.5  409.29  5039.2  411.08
  5044.2  410.77  5059.3  413.78  5062.1  413.78  5065.4  414.45  5073.4  415.05
  5086.5  415.56  5095.5  415.55  5101.5  416.47  5109.3  416.99  5131.6  417.72
  5181.2  418.25  5203.9  417.30  5209.9  417.50  5224.9  419.30  5232.2  419.29
#Mann=4,-1,0
  4748.0    0.05       0  4866.6    0.16       0  4999.4    0.07       0
  5003.4    0.05       0
Bank Sta=4999.4,5003.4
Exp/Cntr=0.3,0.1

Type RM Length L Ch R = 1,9903,487,487,487
BEGIN DESCRIPTION:
NORTH MINERAL CR TRIB 6 20
END DESCRIPTION:
XS GIS Cut Line= 3
      3512026.99     10401205.57      3511753.56     10401080.58
      3511421.51     10401193.87
#Sta/Elev= 30
  4741.5  418.19  4763.2  417.77  4786.2  416.71  4860.8  414.56  4912.3  411.65
  4922.8  410.83  4929.8  409.37  4935.3  409.11  4952.8  406.23  4966.8  404.32
  4975.9  404.18  4981.4  403.31  4988.8  403.25  4998.9  401.53  5002.4  401.28
  5002.6  400.78  5006.1  400.78  5006.4  401.28  5010.8  407.79  5021.8  409.65
  5032.9  410.55  5082.7  411.06  5128.2  411.92  5149.0  411.87  5154.2  412.36
  5180.3  412.57  5185.6  413.00  5202.2  412.91  5274.3  414.73  5393.0  416.88
#Mann=4,-1,0
  4741.5    0.05       0  5002.4    0.03       0  5006.4    0.05       0
  5082.7     0.1       0
Bank Sta=5002.4,5006.4
Exp/Cntr=0.3,0.1

Type RM Length L Ch R = 1,9416,336,336,336
BEGIN DESCRIPTION:
NORTH MINERAL CR TRIB 6 19 1
END DESCRIPTION:
XS GIS Cut Line= 4
      3512080.39     10400869.64      3511860.33     10400761.56
      3511579.08     10400721.20      3511322.59     10400915.20
#Sta/Elev= 30
  4531.0  417.40  4579.3  415.95  4609.3  414.90  4626.2  414.94  4648.6  413.49
  4654.2  413.36  4662.8  413.85  4671.1  413.22  4676.7  413.66  4685.1  413.09
  4761.1  410.95  4776.2  410.86  4810.3  409.41  4885.9  407.17  4956.4  406.79
  4986.5  403.01  4996.6  401.07  5004.7  400.34  5005.0  399.84  5008.5  399.84
  5008.7  400.34  5016.8  402.68  5021.9  407.77  5027.0  407.47  5037.0  409.58
  5126.5  412.21  5157.6  412.98  5301.2  414.46  5322.0  415.21  5381.9  416.13
#Mann=5,-1,0
  4531.0    0.05       0  4579.3    0.16       0  5004.7    0.07       0
  5008.7    0.16       0  5126.5    0.05       0
Bank Sta=5004.7,5008.7
Exp/Cntr=0.3,0.1

Type RM Length L Ch R = 1,9080,466,466,466
BEGIN DESCRIPTION:
Mapping XS d0f7cf75
END DESCRIPTION:
XS GIS Cut Line= 3
      3512168.91     10400499.84      3511847.31     10400428.23
      3511401.07     10400516.70
#Sta/Elev= 30
  4520.0  416.61  4533.4  415.53  4570.0  414.77  4639.7  413.07  4722.8  411.85
  4761.1  410.93  4766.2  411.11  4783.1  410.14  4810.0  409.53  4849.5  408.86
  4875.2  407.88  4891.6  406.74  4896.7  406.80  4966.9  403.95  4977.1  403.01
  4994.0  400.29  5005.7  400.29  5006.0  399.79  5009.5  399.79  5009.7  400.29
  5017.9  400.48  5028.1  401.50  5045.2  406.08  5050.3  406.39  5096.4  408.27
  5119.8  408.54  5147.6  407.83  5198.8  411.87  5234.5  412.52  5304.4  413.67
#Mann=6,-1,0
  4520.0    0.16       0  4570.0     0.1       0  4810.0    0.16       0
  5005.7    0.07       0  5009.7    0.16       0  5234.5    0.05       0
Bank Sta=5005.7,5009.7
Exp/Cntr=0.3,0.1

Type RM Length L Ch R = 1,8614,120,120,120
BEGIN DESCRIPTION:
NORTH MINERAL CR TRIB 6 18 0
END DESCRIPTION:
XS GIS Cut Line= 3
      3512056.90     10400094.91      3511633.77     10400160.00
      3511218.36     10399968.58
#Sta/Elev= 30
  4420.8  410.90  4421.5  410.90  4431.5  410.31  4436.5  410.71  4445.9  410.23
  4492.1  410.17  4623.1  410.24  4699.6  407.68  4757.8  406.83  4810.1  404.75
  4831.1  403.32  4897.3  401.69  4914.8  400.00  4915.1  399.50  4918.6  399.50
  4918.8  400.00  5062.6  400.04  5082.0  400.27  5091.7  402.69  5097.2  402.99
  5104.0  404.48  5120.1  404.73  5189.0  408.70  5217.9  409.56  5247.1  411.11
  5269.1  411.48  5280.2  412.12  5286.3  413.29  5291.8  412.80  5306.3  413.60
#Mann=9,-1,0
  4420.8     0.1       0  4421.5    0.05       0  4492.1     0.1       0
  4623.1    0.08       0  4897.3    0.16       0  4914.8    0.07       0
  4918.8    0.16       0  5062.6     0.1       0  5217.9    0.16       0
Bank Sta=4914.8,4918.8
Exp/Cntr=0.3,0.1

Type RM Length L Ch R = 1,8494,61,61,61
BEGIN DESCRIPTION:
Mapping XS 42fc8ae0
END DESCRIPTION:
XS GIS Cut Line= 6
      3511779.56     10400067.55      3511623.36     10400044.12
      3511589.50     10400014.17      3511499.66     10399962.09
      3511403.30     10399964.69      3511236.21     10399941.37
#Sta/Elev= 30
  4738.9  410.31  4743.2  408.93  4748.3  409.02  4776.8  406.27  4827.4  404.82
  4847.6  402.35  4857.7  400.08  4865.8  398.98  4866.0  398.48  4869.5  398.48
  4869.8  398.98  4876.3  400.15  4881.4  403.34  4888.0  406.24  4895.0  407.10
  4935.2  407.10  4962.5  406.36  4985.3  407.23  5008.4  407.44  5015.5  406.83
  5018.7  407.23  5047.5  407.28  5073.5  406.52  5103.5  404.51  5113.5  404.81
  5140.4  407.08  5146.5  406.94  5153.6  406.01  5199.8  408.47  5311.0  412.58
#Mann=8,-1,0
  4738.9    0.08       0  4827.4    0.16       0  4865.8    0.07       0
  4869.8    0.16       0  4935.2    0.08       0  5018.7     0.1       0
  5047.5    0.08       0  5146.5    0.16       0
Bank Sta=4865.8,4869.8
Exp/Cntr=0.3,0.1

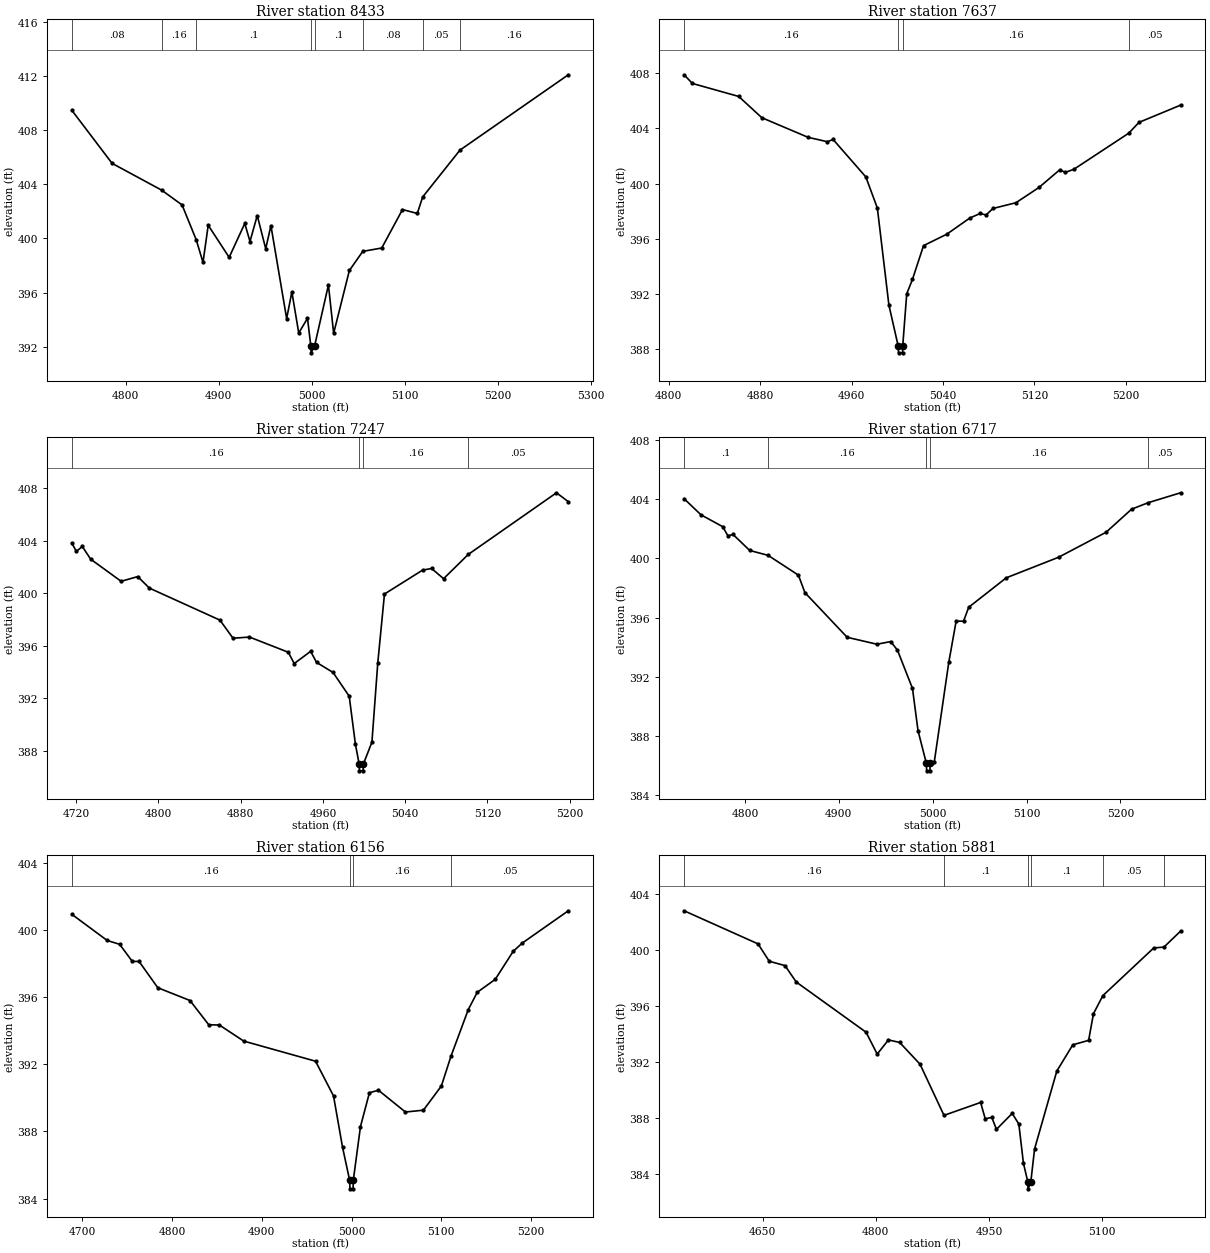
Type RM Length L Ch R = 1,8433,796,796,796
BEGIN DESCRIPTION:
NORTH MINERAL CR TRIB 6 17 0
END DESCRIPTION:
XS GIS Cut Line= 3
      3511780.95     10400040.23      3511444.97     10399874.85
      3511288.70     10399844.89
#Sta/Elev= 30
  4742.0  409.46  4785.3  405.54  4838.6  403.56  4860.5  402.47  4875.7  399.90
  4883.0  398.23  4888.6  400.97  4911.1  398.60  4927.9  401.10  4933.5  399.77
  4941.3  401.69  4950.4  399.24  4956.0  400.94  4972.9  394.08  4978.5  396.05
  4985.9  393.01  4995.3  394.10  4998.9  392.05  4999.2  391.55  5002.9  392.05
  5017.8  396.56  5023.4  392.99  5040.3  397.63  5054.7  399.04  5075.1  399.29
  5097.4  402.13  5113.3  401.84  5119.1  403.06  5159.2  406.52  5275.6  412.08
#Mann=8,-1,0
  4742.0    0.08       0  4838.6    0.16       0  4875.7     0.1       0
  4998.9    0.07       0  5002.9     0.1       0  5054.7    0.08       0
  5119.1    0.05       0  5159.2    0.16       0
Bank Sta=4998.9,5002.9
Exp/Cntr=0.3,0.1

Type RM Length L Ch R = 1,7637,390,390,390
BEGIN DESCRIPTION:
NORTH MINERAL CR TRIB 6 16 0
END DESCRIPTION:
XS GIS Cut Line= 2
      3511899.36     10399605.31      3511469.67     10399541.51
#Sta/Elev= 30
  4813.5  407.89  4820.8  407.26  4861.3  406.32  4881.5  404.78  4921.9  403.36
  4938.8  403.04  4943.9  403.20  4972.5  400.49  4982.6  398.23  4992.7  391.20
  5000.8  388.24  5001.1  387.74  5004.6  387.74  5004.8  388.24  5008.3  392.02
  5013.3  393.06  5023.0  395.51  5043.2  396.33  5063.5  397.51  5072.6  397.84
  5077.7  397.73  5083.7  398.20  5103.9  398.62  5124.1  399.73  5142.1  401.00
  5147.1  400.82  5154.5  401.04  5202.6  403.66  5211.5  404.44  5247.9  405.69
#Mann=4,-1,0
  4813.5    0.16       0  5000.8    0.07       0  5004.8    0.16       0
  5202.6    0.05       0
Bank Sta=5000.8,5004.8
Exp/Cntr=0.3,0.1

Type RM Length L Ch R = 1,7247,530,530,530
BEGIN DESCRIPTION:
NORTH MINERAL CR TRIB 6 15 0
END DESCRIPTION:
XS GIS Cut Line= 3
      3511868.14     10399390.46      3511555.65     10399217.29
      3511430.69     10399230.31
#Sta/Elev= 30
  4715.7  403.83  4720.2  403.20  4725.9  403.58  4734.0  402.61  4763.7  400.92
  4779.8  401.28  4791.2  400.40  4859.8  397.96  4872.5  396.58  4888.5  396.67
  4926.3  395.51  4932.0  394.65  4948.0  395.58  4953.7  394.74  4969.8  393.97
  4985.5  392.16  4991.5  388.52  4995.2  386.97  4995.5  386.47  4999.0  386.47
  4999.2  386.97  5007.6  388.66  5013.3  394.71  5019.8  399.95  5056.8  401.77
  5065.6  401.90  5077.3  401.12  5101.3  402.97  5187.1  407.67  5198.6  406.99
#Mann=4,-1,0
  4715.7    0.16       0  4995.2    0.07       0  4999.2    0.16       0
  5101.3    0.05       0
Bank Sta=4995.2,4999.2
Exp/Cntr=0.3,0.1

Type RM Length L Ch R = 1,6717,561,561,561
BEGIN DESCRIPTION:
NORTH MINERAL CR TRIB 6 14 0
END DESCRIPTION:
XS GIS Cut Line= 3
      3511999.63     10399115.72      3511731.43     10398995.94
      3511500.98     10399042.81
#Sta/Elev= 30
  4735.2  404.04  4753.2  402.95  4776.3  402.15  4781.9  401.53  4787.4  401.62
  4805.1  400.54  4824.7  400.21  4857.0  398.87  4863.9  397.69  4908.9  394.67
  4940.6  394.20  4955.3  394.38  4962.5  393.80  4978.5  391.21  4984.4  388.36
  4993.3  386.14  4993.6  385.64  4997.1  385.64  4997.3  386.14  5001.7  386.23
  5017.2  392.99  5025.0  395.76  5032.9  395.76  5038.4  396.70  5078.4  398.69
  5134.1  400.08  5184.7  401.77  5211.9  403.33  5229.6  403.77  5264.1  404.44
#Mann=5,-1,0
  4735.2     0.1       0  4824.7    0.16       0  4993.3    0.07       0
  4997.3    0.16       0  5229.6    0.05       0
Bank Sta=4993.3,4997.3
Exp/Cntr=0.3,0.1

Type RM Length L Ch R = 1,6156,275,275,275
BEGIN DESCRIPTION:
NORTH MINERAL CR TRIB 6 11 1
END DESCRIPTION:
XS GIS Cut Line= 3
      3512131.17     10398678.23      3512011.38     10398568.86
      3511620.73     10398558.44
#Sta/Elev= 30
  4688.4  400.95  4727.8  399.39  4741.7  399.16  4755.8  398.14  4763.3  398.14
  4784.2  396.57  4820.0  395.81  4841.0  394.36  4852.7  394.35  4879.9  393.39
  4959.9  392.19  4979.9  390.12  4989.9  387.07  4997.9  385.08  4998.2  384.58
  5001.7  384.58  5001.9  385.08  5009.9  388.29  5019.9  390.31  5029.9  390.46
  5060.0  389.16  5080.0  389.27  5100.0  390.71  5110.8  392.50  5130.0  395.27
  5140.0  396.30  5160.0  397.07  5180.0  398.74  5190.0  399.23  5241.4  401.16
#Mann=4,-1,0
  4688.4    0.16       0  4997.9    0.07       0  5001.9    0.16       0
  5110.8    0.05       0
Bank Sta=4997.9,5001.9
Exp/Cntr=0.3,0.1

Type RM Length L Ch R = 1,5881,122,122,122
BEGIN DESCRIPTION:
NORTH MINERAL CR TRIB 6 13 0
END DESCRIPTION:
XS GIS Cut Line= 2
      3512318.67     10398581.88      3511777.09     10398206.94
#Sta/Elev= 30
  4545.6  402.80  4643.7  400.44  4658.6  399.20  4679.5  398.89  4694.4  397.72
  4787.0  394.14  4801.8  392.58  4816.7  393.59  4831.6  393.41  4858.6  391.86
  4890.4  388.21  4939.0  389.13  4945.1  387.97  4953.9  388.06  4960.0  387.21
  4980.9  388.35  4989.7  387.59  4995.8  384.80  5001.6  383.47  5001.9  382.97
  5005.6  383.47  5010.6  385.82  5040.1  391.37  5061.3  393.24  5082.3  393.56
  5088.7  395.46  5101.2  396.75  5168.7  400.15  5182.2  400.21  5204.3  401.35
#Mann=6,-1,0
  4545.6    0.16       0  4890.4     0.1       0  5001.6    0.07       0
  5005.6     0.1       0  5101.2    0.05       0  5182.2    0.16       0
Bank Sta=5001.6,5005.6
Exp/Cntr=0.3,0.1

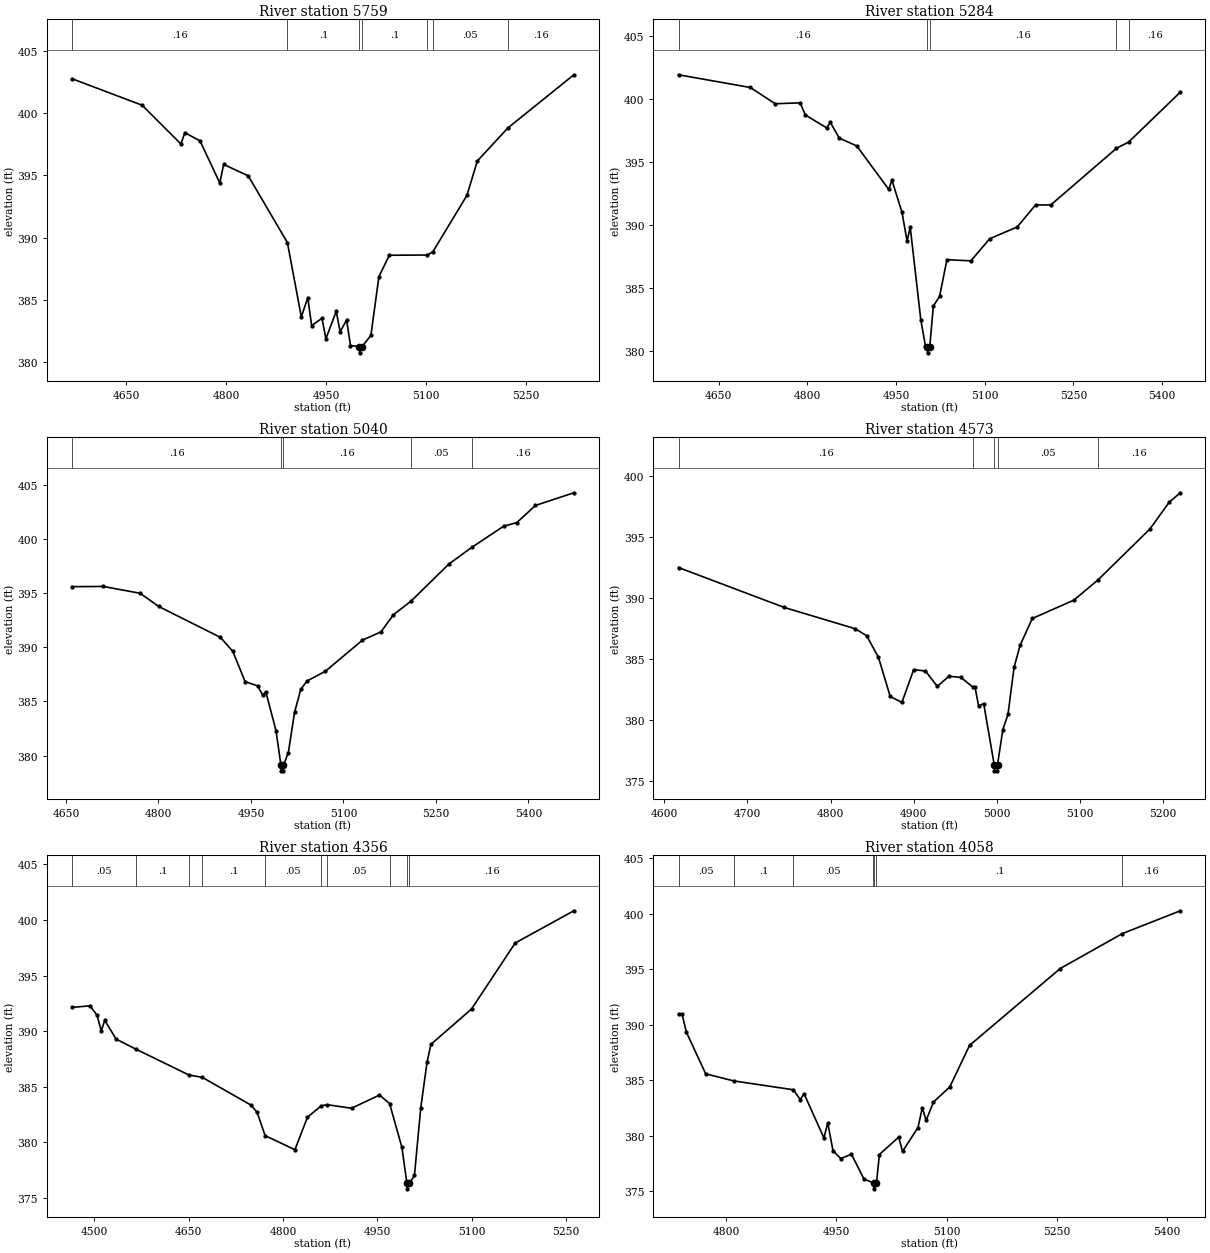
Type RM Length L Ch R = 1,5759,475,475,475
BEGIN DESCRIPTION:
NORTH MINERAL CR TRIB 6 11 0
END DESCRIPTION:
XS GIS Cut Line= 2
      3512426.71     10398501.13      3511780.91     10398113.13
#Sta/Elev= 30
  4568.7  402.78  4673.9  400.65  4732.2  397.53  4738.0  398.44  4760.7  397.79
  4790.5  394.40  4796.3  395.89  4833.2  394.97  4892.0  389.60  4912.9  383.62
  4922.6  385.17  4928.4  382.92  4943.9  383.51  4949.8  381.86  4965.3  384.07
  4971.2  382.43  4980.9  383.37  4986.7  381.32  5000.2  381.23  5000.5  380.73
  5004.2  381.23  5017.4  382.14  5029.4  386.86  5045.0  388.58  5102.1  388.60
  5110.4  388.86  5161.6  393.40  5177.1  396.16  5223.0  398.82  5322.1  403.10
#Mann=7,-1,0
  4568.7    0.16       0  4892.0     0.1       0  5000.2    0.07       0
  5004.2     0.1       0  5102.1    0.16       0  5110.4    0.05       0
  5223.0    0.16       0
Bank Sta=5000.2,5004.2
Exp/Cntr=0.3,0.1

Type RM Length L Ch R = 1,5284,244,244,244
BEGIN DESCRIPTION:
NORTH MINERAL CR TRIB 6 12 0
END DESCRIPTION:
XS GIS Cut Line= 3
      3512653.61     10398346.81      3512384.55     10398168.88
      3511887.57     10397995.26
#Sta/Elev= 30
  4582.0  401.95  4703.4  400.94  4745.6  399.65  4787.7  399.72  4796.7  398.75
  4832.8  397.73  4838.8  398.17  4853.9  396.92  4883.5  396.30  4937.7  392.84
  4943.0  393.58  4960.1  391.02  4968.7  388.73  4974.0  389.85  4991.9  382.49
  4999.8  380.39  5003.1  380.36  5003.3  379.86  5007.1  380.36  5013.1  383.57
  5023.7  384.35  5036.1  387.26  5076.6  387.17  5108.4  388.92  5155.0  389.86
  5186.1  391.61  5211.8  391.61  5323.0  396.11  5343.4  396.60  5431.0  400.57
#Mann=5,-1,0
  4582.0    0.16       0  5003.1    0.07       0  5007.1    0.16       0
  5323.0    0.05       0  5343.4    0.16       0
Bank Sta=5003.1,5007.1
Exp/Cntr=0.3,0.1

Type RM Length L Ch R = 1,5040,467,467,467
BEGIN DESCRIPTION:
NORTH MINERAL CR TRIB 6 91 0
END DESCRIPTION:
XS GIS Cut Line= 2
      3512622.37     10397932.65      3511809.84     10397890.98
#Sta/Elev= 30
  4660.0  395.59  4710.3  395.61  4770.4  394.98  4800.5  393.76  4900.6  390.91
  4920.6  389.62  4940.6  386.83  4960.7  386.44  4969.1  385.59  4974.1  385.90
  4990.7  382.30  4998.7  379.10  4999.0  378.60  5002.5  378.60  5002.7  379.10
  5010.7  380.29  5020.7  383.99  5030.8  386.11  5040.8  386.88  5070.8  387.79
  5130.9  390.66  5160.9  391.42  5181.0  393.00  5209.3  394.24  5271.1  397.68
  5308.0  399.21  5359.6  401.16  5381.2  401.50  5411.3  403.08  5473.6  404.25
#Mann=5,-1,0
  4660.0    0.16       0  4998.7    0.07       0  5002.7    0.16       0
  5209.3    0.05       0  5308.0    0.16       0
Bank Sta=4998.7,5002.7
Exp/Cntr=0.3,0.1

Type RM Length L Ch R = 1,4573,217,217,217
BEGIN DESCRIPTION:
NORTH MINERAL CR TRIB 6 29 0
END DESCRIPTION:
XS GIS Cut Line= 3
      3512592.14     10397791.67      3512342.11     10397541.64
      3512142.10     10397391.64
#Sta/Elev= 30
  4617.2  392.50  4744.5  389.23  4829.4  387.50  4843.5  386.92  4857.7  385.15
  4871.8  381.95  4885.9  381.46  4900.1  384.15  4914.2  384.03  4928.4  382.78
  4942.5  383.60  4956.7  383.51  4971.8  382.69  4973.9  382.69  4978.1  381.18
  4984.3  381.36  4996.9  376.36  4997.2  375.86  5000.7  375.86  5000.9  376.36
  5007.3  379.23  5013.5  380.48  5020.8  384.33  5028.1  386.14  5042.7  388.33
  5092.7  389.83  5121.8  391.49  5184.3  395.66  5207.3  397.84  5220.8  398.62
#Mann=5,-1,0
  4617.2    0.16       0  4971.8    0.05       0  4996.9    0.04       0
  5000.9    0.05       0  5121.8    0.16       0
Bank Sta=4996.9,5000.9
Exp/Cntr=0.3,0.1

Type RM Length L Ch R = 1,4356,298,298,298
BEGIN DESCRIPTION:
NORTH MINERAL CR TRIB 6 7 2
END DESCRIPTION:
XS GIS Cut Line= 4
      3512878.60     10397445.52      3512676.31     10397358.70
      3512324.74     10397369.12      3512101.70     10397331.80
#Sta/Elev= 30
  4464.7  392.14  4493.5  392.28  4504.4  391.42  4511.2  390.02  4516.7  390.97
  4534.8  389.28  4566.2  388.38  4650.7  386.05  4671.9  385.84  4749.1  383.35
  4759.1  382.68  4771.7  380.60  4819.1  379.33  4839.1  382.26  4861.3  383.29
  4870.7  383.38  4909.1  383.06  4953.6  384.25  4969.7  383.48  4989.2  379.55
  4997.2  376.31  4997.4  375.81  5001.2  376.31  5009.2  377.02  5019.2  383.09
  5029.2  387.20  5035.4  388.81  5100.1  392.00  5169.4  397.93  5262.7  400.83
#Mann=10,-1,0
  4464.7    0.05       0  4566.2     0.1       0  4650.7    0.05       0
  4671.9     0.1       0  4771.7    0.05       0  4861.3    0.16       0
  4870.7    0.05       0  4969.7    0.16       0  4997.2    0.07       0
  5001.2    0.16       0
Bank Sta=4997.2,5001.2
Exp/Cntr=0.3,0.1

Type RM Length L Ch R = 1,4058,150,150,150
BEGIN DESCRIPTION:
NORTH MINERAL CR TRIB 6 7 0
END DESCRIPTION:
XS GIS Cut Line= 3
      3512762.20     10397317.89      3512371.62     10397192.90
      3512112.94     10397277.97
#Sta/Elev= 30
  4735.5  390.94  4740.2  390.98  4746.1  389.34  4772.4  385.58  4810.4  384.94
  4891.8  384.14  4901.0  383.25  4906.2  383.79  4933.2  379.80  4938.4  381.16
  4945.6  378.65  4956.1  377.94  4970.6  378.34  4987.6  376.11  5000.2  375.76
  5000.7  375.72  5001.0  375.22  5004.7  375.72  5008.6  378.31  5034.9  379.88
  5040.1  378.59  5061.1  380.74  5067.0  382.50  5072.3  381.39  5082.1  383.03
  5104.4  384.40  5131.3  388.14  5254.6  395.06  5339.2  398.21  5417.9  400.26
#Mann=7,-1,0
  4735.5    0.05       0  4810.4     0.1       0  4891.8    0.05       0
  5000.2     0.1       0  5000.7    0.04       0  5004.7     0.1       0
  5339.2    0.16       0
Bank Sta=5000.7,5004.7
Exp/Cntr=0.3,0.1

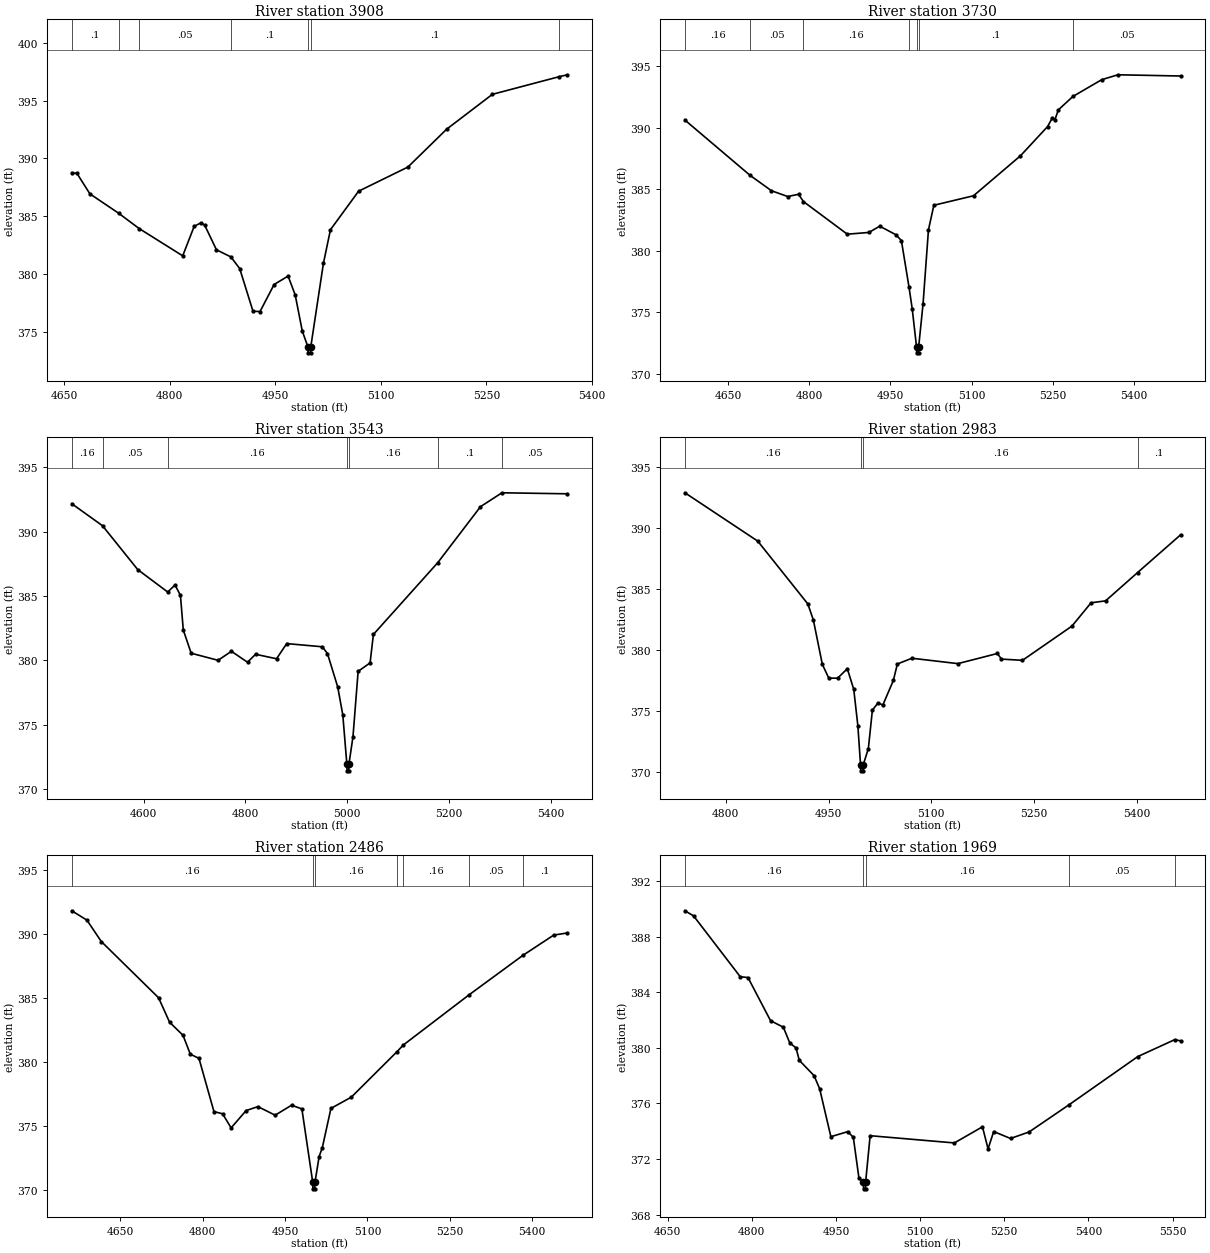
Type RM Length L Ch R = 1,3908,178,178,178
BEGIN DESCRIPTION:
NORTH MINERAL CR TRIB 6 8 0
END DESCRIPTION:
XS GIS Cut Line= 3
      3512786.44     10397198.27      3512560.94     10397119.92
      3512095.53     10397099.16
#Sta/Elev= 30
  4660.6  388.76  4668.0  388.70  4686.4  386.93  4727.1  385.26  4756.4  383.93
  4818.3  381.57  4834.6  384.12  4844.1  384.42  4849.4  384.24  4866.3  382.09
  4886.7  381.48  4899.3  380.47  4918.2  376.78  4928.2  376.75  4948.2  379.09
  4968.1  379.82  4978.2  378.19  4988.2  375.08  4996.3  373.68  4996.5  373.18
  5000.0  373.18  5000.3  373.68  5018.3  380.92  5028.3  383.83  5068.3  387.16
  5138.4  389.25  5193.4  392.52  5258.5  395.54  5353.7  397.07  5365.2  397.23
#Mann=7,-1,0
  4660.6     0.1       0  4727.1    0.16       0  4756.4    0.05       0
  4886.7     0.1       0  4996.3    0.07       0  5000.3     0.1       0
  5353.7    0.05       0
Bank Sta=4996.3,5000.3
Exp/Cntr=0.3,0.1

Type RM Length L Ch R = 1,3730,187,187,187
BEGIN DESCRIPTION:
NORTH MINERAL CR TRIB 6 6 0
END DESCRIPTION:
XS GIS Cut Line= 2
      3512922.00     10397001.86      3512006.21     10396941.16
#Sta/Elev= 30
  4569.4  390.63  4690.0  386.14  4729.6  384.89  4759.7  384.42  4779.8  384.60
  4788.8  384.01  4870.0  381.36  4910.0  381.50  4930.1  382.01  4960.2  381.31
  4970.2  380.84  4984.4  377.03  4990.2  375.31  4998.2  372.22  4998.5  371.72
  5002.0  371.72  5002.2  372.22  5010.3  375.70  5020.3  381.71  5030.3  383.71
  5103.7  384.48  5190.7  387.73  5240.8  390.10  5249.4  390.79  5254.4  390.65
  5260.8  391.46  5287.8  392.55  5341.0  393.91  5371.1  394.31  5487.2  394.21
#Mann=7,-1,0
  4569.4    0.16       0  4690.0    0.05       0  4788.8    0.16       0
  4984.4     0.1       0  4998.2    0.07       0  5002.2     0.1       0
  5287.8    0.05       0
Bank Sta=4998.2,5002.2
Exp/Cntr=0.3,0.1

Type RM Length L Ch R = 1,3543,560,560,560
BEGIN DESCRIPTION:
NORTH MINERAL CR TRIB 6 7 1
END DESCRIPTION:
XS GIS Cut Line= 3
      3512984.53     10396946.30      3512621.70     10396824.78
      3512031.46     10396859.50
#Sta/Elev= 30
  4459.0  392.17  4519.4  390.46  4588.6  387.05  4647.4  385.31  4661.9  385.85
  4672.5  385.05  4678.1  382.36  4693.6  380.55  4746.4  380.00  4772.7  380.70
  4804.3  379.85  4820.1  380.47  4861.3  380.12  4881.3  381.30  4951.4  381.05
  4961.4  380.52  4981.5  377.93  4991.5  375.76  4999.5  371.91  4999.8  371.41
  5003.3  371.41  5003.5  371.91  5011.5  374.07  5021.6  379.14  5045.1  379.80
  5051.6  382.01  5178.3  387.60  5262.0  391.94  5304.2  393.02  5432.9  392.94
#Mann=7,-1,0
  4459.0    0.16       0  4519.4    0.05       0  4647.4    0.16       0
  4999.5    0.07       0  5003.5    0.16       0  5178.3     0.1       0
  5304.2    0.05       0
Bank Sta=4999.5,5003.5
Exp/Cntr=0.3,0.1

Type RM Length L Ch R = 1,2983,497,497,497
BEGIN DESCRIPTION:
NORTH MINERAL CR TRIB 6 6 1
END DESCRIPTION:
XS GIS Cut Line= 2
      3512811.03     10396332.47      3512197.57     10396716.96
#Sta/Elev= 30
  4740.3  392.89  4846.7  388.93  4919.8  383.79  4927.9  382.47  4941.0  378.84
  4950.4  377.71  4963.3  377.71  4977.5  378.48  4986.9  376.79  4992.9  373.80
  4996.8  370.62  4997.0  370.12  5000.5  370.12  5000.8  370.62  5008.2  371.94
  5014.1  375.09  5022.3  375.68  5029.4  375.51  5044.7  377.52  5050.6  378.87
  5071.8  379.34  5139.0  378.90  5196.7  379.73  5202.6  379.27  5233.3  379.17
  5305.5  381.97  5333.5  383.88  5354.7  384.04  5401.5  386.36  5464.3  389.45
#Mann=4,-1,0
  4740.3    0.16       0  4996.8    0.07       0  5000.8    0.16       0
  5401.5     0.1       0
Bank Sta=4996.8,5000.8
Exp/Cntr=0.3,0.1

Type RM Length L Ch R = 1,2486,517,517,517
BEGIN DESCRIPTION:
NORTH MINERAL CR TRIB 6 5 1
END DESCRIPTION:
XS GIS Cut Line= 4
      3512639.63     10396121.94      3512437.81     10396139.30
      3512097.10     10396338.95      3512064.55     10396642.75
#Sta/Elev= 30
  4561.4  391.82  4589.0  391.09  4615.2  389.42  4719.5  385.03  4739.6  383.12
  4764.0  382.10  4777.4  380.62  4793.1  380.30  4820.4  376.14  4836.1  375.97
  4851.7  374.87  4879.0  376.22  4900.5  376.53  4931.9  375.86  4961.8  376.64
  4980.6  376.35  5000.4  370.61  5000.6  370.11  5004.1  370.11  5004.4  370.61
  5012.0  372.63  5017.8  373.32  5033.5  376.39  5070.7  377.27  5153.9  380.82
  5165.4  381.34  5284.6  385.24  5382.9  388.33  5439.3  389.92  5464.4  390.09
#Mann=7,-1,0
  4561.4    0.16       0  5000.4    0.07       0  5004.4    0.16       0
  5153.9    0.05       0  5165.4    0.16       0  5284.6    0.05       0
  5382.9     0.1       0
Bank Sta=5000.4,5004.4
Exp/Cntr=0.3,0.1

Type RM Length L Ch R = 1,1969,353,353,353
BEGIN DESCRIPTION:
NORTH MINERAL CR TRIB 6 5 0
END DESCRIPTION:
XS GIS Cut Line= 4
      3512611.44     10395983.06      3512411.77     10395889.73
      3512018.97     10395904.92      3511836.91     10396104.32
#Sta/Elev= 30
  4680.8  389.85  4696.3  389.48  4779.4  385.11  4793.2  385.05  4833.4  381.95
  4856.2  381.48  4867.7  380.35  4878.8  379.99  4884.6  379.10  4910.9  378.00
  4920.9  377.06  4940.9  373.61  4970.9  373.97  4980.9  373.57  4990.9  370.65
  4998.9  370.36  4999.2  369.86  5002.7  369.86  5002.9  370.36  5010.9  373.68
  5161.1  373.16  5211.1  374.32  5221.1  372.73  5231.1  373.98  5261.1  373.48
  5294.3  373.95  5365.3  375.90  5488.0  379.37  5553.5  380.58  5564.3  380.50
#Mann=5,-1,0
  4680.8    0.16       0  4998.9    0.07       0  5002.9    0.16       0
  5365.3    0.05       0  5553.5    0.16       0
Bank Sta=4998.9,5002.9
Exp/Cntr=0.3,0.1

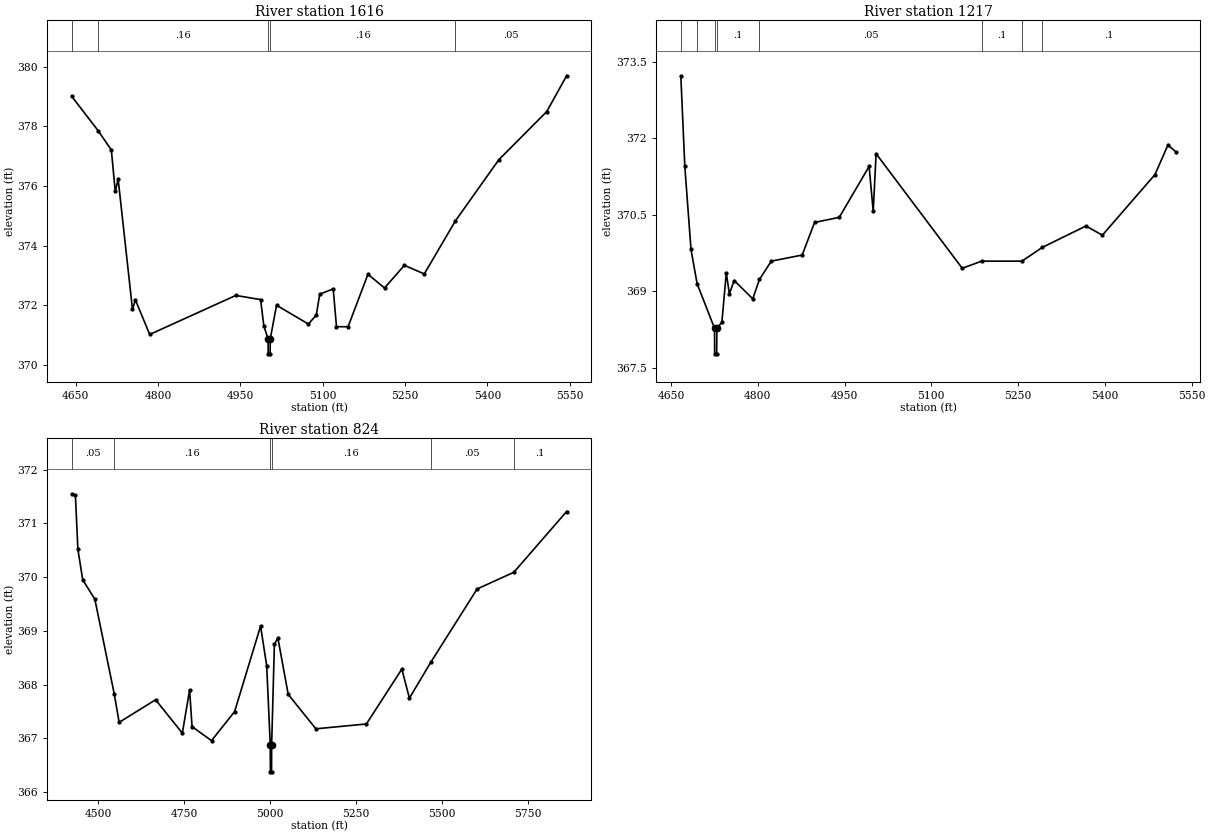
Type RM Length L Ch R = 1,1616,399,399,399
BEGIN DESCRIPTION:
NORTH MINERAL CR TRIB 6 51 0
END DESCRIPTION:
XS GIS Cut Line= 4
      3512510.50     10395500.54      3512212.41     10395601.85
      3512091.62     10395672.96      3511847.27     10396046.79
#Sta/Elev= 30
  4642.6  379.01  4690.6  377.86  4714.8  377.21  4721.9  375.82  4727.2  376.23
  4753.3  371.86  4758.6  372.18  4784.7  371.02  4941.6  372.33  4986.7  372.19
  4992.6  371.31  5000.3  370.87  5000.6  370.37  5004.1  370.37  5004.3  370.87
  5015.8  372.00  5073.8  371.37  5088.2  371.67  5094.4  372.37  5119.0  372.55
  5125.0  371.28  5146.1  371.28  5182.3  373.04  5212.5  372.58  5248.7  373.34
  5284.9  373.05  5341.6  374.83  5420.6  376.88  5508.1  378.50  5544.2  379.70
#Mann=5,-1,0
  4642.6    0.05       0  4690.6    0.16       0  5000.3    0.07       0
  5004.3    0.16       0  5341.6    0.05       0
Bank Sta=5000.3,5004.3
Exp/Cntr=0.3,0.1

Type RM Length L Ch R = 1,1217,393,393,393
BEGIN DESCRIPTION:
Mapping XS 8787daa6
END DESCRIPTION:
XS GIS Cut Line= 4
      3512498.55     10395345.02      3512220.79     10395240.86
      3511910.47     10395206.14      3511793.30     10395423.12
#Sta/Elev= 30
  4666.9  373.23  4673.8  371.45  4684.5  369.82  4695.0  369.15  4725.2  368.27
  4725.4  367.77  4728.9  367.77  4729.2  368.27  4737.9  368.39  4745.5  369.36
  4750.8  368.95  4759.2  369.21  4791.3  368.85  4802.8  369.23  4823.3  369.59
  4876.7  369.71  4898.1  370.35  4940.8  370.45  4992.4  371.45  4999.5  370.57
  5004.5  371.70  5153.4  369.45  5186.9  369.59  5256.6  369.59  5291.8  369.86
  5367.2  370.28  5395.7  370.10  5486.6  371.29  5509.0  371.87  5522.4  371.74
#Mann=8,-1,0
  4666.9    0.05       0  4695.0     0.1       0  4725.2    0.03       0
  4729.2     0.1       0  4802.8    0.05       0  5186.9     0.1       0
  5256.6    0.05       0  5291.8     0.1       0
Bank Sta=4725.2,4729.2
Exp/Cntr=0.3,0.1

Type RM Length L Ch R = 1,824,0,0,0
BEGIN DESCRIPTION:
NORTH MINERAL CR TRIB 6 19 0
END DESCRIPTION:
XS GIS Cut Line= 4
      3512782.87     10395256.07      3512463.85     10394928.36
      3512027.65     10394882.79      3511800.02     10395377.07
#Sta/Elev= 30
  4423.6  371.55  4434.3  371.52  4441.5  370.52  4455.6  369.95  4490.9  369.59
  4547.3  367.83  4561.6  367.30  4667.6  367.72  4745.5  367.10  4766.6  367.90
  4773.8  367.22  4830.4  366.96  4897.6  367.50  4973.2  369.09  4991.0  368.35
  5001.4  366.88  5001.6  366.38  5005.1  366.38  5005.4  366.88  5013.4  368.75
  5023.5  368.87  5053.6  367.82  5134.1  367.18  5281.1  367.27  5384.3  368.29
  5406.3  367.75  5468.8  368.42  5603.3  369.78  5710.1  370.09  5863.7  371.22
#Mann=6,-1,0
  4423.6    0.05       0  4547.3    0.16       0  5001.4    0.07       0
  5005.4    0.16       0  5468.8    0.05       0  5710.1     0.1       0
Bank Sta=5001.4,5005.4
Exp/Cntr=0.3,0.1

Chan Stop Cuts=-1