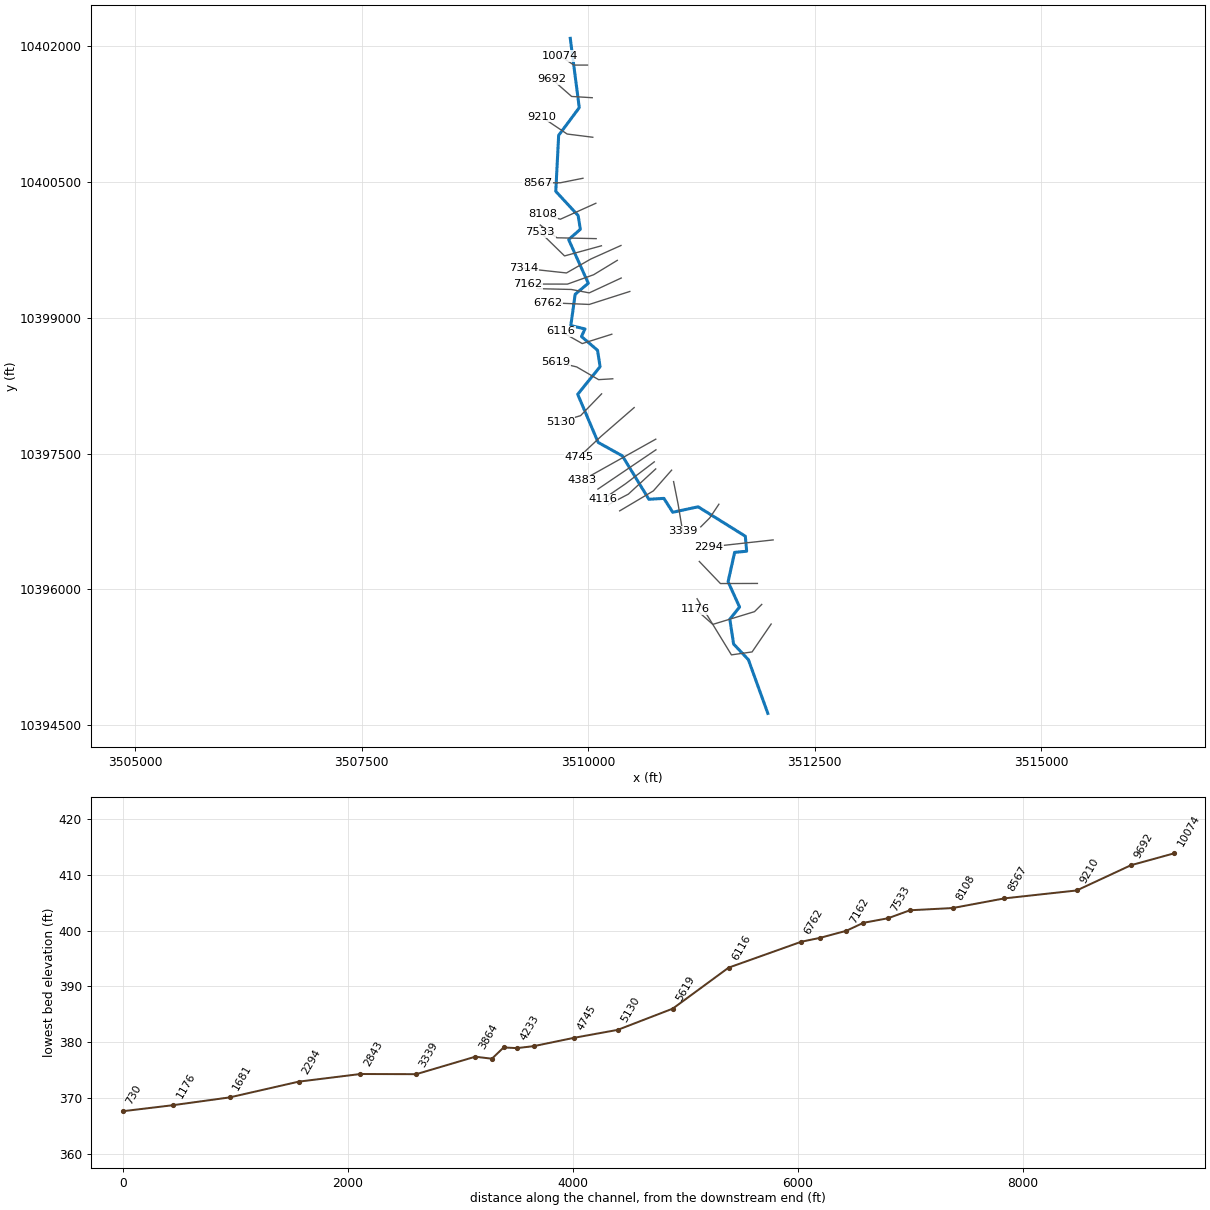
--- NORTH MINERAL CR TRIB 7.prj (project) ---

Proj Title=NORTH MINERAL CR TRIB 7 Base Level Engineering
Current Plan=p01
Default Exp/Contr=0.3,0.1
English Units
Geom File=g01
Flow File=f01
Plan File=p01
Y Axis Title=Elevation
X Axis Title(PF)=Main Channel Distance
X Axis Title(XS)=Station
BEGIN DESCRIPTION:
NORTH MINERAL CR TRIB 7
END DESCRIPTION:
DSS Export Rating Curves= 0
DSS Export Rating Curve Sorted= 0
DSS Export Volume Flow Curves= 0
DXF OffsetX= 0
DXF OffsetY= 0
DXF ScaleX= 1
DXF ScaleY= 10

--- NORTH MINERAL CR TRIB 7.p01 (plan) ---

Plan Title=Multiple Run
Short Identifier=Multiple
Geom File=g01
Flow File=f01
Subcritical Flow
K Sum by GR= 0
Std Step Tol= 0.01
Critical Tol= 0.01
Num of Std Step Trials= 20
Max Error Tol= 0.3
Flow Tol Ratio= 0.001
Split Flow NTrial= 30
Split Flow Tol= 0.02
Split Flow Ratio= 0.02
Log Output Level= 0
Friction Slope Method= 1
Unsteady Friction Slope Method= 2
Unsteady Bridges Friction Slope Method= 1
Parabolic Critical Depth
Global Vel Dist=  1 , 1 , 1
Global Log Level= 0
CheckData=True
Encroach Param= -1, 0, 0, 0
BEGIN DESCRIPTION:
Multiple Run
END DESCRIPTION:

--- NORTH MINERAL CR TRIB 7.f01 (steady flow) ---

Flow Title=Multiple
Number of Profiles=7
Profile Names=10-year,25-year,50-year,1pct_min,100-year,1pct_plu,500-year
River Rch & RM= NORTH MINERAL CR,Reach-1,10074
     806    1095    1330    1179    1594    2156    2286
Boundary for River Rch & Prof#=NORTH MINERAL CR,Reach-1,1
Up Type=0
Dn Type=3
Dn Slope=0.005
Boundary for River Rch & Prof#=NORTH MINERAL CR,Reach-1,2
Up Type=0
Dn Type=3
Dn Slope=0.005
Boundary for River Rch & Prof#=NORTH MINERAL CR,Reach-1,3
Up Type=0
Dn Type=3
Dn Slope=0.005
Boundary for River Rch & Prof#=NORTH MINERAL CR,Reach-1,4
Up Type=0
Dn Type=3
Dn Slope=0.005
Boundary for River Rch & Prof#=NORTH MINERAL CR,Reach-1,5
Up Type=0
Dn Type=3
Dn Slope=0.005
Boundary for River Rch & Prof#=NORTH MINERAL CR,Reach-1,6
Up Type=0
Dn Type=3
Dn Slope=0.005
Boundary for River Rch & Prof#=NORTH MINERAL CR,Reach-1,7
Up Type=0
Dn Type=3
Dn Slope=0.005

--- NORTH MINERAL CR TRIB 7.g01 (geometry) ---

Geom Title=Existing Conditions
Program Version=4.10

River Reach=NORTH MINERAL CR,Reach-1
Reach XY= 30
      3509801.94     10402086.96      3509901.17     10401321.33
      3509673.73     10401015.87      3509642.12     10400397.17
      3509888.66     10400130.21      3509913.13     10399978.03
      3509783.96     10399864.14      3510000.82     10399381.97
      3509855.87     10399260.25      3509807.92     10398914.49
      3509964.03     10398877.55      3509925.49     10398793.48
      3510102.59     10398642.12      3510131.02     10398461.26
      3509883.99     10398155.46      3510109.52     10397624.21
      3510377.22     10397475.25      3510669.39     10396996.12
      3510835.09     10397006.18      3510932.61     10396852.57
      3511212.91     10396913.14      3511733.86     10396588.29
      3511748.44     10396422.48      3511615.75     10396409.78
      3511543.83     10396085.79      3511670.03     10395805.93
      3511562.73     10395672.28      3511604.37     10395397.72
      3511767.78     10395224.61      3511982.11     10394631.64

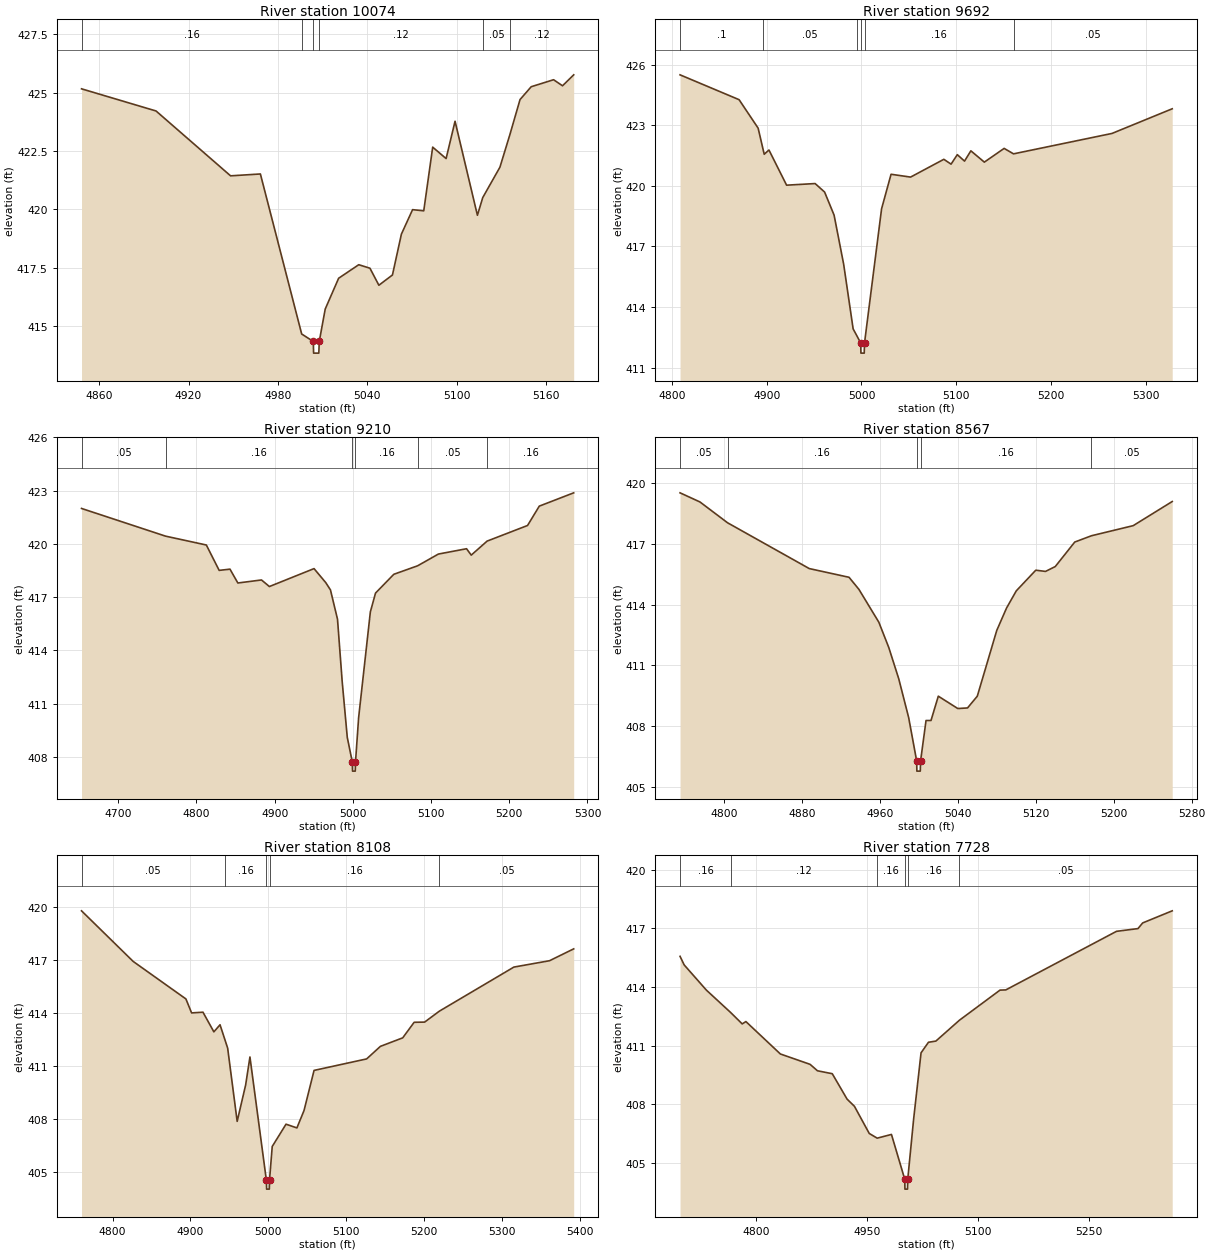
Type RM Length L Ch R = 1 ,10074   ,382,382,382
BEGIN DESCRIPTION:
NORTH MINERAL CR TRIB 7 3 0
END DESCRIPTION:
XS GIS Cut Line= 3
      3509992.08     10401791.64      3509842.11     10401791.64
      3509692.15     10401891.62
#Sta/Elev= 30
  4848.2  425.17  4898.2  424.22  4948.2  421.44  4968.2  421.52  4995.9  414.66
  5003.7  414.34  5003.9  413.84  5007.4  413.84  5007.7  414.34  5011.7  415.73
  5020.7  417.05  5034.2  417.63  5041.7  417.48  5047.7  416.75  5056.8  417.19
  5062.8  418.94  5070.3  419.99  5077.8  419.94  5083.8  422.67  5092.8  422.18
  5098.8  423.78  5113.8  419.75  5117.4  420.51  5128.9  421.81  5135.6  423.21
  5142.4  424.71  5149.9  425.26  5164.9  425.56  5170.9   425.3  5178.4  425.77
#Mann= 6 ,-1 , 0
  4848.2     .16       0  4995.9     .12       0  5003.7     .07       0
  5007.7     .12       0  5117.4     .05       0  5135.6     .12       0
Bank Sta=5003.7,5007.7
XS Rating Curve= 0 ,0
Exp/Cntr=0.3,0.1

Type RM Length L Ch R = 1 ,9692    ,482,482,482
BEGIN DESCRIPTION:
NORTH MINERAL CR TRIB 7 2 0
END DESCRIPTION:
XS GIS Cut Line= 3
      3510044.34     10401431.14      3509816.88     10401445.03
      3509597.91     10401637.18
#Sta/Elev= 30
  4808.6  425.49  4870.9  424.26    4891  422.85  4895.8  421.88  4897.4  421.56
  4902.4  421.77    4921  420.03  4951.1  420.11  4961.1  419.69  4971.1  418.55
  4981.2  416.12  4991.2  412.92  4995.1  412.58  4999.2  412.22  4999.4  411.72
  5002.9  411.72  5003.2  412.22  5021.2  418.86  5031.2  420.57  5051.8  420.43
  5086.9  421.31  5094.5  421.07  5101.1  421.54  5108.7  421.22  5115.4  421.73
  5129.6  421.17  5150.5  421.85  5160.4  421.58  5264.3  422.59  5327.8  423.81
#Mann= 6 ,-1 , 0
  4808.6      .1       0  4895.8     .05       0  4995.1     .16       0
  4999.2     .07       0  5003.2     .16       0  5160.4     .05       0
Bank Sta=4999.2,5003.2
XS Rating Curve= 0 ,0
Exp/Cntr=0.3,0.1

Type RM Length L Ch R = 1 ,9210    ,643,643,643
BEGIN DESCRIPTION:
NORTH MINERAL CR TRIB 7 17 0
END DESCRIPTION:
XS GIS Cut Line= 3
      3510050.41     10400994.51      3509767.41      10401030.1
       3509481.8     10401221.95
#Sta/Elev= 30
  4653.1     422  4760.5  420.44  4812.7  419.94  4829.1  418.51  4842.9  418.58
    4853   417.8  4883.2  417.97  4893.3   417.6  4950.4  418.61  4965.4  417.82
  4971.4  417.41  4980.4  415.76  4986.4  412.24  4992.9   409.1  4999.4   407.7
  4999.6   407.2  5003.1   407.2  5003.4   407.7  5007.4  410.21  5022.4  416.17
    5029  417.23  5052.4  418.29  5082.9  418.77  5109.4  419.43  5145.4  419.73
  5151.4  419.37  5171.7  420.16  5223.4  421.04  5238.4  422.13  5282.4  422.88
#Mann= 6 ,-1 , 0
  4653.1     .05       0  4760.5     .16       0  4999.4     .07       0
  5003.4     .16       0  5082.9     .05       0  5171.7     .16       0
Bank Sta=4999.4,5003.4
XS Rating Curve= 0 ,0
Exp/Cntr=0.3,0.1

Type RM Length L Ch R = 1 ,8567    ,459,459,459
BEGIN DESCRIPTION:
NORTH MINERAL CR TRIB 7 16 0
END DESCRIPTION:
XS GIS Cut Line= 3
      3509942.15     10400541.65      3509692.11     10400491.64
       3509442.1     10400491.64
#Sta/Elev= 30
    4755  419.52  4775.4  419.07  4803.8  418.04  4887.6  415.78  4928.4  415.35
  4938.6  414.75    4959  413.13  4969.2  411.88  4979.4  410.34  4989.6  408.42
  4997.8  406.28    4998  405.78  5001.5  405.78  5001.8  406.28  5007.4  408.28
  5012.5  408.28    5020  409.48    5040  408.87    5050   408.9    5060  409.48
    5080  412.73    5090  413.83    5100  414.68    5120   415.7    5130  415.64
    5140  415.88    5160  417.09  5177.1   417.4    5220   417.9    5260  419.09
#Mann= 5 ,-1 , 0
    4755     .05       0  4803.8     .16       0  4997.8     .07       0
  5001.8     .16       0  5177.1     .05       0
Bank Sta=4997.8,5001.8
XS Rating Curve= 0 ,0
Exp/Cntr=0.3,0.1

Type RM Length L Ch R = 1 ,8108    ,380,380,380
BEGIN DESCRIPTION:
NORTH MINERAL CR TRIB 7 15 0
END DESCRIPTION:
XS GIS Cut Line= 3
      3510084.28     10400265.36      3509692.75     10400089.13
      3509498.33     10400145.55
#Sta/Elev= 30
  4760.2  419.78  4826.5  416.92  4894.2   414.8  4901.5  414.01  4916.1  414.05
  4930.1  412.94    4938  413.34  4944.3  412.49  4947.8  412.02    4960  407.88
  4970.9  409.94  4976.4  411.52  4997.5  404.55  4997.8  404.05  5001.3  404.05
  5001.5  404.55    5005  406.46  5022.7  407.72  5036.7  407.51  5045.8  408.49
  5058.7  410.76  5126.2  411.41  5143.9  412.12  5172.5   412.6  5187.2  413.48
  5200.6  413.49  5219.6  414.11  5315.2   416.6    5361  416.96    5392  417.63
#Mann= 5 ,-1 , 0
  4760.2     .05       0  4944.3     .16       0  4997.5     .07       0
  5001.5     .16       0  5219.6     .05       0
Bank Sta=4997.5,5001.5
XS Rating Curve= 0 ,0
Exp/Cntr=0.3,0.1

Type RM Length L Ch R = 1 ,7728    ,195,195,195
BEGIN DESCRIPTION:
NORTH MINERAL CR TRIB 7 14 0
END DESCRIPTION:
XS GIS Cut Line= 3
      3510087.72     10399874.72      3509653.69     10399884.27
      3509470.49     10400024.92
#Sta/Elev= 30
  4697.7  415.57  4703.3  415.13  4733.3  413.84  4766.2  412.69  4781.7  412.11
  4786.7  412.23  4833.3  410.57  4873.4  410.04  4883.4  409.71  4903.4  409.56
  4923.4  408.26  4933.4  407.89  4953.4   406.5  4964.1  406.26  4983.4  406.45
  5001.4  404.15  5001.6  403.65  5005.1  403.65  5005.4  404.15  5013.4  407.25
  5023.4  410.63  5033.4  411.17  5043.4  411.23  5075.3   412.3  5130.1  413.84
  5137.9  413.85  5287.5  416.85  5316.5  416.99  5322.9  417.28  5362.8   417.9
#Mann= 6 ,-1 , 0
  4697.7     .16       0  4766.2     .12       0  4964.1     .16       0
  5001.4     .07       0  5005.4     .16       0  5075.3     .05       0
Bank Sta=5001.4,5005.4
XS Rating Curve= 0 ,0
Exp/Cntr=0.3,0.1

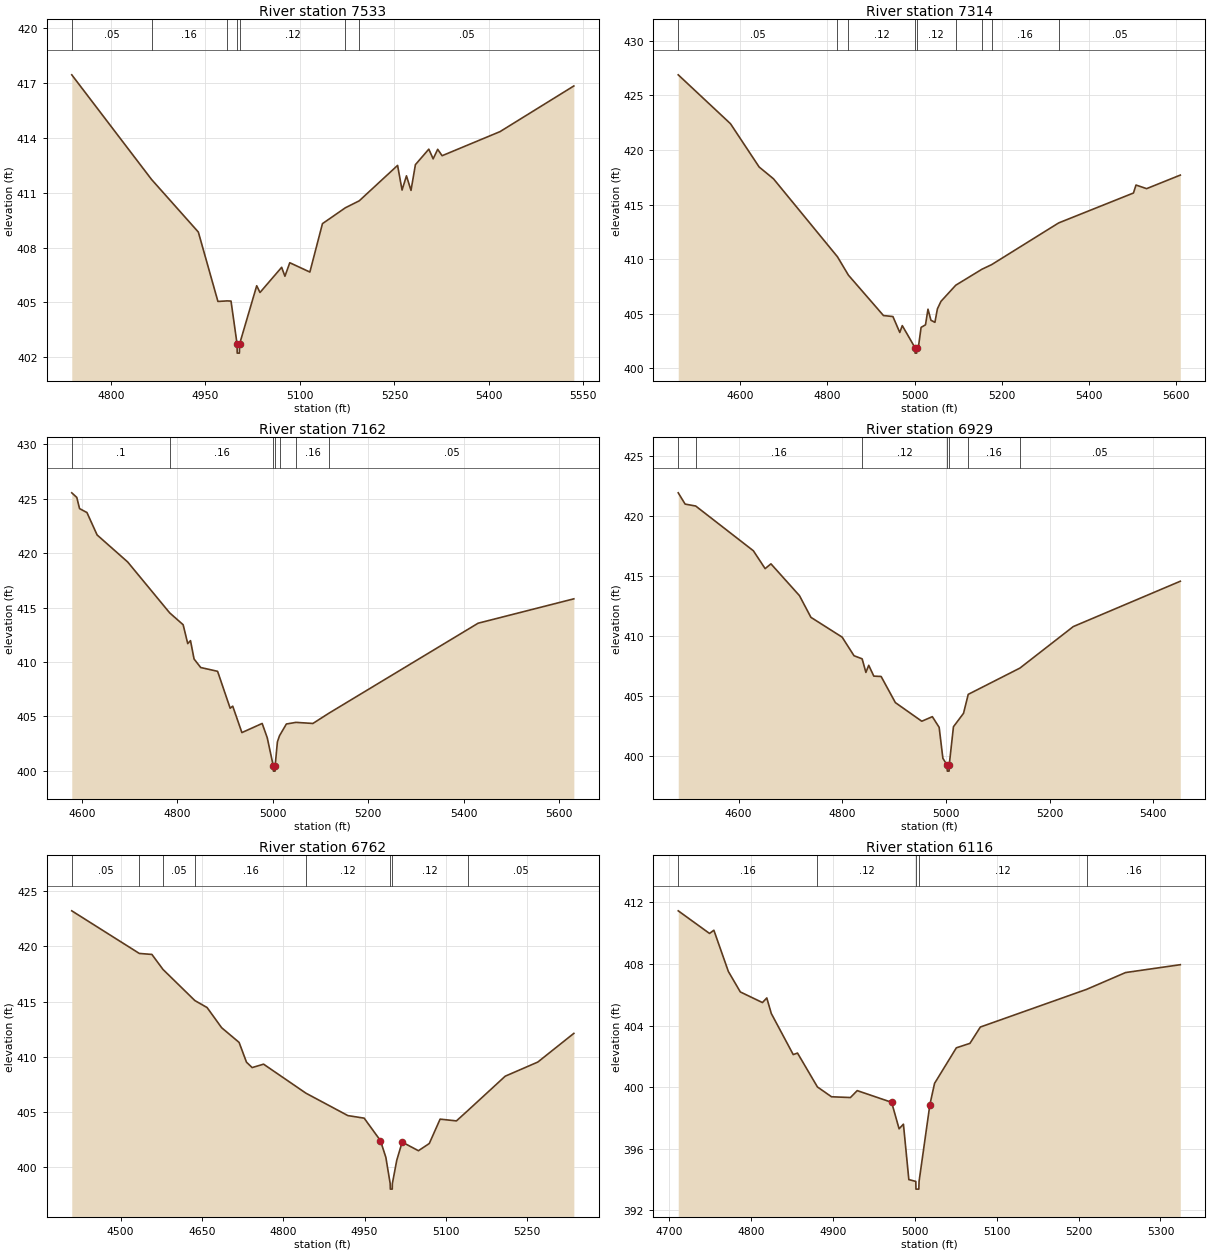
Type RM Length L Ch R = 1 ,7533    ,219,219,219
BEGIN DESCRIPTION:
NORTH MINERAL CR TRIB 7 13 0
END DESCRIPTION:
XS GIS Cut Line= 3
      3510145.92     10399795.74      3509738.76     10399683.75
      3509470.56     10399945.87
#Sta/Elev= 30
  4737.7  417.46  4864.4  411.73  4938.7  408.85  4969.8  405.05  4984.3  405.08
  4990.6  405.07  5000.2  402.72  5000.4  402.22  5003.9  402.22  5004.2  402.72
  5031.4  405.91  5036.6  405.54    5071  406.92  5076.2  406.43  5083.9  407.17
  5115.8  406.66  5135.8  409.31  5172.2  410.18  5194.2  410.56  5255.1   412.5
  5262.2  411.15  5269.2  411.93  5276.4  411.13  5283.4  412.54  5304.7  413.39
  5311.6  412.86  5318.8  413.38  5325.8  413.03  5417.8  414.35    5535  416.85
#Mann= 7 ,-1 , 0
  4737.7     .05       0  4864.4     .16       0  4984.3     .12       0
  5000.2     .07       0  5004.2     .12       0  5172.2     .16       0
  5194.2     .05       0
Bank Sta=5000.2,5004.2
XS Rating Curve= 0 ,0
Exp/Cntr=0.3,0.1

Type RM Length L Ch R = 1 ,7314    ,152,152,152
BEGIN DESCRIPTION:
NORTH MINERAL CR TRIB 7 11 1
END DESCRIPTION:
XS GIS Cut Line= 4
      3510361.53     10399799.14      3510028.15     10399649.38
      3509759.92     10399495.73      3509285.24     10399547.61
#Sta/Elev= 30
  4457.8  426.88  4577.8   422.4  4643.5  418.44  4676.4  417.36  4823.2  410.22
  4848.3  408.54  4928.8  404.84  4950.4  404.75  4966.2  403.29  4971.9  403.92
  5001.1   401.9  5001.4   401.4  5004.9   401.4  5005.1   401.9  5009.4  402.09
  5015.1  403.76  5025.2  403.99  5030.9  405.42  5037.7  404.41  5046.8  404.22
  5052.5  405.45  5060.7  406.14  5094.7  407.62  5154.7  409.08  5176.9   409.5
  5330.7  413.32  5502.4  416.06  5508.2  416.79  5532.6  416.46  5609.9   417.7
#Mann= 9 ,-1 , 0
  4457.8     .05       0  4823.2     .16       0  4848.3     .12       0
  5001.1     .07       0  5005.1     .12       0  5094.7     .16       0
  5154.7     .05       0  5176.9     .16       0  5330.7     .05       0
Bank Sta=5001.1,5005.1
XS Rating Curve= 0 ,0
Exp/Cntr=0.3,0.1

Type RM Length L Ch R = 1 ,7162    ,233,233,233
BEGIN DESCRIPTION:
NORTH MINERAL CR TRIB 7 10 2
END DESCRIPTION:
XS GIS Cut Line= 4
      3510321.13     10399635.06      3510059.51     10399475.99
        3509771.     10399372.63      3509331.55     10399373.33
#Sta/Elev= 30
    4579  425.54  4589.5  425.12  4595.3  424.09  4610.8  423.73  4632.1  421.67
  4696.1  419.19  4784.2  414.51  4812.4  413.42    4822  411.69  4827.8  411.96
  4835.3  410.27  4849.2  409.49  4884.6  409.14  4910.9  405.75  4916.3  405.94
  4935.5  403.51    4978  404.35  4988.6  403.04  5001.2  400.47  5001.5  399.97
    5005  399.97  5005.2  400.47  5009.9  402.66  5014.3  403.22  5028.7   404.3
  5048.9  404.45  5084.3  404.35  5117.8  405.29  5430.5  413.56  5631.1   415.8
#Mann= 7 ,-1 , 0
    4579      .1       0  4784.2     .16       0  5001.2     .07       0
  5005.2     .16       0  5014.3     .12       0  5048.9     .16       0
  5117.8     .05       0
Bank Sta=5001.2,5005.2
XS Rating Curve= 0 ,0
Exp/Cntr=0.3,0.1

Type RM Length L Ch R = 1 ,6929    ,167,167,167
BEGIN DESCRIPTION:
NORTH MINERAL CR TRIB 7 10 1
END DESCRIPTION:
XS GIS Cut Line= 4
      3510364.13     10399439.76      3510011.23     10399275.68
      3509813.31     10399313.44      3509435.78     10399322.52
#Sta/Elev= 30
  4483.7  421.91    4497  420.97  4517.4  420.81  4628.6  417.08  4651.3  415.59
  4662.5  415.99  4717.5  413.34  4739.6  411.53  4799.8  409.88  4822.7  408.33
  4838.4  408.07  4845.6  406.94  4851.1  407.53  4860.9  406.63    4875   406.6
  4902.5  404.42  4953.4  402.87  4973.8  403.25  4986.9  402.36  4994.1  399.78
  5002.3  399.21  5002.6  398.71  5006.1  398.71  5006.3  399.21  5014.5  402.41
  5033.9  403.53    5043  405.11  5142.7   407.3  5245.6  410.76    5452  414.54
#Mann= 7 ,-1 , 0
  4483.7      .1       0  4517.4     .16       0  4838.4     .12       0
  5002.3     .07       0  5006.3     .12       0    5043     .16       0
  5142.7     .05       0
Bank Sta=5002.3,5006.3
XS Rating Curve= 0 ,0
Exp/Cntr=0.3,0.1

Type RM Length L Ch R = 1 ,6762    ,646,646,646
BEGIN DESCRIPTION:
NORTH MINERAL CR TRIB 7 12 0
END DESCRIPTION:
XS GIS Cut Line= 3
       3510459.1     10399291.29      3510011.23     10399148.07
      3509555.66     10399167.54
#Sta/Elev= 30
  4409.8  423.22  4534.4  419.36  4557.6  419.27  4578.1  417.91  4636.9  415.09
  4659.4  414.46  4686.3  412.63  4718.5   411.3  4732.1  409.51  4742.6  409.02
  4763.6  409.33  4841.8   406.7  4919.2  404.67  4949.2  404.44  4979.2  402.41
  4989.2  400.89  4997.2  398.51  4997.5  398.01    5001  398.01  5001.2  398.51
  5009.3  400.62  5019.3  402.27  5049.3  401.49  5069.3  402.14  5089.3  404.35
  5119.4  404.19  5140.3  405.12  5209.4  408.24  5269.5  409.52    5336  412.12
#Mann= 8 ,-1 , 0
  4409.8     .05       0  4534.4     .16       0  4578.1     .05       0
  4636.9     .16       0  4841.8     .12       0  4997.2     .07       0
  5001.2     .12       0  5140.3     .05       0
Bank Sta=4979.2,5019.3
XS Rating Curve= 0 ,0
Exp/Cntr=0.3,0.1

Type RM Length L Ch R = 1 ,6116    ,497,497,497
BEGIN DESCRIPTION:
NORTH MINERAL CR TRIB 7 29 0
END DESCRIPTION:
XS GIS Cut Line= 3
      3510260.46     10398819.16      3509934.07     10398715.87
      3509698.84     10398849.54
#Sta/Elev= 30
  4711.3  411.45  4749.5  409.98  4754.8  410.19  4772.5  407.51  4787.1  406.18
  4814.1  405.49  4819.4  405.79  4824.9  404.78  4851.7  402.11  4856.9  402.21
  4881.2  400.01  4898.4  399.37  4921.5  399.32  4929.8  399.77  4971.8  399.01
  4980.9  397.29  4986.2  397.59  4992.8  393.99  5001.3  393.87  5001.5  393.37
    5005  393.37  5005.3  393.87  5018.5  398.86  5024.2  400.24  5050.8  402.55
  5067.4  402.84  5080.1   403.9  5209.9  406.35  5257.4  407.44  5324.2  407.95
#Mann= 5 ,-1 , 0
  4711.3     .16       0  4881.2     .12       0  5001.3     .07       0
  5005.3     .12       0  5209.9     .16       0
Bank Sta=4971.8,5018.5
XS Rating Curve= 0 ,0
Exp/Cntr=0.3,0.1

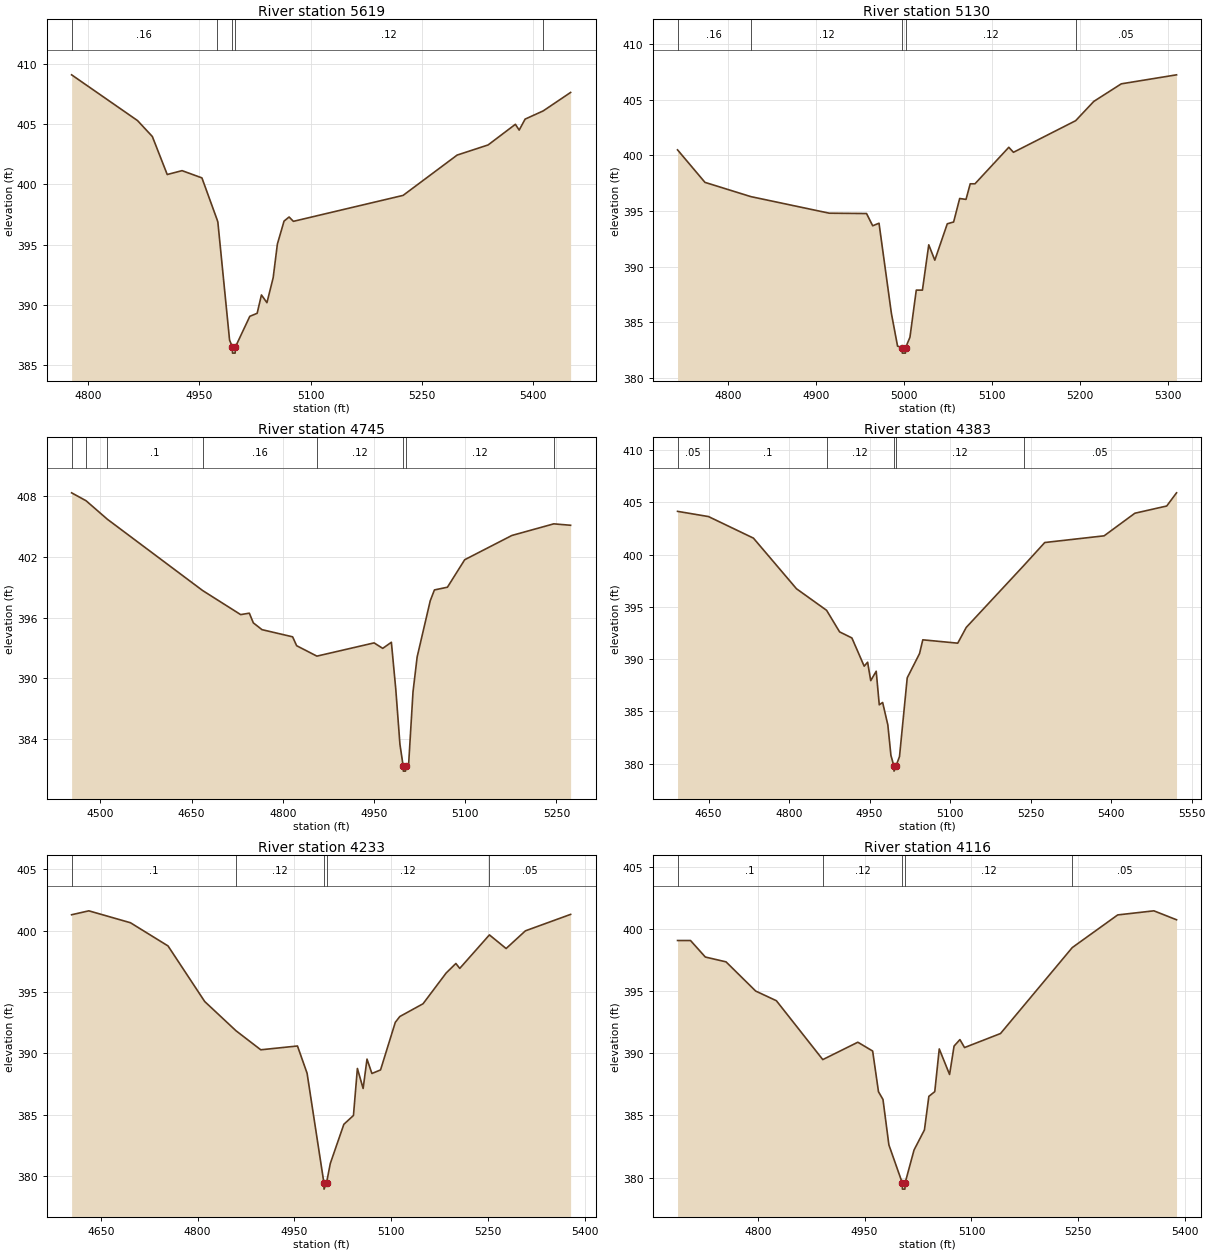
Type RM Length L Ch R = 1 ,5619    ,489,489,489
BEGIN DESCRIPTION:
NORTH MINERAL CR TRIB 7 19 0
END DESCRIPTION:
XS GIS Cut Line= 4
      3510270.85     10398326.97      3510114.63     10398317.43
      3509872.44     10398458.05      3509642.42     10398513.61
#Sta/Elev= 30
  4777.6  409.08  4866.5  405.29  4886.5  403.97  4906.6  400.82  4926.6  401.14
  4953.4  400.54  4973.8  397.09  4974.9  396.88  4990.7   387.1  4994.5  386.52
  4994.7  386.02  4998.2  386.02  4998.5  386.52    5018  389.07  5027.9  389.32
  5033.7  390.84  5041.1   390.2  5049.5  392.26  5055.2  395.06  5064.2  396.96
    5071   397.3  5076.8  396.94  5224.8  399.09  5297.7  402.43  5339.5  403.27
  5376.3  404.98  5381.4   404.5  5389.4  405.41  5413.8  406.09  5450.8  407.62
#Mann= 5 ,-1 , 0
  4777.6     .16       0  4973.8     .12       0  4994.5     .07       0
  4998.5     .12       0  5413.8     .05       0
Bank Sta=4994.5,4998.5
XS Rating Curve= 0 ,0
Exp/Cntr=0.3,0.1

Type RM Length L Ch R = 1 ,5130    ,385,385,385
BEGIN DESCRIPTION:
NORTH MINERAL CR TRIB 7 9 0
END DESCRIPTION:
XS GIS Cut Line= 3
      3510147.61     10398160.31      3509915.84     10397919.86
      3509691.91     10397852.16
#Sta/Elev= 30
  4742.3  400.48  4773.5  397.56  4825.7  396.28    4915  394.79  4957.4  394.76
  4964.4  393.66  4971.6  393.89  4985.7  385.78  4992.7  382.85  4997.9  382.72
  4998.1  382.22  5001.6  382.22  5001.9  382.72  5006.8  383.65    5014  387.88
    5021  387.88  5028.2  391.95  5035.1  390.57  5049.3  393.84  5056.5     394
  5063.4  396.11  5070.6  396.03  5075.4  397.43  5080.8  397.43  5119.3  400.71
  5124.6  400.26  5195.4   403.1    5216  404.83  5247.3  406.41  5310.2  407.22
#Mann= 5 ,-1 , 0
  4742.3     .16       0  4825.7     .12       0  4997.9     .07       0
  5001.9     .12       0  5195.4     .05       0
Bank Sta=4997.9,5001.9
XS Rating Curve= 0 ,0
Exp/Cntr=0.3,0.1

Type RM Length L Ch R = 1 ,4745    ,362,362,362
BEGIN DESCRIPTION:
NORTH MINERAL CR TRIB 7 6 1
END DESCRIPTION:
XS GIS Cut Line= 3
      3510507.14     10398008.83      3510142.11     10397691.64
      3509896.54      10397460.7
#Sta/Elev= 30
  4452.6  408.35  4476.3  407.57  4511.3  405.74  4668.1  398.68  4730.6   396.3
  4744.9  396.44  4751.5  395.48  4765.7  394.81  4816.1   394.1  4822.7  393.22
    4856  392.19  4950.1   393.5  4964.3  392.96  4978.5  393.56  4985.8  388.88
  4992.6  383.46  4997.9  381.31  4998.2  380.81  5001.7  380.81  5001.9  381.31
  5006.8  381.41  5014.1  388.66  5020.9  392.11  5042.4  397.66  5049.3  398.74
  5070.7  399.01  5099.1  401.73  5176.7  404.13  5245.6  405.28  5273.3  405.14
#Mann= 8 ,-1 , 0
  4452.6      .1       0  4476.3     .16       0  4511.3      .1       0
  4668.1     .16       0    4856     .12       0  4997.9     .07       0
  5001.9     .12       0  5245.6     .05       0
Bank Sta=4997.9,5001.9
XS Rating Curve= 0 ,0
Exp/Cntr=0.3,0.1

Type RM Length L Ch R = 1 ,4383    ,150,150,150
BEGIN DESCRIPTION:
NORTH MINERAL CR TRIB 7 7 0
END DESCRIPTION:
XS GIS Cut Line= 2
       3510745.5     10397659.98      3509934.36     10397205.88
#Sta/Elev= 30
  4592.3  404.13    4650  403.63  4733.7  401.57  4813.9  396.73    4870  394.67
  4894.2  392.61  4917.1  392.03    4940  389.33  4946.4  389.71  4952.2  387.95
  4962.4  388.85  4968.1  385.64  4974.4  385.86  4984.1  383.71  4989.8  380.81
  4995.3   379.8  4995.6   379.3  4999.3   379.8  5005.8  380.69  5020.2  388.22
  5043.1  390.53  5049.2  391.85  5114.3  391.53  5130.2  393.04  5237.7  398.97
  5276.4  401.15    5387  401.79  5444.3  403.95  5503.6  404.64  5521.9   405.9
#Mann= 6 ,-1 , 0
  4592.3     .05       0    4650      .1       0    4870     .12       0
  4995.3     .07       0  4999.3     .12       0  5237.7     .05       0
Bank Sta=4995.3,4999.3
XS Rating Curve= 0 ,0
Exp/Cntr=0.3,0.1

Type RM Length L Ch R = 1 ,4233    ,117,117,117
BEGIN DESCRIPTION:
NORTH MINERAL CR TRIB 7 5 1
END DESCRIPTION:
XS GIS Cut Line= 2
      3510747.59     10397542.68      3510107.06     10397108.71
#Sta/Elev= 30
  4604.6   401.3  4631.3  401.62  4695.8  400.65  4754.1  398.76    4811  394.23
  4859.5  391.85  4897.9   390.3  4954.8  390.61  4969.7  388.39  4995.8  379.45
    4996  378.95  4999.8  379.45  5005.7  381.04  5026.7  384.23  5041.6  384.95
  5047.7  388.78  5056.6  387.15  5062.6  389.54  5070.2  388.37  5083.6  388.66
  5106.5  392.54  5113.5  393.01  5149.5  394.05  5185.4  396.56  5200.4  397.33
  5206.4  396.93  5252.4  399.66  5278.3  398.55  5308.2  399.99  5378.3  401.33
#Mann= 5 ,-1 , 0
  4604.6      .1       0  4859.5     .12       0  4995.8     .07       0
  4999.8     .12       0  5252.4     .05       0
Bank Sta=4995.8,4999.8
XS Rating Curve= 0 ,0
Exp/Cntr=0.3,0.1

Type RM Length L Ch R = 1 ,4116    ,104,104,104
BEGIN DESCRIPTION:
NORTH MINERAL CR TRIB 7 6 2
END DESCRIPTION:
XS GIS Cut Line= 3
      3510729.22     10397409.45      3510410.63     10397166.39
      3510163.22      10396997.1
#Sta/Elev= 30
  4687.4  399.09  4705.6  399.09  4726.4  397.76  4755.5  397.37  4797.1  395.02
  4826.2  394.24  4891.3   389.5  4940.5   390.9  4961.3  390.19  4969.5  386.91
  4975.8  386.29  4984.1  382.63  5002.9  379.57  5003.1  379.07  5006.6  379.07
  5006.9  379.57  5019.4  382.22    5034  383.84  5040.2  386.54  5048.5  386.92
  5054.8  390.36  5069.3   388.3  5075.6  390.59  5083.8  391.11  5090.3  390.47
  5140.8   391.6  5241.5  398.52  5305.3  401.15  5356.1  401.48  5387.9  400.76
#Mann= 5 ,-1 , 0
  4687.4      .1       0  4891.3     .12       0  5002.9     .07       0
  5006.9     .12       0  5241.5     .05       0
Bank Sta=5002.9,5006.9
XS Rating Curve= 0 ,0
Exp/Cntr=0.3,0.1

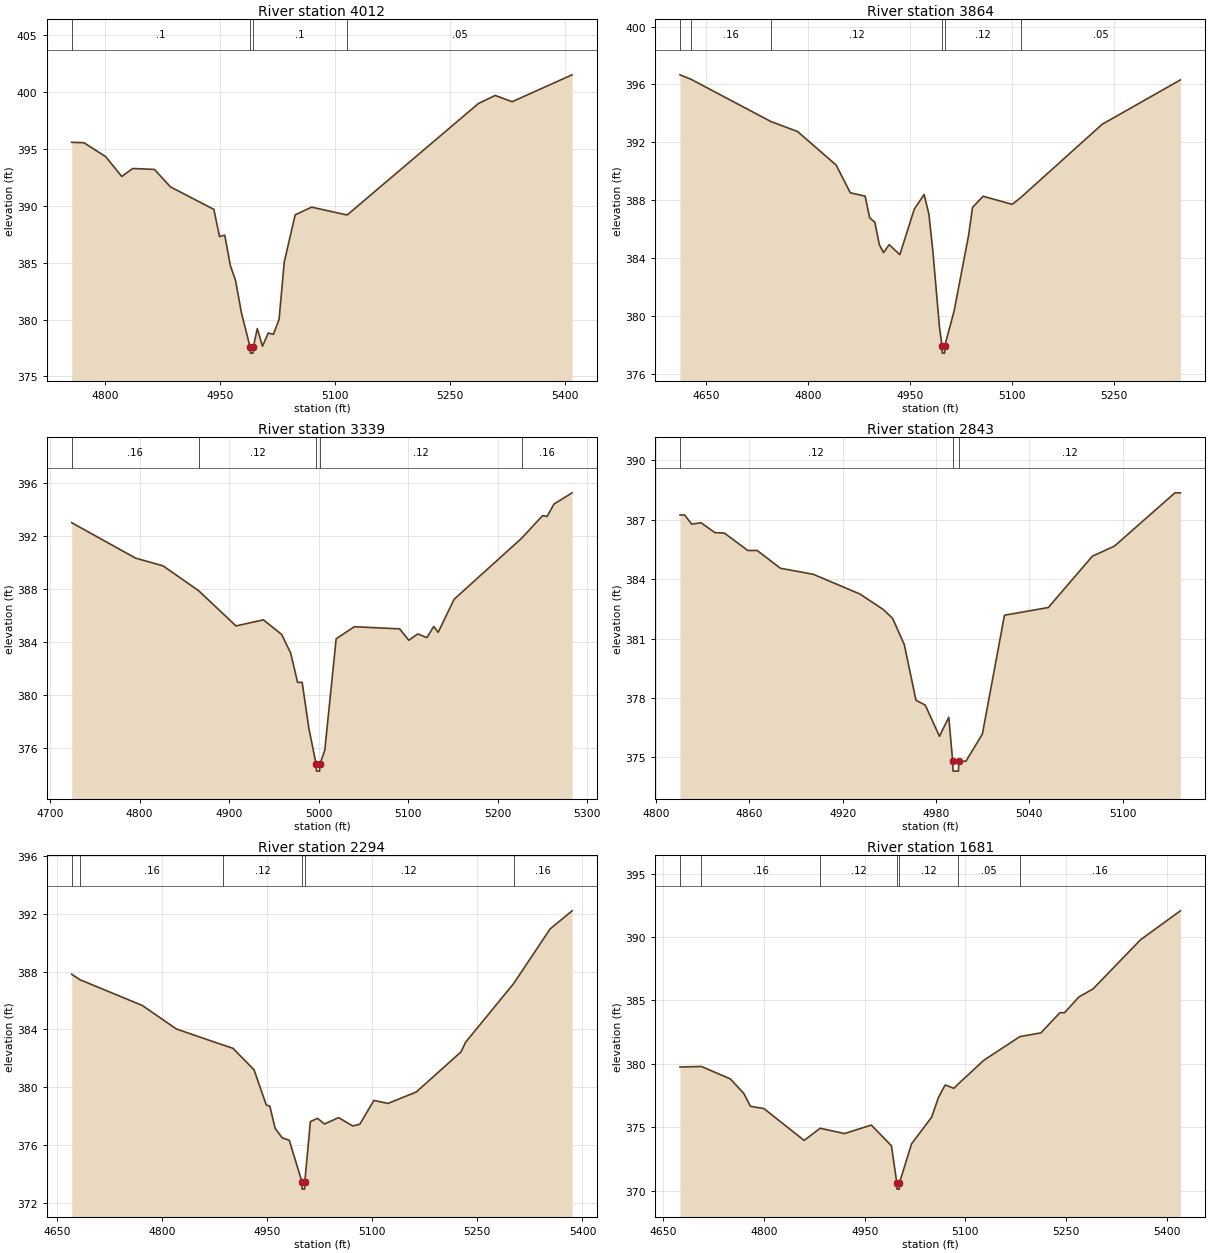
Type RM Length L Ch R = 1 ,4012    ,148,148,148
BEGIN DESCRIPTION:
NORTH MINERAL CR TRIB 7 6 0
END DESCRIPTION:
XS GIS Cut Line= 3
      3510744.84     10397331.32      3510443.62     10397053.54
      3510228.36     10396939.83
#Sta/Elev= 30
  4756.1  395.55  4772.2  395.51  4800.5  394.29  4821.5  392.55  4835.7  393.25
  4864.1  393.17    4885  391.64  4941.7  389.66  4949.1  387.28  4955.9   387.4
  4963.3  384.71  4970.1  383.41  4977.5  380.64  4989.1  377.55  4989.3  377.05
  4992.8  377.05  4993.1  377.55  4998.4   379.2  5005.2  377.65  5012.6  378.81
  5019.4   378.7  5026.8     380  5033.6  385.05  5047.8  389.18  5069.3  389.86
  5115.7  389.17    5287  398.95    5309  399.66    5331  399.11  5409.3  401.47
#Mann= 4 ,-1 , 0
  4756.1      .1       0  4989.1     .07       0  4993.1      .1       0
  5115.7     .05       0
Bank Sta=4989.1,4993.1
XS Rating Curve= 0 ,0
Exp/Cntr=0.3,0.1

Type RM Length L Ch R = 1 ,3864    ,525,525,525
BEGIN DESCRIPTION:
NORTH MINERAL CR TRIB 7 4 1
END DESCRIPTION:
XS GIS Cut Line= 3
      3510920.33     10397317.86      3510718.92     10397088.67
      3510347.43     10396868.21
#Sta/Elev= 30
  4611.1  396.66    4627  396.36    4745  393.43  4784.2  392.74  4841.1  390.42
    4862   388.5  4883.8  388.27  4890.5  386.77  4898.1  386.47  4904.7  384.92
  4910.9  384.36  4919.3  384.91  4934.9  384.22  4956.3  387.38  4970.7  388.38
  4977.7  387.03  4983.5  384.51  4993.3  379.21  4997.1  377.91  4997.4  377.41
  5000.9  377.41  5001.1  377.91  5014.8  380.31  5036.2  385.55    5042  387.49
  5057.6  388.26  5100.5   387.7  5112.8  388.16    5233  393.24  5348.2  396.31
#Mann= 6 ,-1 , 0
  4611.1      .1       0    4627     .16       0    4745     .12       0
  4997.1     .07       0  5001.1     .12       0  5112.8     .05       0
Bank Sta=4997.1,5001.1
XS Rating Curve= 0 ,0
Exp/Cntr=0.3,0.1

Type RM Length L Ch R = 1 ,3339    ,496,496,496
BEGIN DESCRIPTION:
NORTH MINERAL CR TRIB 7 3 1
END DESCRIPTION:
XS GIS Cut Line= 3
      3510942.11     10397191.64      3510992.11     10396941.64
      3511042.11     10396641.63
#Sta/Elev= 30
  4724.2     393  4795.6  390.33  4826.2  389.75    4866  387.88  4907.8  385.22
  4938.4  385.68  4958.8  384.58  4968.9  383.17  4976.6  380.97  4981.7  380.97
  4989.3  377.47  4997.4  374.78  4997.7  374.28  5001.2  374.28  5001.4  374.78
    5007  375.86  5019.7  384.25    5040  385.16  5090.7     385  5100.8  384.14
  5110.9  384.62  5121.1  384.34  5128.7  385.18  5133.7  384.74  5151.5  387.23
  5226.8  391.82  5250.3  393.53  5255.4  393.47    5263   394.4  5283.3  395.25
#Mann= 5 ,-1 , 0
  4724.2     .16       0    4866     .12       0  4997.4     .07       0
  5001.4     .12       0  5226.8     .16       0
Bank Sta=4997.4,5001.4
XS Rating Curve= 0 ,0
Exp/Cntr=0.3,0.1

Type RM Length L Ch R = 1 ,2843    ,549,549,549
BEGIN DESCRIPTION:
NORTH MINERAL CR TRIB 7 2 1
END DESCRIPTION:
XS GIS Cut Line= 3
       3511442.1     10396941.64      3511342.11     10396791.64
       3511242.1     10396691.64
#Sta/Elev= 30
  4815.4  387.24  4818.4  387.24  4822.9  386.78  4828.9  386.85  4837.9  386.35
  4843.9  386.33    4859  385.45    4865  385.45    4880  384.55    4901  384.25
  4931.1  383.25  4946.1  382.47  4952.1  382.02  4959.6   380.7  4967.1  377.89
  4973.1  377.64  4982.2  376.07  4988.2  377.03  4990.7  374.81  4990.9  374.31
  4994.4  374.31  4994.7  374.81  4999.2  374.81  5009.8  376.18    5024  382.18
  5052.2  382.57  5080.5  385.16  5094.7  385.67  5133.6  388.36  5137.1  388.36
#Mann= 3 ,-1 , 0
  4815.4     .12       0  4990.7     .07       0  4994.7     .12       0
Bank Sta=4990.7,4994.7
XS Rating Curve= 0 ,0
Exp/Cntr=0.3,0.1

Type RM Length L Ch R = 1 ,2294    ,613,613,613
BEGIN DESCRIPTION:
NORTH MINERAL CR TRIB 7 10 0
END DESCRIPTION:
XS GIS Cut Line= 2
       3512040.7     10396547.29      3511330.99     10396469.16
#Sta/Elev= 30
  4671.2  387.81  4683.1  387.43    4772  385.65  4820.7  384.02  4886.8  382.92
  4901.2  382.69  4931.4   381.2  4948.9  378.76  4953.9  378.68  4961.5  377.15
  4971.6  376.49  4981.7  376.32  4999.8  373.44    5000  372.94  5003.5  372.94
  5003.8  373.44  5011.8  377.61  5021.9  377.84    5032  377.45  5052.1  377.89
  5072.2  377.31  5082.3  377.43  5102.4  379.08  5122.5  378.87  5162.8  379.66
  5226.8  382.44  5233.2   383.1    5302  387.18  5353.9  390.95  5385.2   392.2
#Mann= 6 ,-1 , 0
  4671.2     .05       0  4683.1     .16       0  4886.8     .12       0
  4999.8     .07       0  5003.8     .12       0    5302     .16       0
Bank Sta=4999.8,5003.8
XS Rating Curve= 0 ,0
Exp/Cntr=0.3,0.1

Type RM Length L Ch R = 1 ,1681    ,505,505,505
BEGIN DESCRIPTION:
NORTH MINERAL CR TRIB 7 5 0
END DESCRIPTION:
XS GIS Cut Line= 3
      3511867.14     10396066.64      3511459.08     10396065.51
      3511225.94     10396309.45
#Sta/Elev= 30
  4674.8  379.75  4706.7  379.79  4749.8  378.81  4769.8  377.67  4779.8  376.65
  4799.8  376.47  4859.8  373.96  4883.6  374.92  4919.8   374.5  4959.8  375.17
  4989.8  373.54  4997.8  370.62  4998.1  370.12  5001.6  370.12  5001.8  370.62
  5019.8  373.69  5049.8   375.8  5059.8  377.34  5069.8  378.33  5082.9  378.07
  5088.9  378.39  5127.5  380.28    5181  382.14  5212.5  382.44  5240.8  384.03
  5247.7  384.03  5269.1  385.27  5290.1   385.9  5360.9  389.78  5420.3  392.06
#Mann= 7 ,-1 , 0
  4674.8     .05       0  4706.7     .16       0  4883.6     .12       0
  4997.8     .07       0  5001.8     .12       0  5088.9     .05       0
    5181     .16       0
Bank Sta=4997.8,5001.8
XS Rating Curve= 0 ,0
Exp/Cntr=0.3,0.1

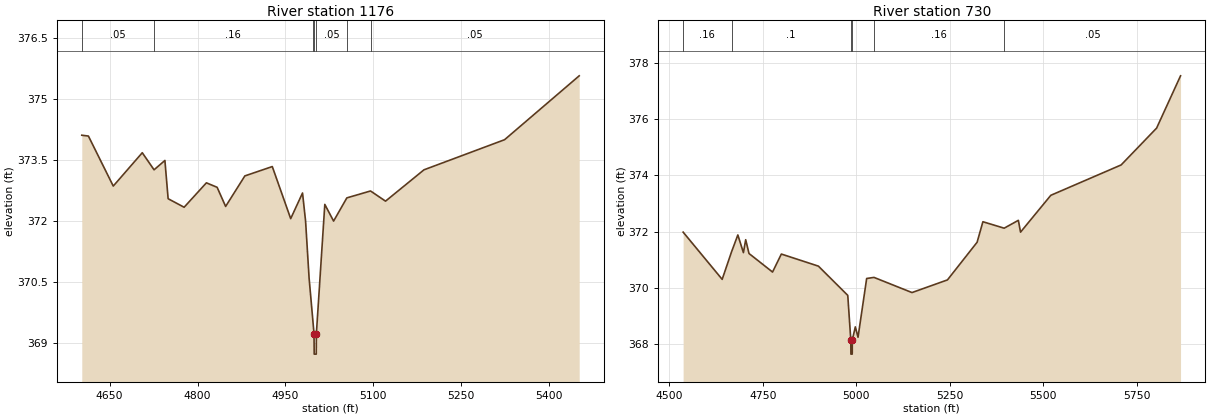
Type RM Length L Ch R = 1 ,1176    ,446,446,446
BEGIN DESCRIPTION:
NORTH MINERAL CR TRIB 7 4 0
END DESCRIPTION:
XS GIS Cut Line= 4
      3511914.79     10395834.89      3511834.94     10395755.04
      3511374.87     10395614.42      3511183.91     10395782.81
#Sta/Elev= 30
  4602.5   374.1  4613.8  374.08  4656.2  372.85  4705.7  373.67  4725.8  373.25
  4744.3  373.48  4749.8  372.54  4777.1  372.33  4815.1  372.93  4833.4  372.82
  4847.9  372.35  4880.7   373.1  4927.5  373.33  4958.9  372.05  4979.1  372.68
  4984.3  371.99  4990.3  370.59  4996.2  369.63  4998.7  369.22    4999  368.72
  5002.5  368.72  5002.7  369.22  5017.1   372.4  5032.1  371.99  5054.7  372.56
  5095.1  372.73  5120.7  372.48  5186.3  373.25  5323.8  373.99  5451.1  375.56
#Mann= 7 ,-1 , 0
  4602.5     .05       0  4725.8     .16       0  4996.2     .05       0
  4998.7     .03       0  5002.7     .05       0  5054.7      .1       0
  5095.1     .05       0
Bank Sta=4998.7,5002.7
XS Rating Curve= 0 ,0
Exp/Cntr=0.3,0.1

Type RM Length L Ch R = 1 ,730     ,0,0,0
BEGIN DESCRIPTION:
Mapping XS ec3c642d
END DESCRIPTION:
XS GIS Cut Line= 4
      3512018.95     10395618.44      3511808.47     10395310.31
       3511580.6     10395277.75      3511201.39      10395897.5
#Sta/Elev= 30
  4536.8  371.98  4641.2   370.3  4666.3  371.28  4683.1  371.88    4698  371.25
  4704.1  371.71  4712.9  371.22  4775.9  370.56  4799.4   371.2  4898.5  370.77
    4977  369.73  4985.1  368.14  4985.4  367.64  4988.9  367.64  4989.1  368.14
  4997.2  368.61  5004.4  368.24  5027.5  370.33    5047  370.37  5148.7  369.83
  5243.5  370.28  5322.8  371.62  5338.3  372.35  5395.1  372.12  5433.1   372.4
  5438.9  371.98  5519.9  373.29  5707.9  374.37  5802.7  375.68  5866.7  377.54
#Mann= 6 ,-1 , 0
  4536.8     .16       0  4666.3      .1       0  4985.1     .07       0
  4989.1      .1       0    5047     .16       0  5395.1     .05       0
Bank Sta=4985.1,4989.1
XS Rating Curve= 0 ,0
Exp/Cntr=0.3,0.1

Chan Stop Cuts=-1
Use User Specified Reach Order=0
Composite Channel Slope=5