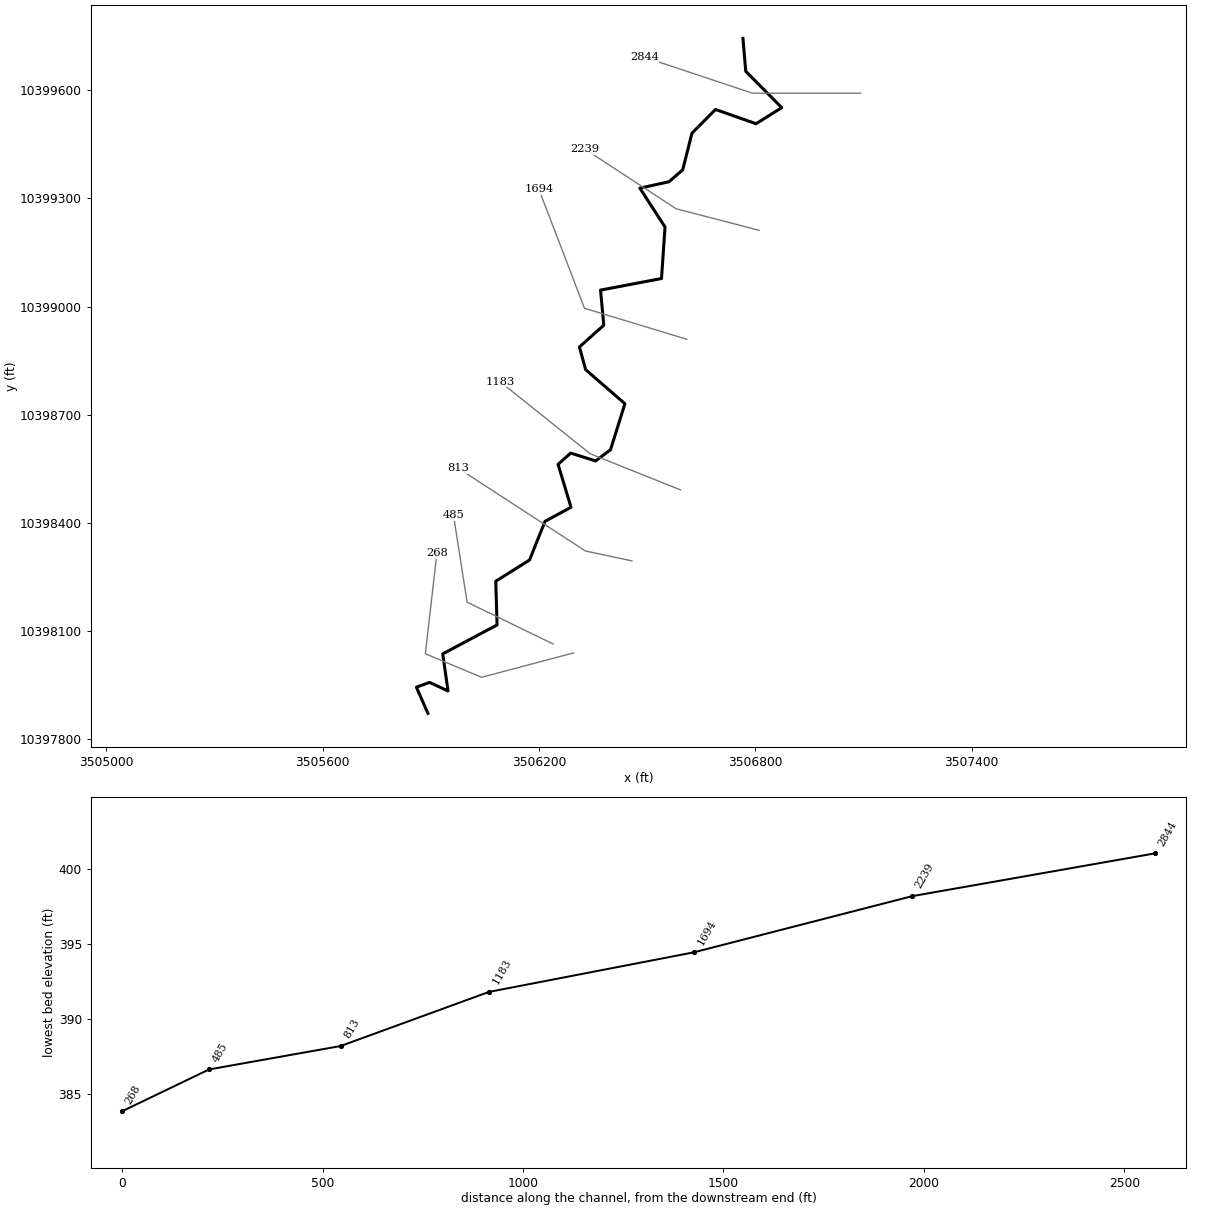
--- NORTH MINERAL CR TRIB 8 1 2.prj (project) ---

Proj Title=NORTH MINERAL CR TRIB 8 1 2 Base Level Engineering
Current Plan=p01
Default Exp/Contr=0.3,0.1
English Units
Geom File=g01
Flow File=f01
Plan File=p01
BEGIN DESCRIPTION:
NORTH MINERAL CR TRIB 8 1 2
END DESCRIPTION:

--- NORTH MINERAL CR TRIB 8 1 2.p01 (plan) ---

Plan Title=Multiple Run
Short Identifier=Multiple
Geom File=g01
Flow File=f01
Subcritical Flow
K Sum by GR= 0
Std Step Tol= 0.01
Critical Tol= 0.01
Num of Std Step Trials= 20
Max Error Tol= 0.3
Flow Tol Ratio= 0.001
Split Flow NTrial= 30
Split Flow Tol= 0.02
Split Flow Ratio= 0.02
Log Output Level= 0
Friction Slope Method= 1
Unsteady Friction Slope Method= 2
Unsteady Bridges Friction Slope Method= 1
Parabolic Critical Depth
Global Vel Dist=  1 , 1 , 1
Global Log Level= 0
CheckData=True
Encroach Param= -1, 0, 0, 0
BEGIN DESCRIPTION:
Multiple Run
END DESCRIPTION:

--- NORTH MINERAL CR TRIB 8 1 2.f01 (steady flow) ---

Flow Title=Multiple
Number of Profiles=7
Profile Names=10-year,25-year,50-year,1pct_min,100-year,1pct_plu,500-year
River Rch & RM= NORTH MINERAL CR,Reach-1,2844
     455     599     712     620     839    1134    1159
Boundary for River Rch & Prof#=NORTH MINERAL CR,Reach-1,1
Up Type=0
Dn Type=3
Dn Slope=0.005
Boundary for River Rch & Prof#=NORTH MINERAL CR,Reach-1,2
Up Type=0
Dn Type=3
Dn Slope=0.005
Boundary for River Rch & Prof#=NORTH MINERAL CR,Reach-1,3
Up Type=0
Dn Type=3
Dn Slope=0.005
Boundary for River Rch & Prof#=NORTH MINERAL CR,Reach-1,4
Up Type=0
Dn Type=3
Dn Slope=0.005
Boundary for River Rch & Prof#=NORTH MINERAL CR,Reach-1,5
Up Type=0
Dn Type=3
Dn Slope=0.005
Boundary for River Rch & Prof#=NORTH MINERAL CR,Reach-1,6
Up Type=0
Dn Type=3
Dn Slope=0.005
Boundary for River Rch & Prof#=NORTH MINERAL CR,Reach-1,7
Up Type=0
Dn Type=3
Dn Slope=0.005

--- NORTH MINERAL CR TRIB 8 1 2.g01 (geometry) ---

Geom Title=Existing Conditions

River Reach=NORTH MINERAL CR,Reach-1
Reach XY= 30
      3506765.75     10399743.79      3506773.58     10399652.43
      3506873.33     10399551.56      3506802.15     10399506.96
      3506689.71     10399546.52      3506624.38     10399480.67
      3506598.66     10399378.99      3506560.65     10399345.98
      3506479.93     10399328.38      3506549.67     10399220.49
      3506539.89     10399077.63      3506370.85     10399045.54
      3506379.88     10398948.16      3506312.22     10398887.83
      3506329.55     10398824.91      3506438.48     10398730.41
      3506398.44     10398602.67      3506357.04     10398571.79
      3506288.12     10398593.53      3506253.03     10398562.30
      3506288.96     10398443.17      3506216.90     10398404.31
      3506173.92     10398296.97      3506080.23     10398238.11
      3506083.85     10398116.86      3505933.20     10398036.65
      3505947.87     10397933.79      3505896.61     10397957.57
      3505860.06     10397944.29      3505892.11     10397871.64

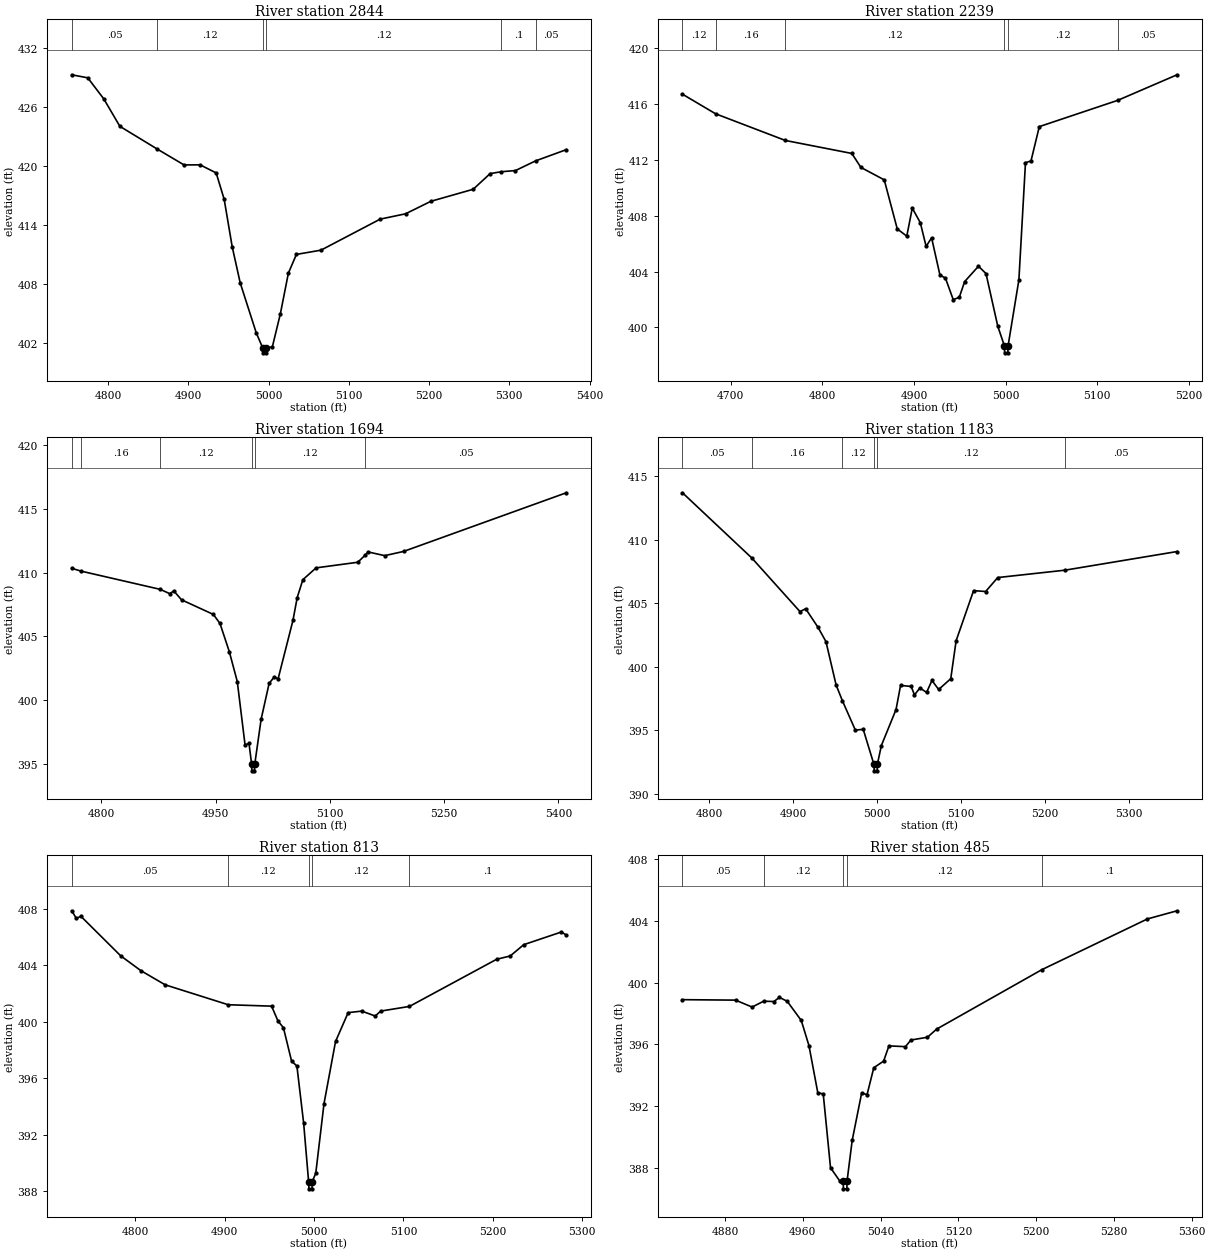
Type RM Length L Ch R = 1,2844,605,605,605
BEGIN DESCRIPTION:
NORTH MINERAL CR TRIB 8 1 2 31 0
END DESCRIPTION:
XS GIS Cut Line= 3
      3507092.15     10399591.64      3506792.11     10399591.64
      3506492.08     10399691.65
#Sta/Elev= 30
  4754.7  429.25  4774.7  428.94  4794.7  426.80  4814.7  424.02  4861.3  421.71
  4894.7  420.10  4914.7  420.11  4934.7  419.29  4944.7  416.61  4954.7  411.79
  4964.7  408.12  4984.7  403.05  4992.7  401.53  4993.0  401.03  4996.5  401.03
  4996.7  401.53  5004.7  401.63  5014.7  404.99  5024.7  409.12  5034.7  411.02
  5065.3  411.45  5139.1  414.60  5170.7  415.14  5202.3  416.41  5255.0  417.63
  5276.1  419.22  5290.0  419.41  5307.7  419.53  5332.7  420.51  5371.0  421.65
#Mann=6,-1,0
  4754.7    0.05       0  4861.3    0.12       0  4992.7    0.07       0
  4996.7    0.12       0  5290.0     0.1       0  5332.7    0.05       0
Bank Sta=4992.7,4996.7
Exp/Cntr=0.3,0.1

Type RM Length L Ch R = 1,2239,545,545,545
BEGIN DESCRIPTION:
NORTH MINERAL CR TRIB 8 1 2 30 0
END DESCRIPTION:
XS GIS Cut Line= 3
      3506810.65     10399211.33      3506580.22     10399271.22
      3506327.62     10399436.58
#Sta/Elev= 30
  4647.2  416.69  4683.3  415.29  4759.5  413.38  4832.1  412.45  4842.0  411.45
  4867.5  410.56  4881.7  407.05  4892.1  406.53  4898.1  408.54  4906.9  407.49
  4913.2  405.80  4919.2  406.41  4928.3  403.75  4934.3  403.53  4942.8  401.99
  4949.4  402.15  4955.3  403.28  4970.4  404.38  4978.6  403.85  4991.5  400.07
  4998.7  398.68  4998.9  398.18  5002.4  398.18  5002.7  398.68  5014.5  403.40
  5021.7  411.79  5027.7  411.91  5036.8  414.37  5122.4  416.25  5187.2  418.08
#Mann=6,-1,0
  4647.2    0.12       0  4683.3    0.16       0  4759.5    0.12       0
  4998.7    0.07       0  5002.7    0.12       0  5122.4    0.05       0
Bank Sta=4998.7,5002.7
Exp/Cntr=0.3,0.1

Type RM Length L Ch R = 1,1694,511,511,511
BEGIN DESCRIPTION:
NORTH MINERAL CR TRIB 8 1 2 50
END DESCRIPTION:
XS GIS Cut Line= 3
      3506610.14     10398909.25      3506326.32     10398995.18
      3506200.00     10399324.64
#Sta/Elev= 30
  4761.0  410.35  4772.8  410.13  4877.3  408.69  4889.8  408.35  4895.0  408.57
  4905.2  407.87  4947.0  406.72  4955.7  406.01  4967.9  403.80  4978.4  401.45
  4988.6  396.47  4993.8  396.58  4997.3  394.93  4997.5  394.43  5001.0  394.43
  5001.3  394.93  5009.7  398.48  5020.2  401.30  5026.7  401.79  5032.0  401.66
  5051.5  406.25  5057.1  408.05  5064.5  409.45  5081.9  410.38  5136.6  410.82
  5146.7  411.40  5150.2  411.63  5172.0  411.34  5196.7  411.67  5410.4  416.28
#Mann=6,-1,0
  4761.0    0.05       0  4772.8    0.16       0  4877.3    0.12       0
  4997.3    0.07       0  5001.3    0.12       0  5146.7    0.05       0
Bank Sta=4997.3,5001.3
Exp/Cntr=0.3,0.1

Type RM Length L Ch R = 1,1183,370,370,370
BEGIN DESCRIPTION:
NORTH MINERAL CR TRIB 8 1 2 40
END DESCRIPTION:
XS GIS Cut Line= 3
      3506592.13     10398491.63      3506342.11     10398591.64
      3506092.13     10398791.62
#Sta/Elev= 30
  4767.8  413.70  4850.3  408.57  4907.8  404.34  4914.6  404.56  4929.4  403.09
  4938.8  401.97  4950.9  398.55  4958.4  397.31  4973.8  395.00  4983.2  395.06
  4996.0  392.29  4996.3  391.79  4999.8  391.79  5000.0  392.29  5004.8  393.78
  5022.3  396.62  5027.7  398.52  5040.3  398.44  5044.3  397.77  5050.7  398.32
  5058.7  397.97  5065.1  398.91  5073.1  398.20  5087.5  399.05  5093.9  402.04
  5114.7  405.99  5129.1  405.92  5143.5  407.02  5223.5  407.60  5357.2  409.07
#Mann=6,-1,0
  4767.8    0.05       0  4850.3    0.16       0  4958.4    0.12       0
  4996.0    0.07       0  5000.0    0.12       0  5223.5    0.05       0
Bank Sta=4996,5000
Exp/Cntr=0.3,0.1

Type RM Length L Ch R = 1,813,328,328,328
BEGIN DESCRIPTION:
Mapping XS bad7798b
END DESCRIPTION:
XS GIS Cut Line= 3
      3506457.86     10398294.65      3506328.92     10398322.00
      3505975.90     10398551.73
#Sta/Elev= 30
  4729.1  407.86  4734.3  407.32  4739.4  407.47  4783.9  404.67  4806.5  403.62
  4833.6  402.62  4904.1  401.21  4952.6  401.11  4959.8  400.05  4965.8  399.59
  4974.9  397.23  4980.9  396.87  4988.4  392.85  4994.0  388.68  4994.3  388.18
  4997.8  388.18  4998.0  388.68  5002.0  389.29  5011.2  394.21  5024.1  398.61
  5038.2  400.65  5053.4  400.76  5068.5  400.41  5074.5  400.76  5106.7  401.09
  5204.3  404.43  5219.4  404.66  5234.5  405.46  5276.7  406.36  5282.1  406.14
#Mann=5,-1,0
  4729.1    0.05       0  4904.1    0.12       0  4994.0    0.07       0
  4998.0    0.12       0  5106.7     0.1       0
Bank Sta=4994,4998
Exp/Cntr=0.3,0.1

Type RM Length L Ch R = 1,485,217,217,217
BEGIN DESCRIPTION:
Mapping XS fd6cf601
END DESCRIPTION:
XS GIS Cut Line= 3
      3506239.08     10398064.19      3506000.80     10398180.07
      3505963.03     10398420.96
#Sta/Elev= 30
  4836.2  398.90  4890.8  398.87  4907.8  398.42  4919.7  398.80  4930.3  398.78
  4935.9  399.05  4944.0  398.79  4958.4  397.55  4966.3  395.92  4975.4  392.86
  4981.0  392.78  4988.5  387.99  4998.0  387.13  5001.5  387.12  5001.8  386.62
  5005.3  386.62  5005.5  387.12  5010.8  389.77  5020.5  392.83  5026.1  392.74
  5033.0  394.48  5043.1  394.91  5048.6  395.90  5065.6  395.85  5071.2  396.28
  5088.2  396.46  5097.7  396.99  5206.0  400.85  5314.5  404.14  5345.0  404.67
#Mann=5,-1,0
  4836.2    0.05       0  4919.7    0.12       0  5001.5    0.07       0
  5005.5    0.12       0  5206.0     0.1       0
Bank Sta=5001.5,5005.5
Exp/Cntr=0.3,0.1

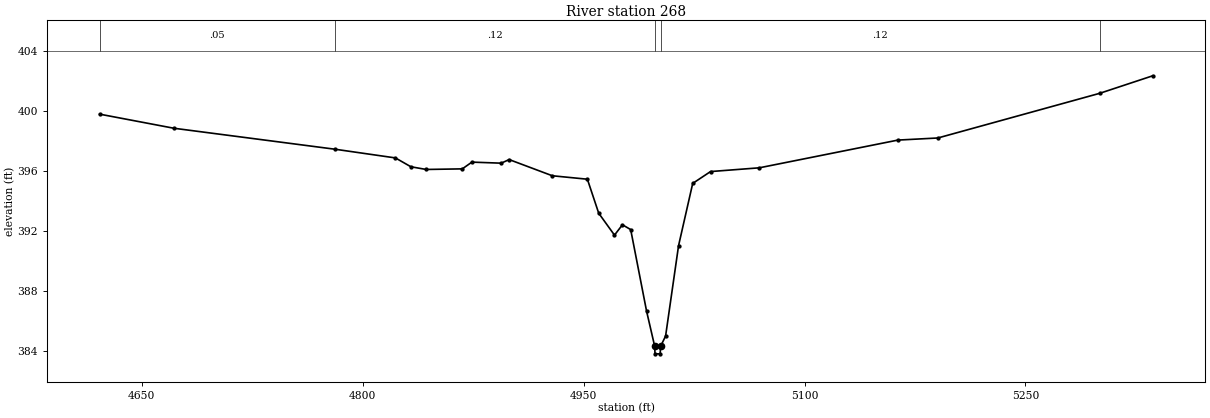
Type RM Length L Ch R = 1,268,0,0,0
BEGIN DESCRIPTION:
NORTH MINERAL CR TRIB 8 1 2 1 0
END DESCRIPTION:
XS GIS Cut Line= 4
      3506296.35     10398039.44      3506041.16     10397971.74
      3505884.91     10398036.84      3505917.10     10398316.61
#Sta/Elev= 30
  4621.5  399.82  4671.9  398.88  4781.3  397.48  4822.3  396.90  4832.8  396.31
  4843.2  396.13  4867.7  396.17  4874.2  396.62  4894.1  396.55  4899.5  396.79
  4928.8  395.71  4952.6  395.48  4960.3  393.21  4971.0  391.75  4976.4  392.44
  4982.0  392.12  4992.8  386.67  4998.3  384.33  4998.5  383.83  5002.0  383.83
  5002.3  384.33  5005.7  385.02  5014.5  391.05  5024.1  395.20  5036.2  395.99
  5069.3  396.24  5163.4  398.09  5190.5  398.23  5300.4  401.21  5336.4  402.38
#Mann=5,-1,0
  4621.5    0.05       0  4781.3    0.12       0  4998.3    0.07       0
  5002.3    0.12       0  5300.4     0.1       0
Bank Sta=4998.3,5002.3
Exp/Cntr=0.3,0.1

Chan Stop Cuts=-1