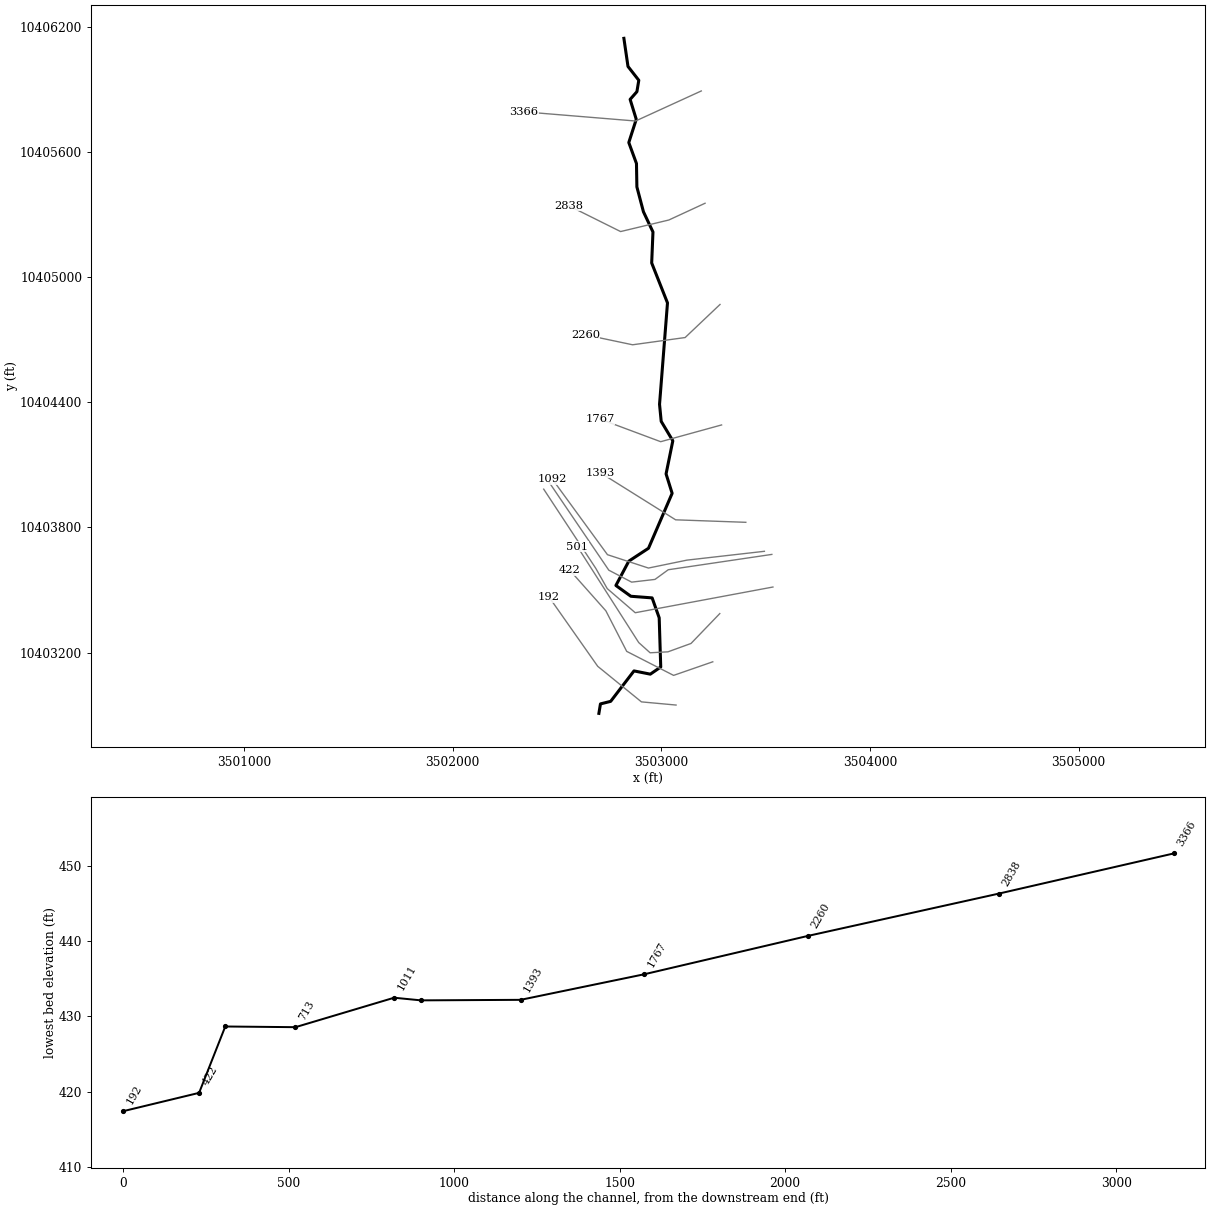
--- NORTH MINERAL CR TRIB 8 1 3.prj (project) ---

Proj Title=NORTH MINERAL CR TRIB 8 1 3 Base Level Engineering
Current Plan=p01
Default Exp/Contr=0.3,0.1
English Units
Geom File=g01
Flow File=f01
Plan File=p01
BEGIN DESCRIPTION:
NORTH MINERAL CR TRIB 8 1 3
END DESCRIPTION:

--- NORTH MINERAL CR TRIB 8 1 3.p01 (plan) ---

Plan Title=Multiple Run
Short Identifier=Multiple
Geom File=g01
Flow File=f01
Subcritical Flow
K Sum by GR= 0
Std Step Tol= 0.01
Critical Tol= 0.01
Num of Std Step Trials= 20
Max Error Tol= 0.3
Flow Tol Ratio= 0.001
Split Flow NTrial= 30
Split Flow Tol= 0.02
Split Flow Ratio= 0.02
Log Output Level= 0
Friction Slope Method= 1
Unsteady Friction Slope Method= 2
Unsteady Bridges Friction Slope Method= 1
Parabolic Critical Depth
Global Vel Dist=  1 , 1 , 1
Global Log Level= 0
CheckData=True
Encroach Param= -1, 0, 0, 0
BEGIN DESCRIPTION:
Multiple Run
END DESCRIPTION:

--- NORTH MINERAL CR TRIB 8 1 3.f01 (steady flow) ---

Flow Title=Multiple
Number of Profiles=7
Profile Names=10-year,25-year,50-year,1pct_min,100-year,1pct_plu,500-year
River Rch & RM= NORTH MINERAL CR,Reach-1,3366
     353     456     536     462     625     846     846
Boundary for River Rch & Prof#=NORTH MINERAL CR,Reach-1,1
Up Type=0
Dn Type=3
Dn Slope=0.005
Boundary for River Rch & Prof#=NORTH MINERAL CR,Reach-1,2
Up Type=0
Dn Type=3
Dn Slope=0.005
Boundary for River Rch & Prof#=NORTH MINERAL CR,Reach-1,3
Up Type=0
Dn Type=3
Dn Slope=0.005
Boundary for River Rch & Prof#=NORTH MINERAL CR,Reach-1,4
Up Type=0
Dn Type=3
Dn Slope=0.005
Boundary for River Rch & Prof#=NORTH MINERAL CR,Reach-1,5
Up Type=0
Dn Type=3
Dn Slope=0.005
Boundary for River Rch & Prof#=NORTH MINERAL CR,Reach-1,6
Up Type=0
Dn Type=3
Dn Slope=0.005
Boundary for River Rch & Prof#=NORTH MINERAL CR,Reach-1,7
Up Type=0
Dn Type=3
Dn Slope=0.005

--- NORTH MINERAL CR TRIB 8 1 3.g01 (geometry) ---

Geom Title=Existing Conditions

River Reach=NORTH MINERAL CR,Reach-1
Reach XY= 30
      3502821.23     10406143.78      3502840.87     10406009.02
      3502892.64     10405942.74      3502883.62     10405888.23
      3502851.13     10405851.21      3502880.49     10405755.76
      3502844.73     10405644.48      3502881.53     10405543.78
      3502883.52     10405431.68      3502914.90     10405312.80
      3502960.55     10405215.90      3502954.43     10405067.32
      3503030.15     10404876.06      3502992.07     10404390.21
      3503000.02     10404308.46      3503055.71     10404215.30
      3503023.36     10404056.58      3503052.43     10403963.58
      3502939.18     10403700.36      3502844.78     10403638.51
      3502782.93     10403521.97      3502854.55     10403470.32
      3502956.54     10403462.51      3502990.40     10403367.03
      3502997.78     10403131.35      3502947.86     10403097.06
      3502869.65     10403112.60      3502757.93     10402966.77
      3502708.97     10402954.53      3502701.41     10402909.14

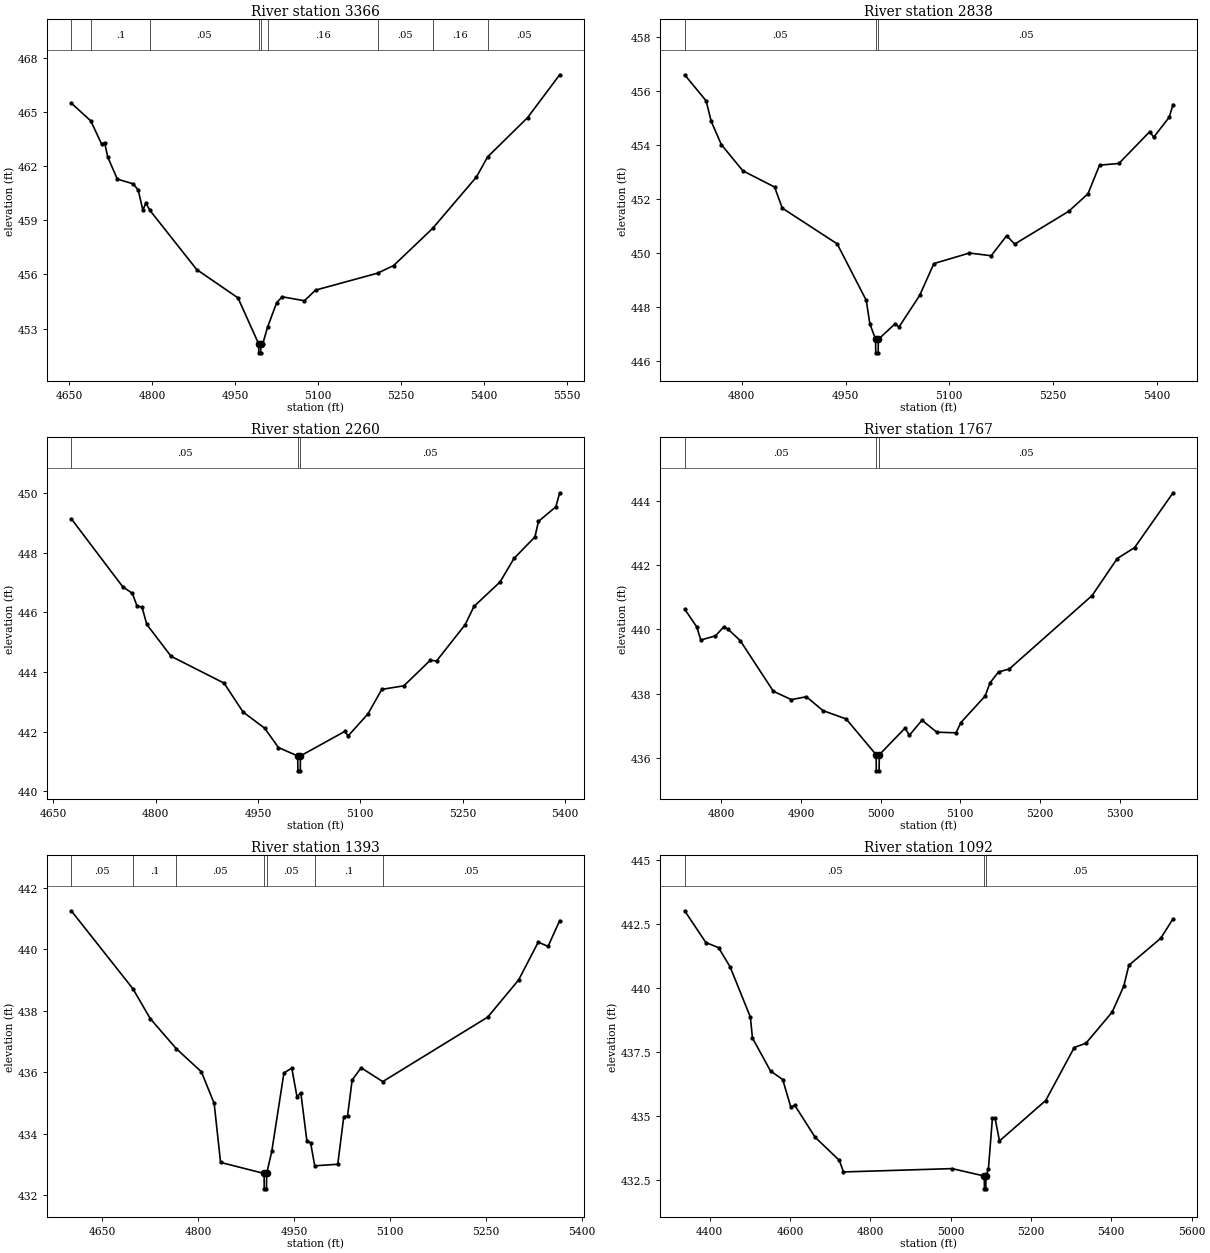
Type RM Length L Ch R = 1,3366,528,528,528
BEGIN DESCRIPTION:
NORTH MINERAL CR TRIB 8 1 3 21 0
END DESCRIPTION:
XS GIS Cut Line= 3
      3503192.11     10405891.65      3502877.19     10405747.60
      3502342.10     10405791.64
#Sta/Elev= 30
  4653.7  465.51  4689.0  464.52  4708.5  463.24  4714.0  463.31  4719.7  462.51
  4737.0  461.29  4765.5  461.03  4774.7  460.69  4783.1  459.57  4788.6  459.96
  4795.8  459.56  4880.6  456.27  4955.2  454.70  4992.5  452.15  4992.8  451.65
  4996.3  451.65  4996.5  452.15  5000.0  452.15  5008.6  453.07  5025.2  454.44
  5035.2  454.76  5075.3  454.54  5095.4  455.13  5207.5  456.07  5236.5  456.49
  5307.0  458.55  5386.4  461.41  5406.5  462.52  5478.8  464.70  5536.9  467.08
#Mann=9,-1,0
  4653.7    0.05       0  4689.0     0.1       0  4795.8    0.05       0
  4992.5    0.03       0  4996.5    0.05       0  5008.6    0.16       0
  5207.5    0.05       0  5307.0    0.16       0  5406.5    0.05       0
Bank Sta=4992.5,4996.5
Exp/Cntr=0.3,0.1

Type RM Length L Ch R = 1,2838,578,578,578
BEGIN DESCRIPTION:
NORTH MINERAL CR TRIB 8 1 3 20 0
END DESCRIPTION:
XS GIS Cut Line= 4
      3503210.24     10405353.55      3503036.60     10405273.24
      3502805.48     10405217.90      3502557.02     10405341.59
#Sta/Elev= 30
  4717.3  456.60  4748.3  455.64  4755.7  454.88  4770.3  454.02  4801.5  453.05
  4847.4  452.45  4858.5  451.67  4937.9  450.35  4980.0  448.26  4985.2  447.39
  4993.5  446.82  4993.7  446.32  4997.2  446.32  4997.5  446.82  5022.0  447.40
  5027.2  447.27  5057.2  448.44  5077.8  449.62  5129.2  450.01  5160.7  449.91
  5183.1  450.65  5194.7  450.34  5272.7  451.55  5300.7  452.20  5317.5  453.26
  5345.4  453.32  5390.2  454.50  5395.8  454.29  5418.2  455.03  5423.8  455.50
#Mann=3,-1,0
  4717.3    0.05       0  4993.5    0.03       0  4997.5    0.05       0
Bank Sta=4993.5,4997.5
Exp/Cntr=0.3,0.1

Type RM Length L Ch R = 1,2260,493,493,493
BEGIN DESCRIPTION:
NORTH MINERAL CR TRIB 8 1 3 60
END DESCRIPTION:
XS GIS Cut Line= 4
      3503281.82     10404868.50      3503114.73     10404710.09
      3502862.99     10404675.37      3502636.62     10404723.03
#Sta/Elev= 30
  4676.4  449.14  4751.8  446.86  4765.9  446.64  4772.8  446.21  4780.1  446.18
  4787.0  445.60  4822.6  444.53  4900.3  443.63  4928.2  442.66  4959.8  442.12
  4980.0  441.47  5008.2  441.19  5008.5  440.69  5012.0  440.69  5012.2  441.19
  5077.1  442.01  5082.1  441.86  5111.2  442.60  5131.4  443.42  5163.8  443.54
  5202.6  444.40  5211.6  444.37  5253.6  445.59  5266.5  446.20  5304.7  447.02
  5325.2  447.81  5355.8  448.53  5361.0  449.05  5386.5  449.54  5392.1  450.01
#Mann=3,-1,0
  4676.4    0.05       0  5008.2    0.03       0  5012.2    0.05       0
Bank Sta=5008.2,5012.2
Exp/Cntr=0.3,0.1

Type RM Length L Ch R = 1,1767,374,374,374
BEGIN DESCRIPTION:
NORTH MINERAL CR TRIB 8 1 3 31
END DESCRIPTION:
XS GIS Cut Line= 3
      3503289.41     10404291.25      3502997.54     10404210.96
      3502706.93     10404319.40
#Sta/Elev= 30
  4754.1  440.63  4769.2  440.08  4774.4  439.67  4792.8  439.80  4803.2  440.08
  4808.8  440.00  4823.9  439.65  4865.4  438.08  4888.0  437.82  4906.9  437.91
  4927.6  437.48  4956.8  437.22  4994.4  436.11  4994.6  435.61  4998.1  435.61
  4998.4  436.11  5030.8  436.94  5036.0  436.71  5051.9  437.18  5070.5  436.81
  5094.6  436.79  5100.8  437.11  5131.1  437.93  5137.3  438.34  5148.0  438.68
  5161.4  438.77  5265.4  441.05  5297.0  442.20  5318.8  442.54  5367.0  444.24
#Mann=3,-1,0
  4754.1    0.05       0  4994.4    0.03       0  4998.4    0.05       0
Bank Sta=4994.4,4998.4
Exp/Cntr=0.3,0.1

Type RM Length L Ch R = 1,1393,301,301,301
BEGIN DESCRIPTION:
NORTH MINERAL CR TRIB 8 1 3 22
END DESCRIPTION:
XS GIS Cut Line= 3
      3503405.51     10403824.68      3503069.16     10403836.61
      3502706.90     10404063.29
#Sta/Elev= 30
  4601.3  441.26  4697.8  438.72  4724.8  437.75  4765.6  436.77  4804.8  436.02
  4824.8  434.99  4834.8  433.07  4902.9  432.71  4903.1  432.21  4906.6  432.21
  4906.9  432.71  4914.9  433.43  4933.9  435.98  4946.2  436.14  4954.4  435.20
  4960.3  435.34  4969.8  433.77  4975.6  433.71  4982.1  432.96  5018.1  433.01
  5027.5  434.56  5033.4  434.58  5040.6  435.75  5054.6  436.15  5088.5  435.70
  5252.7  437.80  5301.0  439.01  5331.7  440.24  5347.0  440.10  5365.2  440.94
#Mann=7,-1,0
  4601.3    0.05       0  4697.8     0.1       0  4765.6    0.05       0
  4902.9    0.07       0  4906.9    0.05       0  4982.1     0.1       0
  5088.5    0.05       0
Bank Sta=4902.9,4906.9
Exp/Cntr=0.3,0.1

Type RM Length L Ch R = 1,1092,81,81,81
BEGIN DESCRIPTION:
NORTH MINERAL CR TRIB 8 1 3 50
END DESCRIPTION:
XS GIS Cut Line= 5
      3503494.53     10403685.79      3503123.41     10403643.47
      3502938.95     10403605.49      3502742.55     10403669.51
      3502478.89     10404030.82
#Sta/Elev= 30
  4338.0  443.00  4390.8  441.76  4422.4  441.56  4451.1  440.81  4501.5  438.85
  4506.8  438.03  4551.8  436.74  4582.0  436.41  4602.1  435.34  4612.2  435.40
  4662.5  434.16  4723.1  433.25  4733.3  432.80  5003.7  432.93  5083.9  432.64
  5084.1  432.14  5087.6  432.14  5087.9  432.64  5094.1  432.92  5104.0  434.89
  5110.8  434.89  5121.6  434.01  5236.7  435.59  5307.8  437.66  5337.1  437.83
  5402.0  439.04  5430.9  440.05  5443.7  440.87  5523.3  441.93  5553.7  442.69
#Mann=3,-1,0
  4338.0    0.05       0  5083.9   0.035       0  5087.9    0.05       0
Bank Sta=5083.9,5087.9
Exp/Cntr=0.3,0.1

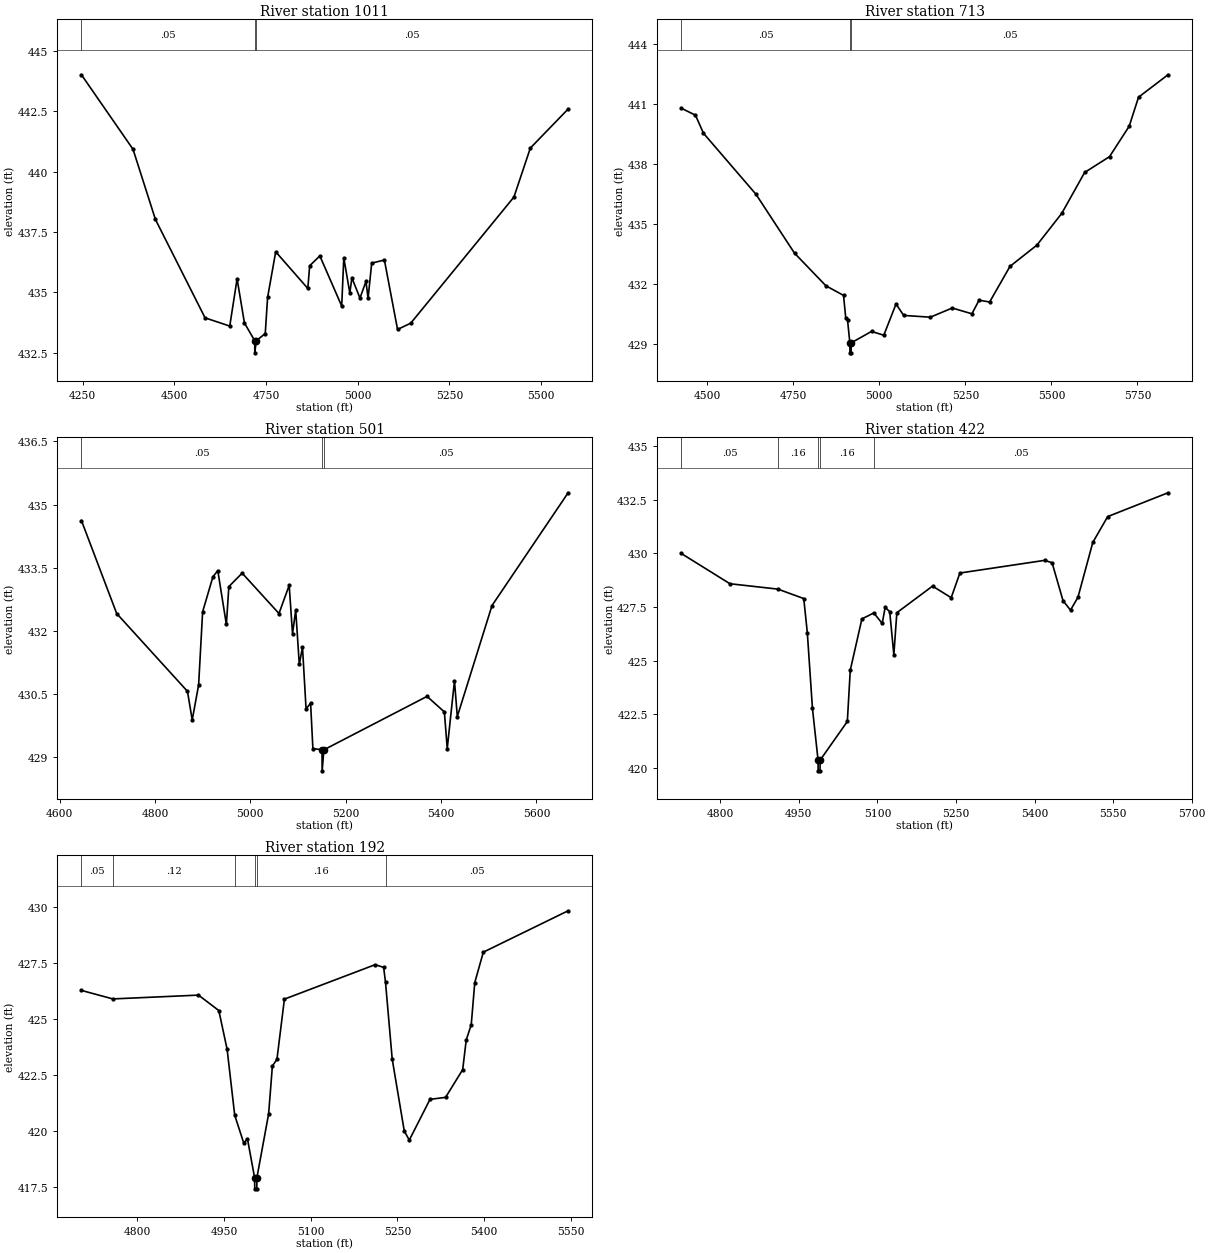
Type RM Length L Ch R = 1,1011,298,298,298
BEGIN DESCRIPTION:
NORTH MINERAL CR TRIB 8 1 3 32
END DESCRIPTION:
XS GIS Cut Line= 6
      3503530.20     10403670.86      3503033.77     10403597.37
      3502970.29     10403551.06      3502858.31     10403538.04
      3502748.93     10403595.33      3502462.68     10404016.91
#Sta/Elev= 30
  4246.7  444.02  4387.4  440.93  4448.5  438.02  4583.9  433.94  4651.2  433.60
  4671.2  435.56  4691.2  433.73  4719.3  432.99  4719.5  432.49  4723.3  432.99
  4748.0  433.29  4754.4  434.79  4776.5  436.68  4864.1  435.16  4869.1  436.10
  4896.9  436.51  4956.5  434.43  4962.2  436.43  4978.6  434.97  4984.3  435.60
  5006.3  434.76  5022.7  435.45  5028.4  434.75  5038.3  436.21  5072.9  436.34
  5108.8  433.46  5144.8  433.72  5426.2  438.95  5470.9  440.98  5574.0  442.60
#Mann=3,-1,0
  4246.7    0.05       0  4719.3   0.035       0  4723.3    0.05       0
Bank Sta=4719.3,4723.3
Exp/Cntr=0.3,0.1

Type RM Length L Ch R = 1,713,212,212,212
BEGIN DESCRIPTION:
NORTH MINERAL CR TRIB 8 1 3 30
END DESCRIPTION:
XS GIS Cut Line= 5
      3503535.42     10403514.61      3502875.64     10403391.42
      3502741.40     10403507.05      3502686.87     10403603.58
      3502437.01     10403983.57
#Sta/Elev= 30
  4424.6  440.80  4465.8  440.45  4489.0  439.55  4641.6  436.50  4753.5  433.56
  4844.7  431.93  4895.9  431.45  4902.4  430.32  4907.5  430.23  4914.3  429.08
  4914.5  428.58  4918.0  428.58  4918.3  429.08  4977.3  429.65  5012.9  429.46
  5048.5  431.02  5070.6  430.45  5148.2  430.36  5211.8  430.82  5268.9  430.53
  5289.7  431.21  5320.4  431.12  5379.6  432.90  5457.7  433.96  5530.1  435.55
  5596.4  437.59  5668.7  438.38  5725.9  439.90  5753.0  441.35  5838.6  442.47
#Mann=3,-1,0
  4424.6    0.05       0  4914.3   0.035       0  4918.3    0.05       0
Bank Sta=4914.3,4918.3
Exp/Cntr=0.3,0.1

Type RM Length L Ch R = 1,501,79,79,79
BEGIN DESCRIPTION:
NORTH MINERAL CR TRIB 8 1 3 23
END DESCRIPTION:
XS GIS Cut Line= 6
      3503280.72     10403387.36      3503142.94     10403244.16
      3503032.26     10403204.02      3502946.85     10403199.50
      3502892.29     10403248.50      3502598.86     10403707.59
#Sta/Elev= 30
  4645.9  434.62  4719.8  432.41  4868.2  430.56  4878.2  429.88  4891.6  430.71
  4900.0  432.45  4921.5  433.28  4931.8  433.43  4949.8  432.15  4955.0  433.05
  4982.9  433.37  5060.1  432.41  5081.5  433.08  5088.5  431.93  5095.2  432.49
  5102.7  431.20  5109.4  431.61  5116.9  430.14  5126.4  430.28  5131.2  429.20
  5150.3  429.17  5150.6  428.67  5154.3  429.17  5370.6  430.44  5406.9  430.07
  5412.9  429.20  5428.1  430.81  5434.0  429.96  5506.8  432.60  5666.4  435.28
#Mann=3,-1,0
  4645.9    0.05       0  5150.3   0.035       0  5154.3    0.05       0
Bank Sta=5150.3,5154.3
Exp/Cntr=0.3,0.1

Type RM Length L Ch R = 1,422,230,230,230
BEGIN DESCRIPTION:
NORTH MINERAL CR TRIB 8 1 3 40
END DESCRIPTION:
XS GIS Cut Line= 5
      3503247.12     10403156.28      3503059.39     10403091.17
      3502834.78     10403206.19      3502734.95     10403400.41
      3502562.44     10403594.63
#Sta/Elev= 30
  4725.6  429.99  4818.5  428.58  4910.0  428.33  4959.4  427.89  4966.2  426.30
  4976.0  422.77  4986.7  420.36  4986.9  419.86  4990.4  419.86  4990.7  420.36
  5042.6  422.16  5048.2  424.55  5070.4  426.94  5093.1  427.22  5109.2  426.73
  5114.8  427.48  5123.5  427.28  5131.4  425.27  5137.1  427.23  5205.3  428.47
  5240.9  427.93  5257.5  429.08  5419.3  429.67  5433.5  429.56  5454.4  427.79
  5468.7  427.35  5482.9  427.95  5511.3  430.51  5539.7  431.71  5654.8  432.82
#Mann=5,-1,0
  4725.6    0.05       0  4910.0    0.16       0  4986.7    0.07       0
  4990.7    0.16       0  5093.1    0.05       0
Bank Sta=4986.7,4990.7
Exp/Cntr=0.3,0.1

Type RM Length L Ch R = 1,192,0,0,0
BEGIN DESCRIPTION:
NORTH MINERAL CR TRIB 8 1 3 1 0
END DESCRIPTION:
XS GIS Cut Line= 4
      3503071.29     10402949.03      3502905.31     10402964.22
      3502695.89     10403134.57      3502462.62     10403466.58
#Sta/Elev= 30
  4703.2  426.29  4757.5  425.91  4905.8  426.08  4941.0  425.39  4955.4  423.65
  4968.5  420.71  4984.1  419.47  4990.6  419.65  5002.9  417.92  5003.2  417.42
  5006.7  417.42  5006.9  417.92  5027.2  420.77  5033.7  422.91  5041.6  423.21
  5054.5  425.90  5211.5  427.44  5226.3  427.32  5229.5  426.65  5241.1  423.22
  5262.0  420.00  5270.7  419.60  5306.5  421.42  5333.5  421.51  5363.1  422.75
  5369.2  424.07  5377.9  424.76  5384.0  426.64  5398.8  428.00  5545.6  429.85
#Mann=6,-1,0
  4703.2    0.05       0  4757.5    0.12       0  4968.5    0.16       0
  5002.9    0.07       0  5006.9    0.16       0  5229.5    0.05       0
Bank Sta=5002.9,5006.9
Exp/Cntr=0.3,0.1

Chan Stop Cuts=-1