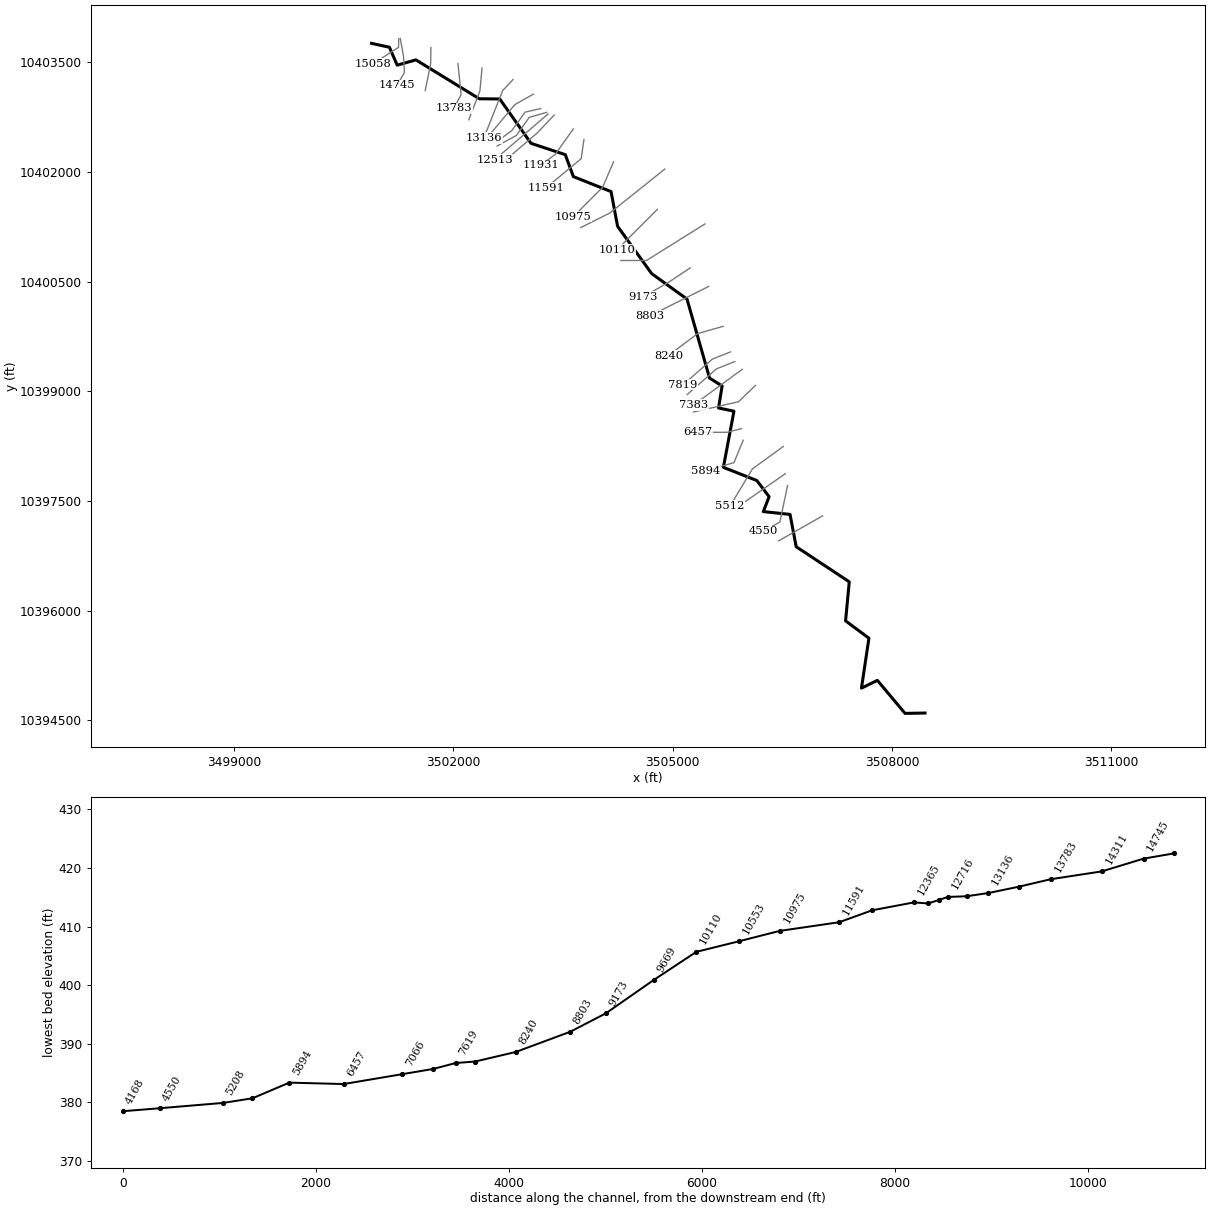
--- NORTH MINERAL CR TRIB 8 1.prj (project) ---

Proj Title=NORTH MINERAL CR TRIB 8 1 Base Level Engineering
Current Plan=p01
Default Exp/Contr=0.3,0.1
English Units
Geom File=g01
Flow File=f01
Plan File=p01
Y Axis Title=Elevation
X Axis Title(PF)=Main Channel Distance
X Axis Title(XS)=Station
BEGIN DESCRIPTION:
NORTH MINERAL CR TRIB 8 1
END DESCRIPTION:
DSS Export Rating Curves= 0
DSS Export Rating Curve Sorted= 0
DSS Export Volume Flow Curves= 0
DXF OffsetX= 0
DXF OffsetY= 0
DXF ScaleX= 1
DXF ScaleY= 10

--- NORTH MINERAL CR TRIB 8 1.p01 (plan) ---

Plan Title=Multiple Run
Short Identifier=Multiple
Geom File=g01
Flow File=f01
Subcritical Flow
K Sum by GR= 0
Std Step Tol= 0.01
Critical Tol= 0.01
Num of Std Step Trials= 20
Max Error Tol= 0.3
Flow Tol Ratio= 0.001
Split Flow NTrial= 30
Split Flow Tol= 0.02
Split Flow Ratio= 0.02
Log Output Level= 0
Friction Slope Method= 1
Unsteady Friction Slope Method= 2
Unsteady Bridges Friction Slope Method= 1
Parabolic Critical Depth
Global Vel Dist=  1 , 1 , 1
Global Log Level= 0
CheckData=True
Encroach Param= -1, 0, 0, 0
BEGIN DESCRIPTION:
Multiple Run
END DESCRIPTION:

--- NORTH MINERAL CR TRIB 8 1.f01 (steady flow) ---

Flow Title=Multiple
Program Version=4.10
Number of Profiles= 7
Profile Names=10-year,25-year,50-year,1pct_min,100-year,1pct_plu,500-year
River Rch & RM=NORTH MINERAL CR,Reach-1         ,15058
     728     994    1212    1081    1462    1977    2118
River Rch & RM=NORTH MINERAL CR,Reach-1         ,12911
    1401    1978    2464    2238    3027    4094    4559
River Rch & RM=NORTH MINERAL CR,Reach-1         ,5512
    1663    2356    2943    2677    3620    4896    5469
Boundary for River Rch & Prof#=NORTH MINERAL CR,Reach-1         , 1
Up Type= 0
Dn Type= 3
Dn Slope=0.005
Boundary for River Rch & Prof#=NORTH MINERAL CR,Reach-1         , 2
Up Type= 0
Dn Type= 3
Dn Slope=0.005
Boundary for River Rch & Prof#=NORTH MINERAL CR,Reach-1         , 3
Up Type= 0
Dn Type= 3
Dn Slope=0.005
Boundary for River Rch & Prof#=NORTH MINERAL CR,Reach-1         , 4
Up Type= 0
Dn Type= 3
Dn Slope=0.005
Boundary for River Rch & Prof#=NORTH MINERAL CR,Reach-1         , 5
Up Type= 0
Dn Type= 3
Dn Slope=0.005
Boundary for River Rch & Prof#=NORTH MINERAL CR,Reach-1         , 6
Up Type= 0
Dn Type= 3
Dn Slope=0.005
Boundary for River Rch & Prof#=NORTH MINERAL CR,Reach-1         , 7
Up Type= 0
Dn Type= 3
Dn Slope=0.005
DSS Import GetInterval= 0
DSS Import GetPeak= 0
DSS Import FillOption= 0

--- NORTH MINERAL CR TRIB 8 1.g01 (geometry) ---

Geom Title=Existing Conditions
Program Version=4.10

River Reach=NORTH MINERAL CR,Reach-1
Reach XY= 30
      3500882.11     10403761.64       3501125.8     10403708.52
      3501232.78     10403463.51      3501488.69     10403535.73
      3502355.35     10403003.78      3502634.94     10403001.13
      3503063.22     10402393.98      3503531.64     10402239.42
       3503642.7      10401938.7      3504157.57     10401734.32
      3504247.26      10401258.8      3504712.85     10400612.49
      3505196.46     10400264.12      3505505.41     10399182.86
      3505676.99     10399075.16      3505627.91     10398774.09
      3505838.81     10398730.24      3505694.15     10397962.42
      3506152.12      10397781.6      3506319.67     10397560.64
      3506240.52     10397356.94      3506605.68     10397318.57
      3506690.23     10396876.49      3507416.01     10396396.46
      3507365.53     10395862.85      3507685.02     10395624.95
      3507582.88     10394942.14      3507800.49     10395048.48
      3508179.37     10394596.95      3508452.11     10394601.64

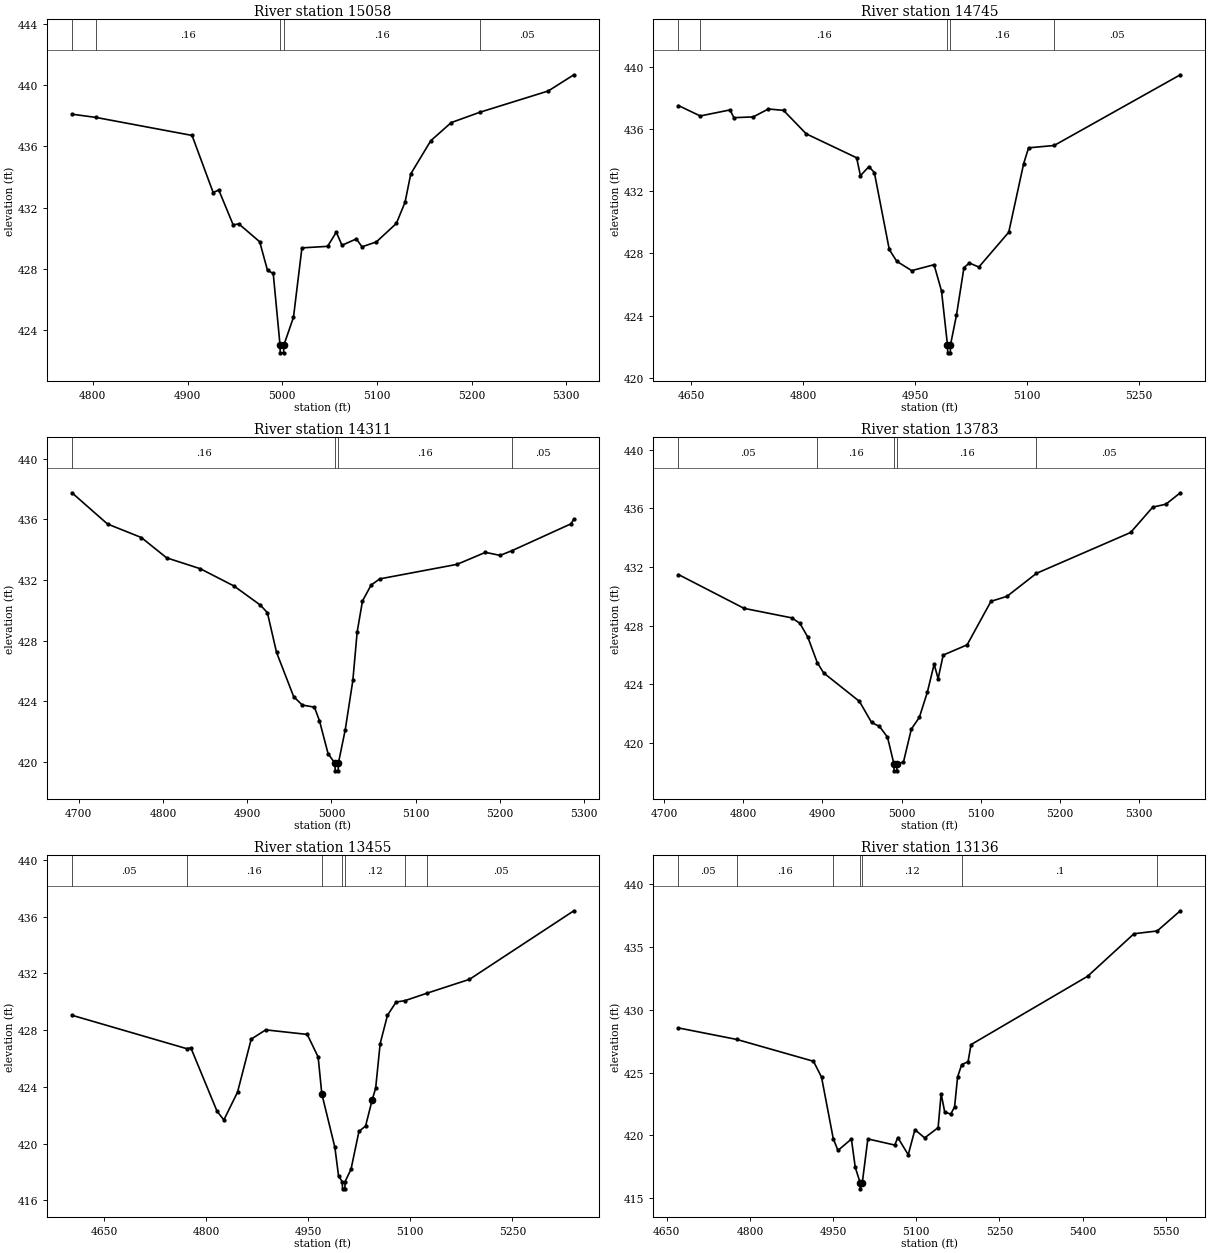
Type RM Length L Ch R = 1 ,15058   ,313,313,313
BEGIN DESCRIPTION:
NORTH MINERAL CR TRIB 8 1 5 0
END DESCRIPTION:
XS GIS Cut Line= 3
      3501253.74     10403823.12      3501250.86      10403706.8
      3500903.28     10403482.74
#Sta/Elev= 30
    4778  438.11  4803.2   437.9  4904.8  436.72  4927.1  432.98    4933  433.15
  4948.2  430.87  4954.2  430.93  4976.2  429.76  4984.5  427.88  4990.5  427.69
  4997.7  422.99  4997.9  422.49  5001.4  422.49  5001.7  422.99  5011.9  424.82
  5020.8  429.36  5047.9  429.46  5057.1  430.39  5063.1  429.53  5078.3  429.95
  5084.2  429.43  5099.4  429.75  5120.5  430.96  5129.7  432.35  5135.7   434.2
  5156.8  436.37  5178.4  437.56  5208.8  438.24  5280.9  439.63  5307.9  440.69
#Mann= 5 ,-1 , 0
    4778     .05       0  4803.2     .16       0  4997.7     .07       0
  5001.7     .16       0  5208.8     .05       0
Bank Sta=4997.7,5001.7
XS Rating Curve= 0 ,0
Exp/Cntr=0.3,0.1

Type RM Length L Ch R = 1 ,14745   ,434,434,434
BEGIN DESCRIPTION:
NORTH MINERAL CR TRIB 8 1 4 0
END DESCRIPTION:
XS GIS Cut Line= 4
      3501273.84     10403830.37      3501319.81     10403578.97
       3501331.3     10403363.51      3501230.74     10403188.24
#Sta/Elev= 30
  4632.7  437.51    4662  436.84    4702  437.23  4707.1  436.73  4733.1  436.78
  4753.4  437.29  4773.7   437.2  4804.2  435.69  4871.8  434.15  4876.9     433
  4888.3  433.58  4895.6   433.2  4915.6  428.25  4925.6  427.49  4945.7  426.89
  4975.7  427.27  4985.7  425.58  4993.7   422.1    4994   421.6  4997.5   421.6
  4997.7   422.1  5005.8  424.03  5015.8  427.08    5023  427.38  5035.8  427.12
  5075.9  429.36  5095.9  433.77  5102.5  434.79  5136.8  434.94  5306.1  439.49
#Mann= 5 ,-1 , 0
  4632.7     .05       0    4662     .16       0  4993.7     .07       0
  4997.7     .16       0  5136.8     .05       0
Bank Sta=4993.7,4997.7
XS Rating Curve= 0 ,0
Exp/Cntr=0.3,0.1

Type RM Length L Ch R = 1 ,14311   ,528,528,528
BEGIN DESCRIPTION:
NORTH MINERAL CR TRIB 8 1 3 2
END DESCRIPTION:
XS GIS Cut Line= 3
      3501693.26     10403703.89      3501690.39     10403484.17
      3501615.87     10403115.87
#Sta/Elev= 30
  4692.1  437.76  4734.3   435.7  4774.4  434.81  4804.4  433.47  4844.4  432.75
  4884.4  431.61  4915.7  430.35    4924  429.85  4934.8  427.24  4955.2  424.31
  4965.4  423.76  4979.8  423.62  4985.8  422.72    4996  420.55  5004.2  419.92
  5004.5  419.42    5008  419.42  5008.2  419.92  5016.4  422.14  5025.4  425.39
  5030.5  428.58  5036.8  430.62    5047  431.67  5057.3  432.08  5149.1  433.04
  5182.7  433.83  5200.1  433.63  5214.5  433.95  5284.1  435.71  5287.6  436.02
#Mann= 4 ,-1 , 0
  4692.1     .16       0  5004.2     .07       0  5008.2     .16       0
  5214.5     .05       0
Bank Sta=5004.2,5008.2
XS Rating Curve= 0 ,0
Exp/Cntr=0.3,0.1

Type RM Length L Ch R = 1 ,13783   ,328,328,328
BEGIN DESCRIPTION:
NORTH MINERAL CR TRIB 8 1 3 0
END DESCRIPTION:
XS GIS Cut Line= 3
      3502063.85     10403484.14      3502106.94     10403063.31
       3502011.1     10402875.92
#Sta/Elev= 30
  4718.3  431.49  4801.2  429.18  4861.5  428.53  4871.6  428.16  4881.6  427.22
  4893.6  425.47  4901.7  424.77  4946.8  422.83  4962.1  421.39  4972.1  421.12
  4982.2  420.39  4990.2  418.59  4990.5  418.09    4994  418.09  4994.2  418.59
  5002.3  418.68  5012.3  420.94  5022.4  421.74  5032.4  423.44  5041.1  425.37
  5046.1  424.38  5052.5  425.99  5082.7  426.69  5112.8  429.66    5133     430
  5170.2  431.57  5289.1  434.36    5317  436.09  5333.6  436.29  5351.8  437.07
#Mann= 5 ,-1 , 0
  4718.3     .05       0  4893.6     .16       0  4990.2     .07       0
  4994.2     .16       0  5170.2     .05       0
Bank Sta=4990.2,4994.2
XS Rating Curve= 0 ,0
Exp/Cntr=0.3,0.1

Type RM Length L Ch R = 1 ,13455   ,319,319,319
BEGIN DESCRIPTION:
Mapping XS bf2dc0d7
END DESCRIPTION:
XS GIS Cut Line= 3
      3502392.77      10403423.8      3502364.05     10403110.71
      3502211.99     10402716.21
#Sta/Elev= 30
    4603  429.05  4771.3   426.7  4777.7  426.75    4816   422.3  4826.1  421.67
  4846.2  423.63  4866.3  427.37  4887.7  428.02  4948.6   427.7  4964.6  426.11
  4969.9  423.56    4970  423.51  4989.2  419.74  4994.6  417.72  5000.1  417.32
  5000.4  416.82  5003.9  416.82  5004.1  417.32  5012.9   418.2  5024.5  420.86
  5034.3  421.25  5043.8  423.05  5049.1  423.92  5055.7  427.05  5066.4  429.04
  5079.1  429.98  5092.2  430.08  5124.9  430.61  5186.9  431.58  5340.2  436.41
#Mann= 7 ,-1 , 0
    4603     .05       0  4771.3     .16       0  4969.9     .12       0
  5000.1     .07       0  5004.1     .12       0  5092.2     .16       0
  5124.9     .05       0
Bank Sta=4970,5043.8
XS Rating Curve= 0 ,0
Exp/Cntr=0.3,0.1

Type RM Length L Ch R = 1 ,13136   ,225,225,225
BEGIN DESCRIPTION:
NORTH MINERAL CR TRIB 8 1 29 0
END DESCRIPTION:
XS GIS Cut Line= 3
      3502817.14     10403266.67      3502675.28      10403115.4
      3502417.11     10402466.67
#Sta/Elev= 30
  4670.9  428.56  4776.4  427.64  4914.6   425.9  4929.1  424.64  4950.3  419.73
  4958.8  418.79    4983   419.7    4990  417.44  4998.7  416.23    4999  415.73
  5002.7  416.23  5012.7  419.71  5061.3  419.22  5066.7  419.82  5085.6  418.45
  5097.6  420.45  5115.2  419.79  5139.5  420.61  5144.9  423.31  5151.4  421.86
  5162.2  421.69  5169.2  422.26  5174.6  424.65    5182  425.63  5193.5  425.87
  5198.9  427.23  5409.3  432.68  5492.9  436.07  5534.8  436.29  5576.5   437.9
#Mann= 7 ,-1 , 0
  4670.9     .05       0  4776.4     .16       0  4950.3     .12       0
  4998.7     .07       0  5002.7     .12       0    5182      .1       0
  5534.8     .05       0
Bank Sta=4998.7,5002.7
XS Rating Curve= 0 ,0
Exp/Cntr=0.3,0.1

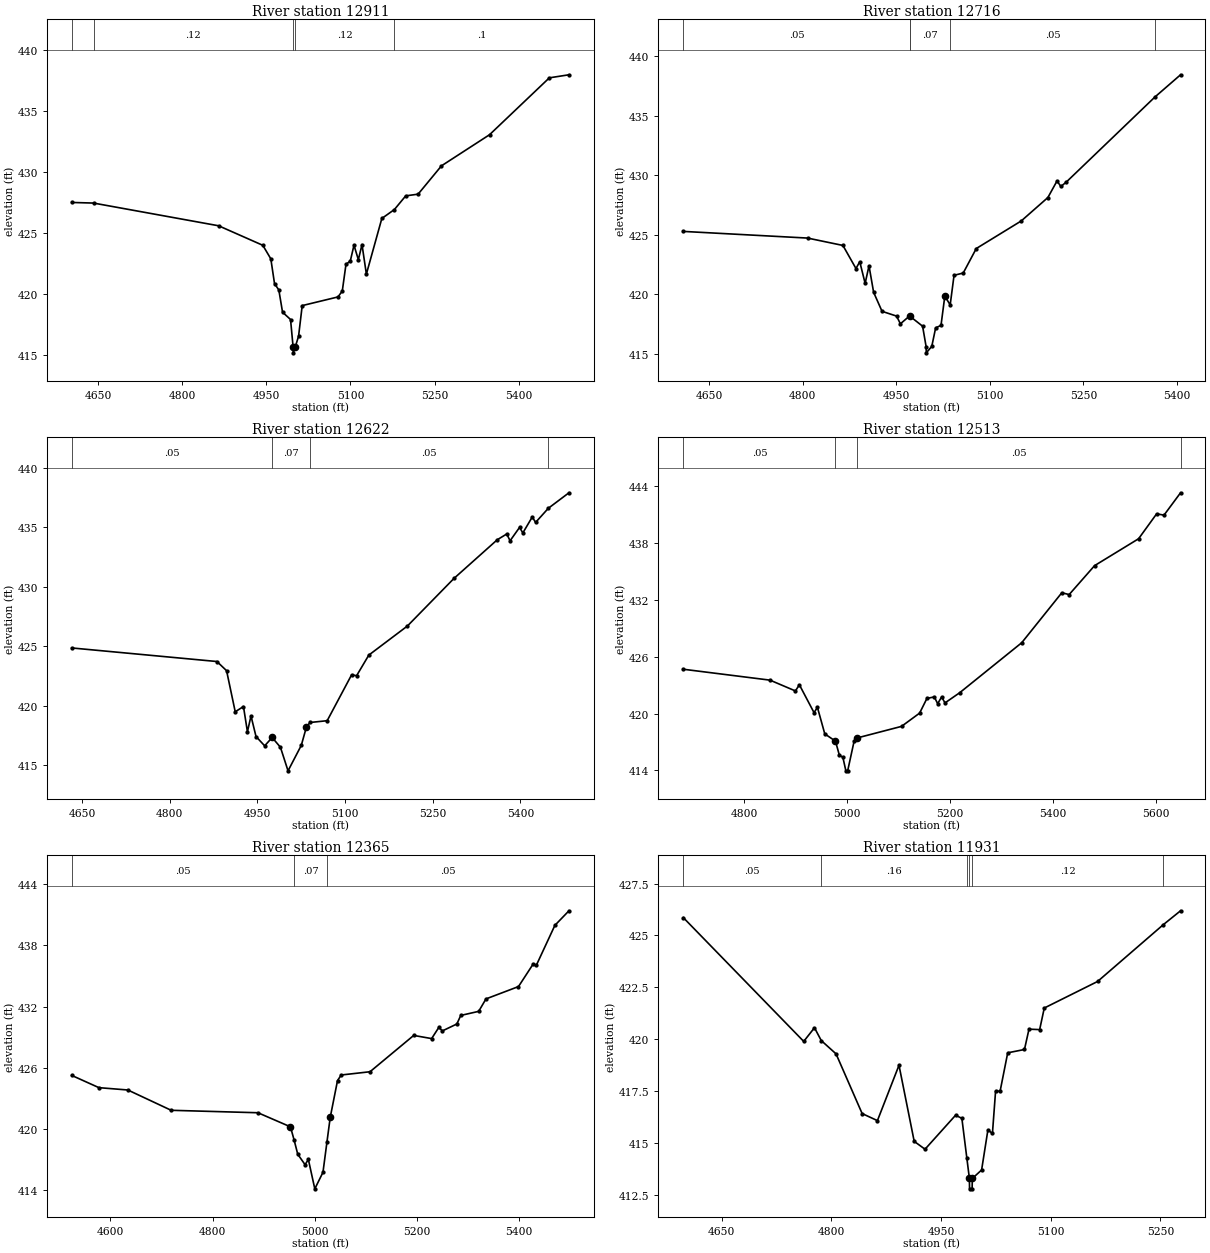
Type RM Length L Ch R = 1 ,12911   ,195,195,195
BEGIN DESCRIPTION:
NORTH MINERAL CR TRIB 8 1 26 0
END DESCRIPTION:
XS GIS Cut Line= 3
      3503094.07     10403066.51      3502842.01     10402923.64
       3502457.9     10402465.88
#Sta/Elev= 30
  4602.6   427.5  4641.5  427.45  4864.7  425.59  4943.6  423.99  4957.9  422.88
  4964.5  420.85  4972.2  420.33  4978.8  418.51  4993.1  417.91  4997.6  415.68
  4997.9  415.18  5001.6  415.68  5007.4  416.54  5013.9  419.05  5077.7  419.76
  5085.4  420.24    5092  422.43  5099.7   422.7  5106.3     424  5114.1  422.81
  5120.6  424.05  5128.4  421.63    5156  426.19  5178.4  426.92  5198.6  428.04
  5220.7  428.18  5262.4   430.5  5348.2  433.05  5454.9  437.71  5489.9  437.96
#Mann= 5 ,-1 , 0
  4602.6     .05       0  4641.5     .12       0  4997.6     .07       0
  5001.6     .12       0  5178.4      .1       0
Bank Sta=4997.6,5001.6
XS Rating Curve= 0 ,0
Exp/Cntr=0.3,0.1

Type RM Length L Ch R = 1 ,12716   ,94,94,94
BEGIN DESCRIPTION:
NORTH MINERAL CR TRIB 8 1 28 0
END DESCRIPTION:
XS GIS Cut Line= 4
      3503196.09     10402870.17      3502981.27     10402820.26
      3502798.97     10402566.36      3502585.64     10402411.21
#Sta/Elev= 30
  4608.8  425.27    4808  424.71  4864.6  424.09  4885.5  422.15  4891.6  422.72
  4900.2   420.9  4906.4  422.38  4913.8  420.15  4927.3  418.55  4950.6  418.15
  4956.7   417.5  4971.4  418.16  4992.3   417.3    4998  415.56  4998.2  415.06
    5007   415.6  5013.2  417.16  5021.8  417.37  5027.9  419.83  5036.5  419.09
  5042.7  421.58  5057.4  421.77  5078.3  423.83  5150.4  426.15  5193.1  428.12
  5207.7  429.51  5213.9  429.05  5222.4  429.41  5364.6  436.57  5405.7  438.44
#Mann= 5 ,-1 , 0
  4608.8     .05       0  4971.4     .16       0  4971.4     .07       0
  5036.5     .05       0  5364.6     .05       0
Bank Sta=4971.4,5027.9
XS Rating Curve= 0 ,0
Exp/Cntr=0.3,0.1

Type RM Length L Ch R = 1 ,12622   ,109,109,109
BEGIN DESCRIPTION:
NORTH MINERAL CR TRIB 8 1 26 2
END DESCRIPTION:
XS GIS Cut Line= 4
      3503276.39     10402818.09      3503037.69     10402748.65
      3502861.91     10402501.25      3502599.32     10402358.02
#Sta/Elev= 30
    4632  424.86  4880.6  423.72  4897.1  422.95  4911.9   419.5    4926  419.94
  4932.8  417.82  4938.9  419.15  4947.5  417.42  4962.3  416.64  4975.1  417.34
  4989.3  416.52  5002.3  414.54    5025  416.68  5033.6  418.19  5039.8   418.6
  5069.3  418.75  5111.1   422.6  5119.7  422.53  5140.6  424.26  5206.6   426.7
  5286.4   430.7  5360.6  433.95  5376.7  434.43  5382.4  433.86  5398.6  434.98
  5404.3  434.52  5420.4  435.86  5426.1   435.4  5447.9  436.59  5483.2  437.89
#Mann= 4 ,-1 , 0
    4632     .05       0  4975.1     .07       0  5039.8     .05       0
  5447.9     .05       0
Bank Sta=4975.1,5033.6
XS Rating Curve= 0 ,0
Exp/Cntr=0.3,0.1

Type RM Length L Ch R = 1 ,12513   ,148,148,148
BEGIN DESCRIPTION:
NORTH MINERAL CR TRIB 8 1 27 0
END DESCRIPTION:
XS GIS Cut Line= 2
       3503295.8     10402795.85      3502562.04     10402166.17
#Sta/Elev= 30
  4681.5  424.67  4850.1  423.52  4899.5  422.38  4907.2  423.03  4935.7  420.09
  4942.3  420.65  4956.6  417.85  4977.4  417.08  4985.1  415.57  4991.7   415.4
  4997.6  413.95  5001.1  413.95  5013.7   417.1  5020.2  417.43  5105.8  418.64
    5141  420.04  5155.2  421.59  5169.5  421.75  5176.1  421.04  5183.8  421.74
  5190.4  421.12  5218.9  422.19  5339.6  427.47  5417.5  432.74  5431.8  432.55
  5481.2   435.6  5566.8  438.44  5601.9  441.07  5616.2  440.93  5648.4  443.29
#Mann= 4 ,-1 , 0
  4681.5     .05       0  4977.4     .07       0  5020.2     .05       0
  5648.4     .05       0
Bank Sta=4977.4,5020.2
XS Rating Curve= 0 ,0
Exp/Cntr=0.3,0.1

Type RM Length L Ch R = 1 ,12365   ,434,434,434
BEGIN DESCRIPTION:
NORTH MINERAL CR TRIB 8 1 26 1
END DESCRIPTION:
XS GIS Cut Line= 3
      3503379.15     10402780.24      3503149.98     10402538.04
      3502663.03      10402121.4
#Sta/Elev= 30
  4524.1  425.25  4577.4  424.05  4634.1  423.82    4719  421.83    4889  421.59
  4952.7  420.21    4960  418.89    4967  417.52  4981.3   416.5  4987.8  417.01
  5000.4  414.13  5016.4  415.75  5024.1  418.68  5030.6  421.13  5044.9  424.74
  5052.1  425.29  5108.6  425.61  5194.2  429.17  5229.3  428.86  5243.6  429.97
  5250.2  429.61  5278.7  430.29  5286.4  431.13  5321.5  431.53  5335.8  432.75
  5399.5  433.96    5428  436.15  5434.6  436.06  5470.8  439.96  5498.4  441.39
#Mann= 3 ,-1 , 0
  4524.1     .05       0    4960     .07       0  5024.1     .05       0
Bank Sta=4952.7,5030.6
XS Rating Curve= 0 ,0
Exp/Cntr=0.3,0.1

Type RM Length L Ch R = 1 ,11931   ,340,340,340
BEGIN DESCRIPTION:
NORTH MINERAL CR TRIB 8 1 25 0
END DESCRIPTION:
XS GIS Cut Line= 3
      3503642.12     10402591.66      3503392.11     10402241.64
      3503192.14     10402091.66
#Sta/Elev= 30
  4597.5  425.86  4762.2  419.89  4776.9  420.55  4786.2  419.93  4806.4  419.29
  4842.1  416.41    4863  416.07  4892.5  418.74  4913.3  415.07  4928.1  414.69
  4969.9  416.33  4978.5  416.18  4985.2  414.29  4988.8  413.28    4989  412.78
  4992.5  412.78  4992.8  413.28  5005.5  413.69  5014.1  415.62  5020.3  415.45
  5024.6  417.49  5030.8  417.49  5041.2  419.34  5064.1   419.5  5070.3  420.48
  5084.9  420.46  5091.2   421.5  5164.1  422.78    5254  425.52  5277.6  426.19
#Mann= 6 ,-1 , 0
  4597.5     .05       0  4786.2     .16       0  4985.2     .12       0
  4988.8     .07       0  4992.8     .12       0    5254     .05       0
Bank Sta=4988.8,4992.8
XS Rating Curve= 0 ,0
Exp/Cntr=0.3,0.1

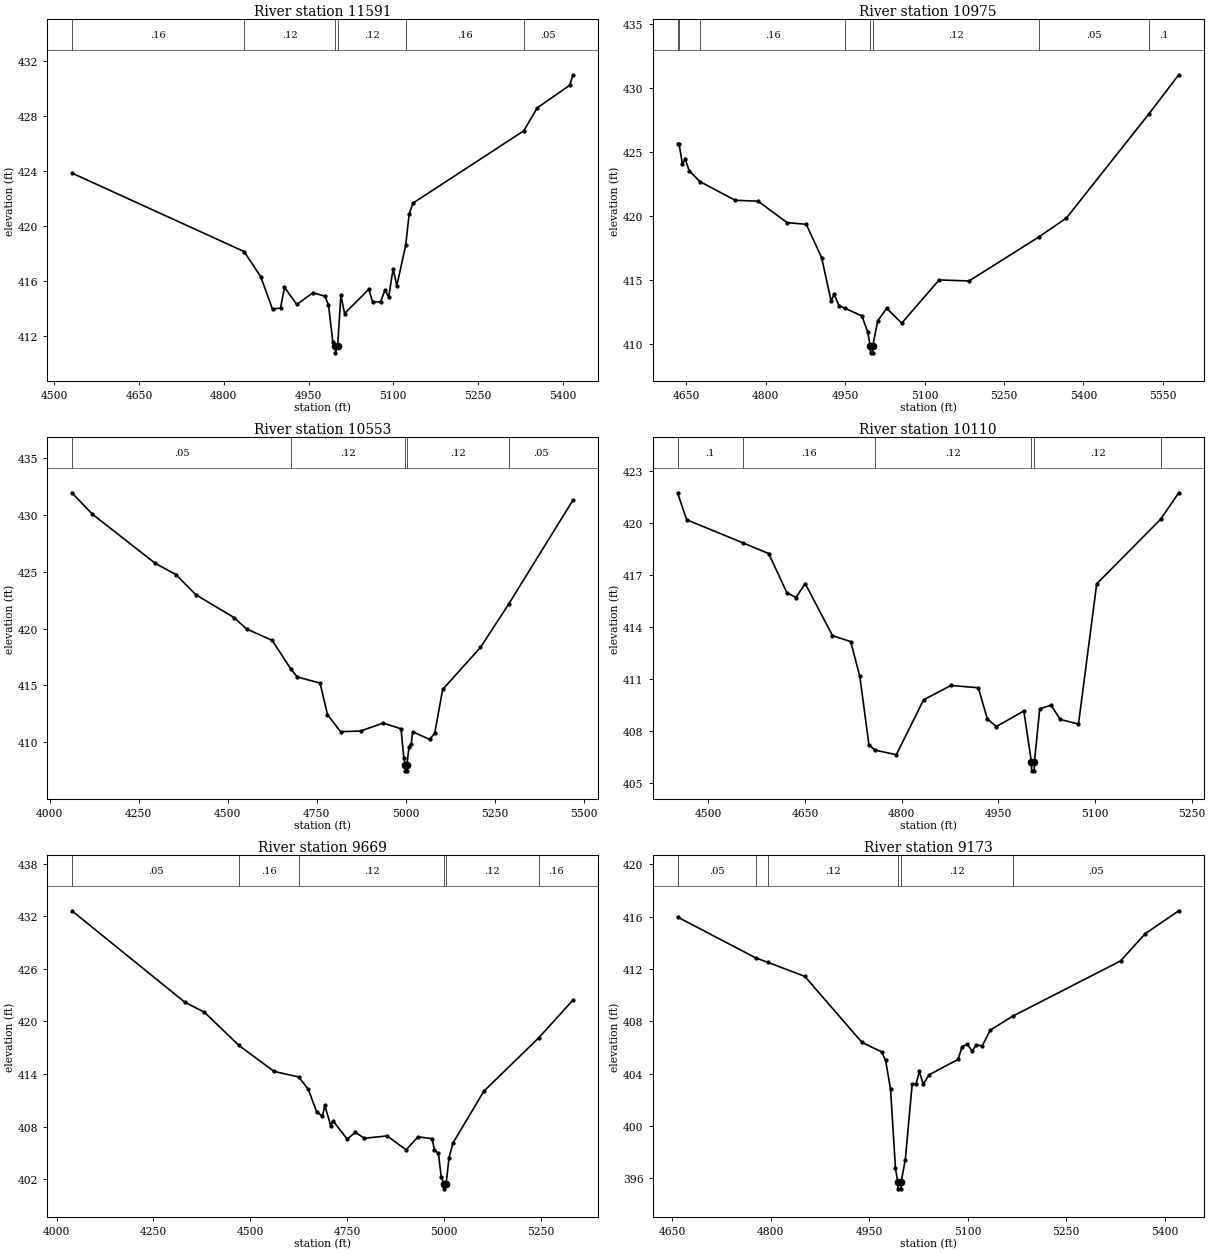
Type RM Length L Ch R = 1 ,11591   ,616,616,616
BEGIN DESCRIPTION:
NORTH MINERAL CR TRIB 8 1 25 1
END DESCRIPTION:
XS GIS Cut Line= 3
      3503786.38     10402444.79      3503749.49     10402184.41
      3503268.66     10401785.89
#Sta/Elev= 30
  4530.9  423.83  4835.8  418.12  4865.3  416.29  4886.2  413.92  4900.5  414.02
  4907.4  415.52  4929.1  414.27  4957.8  415.12  4978.6  414.88  4985.3  414.25
    4993  411.53  4997.5  411.25  4997.7  410.75  5001.5  411.25  5007.3  414.94
  5013.8  413.61  5056.8  415.38  5063.3  414.46  5077.6  414.46  5085.4  415.32
  5091.9   414.8  5099.8  416.87  5106.3  415.63    5122  418.56  5128.2  420.85
  5134.9  421.64  5331.1   426.9    5355  428.57  5412.3  430.21  5418.4  430.98
#Mann= 6 ,-1 , 0
  4530.9     .16       0  4835.8     .12       0  4997.5     .07       0
  5001.5     .12       0    5122     .16       0  5331.1     .05       0
Bank Sta=4997.5,5001.5
XS Rating Curve= 0 ,0
Exp/Cntr=0.3,0.1

Type RM Length L Ch R = 1 ,10975   ,422,422,422
BEGIN DESCRIPTION:
NORTH MINERAL CR TRIB 8 1 24 0
END DESCRIPTION:
XS GIS Cut Line= 3
      3504192.09      10402141.6      3504042.11     10401791.64
      3503642.12     10401391.66
#Sta/Elev= 30
  4633.7  425.63  4636.4  425.63  4642.7  424.04  4648.2  424.41  4655.4  423.52
  4675.7  422.66  4742.4   421.2    4786  421.12  4840.4  419.45  4876.6  419.32
  4905.6  416.72  4923.8   413.3  4929.2  413.87  4938.3  412.97  4950.2  412.75
  4981.8  412.15  4992.7   410.9  4997.7  409.77    4998  409.27  5001.8  409.27
  5002.1  409.77  5011.7  411.78  5028.6  412.75  5056.9  411.59  5127.6  414.97
  5184.1  414.89  5316.3  418.34    5368  419.81  5524.1  427.97  5580.1  431.01
#Mann= 8 ,-1 , 0
  4633.7      .1       0  4636.4     .05       0  4675.7     .16       0
  4950.2     .12       0  4997.7     .07       0  5002.1     .12       0
  5316.3     .05       0  5524.1      .1       0
Bank Sta=4997.7,5002.1
XS Rating Curve= 0 ,0
Exp/Cntr=0.3,0.1

Type RM Length L Ch R = 1 ,10553   ,443,443,443
BEGIN DESCRIPTION:
NORTH MINERAL CR TRIB 8 1 23 0
END DESCRIPTION:
XS GIS Cut Line= 3
      3504892.11     10402041.65      3504142.11     10401441.64
       3503742.1     10401241.64
#Sta/Elev= 30
  4062.2  431.93    4119  430.07  4296.7  425.72  4354.4  424.75  4410.4  422.97
  4517.6  420.97  4552.8  419.97  4624.9  418.96  4677.9  416.41  4695.3  415.75
  4759.3  415.21  4780.2  412.44    4817  410.94    4873     411    4937   411.7
  4986.7  411.19  4994.7  408.61  4998.8     408  4999.1   407.5    5003   407.5
  5003.3     408  5009.1  409.58  5015.5   409.9  5019.5  410.93  5067.4  410.26
  5081.4  410.81  5103.7  414.65  5209.9  418.34  5289.2  422.15  5469.9  431.29
#Mann= 5 ,-1 , 0
  4062.2     .05       0  4677.9     .12       0  4998.8     .07       0
  5003.3     .12       0  5289.2     .05       0
Bank Sta=4998.8,5003.3
XS Rating Curve= 0 ,0
Exp/Cntr=0.3,0.1

Type RM Length L Ch R = 1 ,10110   ,441,441,441
BEGIN DESCRIPTION:
NORTH MINERAL CR TRIB 8 1 22 0
END DESCRIPTION:
XS GIS Cut Line= 3
      3504792.08     10401491.62      3504392.11     10401091.64
       3504242.1     10400941.63
#Sta/Elev= 30
  4452.1  421.73  4466.2  420.19  4553.3  418.86  4593.5  418.24  4621.8  415.97
  4635.9   415.7  4650.1  416.51  4692.5   413.5  4720.8  413.15  4734.9  411.15
  4749.1  407.19  4758.2  406.89  4791.5  406.62  4833.9  409.79  4876.3  410.62
  4918.8  410.49  4932.9  408.68    4947  408.25  4989.5  409.15  5001.3  406.19
  5001.7  405.69  5005.6  405.69  5005.9  406.19  5014.2  409.28  5031.9  409.48
    5046  408.66  5074.3  408.39  5102.6  416.49  5201.8  420.22  5229.9  421.75
#Mann= 6 ,-1 , 0
  4452.1      .1       0  4553.3     .16       0  4758.2     .12       0
  5001.3     .07       0  5005.9     .12       0  5201.8     .16       0
Bank Sta=5001.3,5005.9
XS Rating Curve= 0 ,0
Exp/Cntr=0.3,0.1

Type RM Length L Ch R = 1 ,9669    ,496,496,496
BEGIN DESCRIPTION:
NORTH MINERAL CR TRIB 8 1 2 1
END DESCRIPTION:
XS GIS Cut Line= 3
      3505442.11     10401291.65      3504642.11     10400791.64
      3504292.11     10400791.64
#Sta/Elev= 30
  4039.5  432.63  4330.2  422.22  4381.5  421.05  4470.4  417.27  4561.3  414.29
    4625  413.66  4649.8  412.24    4671  409.68  4686.3  409.19  4692.2  410.43
  4707.5   408.1  4713.4  408.66    4750  406.56  4771.2  407.35  4794.2  406.66
  4853.2  406.93  4902.1  405.34  4932.8  406.83  4969.3  406.61  4975.2  405.34
  4985.4  404.94  4992.9   402.2  5000.6  401.39    5001  400.89  5005.2  401.39
  5012.9  404.45  5022.9  406.11  5102.9  412.04    5244  418.11  5332.9  422.44
#Mann= 6 ,-1 , 0
  4039.5     .05       0  4470.4     .16       0    4625     .12       0
  5000.6     .07       0  5005.2     .12       0    5244     .16       0
Bank Sta=5000.6,5005.2
XS Rating Curve= 0 ,0
Exp/Cntr=0.3,0.1

Type RM Length L Ch R = 1 ,9173    ,370,370,370
BEGIN DESCRIPTION:
NORTH MINERAL CR TRIB 8 1 2 0
END DESCRIPTION:
XS GIS Cut Line= 3
       3505242.1     10400691.64      3504942.11     10400491.64
      3504592.08     10400291.63
#Sta/Elev= 30
  4657.9  415.96  4777.4  412.83    4795  412.51  4851.7  411.43  4938.8  406.39
  4968.9  405.66  4974.9  405.01  4982.4   402.8  4989.9  396.79  4993.4   395.7
  4993.8   395.2  4998.1   395.2  4998.5   395.7  5004.9  397.43  5015.4  403.21
  5021.3  403.21  5026.4  404.17  5032.1   403.2  5041.5  403.92  5085.4  405.09
  5091.2  406.03  5099.1  406.26    5107  405.71  5112.8   406.2  5122.1  406.12
  5134.3  407.32  5168.3  408.38    5333  412.61  5370.5  414.69  5421.6  416.44
#Mann= 6 ,-1 , 0
  4657.9     .05       0  4777.4     .16       0    4795     .12       0
  4993.4     .07       0  4998.5     .12       0  5168.3     .05       0
Bank Sta=4993.4,4998.5
XS Rating Curve= 0 ,0
Exp/Cntr=0.3,0.1

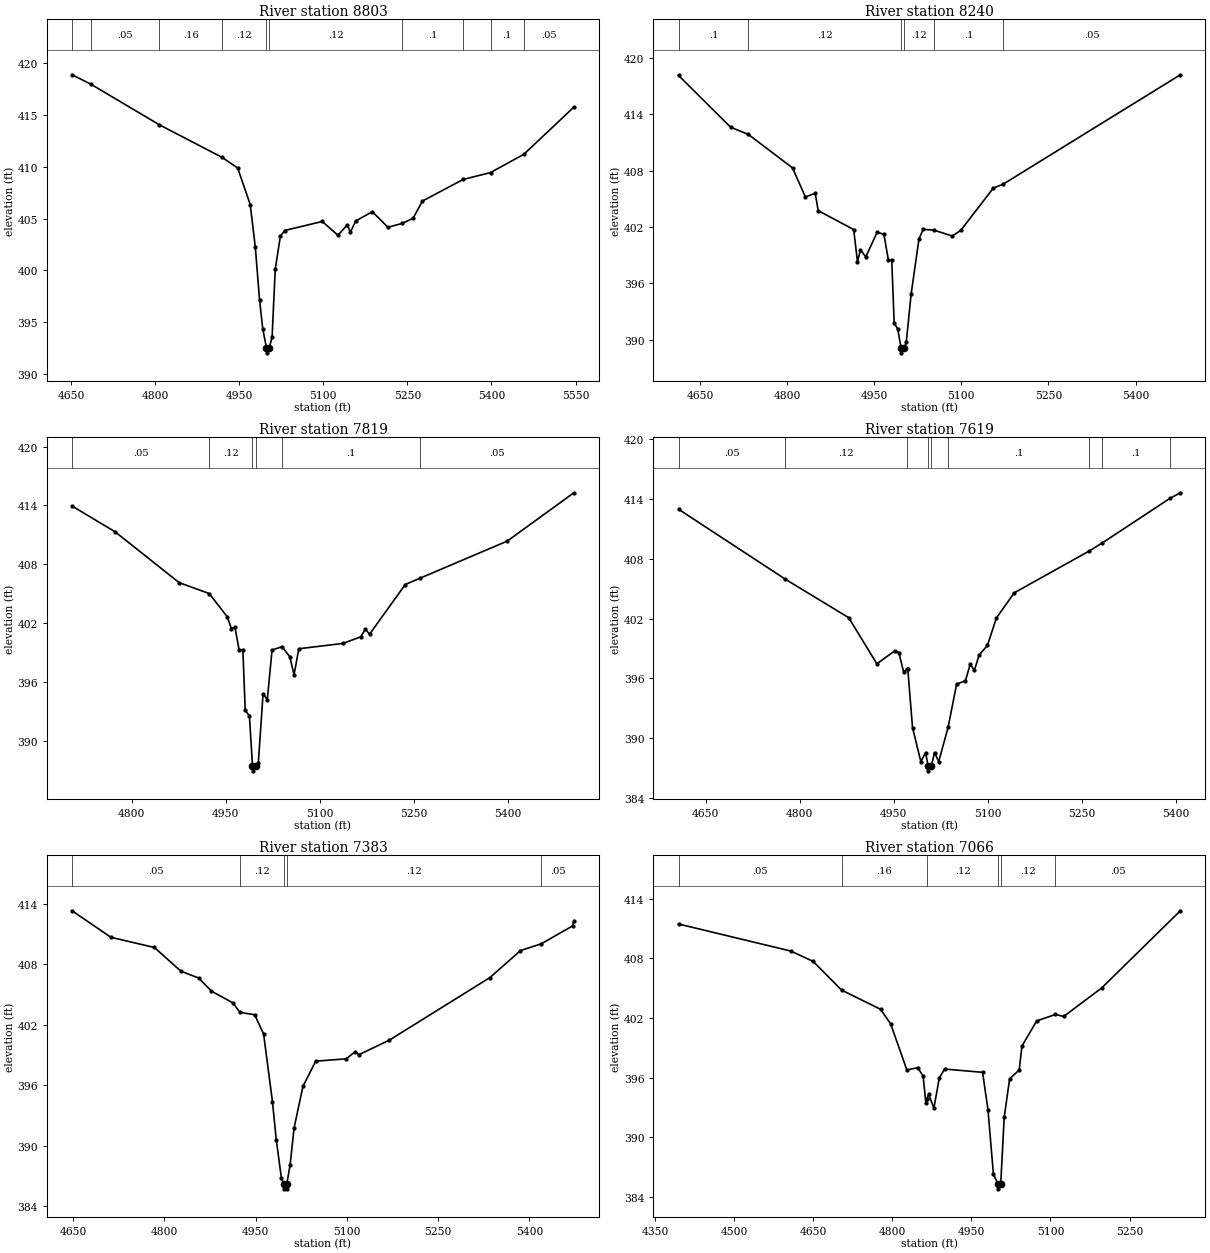
Type RM Length L Ch R = 1 ,8803    ,563,563,563
BEGIN DESCRIPTION:
NORTH MINERAL CR TRIB 8 1 19 0
END DESCRIPTION:
XS GIS Cut Line= 2
      3505494.32     10400437.47      3504694.15      10400036.3
#Sta/Elev= 30
  4651.9  418.87  4684.9  417.98  4807.5  414.05  4919.3  410.91  4947.3  409.88
  4969.7  406.35  4978.8  402.22  4986.4  397.11    4992  394.39  4998.6  392.55
    4999  392.05  5003.7  392.55  5008.7  393.56  5014.3   400.1  5023.5  403.31
  5031.1  403.85  5098.1  404.72  5126.1   403.4  5142.8  404.38  5148.4  403.67
  5157.8  404.77  5187.5  405.66  5215.4  404.16    5241  404.54  5260.1  405.02
  5276.9  406.69  5349.4  408.77  5398.4  409.44  5457.8   411.2    5547  415.75
#Mann= 10 ,-1 , 0
  4651.9     .16       0  4684.9     .05       0  4807.5     .16       0
  4919.3     .12       0  4998.6     .07       0  5003.7     .12       0
    5241      .1       0  5349.4     .05       0  5398.4      .1       0
  5457.8     .05       0
Bank Sta=4998.6,5003.7
XS Rating Curve= 0 ,0
Exp/Cntr=0.3,0.1

Type RM Length L Ch R = 1 ,8240    ,421,421,421
BEGIN DESCRIPTION:
NORTH MINERAL CR TRIB 8 1 18 0
END DESCRIPTION:
XS GIS Cut Line= 3
      3505692.07     10399891.63      3505342.11     10399791.64
      3504942.08     10399491.63
#Sta/Elev= 30
  4613.1  418.13  4702.8  412.62  4733.4  411.85  4809.4  408.29  4831.5   405.2
  4848.4  405.59  4853.6  403.74  4914.7  401.73  4921.2   398.3  4926.4  399.58
  4935.5  398.81    4955  401.44  4966.7  401.23  4974.5  398.47  4980.2  398.47
  4984.4  391.79  4990.6  391.13  4996.3  389.11  4996.7  388.61  5001.6  389.11
  5005.2  389.72  5013.5  394.82  5027.1  400.73  5034.4  401.75  5053.3  401.66
  5084.4  401.04  5098.9  401.63  5155.2  406.15  5172.1  406.56  5477.1   418.2
#Mann= 6 ,-1 , 0
  4613.1      .1       0  4733.4     .12       0  4996.3     .07       0
  5001.6     .12       0  5053.3      .1       0  5172.1     .05       0
Bank Sta=4996.3,5001.6
XS Rating Curve= 0 ,0
Exp/Cntr=0.3,0.1

Type RM Length L Ch R = 1 ,7819    ,200,200,200
BEGIN DESCRIPTION:
NORTH MINERAL CR TRIB 8 1 16 0
END DESCRIPTION:
XS GIS Cut Line= 3
      3505792.07     10399541.63      3505542.11     10399441.64
      3505142.13     10399091.66
#Sta/Elev= 30
    4705  413.94  4773.6  411.32  4875.9  406.14  4923.8  405.03  4952.7  402.66
  4959.4  401.43  4964.8  401.64  4971.5  399.31  4977.5  399.31  4981.3  393.16
    4988  392.57  4992.9  387.48  4993.3  386.98  4998.2  387.48  5002.2  387.79
  5009.8  394.84  5016.5  394.21  5024.1  399.28    5040  399.62  5052.5  398.59
  5059.2  396.76  5066.8  399.41    5137  399.95  5165.5  400.62  5173.1   401.4
  5179.7  400.89  5236.7  405.95  5259.4  406.57  5399.4  410.37  5505.7  415.29
#Mann= 6 ,-1 , 0
    4705     .05       0  4923.8     .12       0  4992.9     .07       0
  4998.2     .12       0    5040      .1       0  5259.4     .05       0
Bank Sta=4992.9,4998.2
XS Rating Curve= 0 ,0
Exp/Cntr=0.3,0.1

Type RM Length L Ch R = 1 ,7619    ,236,236,236
BEGIN DESCRIPTION:
NORTH MINERAL CR TRIB 8 1 17 0
END DESCRIPTION:
XS GIS Cut Line= 3
      3505850.49     10399409.61      3505600.51     10399309.62
      3505200.47     10398959.59
#Sta/Elev= 30
  4606.5  412.98  4776.9  405.96    4878   402.1    4923  397.47  4951.4  398.76
  4958.1   398.6  4965.7  396.65  4970.5   396.9  4972.3  396.99  4979.9  391.07
  4993.2  387.66  5000.8  388.56  5004.7  387.23  5005.2  386.73  5010.1  387.23
    5015  388.57  5021.7  387.66  5036.7  391.09  5050.2  395.42  5064.4  395.78
    5072  397.43  5078.6  396.81  5086.2  398.35  5099.5  399.32  5113.7  402.06
  5142.2  404.59  5261.4  408.77  5282.8   409.6  5390.5  414.06  5407.3  414.63
#Mann= 9 ,-1 , 0
  4606.5     .05       0  4776.9     .12       0  4970.5     .05       0
  5004.7     .04       0  5010.1     .05       0  5036.7      .1       0
  5261.4     .05       0  5282.8      .1       0  5390.5     .05       0
Bank Sta=5004.7,5010.1
XS Rating Curve= 0 ,0
Exp/Cntr=0.3,0.1

Type RM Length L Ch R = 1 ,7383    ,317,317,317
BEGIN DESCRIPTION:
NORTH MINERAL CR TRIB 8 1 15 0
END DESCRIPTION:
XS GIS Cut Line= 2
      3505951.29     10399302.45      3505285.88     10398815.09
#Sta/Elev= 30
  4648.2  413.28  4712.1  410.65  4783.5  409.64  4827.1  407.29  4856.4  406.61
  4877.3  405.31  4912.8  404.14    4924  403.21  4948.3  402.97    4963  401.07
  4977.6  394.35  4983.8  390.59  4992.3  386.78  4995.8  386.21  4996.2  385.71
  5000.8  385.71  5001.2  386.21  5006.7  388.12  5013.1  391.74  5027.8  395.89
  5048.7  398.37  5098.8   398.6  5113.5  399.31  5119.7  399.01  5169.9  400.46
  5335.1  406.66  5385.2  409.33  5419.6  410.01  5470.9  411.78    5473  412.28
#Mann= 5 ,-1 , 0
  4648.2     .05       0    4924     .12       0  4995.8     .07       0
  5001.2     .12       0  5419.6     .05       0
Bank Sta=4995.8,5001.2
XS Rating Curve= 0 ,0
Exp/Cntr=0.3,0.1

Type RM Length L Ch R = 1 ,7066    ,609,609,609
BEGIN DESCRIPTION:
NORTH MINERAL CR TRIB 8 1 14 1
END DESCRIPTION:
XS GIS Cut Line= 3
      3506132.29      10399082.4      3505901.84     10398859.76
       3505286.5     10398719.26
#Sta/Elev= 30
  4394.7  411.47  4607.5  408.75  4649.9  407.71    4704  404.82  4777.8  402.89
  4796.9  401.43  4827.7  396.79  4848.2  397.02  4858.5  396.18  4863.7  393.48
    4866  393.87  4868.9  394.37    4879  392.95  4889.2  395.99  4899.5  396.88
  4971.3  396.55  4981.5  392.79  4991.8  386.33  5000.2  385.33  5000.6  384.83
  5005.7  385.33  5012.3  392.02  5022.6  395.91  5040.8  396.78  5045.9  399.19
  5073.9  401.72  5109.4  402.37  5125.1  402.17    5197  405.03  5346.3   412.8
#Mann= 6 ,-1 , 0
  4394.7     .05       0    4704     .16       0    4866     .12       0
  5000.2     .07       0  5005.7     .12       0  5109.4     .05       0
Bank Sta=5000.2,5005.7
XS Rating Curve= 0 ,0
Exp/Cntr=0.3,0.1

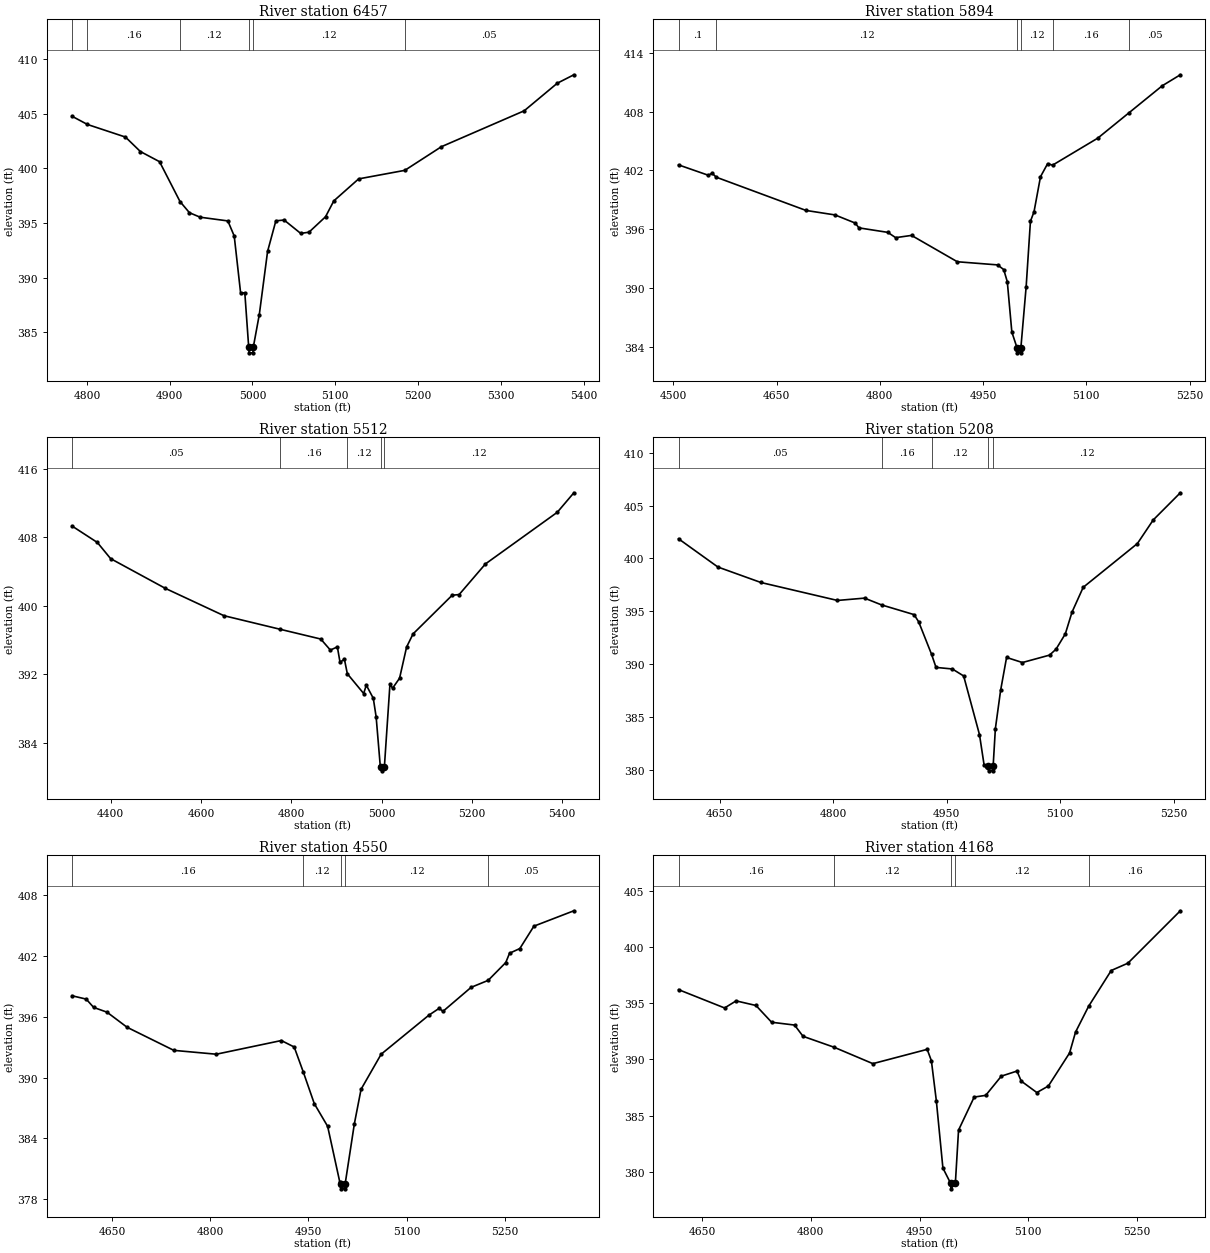
Type RM Length L Ch R = 1 ,6457    ,563,563,563
BEGIN DESCRIPTION:
NORTH MINERAL CR TRIB 8 1 14 0
END DESCRIPTION:
XS GIS Cut Line= 3
      3505942.14     10398491.65      3505742.11     10398441.64
       3505342.1     10398441.64
#Sta/Elev= 30
  4782.1  404.75  4800.7     404  4846.6  402.85  4864.6  401.53  4887.8   400.6
  4912.5  396.96  4923.9  395.94  4936.8  395.53  4970.3  395.19    4978  393.81
  4985.7  388.62  4990.8  388.62  4995.5  383.64    4996  383.14  5000.6  383.14
    5001  383.64  5008.3  386.64  5018.3  392.41  5028.3   395.2  5038.3  395.27
  5058.3  394.05  5068.3  394.16  5088.3  395.57  5098.3  397.02  5128.3  399.03
  5184.1  399.81  5228.3  401.97  5328.3  405.25  5368.3  407.77  5388.3  408.54
#Mann= 6 ,-1 , 0
  4782.1      .1       0  4800.7     .16       0  4912.5     .12       0
  4995.5     .07       0    5001     .12       0  5184.1     .05       0
Bank Sta=4995.5,5001
XS Rating Curve= 0 ,0
Exp/Cntr=0.3,0.1

Type RM Length L Ch R = 1 ,5894    ,382,382,382
BEGIN DESCRIPTION:
NORTH MINERAL CR TRIB 8 1 13 0
END DESCRIPTION:
XS GIS Cut Line= 3
       3505965.2     10398332.82      3505839.34     10398026.85
      3505456.94     10397916.67
#Sta/Elev= 30
  4507.7  402.57    4551  401.51  4556.4  401.72  4562.6  401.31  4692.8  397.92
    4735  397.46  4764.3  396.63  4769.7  396.14  4811.7  395.68    4823  395.14
  4846.1  395.37  4912.6  392.68    4971  392.36    4980  391.88  4985.2  390.64
  4991.8   385.5  4999.4  383.88  4999.9  383.38  5004.5  383.38  5004.9  383.88
  5012.6  390.15  5018.8  396.81    5024  397.78  5033.4  401.36  5043.8   402.7
  5050.9  402.54  5116.6   405.3  5161.6  407.87  5210.3  410.65  5236.5  411.77
#Mann= 6 ,-1 , 0
  4507.7      .1       0  4562.6     .12       0  4999.4     .07       0
  5004.9     .12       0  5050.9     .16       0  5161.6     .05       0
Bank Sta=4999.4,5004.9
XS Rating Curve= 0 ,0
Exp/Cntr=0.3,0.1

Type RM Length L Ch R = 1 ,5512    ,304,304,304
BEGIN DESCRIPTION:
NORTH MINERAL CR TRIB 8 1 12 0
END DESCRIPTION:
XS GIS Cut Line= 3
      3506514.28     10398248.23      3506092.11     10397941.64
       3505787.3     10397436.65
#Sta/Elev= 30
  4314.2  409.33  4370.2  407.41  4399.6  405.52    4521  402.04  4650.6  398.85
  4774.4  397.27  4865.1  396.12  4886.4  394.83  4901.9   395.2  4907.8   393.4
  4917.5  393.76    4924  392.06  4960.2  389.75    4966  390.73  4981.5  389.19
  4987.8  387.02    4997  381.23  4999.6  381.21  5000.1  380.71  5006.1  381.21
  5018.4  390.84  5024.2  390.37  5039.7  391.54  5055.3  395.19  5069.6  396.72
  5156.2  401.24  5171.7  401.32  5229.9   404.9  5389.1  410.94  5425.8  413.22
#Mann= 5 ,-1 , 0
  4314.2     .05       0  4774.4     .16       0    4924     .12       0
  4999.6     .07       0  5006.1     .12       0
Bank Sta=4999.6,5006.1
XS Rating Curve= 0 ,0
Exp/Cntr=0.3,0.1

Type RM Length L Ch R = 1 ,5208    ,658,658,658
BEGIN DESCRIPTION:
NORTH MINERAL CR TRIB 8 1 41 0
END DESCRIPTION:
XS GIS Cut Line= 2
      3506541.15     10397875.38      3505997.37     10397496.42
#Sta/Elev= 30
  4595.8  401.86  4647.8  399.19  4704.5  397.73  4805.7  396.03  4841.5  396.25
  4863.9  395.61  4906.9  394.69    4913  394.01    4930  390.94  4935.9   389.7
  4957.5  389.55  4972.4  388.89  4993.3  383.35  4999.4  380.48  5004.9  380.42
  5005.4  379.92  5010.9  379.92  5011.4  380.42  5014.3  383.91  5021.2  387.52
  5029.1  390.64    5050  390.16  5085.8  390.86  5094.4  391.42  5106.7  392.87
  5115.5  394.92  5130.3  397.27  5201.9  401.41  5222.8  403.64  5258.6  406.21
#Mann= 5 ,-1 , 0
  4595.8     .05       0  4863.9     .16       0    4930     .12       0
  5004.9     .07       0  5011.4     .12       0
Bank Sta=5004.9,5011.4
XS Rating Curve= 0 ,0
Exp/Cntr=0.3,0.1

Type RM Length L Ch R = 1 ,4550    ,382,382,382
BEGIN DESCRIPTION:
NORTH MINERAL CR TRIB 8 1 40 0
END DESCRIPTION:
XS GIS Cut Line= 3
       3506572.4      10397713.9      3506466.94     10397215.23
      3506244.42     10397085.85
#Sta/Elev= 30
  4588.6  398.07  4610.2  397.74  4621.6  396.92    4642  396.45  4672.7  394.96
  4744.2  392.68  4809.1   392.3  4908.5  393.65  4928.2  393.01  4942.2  390.52
  4958.9  387.42  4979.3  385.18  4997.7  379.73  4999.6  379.51  5000.1  379.01
  5005.6  379.01  5006.1  379.51  5020.2  385.45  5030.4  388.84  5061.1   392.3
    5134  396.15  5149.8  396.83  5155.6  396.53  5198.6   398.9  5224.7  399.59
  5251.6  401.35  5257.4  402.27  5273.1  402.73  5294.6  404.94  5355.7  406.46
#Mann= 5 ,-1 , 0
  4588.6     .16       0  4942.2     .12       0  4999.6     .07       0
  5006.1     .12       0  5224.7     .05       0
Bank Sta=4999.6,5006.1
XS Rating Curve= 0 ,0
Exp/Cntr=0.3,0.1

Type RM Length L Ch R = 1 ,4168    ,616,616,616
BEGIN DESCRIPTION:
NORTH MINERAL CR TRIB 8 1 9 0
END DESCRIPTION:
XS GIS Cut Line= 2
      3507051.55     10397298.55      3506449.15     10396956.36
#Sta/Elev= 30
  4617.3  396.21  4680.9  394.58  4696.8  395.21  4724.2   394.8  4745.8  393.31
  4777.5  393.06  4789.2  392.06    4832  391.09  4885.6  389.63  4960.6   390.9
  4966.4  389.89  4973.2  386.35  4982.3  380.35  4992.9     379  4993.4   378.5
  4999.5     379  5003.9  383.72  5025.5  386.66  5041.4  386.81    5063  388.52
  5084.6  388.97  5090.4  388.08    5112  387.06  5127.9  387.64  5157.2  390.58
  5165.4  392.43  5183.4  394.72  5214.7  397.91  5237.7  398.56  5310.1  403.22
#Mann= 5 ,-1 , 0
  4617.3     .16       0    4832     .12       0  4992.9     .07       0
  4999.5     .12       0  5183.4     .16       0
Bank Sta=4992.9,4999.5
XS Rating Curve= 0 ,0
Exp/Cntr=0.3,0.1