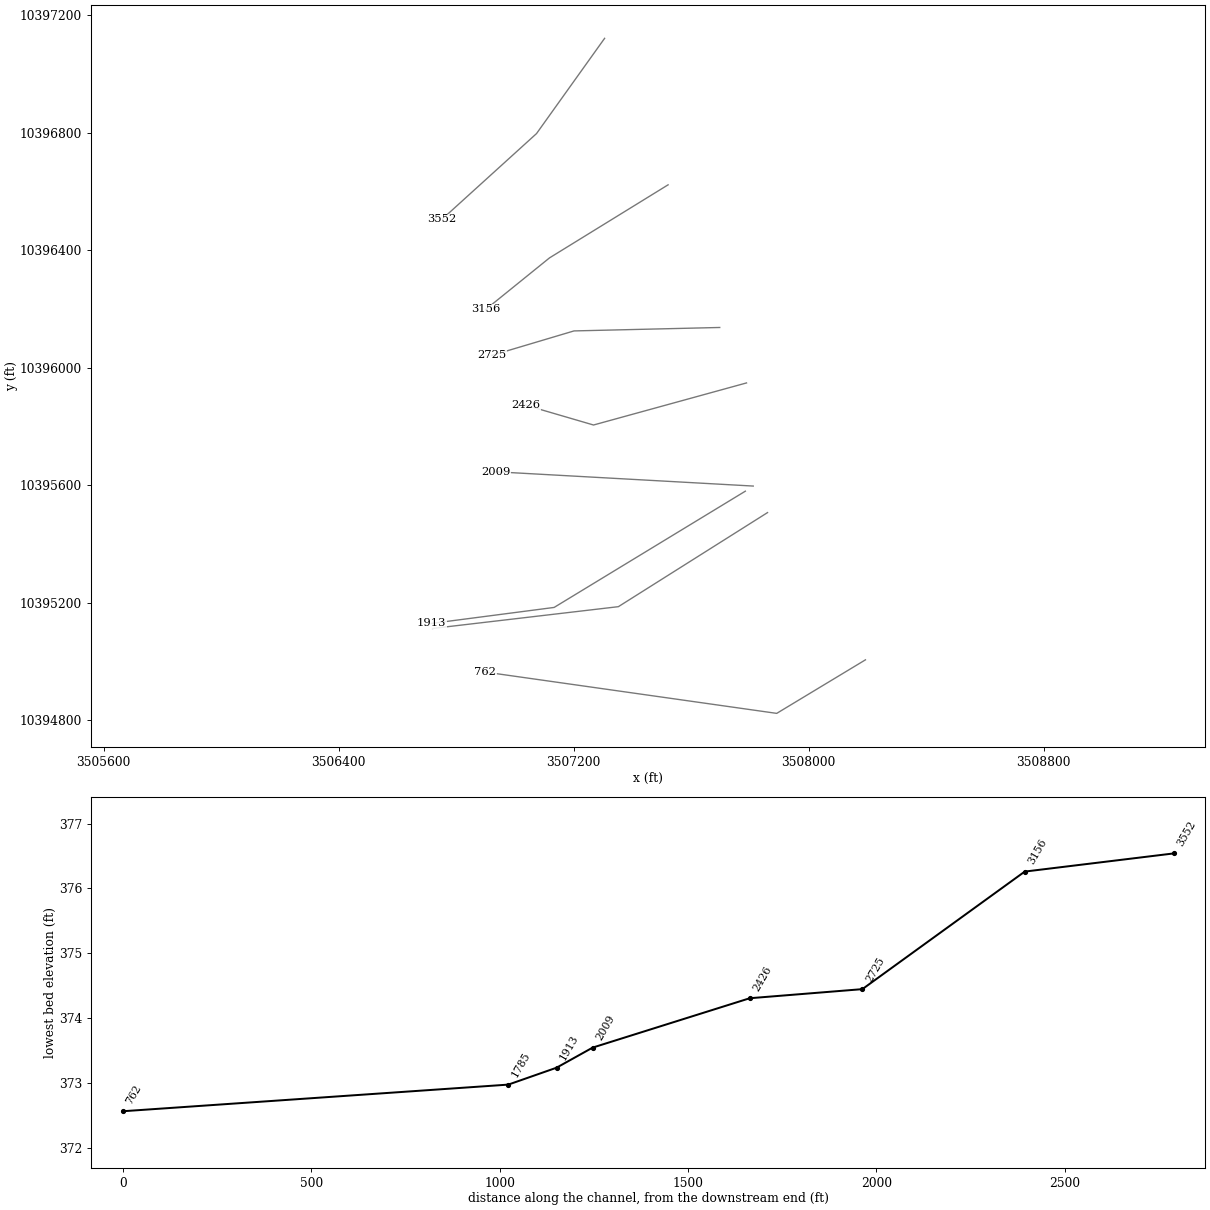
HEC-RAS study NORTH MINERAL CR TRIB 8 1.prj: NORTH MINERAL CR TRIB 8 1 Base Level Engineering

--- NORTH MINERAL CR TRIB 8 1.g01 (geometry) --- (continued)

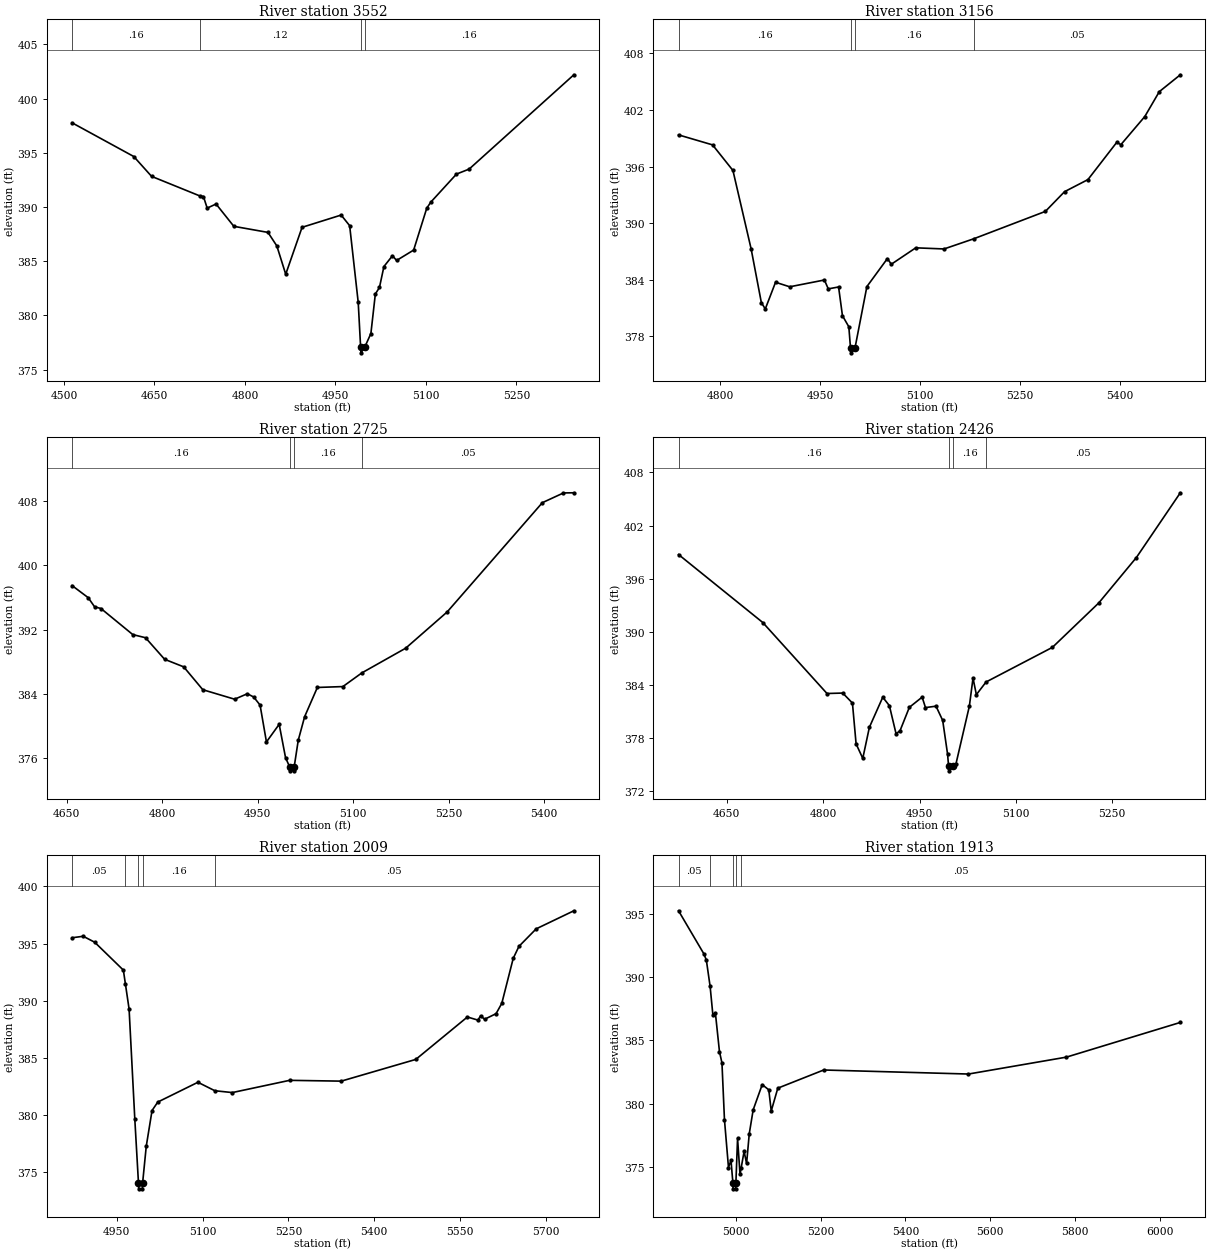
Type RM Length L Ch R = 1 ,3552    ,396,396,396
BEGIN DESCRIPTION:
NORTH MINERAL CR TRIB 8 1 8 0
END DESCRIPTION:
XS GIS Cut Line= 3
      3507305.49     10397121.49      3507073.71     10396797.26
      3506752.71     10396506.15
#Sta/Elev= 30
  4513.5  397.76  4615.8  394.65  4645.3  392.82  4725.5  391.01  4731.3  390.96
  4737.5  389.89  4752.2  390.27  4781.7  388.21  4838.3  387.65    4853   386.4
  4867.7  383.79  4894.8  388.12  4959.6  389.25  4973.7  388.27  4987.9  381.19
  4991.9  377.04  4992.4  376.54  4998.5  377.04  5008.9  378.32  5016.3  381.97
  5023.1  382.57  5030.5   384.5  5044.7   385.5  5051.5  385.06  5079.8  386.02
  5101.5  389.88  5108.2  390.44  5150.8  393.03  5171.8  393.49  5345.4  402.19
#Mann= 4 ,-1 , 0
  4513.5     .16       0  4725.5     .12       0  4991.9     .07       0
  4998.5     .16       0
Bank Sta=4991.9,4998.5
XS Rating Curve= 0 ,0
Exp/Cntr=0.3,0.1

Type RM Length L Ch R = 1 ,3156    ,431,431,431
BEGIN DESCRIPTION:
NORTH MINERAL CR TRIB 8 1 7 0
END DESCRIPTION:
XS GIS Cut Line= 3
      3507521.63     10396622.78      3507117.98     10396374.08
      3506900.56     10396198.32
#Sta/Elev= 30
    4737  399.36  4788.1   398.3  4818.7  395.59    4846  387.29  4861.4  381.58
  4867.3  380.91  4882.7  383.74    4904  383.26  4956.1  383.98  4961.9  383.04
  4977.4  383.24  4983.2   380.2  4992.8  379.02  4995.3  376.76  4995.8  376.26
    5002  376.76  5019.9  383.28  5050.7  386.25  5056.6  385.65  5093.3  387.39
  5135.8  387.27  5180.1  388.34    5288  391.25  5316.8  393.34  5351.9  394.62
  5395.1  398.56  5401.5  398.33  5437.3   401.3  5459.1  403.94  5490.7  405.73
#Mann= 4 ,-1 , 0
    4737     .16       0  4995.3     .07       0    5002     .16       0
  5180.1     .05       0
Bank Sta=4995.3,5002
XS Rating Curve= 0 ,0
Exp/Cntr=0.3,0.1

Type RM Length L Ch R = 1 ,2725    ,299,299,299
BEGIN DESCRIPTION:
NORTH MINERAL CR TRIB 8 1 6 0
END DESCRIPTION:
XS GIS Cut Line= 3
      3507697.45      10396137.1      3507201.32     10396125.38
      3506921.33     10396042.04
#Sta/Elev= 30
  4658.4  397.47  4683.7  395.97  4693.8  394.83  4703.8  394.62  4753.8  391.38
  4773.8  390.99  4803.8  388.31  4833.8  387.37  4863.8  384.53  4913.8  383.35
  4933.8  384.03  4943.8  383.62  4953.8  382.62  4963.8  378.04  4983.8  380.23
  4993.8  376.09  5000.2  374.95  5000.7  374.45  5006.9  374.45  5007.4  374.95
  5013.8  378.26  5023.8  381.18  5043.8  384.81  5083.9  384.92  5113.7  386.62
  5182.6  389.69  5247.7  394.19  5397.3  407.77  5430.5  408.98  5446.8     409
#Mann= 4 ,-1 , 0
  4658.4     .16       0  5000.2     .07       0  5007.4     .16       0
  5113.7     .05       0
Bank Sta=5000.2,5007.4
XS Rating Curve= 0 ,0
Exp/Cntr=0.3,0.1

Type RM Length L Ch R = 1 ,2426    ,417,417,417
BEGIN DESCRIPTION:
NORTH MINERAL CR TRIB 8 1 3 10
END DESCRIPTION:
XS GIS Cut Line= 3
      3507788.59     10395948.31      3507267.72     10395805.07
      3507036.49     10395872.62
#Sta/Elev= 30
  4574.8  398.73    4706  391.05  4805.9  383.04  4830.4  383.09  4845.5  381.96
  4851.2  377.35  4861.6  375.72  4871.9  379.23  4892.7  382.62    4903  381.67
  4913.4   378.5  4919.6  378.84  4934.1  381.48    4954  382.63  4959.2  381.45
  4975.6  381.61    4986     380  4993.6  376.19  4995.2  374.81  4995.7  374.31
  5002.4  374.81  5006.7  375.11  5027.5  381.61  5033.2  384.78  5038.4  382.91
  5053.5  384.34  5156.8  388.25  5228.9  393.26  5287.5  398.39  5355.9   405.7
#Mann= 4 ,-1 , 0
  4574.8     .16       0  4995.2     .07       0  5002.4     .16       0
  5053.5     .05       0
Bank Sta=4995.2,5002.4
XS Rating Curve= 0 ,0
Exp/Cntr=0.3,0.1

Type RM Length L Ch R = 1 ,2009    ,96,96,96
BEGIN DESCRIPTION:
NORTH MINERAL CR TRIB 8 1 3 20
END DESCRIPTION:
XS GIS Cut Line= 2
      3507811.54      10395597.2      3506936.39     10395645.75
#Sta/Elev= 30
  4872.1  395.51  4891.6  395.64  4911.6  395.12  4961.7  392.68  4965.3  391.46
  4971.7  389.28  4981.7  379.64  4988.1  374.05  4988.6  373.55  4994.8  373.55
  4995.3  374.05  5001.7  377.28  5011.8   380.4  5021.8  381.14  5091.9  382.87
  5121.5  382.13    5152  381.97  5252.1  383.04  5342.3  382.97  5472.5  384.87
  5562.6  388.58  5580.9  388.31  5585.9  388.69  5592.6  388.38  5612.7  388.87
  5622.7  389.77  5642.7  393.71  5652.7  394.76  5682.8  396.29  5748.6  397.87
#Mann= 5 ,-1 , 0
  4872.1     .05       0  4965.3     .16       0  4988.1     .07       0
  4995.3     .16       0  5121.5     .05       0
Bank Sta=4988.1,4995.3
XS Rating Curve= 0 ,0
Exp/Cntr=0.3,0.1

Type RM Length L Ch R = 1 ,1913    ,128,128,128
BEGIN DESCRIPTION:
NORTH MINERAL CR TRIB 8 1 2 10
END DESCRIPTION:
XS GIS Cut Line= 3
      3507784.62     10395579.79      3507133.61     10395183.98
      3506715.74     10395129.47
#Sta/Elev= 30
  4865.2  395.28  4924.9  391.87  4930.8  391.37  4939.7  389.28  4946.2  387.02
  4952.1  387.18  4961.7  384.12  4967.6  383.22  4973.5  378.72    4983  374.93
  4988.9  375.51  4993.3  373.74  4993.8  373.24    5000  373.24  5000.5  373.74
  5004.4  377.24  5010.2  374.38  5012.7  374.86  5019.8  376.21  5025.7  375.25
    5032  377.61  5041.2   379.5  5062.5   381.5    5078  381.09  5083.8  379.41
  5099.3  381.22  5207.5  382.66  5548.9  382.34  5779.9  383.68  6048.5  386.43
#Mann= 5 ,-1 , 0
  4865.2     .05       0  4939.7     .16       0  4993.3     .07       0
  5000.5     .16       0  5012.7     .05       0
Bank Sta=4993.3,5000.5
XS Rating Curve= 0 ,0
Exp/Cntr=0.3,0.1

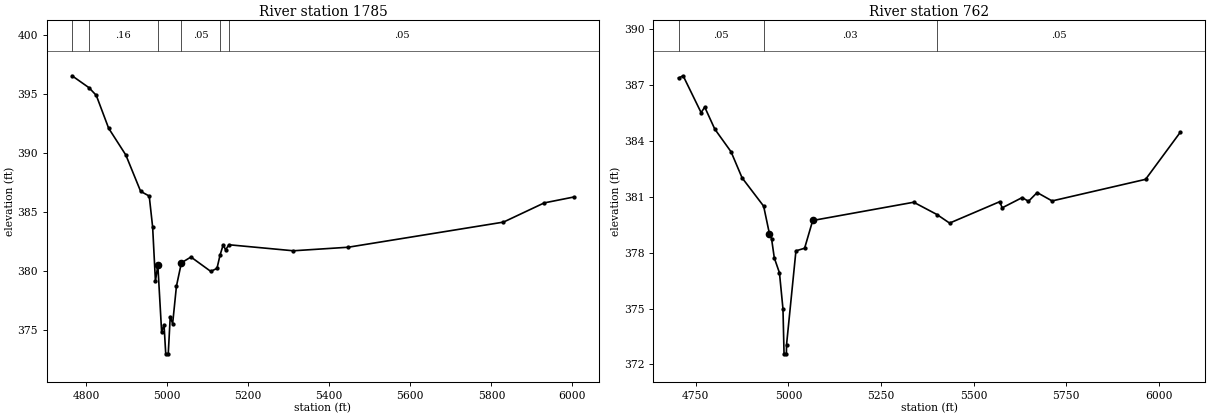
Type RM Length L Ch R = 1 ,1785    ,1023,1023,1023
BEGIN DESCRIPTION:
NORTH MINERAL CR TRIB 8 1 2 20
END DESCRIPTION:
XS GIS Cut Line= 3
      3507860.14     10395506.87      3507352.36     10395186.58
      3506719.55     10395112.36
#Sta/Elev= 30
  4765.9  396.56  4807.6  395.55  4825.6   394.9  4856.1  392.11  4898.5  389.84
    4935  386.76  4956.2  386.36  4964.6  383.73  4971.5  379.15  4977.4  380.51
  4986.8  374.82  4992.7  375.45  4996.9  372.98  5003.1  372.98    5008  376.14
  5013.9  375.53  5023.3  378.72  5035.5   380.7  5059.1  381.19    5108  379.97
  5123.3  380.23  5130.9  381.36  5138.6  382.22  5144.5   381.8  5152.8  382.23
  5311.6  381.72  5446.8  382.02  5829.7  384.15  5930.3  385.78  6003.4  386.28
#Mann= 6 ,-1 , 0
  4765.9     .05       0  4807.6     .16       0  4977.4     .04       0
  5035.5     .05       0  5130.9     .16       0  5152.8     .05       0
Bank Sta=4977.4,5035.5
XS Rating Curve= 0 ,0
Exp/Cntr=0.3,0.1

Type RM Length L Ch R = 1 ,762     ,0,0,0
BEGIN DESCRIPTION:
NORTH MINERAL CR TRIB 8 1 3 1
END DESCRIPTION:
XS GIS Cut Line= 3
      3508193.52      10395005.6      3507891.42      10394823.3
      3506899.28     10394963.92
#Sta/Elev= 30
  4703.2  387.38  4715.6   387.5  4764.2  385.52  4773.9  385.82    4801  384.64
    4845  383.42  4874.8  382.02    4933   380.5  4948.5  379.03  4954.4  378.75
  4961.8  377.72  4975.7  376.92  4985.2  374.98  4988.1  372.57  4994.4  372.57
  4994.9  373.07  5020.2   378.1  5043.6  378.24  5065.5  379.73  5338.2  380.71
    5401  380.05  5435.1  379.59  5570.5  380.74  5577.1  380.41  5631.1  380.96
  5648.1  380.76  5671.5  381.23  5711.9  380.78  5964.3  381.94  6058.1  384.47
#Mann= 3 ,-1 , 0
  4703.2     .05       0    4933     .03       0    5401     .05       0
Bank Sta=4948.5,5065.5
XS Rating Curve= 0 ,0
Exp/Cntr=0.3,0.1

Chan Stop Cuts=-1
Use User Specified Reach Order=0
Composite Channel Slope=5