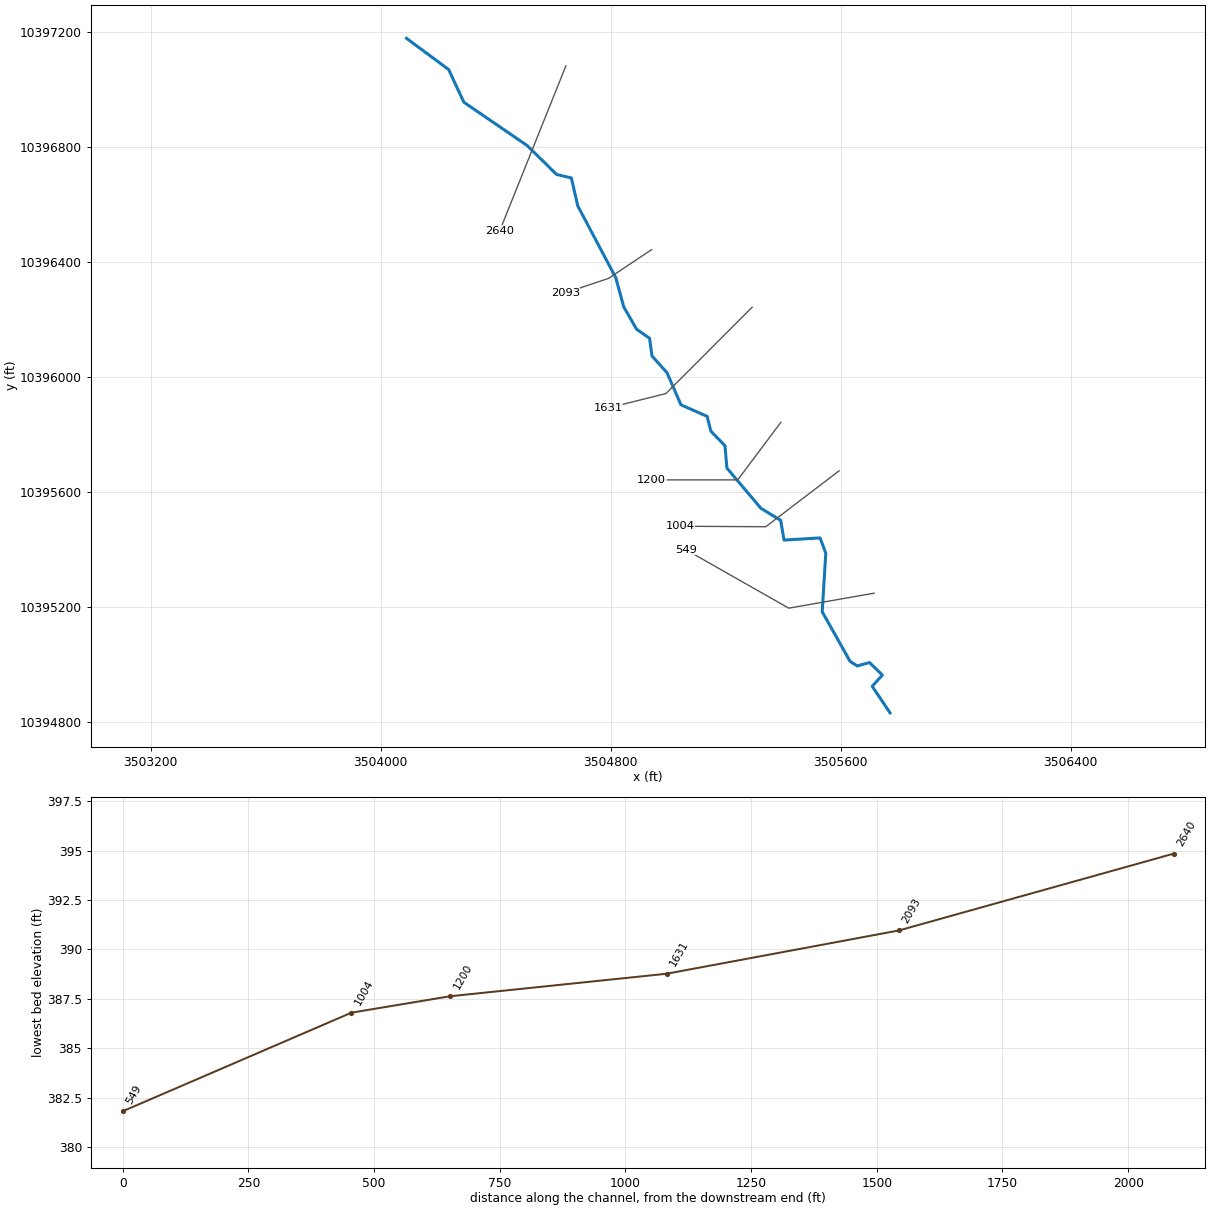
--- NORTH MINERAL CR TRIB 8 2.prj (project) ---

Proj Title=NORTH MINERAL CR TRIB 8 2 Base Level Engineering
Current Plan=p01
Default Exp/Contr=0.3,0.1
English Units
Geom File=g01
Flow File=f01
Plan File=p01
BEGIN DESCRIPTION:
NORTH MINERAL CR TRIB 8 2
END DESCRIPTION:

--- NORTH MINERAL CR TRIB 8 2.p01 (plan) ---

Plan Title=Multiple Run
Short Identifier=Multiple
Geom File=g01
Flow File=f01
Subcritical Flow
K Sum by GR= 0
Std Step Tol= 0.01
Critical Tol= 0.01
Num of Std Step Trials= 20
Max Error Tol= 0.3
Flow Tol Ratio= 0.001
Split Flow NTrial= 30
Split Flow Tol= 0.02
Split Flow Ratio= 0.02
Log Output Level= 0
Friction Slope Method= 1
Unsteady Friction Slope Method= 2
Unsteady Bridges Friction Slope Method= 1
Parabolic Critical Depth
Global Vel Dist=  1 , 1 , 1
Global Log Level= 0
CheckData=True
Encroach Param= -1, 0, 0, 0
BEGIN DESCRIPTION:
Multiple Run
END DESCRIPTION:

--- NORTH MINERAL CR TRIB 8 2.f01 (steady flow) ---

Flow Title=Multiple
Number of Profiles=7
Profile Names=10-year,25-year,50-year,1pct_min,100-year,1pct_plu,500-year
River Rch & RM= NORTH MINERAL CR,Reach-1,2640
     345     447     527     455     615     832     835
Boundary for River Rch & Prof#=NORTH MINERAL CR,Reach-1,1
Up Type=0
Dn Type=3
Dn Slope=0.005
Boundary for River Rch & Prof#=NORTH MINERAL CR,Reach-1,2
Up Type=0
Dn Type=3
Dn Slope=0.005
Boundary for River Rch & Prof#=NORTH MINERAL CR,Reach-1,3
Up Type=0
Dn Type=3
Dn Slope=0.005
Boundary for River Rch & Prof#=NORTH MINERAL CR,Reach-1,4
Up Type=0
Dn Type=3
Dn Slope=0.005
Boundary for River Rch & Prof#=NORTH MINERAL CR,Reach-1,5
Up Type=0
Dn Type=3
Dn Slope=0.005
Boundary for River Rch & Prof#=NORTH MINERAL CR,Reach-1,6
Up Type=0
Dn Type=3
Dn Slope=0.005
Boundary for River Rch & Prof#=NORTH MINERAL CR,Reach-1,7
Up Type=0
Dn Type=3
Dn Slope=0.005

--- NORTH MINERAL CR TRIB 8 2.g01 (geometry) ---

Geom Title=Existing Conditions

River Reach=NORTH MINERAL CR,Reach-1
Reach XY= 30
      3504089.82     10397176.34      3504236.30     10397068.00
      3504289.26     10396954.29      3504509.40     10396803.81
      3504612.02     10396703.23      3504663.36     10396690.90
      3504685.96     10396593.27      3504817.76     10396344.55
      3504845.57     10396243.06      3504890.02     10396165.42
      3504935.41     10396133.72      3504943.81     10396072.49
      3504996.19     10396013.95      3505044.54     10395902.49
      3505135.62     10395862.41      3505148.76     10395810.79
      3505197.78     10395760.30      3505204.40     10395682.71
      3505323.09     10395542.57      3505391.36     10395501.22
      3505403.03     10395432.50      3505528.71     10395439.97
      3505548.42     10395386.91      3505535.97     10395183.31
      3505632.70     10395011.31      3505657.56     10394994.90
      3505700.62     10395006.76      3505745.34     10394963.36
      3505709.87     10394924.20      3505772.11     10394831.64

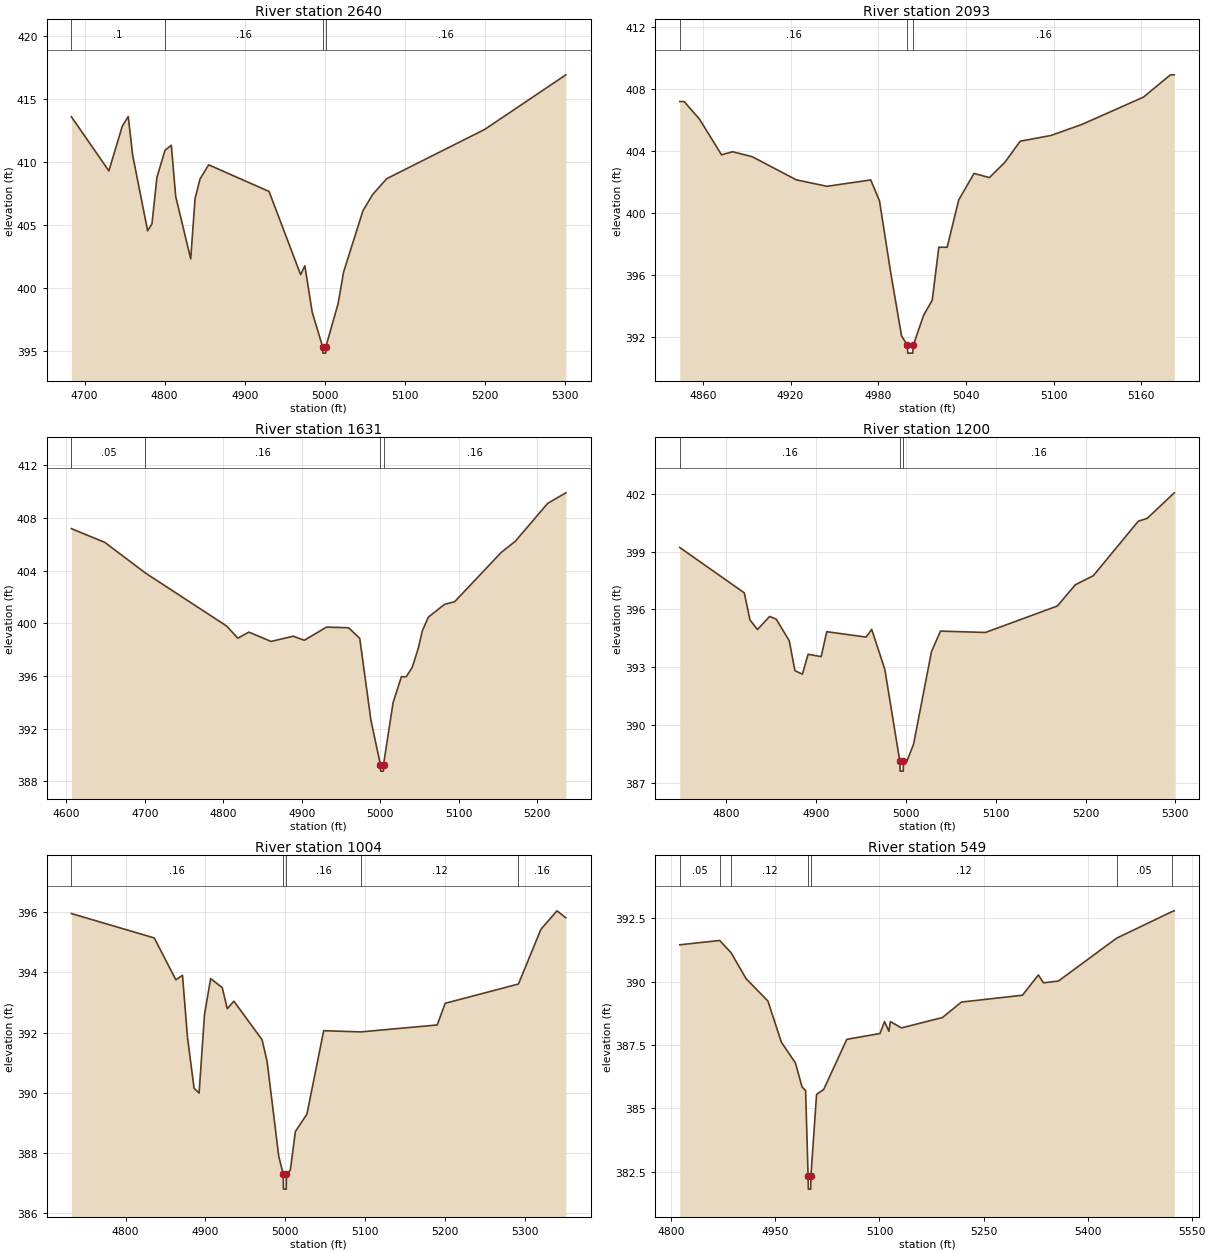
Type RM Length L Ch R = 1,2640,547,547,547
BEGIN DESCRIPTION:
NORTH MINERAL CR TRIB 8 2 8 0
END DESCRIPTION:
XS GIS Cut Line= 2
      3504644.32     10397080.71      3504414.28     10396507.76
#Sta/Elev= 30
  4683.6  413.58  4730.4  409.29  4747.2  412.84  4754.6  413.60  4760.0  410.57
  4778.8  404.54  4784.2  405.09  4790.4  408.78  4800.5  410.92  4808.4  411.32
  4813.8  407.28  4832.6  402.32  4838.0  407.09  4844.2  408.64  4855.0  409.77
  4930.4  407.66  4969.8  401.07  4975.1  401.77  4984.3  398.09  4997.3  395.35
  4997.6  394.85  5001.1  394.85  5001.3  395.35  5016.6  398.77  5023.5  401.28
  5047.7  406.14  5059.8  407.42  5077.3  408.67  5199.8  412.58  5301.0  416.90
#Mann=4,-1,0
  4683.6     0.1       0  4800.5    0.16       0  4997.3    0.07       0
  5001.3    0.16       0
Bank Sta=4997.3,5001.3
Exp/Cntr=0.3,0.1

Type RM Length L Ch R = 1,2093,462,462,462
BEGIN DESCRIPTION:
NORTH MINERAL CR TRIB 8 2 7 0
END DESCRIPTION:
XS GIS Cut Line= 3
      3504942.14     10396441.66      3504792.11     10396341.64
      3504642.13     10396291.65
#Sta/Elev= 30
  4844.2  407.19  4847.2  407.19  4857.8  406.04  4872.8  403.75  4880.3  403.95
  4893.8  403.63  4923.9  402.14  4944.9  401.72  4974.9  402.13  4980.9  400.78
  4988.5  396.19  4996.0  392.07  5000.0  391.46  5000.2  390.96  5003.7  390.96
  5004.0  391.46  5011.0  393.38  5017.0  394.38  5021.5  397.79  5027.2  397.79
  5035.1  400.84  5045.6  402.55  5056.1  402.28  5066.7  403.27  5077.2  404.63
  5098.3  405.00  5119.4  405.71  5161.5  407.47  5180.0  408.91  5182.6  408.91
#Mann=3,-1,0
  4844.2    0.16       0  5000.0    0.07       0  5004.0    0.16       0
Bank Sta=5000,5004
Exp/Cntr=0.3,0.1

Type RM Length L Ch R = 1,1631,431,431,431
BEGIN DESCRIPTION:
NORTH MINERAL CR TRIB 8 2 6 0
END DESCRIPTION:
XS GIS Cut Line= 3
      3505292.13     10396241.67      3504992.11     10395941.64
      3504792.06     10395891.63
#Sta/Elev= 30
  4606.3  407.19  4648.8  406.15  4700.7  403.82  4804.3  399.79  4818.5  398.87
  4832.6  399.33  4860.9  398.62  4889.2  399.02  4903.3  398.71  4931.6  399.71
  4959.9  399.66  4974.0  398.85  4988.2  392.65  5000.3  389.27  5000.6  388.77
  5004.1  388.77  5004.3  389.27  5016.5  393.98  5027.1  395.94  5033.2  395.94
  5040.9  396.65  5048.6  398.10  5053.8  399.43  5061.5  400.47  5082.1  401.44
  5095.0  401.64  5154.3  405.38  5172.3  406.23  5213.6  409.11  5236.8  409.91
#Mann=4,-1,0
  4606.3    0.05       0  4700.7    0.16       0  5000.3    0.07       0
  5004.3    0.16       0
Bank Sta=5000.3,5004.3
Exp/Cntr=0.3,0.1

Type RM Length L Ch R = 1,1200,196,196,196
BEGIN DESCRIPTION:
NORTH MINERAL CR TRIB 8 2 4 0
END DESCRIPTION:
XS GIS Cut Line= 3
      3505392.08     10395841.61      3505242.11     10395641.64
      3504942.07     10395641.64
#Sta/Elev= 30
  4748.7  399.21  4820.5  396.86  4826.8  395.46  4835.1  394.96  4848.7  395.64
  4856.0  395.50  4870.5  394.38  4876.8  392.83  4885.1  392.65  4891.4  393.68
  4906.0  393.56  4912.2  394.85  4956.0  394.57  4962.2  394.97  4976.8  392.90
  4993.5  388.13  4993.8  387.63  4997.3  387.63  4997.5  388.13  5001.2  388.13
  5008.7  389.01  5028.7  393.82  5038.7  394.88  5088.7  394.81  5168.7  396.18
  5188.7  397.28  5208.7  397.75  5258.7  400.57  5268.7  400.72  5298.7  402.04
#Mann=3,-1,0
  4748.7    0.16       0  4993.5    0.07       0  4997.5    0.16       0
Bank Sta=4993.5,4997.5
Exp/Cntr=0.3,0.1

Type RM Length L Ch R = 1,1004,455,455,455
BEGIN DESCRIPTION:
Mapping XS 31897380
END DESCRIPTION:
XS GIS Cut Line= 3
      3505594.82     10395673.24      3505339.62     10395478.80
      3505040.96     10395480.54
#Sta/Elev= 30
  4732.2  395.95  4836.0  395.14  4863.1  393.75  4871.4  393.90  4877.6  391.85
  4885.9  390.15  4892.2  389.99  4899.0  392.61  4906.7  393.79  4921.2  393.49
  4927.5  392.79  4935.8  393.04  4971.1  391.76  4977.4  391.04  4992.0  387.89
  4997.6  387.30  4997.9  386.80  5001.4  386.80  5001.6  387.30  5006.5  387.43
  5012.8  388.71  5027.3  389.29  5048.3  392.06  5094.7  392.02  5190.5  392.25
  5200.5  392.97  5292.3  393.61  5320.5  395.43  5340.6  396.04  5351.7  395.81
#Mann=5,-1,0
  4732.2    0.16       0  4997.6    0.07       0  5001.6    0.16       0
  5094.7    0.12       0  5292.3    0.16       0
Bank Sta=4997.6,5001.6
Exp/Cntr=0.3,0.1

Type RM Length L Ch R = 1,549,0,0,0
BEGIN DESCRIPTION:
NORTH MINERAL CR TRIB 8 2 1 0
END DESCRIPTION:
XS GIS Cut Line= 3
      3505716.34     10395247.89      3505419.48     10395195.81
      3505061.83     10395398.94
#Sta/Elev= 30
  4812.2  391.45  4869.8  391.62  4886.1  391.14  4907.9  390.11  4939.3  389.23
  4958.6  387.61  4978.9  386.79  4988.5  385.84  4993.6  385.70  4997.2  382.31
  4997.5  381.81  5001.0  381.81  5001.2  382.31  5009.4  385.55  5019.6  385.74
  5053.0  387.72  5100.8  387.95  5107.3  388.42  5113.6  388.04  5115.8  388.42
  5131.7  388.17  5190.8  388.58  5218.2  389.19  5306.1  389.46  5329.1  390.26
  5336.4  389.95  5358.0  390.02  5441.8  391.71  5521.0  392.75  5524.9  392.79
#Mann=7,-1,0
  4812.2    0.05       0  4869.8    0.16       0  4886.1    0.12       0
  4997.2    0.07       0  5001.2    0.12       0  5441.8    0.05       0
  5521.0    0.12       0
Bank Sta=4997.2,5001.2
Exp/Cntr=0.3,0.1

Chan Stop Cuts=-1