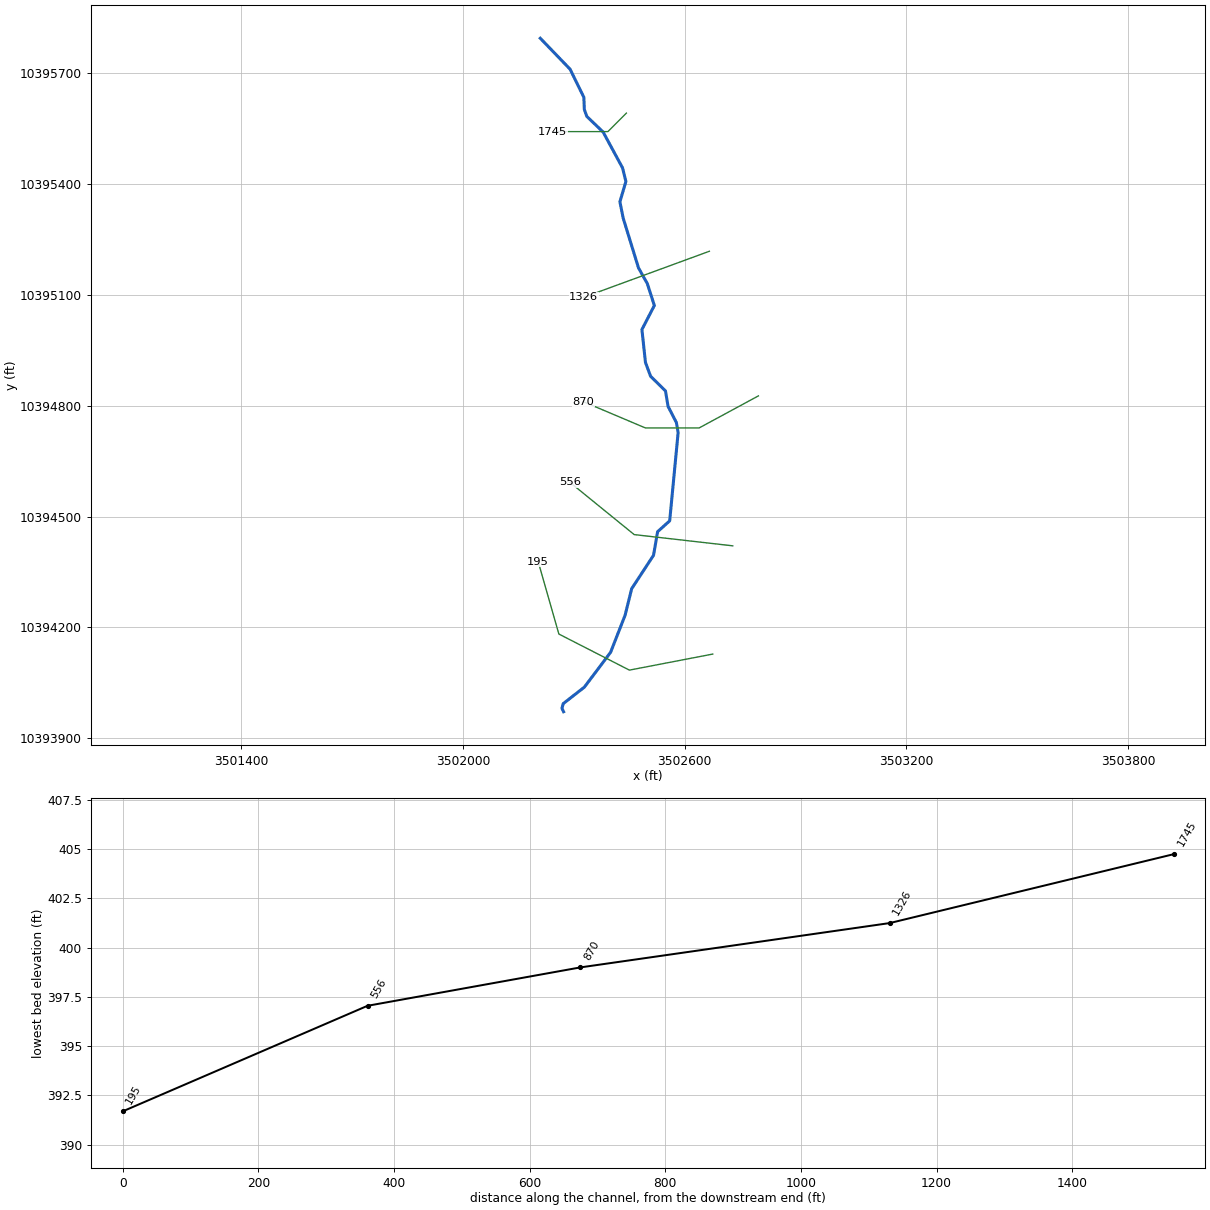
--- NORTH MINERAL CR TRIB 8 3.prj (project) ---

Proj Title=NORTH MINERAL CR TRIB 8 3 Base Level Engineering
Current Plan=p01
Default Exp/Contr=0.3,0.1
English Units
Geom File=g01
Flow File=f01
Plan File=p01
BEGIN DESCRIPTION:
NORTH MINERAL CR TRIB 8 3
END DESCRIPTION:

--- NORTH MINERAL CR TRIB 8 3.p01 (plan) ---

Plan Title=Multiple Run
Short Identifier=Multiple
Geom File=g01
Flow File=f01
Subcritical Flow
K Sum by GR= 0
Std Step Tol= 0.01
Critical Tol= 0.01
Num of Std Step Trials= 20
Max Error Tol= 0.3
Flow Tol Ratio= 0.001
Split Flow NTrial= 30
Split Flow Tol= 0.02
Split Flow Ratio= 0.02
Log Output Level= 0
Friction Slope Method= 1
Unsteady Friction Slope Method= 2
Unsteady Bridges Friction Slope Method= 1
Parabolic Critical Depth
Global Vel Dist=  1 , 1 , 1
Global Log Level= 0
CheckData=True
Encroach Param= -1, 0, 0, 0
BEGIN DESCRIPTION:
Multiple Run
END DESCRIPTION:

--- NORTH MINERAL CR TRIB 8 3.f01 (steady flow) ---

Flow Title=Multiple
Number of Profiles=7
Profile Names=10-year,25-year,50-year,1pct_min,100-year,1pct_plu,500-year
River Rch & RM= NORTH MINERAL CR,Reach-1,1745
     286     366     427     365     494     668     657
Boundary for River Rch & Prof#=NORTH MINERAL CR,Reach-1,1
Up Type=0
Dn Type=3
Dn Slope=0.005
Boundary for River Rch & Prof#=NORTH MINERAL CR,Reach-1,2
Up Type=0
Dn Type=3
Dn Slope=0.005
Boundary for River Rch & Prof#=NORTH MINERAL CR,Reach-1,3
Up Type=0
Dn Type=3
Dn Slope=0.005
Boundary for River Rch & Prof#=NORTH MINERAL CR,Reach-1,4
Up Type=0
Dn Type=3
Dn Slope=0.005
Boundary for River Rch & Prof#=NORTH MINERAL CR,Reach-1,5
Up Type=0
Dn Type=3
Dn Slope=0.005
Boundary for River Rch & Prof#=NORTH MINERAL CR,Reach-1,6
Up Type=0
Dn Type=3
Dn Slope=0.005
Boundary for River Rch & Prof#=NORTH MINERAL CR,Reach-1,7
Up Type=0
Dn Type=3
Dn Slope=0.005

--- NORTH MINERAL CR TRIB 8 3.g01 (geometry) ---

Geom Title=Existing Conditions

River Reach=NORTH MINERAL CR,Reach-1
Reach XY= 30
      3502209.01     10395794.27      3502289.64     10395710.61
      3502327.03     10395634.40      3502328.27     10395601.58
      3502335.01     10395582.73      3502379.23     10395540.41
      3502431.81     10395443.35      3502440.85     10395406.71
      3502424.62     10395351.63      3502433.51     10395307.39
      3502474.96     10395172.81      3502498.85     10395130.16
      3502517.91     10395071.02      3502484.22     10395005.97
      3502493.81     10394916.95      3502507.77     10394879.48
      3502548.00     10394839.85      3502555.01     10394797.89
      3502577.54     10394754.38      3502582.23     10394726.65
      3502559.40     10394488.19      3502526.74     10394458.92
      3502515.62     10394394.97      3502456.46     10394304.55
      3502438.75     10394233.03      3502399.51     10394132.71
      3502328.49     10394038.29      3502271.08     10393993.46
      3502267.69     10393980.84      3502272.11     10393971.64

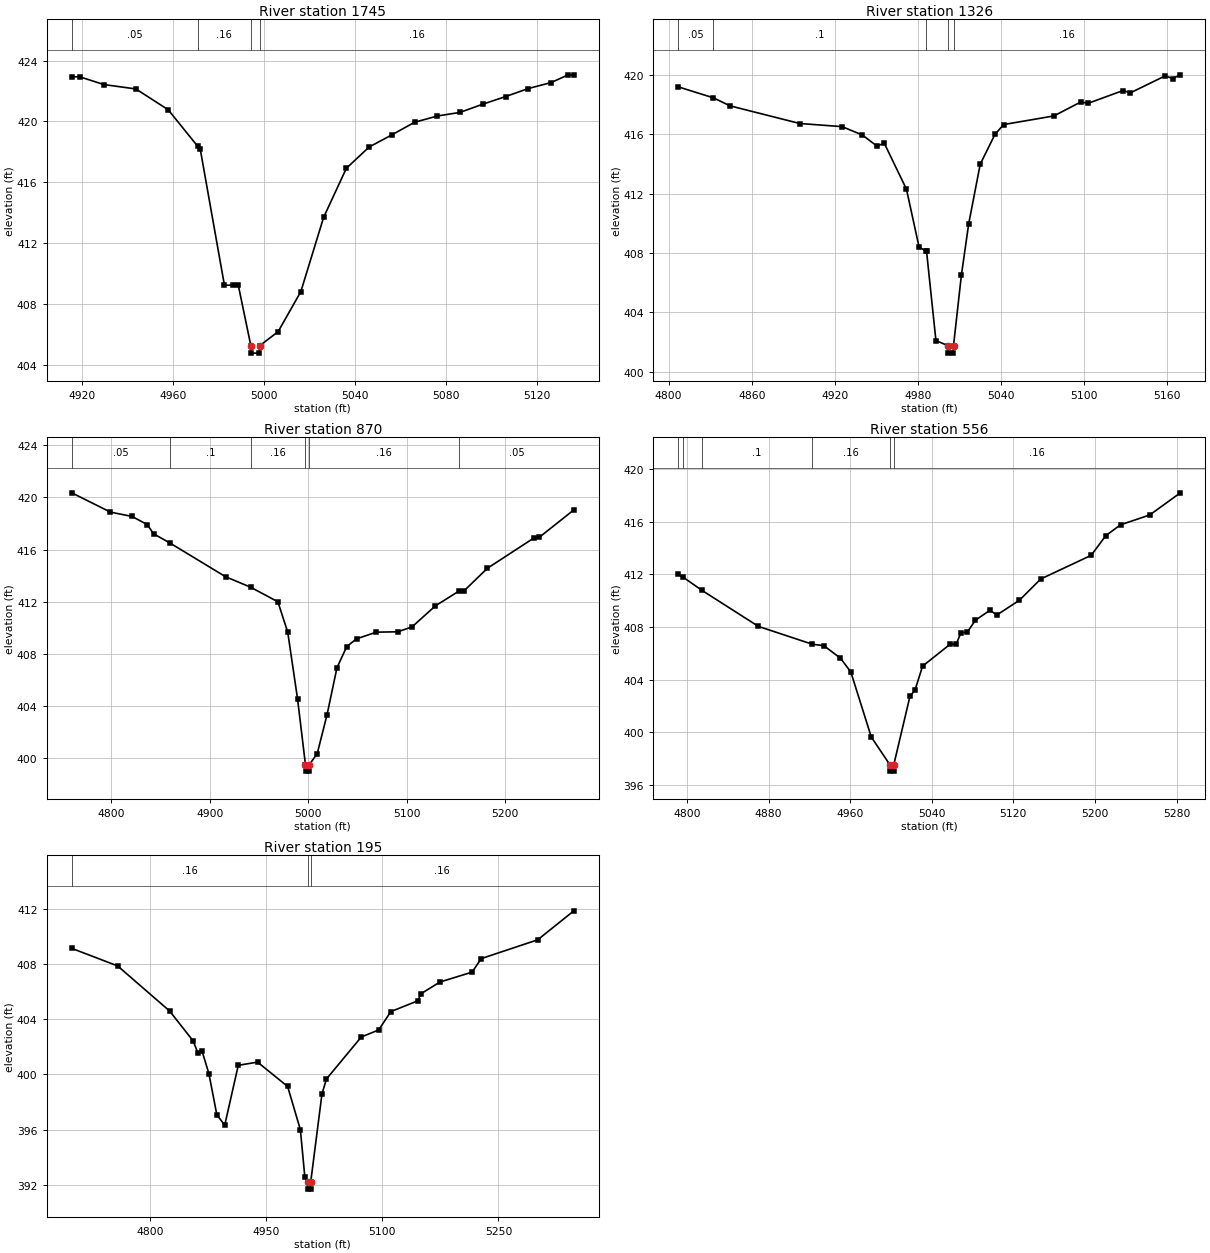
Type RM Length L Ch R = 1,1745,419,419,419
BEGIN DESCRIPTION:
NORTH MINERAL CR TRIB 8 3 2 0
END DESCRIPTION:
XS GIS Cut Line= 3
      3502442.08     10395591.61      3502392.11     10395541.64
      3502242.07     10395541.64
#Sta/Elev= 29
  4915.6  422.93  4919.1  422.93  4929.7  422.42  4943.8  422.13  4958.0  420.76
  4971.0  418.35  4972.1  418.15  4982.7  409.22  4986.3  409.22  4988.8  409.22
  4994.3  405.25  4994.5  404.75  4998.0  404.75  4998.3  405.25  5006.3  406.16
  5016.3  408.80  5026.3  413.68  5036.3  416.91  5046.3  418.31  5056.3  419.11
  5066.3  419.94  5076.3  420.35  5086.3  420.59  5096.3  421.13  5106.3  421.63
  5116.3  422.16  5126.3  422.55  5133.8  423.06  5136.3  423.06
#Mann=4,-1,0
  4915.6    0.05       0  4971.0    0.16       0  4994.3    0.07       0
  4998.3    0.16       0
Bank Sta=4994.3,4998.3
Exp/Cntr=0.3,0.1

Type RM Length L Ch R = 1,1326,456,456,456
BEGIN DESCRIPTION:
NORTH MINERAL CR TRIB 8 3 3 0
END DESCRIPTION:
XS GIS Cut Line= 2
      3502666.87     10395217.84      3502326.41     10395093.09
#Sta/Elev= 30
  4806.9  419.19  4832.3  418.45  4844.3  417.91  4894.7  416.72  4925.2  416.51
  4939.8  415.95  4950.4  415.20  4955.7  415.39  4971.7  412.30  4980.9  408.37
  4985.7  408.16  4986.2  408.14  4993.0  402.10  5001.7  401.75  5001.9  401.25
  5005.4  401.25  5005.7  401.75  5011.4  406.51  5016.7  409.98  5025.0  413.98
  5035.6  415.98  5041.9  416.65  5078.2  417.23  5097.6  418.17  5102.9  418.08
  5128.1  418.94  5133.5  418.79  5158.6  419.93  5164.0  419.75  5169.5  420.00
#Mann=5,-1,0
  4806.9    0.05       0  4832.3     0.1       0  4985.7    0.16       0
  5001.7    0.07       0  5005.7    0.16       0
Bank Sta=5001.7,5005.7
Exp/Cntr=0.3,0.1

Type RM Length L Ch R = 1,870,314,314,314
BEGIN DESCRIPTION:
NORTH MINERAL CR TRIB 8 3 4 0
END DESCRIPTION:
XS GIS Cut Line= 4
      3502799.66     10394826.44      3502639.10     10394739.65
      3502493.70     10394739.65      3502325.73     10394810.71
#Sta/Elev= 30
  4759.7  420.35  4799.0  418.87  4820.9  418.54  4836.5  417.91  4842.8  417.21
  4859.7  416.49  4916.1  413.91  4941.5  413.11  4969.2  411.99  4979.2  409.66
  4989.2  404.53  4997.2  399.50  4997.5  399.00  5001.0  399.00  5001.2  399.50
  5009.2  400.35  5019.2  403.34  5029.2  406.92  5039.2  408.56  5049.2  409.15
  5069.2  409.66  5091.2  409.69  5105.6  410.07  5129.3  411.68  5153.4  412.82
  5158.4  412.83  5182.1  414.56  5229.5  416.89  5234.9  416.94  5270.0  419.04
#Mann=6,-1,0
  4759.7    0.05       0  4859.7     0.1       0  4941.5    0.16       0
  4997.2    0.07       0  5001.2    0.16       0  5153.4    0.05       0
Bank Sta=4997.2,5001.2
Exp/Cntr=0.3,0.1

Type RM Length L Ch R = 1,556,361,361,361
BEGIN DESCRIPTION:
Mapping XS d8bfafd4
END DESCRIPTION:
XS GIS Cut Line= 3
      3502730.20     10394420.64      3502463.31     10394451.02
      3502289.71     10394592.08
#Sta/Elev= 30
  4791.4  412.00  4795.8  411.81  4814.6  410.79  4870.0  408.05  4923.0  406.69
  4934.1  406.59  4950.5  405.63  4960.6  404.59  4980.7  399.64  4998.8  397.55
  4999.1  397.05  5002.6  397.05  5002.8  397.55  5018.6  402.73  5023.6  403.22
  5031.0  405.03  5058.1  406.70  5064.0  406.70  5068.5  407.56  5074.9  407.62
  5082.8  408.52  5097.2  409.28  5103.7  408.91  5126.0  410.04  5146.8  411.65
  5196.3  413.45  5210.7  414.95  5225.1  415.77  5253.8  416.52  5283.7  418.20
#Mann=6,-1,0
  4791.4     0.1       0  4795.8    0.05       0  4814.6     0.1       0
  4923.0    0.16       0  4998.8    0.07       0  5002.8    0.16       0
Bank Sta=4998.8,5002.8
Exp/Cntr=0.3,0.1

Type RM Length L Ch R = 1,195,0,0,0
BEGIN DESCRIPTION:
NORTH MINERAL CR TRIB 8 3 1 0
END DESCRIPTION:
XS GIS Cut Line= 4
      3502676.01     10394127.68      3502450.29     10394084.27
      3502259.32     10394181.92      3502203.29     10394378.03
#Sta/Elev= 30
  4699.0  409.13  4758.2  407.86  4825.2  404.60  4855.7  402.43  4862.1  401.52
  4867.2  401.69  4876.1  400.05  4886.3  397.08  4896.5  396.32  4914.0  400.66
  4938.9  400.89  4977.7  399.13  4994.2  395.99  4999.9  392.59  5003.5  392.19
  5003.8  391.69  5007.3  391.69  5007.5  392.19  5022.1  398.60  5027.9  399.67
  5072.8  402.71  5095.3  403.22  5111.0  404.55  5145.8  405.33  5149.8  405.84
  5174.3  406.69  5215.9  407.41  5227.8  408.39  5300.6  409.75  5347.3  411.85
#Mann=3,-1,0
  4699.0    0.16       0  5003.5    0.07       0  5007.5    0.16       0
Bank Sta=5003.5,5007.5
Exp/Cntr=0.3,0.1

Chan Stop Cuts=-1