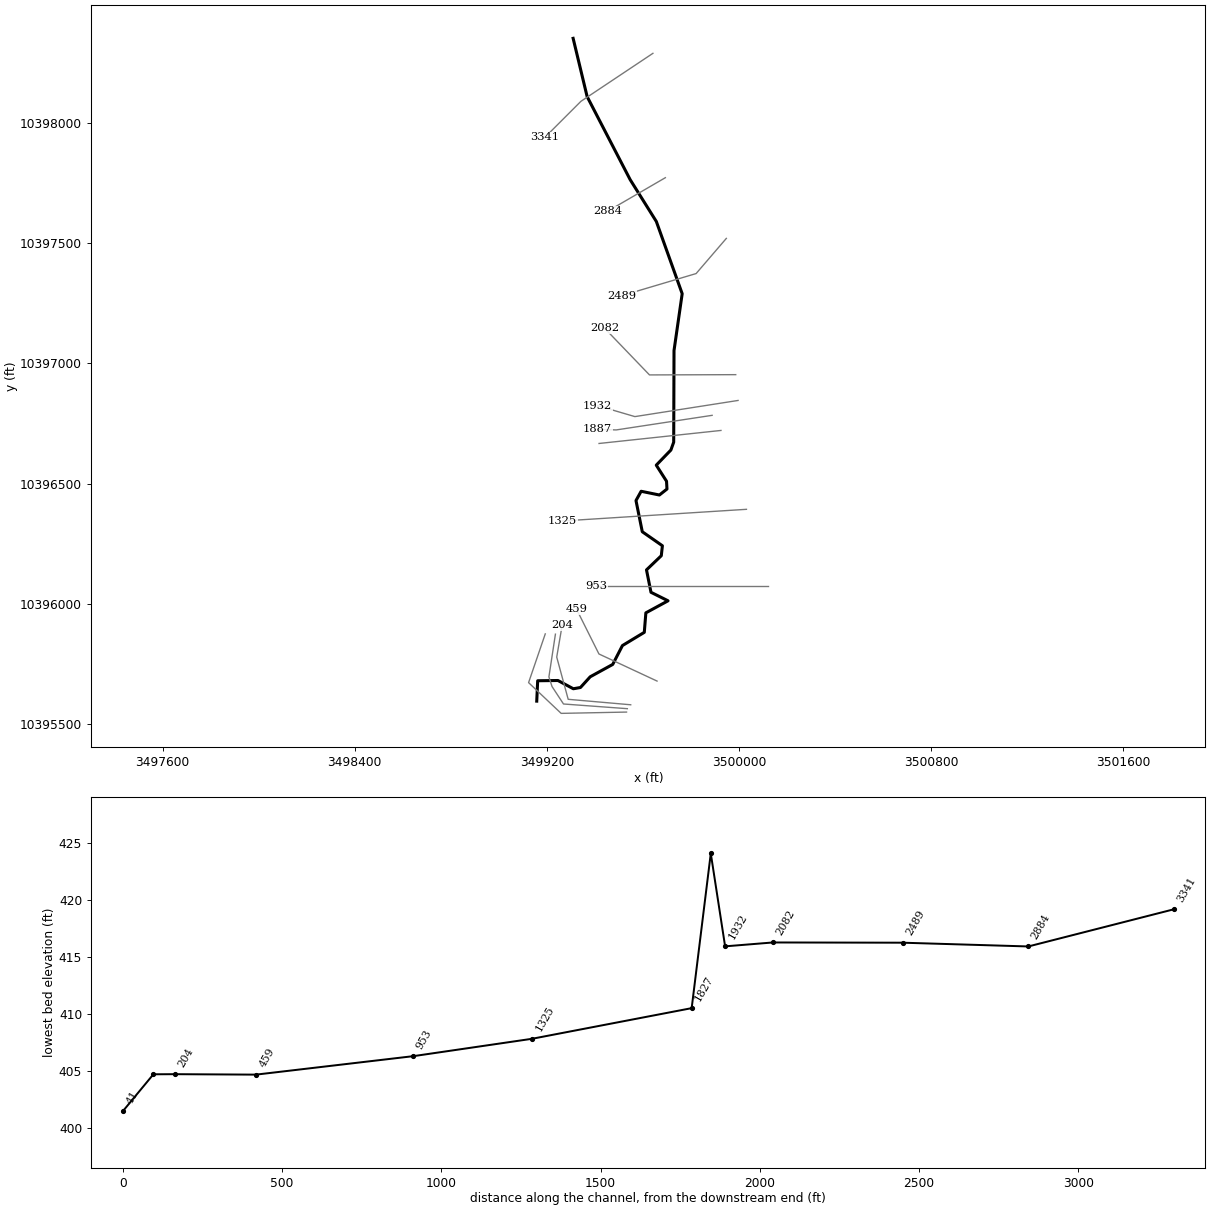
--- NORTH MINERAL CR TRIB 8 4.prj (project) ---

Proj Title=NORTH MINERAL CR TRIB 8 4 Base Level Engineering
Current Plan=p01
Default Exp/Contr=0.3,0.1
English Units
Geom File=g01
Flow File=f01
Plan File=p01
BEGIN DESCRIPTION:
NORTH MINERAL CR TRIB 8 4
END DESCRIPTION:

--- NORTH MINERAL CR TRIB 8 4.p01 (plan) ---

Plan Title=Multiple Run
Short Identifier=Multiple
Geom File=g01
Flow File=f01
Subcritical Flow
K Sum by GR= 0
Std Step Tol= 0.01
Critical Tol= 0.01
Num of Std Step Trials= 20
Max Error Tol= 0.3
Flow Tol Ratio= 0.001
Split Flow NTrial= 30
Split Flow Tol= 0.02
Split Flow Ratio= 0.02
Log Output Level= 0
Friction Slope Method= 1
Unsteady Friction Slope Method= 2
Unsteady Bridges Friction Slope Method= 1
Parabolic Critical Depth
Global Vel Dist=  1 , 1 , 1
Global Log Level= 0
CheckData=True
Encroach Param= -1, 0, 0, 0
BEGIN DESCRIPTION:
Multiple Run
END DESCRIPTION:

--- NORTH MINERAL CR TRIB 8 4.f01 (steady flow) ---

Flow Title=Multiple
Number of Profiles=7
Profile Names=10-year,25-year,50-year,1pct_min,100-year,1pct_plu,500-year
River Rch & RM= NORTH MINERAL CR,Reach-1,3341
     540     721     866     761    1029    1392    1448
River Rch & RM= NORTH MINERAL CR,Reach-1,41
    2337    3349    4214    3853    5211    7047    7961
Boundary for River Rch & Prof#=NORTH MINERAL CR,Reach-1,1
Up Type=0
Dn Type=3
Dn Slope=0.005
Boundary for River Rch & Prof#=NORTH MINERAL CR,Reach-1,2
Up Type=0
Dn Type=3
Dn Slope=0.005
Boundary for River Rch & Prof#=NORTH MINERAL CR,Reach-1,3
Up Type=0
Dn Type=3
Dn Slope=0.005
Boundary for River Rch & Prof#=NORTH MINERAL CR,Reach-1,4
Up Type=0
Dn Type=3
Dn Slope=0.005
Boundary for River Rch & Prof#=NORTH MINERAL CR,Reach-1,5
Up Type=0
Dn Type=3
Dn Slope=0.005
Boundary for River Rch & Prof#=NORTH MINERAL CR,Reach-1,6
Up Type=0
Dn Type=3
Dn Slope=0.005
Boundary for River Rch & Prof#=NORTH MINERAL CR,Reach-1,7
Up Type=0
Dn Type=3
Dn Slope=0.005

--- NORTH MINERAL CR TRIB 8 4.g01 (geometry) ---

Geom Title=Existing Conditions

River Reach=NORTH MINERAL CR,Reach-1
Reach XY= 30
      3499309.78     10398354.07      3499368.12     10398111.41
      3499547.29     10397765.58      3499656.32     10397591.28
      3499763.95     10397290.58      3499729.93     10397053.78
      3499728.63     10396672.42      3499716.91     10396639.55
      3499655.99     10396576.57      3499698.78     10396509.61
      3499700.57     10396477.09      3499669.08     10396452.25
      3499593.02     10396467.82      3499571.57     10396429.12
      3499597.80     10396299.29      3499681.54     10396240.94
      3499676.97     10396199.43      3499615.31     10396140.42
      3499634.06     10396047.07      3499705.05     10396011.72
      3499612.68     10395961.53      3499606.16     10395880.33
      3499515.14     10395825.27      3499474.65     10395746.71
      3499380.93     10395695.24      3499340.30     10395650.61
      3499310.61     10395645.40      3499246.55     10395679.77
      3499162.17     10395678.73      3499158.26     10395593.84

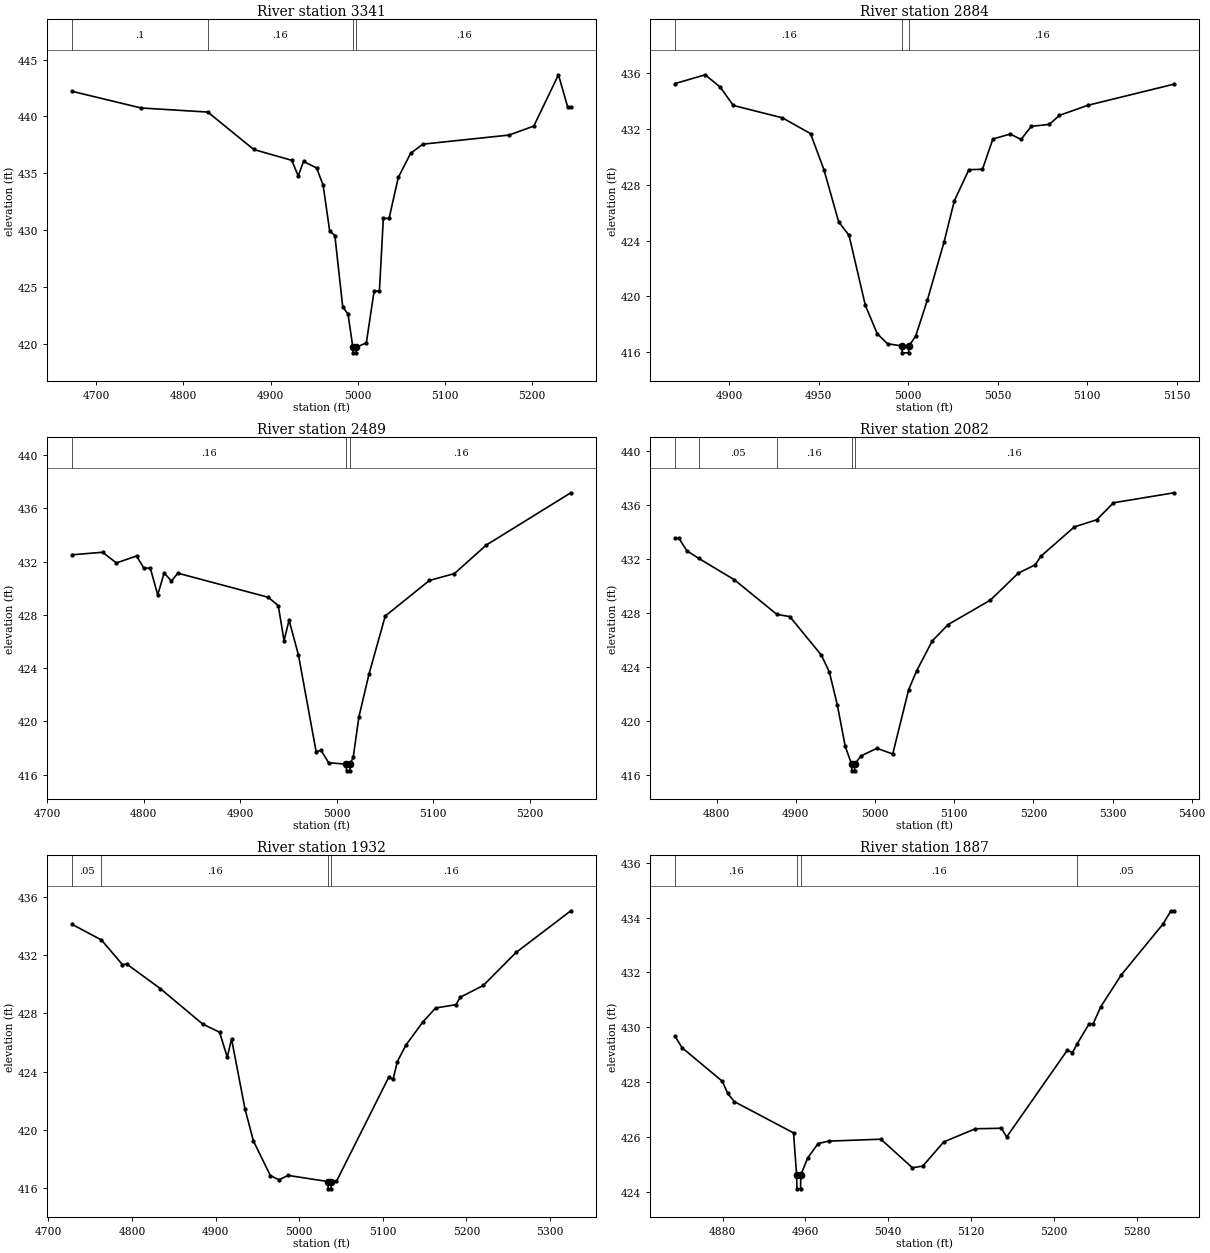
Type RM Length L Ch R = 1,3341,457,457,457
BEGIN DESCRIPTION:
NORTH MINERAL CR TRIB 8 4 2 0
END DESCRIPTION:
XS GIS Cut Line= 3
      3499642.08     10398291.62      3499342.11     10398091.64
      3499192.07     10397941.61
#Sta/Elev= 30
  4671.9  442.21  4751.5  440.74  4828.0  440.38  4880.7  437.09  4924.3  436.14
  4931.8  434.76  4937.8  436.04  4952.8  435.47  4960.3  433.96  4967.8  429.95
  4973.8  429.52  4982.8  423.26  4988.9  422.61  4994.4  419.71  4994.6  419.21
  4998.1  419.21  4998.4  419.71  5009.9  420.08  5018.9  424.68  5024.9  424.61
  5029.4  431.03  5036.0  431.03  5046.6  434.63  5060.7  436.75  5074.8  437.56
  5173.8  438.36  5202.1  439.15  5230.4  443.66  5241.0  440.82  5244.6  440.82
#Mann=4,-1,0
  4671.9     0.1       0  4828.0    0.16       0  4994.4    0.07       0
  4998.4    0.16       0
Bank Sta=4994.4,4998.4
Exp/Cntr=0.3,0.1

Type RM Length L Ch R = 1,2884,395,395,395
BEGIN DESCRIPTION:
NORTH MINERAL CR TRIB 8 4 3 0
END DESCRIPTION:
XS GIS Cut Line= 2
      3499693.92     10397773.76      3499453.03     10397633.79
#Sta/Elev= 30
  4869.9  435.27  4886.7  435.90  4895.1  435.01  4902.4  433.70  4929.8  432.81
  4945.5  431.68  4953.0  429.09  4961.2  425.35  4967.0  424.38  4976.1  419.36
  4982.7  417.33  4988.5  416.60  4996.5  416.45  4996.7  415.95  5000.2  415.95
  5000.5  416.45  5004.2  417.15  5010.8  419.76  5020.0  423.88  5025.8  426.86
  5033.9  429.09  5041.5  429.12  5047.3  431.29  5057.0  431.65  5063.0  431.26
  5068.8  432.20  5078.8  432.34  5084.5  432.99  5100.3  433.71  5148.5  435.23
#Mann=3,-1,0
  4869.9    0.16       0  4996.5    0.07       0  5000.5    0.16       0
Bank Sta=4996.5,5000.5
Exp/Cntr=0.3,0.1

Type RM Length L Ch R = 1,2489,407,407,407
BEGIN DESCRIPTION:
NORTH MINERAL CR TRIB 8 4 7 0
END DESCRIPTION:
XS GIS Cut Line= 3
      3499947.83     10397520.93      3499821.98     10397374.47
      3499511.70     10397282.25
#Sta/Elev= 30
  4725.7  432.51  4757.6  432.70  4771.9  431.90  4792.7  432.42  4800.4  431.51
  4807.0  431.51  4814.7  429.50  4821.3  431.14  4828.9  430.54  4835.5  431.13
  4929.1  429.32  4939.5  428.69  4945.5  426.06  4950.7  427.60  4960.4  424.99
  4978.7  417.73  4983.9  417.81  4991.7  416.89  5009.9  416.78  5010.2  416.28
  5013.7  416.28  5013.9  416.78  5017.1  417.29  5023.0  420.32  5033.4  423.53
  5050.3  427.91  5096.0  430.58  5121.9  431.10  5155.1  433.25  5242.5  437.17
#Mann=3,-1,0
  4725.7    0.16       0  5009.9    0.07       0  5013.9    0.16       0
Bank Sta=5009.9,5013.9
Exp/Cntr=0.3,0.1

Type RM Length L Ch R = 1,2082,150,150,150
BEGIN DESCRIPTION:
NORTH MINERAL CR TRIB 8 4 5 0
END DESCRIPTION:
XS GIS Cut Line= 3
      3499986.92     10396953.46      3499627.76     10396952.38
      3499439.99     10397147.70
#Sta/Elev= 30
  4747.7  433.54  4752.6  433.54  4762.5  432.62  4777.4  432.06  4822.5  430.47
  4876.2  427.90  4892.5  427.74  4932.5  424.87  4942.5  423.62  4952.5  421.19
  4962.5  418.12  4970.5  416.80  4970.8  416.30  4974.3  416.30  4974.5  416.80
  4982.5  417.41  5002.5  417.97  5022.5  417.55  5042.5  422.30  5052.5  423.70
  5072.5  425.94  5092.5  427.15  5145.8  428.96  5181.0  430.96  5202.4  431.58
  5209.3  432.20  5251.8  434.39  5280.1  434.92  5301.2  436.18  5377.8  436.92
#Mann=5,-1,0
  4747.7    0.16       0  4777.4    0.05       0  4876.2    0.16       0
  4970.5    0.07       0  4974.5    0.16       0
Bank Sta=4970.5,4974.5
Exp/Cntr=0.3,0.1

Type RM Length L Ch R = 1,1932,45,45,45
BEGIN DESCRIPTION:
Mapping XS f5e8ecde
END DESCRIPTION:
XS GIS Cut Line= 3
      3499996.69     10396846.04      3499566.99     10396778.77
      3499411.78     10396824.35
#Sta/Elev= 30
  4728.1  434.11  4763.5  433.03  4788.6  431.34  4793.7  431.38  4834.0  429.69
  4884.6  427.26  4904.8  426.70  4914.0  424.99  4919.1  426.24  4935.2  421.43
  4945.3  419.24  4965.5  416.87  4975.7  416.58  4986.8  416.88  5034.4  416.46
  5034.6  415.96  5038.1  415.96  5038.4  416.46  5044.5  416.47  5107.2  423.63
  5112.2  423.46  5117.4  424.69  5127.5  425.81  5147.7  427.39  5163.0  428.36
  5187.4  428.59  5192.6  429.10  5220.2  429.91  5259.3  432.17  5324.8  435.03
#Mann=4,-1,0
  4728.1    0.05       0  4763.5    0.16       0  5034.4    0.07       0
  5038.4    0.16       0
Bank Sta=5034.4,5038.4
Exp/Cntr=0.3,0.1

Type RM Length L Ch R = 1,1887,60,60,60
BEGIN DESCRIPTION:
NORTH MINERAL CR TRIB 8 4 6 0
END DESCRIPTION:
XS GIS Cut Line= 3
      3499888.68     10396784.08      3499489.37     10396723.31
      3499411.21     10396725.48
#Sta/Elev= 30
  4834.1  429.67  4840.7  429.26  4879.8  428.03  4884.9  427.59  4891.3  427.29
  4948.5  426.15  4951.5  424.61  4951.8  424.11  4955.3  424.11  4955.5  424.61
  4962.1  425.23  4972.2  425.76  4982.4  425.85  5032.9  425.92  5063.3  424.88
  5073.4  424.94  5093.6  425.82  5124.0  426.30  5149.3  426.32  5154.4  426.00
  5212.9  429.16  5218.0  429.08  5222.7  429.41  5234.1  430.13  5238.0  430.13
  5245.3  430.75  5265.3  431.92  5305.3  433.76  5313.2  434.25  5316.2  434.25
#Mann=4,-1,0
  4834.1    0.16       0  4951.5    0.07       0  4955.5    0.16       0
  5222.7    0.05       0
Bank Sta=4951.5,4955.5
Exp/Cntr=0.3,0.1

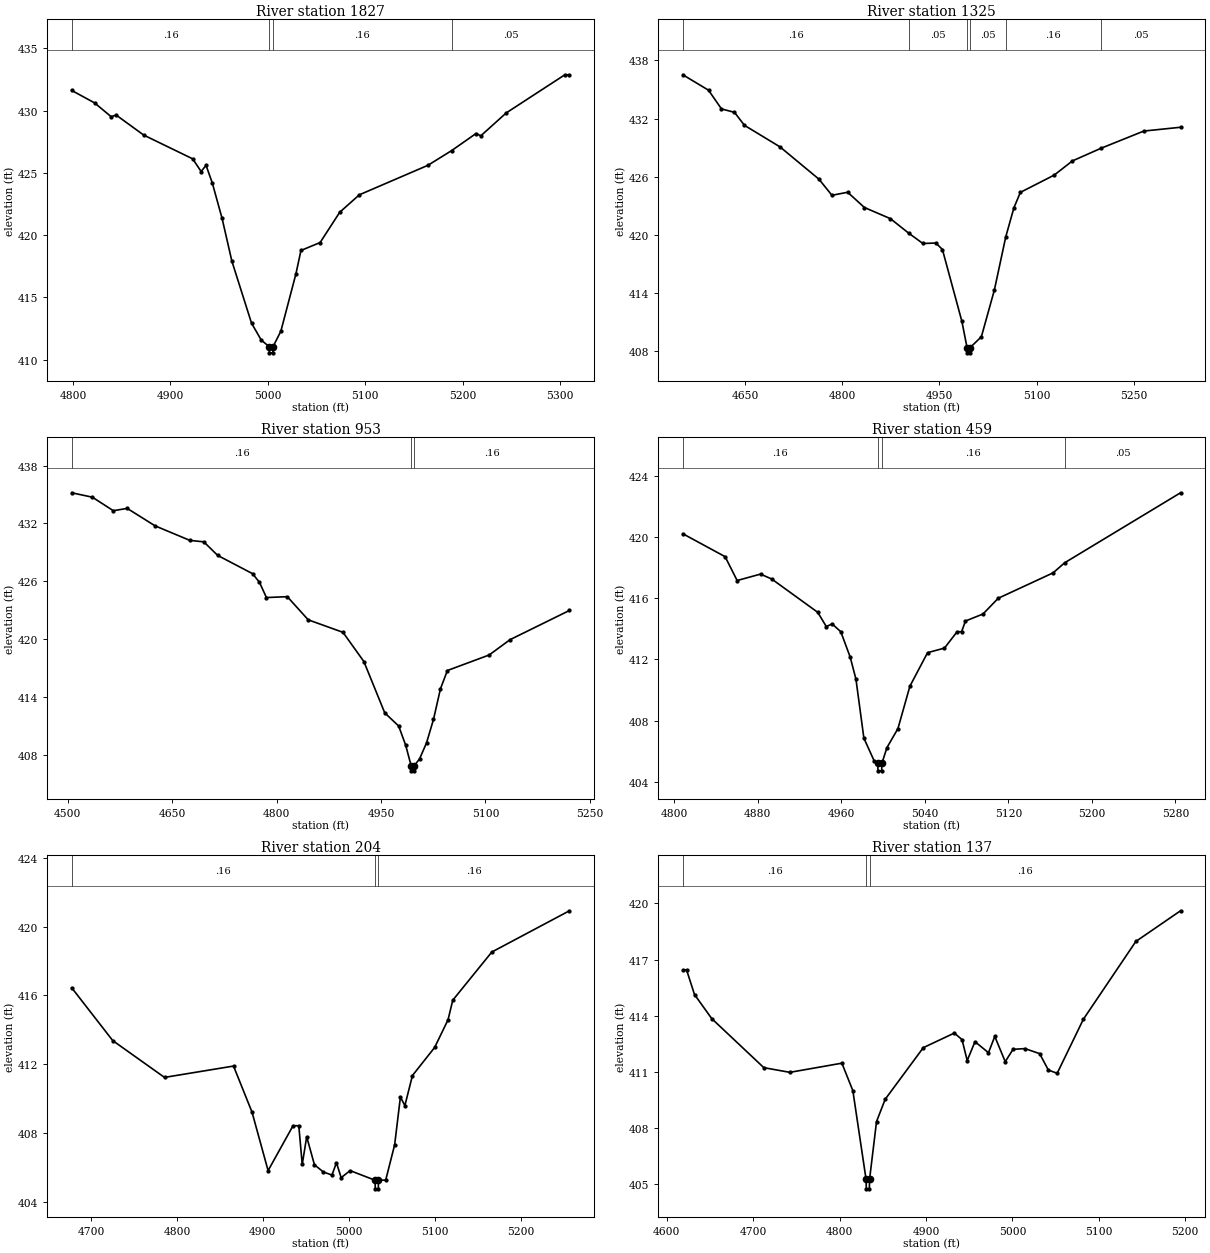
Type RM Length L Ch R = 1,1827,502,502,502
BEGIN DESCRIPTION:
NORTH MINERAL CR TRIB 8 4 4 1
END DESCRIPTION:
XS GIS Cut Line= 2
      3499925.52     10396721.14      3499417.71     10396666.88
#Sta/Elev= 30
  4798.7  431.61  4822.2  430.61  4839.2  429.50  4844.2  429.64  4872.5  428.03
  4922.8  426.12  4931.5  425.10  4936.5  425.60  4942.9  424.19  4953.0  421.33
  4963.0  417.91  4983.2  412.92  4993.2  411.56  5001.3  411.04  5001.5  410.54
  5005.0  410.54  5005.3  411.04  5013.3  412.28  5028.8  416.90  5033.9  418.76
  5053.6  419.40  5073.7  421.83  5093.8  423.23  5164.2  425.60  5188.5  426.78
  5213.5  428.15  5218.5  427.97  5244.6  429.81  5304.7  432.87  5309.4  432.87
#Mann=4,-1,0
  4798.7    0.16       0  5001.3    0.07       0  5005.3    0.16       0
  5188.5    0.05       0
Bank Sta=5001.3,5005.3
Exp/Cntr=0.3,0.1

Type RM Length L Ch R = 1,1325,372,372,372
BEGIN DESCRIPTION:
NORTH MINERAL CR TRIB 8 4 4 0
END DESCRIPTION:
XS GIS Cut Line= 2
      3500031.59     10396392.67      3499265.63     10396344.14
#Sta/Elev= 30
  4554.3  436.51  4593.9  434.92  4613.9  432.99  4633.9  432.64  4649.3  431.30
  4704.1  429.08  4764.2  425.75  4784.2  424.09  4808.5  424.40  4834.3  422.83
  4874.4  421.68  4902.7  420.18  4924.5  419.12  4944.6  419.17  4954.6  418.50
  4984.6  411.10  4992.7  408.35  4992.9  407.85  4996.4  407.85  4996.7  408.35
  5014.7  409.51  5034.7  414.32  5052.3  419.81  5064.8  422.79  5074.8  424.39
  5127.0  426.17  5155.0  427.63  5199.0  428.93  5265.2  430.71  5321.8  431.10
#Mann=6,-1,0
  4554.3    0.16       0  4902.7    0.05       0  4992.7    0.03       0
  4996.7    0.05       0  5052.3    0.16       0  5199.0    0.05       0
Bank Sta=4992.7,4996.7
Exp/Cntr=0.3,0.1

Type RM Length L Ch R = 1,953,494,494,494
BEGIN DESCRIPTION:
NORTH MINERAL CR TRIB 8 4 3 1
END DESCRIPTION:
XS GIS Cut Line= 2
      3500121.85     10396073.22      3499406.85     10396073.22
#Sta/Elev= 30
  4505.6  435.18  4535.3  434.72  4565.3  433.32  4585.3  433.56  4625.3  431.75
  4675.3  430.24  4695.3  430.09  4715.3  428.68  4765.3  426.79  4775.3  425.89
  4785.3  424.31  4815.3  424.40  4845.3  422.00  4895.3  420.70  4925.3  417.67
  4955.3  412.34  4975.3  410.98  4985.3  409.00  4993.3  406.83  4993.6  406.33
  4997.1  406.33  4997.3  406.83  5005.3  407.57  5015.3  409.23  5025.3  411.66
  5035.3  414.84  5045.3  416.74  5105.3  418.35  5135.3  419.94  5220.6  422.97
#Mann=3,-1,0
  4505.6    0.16       0  4993.3    0.07       0  4997.3    0.16       0
Bank Sta=4993.3,4997.3
Exp/Cntr=0.3,0.1

Type RM Length L Ch R = 1,459,255,255,255
BEGIN DESCRIPTION:
Mapping XS 6c4a36f4
END DESCRIPTION:
XS GIS Cut Line= 3
      3499659.24     10395677.41      3499417.25     10395790.27
      3499323.48     10395977.82
#Sta/Elev= 30
  4808.2  420.22  4848.7  418.72  4860.2  417.16  4882.6  417.58  4893.3  417.26
  4937.4  415.08  4945.6  414.15  4951.2  414.32  4959.5  413.81  4968.5  412.15
  4974.0  410.71  4981.6  406.85  4991.4  405.37  4994.9  405.21  4995.1  404.71
  4998.6  404.71  4998.9  405.21  5003.7  406.23  5014.2  407.47  5025.7  410.25
  5042.6  412.44  5058.8  412.74  5070.9  413.81  5075.2  413.81  5078.9  414.51
  5095.7  414.97  5110.3  416.00  5162.8  417.66  5173.9  418.32  5284.9  422.90
#Mann=4,-1,0
  4808.2    0.16       0  4994.9    0.07       0  4998.9    0.16       0
  5173.9    0.05       0
Bank Sta=4994.9,4998.9
Exp/Cntr=0.3,0.1

Type RM Length L Ch R = 1,204,67,67,67
BEGIN DESCRIPTION:
Mapping XS 48c76655
END DESCRIPTION:
XS GIS Cut Line= 4
      3499549.62     10395578.68      3499289.21     10395601.47
      3499241.47     10395777.25      3499264.25     10395910.67
#Sta/Elev= 30
  4677.7  416.44  4725.4  413.37  4785.6  411.23  4865.9  411.89  4887.4  409.21
  4906.1  405.81  4935.1  408.42  4941.8  408.42  4945.8  406.17  4951.0  407.78
  4960.0  406.15  4970.4  405.73  4980.4  405.55  4985.6  406.27  4991.1  405.40
  5001.5  405.81  5030.5  405.25  5030.8  404.75  5034.3  404.75  5034.5  405.25
  5042.9  405.26  5053.3  407.31  5060.0  410.09  5065.2  409.59  5074.0  411.34
  5099.8  412.97  5115.4  414.58  5120.9  415.72  5166.3  418.52  5256.6  420.92
#Mann=3,-1,0
  4677.7    0.16       0  5030.5    0.07       0  5034.5    0.16       0
Bank Sta=5030.5,5034.5
Exp/Cntr=0.3,0.1

Type RM Length L Ch R = 1,137,96,96,96
BEGIN DESCRIPTION:
Mapping XS 78b6f4f9
END DESCRIPTION:
XS GIS Cut Line= 5
      3499535.56     10395562.40      3499269.68     10395581.94
      3499221.94     10395654.63      3499208.92     10395694.78
      3499236.05     10395872.75
#Sta/Elev= 30
  4618.7  416.45  4623.0  416.45  4632.2  415.13  4652.2  413.84  4712.4  411.22
  4742.5  410.97  4802.7  411.46  4815.4  409.99  4830.7  405.24  4831.0  404.74
  4834.5  404.74  4834.7  405.24  4842.8  408.34  4852.8  409.53  4896.9  412.29
  4932.8  413.07  4941.7  412.72  4947.7  411.60  4956.7  412.61  4972.3  412.02
  4979.6  412.89  4991.7  411.54  5000.7  412.20  5014.5  412.24  5031.5  411.97
  5041.6  411.09  5051.8  410.92  5082.1  413.81  5142.8  417.97  5194.5  419.61
#Mann=3,-1,0
  4618.7    0.16       0  4830.7    0.07       0  4834.7    0.16       0
Bank Sta=4830.7,4834.7
Exp/Cntr=0.3,0.1

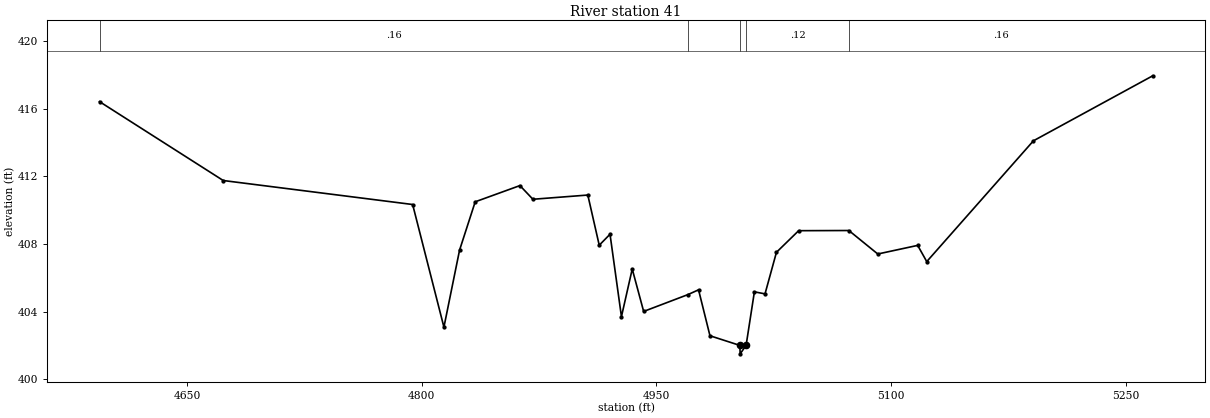
Type RM Length L Ch R = 1,41,0,0,0
BEGIN DESCRIPTION:
NORTH MINERAL CR TRIB 8 4 1 0
END DESCRIPTION:
XS GIS Cut Line= 4
      3499532.24     10395548.30      3499259.92     10395542.87
      3499124.28     10395670.91      3499193.74     10395873.86
#Sta/Elev= 30
  4593.9  416.43  4673.0  411.76  4794.1  410.34  4814.1  403.08  4824.1  407.64
  4834.1  410.50  4862.7  411.46  4871.0  410.65  4906.1  410.90  4913.4  407.93
  4920.3  408.58  4927.6  403.70  4934.5  406.52  4941.8  404.01  4970.2  405.01
  4976.9  405.29  4984.2  402.57  5003.3  402.00  5003.5  401.50  5007.3  402.00
  5012.6  405.17  5019.4  405.05  5026.7  407.51  5040.9  408.79  5073.0  408.80
  5091.5  407.41  5117.0  407.92  5122.8  406.96  5191.0  414.11  5267.3  417.96
#Mann=5,-1,0
  4593.9    0.16       0  4970.2    0.12       0  5003.3    0.07       0
  5007.3    0.12       0  5073.0    0.16       0
Bank Sta=5003.3,5007.3
Exp/Cntr=0.3,0.1

Chan Stop Cuts=-1