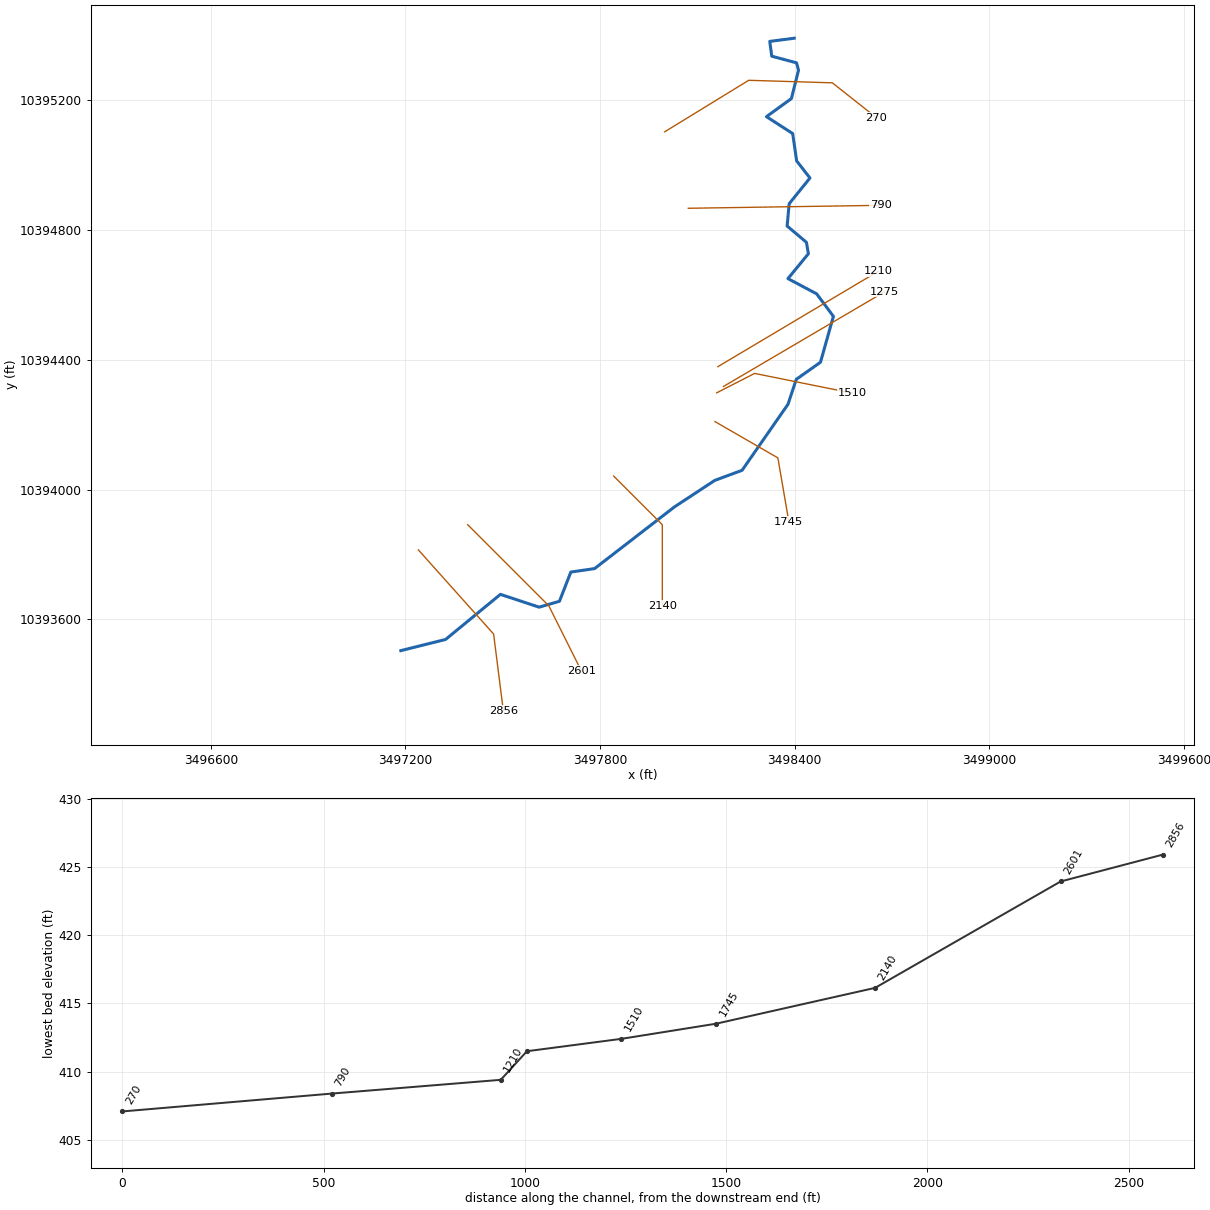
--- NORTH MINERAL CR TRIB 8 5.prj (project) ---

Proj Title=NORTH MINERAL CR TRIB 8 5 Base Level Engineering
Current Plan=p01
Default Exp/Contr=0.3,0.1
English Units
Geom File=g01
Flow File=f01
Plan File=p01
BEGIN DESCRIPTION:
NORTH MINERAL CR TRIB 8 5
END DESCRIPTION:

--- NORTH MINERAL CR TRIB 8 5.p01 (plan) ---

Plan Title=Multiple Run
Short Identifier=Multiple
Geom File=g01
Flow File=f01
Subcritical Flow
K Sum by GR= 0
Std Step Tol= 0.01
Critical Tol= 0.01
Num of Std Step Trials= 20
Max Error Tol= 0.3
Flow Tol Ratio= 0.001
Split Flow NTrial= 30
Split Flow Tol= 0.02
Split Flow Ratio= 0.02
Log Output Level= 0
Friction Slope Method= 1
Unsteady Friction Slope Method= 2
Unsteady Bridges Friction Slope Method= 1
Parabolic Critical Depth
Global Vel Dist=  1 , 1 , 1
Global Log Level= 0
CheckData=True
Encroach Param= -1, 0, 0, 0
BEGIN DESCRIPTION:
Multiple Run
END DESCRIPTION:

--- NORTH MINERAL CR TRIB 8 5.f01 (steady flow) ---

Flow Title=Multiple
Number of Profiles=7
Profile Names=10-year,25-year,50-year,1pct_min,100-year,1pct_plu,500-year
River Rch & RM= NORTH MINERAL CR,Reach-1,2856
     475     629     753     659     891    1205    1243
Boundary for River Rch & Prof#=NORTH MINERAL CR,Reach-1,1
Up Type=0
Dn Type=3
Dn Slope=0.005
Boundary for River Rch & Prof#=NORTH MINERAL CR,Reach-1,2
Up Type=0
Dn Type=3
Dn Slope=0.005
Boundary for River Rch & Prof#=NORTH MINERAL CR,Reach-1,3
Up Type=0
Dn Type=3
Dn Slope=0.005
Boundary for River Rch & Prof#=NORTH MINERAL CR,Reach-1,4
Up Type=0
Dn Type=3
Dn Slope=0.005
Boundary for River Rch & Prof#=NORTH MINERAL CR,Reach-1,5
Up Type=0
Dn Type=3
Dn Slope=0.005
Boundary for River Rch & Prof#=NORTH MINERAL CR,Reach-1,6
Up Type=0
Dn Type=3
Dn Slope=0.005
Boundary for River Rch & Prof#=NORTH MINERAL CR,Reach-1,7
Up Type=0
Dn Type=3
Dn Slope=0.005

--- NORTH MINERAL CR TRIB 8 5.g01 (geometry) ---

Geom Title=Existing Conditions

River Reach=NORTH MINERAL CR,Reach-1
Reach XY= 30
      3497185.90     10393503.49      3497323.92     10393537.86
      3497492.97     10393676.89      3497612.41     10393637.44
      3497674.95     10393655.57      3497710.10     10393745.68
      3497783.28     10393756.35      3498029.48     10393946.49
      3498153.57     10394028.15      3498237.96     10394059.36
      3498379.46     10394262.78      3498404.98     10394339.73
      3498479.68     10394392.47      3498519.50     10394533.97
      3498467.83     10394603.39      3498379.37     10394650.36
      3498442.39     10394726.93      3498436.28     10394762.25
      3498376.86     10394812.49      3498383.14     10394881.12
      3498447.24     10394960.49      3498406.25     10395013.22
      3498393.94     10395097.52      3498313.23     10395149.58
      3498390.05     10395205.31      3498411.93     10395292.81
      3498405.94     10395315.47      3498329.37     10395336.04
      3498323.38     10395381.61      3498398.88     10395391.41

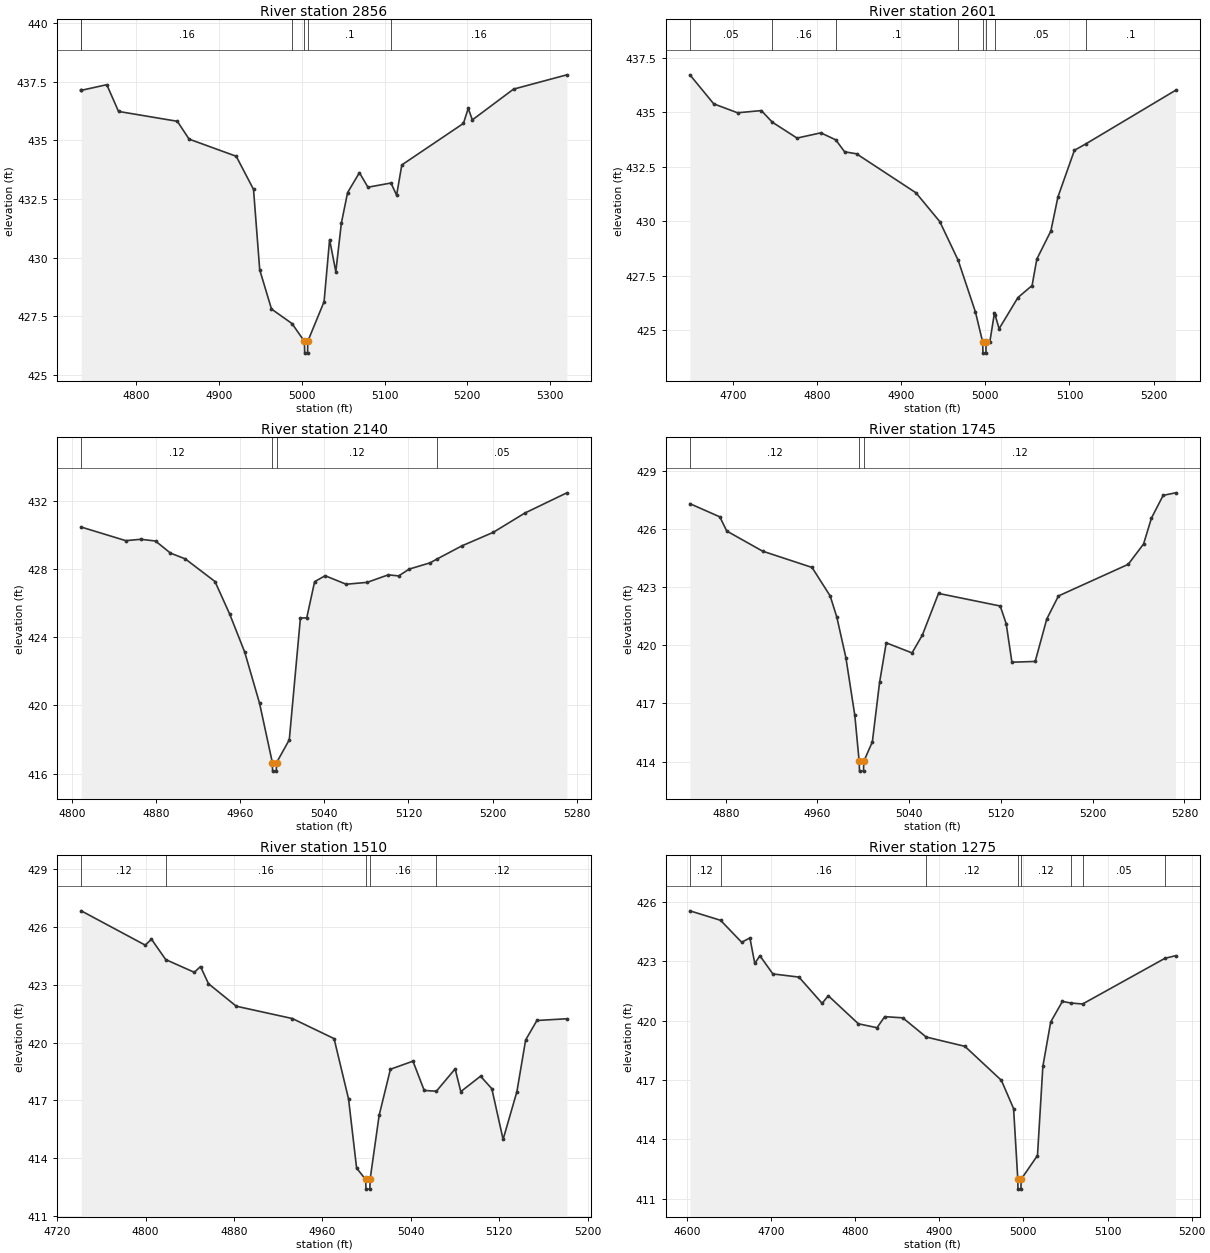
Type RM Length L Ch R = 1,2856,255,255,255
BEGIN DESCRIPTION:
NORTH MINERAL CR TRIB 8 5 21 0
END DESCRIPTION:
XS GIS Cut Line= 3
      3497240.22     10393813.79      3497472.01     10393554.66
      3497501.95     10393317.71
#Sta/Elev= 30
  4733.7  437.13  4733.9  437.13  4764.6  437.37  4778.8  436.23  4849.8  435.81
  4864.0  435.05  4920.9  434.32  4941.8  432.91  4949.3  429.48  4963.5  427.81
  4988.3  427.19  5003.3  426.43  5003.6  425.93  5007.1  425.93  5007.3  426.43
  5027.0  428.12  5033.7  430.77  5041.2  429.40  5047.9  431.47  5055.4  432.77
  5069.7  433.62  5080.0  433.00  5107.8  433.18  5114.6  432.66  5120.9  433.95
  5195.3  435.72  5201.1  436.36  5206.1  435.87  5255.8  437.18  5320.2  437.79
#Mann=6,-1,0
  4733.7    0.05       0  4733.9    0.16       0  4988.3     0.1       0
  5003.3    0.07       0  5007.3     0.1       0  5107.8    0.16       0
Bank Sta=5003.3,5007.3
Exp/Cntr=0.3,0.1

Type RM Length L Ch R = 1,2601,461,461,461
BEGIN DESCRIPTION:
NORTH MINERAL CR TRIB 8 5 22 0
END DESCRIPTION:
XS GIS Cut Line= 3
      3497392.09     10393891.66      3497642.11     10393641.64
      3497742.12     10393441.62
#Sta/Elev= 30
  4648.9  436.71  4677.2  435.38  4705.5  434.97  4733.8  435.07  4746.8  434.54
  4776.2  433.81  4804.5  434.05  4822.2  433.73  4832.8  433.18  4846.9  433.09
  4917.6  431.30  4945.9  429.98  4967.7  428.21  4988.3  425.83  4996.9  424.45
  4997.2  423.95  5000.7  423.95  5000.9  424.45  5005.3  424.45  5010.9  425.80
  5011.7  425.69  5016.4  425.07  5038.8  426.50  5055.6  427.05  5061.2  428.26
  5077.9  429.55  5086.3  431.11  5105.9  433.25  5119.3  433.54  5226.1  436.00
#Mann=8,-1,0
  4648.9    0.05       0  4746.8    0.16       0  4822.2     0.1       0
  4967.7    0.16       0  4996.9    0.07       0  5000.9    0.16       0
  5011.7    0.05       0  5119.3     0.1       0
Bank Sta=4996.9,5000.9
Exp/Cntr=0.3,0.1

Type RM Length L Ch R = 1,2140,395,395,395
BEGIN DESCRIPTION:
NORTH MINERAL CR TRIB 8 5 6 0
END DESCRIPTION:
XS GIS Cut Line= 3
      3497842.10     10394041.65      3497992.11     10393891.64
      3497992.11     10393641.68
#Sta/Elev= 30
  4808.6  430.48  4851.0  429.68  4865.2  429.76  4879.3  429.66  4893.5  428.95
  4907.6  428.61  4935.9  427.28  4950.0  425.35  4964.2  423.13  4978.3  420.13
  4990.5  416.64  4990.7  416.14  4994.2  416.14  4994.5  416.64  5006.6  417.98
  5017.2  425.14  5023.2  425.14  5030.7  427.27  5040.7  427.62  5060.7  427.12
  5080.7  427.23  5100.7  427.67  5110.7  427.61  5120.7  428.01  5140.7  428.38
  5147.1  428.60  5170.7  429.37  5200.7  430.17  5230.7  431.30  5270.7  432.49
#Mann=4,-1,0
  4808.6    0.12       0  4990.5    0.07       0  4994.5    0.12       0
  5147.1    0.05       0
Bank Sta=4990.5,4994.5
Exp/Cntr=0.3,0.1

Type RM Length L Ch R = 1,1745,235,235,235
BEGIN DESCRIPTION:
NORTH MINERAL CR TRIB 8 5 5 0
END DESCRIPTION:
XS GIS Cut Line= 3
      3498154.33     10394209.59      3498348.31     10394097.63
      3498382.17     10393900.99
#Sta/Elev= 30
  4848.8  427.31  4874.9  426.63  4880.9  425.90  4912.2  424.86  4955.3  424.02
  4971.1  422.55  4976.9  421.46  4984.8  419.37  4992.6  416.39  4996.4  414.01
  4996.7  413.51  5000.2  413.51  5000.4  414.01  5007.9  415.02  5014.2  418.09
  5020.0  420.13  5042.5  419.61  5051.5  420.53  5065.6  422.68  5119.4  422.03
  5124.6  421.12  5129.6  419.13  5149.9  419.17  5160.0  421.36  5170.2  422.55
  5231.0  424.18  5244.4  425.23  5251.3  426.57  5261.5  427.74  5272.3  427.87
#Mann=3,-1,0
  4848.8    0.12       0  4996.4    0.07       0  5000.4    0.12       0
Bank Sta=4996.4,5000.4
Exp/Cntr=0.3,0.1

Type RM Length L Ch R = 1,1510,235,235,235
BEGIN DESCRIPTION:
Mapping XS 591aae5a
END DESCRIPTION:
XS GIS Cut Line= 3
      3498159.54     10394298.16      3498276.69     10394358.04
      3498578.64     10394297.13
#Sta/Elev= 30
  4741.7  426.84  4799.7  425.06  4805.3  425.37  4818.2  424.31  4844.1  423.65
  4849.7  423.95  4856.9  423.06  4882.1  421.89  4932.9  421.25  4970.6  420.21
  4983.7  417.08  4991.0  413.49  4999.2  412.90  4999.5  412.40  5003.0  412.40
  5003.2  412.90  5011.4  416.23  5021.6  418.62  5042.0  419.04  5052.2  417.52
  5063.2  417.48  5080.2  418.64  5085.3  417.46  5103.2  418.26  5113.4  417.61
  5123.6  414.98  5136.1  417.46  5144.0  420.14  5154.2  421.15  5181.3  421.24
#Mann=5,-1,0
  4741.7    0.12       0  4818.2    0.16       0  4999.2    0.07       0
  5003.2    0.16       0  5063.2    0.12       0
Bank Sta=4999.2,5003.2
Exp/Cntr=0.3,0.1

Type RM Length L Ch R = 1,1275,65,65,65
BEGIN DESCRIPTION:
Mapping XS 00d0a5cc
END DESCRIPTION:
XS GIS Cut Line= 2
      3498180.37     10394317.70      3498678.05     10394610.07
#Sta/Elev= 30
  4603.6  425.56  4640.1  425.08  4665.1  423.97  4674.9  424.19  4680.7  422.90
  4686.8  423.29  4702.2  422.37  4733.2  422.21  4760.8  420.88  4768.0  421.27
  4803.8  419.85  4826.0  419.65  4835.1  420.21  4856.6  420.15  4884.4  419.18
  4930.4  418.71  4973.8  416.99  4988.3  415.56  4993.3  411.99  4993.5  411.49
  4997.0  411.49  4997.3  411.99  5016.7  413.19  5023.1  417.70  5032.4  419.94
  5046.3  420.98  5056.2  420.90  5070.3  420.85  5168.2  423.16  5180.8  423.29
#Mann=8,-1,0
  4603.6    0.12       0  4640.1    0.16       0  4884.4    0.12       0
  4993.3    0.07       0  4997.3    0.12       0  5056.2     0.1       0
  5070.3    0.05       0  5168.2     0.1       0
Bank Sta=4993.3,4997.3
Exp/Cntr=0.3,0.1

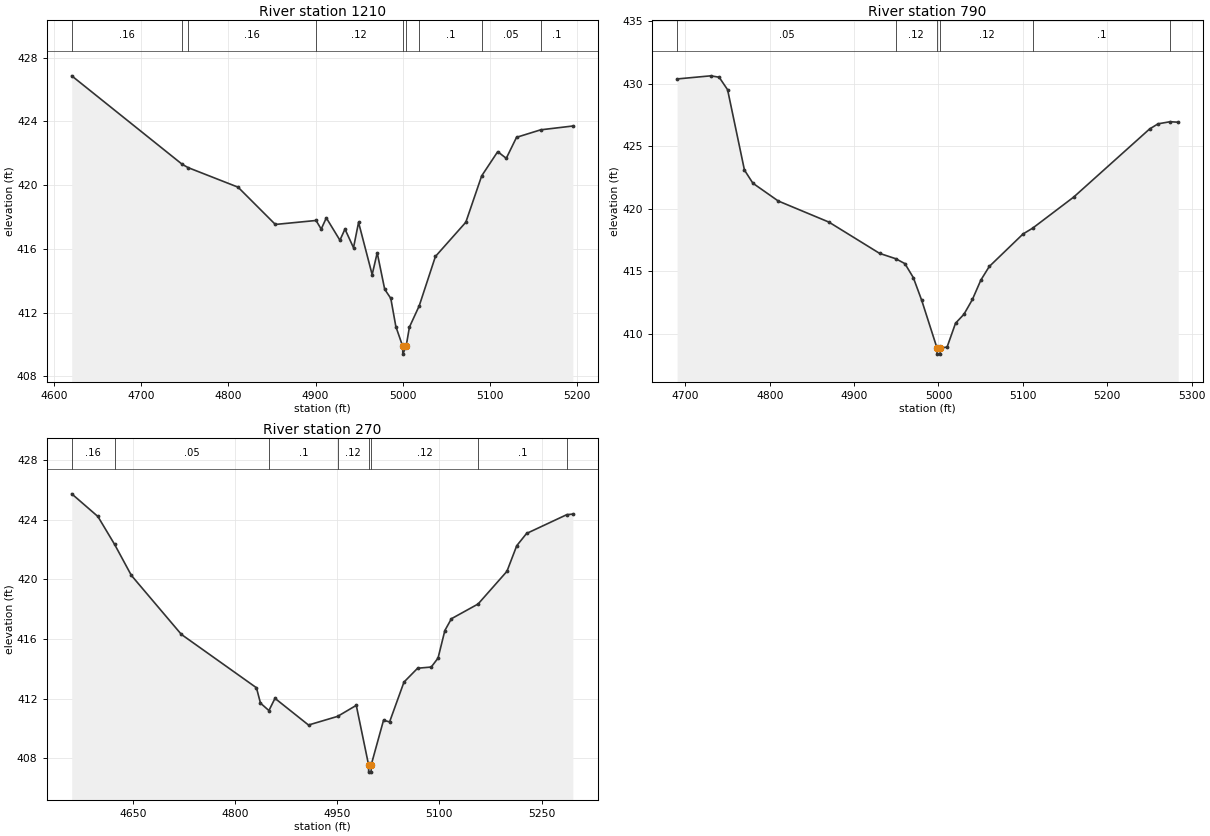
Type RM Length L Ch R = 1,1210,420,420,420
BEGIN DESCRIPTION:
NORTH MINERAL CR TRIB 8 5 4 0
END DESCRIPTION:
XS GIS Cut Line= 2
      3498163.38     10394378.86      3498657.67     10394672.83
#Sta/Elev= 30
  4620.1  426.86  4746.8  421.31  4753.6  421.10  4811.0  419.87  4853.8  417.53
  4900.5  417.78  4906.4  417.24  4912.3  417.94  4927.9  416.54  4933.7  417.24
  4943.5  416.07  4949.3  417.66  4964.9  414.38  4970.7  415.75  4979.3  413.46
  4986.3  412.89  4992.1  411.12  4999.9  409.89  5000.1  409.39  5003.9  409.89
  5007.7  411.09  5018.9  412.42  5037.5  415.52  5072.4  417.67  5090.6  420.58
  5109.0  422.10  5118.8  421.68  5130.6  423.00  5158.3  423.47  5195.2  423.71
#Mann=9,-1,0
  4620.1    0.16       0  4746.8    0.05       0  4753.6    0.16       0
  4900.5    0.12       0  4999.9    0.07       0  5003.9    0.12       0
  5018.9     0.1       0  5090.6    0.05       0  5158.3     0.1       0
Bank Sta=4999.9,5003.9
Exp/Cntr=0.3,0.1

Type RM Length L Ch R = 1,790,520,520,520
BEGIN DESCRIPTION:
Mapping XS 334156e7
END DESCRIPTION:
XS GIS Cut Line= 2
      3498072.27     10394867.16      3498666.00     10394876.27
#Sta/Elev= 30
  4690.3  430.39  4730.1  430.64  4740.1  430.53  4750.1  429.53  4770.1  423.10
  4780.1  422.05  4810.1  420.63  4870.2  418.94  4930.2  416.44  4949.4  416.01
  4960.2  415.62  4970.2  414.50  4980.2  412.67  4998.2  408.88  4998.4  408.38
  5001.9  408.38  5002.2  408.88  5010.2  408.94  5020.2  410.85  5030.2  411.57
  5040.2  412.75  5050.2  414.30  5060.2  415.39  5100.2  417.99  5111.7  418.46
  5160.2  420.94  5250.2  426.39  5260.2  426.80  5274.5  426.97  5284.1  426.93
#Mann=6,-1,0
  4690.3    0.05       0  4949.4    0.12       0  4998.2    0.07       0
  5002.2    0.12       0  5111.7     0.1       0  5274.5    0.05       0
Bank Sta=4998.2,5002.2
Exp/Cntr=0.3,0.1

Type RM Length L Ch R = 1,270,0,0,0
BEGIN DESCRIPTION:
NORTH MINERAL CR TRIB 8 5 1 0
END DESCRIPTION:
XS GIS Cut Line= 4
      3497999.39     10395102.86      3498258.46     10395261.69
      3498516.28     10395253.88      3498652.45     10395146.23
#Sta/Elev= 30
  4560.4  425.74  4598.8  424.22  4623.3  422.35  4647.9  420.27  4721.3  416.31
  4831.5  412.73  4837.4  411.70  4849.8  411.20  4858.7  412.02  4907.9  410.23
  4950.6  410.81  4978.0  411.55  4996.0  407.57  4996.2  407.07  4999.7  407.07
  5000.0  407.57  5018.0  410.55  5026.9  410.44  5048.0  413.11  5068.0  414.04
  5088.0  414.12  5098.0  414.72  5108.0  416.57  5117.6  417.36  5156.8  418.35
  5199.1  420.54  5213.5  422.26  5227.9  423.08  5286.8  424.34  5295.8  424.38
#Mann=8,-1,0
  4560.4    0.16       0  4623.3    0.05       0  4849.8     0.1       0
  4950.6    0.12       0  4996.0    0.07       0  5000.0    0.12       0
  5156.8     0.1       0  5286.8    0.05       0
Bank Sta=4996,5000
Exp/Cntr=0.3,0.1

Chan Stop Cuts=-1