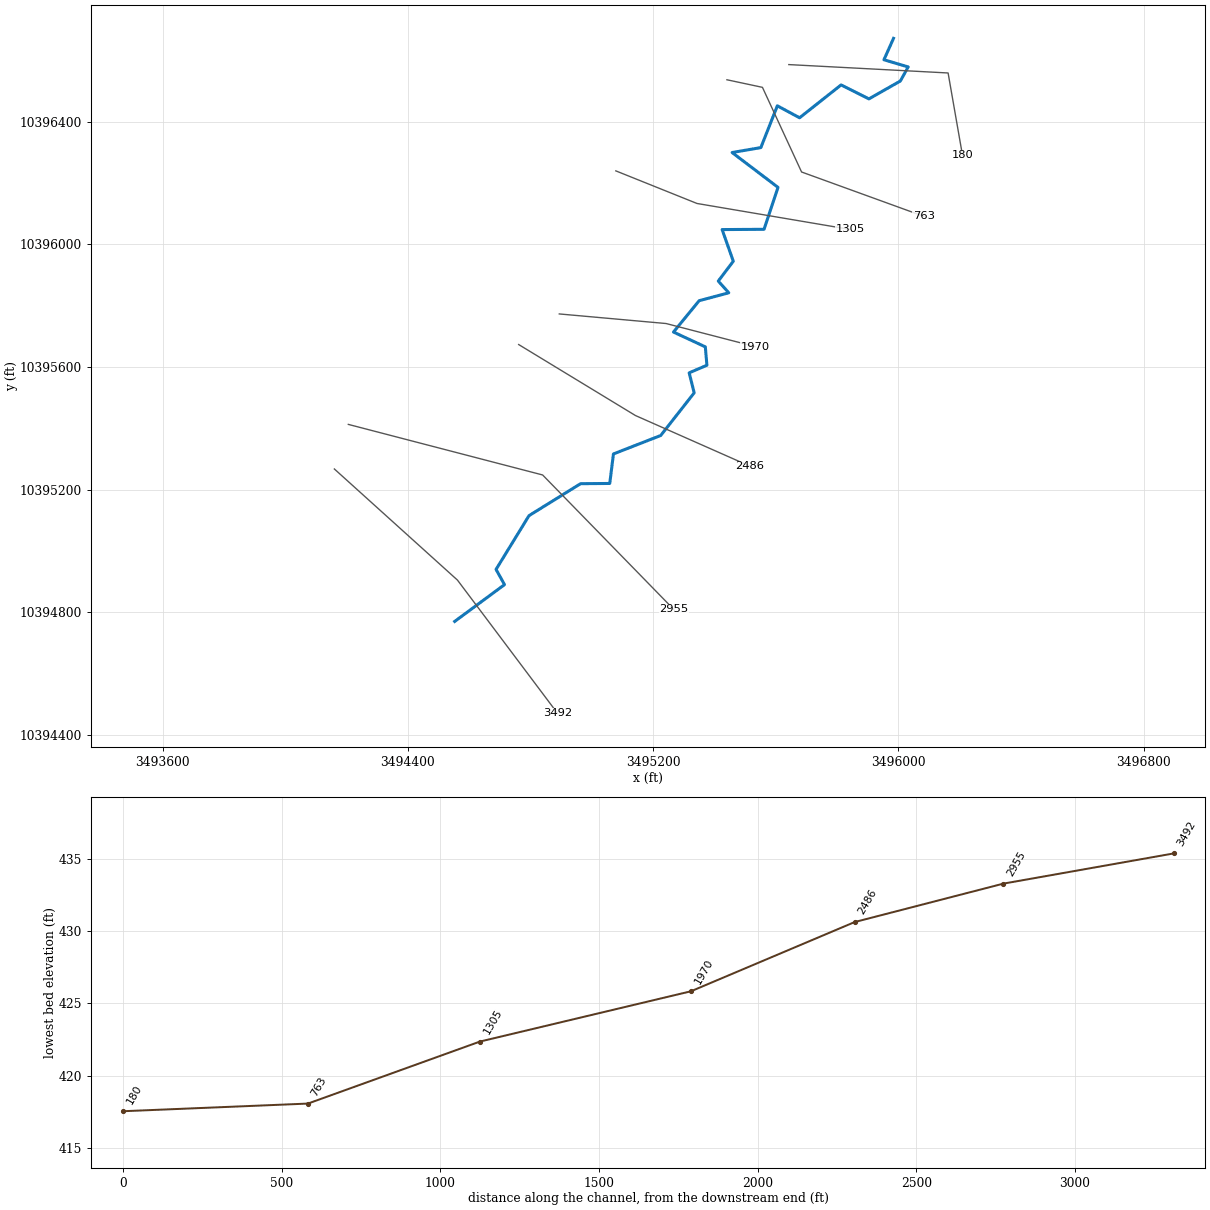
--- NORTH MINERAL CR TRIB 8 6 1.prj (project) ---

Proj Title=NORTH MINERAL CR TRIB 8 6 1 Base Level Engineering
Current Plan=p01
Default Exp/Contr=0.3,0.1
English Units
Geom File=g01
Flow File=f01
Plan File=p01
BEGIN DESCRIPTION:
NORTH MINERAL CR TRIB 8 6 1
END DESCRIPTION:

--- NORTH MINERAL CR TRIB 8 6 1.p01 (plan) ---

Plan Title=Multiple Run
Short Identifier=Multiple
Geom File=g01
Flow File=f01
Subcritical Flow
K Sum by GR= 0
Std Step Tol= 0.01
Critical Tol= 0.01
Num of Std Step Trials= 20
Max Error Tol= 0.3
Flow Tol Ratio= 0.001
Split Flow NTrial= 30
Split Flow Tol= 0.02
Split Flow Ratio= 0.02
Log Output Level= 0
Friction Slope Method= 1
Unsteady Friction Slope Method= 2
Unsteady Bridges Friction Slope Method= 1
Parabolic Critical Depth
Global Vel Dist=  1 , 1 , 1
Global Log Level= 0
CheckData=True
Encroach Param= -1, 0, 0, 0
BEGIN DESCRIPTION:
Multiple Run
END DESCRIPTION:

--- NORTH MINERAL CR TRIB 8 6 1.f01 (steady flow) ---

Flow Title=Multiple
Number of Profiles=7
Profile Names=10-year,25-year,50-year,1pct_min,100-year,1pct_plu,500-year
River Rch & RM= NORTH MINERAL CR,Reach-1,3492
     343     445     524     452     611     827     828
Boundary for River Rch & Prof#=NORTH MINERAL CR,Reach-1,1
Up Type=0
Dn Type=3
Dn Slope=0.005
Boundary for River Rch & Prof#=NORTH MINERAL CR,Reach-1,2
Up Type=0
Dn Type=3
Dn Slope=0.005
Boundary for River Rch & Prof#=NORTH MINERAL CR,Reach-1,3
Up Type=0
Dn Type=3
Dn Slope=0.005
Boundary for River Rch & Prof#=NORTH MINERAL CR,Reach-1,4
Up Type=0
Dn Type=3
Dn Slope=0.005
Boundary for River Rch & Prof#=NORTH MINERAL CR,Reach-1,5
Up Type=0
Dn Type=3
Dn Slope=0.005
Boundary for River Rch & Prof#=NORTH MINERAL CR,Reach-1,6
Up Type=0
Dn Type=3
Dn Slope=0.005
Boundary for River Rch & Prof#=NORTH MINERAL CR,Reach-1,7
Up Type=0
Dn Type=3
Dn Slope=0.005

--- NORTH MINERAL CR TRIB 8 6 1.g01 (geometry) ---

Geom Title=Existing Conditions

River Reach=NORTH MINERAL CR,Reach-1
Reach XY= 30
      3494552.70     10394770.06      3494715.16     10394890.02
      3494687.62     10394939.76      3494795.15     10395115.11
      3494963.24     10395219.32      3495058.41     10395220.04
      3495070.51     10395316.32      3495224.67     10395376.51
      3495333.78     10395515.53      3495317.44     10395580.87
      3495375.25     10395605.55      3495370.13     10395665.53
      3495266.23     10395713.83      3495349.93     10395816.01
      3495446.60     10395841.89      3495412.31     10395880.08
      3495461.36     10395944.75      3495424.90     10396048.05
      3495561.62     10396048.92      3495607.19     10396185.64
      3495457.45     10396299.36      3495551.20     10396315.41
      3495605.02     10396451.70      3495677.50     10396412.64
      3495812.92     10396519.84      3495903.63     10396474.27
      3496006.06     10396532.43      3496031.67     10396578.44
      3495952.68     10396601.87      3495983.93     10396671.75

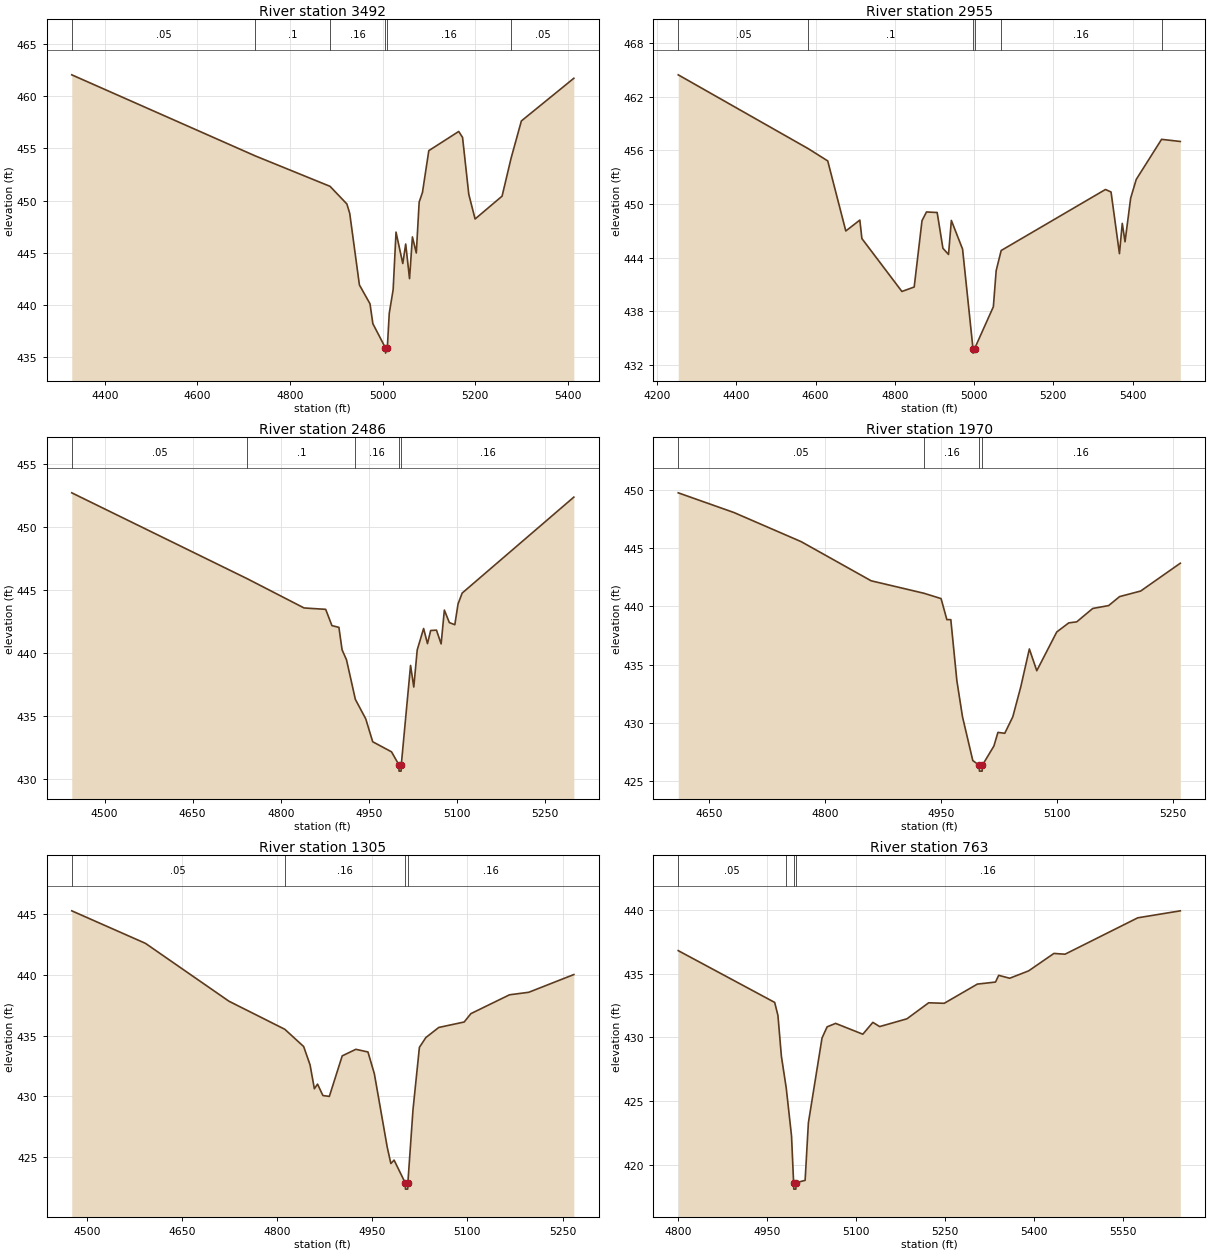
Type RM Length L Ch R = 1,3492,537,537,537
BEGIN DESCRIPTION:
NORTH MINERAL CR TRIB 8 6 1 70
END DESCRIPTION:
XS GIS Cut Line= 3
      3494160.27     10395267.28      3494561.75     10394904.86
      3494888.28     10394470.21
#Sta/Elev= 30
  4328.6  462.06  4724.3  454.30  4886.5  451.37  4922.8  449.68  4929.0  448.78
  4949.9  441.92  4972.8  440.11  4979.0  438.20  5006.2  435.88  5006.4  435.38
  5010.2  435.88  5014.4  439.20  5022.8  441.47  5029.0  446.98  5043.6  443.97
  5049.9  445.84  5058.2  442.52  5064.4  446.52  5072.8  444.98  5079.0  449.86
  5086.1  450.78  5099.8  454.79  5164.4  456.63  5172.7  456.06  5186.2  450.60
  5199.8  448.24  5258.1  450.43  5277.6  454.08  5299.8  457.64  5413.1  461.73
#Mann=6,-1,0
  4328.6    0.05       0  4724.3     0.1       0  4886.5    0.16       0
  5006.2    0.07       0  5010.2    0.16       0  5277.6    0.05       0
Bank Sta=5006.2,5010.2
Exp/Cntr=0.3,0.1

Type RM Length L Ch R = 1,2955,469,469,469
BEGIN DESCRIPTION:
NORTH MINERAL CR TRIB 8 6 1 20
END DESCRIPTION:
XS GIS Cut Line= 3
      3494205.85     10395412.67      3494839.53     10395247.74
      3495267.04     10394809.38
#Sta/Elev= 30
  4253.3  464.48  4582.0  456.19  4630.6  454.83  4676.2  446.98  4711.6  448.20
  4716.8  446.13  4817.8  440.20  4848.8  440.70  4868.5  448.13  4879.8  449.11
  4906.8  449.05  4921.3  445.04  4935.4  444.35  4942.6  448.16  4970.9  444.95
  4997.2  433.79  4997.4  433.29  5001.2  433.79  5048.6  438.49  5055.7  442.54
  5068.3  444.79  5331.5  451.63  5345.6  451.35  5366.8  444.44  5373.9  447.83
  5380.9  445.77  5395.1  450.66  5409.2  452.76  5473.1  457.25  5520.4  457.01
#Mann=6,-1,0
  4253.3    0.05       0  4582.0     0.1       0  4997.2    0.07       0
  5001.2     0.1       0  5068.3    0.16       0  5473.1    0.05       0
Bank Sta=4997.2,5001.2
Exp/Cntr=0.3,0.1

Type RM Length L Ch R = 1,2486,516,516,516
BEGIN DESCRIPTION:
NORTH MINERAL CR TRIB 8 6 1 60
END DESCRIPTION:
XS GIS Cut Line= 3
      3494761.39     10395673.10      3495142.11     10395441.64
      3495515.82     10395276.31
#Sta/Elev= 30
  4444.3  452.70  4743.2  445.88  4839.5  443.57  4876.3  443.46  4886.9  442.17
  4898.8  442.03  4904.2  440.25  4911.7  439.46  4926.8  436.32  4944.5  434.77
  4956.3  432.96  4988.3  432.16  5000.9  431.13  5001.1  430.63  5004.6  430.63
  5004.9  431.13  5020.7  439.01  5026.2  437.30  5032.0  440.24  5042.9  441.94
  5049.5  440.74  5054.9  441.78  5064.8  441.81  5072.7  440.72  5078.2  443.40
  5086.7  442.41  5096.0  442.24  5101.5  443.89  5108.5  444.75  5298.5  452.36
#Mann=5,-1,0
  4444.3    0.05       0  4743.2     0.1       0  4926.8    0.16       0
  5000.9    0.07       0  5004.9    0.16       0
Bank Sta=5000.9,5004.9
Exp/Cntr=0.3,0.1

Type RM Length L Ch R = 1,1970,665,665,665
BEGIN DESCRIPTION:
NORTH MINERAL CR TRIB 8 6 1 50
END DESCRIPTION:
XS GIS Cut Line= 3
      3494893.78     10395772.91      3495242.11     10395741.64
      3495531.72     10395666.60
#Sta/Elev= 30
  4610.5  449.76  4682.4  448.07  4769.5  445.56  4859.8  442.20  4927.9  441.13
  4950.2  440.67  4957.7  438.86  4962.8  438.86  4970.6  433.62  4977.9  430.51
  4991.2  426.75  4999.5  426.34  4999.8  425.84  5003.3  425.84  5003.5  426.34
  5018.5  428.00  5023.7  429.17  5032.5  429.09  5042.9  430.51  5053.2  433.08
  5064.3  436.34  5073.9  434.47  5099.7  437.80  5115.2  438.58  5125.5  438.67
  5146.2  439.82  5166.8  440.07  5180.9  440.84  5208.2  441.32  5259.4  443.71
#Mann=4,-1,0
  4610.5    0.05       0  4927.9    0.16       0  4999.5    0.07       0
  5003.5    0.16       0
Bank Sta=4999.5,5003.5
Exp/Cntr=0.3,0.1

Type RM Length L Ch R = 1,1305,542,542,542
BEGIN DESCRIPTION:
NORTH MINERAL CR TRIB 8 6 1 40
END DESCRIPTION:
XS GIS Cut Line= 3
      3495078.22     10396239.50      3495343.00     10396133.16
      3495842.14     10396048.52
#Sta/Elev= 30
  4476.2  445.29  4592.4  442.61  4724.1  437.84  4812.1  435.53  4841.8  434.11
  4851.9  432.60  4858.7  430.63  4863.7  431.01  4872.2  430.07  4882.3  430.00
  4902.6  433.34  4924.1  433.88  4943.2  433.66  4953.3  431.86  4973.6  425.81
  4979.3  424.47  4984.4  424.75  5002.1  422.86  5002.3  422.36  5005.8  422.36
  5006.1  422.86  5014.2  428.90  5024.3  434.04  5034.5  434.85  5054.8  435.68
  5094.9  436.13  5105.5  436.82  5166.3  438.37  5196.8  438.58  5267.8  440.04
#Mann=4,-1,0
  4476.2    0.05       0  4812.1    0.16       0  5002.1    0.07       0
  5006.1    0.16       0
Bank Sta=5002.1,5006.1
Exp/Cntr=0.3,0.1

Type RM Length L Ch R = 1,763,583,583,583
BEGIN DESCRIPTION:
Mapping XS e81f7b87
END DESCRIPTION:
XS GIS Cut Line= 4
      3495440.55     10396536.64      3495556.42     10396511.90
      3495684.03     10396235.86      3496082.43     10396091.34
#Sta/Elev= 30
  4800.3  436.82  4962.9  432.75  4968.4  431.72  4974.2  428.52  4982.4  426.01
  4991.3  422.25  4994.8  418.57  4995.1  418.07  4998.6  418.07  4998.8  418.57
  5014.2  418.76  5019.7  423.28  5042.7  429.95  5051.3  430.83  5065.6  431.10
  5111.5  430.25  5128.4  431.18  5139.9  430.85  5185.8  431.46  5222.5  432.72
  5248.7  432.68  5304.6  434.19  5335.2  434.35  5340.5  434.88  5359.1  434.65
  5391.0  435.23  5433.6  436.60  5452.4  436.54  5574.9  439.40  5646.7  439.95
#Mann=4,-1,0
  4800.3    0.05       0  4982.4    0.16       0  4994.8    0.07       0
  4998.8    0.16       0
Bank Sta=4994.8,4998.8
Exp/Cntr=0.3,0.1

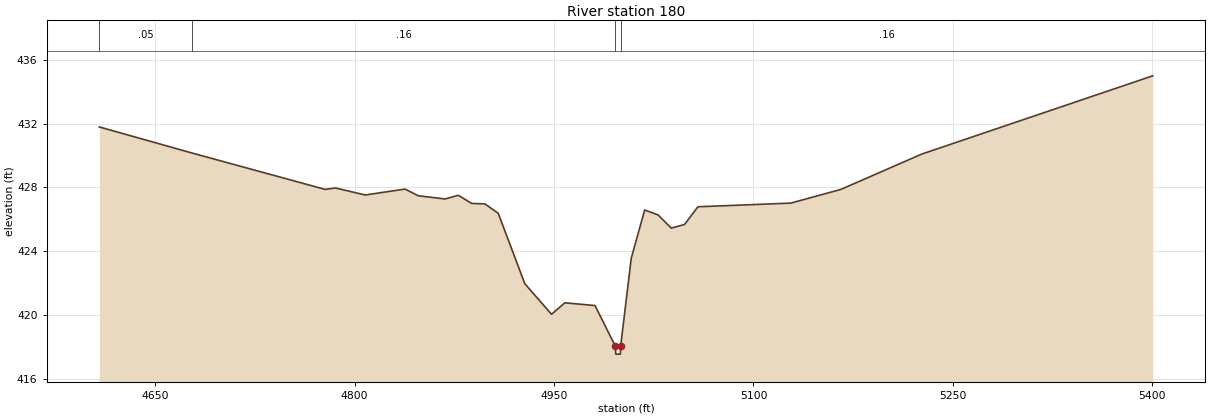
Type RM Length L Ch R = 1,180,0,0,0
BEGIN DESCRIPTION:
NORTH MINERAL CR TRIB 8 6 1 10
END DESCRIPTION:
XS GIS Cut Line= 3
      3495642.41     10396586.12      3496161.89     10396558.78
      3496208.77     10396290.55
#Sta/Elev= 30
  4607.9  431.80  4677.4  430.17  4777.8  427.88  4785.5  427.97  4807.9  427.53
  4837.9  427.90  4847.9  427.48  4868.0  427.28  4878.0  427.51  4888.0  427.00
  4898.0  426.97  4908.0  426.38  4928.0  421.96  4948.1  420.04  4958.1  420.76
  4980.8  420.59  4996.1  418.04  4996.4  417.54  4999.9  417.54  5000.1  418.04
  5008.1  423.57  5018.2  426.59  5028.2  426.28  5038.2  425.45  5048.2  425.68
  5058.2  426.79  5128.1  427.02  5165.8  427.88  5226.7  430.10  5400.4  435.01
#Mann=4,-1,0
  4607.9    0.05       0  4677.4    0.16       0  4996.1    0.07       0
  5000.1    0.16       0
Bank Sta=4996.1,5000.1
Exp/Cntr=0.3,0.1

Chan Stop Cuts=-1