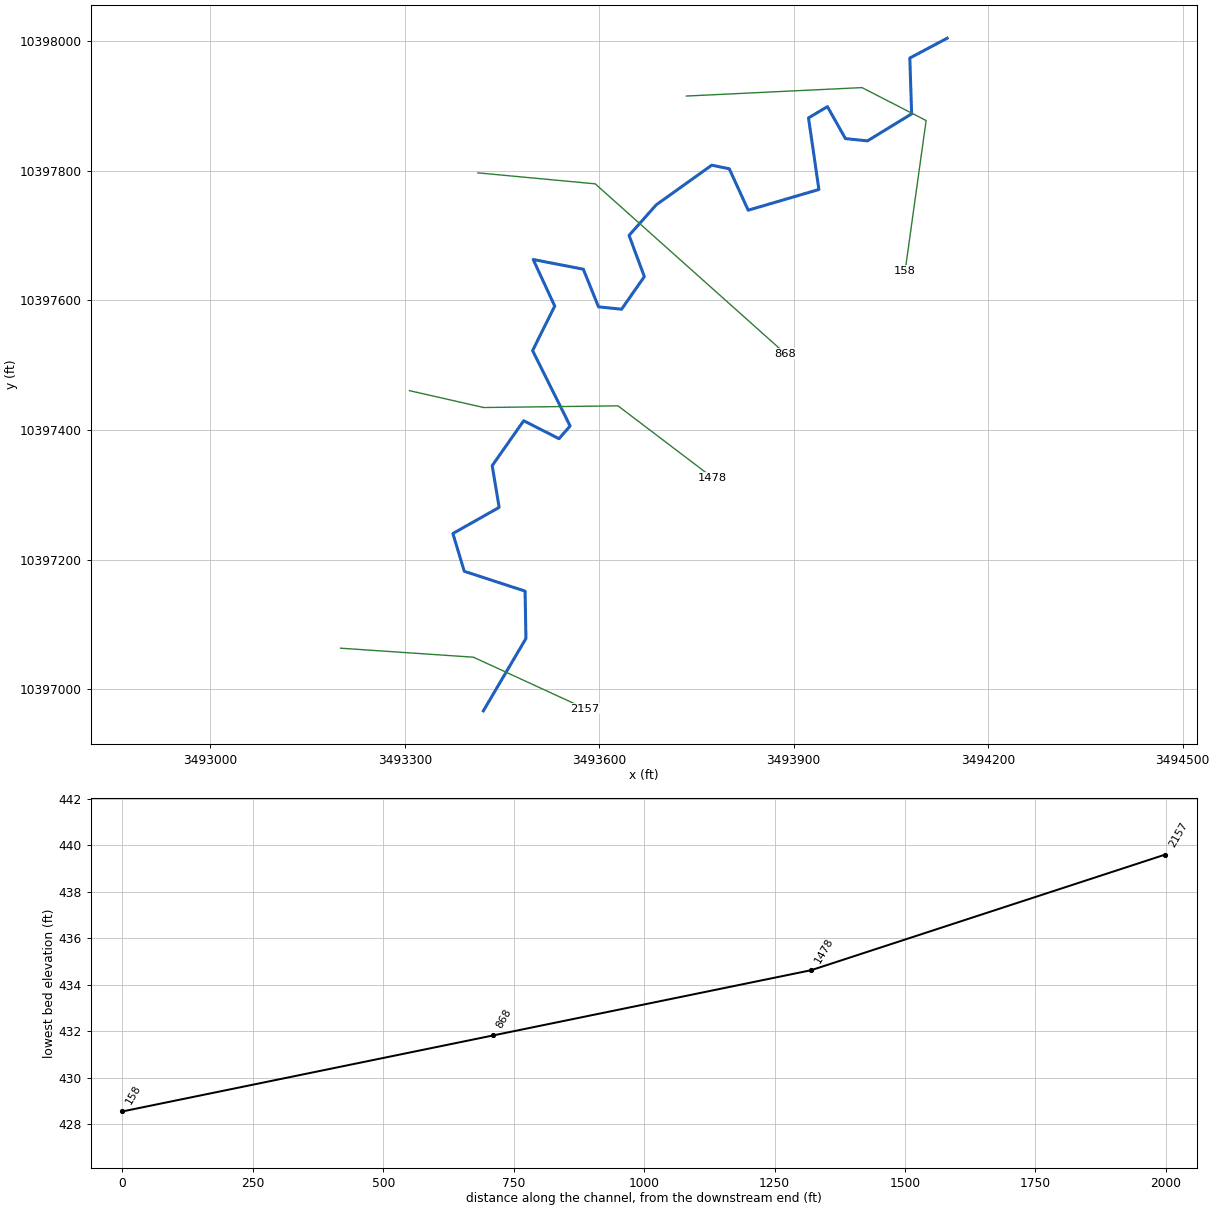
--- NORTH MINERAL CR TRIB 8 6 2.prj (project) ---

Proj Title=NORTH MINERAL CR TRIB 8 6 2 Base Level Engineering
Current Plan=p01
Default Exp/Contr=0.3,0.1
English Units
Geom File=g01
Flow File=f01
Plan File=p01
BEGIN DESCRIPTION:
NORTH MINERAL CR TRIB 8 6 2
END DESCRIPTION:

--- NORTH MINERAL CR TRIB 8 6 2.p01 (plan) ---

Plan Title=Multiple Run
Short Identifier=Multiple
Geom File=g01
Flow File=f01
Subcritical Flow
K Sum by GR= 0
Std Step Tol= 0.01
Critical Tol= 0.01
Num of Std Step Trials= 20
Max Error Tol= 0.3
Flow Tol Ratio= 0.001
Split Flow NTrial= 30
Split Flow Tol= 0.02
Split Flow Ratio= 0.02
Log Output Level= 0
Friction Slope Method= 1
Unsteady Friction Slope Method= 2
Unsteady Bridges Friction Slope Method= 1
Parabolic Critical Depth
Global Vel Dist=  1 , 1 , 1
Global Log Level= 0
CheckData=True
Encroach Param= -1, 0, 0, 0
BEGIN DESCRIPTION:
Multiple Run
END DESCRIPTION:

--- NORTH MINERAL CR TRIB 8 6 2.f01 (steady flow) ---

Flow Title=Multiple
Number of Profiles=7
Profile Names=10-year,25-year,50-year,1pct_min,100-year,1pct_plu,500-year
River Rch & RM= NORTH MINERAL CR,Reach-1,2157
     427     565     675     590     798    1080    1113
Boundary for River Rch & Prof#=NORTH MINERAL CR,Reach-1,1
Up Type=0
Dn Type=3
Dn Slope=0.005
Boundary for River Rch & Prof#=NORTH MINERAL CR,Reach-1,2
Up Type=0
Dn Type=3
Dn Slope=0.005
Boundary for River Rch & Prof#=NORTH MINERAL CR,Reach-1,3
Up Type=0
Dn Type=3
Dn Slope=0.005
Boundary for River Rch & Prof#=NORTH MINERAL CR,Reach-1,4
Up Type=0
Dn Type=3
Dn Slope=0.005
Boundary for River Rch & Prof#=NORTH MINERAL CR,Reach-1,5
Up Type=0
Dn Type=3
Dn Slope=0.005
Boundary for River Rch & Prof#=NORTH MINERAL CR,Reach-1,6
Up Type=0
Dn Type=3
Dn Slope=0.005
Boundary for River Rch & Prof#=NORTH MINERAL CR,Reach-1,7
Up Type=0
Dn Type=3
Dn Slope=0.005

--- NORTH MINERAL CR TRIB 8 6 2.g01 (geometry) ---

Geom Title=Existing Conditions

River Reach=NORTH MINERAL CR,Reach-1
Reach XY= 30
      3493421.30     10396967.00      3493486.92     10397078.58
      3493485.64     10397151.64      3493391.80     10397182.25
      3493374.28     10397240.48      3493445.58     10397280.78
      3493434.90     10397345.22      3493483.48     10397414.40
      3493537.98     10397386.76      3493555.07     10397406.40
      3493497.20     10397522.65      3493531.36     10397591.31
      3493498.11     10397663.14      3493575.43     10397648.21
      3493598.86     10397590.17      3493634.44     10397586.44
      3493669.57     10397636.76      3493646.01     10397700.34
      3493687.74     10397747.28      3493773.51     10397808.64
      3493800.59     10397803.09      3493829.76     10397739.20
      3493938.79     10397771.14      3493922.82     10397881.56
      3493951.98     10397898.92      3493979.76     10397849.62
      3494013.79     10397846.14      3494081.84     10397887.81
      3494079.07     10397973.92      3494136.71     10398004.48

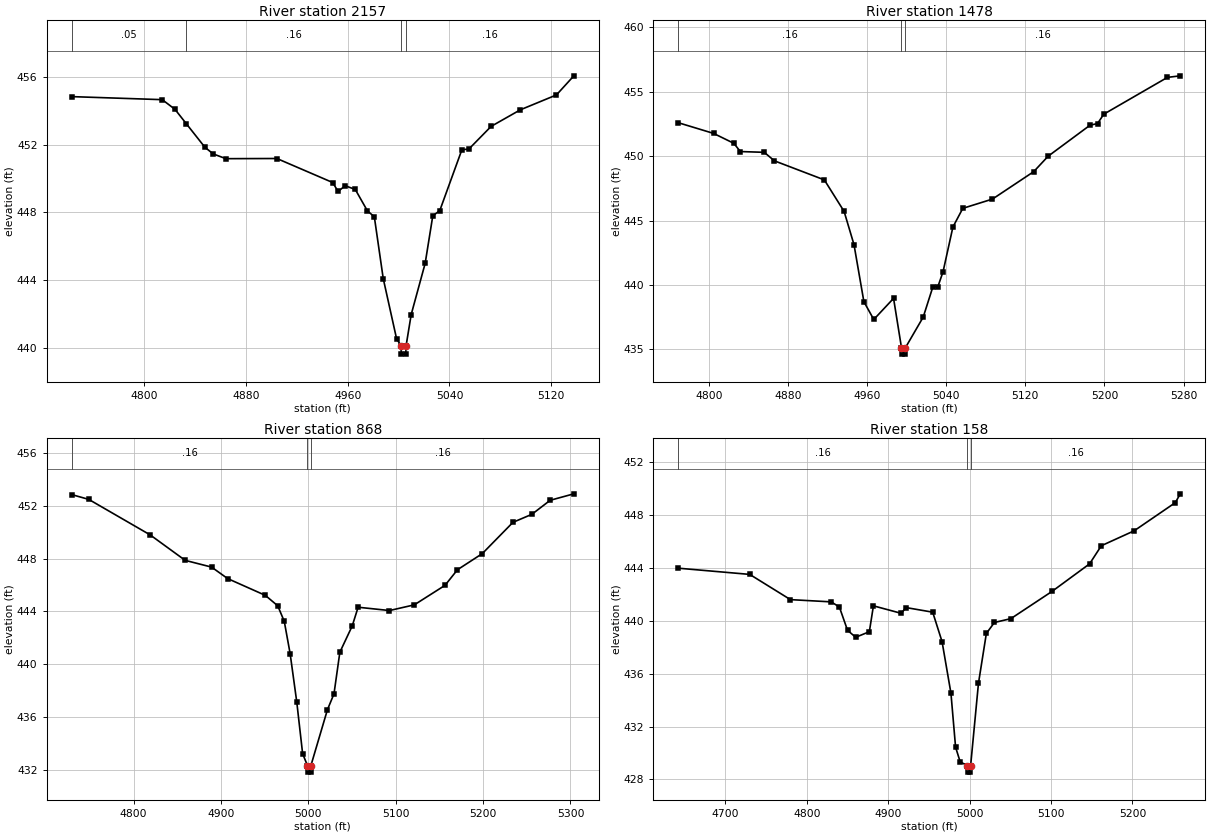
Type RM Length L Ch R = 1,2157,679,679,679
BEGIN DESCRIPTION:
NORTH MINERAL CR TRIB 8 6 2 30
END DESCRIPTION:
XS GIS Cut Line= 3
      3493201.11     10397063.61      3493405.96     10397049.73
      3493578.37     10396970.42
#Sta/Elev= 30
  4742.8  454.84  4814.0  454.66  4824.0  454.09  4832.8  453.25  4847.5  451.85
  4854.1  451.45  4864.1  451.17  4904.2  451.18  4948.1  449.76  4952.4  449.23
  4957.9  449.57  4965.9  449.35  4975.4  448.09  4980.9  447.73  4987.9  444.08
  4998.4  440.52  5001.9  440.11  5002.1  439.61  5005.6  439.61  5005.9  440.11
  5009.9  441.95  5020.9  444.98  5026.9  447.79  5032.4  448.10  5049.8  451.70
  5055.3  451.74  5072.8  453.08  5095.8  454.06  5124.2  454.94  5137.9  456.07
#Mann=4,-1,0
  4742.8    0.05       0  4832.8    0.16       0  5001.9    0.07       0
  5005.9    0.16       0
Bank Sta=5001.9,5005.9
Exp/Cntr=0.3,0.1

Type RM Length L Ch R = 1,1478,610,610,610
BEGIN DESCRIPTION:
NORTH MINERAL CR TRIB 8 6 2 20
END DESCRIPTION:
XS GIS Cut Line= 4
      3493307.32     10397460.87      3493421.92     10397434.82
      3493628.95     10397437.43      3493774.74     10397326.78
#Sta/Elev= 30
  4769.1  452.60  4804.8  451.77  4825.3  451.00  4831.9  450.36  4856.1  450.30
  4866.3  449.64  4916.8  448.16  4936.8  445.71  4946.8  443.13  4956.8  438.70
  4966.8  437.32  4986.8  438.96  4994.8  435.13  4995.1  434.63  4998.6  434.63
  4998.8  435.13  5016.8  437.51  5026.6  439.87  5031.6  439.87  5036.8  441.02
  5046.8  444.50  5056.8  445.95  5086.8  446.67  5128.5  448.80  5143.1  450.00
  5185.5  452.41  5193.0  452.53  5199.3  453.26  5263.7  456.12  5276.7  456.24
#Mann=3,-1,0
  4769.1    0.16       0  4994.8    0.07       0  4998.8    0.16       0
Bank Sta=4994.8,4998.8
Exp/Cntr=0.3,0.1

Type RM Length L Ch R = 1,868,710,710,710
BEGIN DESCRIPTION:
Mapping XS 22aa285d
END DESCRIPTION:
XS GIS Cut Line= 3
      3493412.83     10397796.80      3493593.79     10397779.87
      3493886.76     10397518.16
#Sta/Elev= 30
  4729.3  452.84  4748.7  452.48  4819.0  449.79  4859.1  447.86  4889.3  447.35
  4907.7  446.48  4950.8  445.21  4965.0  444.42  4972.5  443.24  4979.2  440.80
  4986.8  437.13  4993.5  433.22  4999.0  432.32  4999.2  431.82  5002.7  431.82
  5003.0  432.32  5021.9  436.55  5029.4  437.75  5036.1  440.90  5050.3  442.90
  5057.0  444.31  5092.9  444.06  5121.3  444.49  5156.5  445.97  5170.7  447.15
  5199.1  448.37  5234.2  450.74  5255.9  451.35  5276.8  452.41  5303.9  452.90
#Mann=3,-1,0
  4729.3    0.16       0  4999.0    0.07       0  5003.0    0.16       0
Bank Sta=4999,5003
Exp/Cntr=0.3,0.1

Type RM Length L Ch R = 1,158,0,0,0
BEGIN DESCRIPTION:
NORTH MINERAL CR TRIB 8 6 2 10
END DESCRIPTION:
XS GIS Cut Line= 4
      3493734.44     10397915.29      3494005.25     10397928.31
      3494104.21     10397877.53      3494071.81     10397645.53
#Sta/Elev= 30
  4642.2  443.99  4730.0  443.52  4780.0  441.61  4830.1  441.44  4840.1  441.05
  4850.1  439.29  4860.1  438.76  4876.9  439.18  4881.9  441.14  4916.2  440.57
  4921.8  441.01  4954.7  440.66  4966.2  438.43  4977.1  434.53  4982.8  430.44
  4988.5  429.32  4997.3  429.05  4997.6  428.55  5001.1  428.55  5001.3  429.05
  5010.9  435.27  5020.6  439.05  5030.5  439.88  5050.7  440.17  5101.2  442.23
  5147.4  444.32  5161.8  445.69  5202.1  446.82  5252.6  448.95  5258.8  449.62
#Mann=3,-1,0
  4642.2    0.16       0  4997.3    0.07       0  5001.3    0.16       0
Bank Sta=4997.3,5001.3
Exp/Cntr=0.3,0.1

Chan Stop Cuts=-1