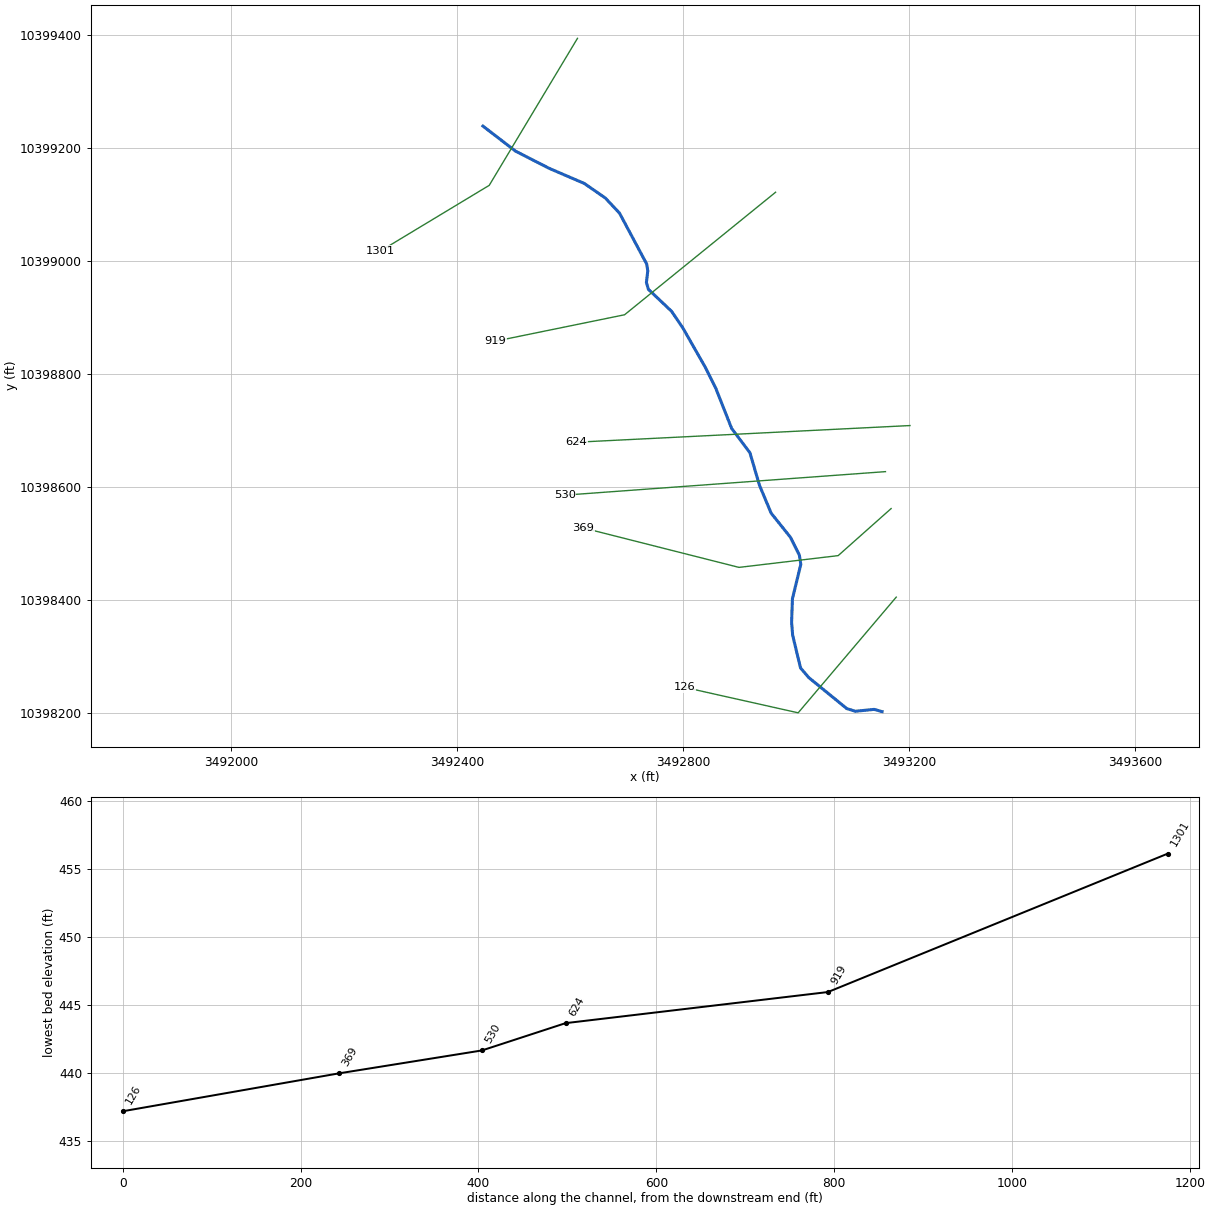
--- NORTH MINERAL CR TRIB 8 6 3.prj (project) ---

Proj Title=NORTH MINERAL CR TRIB 8 6 3 Base Level Engineering
Current Plan=p01
Default Exp/Contr=0.3,0.1
English Units
Geom File=g01
Flow File=f01
Plan File=p01
Y Axis Title=Elevation
X Axis Title(PF)=Main Channel Distance
X Axis Title(XS)=Station
BEGIN DESCRIPTION:
NORTH MINERAL CR TRIB 8 6 3
END DESCRIPTION:
DSS Export Rating Curves= 0
DSS Export Rating Curve Sorted= 0
DSS Export Volume Flow Curves= 0
DXF OffsetX= 0
DXF OffsetY= 0
DXF ScaleX= 1
DXF ScaleY= 10

--- NORTH MINERAL CR TRIB 8 6 3.p01 (plan) ---

Plan Title=Multiple Run
Short Identifier=Multiple
Geom File=g01
Flow File=f01
Subcritical Flow
K Sum by GR= 0
Std Step Tol= 0.01
Critical Tol= 0.01
Num of Std Step Trials= 20
Max Error Tol= 0.3
Flow Tol Ratio= 0.001
Split Flow NTrial= 30
Split Flow Tol= 0.02
Split Flow Ratio= 0.02
Log Output Level= 0
Friction Slope Method= 1
Unsteady Friction Slope Method= 2
Unsteady Bridges Friction Slope Method= 1
Parabolic Critical Depth
Global Vel Dist=  1 , 1 , 1
Global Log Level= 0
CheckData=True
Encroach Param= -1, 0, 0, 0
BEGIN DESCRIPTION:
Multiple Run
END DESCRIPTION:

--- NORTH MINERAL CR TRIB 8 6 3.f01 (steady flow) ---

Flow Title=Multiple
Number of Profiles=7
Profile Names=10-year,25-year,50-year,1pct_min,100-year,1pct_plu,500-year
River Rch & RM= NORTH MINERAL CR,Reach-1,1301
     355     461     544     470     636     860     866
Boundary for River Rch & Prof#=NORTH MINERAL CR,Reach-1,1
Up Type=0
Dn Type=3
Dn Slope=0.005
Boundary for River Rch & Prof#=NORTH MINERAL CR,Reach-1,2
Up Type=0
Dn Type=3
Dn Slope=0.005
Boundary for River Rch & Prof#=NORTH MINERAL CR,Reach-1,3
Up Type=0
Dn Type=3
Dn Slope=0.005
Boundary for River Rch & Prof#=NORTH MINERAL CR,Reach-1,4
Up Type=0
Dn Type=3
Dn Slope=0.005
Boundary for River Rch & Prof#=NORTH MINERAL CR,Reach-1,5
Up Type=0
Dn Type=3
Dn Slope=0.005
Boundary for River Rch & Prof#=NORTH MINERAL CR,Reach-1,6
Up Type=0
Dn Type=3
Dn Slope=0.005
Boundary for River Rch & Prof#=NORTH MINERAL CR,Reach-1,7
Up Type=0
Dn Type=3
Dn Slope=0.005

--- NORTH MINERAL CR TRIB 8 6 3.g01 (geometry) ---

Geom Title=Existing Conditions
Program Version=4.10

River Reach=NORTH MINERAL CR,Reach-1
Reach XY= 30
      3492445.51     10399238.53      3492503.17     10399194.21
      3492562.94     10399163.64      3492624.94     10399136.98
      3492662.12     10399111.23      3492687.24     10399084.47
      3492735.41     10398994.22      3492737.31     10398982.12
      3492734.86     10398961.66      3492738.36     10398949.54
      3492779.47     10398910.51      3492799.63      10398880.7
       3492839.6     10398810.61      3492857.62      10398774.5
      3492885.75     10398703.15      3492918.17     10398660.01
      3492934.91      10398602.8      3492955.67      10398553.1
      3492989.76     10398510.54      3493005.67      10398478.7
      3493008.21     10398462.46      3492993.36     10398401.72
      3492991.88     10398359.93      3492993.73     10398337.09
      3493007.65     10398279.16      3493022.07     10398262.15
      3493089.64     10398206.98      3493104.91     10398202.34
      3493137.94     10398205.65      3493152.11     10398201.64

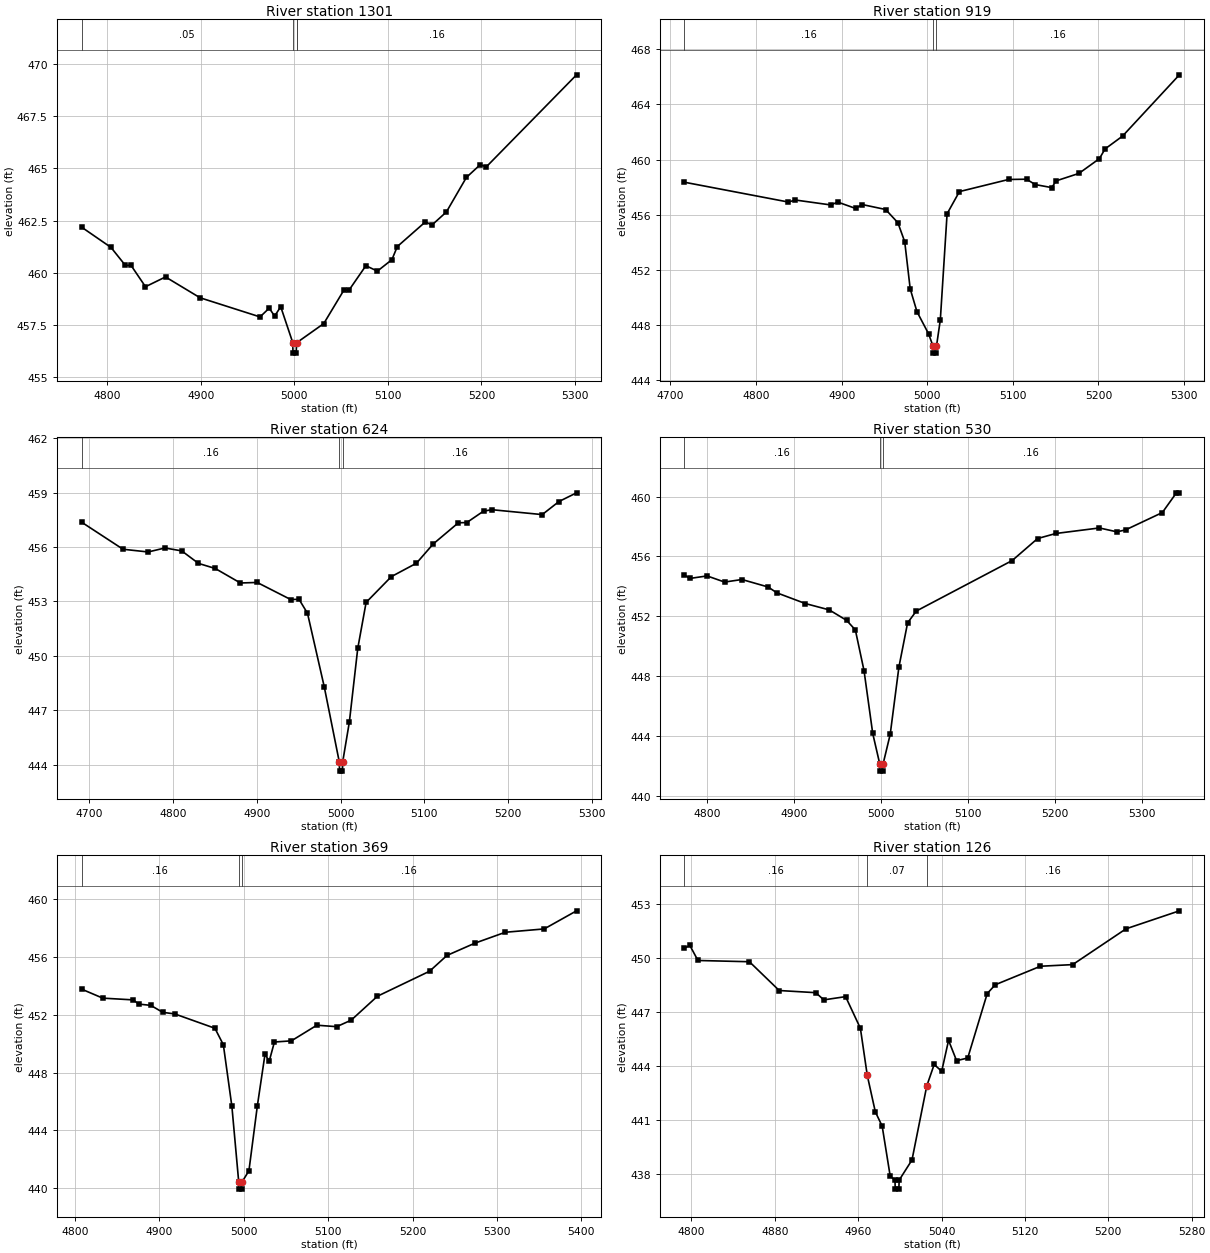
Type RM Length L Ch R = 1 ,1301    ,382,382,382
BEGIN DESCRIPTION:
NORTH MINERAL CR TRIB 8 6 3 3
END DESCRIPTION:
XS GIS Cut Line= 3
      3492612.87     10399393.99      3492456.64     10399133.61
      3492263.89     10399017.26
#Sta/Elev= 30
  4772.8  462.18  4804.1  461.21  4819.6  460.34  4825.5  460.35    4841  459.32
  4862.4  459.79  4899.3  458.79  4963.4  457.87  4973.2  458.29    4979  457.91
  4985.5  458.36  4998.4  456.63  4998.6  456.13  5002.1  456.13  5002.4  456.63
  5002.9  456.64  5031.5  457.55  5052.9  459.15  5058.7  459.17  5076.5  460.33
  5088.8  460.07  5104.3  460.62  5110.1  461.25  5140.2  462.44    5147  462.28
  5162.5  462.91  5183.9  464.57  5198.6  465.18  5205.2  465.08  5301.6   469.5
#Mann= 4 ,-1 , 0
  4772.8     .05       0  4998.4     .03       0  5002.4     .05       0
  5002.9     .16       0
Bank Sta=4998.4,5002.4
XS Rating Curve= 0 ,0
Exp/Cntr=0.3,0.1

Type RM Length L Ch R = 1 ,919     ,295,295,295
BEGIN DESCRIPTION:
NORTH MINERAL CR TRIB 8 6 3 2
END DESCRIPTION:
XS GIS Cut Line= 3
      3492963.56     10399121.44      3492696.22     10398904.44
      3492467.09     10398857.57
#Sta/Elev= 30
  4716.4  458.35  4837.9  456.91  4845.8  457.06  4887.4   456.7  4895.4  456.91
  4916.2  456.45  4924.1  456.73  4951.4  456.37  4965.7  455.41  4973.7  454.03
  4980.1  450.61    4988  448.95  5001.6  447.34  5006.8  446.44  5007.1  445.94
  5010.6  445.94  5010.8  446.44  5015.3  448.36  5023.2  456.06  5037.6  457.67
    5095  458.55    5116  458.57  5126.2  458.18  5145.5  457.96  5150.6  458.45
  5177.2  458.99  5201.1  460.06  5207.8  460.77  5228.2   461.7  5294.6  466.15
#Mann= 3 ,-1 , 0
  4716.4     .16       0  5006.8     .07       0  5010.8     .16       0
Bank Sta=5006.8,5010.8
XS Rating Curve= 0 ,0
Exp/Cntr=0.3,0.1

Type RM Length L Ch R = 1 ,624     ,94,94,94
BEGIN DESCRIPTION:
Mapping XS 1d92d77c
END DESCRIPTION:
XS GIS Cut Line= 2
      3493201.43     10398708.26      3492611.16     10398678.75
#Sta/Elev= 30
  4690.8  457.37  4740.2  455.88  4770.2  455.73  4790.2  455.95  4810.3  455.79
  4830.3   455.1  4850.3  454.82  4880.4  454.02  4900.4  454.05  4940.4  453.11
  4950.4  453.12  4960.5  452.35  4980.5   448.3  4998.5  444.15  4998.8  443.65
  5002.3  443.65  5002.5  444.15  5010.5  446.36  5020.5  450.41  5030.5  452.95
  5060.6  454.37  5090.6  455.11  5110.6  456.17  5140.7  457.34  5150.7  457.35
  5170.7  457.98  5180.7  458.06  5240.8  457.79  5260.8  458.51  5281.8  458.99
#Mann= 3 ,-1 , 0
  4690.8     .16       0  4998.5     .07       0  5002.5     .16       0
Bank Sta=4998.5,5002.5
XS Rating Curve= 0 ,0
Exp/Cntr=0.3,0.1

Type RM Length L Ch R = 1 ,530     ,161,161,161
BEGIN DESCRIPTION:
Mapping XS ec748cc2
END DESCRIPTION:
XS GIS Cut Line= 2
      3493158.04     10398626.66      3492590.36       10398585.
#Sta/Elev= 30
    4774  454.77  4779.9  454.53    4800   454.7  4820.1  454.29  4840.1  454.46
  4870.2  453.96  4880.2  453.57  4913.1  452.85  4940.4  452.43  4960.4  451.73
  4970.5  451.09  4980.5  448.36  4990.5  444.16  4998.5  442.14  4998.8  441.64
  5002.3  441.64  5002.5  442.14  5010.6   444.1  5020.6   448.6  5030.6  451.56
  5040.6  452.35  5150.9  455.73  5180.1   457.2  5201.1  457.54  5251.2  457.91
  5271.3  457.65  5281.3  457.78  5323.6  458.94  5339.8  460.26  5343.2  460.26
#Mann= 3 ,-1 , 0
    4774     .16       0  4998.5     .07       0  5002.5     .16       0
Bank Sta=4998.5,5002.5
XS Rating Curve= 0 ,0
Exp/Cntr=0.3,0.1

Type RM Length L Ch R = 1 ,369     ,243,243,243
BEGIN DESCRIPTION:
Mapping XS 91976c3a
END DESCRIPTION:
XS GIS Cut Line= 4
      3493168.07     10398561.28       3493074.3     10398477.93
      3492898.78      10398457.1      3492623.29     10398526.88
#Sta/Elev= 30
  4807.9  453.76  4832.9  453.14  4868.9  453.02  4875.6  452.73  4889.8  452.64
    4904  452.16  4918.2  452.05  4965.8  451.06  4975.8  449.92  4985.9  445.67
    4994  440.45  4994.2  439.95  4997.7  439.95    4998  440.45  5006.1  441.22
  5016.1  445.71  5025.1  449.25  5030.2   448.8  5036.3  450.11  5056.4  450.19
  5086.6  451.27  5110.1  451.17  5127.3  451.62  5158.3  453.27  5220.2     455
  5240.8  456.09    5274  456.94  5309.9  457.69    5356  457.92  5394.3  459.17
#Mann= 3 ,-1 , 0
  4807.9     .16       0    4994     .07       0    4998     .16       0
Bank Sta=4994,4998
XS Rating Curve= 0 ,0
Exp/Cntr=0.3,0.1

Type RM Length L Ch R = 1 ,126     ,0,0,0
BEGIN DESCRIPTION:
NORTH MINERAL CR TRIB 8 6 3 1
END DESCRIPTION:
XS GIS Cut Line= 3
      3493177.12     10398404.44      3493003.52     10398199.58
      3492802.14     10398244.71
#Sta/Elev= 30
  4793.3  450.55  4798.4  450.71  4806.2  449.87  4855.6   449.8  4884.2   448.2
  4919.3  448.08    4927  447.68  4947.9  447.86  4962.1   446.1  4968.7  443.48
  4976.4  441.46    4983  440.66  4990.7  437.88  4995.3  437.66  4995.5  437.16
    4999  437.16  4999.3  437.66  5011.6  438.78  5025.8   442.9  5032.9  444.09
  5040.1  443.71  5046.7  445.43  5054.4   444.3  5065.1  444.45  5083.8  448.03
  5091.5  448.52  5134.9  449.55  5165.8  449.64    5217  451.63  5268.2  452.63
#Mann= 3 , 0 , 0
  4793.3     .16       0  4968.7     .07       0  5025.8     .16       0
Bank Sta=4968.7,5025.8
XS Rating Curve= 0 ,0
Exp/Cntr=0.3,0.1

Chan Stop Cuts=-1
Use User Specified Reach Order=0
Composite Channel Slope=5