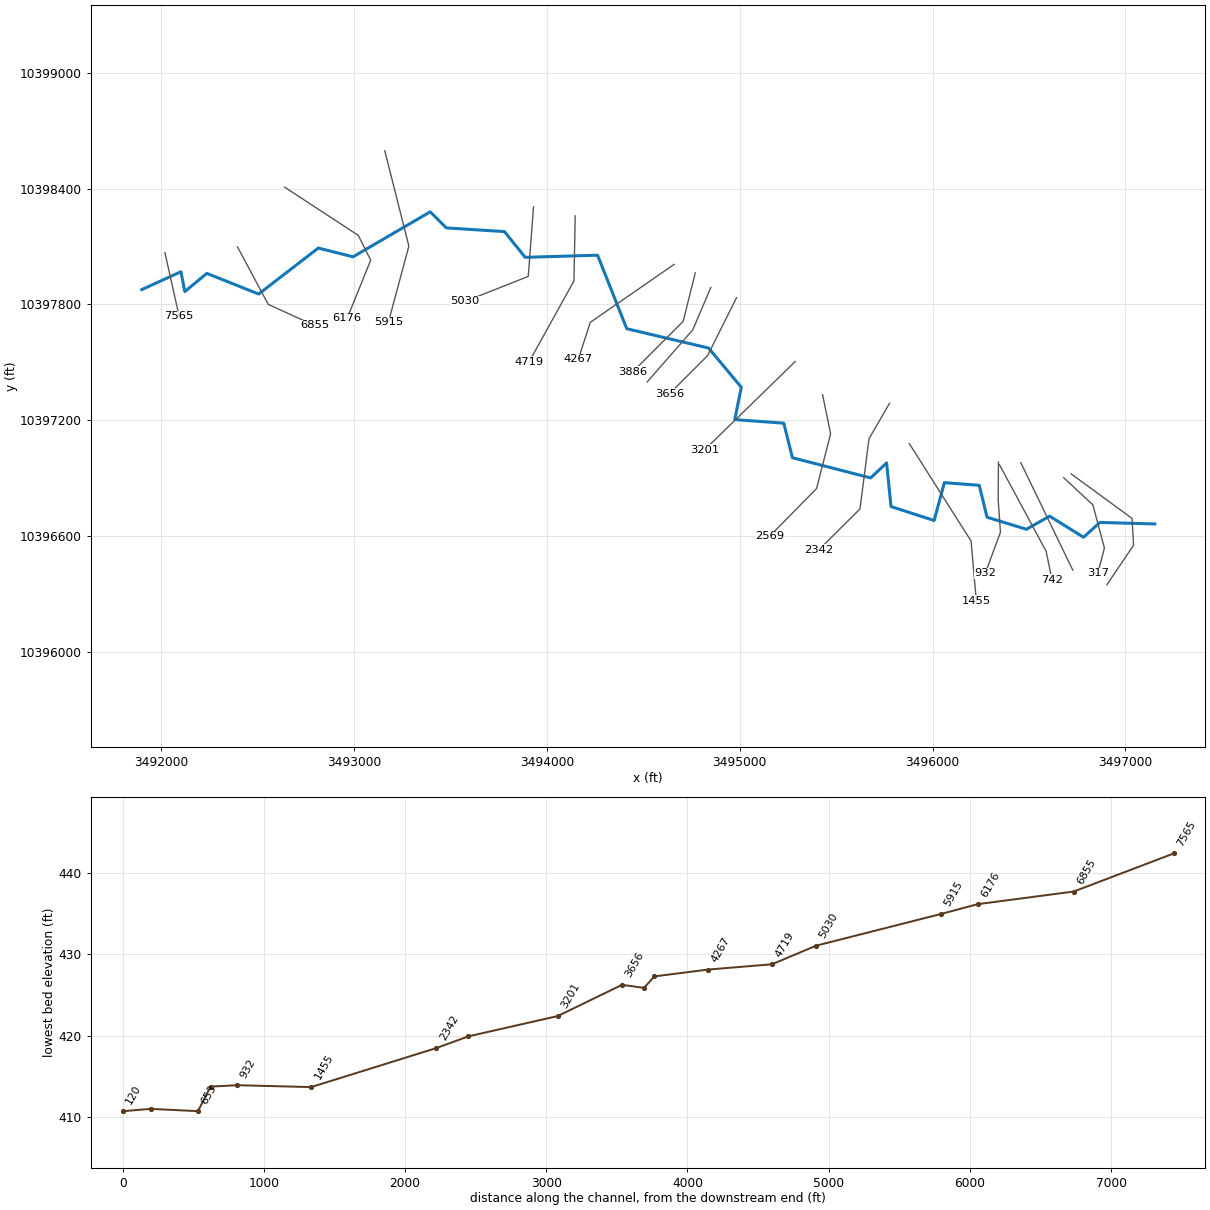
--- NORTH MINERAL CR TRIB 8 6.prj (project) ---

Proj Title=NORTH MINERAL CR TRIB 8 6 Base Level Engineering
Current Plan=p01
Default Exp/Contr=0.3,0.1
English Units
Geom File=g01
Flow File=f01
Plan File=p01
BEGIN DESCRIPTION:
NORTH MINERAL CR TRIB 8 6
END DESCRIPTION:

--- NORTH MINERAL CR TRIB 8 6.p01 (plan) ---

Plan Title=Multiple Run
Short Identifier=Multiple
Geom File=g01
Flow File=f01
Subcritical Flow
K Sum by GR= 0
Std Step Tol= 0.01
Critical Tol= 0.01
Num of Std Step Trials= 20
Max Error Tol= 0.3
Flow Tol Ratio= 0.001
Split Flow NTrial= 30
Split Flow Tol= 0.02
Split Flow Ratio= 0.02
Log Output Level= 0
Friction Slope Method= 1
Unsteady Friction Slope Method= 2
Unsteady Bridges Friction Slope Method= 1
Parabolic Critical Depth
Global Vel Dist=  1 , 1 , 1
Global Log Level= 0
CheckData=True
Encroach Param= -1, 0, 0, 0
BEGIN DESCRIPTION:
Multiple Run
END DESCRIPTION:

--- NORTH MINERAL CR TRIB 8 6.f01 (steady flow) ---

Flow Title=Multiple
Number of Profiles=7
Profile Names=10-year,25-year,50-year,1pct_min,100-year,1pct_plu,500-year
River Rch & RM= NORTH MINERAL CR,Reach-1,7565
     488     646     771     674     911    1232    1267
River Rch & RM= NORTH MINERAL CR,Reach-1,5915
     721     979    1189    1055    1426    1929    2047
River Rch & RM= NORTH MINERAL CR,Reach-1,4719
    1034    1433    1764    1584    2143    2898    3153
River Rch & RM= NORTH MINERAL CR,Reach-1,1455
    1205    1683    2081    1876    2538    3432    3767
Boundary for River Rch & Prof#=NORTH MINERAL CR,Reach-1,1
Up Type=0
Dn Type=3
Dn Slope=0.005
Boundary for River Rch & Prof#=NORTH MINERAL CR,Reach-1,2
Up Type=0
Dn Type=3
Dn Slope=0.005
Boundary for River Rch & Prof#=NORTH MINERAL CR,Reach-1,3
Up Type=0
Dn Type=3
Dn Slope=0.005
Boundary for River Rch & Prof#=NORTH MINERAL CR,Reach-1,4
Up Type=0
Dn Type=3
Dn Slope=0.005
Boundary for River Rch & Prof#=NORTH MINERAL CR,Reach-1,5
Up Type=0
Dn Type=3
Dn Slope=0.005
Boundary for River Rch & Prof#=NORTH MINERAL CR,Reach-1,6
Up Type=0
Dn Type=3
Dn Slope=0.005
Boundary for River Rch & Prof#=NORTH MINERAL CR,Reach-1,7
Up Type=0
Dn Type=3
Dn Slope=0.005

--- NORTH MINERAL CR TRIB 8 6.g01 (geometry) ---

Geom Title=Existing Conditions

River Reach=NORTH MINERAL CR,Reach-1
Reach XY= 30
      3491900.11     10397876.85      3492102.91     10397969.53
      3492123.17     10397866.48      3492237.14     10397960.86
      3492505.93     10397853.83      3492815.29     10398092.20
      3492995.37     10398046.83      3493395.51     10398280.07
      3493478.79     10398196.81      3493780.17     10398177.53
      3493887.80     10398044.19      3494263.09     10398055.17
      3494414.48     10397673.92      3494838.70     10397573.69
      3495008.39     10397370.31      3494974.36     10397202.66
      3495228.76     10397184.02      3495273.31     10397005.05
      3495679.07     10396900.31      3495761.71     10396978.09
      3495784.62     10396751.70      3496008.23     10396679.56
      3496061.18     10396875.74      3496242.17     10396861.86
      3496282.54     10396696.49      3496486.53     10396633.99
      3496607.07     10396701.96      3496782.73     10396592.60
      3496867.50     10396669.44      3497152.11     10396661.64

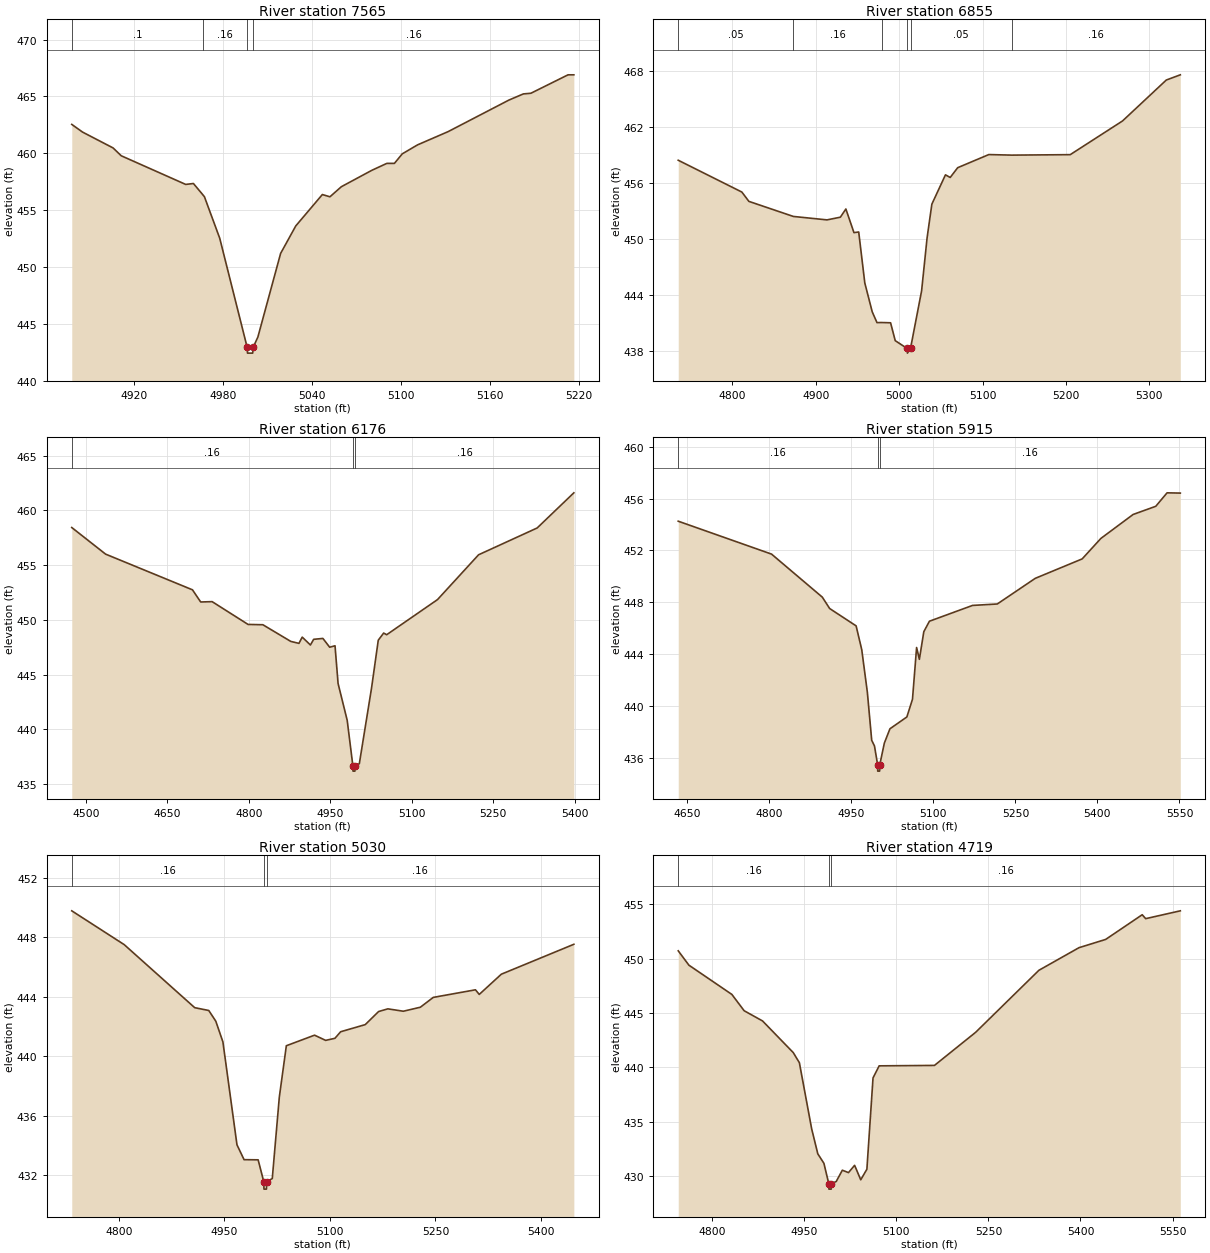
Type RM Length L Ch R = 1,7565,710,710,710
BEGIN DESCRIPTION:
NORTH MINERAL CR TRIB 8 6 2 5
END DESCRIPTION:
XS GIS Cut Line= 2
      3492019.75     10398068.81      3492093.53     10397738.96
#Sta/Elev= 30
  4878.4  462.54  4885.7  461.86  4906.2  460.47  4911.7  459.78  4955.1  457.26
  4960.3  457.34  4966.7  456.34  4967.7  456.18  4978.0  452.53  4996.5  442.92
  4996.7  442.42  5000.2  442.42  5000.5  442.92  5003.7  443.84  5019.0  451.19
  5029.2  453.61  5047.1  456.37  5052.2  456.17  5059.9  457.06  5080.4  458.50
  5090.5  459.11  5095.6  459.11  5100.9  459.95  5111.2  460.74  5131.7  461.90
  5172.7  464.68  5182.4  465.22  5187.5  465.28  5212.5  466.90  5216.4  466.90
#Mann=4,-1,0
  4878.4     0.1       0  4966.7    0.16       0  4996.5    0.07       0
  5000.5    0.16       0
Bank Sta=4996.5,5000.5
Exp/Cntr=0.3,0.1

Type RM Length L Ch R = 1,6855,679,679,679
BEGIN DESCRIPTION:
NORTH MINERAL CR TRIB 8 6 2 0
END DESCRIPTION:
XS GIS Cut Line= 3
      3492395.86     10398098.91      3492555.60     10397800.27
      3492795.14     10397690.92
#Sta/Elev= 30
  4735.1  458.46  4811.4  455.04  4819.8  454.04  4873.1  452.42  4913.5  452.05
  4929.5  452.34  4936.1  453.22  4945.8  450.68  4951.5  450.75  4958.8  445.27
  4967.7  442.17  4973.4  441.01  4978.9  441.02  4989.7  440.99  4995.3  439.07
  5009.6  438.23  5009.9  437.73  5013.6  438.23  5026.9  444.42  5033.5  450.13
  5039.2  453.74  5055.5  456.89  5061.2  456.61  5070.2  457.66  5107.5  459.07
  5134.9  459.01  5205.1  459.06  5267.8  462.68  5320.3  467.08  5337.1  467.64
#Mann=6,-1,0
  4735.1    0.05       0  4873.1    0.16       0  4978.9    0.05       0
  5009.6    0.03       0  5013.6    0.05       0  5134.9    0.16       0
Bank Sta=5009.6,5013.6
Exp/Cntr=0.3,0.1

Type RM Length L Ch R = 1,6176,261,261,261
BEGIN DESCRIPTION:
NORTH MINERAL CR TRIB 8 6 13 0
END DESCRIPTION:
XS GIS Cut Line= 4
      3492640.63     10398407.94      3493022.61     10398157.91
      3493086.85     10398029.44      3492965.31     10397729.07
#Sta/Elev= 30
  4474.1  458.43  4536.4  456.00  4696.3  452.74  4711.4  451.63  4732.5  451.66
  4798.6  449.58  4825.9  449.55  4877.2  448.03  4892.3  447.85  4898.3  448.42
  4913.4  447.70  4919.4  448.22  4936.4  448.30  4948.8  447.50  4958.7  447.63
  4964.3  444.19  4981.1  440.82  4991.5  436.68  4991.8  436.18  4995.3  436.18
  4995.5  436.68  5003.4  436.85  5025.8  443.73  5038.3  448.14  5048.2  448.79
  5053.8  448.64  5147.4  451.85  5222.9  455.94  5330.8  458.39  5398.3  461.60
#Mann=3,-1,0
  4474.1    0.16       0  4991.5    0.07       0  4995.5    0.16       0
Bank Sta=4991.5,4995.5
Exp/Cntr=0.3,0.1

Type RM Length L Ch R = 1,5915,885,885,885
BEGIN DESCRIPTION:
NORTH MINERAL CR TRIB 8 6 12 0
END DESCRIPTION:
XS GIS Cut Line= 3
      3493159.77     10398597.14      3493284.77     10398102.36
      3493178.86     10397708.26
#Sta/Elev= 30
  4633.2  454.26  4803.9  451.72  4896.7  448.40  4910.2  447.52  4958.6  446.18
  4968.9  444.34  4979.2  441.04  4987.1  437.35  4992.2  436.91  4997.9  435.47
  4998.1  434.97  5001.6  434.97  5001.9  435.47  5010.2  437.13  5020.5  438.24
  5051.4  439.15  5061.7  440.52  5069.2  444.51  5074.3  443.60  5082.4  445.73
  5092.7  446.54  5171.6  447.76  5216.8  447.87  5286.3  449.85  5372.1  451.35
  5406.3  452.93  5465.3  454.78  5506.7  455.41  5527.4  456.45  5551.6  456.43
#Mann=3,-1,0
  4633.2    0.16       0  4997.9    0.07       0  5001.9    0.16       0
Bank Sta=4997.9,5001.9
Exp/Cntr=0.3,0.1

Type RM Length L Ch R = 1,5030,311,311,311
BEGIN DESCRIPTION:
NORTH MINERAL CR TRIB 8 6 29 0
END DESCRIPTION:
XS GIS Cut Line= 3
      3493931.03     10398305.90      3493903.69     10397945.24
      3493576.32     10397815.33
#Sta/Elev= 30
  4732.9  449.78  4807.4  447.51  4907.7  443.27  4927.7  443.08  4937.7  442.36
  4947.8  440.97  4967.8  434.05  4977.9  433.05  4997.9  433.04  5005.9  431.57
  5006.2  431.07  5009.7  431.07  5009.9  431.57  5018.0  431.78  5028.0  437.25
  5038.0  440.71  5078.1  441.42  5093.9  441.07  5107.1  441.21  5115.2  441.65
  5150.2  442.13  5169.2  443.01  5182.4  443.19  5204.3  443.03  5228.6  443.30
  5246.9  443.96  5306.9  444.47  5312.3  444.16  5343.7  445.52  5446.8  447.53
#Mann=3,-1,0
  4732.9    0.16       0  5005.9    0.07       0  5009.9    0.16       0
Bank Sta=5005.9,5009.9
Exp/Cntr=0.3,0.1

Type RM Length L Ch R = 1,4719,452,452,452
BEGIN DESCRIPTION:
NORTH MINERAL CR TRIB 8 6 19 0
END DESCRIPTION:
XS GIS Cut Line= 3
      3494147.18     10398259.00      3494140.67     10397921.80
      3493907.59     10397501.23
#Sta/Elev= 30
  4744.6  450.71  4762.0  449.39  4832.0  446.70  4852.0  445.20  4882.0  444.26
  4932.0  441.35  4942.0  440.42  4962.0  434.34  4972.0  432.04  4982.0  431.16
  4989.9  429.29  4990.2  428.79  4993.9  428.79  4994.1  429.29  5002.0  429.49
  5012.0  430.53  5022.0  430.31  5032.0  430.98  5042.0  429.65  5052.0  430.62
  5062.0  439.02  5072.0  440.13  5162.1  440.17  5229.3  443.22  5332.3  448.92
  5397.6  451.00  5441.1  451.76  5500.6  454.03  5506.3  453.67  5562.7  454.39
#Mann=3,-1,0
  4744.6    0.16       0  4989.9    0.07       0  4994.1    0.16       0
Bank Sta=4989.9,4994.1
Exp/Cntr=0.3,0.1

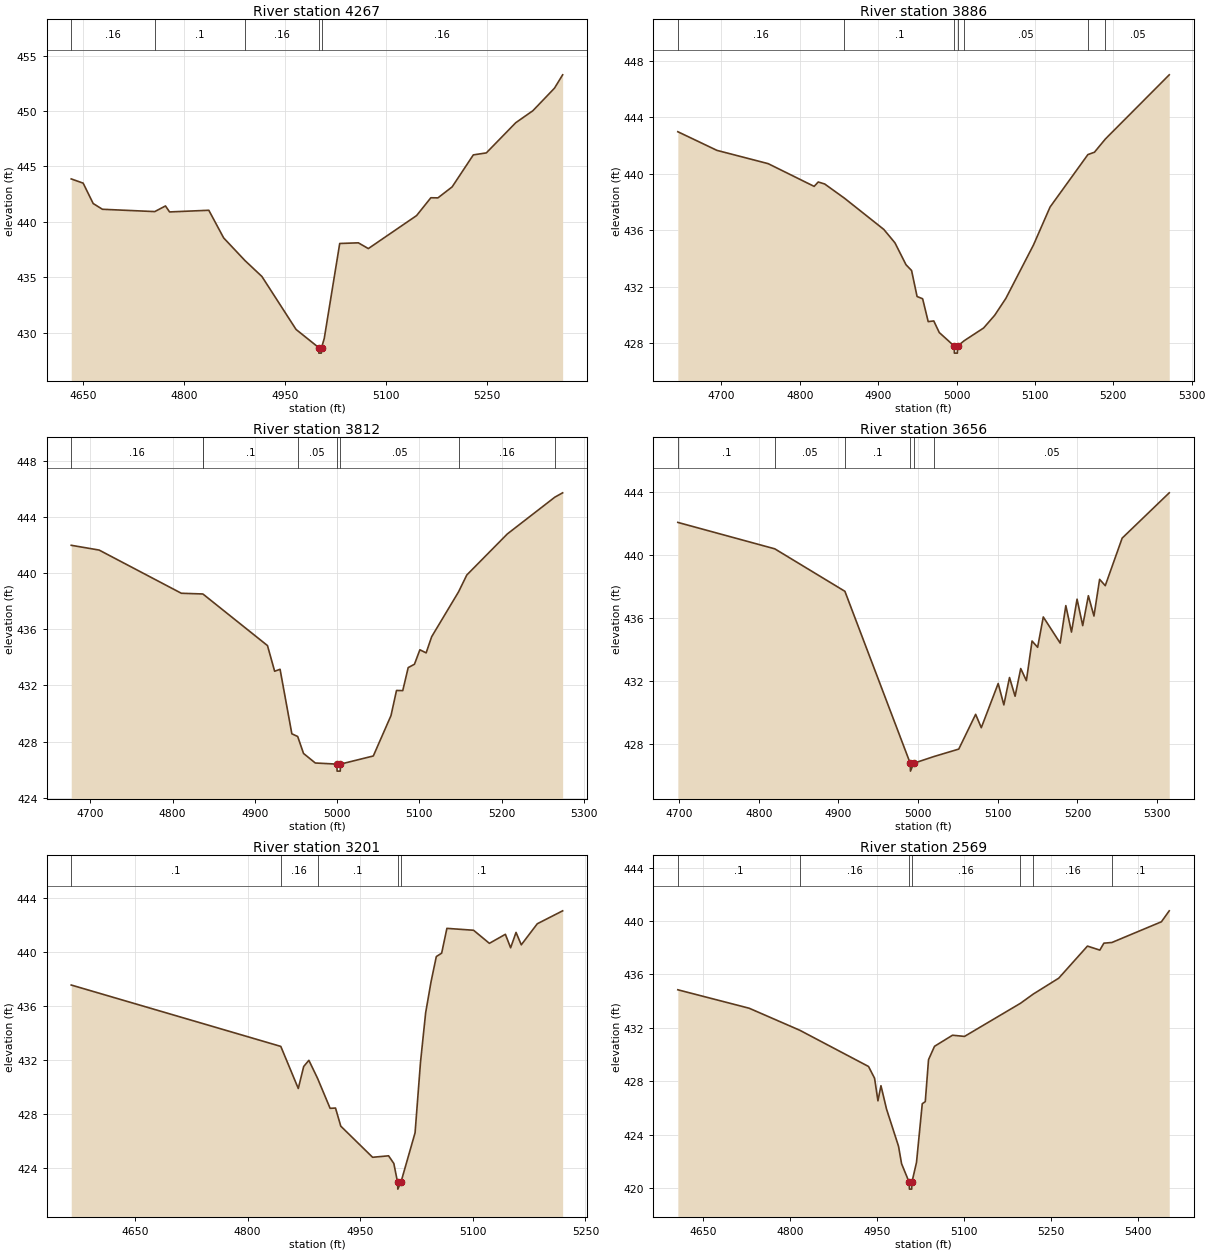
Type RM Length L Ch R = 1,4267,381,381,381
BEGIN DESCRIPTION:
NORTH MINERAL CR TRIB 8 6 7 1
END DESCRIPTION:
XS GIS Cut Line= 3
      3494660.18     10398007.72      3494225.30     10397706.96
      3494163.19     10397515.43
#Sta/Elev= 30
  4632.6  443.87  4650.3  443.49  4665.2  441.65  4678.9  441.13  4756.7  440.92
  4772.6  441.43  4778.7  440.89  4837.0  441.04  4859.1  438.54  4890.7  436.50
  4915.9  435.06  4966.6  430.28  5000.3  428.64  5000.5  428.14  5004.2  428.14
  5004.5  428.64  5008.5  429.46  5031.5  438.04  5059.2  438.10  5074.0  437.58
  5145.7  440.56  5166.9  442.17  5177.4  442.16  5198.5  443.15  5230.0  446.04
  5249.3  446.22  5293.1  448.95  5318.5  450.03  5350.5  452.06  5362.7  453.27
#Mann=5,-1,0
  4632.6    0.16       0  4756.7     0.1       0  4890.7    0.16       0
  5000.3    0.07       0  5004.5    0.16       0
Bank Sta=5000.3,5004.5
Exp/Cntr=0.3,0.1

Type RM Length L Ch R = 1,3886,74,74,74
BEGIN DESCRIPTION:
NORTH MINERAL CR TRIB 8 6 9 0
END DESCRIPTION:
XS GIS Cut Line= 3
      3494769.57     10397963.44      3494707.07     10397712.17
      3494446.88     10397451.97
#Sta/Elev= 30
  4644.5  442.98  4694.4  441.66  4759.7  440.72  4818.4  439.11  4823.6  439.42
  4831.8  439.28  4856.9  438.28  4907.3  436.06  4921.5  435.11  4935.6  433.56
  4942.7  433.15  4949.7  431.31  4956.8  431.15  4963.9  429.53  4971.0  429.58
  4978.0  428.76  4997.1  427.80  4997.3  427.30  5001.1  427.30  5001.4  427.80
  5010.1  428.19  5034.6  429.08  5048.7  429.98  5062.9  431.17  5098.2  434.96
  5119.4  437.65  5167.6  441.36  5176.0  441.53  5190.0  442.47  5271.4  447.01
#Mann=7,-1,0
  4644.5    0.16       0  4856.9     0.1       0  4997.1    0.07       0
  5001.4     0.1       0  5010.1    0.05       0  5167.6    0.16       0
  5190.0    0.05       0
Bank Sta=4997.1,5001.4
Exp/Cntr=0.3,0.1

Type RM Length L Ch R = 1,3812,156,156,156
BEGIN DESCRIPTION:
NORTH MINERAL CR TRIB 8 6 7 0
END DESCRIPTION:
XS GIS Cut Line= 3
      3494850.30     10397887.95      3494756.55     10397667.89
      3494520.90     10397398.39
#Sta/Elev= 30
  4676.9  441.99  4710.8  441.65  4810.7  438.57  4836.5  438.52  4837.3  438.50
  4915.4  434.84  4924.1  433.01  4930.7  433.15  4945.0  428.55  4952.1  428.36
  4959.2  427.15  4973.5  426.47  4999.7  426.39  5000.0  425.89  5003.8  425.89
  5004.1  426.39  5044.0  426.97  5065.5  429.85  5072.2  431.64  5079.8  431.63
  5086.4  433.27  5094.0  433.51  5100.6  434.54  5108.2  434.32  5114.9  435.47
  5147.6  438.67  5157.6  439.87  5206.9  442.80  5264.6  445.42  5274.1  445.73
#Mann=8,-1,0
  4676.9    0.16       0  4836.5    0.05       0  4837.3     0.1       0
  4952.1    0.05       0  4999.7    0.03       0  5004.1    0.05       0
  5147.6    0.16       0  5264.6    0.05       0
Bank Sta=4999.7,5004.1
Exp/Cntr=0.3,0.1

Type RM Length L Ch R = 1,3656,455,455,455
BEGIN DESCRIPTION:
NORTH MINERAL CR TRIB 8 6 8 0
END DESCRIPTION:
XS GIS Cut Line= 3
      3494983.57     10397834.54      3494833.56     10397534.52
      3494634.60     10397335.56
#Sta/Elev= 30
  4698.4  442.07  4820.1  440.39  4908.1  437.69  4990.1  426.76  4990.4  426.26
  4994.5  426.76  5020.0  427.19  5051.0  427.66  5072.2  429.87  5079.3  429.02
  5100.5  431.83  5107.6  430.47  5114.7  432.21  5121.7  431.02  5128.8  432.78
  5135.9  432.01  5143.0  434.53  5150.0  434.13  5157.1  436.06  5178.3  434.40
  5185.4  436.78  5192.5  435.10  5199.5  437.19  5206.6  435.51  5213.7  437.41
  5220.7  436.12  5227.8  438.45  5234.9  438.05  5256.1  441.07  5315.2  443.95
#Mann=6,-1,0
  4698.4     0.1       0  4820.1    0.05       0  4908.1     0.1       0
  4990.1    0.07       0  4994.5     0.1       0  5020.0    0.05       0
Bank Sta=4990.1,4994.5
Exp/Cntr=0.3,0.1

Type RM Length L Ch R = 1,3201,632,632,632
BEGIN DESCRIPTION:
NORTH MINERAL CR TRIB 8 6 6 0
END DESCRIPTION:
XS GIS Cut Line= 2
      3495287.79     10397503.82      3494819.02     10397046.77
#Sta/Elev= 30
  4565.0  437.55  4844.2  433.00  4867.5  429.88  4874.7  431.51  4881.6  431.97
  4893.2  430.63  4909.9  428.41  4917.1  428.43  4924.1  427.09  4966.5  424.78
  4987.8  424.89  4994.8  424.32  4999.8  422.92  5000.1  422.42  5004.2  422.92
  5023.1  426.60  5030.3  431.81  5037.2  435.50  5044.4  437.80  5051.4  439.66
  5058.5  439.91  5065.5  441.75  5101.0  441.61  5122.1  440.64  5143.4  441.31
  5150.4  440.31  5157.6  441.45  5164.6  440.53  5185.9  442.09  5219.7  443.05
#Mann=5,-1,0
  4565.0     0.1       0  4844.2    0.16       0  4893.2     0.1       0
  4999.8    0.07       0  5004.2     0.1       0
Bank Sta=4999.8,5004.2
Exp/Cntr=0.3,0.1

Type RM Length L Ch R = 1,2569,227,227,227
BEGIN DESCRIPTION:
NORTH MINERAL CR TRIB 8 6 6 1
END DESCRIPTION:
XS GIS Cut Line= 4
      3495429.74     10397331.94      3495471.40     10397128.83
      3495398.48     10396844.98      3495156.06     10396598.67
#Sta/Elev= 30
  4607.2  434.85  4730.0  433.47  4817.2  431.82  4935.5  429.11  4945.9  428.23
  4951.7  426.54  4956.9  427.67  4966.5  425.92  4987.2  423.13  4992.4  421.83
  5005.6  420.43  5005.9  419.93  5009.8  419.93  5010.1  420.43  5018.1  421.93
  5028.0  426.32  5033.2  426.48  5038.8  429.62  5049.1  430.62  5080.1  431.45
  5100.7  431.36  5197.1  433.84  5219.1  434.53  5263.0  435.72  5312.4  438.12
  5333.7  437.82  5340.7  438.34  5354.5  438.39  5439.7  439.94  5453.2  440.76
#Mann=7,-1,0
  4607.2     0.1       0  4817.2    0.16       0  5005.6    0.07       0
  5010.1    0.16       0  5197.1     0.1       0  5219.1    0.16       0
  5354.5     0.1       0
Bank Sta=5005.6,5010.1
Exp/Cntr=0.3,0.1

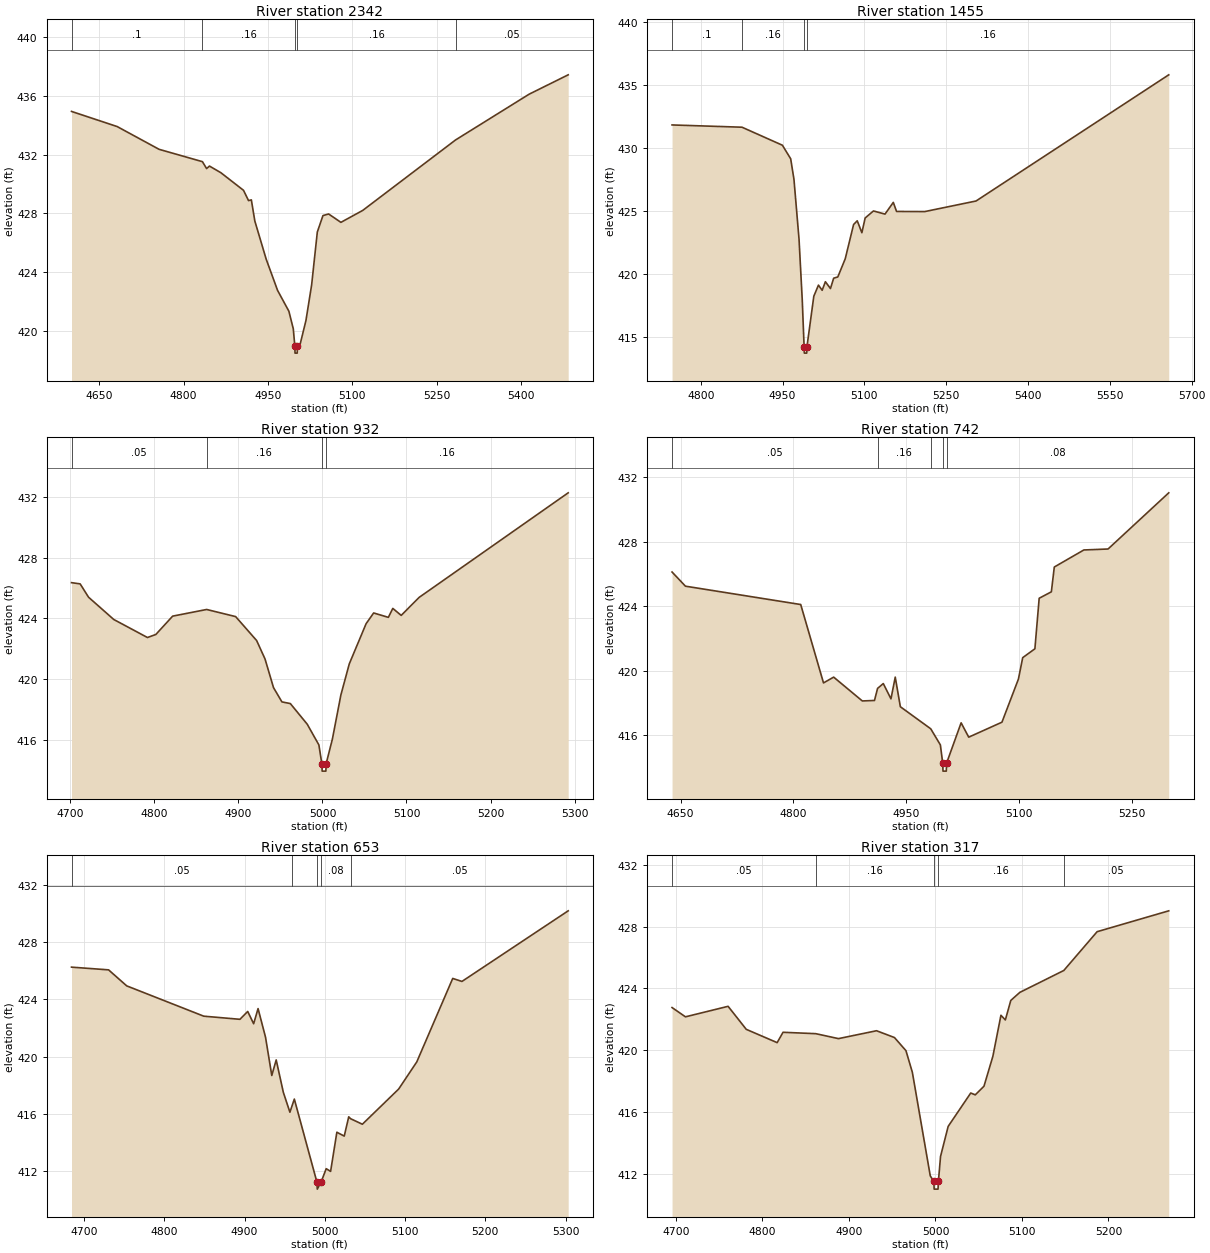
Type RM Length L Ch R = 1,2342,887,887,887
BEGIN DESCRIPTION:
NORTH MINERAL CR TRIB 8 6 3 20
END DESCRIPTION:
XS GIS Cut Line= 4
      3495777.38     10397287.67      3495670.62     10397104.09
      3495623.74     10396739.51      3495409.23     10396526.30
#Sta/Elev= 30
  4601.0  434.94  4682.1  433.91  4756.6  432.36  4833.6  431.52  4841.0  431.05
  4846.1  431.22  4866.3  430.77  4906.6  429.57  4915.5  428.87  4920.5  428.92
  4926.7  427.48  4946.9  424.88  4967.1  422.76  4987.2  421.34  4995.0  420.15
  4997.7  418.99  4998.1  418.49  5002.0  418.49  5002.3  418.99  5007.4  419.13
  5017.5  420.71  5027.6  423.13  5037.7  426.73  5047.7  427.85  5057.8  427.96
  5079.6  427.39  5118.3  428.20  5283.4  433.00  5413.9  436.11  5483.4  437.43
#Mann=5,-1,0
  4601.0     0.1       0  4833.6    0.16       0  4997.7    0.07       0
  5002.3    0.16       0  5283.4    0.05       0
Bank Sta=4997.7,5002.3
Exp/Cntr=0.3,0.1

Type RM Length L Ch R = 1,1455,523,523,523
BEGIN DESCRIPTION:
NORTH MINERAL CR TRIB 8 6 2 11
END DESCRIPTION:
XS GIS Cut Line= 3
      3495879.32     10397078.34      3496199.65     10396573.10
      3496226.99     10396261.92
#Sta/Elev= 30
  4747.4  431.81  4875.6  431.63  4949.7  430.20  4964.9  429.12  4970.9  427.49
  4980.2  422.73  4986.1  417.91  4989.5  414.19  4989.9  413.69  4994.3  413.69
  4994.7  414.19  5007.3  418.21  5015.8  419.09  5022.6  418.68  5028.5  419.36
  5037.8  418.82  5043.7  419.64  5051.3  419.74  5064.9  421.18  5080.2  423.90
  5086.9  424.20  5095.4  423.25  5101.4  424.42  5116.6  424.98  5137.8  424.73
  5153.0  425.66  5159.0  424.94  5210.7  424.93  5304.7  425.77  5658.0  435.79
#Mann=4,-1,0
  4747.4     0.1       0  4875.6    0.16       0  4989.5    0.07       0
  4994.7    0.16       0
Bank Sta=4989.5,4994.7
Exp/Cntr=0.3,0.1

Type RM Length L Ch R = 1,932,190,190,190
BEGIN DESCRIPTION:
NORTH MINERAL CR TRIB 8 6 2 21
END DESCRIPTION:
XS GIS Cut Line= 4
      3496341.58     10396981.99      3496340.28     10396786.64
      3496352.00     10396618.68      3496273.08     10396405.22
#Sta/Elev= 30
  4701.2  426.36  4711.5  426.28  4721.5  425.40  4751.5  423.93  4791.6  422.74
  4801.6  422.94  4821.6  424.15  4862.1  424.59  4896.6  424.12  4921.6  422.54
  4931.6  421.32  4941.7  419.43  4951.7  418.49  4961.7  418.38  4981.8  417.02
  4995.7  415.65  4999.2  414.42  4999.6  413.92  5004.0  413.92  5004.4  414.42
  5011.8  416.04  5021.9  418.95  5031.9  421.00  5051.9  423.65  5060.9  424.36
  5078.4  424.07  5083.7  424.66  5093.7  424.20  5115.1  425.39  5292.5  432.29
#Mann=4,-1,0
  4701.2    0.05       0  4862.1    0.16       0  4999.2    0.07       0
  5004.4    0.16       0
Bank Sta=4999.2,5004.4
Exp/Cntr=0.3,0.1

Type RM Length L Ch R = 1,742,89,89,89
BEGIN DESCRIPTION:
NORTH MINERAL CR TRIB 8 6 2 4
END DESCRIPTION:
XS GIS Cut Line= 3
      3496346.81     10396968.90      3496588.98     10396519.72
      3496618.93     10396372.54
#Sta/Elev= 30
  4638.7  426.12  4656.5  425.24  4809.8  424.10  4840.1  419.23  4853.6  419.59
  4891.7  418.11  4907.9  418.14  4912.0  418.89  4919.6  419.19  4929.8  418.24
  4935.5  419.59  4942.3  417.75  4982.7  416.38  4995.5  415.38  4998.6  414.25
  4999.0  413.75  5003.4  413.75  5003.8  414.25  5023.1  416.75  5033.2  415.86
  5077.4  416.79  5099.3  419.47  5105.0  420.80  5121.2  421.35  5126.9  424.49
  5143.1  424.89  5147.0  426.43  5186.3  427.49  5218.5  427.55  5299.2  431.04
#Mann=5,-1,0
  4638.7    0.05       0  4912.0    0.16       0  4982.7    0.08       0
  4998.6    0.07       0  5003.8    0.08       0
Bank Sta=4998.6,5003.8
Exp/Cntr=0.3,0.1

Type RM Length L Ch R = 1,653,336,336,336
BEGIN DESCRIPTION:
NORTH MINERAL CR TRIB 8 6 1 21
END DESCRIPTION:
XS GIS Cut Line= 2
      3496457.48     10396979.33      3496726.99     10396422.08
#Sta/Elev= 30
  4684.3  426.26  4730.5  426.07  4753.1  424.95  4849.1  422.83  4894.2  422.61
  4903.9  423.16  4911.3  422.30  4916.8  423.36  4926.1  421.36  4933.9  418.68
  4939.4  419.77  4948.3  417.50  4956.5  416.11  4958.7  416.48  4962.0  417.03
  4990.1  411.23  4990.6  410.73  4995.4  411.23  5001.7  412.16  5007.2  411.97
  5015.0  414.71  5024.2  414.44  5029.8  415.79  5032.0  415.66  5046.8  415.27
  5092.0  417.73  5114.6  419.63  5159.4  425.47  5170.9  425.26  5303.3  430.20
#Mann=5,-1,0
  4684.3    0.05       0  4958.7    0.08       0  4990.1    0.07       0
  4995.4    0.08       0  5032.0    0.05       0
Bank Sta=4990.1,4995.4
Exp/Cntr=0.3,0.1

Type RM Length L Ch R = 1,317,197,197,197
BEGIN DESCRIPTION:
NORTH MINERAL CR TRIB 8 64 0
END DESCRIPTION:
XS GIS Cut Line= 4
      3496680.10     10396901.25      3496831.16     10396760.60
      3496891.06     10396536.64      3496856.26     10396405.20
#Sta/Elev= 30
  4695.5  422.76  4711.0  422.16  4760.3  422.84  4781.3  421.35  4817.0  420.49
  4823.8  421.16  4861.6  421.07  4887.9  420.75  4931.9  421.26  4952.6  420.82
  4965.9  419.97  4973.3  418.57  4994.0  411.87  4998.1  411.51  4998.5  411.01
  5003.0  411.01  5003.4  411.51  5005.9  413.13  5014.7  415.07  5040.8  417.23
  5046.0  417.11  5056.1  417.67  5066.4  419.61  5075.7  422.26  5080.8  421.96
  5087.1  423.22  5097.5  423.74  5148.4  425.16  5186.9  427.67  5269.7  429.02
#Mann=5,-1,0
  4695.5    0.05       0  4861.6    0.16       0  4998.1    0.07       0
  5003.4    0.16       0  5148.4    0.05       0
Bank Sta=4998.1,5003.4
Exp/Cntr=0.3,0.1

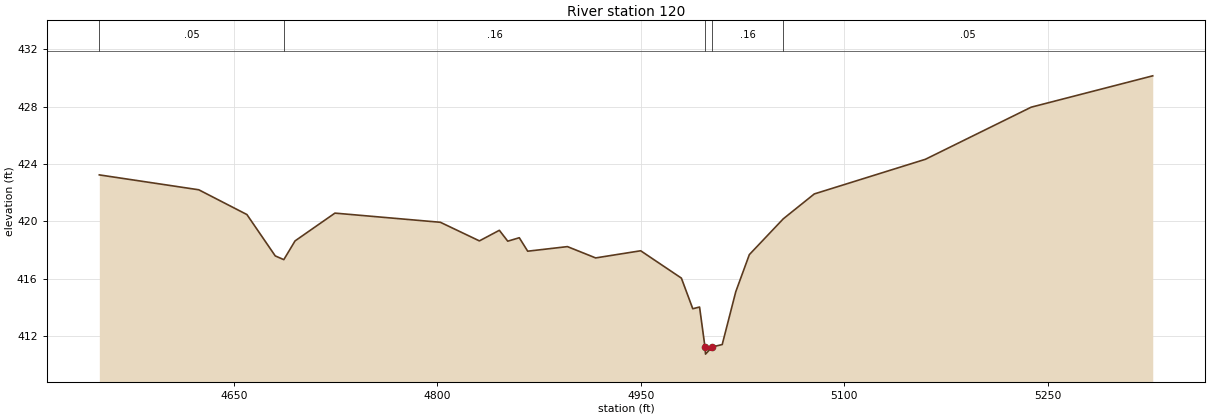
Type RM Length L Ch R = 1,120,0,0,0
BEGIN DESCRIPTION:
NORTH MINERAL CR TRIB 8 61 0
END DESCRIPTION:
XS GIS Cut Line= 4
      3496719.15     10396920.78      3497034.29     10396690.29
      3497042.10     10396550.97      3496904.10     10396346.57
#Sta/Elev= 30
  4550.9  423.24  4624.2  422.20  4659.7  420.47  4680.6  417.58  4686.9  417.32
  4695.2  418.63  4724.6  420.57  4802.3  419.93  4831.1  418.63  4845.8  419.37
  4852.0  418.61  4860.5  418.85  4866.7  417.91  4896.0  418.23  4916.8  417.44
  4950.0  417.94  4980.0  416.03  4988.4  413.89  4993.4  414.01  4997.4  411.22
  4997.8  410.72  5002.7  411.22  5010.1  411.39  5020.1  415.08  5030.1  417.67
  5055.1  420.17  5078.0  421.91  5159.9  424.33  5237.9  427.97  5327.5  430.16
#Mann=5,-1,0
  4550.9    0.05       0  4686.9    0.16       0  4997.4    0.07       0
  5002.7    0.16       0  5055.1    0.05       0
Bank Sta=4997.4,5002.7
Exp/Cntr=0.3,0.1

Chan Stop Cuts=-1