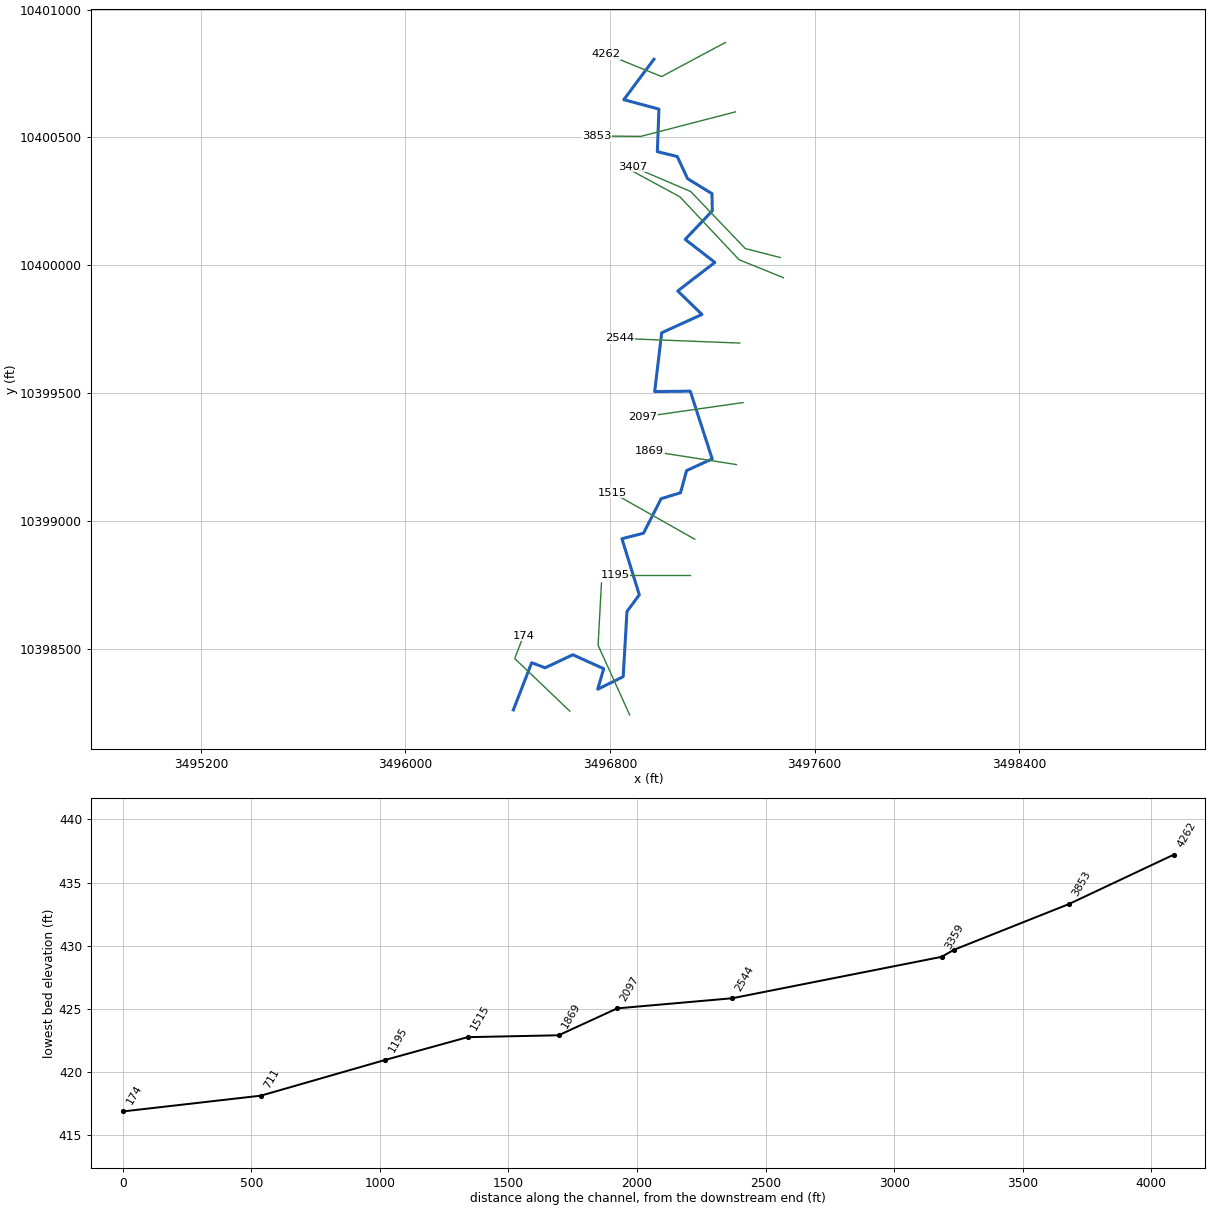
--- NORTH MINERAL CR TRIB 8 7.prj (project) ---

Proj Title=NORTH MINERAL CR TRIB 8 7 Base Level Engineering
Current Plan=p01
Default Exp/Contr=0.3,0.1
English Units
Geom File=g01
Flow File=f01
Plan File=p01
BEGIN DESCRIPTION:
NORTH MINERAL CR TRIB 8 7
END DESCRIPTION:

--- NORTH MINERAL CR TRIB 8 7.p01 (plan) ---

Plan Title=Multiple Run
Short Identifier=Multiple
Geom File=g01
Flow File=f01
Subcritical Flow
K Sum by GR= 0
Std Step Tol= 0.01
Critical Tol= 0.01
Num of Std Step Trials= 20
Max Error Tol= 0.3
Flow Tol Ratio= 0.001
Split Flow NTrial= 30
Split Flow Tol= 0.02
Split Flow Ratio= 0.02
Log Output Level= 0
Friction Slope Method= 1
Unsteady Friction Slope Method= 2
Unsteady Bridges Friction Slope Method= 1
Parabolic Critical Depth
Global Vel Dist=  1 , 1 , 1
Global Log Level= 0
CheckData=True
Encroach Param= -1, 0, 0, 0
BEGIN DESCRIPTION:
Multiple Run
END DESCRIPTION:

--- NORTH MINERAL CR TRIB 8 7.f01 (steady flow) ---

Flow Title=Multiple
Number of Profiles=7
Profile Names=10-year,25-year,50-year,1pct_min,100-year,1pct_plu,500-year
River Rch & RM= NORTH MINERAL CR,Reach-1,4262
     458     606     722     630     852    1153    1183
Boundary for River Rch & Prof#=NORTH MINERAL CR,Reach-1,1
Up Type=0
Dn Type=3
Dn Slope=0.005
Boundary for River Rch & Prof#=NORTH MINERAL CR,Reach-1,2
Up Type=0
Dn Type=3
Dn Slope=0.005
Boundary for River Rch & Prof#=NORTH MINERAL CR,Reach-1,3
Up Type=0
Dn Type=3
Dn Slope=0.005
Boundary for River Rch & Prof#=NORTH MINERAL CR,Reach-1,4
Up Type=0
Dn Type=3
Dn Slope=0.005
Boundary for River Rch & Prof#=NORTH MINERAL CR,Reach-1,5
Up Type=0
Dn Type=3
Dn Slope=0.005
Boundary for River Rch & Prof#=NORTH MINERAL CR,Reach-1,6
Up Type=0
Dn Type=3
Dn Slope=0.005
Boundary for River Rch & Prof#=NORTH MINERAL CR,Reach-1,7
Up Type=0
Dn Type=3
Dn Slope=0.005

--- NORTH MINERAL CR TRIB 8 7.g01 (geometry) ---

Geom Title=Existing Conditions

River Reach=NORTH MINERAL CR,Reach-1
Reach XY= 30
      3496971.88     10400805.85      3496854.03     10400647.75
      3496991.44     10400610.86      3496985.19     10400444.56
      3497063.03     10400425.48      3497103.35     10400338.97
      3497198.97     10400280.10      3497200.08     10400212.76
      3497094.00     10400101.55      3497210.12     10400011.51
      3497065.05     10399899.87      3497159.66     10399807.92
      3497002.23     10399736.39      3496974.75     10399506.53
      3497114.00     10399508.07      3497199.65     10399243.18
      3497099.73     10399197.63      3497075.77     10399110.74
      3497000.03     10399087.60      3496930.95     10398952.62
      3496846.73     10398931.01      3496914.70     10398711.63
      3496866.41     10398646.62      3496851.57     10398391.59
      3496752.03     10398342.60      3496775.41     10398422.81
      3496654.83     10398477.43      3496546.33     10398426.40
      3496493.68     10398446.22      3496422.11     10398261.64

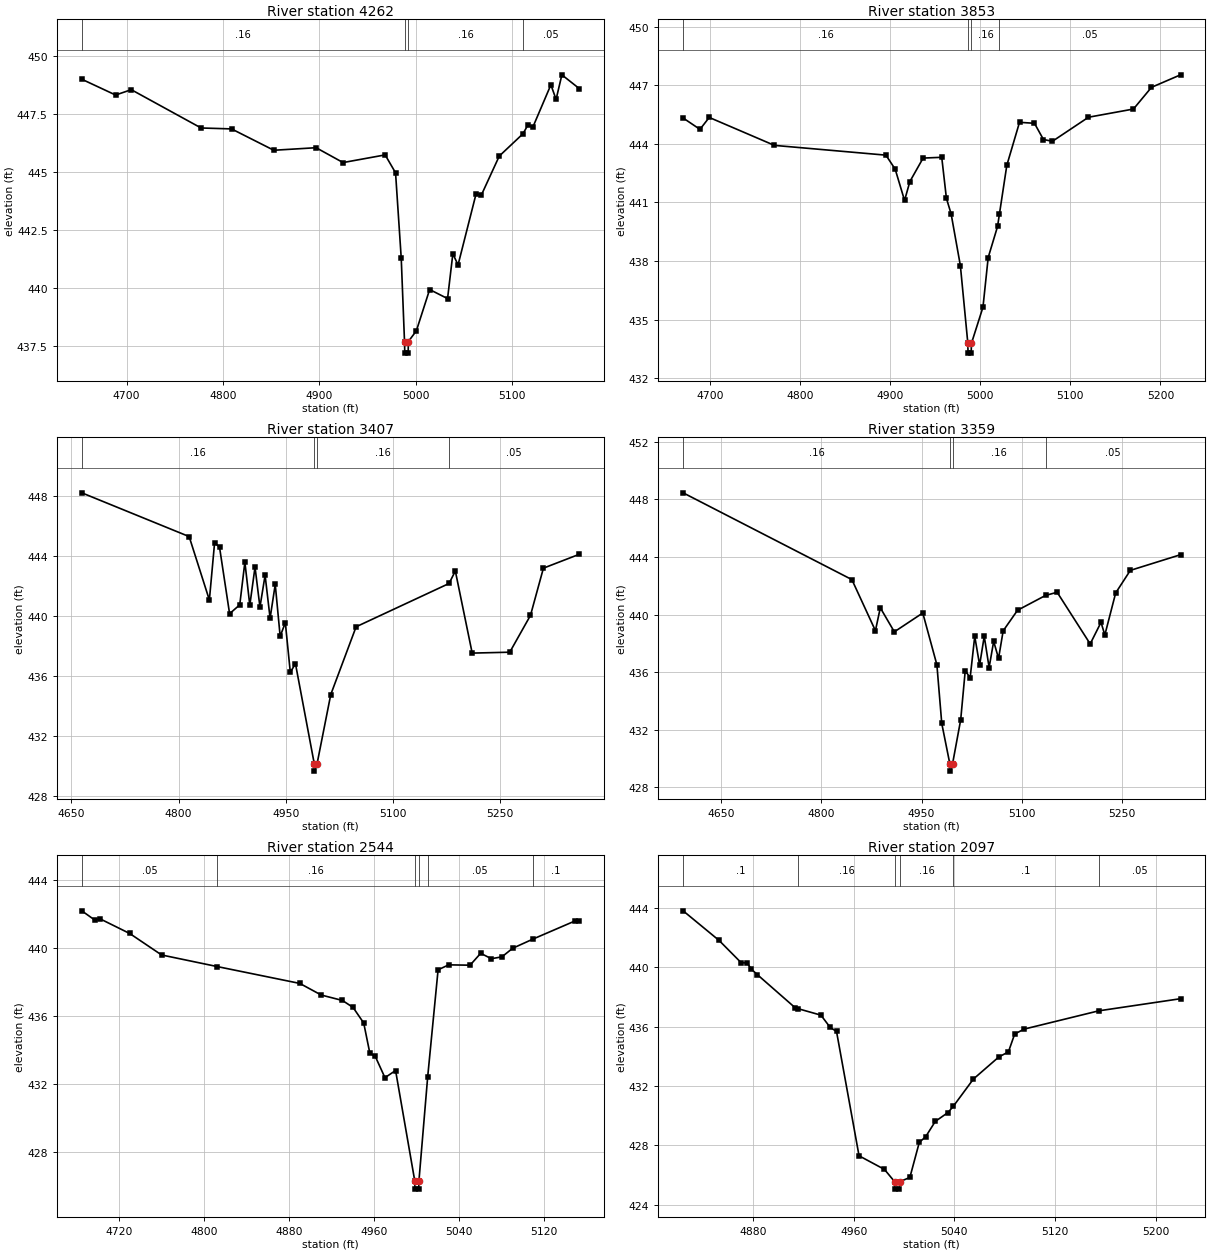
Type RM Length L Ch R = 1,4262,409,409,409
BEGIN DESCRIPTION:
NORTH MINERAL CR TRIB 8 7 10 0
END DESCRIPTION:
XS GIS Cut Line= 3
      3497251.43     10400871.40      3497001.84     10400738.12
      3496785.41     10400825.89
#Sta/Elev= 30
  4653.4  449.01  4688.5  448.33  4704.8  448.56  4777.3  446.91  4808.9  446.87
  4852.8  445.95  4896.7  446.06  4924.7  445.42  4968.4  445.75  4979.2  444.98
  4985.1  441.30  4988.5  437.71  4988.8  437.21  4992.3  437.21  4992.5  437.71
  5000.8  438.17  5014.6  439.95  5033.2  439.56  5038.7  441.49  5044.1  441.01
  5062.8  444.07  5068.2  444.01  5086.9  445.70  5111.5  446.66  5116.4  447.02
  5121.8  446.95  5140.5  448.77  5145.9  448.14  5151.9  449.20  5169.9  448.61
#Mann=4,-1,0
  4653.4    0.16       0  4988.5    0.07       0  4992.5    0.16       0
  5111.5    0.05       0
Bank Sta=4988.5,4992.5
Exp/Cntr=0.3,0.1

Type RM Length L Ch R = 1,3853,446,446,446
BEGIN DESCRIPTION:
NORTH MINERAL CR TRIB 8 7 9 0
END DESCRIPTION:
XS GIS Cut Line= 3
      3497290.22     10400599.99      3496920.66     10400504.27
      3496749.82     10400505.48
#Sta/Elev= 30
  4669.8  445.32  4688.5  444.74  4698.8  445.35  4771.2  443.92  4895.1  443.42
  4905.4  442.70  4915.8  441.10  4921.7  442.07  4936.4  443.27  4957.1  443.31
  4962.3  441.21  4967.5  440.42  4977.8  437.77  4986.1  433.79  4986.3  433.29
  4989.8  433.29  4990.1  433.79  5002.9  435.64  5008.7  438.18  5019.1  439.77
  5021.2  440.41  5029.4  442.90  5043.5  445.10  5060.1  445.05  5070.1  444.22
  5080.1  444.13  5120.1  445.36  5170.1  445.78  5190.1  446.89  5222.4  447.53
#Mann=4,-1,0
  4669.8    0.16       0  4986.1    0.07       0  4990.1    0.16       0
  5021.2    0.05       0
Bank Sta=4986.1,4990.1
Exp/Cntr=0.3,0.1

Type RM Length L Ch R = 1,3407,48,48,48
BEGIN DESCRIPTION:
NORTH MINERAL CR TRIB 8 7 8 0
END DESCRIPTION:
XS GIS Cut Line= 4
      3497465.91     10400030.50      3497328.99     10400065.64
      3497115.73     10400288.59      3496889.17     10400385.51
#Sta/Elev= 30
  4664.5  448.19  4814.8  445.28  4843.1  441.06  4850.4  444.87  4857.3  444.58
  4871.4  440.15  4885.6  440.74  4892.8  443.58  4899.7  440.71  4907.0  443.25
  4913.9  440.59  4921.1  442.71  4928.1  439.85  4935.3  442.10  4942.2  438.64
  4949.4  439.56  4956.4  436.25  4963.6  436.83  4989.9  430.18  4990.1  429.68
  4993.9  430.18  5013.0  434.77  5048.5  439.28  5178.6  442.16  5187.4  442.99
  5211.0  437.53  5263.6  437.59  5292.6  440.04  5310.7  443.18  5360.8  444.10
#Mann=4,-1,0
  4664.5    0.16       0  4989.9    0.07       0  4993.9    0.16       0
  5178.6    0.05       0
Bank Sta=4989.9,4993.9
Exp/Cntr=0.3,0.1

Type RM Length L Ch R = 1,3359,815,815,815
BEGIN DESCRIPTION:
Mapping XS 881db17c
END DESCRIPTION:
XS GIS Cut Line= 4
      3497477.98     10399951.76      3497304.75     10400022.02
      3497073.33     10400267.99      3496880.67     10400372.20
#Sta/Elev= 30
  4593.5  448.46  4845.8  442.43  4881.0  438.88  4888.3  440.47  4909.3  438.80
  4951.8  440.11  4972.9  436.51  4980.2  432.43  4992.3  429.62  4992.6  429.12
  4996.3  429.62  5008.5  432.69  5015.3  436.11  5022.6  435.60  5029.5  438.49
  5036.8  436.49  5043.7  438.49  5051.0  436.32  5057.8  438.14  5065.1  436.95
  5072.0  438.87  5093.5  440.30  5135.4  441.33  5152.7  441.55  5202.1  437.96
  5218.3  439.46  5224.0  438.58  5240.2  441.50  5262.1  443.07  5337.2  444.16
#Mann=4,-1,0
  4593.5    0.16       0  4992.3    0.07       0  4996.3    0.16       0
  5135.4    0.05       0
Bank Sta=4992.3,4996.3
Exp/Cntr=0.3,0.1

Type RM Length L Ch R = 1,2544,447,447,447
BEGIN DESCRIPTION:
NORTH MINERAL CR TRIB 8 7 7 0
END DESCRIPTION:
XS GIS Cut Line= 2
      3497307.19     10399696.09      3496839.45     10399714.26
#Sta/Elev= 30
  4685.0  442.17  4697.2  441.63  4702.2  441.70  4730.1  440.84  4760.1  439.58
  4812.4  438.90  4890.2  437.91  4910.3  437.23  4930.3  436.91  4940.3  436.50
  4950.3  435.59  4956.1  433.81  4961.1  433.64  4970.3  432.38  4980.3  432.80
  4998.3  426.34  4998.6  425.84  5002.1  425.84  5002.3  426.34  5010.5  432.42
  5020.3  438.71  5030.3  439.00  5050.4  438.98  5060.4  439.68  5070.4  439.36
  5080.4  439.47  5090.4  439.97  5109.5  440.51  5149.3  441.58  5153.1  441.58
#Mann=6,-1,0
  4685.0    0.05       0  4812.4    0.16       0  4998.3    0.07       0
  5002.3    0.16       0  5010.5    0.05       0  5109.5     0.1       0
Bank Sta=4998.3,5002.3
Exp/Cntr=0.3,0.1

Type RM Length L Ch R = 1,2097,228,228,228
BEGIN DESCRIPTION:
NORTH MINERAL CR TRIB 8 7 6 0
END DESCRIPTION:
XS GIS Cut Line= 2
      3497320.47     10399463.44      3496929.11     10399407.71
#Sta/Elev= 30
  4824.4  443.82  4853.0  441.82  4870.4  440.33  4875.5  440.29  4878.3  439.91
  4883.3  439.52  4913.7  437.26  4916.0  437.21  4933.9  436.78  4941.2  435.96
  4946.3  435.68  4964.2  427.29  4984.4  426.37  4992.5  425.54  4992.7  425.04
  4996.2  425.04  4996.5  425.54  5004.6  425.83  5012.1  428.20  5017.1  428.57
  5024.8  429.61  5034.9  430.21  5039.2  430.64  5055.1  432.47  5075.3  433.96
  5082.9  434.30  5087.9  435.51  5095.5  435.84  5154.6  437.07  5219.7  437.89
#Mann=6,-1,0
  4824.4     0.1       0  4916.0    0.16       0  4992.5    0.07       0
  4996.5    0.16       0  5039.2     0.1       0  5154.6    0.05       0
Bank Sta=4992.5,4996.5
Exp/Cntr=0.3,0.1

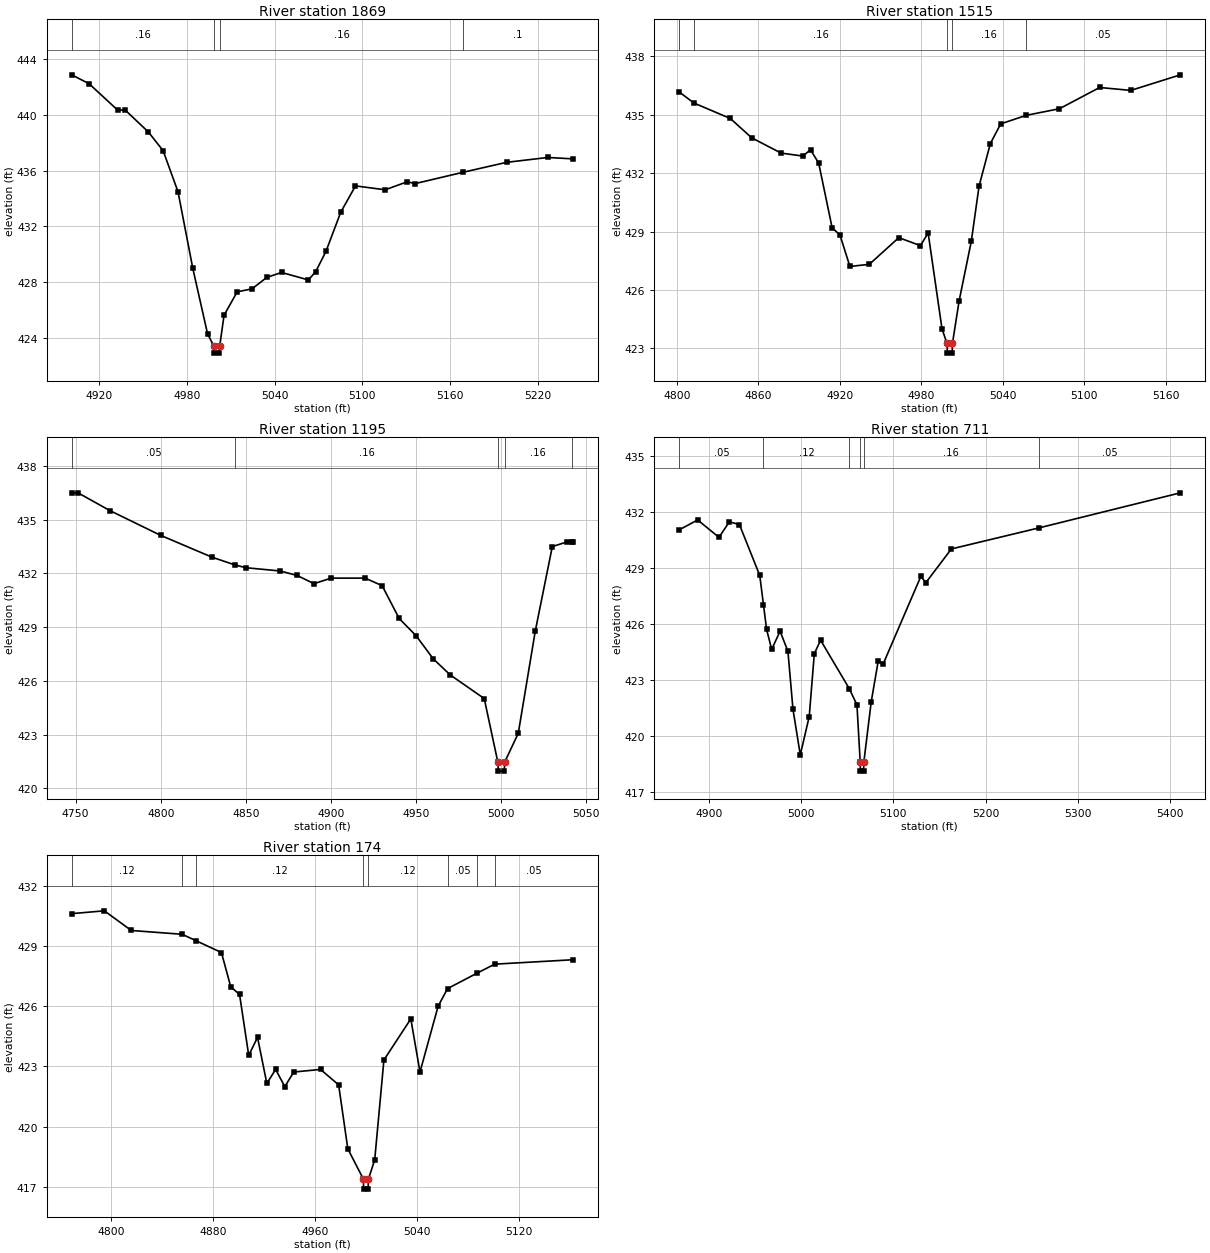
Type RM Length L Ch R = 1,1869,354,354,354
BEGIN DESCRIPTION:
Mapping XS 41564156
END DESCRIPTION:
XS GIS Cut Line= 2
      3497293.90     10399221.11      3496955.22     10399274.14
#Sta/Elev= 30
  4901.3  442.88  4913.2  442.24  4932.7  440.35  4937.8  440.36  4953.7  438.78
  4963.8  437.44  4974.0  434.49  4984.1  429.00  4994.2  424.30  4998.5  423.41
  4998.7  422.91  5002.2  422.91  5002.5  423.41  5005.5  425.63  5014.5  427.31
  5024.6  427.52  5034.7  428.34  5044.8  428.70  5063.2  428.16  5068.2  428.76
  5075.2  430.21  5085.3  433.02  5095.4  434.91  5115.7  434.63  5130.9  435.21
  5136.0  435.07  5169.1  435.89  5198.7  436.60  5227.0  436.95  5244.1  436.85
#Mann=4,-1,0
  4901.3    0.16       0  4998.5    0.07       0  5002.5    0.16       0
  5169.1     0.1       0
Bank Sta=4998.5,5002.5
Exp/Cntr=0.3,0.1

Type RM Length L Ch R = 1,1515,320,320,320
BEGIN DESCRIPTION:
NORTH MINERAL CR TRIB 8 7 5 0
END DESCRIPTION:
XS GIS Cut Line= 2
      3497131.50     10398929.10      3496810.38     10399110.87
#Sta/Elev= 30
  4801.7  436.17  4812.6  435.60  4839.3  434.81  4855.2  433.81  4876.8  433.03
  4892.7  432.88  4898.4  433.20  4904.4  432.52  4914.3  429.20  4920.1  428.82
  4927.4  427.21  4941.7  427.32  4963.4  428.69  4979.3  428.28  4985.0  428.93
  4995.2  424.01  4998.9  423.26  4999.2  422.76  5002.7  422.76  5002.9  423.26
  5007.8  425.44  5016.8  428.51  5022.5  431.34  5030.8  433.52  5038.4  434.53
  5057.2  434.97  5081.7  435.31  5111.3  436.40  5134.2  436.25  5170.7  437.05
#Mann=5,-1,0
  4801.7    0.05       0  4812.6    0.16       0  4998.9    0.07       0
  5002.9    0.16       0  5057.2    0.05       0
Bank Sta=4998.9,5002.9
Exp/Cntr=0.3,0.1

Type RM Length L Ch R = 1,1195,484,484,484
BEGIN DESCRIPTION:
NORTH MINERAL CR TRIB 8 7 2 0
END DESCRIPTION:
XS GIS Cut Line= 2
      3497114.55     10398790.98      3496820.05     10398790.98
#Sta/Elev= 28
  4747.7  436.49  4751.4  436.49  4770.1  435.50  4800.1  434.11  4830.1  432.90
  4843.8  432.46  4850.1  432.31  4870.1  432.13  4880.1  431.88  4890.1  431.42
  4900.1  431.73  4920.1  431.73  4930.1  431.31  4940.1  429.48  4950.1  428.51
  4960.1  427.23  4970.1  426.33  4990.1  425.01  4998.1  421.46  4998.4  420.96
  5001.9  420.96  5002.1  421.46  5010.1  423.07  5020.1  428.78  5030.1  433.49
  5038.7  433.75  5041.4  433.75  5042.2  433.75
#Mann=5,-1,0
  4747.7    0.05       0  4843.8    0.16       0  4998.1    0.07       0
  5002.1    0.16       0  5041.4    0.05       0
Bank Sta=4998.1,5002.1
Exp/Cntr=0.3,0.1

Type RM Length L Ch R = 1,711,537,537,537
BEGIN DESCRIPTION:
NORTH MINERAL CR TRIB 8 7 4 0
END DESCRIPTION:
XS GIS Cut Line= 3
      3496877.02     10398242.13      3496753.45     10398514.72
      3496766.70     10398758.07
#Sta/Elev= 30
  4868.0  431.03  4888.0  431.56  4911.1  430.63  4922.4  431.46  4933.3  431.31
  4955.3  428.59  4959.3  427.03  4962.7  425.71  4968.2  424.64  4977.3  425.61
  4985.8  424.54  4991.3  421.43  4999.2  419.00  5008.9  421.05  5014.4  424.41
  5021.2  425.13  5052.4  422.53  5060.6  421.67  5064.1  418.63  5064.3  418.13
  5067.8  418.13  5068.1  418.63  5076.1  421.85  5083.7  424.03  5089.2  423.88
  5129.8  428.54  5135.3  428.21  5162.9  430.01  5257.4  431.13  5411.0  433.01
#Mann=6,-1,0
  4868.0    0.05       0  4959.3    0.12       0  5052.4    0.16       0
  5064.1    0.07       0  5068.1    0.16       0  5257.4    0.05       0
Bank Sta=5064.1,5068.1
Exp/Cntr=0.3,0.1

Type RM Length L Ch R = 1,174,0,0,0
BEGIN DESCRIPTION:
NORTH MINERAL CR TRIB 8 7 1 0
END DESCRIPTION:
XS GIS Cut Line= 3
      3496643.19     10398256.63      3496427.51     10398462.62
      3496461.45     10398551.09
#Sta/Elev= 30
  4769.4  430.62  4795.0  430.76  4816.1  429.78  4856.0  429.59  4867.2  429.26
  4886.8  428.68  4894.1  426.97  4901.0  426.59  4908.2  423.55  4915.1  424.45
  4922.4  422.15  4929.3  422.85  4936.5  421.99  4943.5  422.72  4964.5  422.85
  4978.7  422.08  4985.9  418.89  4998.1  417.38  4998.3  416.88  5001.8  416.88
  5002.1  417.38  5007.0  418.35  5014.2  423.32  5035.3  425.37  5042.5  422.72
  5056.7  426.00  5064.1  426.88  5087.5  427.66  5101.1  428.10  5162.4  428.32
#Mann=8,-1,0
  4769.4    0.12       0  4856.0    0.16       0  4867.2    0.12       0
  4998.1    0.07       0  5002.1    0.12       0  5064.1    0.05       0
  5087.5    0.12       0  5101.1    0.05       0
Bank Sta=4998.1,5002.1
Exp/Cntr=0.3,0.1

Chan Stop Cuts=-1