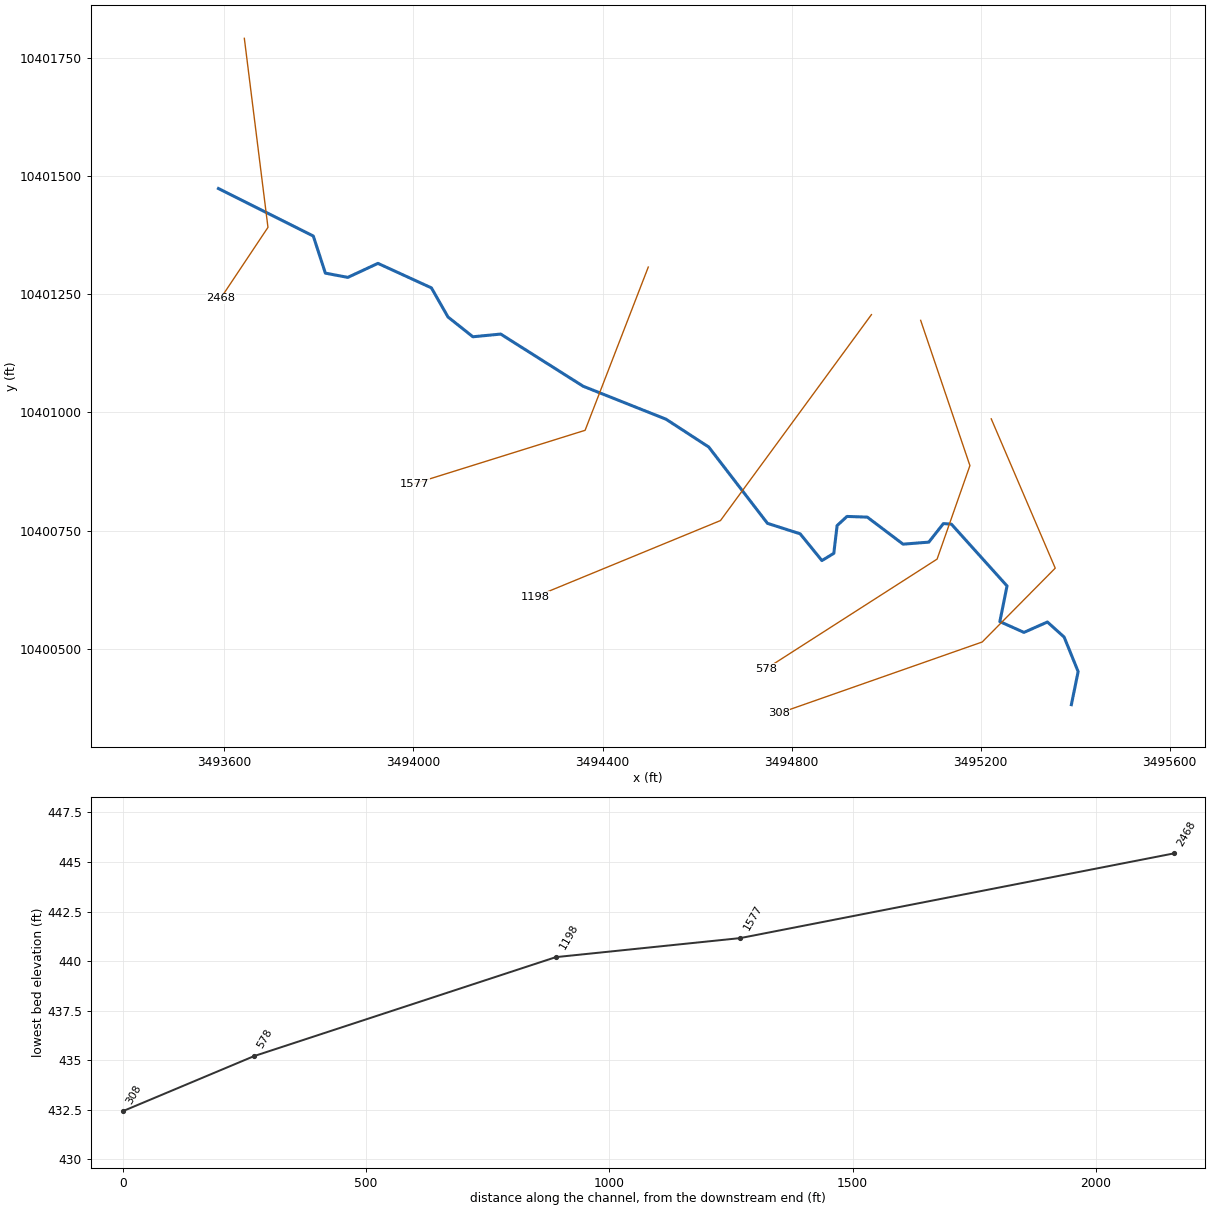
--- NORTH MINERAL CR TRIB 8 8.prj (project) ---

Proj Title=NORTH MINERAL CR TRIB 8 8 Base Level Engineering
Current Plan=p01
Default Exp/Contr=0.3,0.1
English Units
Geom File=g01
Flow File=f01
Plan File=p01
BEGIN DESCRIPTION:
NORTH MINERAL CR TRIB 8 8
END DESCRIPTION:

--- NORTH MINERAL CR TRIB 8 8.p01 (plan) ---

Plan Title=Multiple Run
Short Identifier=Multiple
Geom File=g01
Flow File=f01
Subcritical Flow
K Sum by GR= 0
Std Step Tol= 0.01
Critical Tol= 0.01
Num of Std Step Trials= 20
Max Error Tol= 0.3
Flow Tol Ratio= 0.001
Split Flow NTrial= 30
Split Flow Tol= 0.02
Split Flow Ratio= 0.02
Log Output Level= 0
Friction Slope Method= 1
Unsteady Friction Slope Method= 2
Unsteady Bridges Friction Slope Method= 1
Parabolic Critical Depth
Global Vel Dist=  1 , 1 , 1
Global Log Level= 0
CheckData=True
Encroach Param= -1, 0, 0, 0
BEGIN DESCRIPTION:
Multiple Run
END DESCRIPTION:

--- NORTH MINERAL CR TRIB 8 8.f01 (steady flow) ---

Flow Title=Multiple
Number of Profiles=7
Profile Names=10-year,25-year,50-year,1pct_min,100-year,1pct_plu,500-year
River Rch & RM= NORTH MINERAL CR,Reach-1,2468
     352     456     538     465     629     850     854
Boundary for River Rch & Prof#=NORTH MINERAL CR,Reach-1,1
Up Type=0
Dn Type=3
Dn Slope=0.005
Boundary for River Rch & Prof#=NORTH MINERAL CR,Reach-1,2
Up Type=0
Dn Type=3
Dn Slope=0.005
Boundary for River Rch & Prof#=NORTH MINERAL CR,Reach-1,3
Up Type=0
Dn Type=3
Dn Slope=0.005
Boundary for River Rch & Prof#=NORTH MINERAL CR,Reach-1,4
Up Type=0
Dn Type=3
Dn Slope=0.005
Boundary for River Rch & Prof#=NORTH MINERAL CR,Reach-1,5
Up Type=0
Dn Type=3
Dn Slope=0.005
Boundary for River Rch & Prof#=NORTH MINERAL CR,Reach-1,6
Up Type=0
Dn Type=3
Dn Slope=0.005
Boundary for River Rch & Prof#=NORTH MINERAL CR,Reach-1,7
Up Type=0
Dn Type=3
Dn Slope=0.005

--- NORTH MINERAL CR TRIB 8 8.g01 (geometry) ---

Geom Title=Existing Conditions

River Reach=NORTH MINERAL CR,Reach-1
Reach XY= 30
      3493587.29     10401473.81      3493788.01     10401373.28
      3493813.56     10401294.76      3493861.06     10401285.77
      3493924.80     10401315.43      3494037.97     10401263.58
      3494073.03     10401201.97      3494125.72     10401160.09
      3494184.52     10401165.85      3494358.98     10401055.47
      3494534.47     10400985.66      3494624.75     10400926.85
      3494749.05     10400765.33      3494818.20     10400743.21
      3494864.26     10400686.54      3494889.41     10400701.84
      3494896.39     10400760.62      3494917.31     10400779.94
      3494960.33     10400778.45      3495035.98     10400721.27
      3495090.42     10400725.57      3495121.28     10400764.76
      3495138.26     10400763.65      3495255.96     10400632.84
      3495240.75     10400557.43      3495291.83     10400534.57
      3495341.40     10400556.55      3495376.77     10400524.74
      3495406.45     10400451.61      3495392.11     10400381.64

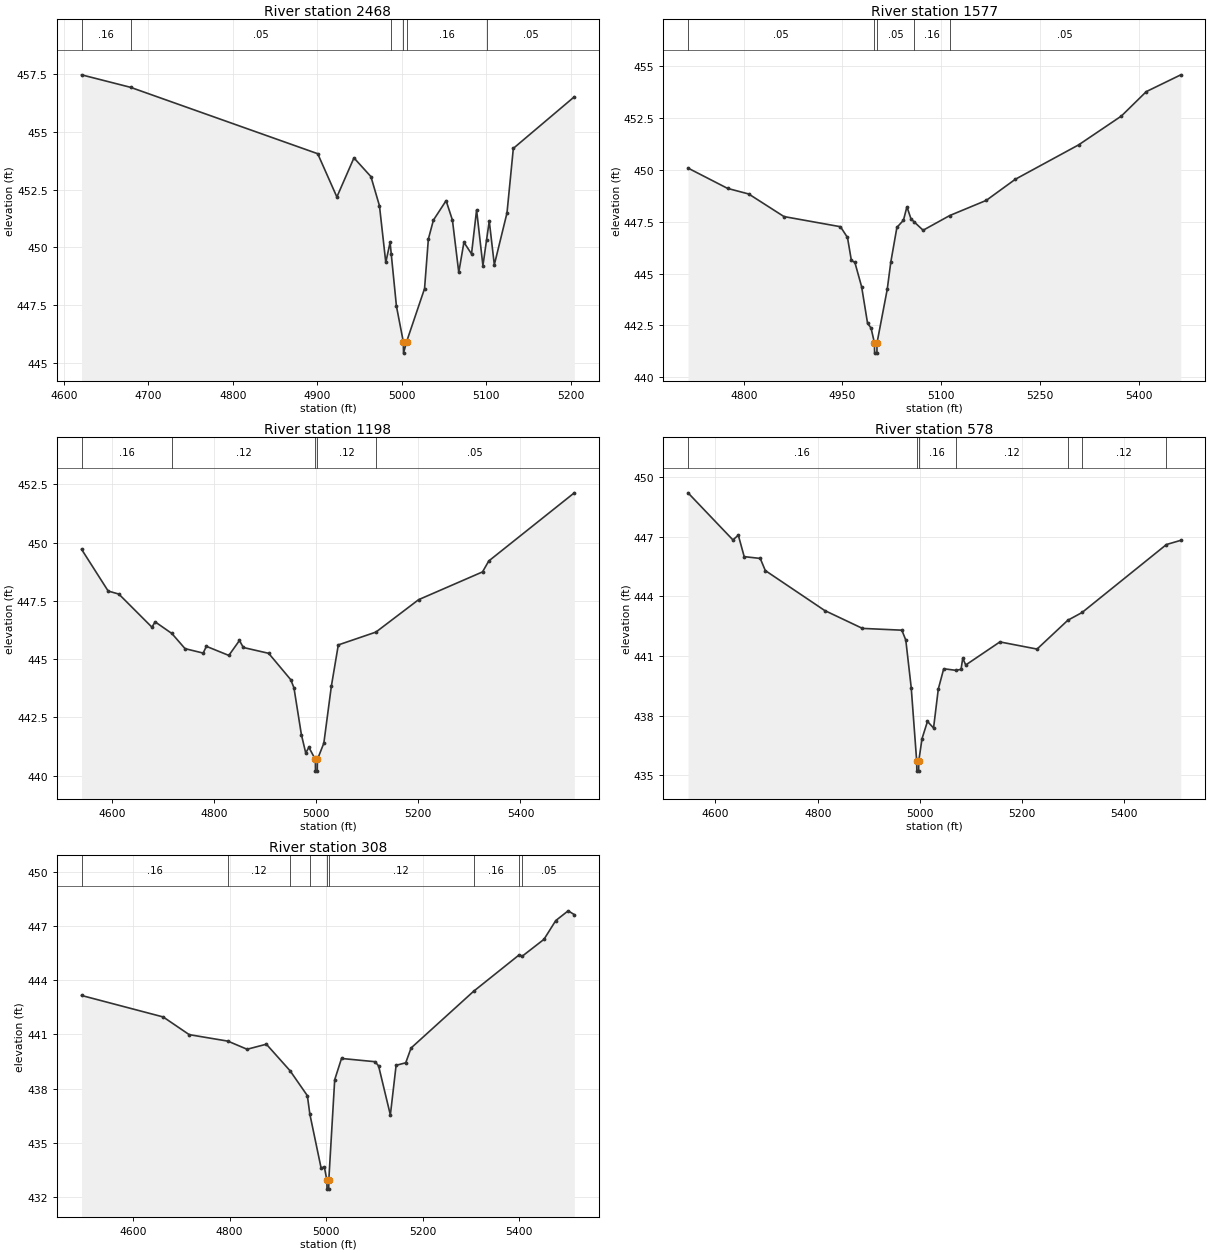
Type RM Length L Ch R = 1,2468,891,891,891
BEGIN DESCRIPTION:
NORTH MINERAL CR TRIB 8 8 3 0
END DESCRIPTION:
XS GIS Cut Line= 3
      3493642.11     10401791.61      3493692.11     10401391.64
      3493592.08     10401241.60
#Sta/Elev= 30
  4620.8  457.46  4678.8  456.92  4900.4  454.05  4923.1  452.18  4943.3  453.87
  4963.4  453.06  4973.5  451.80  4981.0  449.35  4986.1  450.22  4987.5  449.70
  4993.6  447.46  5001.7  445.93  5002.0  445.43  5005.7  445.93  5026.9  448.22
  5031.4  450.36  5037.4  451.18  5052.4  452.02  5059.9  451.18  5067.4  448.92
  5073.5  450.22  5082.5  449.72  5088.5  451.62  5096.0  449.21  5100.3  450.32
  5103.5  451.14  5109.5  449.25  5124.5  451.49  5132.0  454.28  5204.2  456.51
#Mann=6,-1,0
  4620.8    0.16       0  4678.8    0.05       0  4987.5    0.16       0
  5001.7    0.07       0  5005.7    0.16       0  5100.3    0.05       0
Bank Sta=5001.7,5005.7
Exp/Cntr=0.3,0.1

Type RM Length L Ch R = 1,1577,379,379,379
BEGIN DESCRIPTION:
NORTH MINERAL CR TRIB 8 8 2 0
END DESCRIPTION:
XS GIS Cut Line= 3
      3494496.84     10401307.65      3494363.17     10400962.20
      3494002.11     10400849.36
#Sta/Elev= 30
  4715.3  450.09  4775.4  449.11  4807.5  448.84  4861.1  447.75  4946.9  447.26
  4957.6  446.74  4963.5  445.63  4968.8  445.54  4979.1  444.36  4988.1  442.60
  4993.4  442.37  4998.5  441.66  4998.8  441.16  5002.3  441.16  5002.5  441.66
  5018.0  444.24  5023.4  445.55  5032.7  447.23  5042.6  447.57  5047.9  448.22
  5054.1  447.64  5059.0  447.49  5072.5  447.09  5113.0  447.80  5168.4  448.53
  5212.6  449.55  5308.8  451.21  5373.7  452.60  5411.6  453.78  5464.0  454.59
#Mann=5,-1,0
  4715.3    0.05       0  4998.5    0.03       0  5002.5    0.05       0
  5059.0    0.16       0  5113.0    0.05       0
Bank Sta=4998.5,5002.5
Exp/Cntr=0.3,0.1

Type RM Length L Ch R = 1,1198,620,620,620
BEGIN DESCRIPTION:
NORTH MINERAL CR TRIB 8 8 4 0
END DESCRIPTION:
XS GIS Cut Line= 3
      3494969.10     10401207.03      3494649.63     10400771.22
      3494257.31     10400609.78
#Sta/Elev= 30
  4540.8  449.71  4592.9  447.92  4613.8  447.79  4678.6  446.37  4684.8  446.60
  4717.6  446.10  4743.4  445.45  4778.9  445.26  4785.1  445.55  4829.1  445.16
  4849.9  445.80  4857.5  445.50  4907.1  445.25  4950.3  444.12  4956.6  443.77
  4971.1  441.77  4979.6  440.98  4985.8  441.22  4998.5  440.70  4998.7  440.20
  5002.2  440.20  5002.5  440.70  5015.1  441.40  5029.8  443.84  5043.4  445.61
  5117.0  446.16  5200.6  447.55  5325.7  448.74  5338.0  449.21  5505.4  452.13
#Mann=5,-1,0
  4540.8    0.16       0  4717.6    0.12       0  4998.5    0.07       0
  5002.5    0.12       0  5117.0    0.05       0
Bank Sta=4998.5,5002.5
Exp/Cntr=0.3,0.1

Type RM Length L Ch R = 1,578,270,270,270
BEGIN DESCRIPTION:
Mapping XS c465de73
END DESCRIPTION:
XS GIS Cut Line= 4
      3495073.23     10401194.85      3495177.41     10400887.54
      3495107.96     10400689.63      3494746.09     10400457.61
#Sta/Elev= 30
  4546.3  449.21  4634.2  446.84  4644.7  447.08  4656.2  446.00  4687.6  445.91
  4697.5  445.30  4813.7  443.29  4887.6  442.39  4964.7  442.30  4972.4  441.80
  4983.0  439.41  4993.7  435.71  4994.0  435.21  4997.5  435.21  4997.7  435.71
  5004.2  436.85  5014.8  437.71  5026.7  437.38  5036.0  439.34  5046.6  440.36
  5070.6  440.28  5080.5  440.33  5083.8  440.89  5089.7  440.55  5156.5  441.71
  5229.2  441.35  5289.4  442.80  5317.3  443.19  5482.4  446.61  5510.4  446.82
#Mann=7,-1,0
  4546.3    0.16       0  4993.7    0.07       0  4997.7    0.16       0
  5070.6    0.12       0  5289.4    0.16       0  5317.3    0.12       0
  5482.4    0.05       0
Bank Sta=4993.7,4997.7
Exp/Cntr=0.3,0.1

Type RM Length L Ch R = 1,308,0,0,0
BEGIN DESCRIPTION:
NORTH MINERAL CR TRIB 8 8 1 0
END DESCRIPTION:
XS GIS Cut Line= 4
      3495222.56     10400986.46      3495357.96     10400670.53
      3495203.45     10400514.28      3494772.85     10400363.22
#Sta/Elev= 30
  4493.8  443.16  4662.7  441.97  4716.6  440.99  4796.6  440.63  4836.4  440.18
  4876.3  440.46  4925.3  438.99  4961.1  437.61  4966.3  436.58  4989.4  433.62
  4996.4  433.64  5001.5  432.93  5001.8  432.43  5005.3  432.43  5005.5  432.93
  5017.7  438.49  5031.8  439.67  5101.1  439.49  5108.5  439.26  5132.9  436.54
  5144.8  439.29  5164.7  439.43  5175.8  440.25  5305.1  443.39  5399.5  445.41
  5406.0  445.34  5450.8  446.27  5475.2  447.31  5500.9  447.85  5513.6  447.64
#Mann=9,-1,0
  4493.8    0.16       0  4796.6    0.12       0  4925.3    0.16       0
  4966.3    0.12       0  5001.5    0.07       0  5005.5    0.12       0
  5305.1    0.16       0  5399.5    0.12       0  5406.0    0.05       0
Bank Sta=5001.5,5005.5
Exp/Cntr=0.3,0.1

Chan Stop Cuts=-1