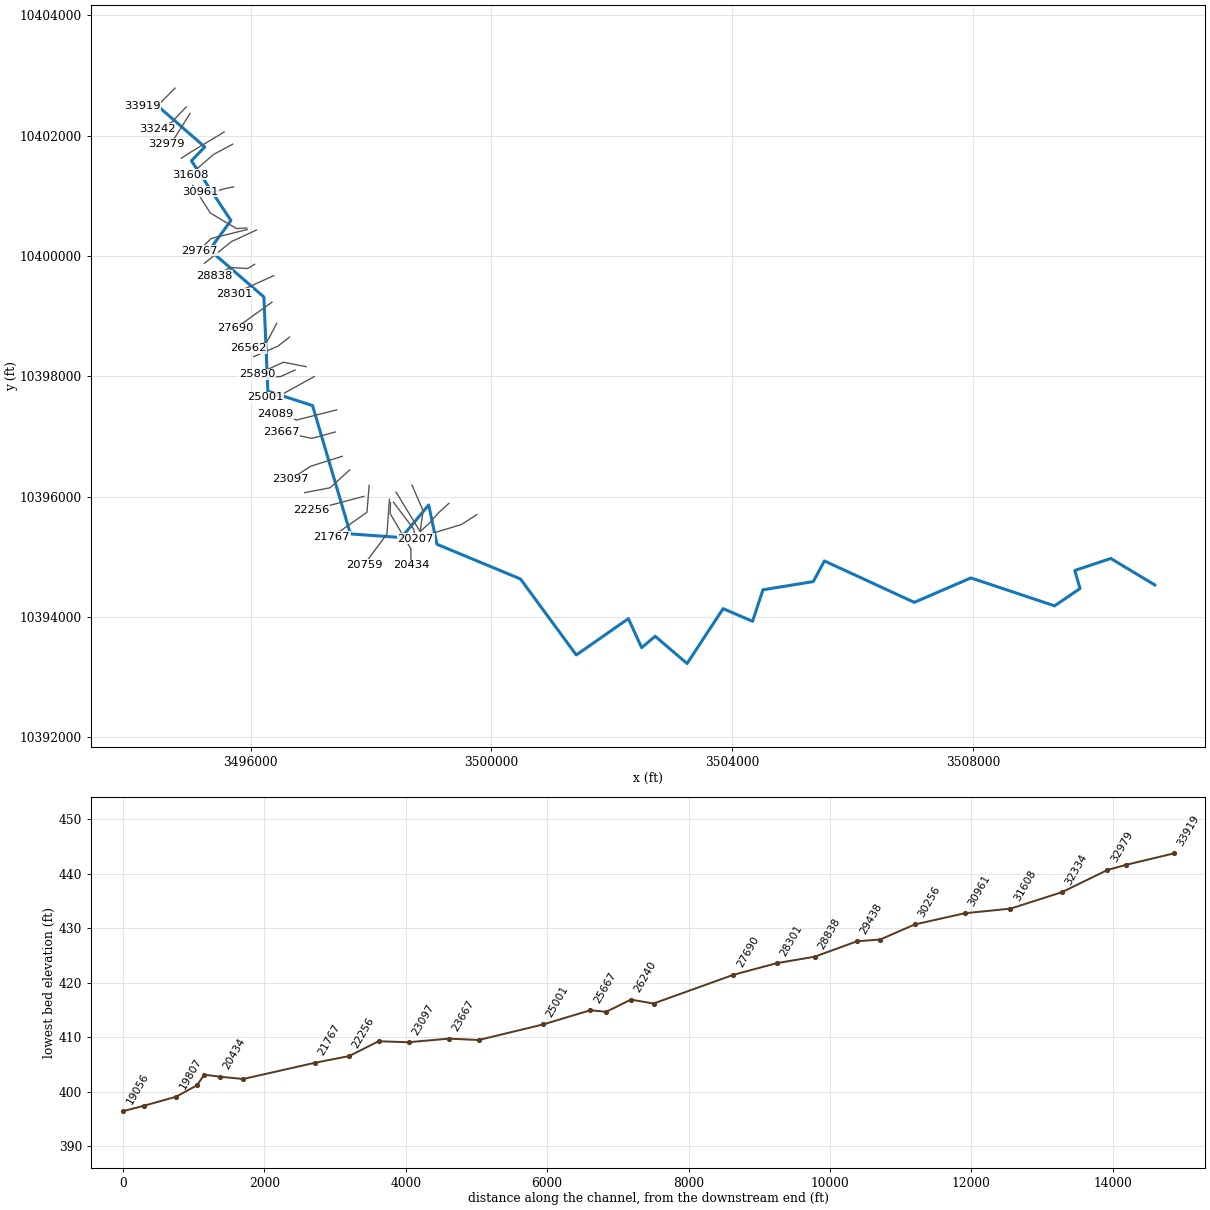
--- NORTH MINERAL CR TRIB 8.prj (project) ---

Proj Title=NORTH MINERAL CR TRIB 8 Base Level Engineering
Current Plan=p01
Default Exp/Contr=0.3,0.1
English Units
Geom File=g01
Flow File=f01
Plan File=p01
Y Axis Title=Elevation
X Axis Title(PF)=Main Channel Distance
X Axis Title(XS)=Station
BEGIN DESCRIPTION:
NORTH MINERAL CR TRIB 8
END DESCRIPTION:
DSS Export Rating Curves= 0
DSS Export Rating Curve Sorted= 0
DSS Export Volume Flow Curves= 0
DXF OffsetX= 0
DXF OffsetY= 0
DXF ScaleX= 1
DXF ScaleY= 10

--- NORTH MINERAL CR TRIB 8.p01 (plan) ---

Plan Title=Multiple Run
Short Identifier=Multiple
Geom File=g01
Flow File=f01
Subcritical Flow
K Sum by GR= 0
Std Step Tol= 0.01
Critical Tol= 0.01
Num of Std Step Trials= 20
Max Error Tol= 0.3
Flow Tol Ratio= 0.001
Split Flow NTrial= 30
Split Flow Tol= 0.02
Split Flow Ratio= 0.02
Log Output Level= 0
Friction Slope Method= 1
Unsteady Friction Slope Method= 2
Unsteady Bridges Friction Slope Method= 1
Parabolic Critical Depth
Global Vel Dist=  1 , 1 , 1
Global Log Level= 0
CheckData=True
Encroach Param= -1, 0, 0, 0
BEGIN DESCRIPTION:
Multiple Run
END DESCRIPTION:

--- NORTH MINERAL CR TRIB 8.f01 (steady flow) ---

Flow Title=Multiple
Program Version=4.10
Number of Profiles= 7
Profile Names=10-year,25-year,50-year,1pct_min,100-year,1pct_plu,500-year
River Rch & RM=NORTH MINERAL CR,Reach-1         ,33919
     586     786     945     831    1124    1520    1585
River Rch & RM=NORTH MINERAL CR,Reach-1         ,29767
     839    1145    1396    1241    1679    2271    2423
River Rch & RM=NORTH MINERAL CR,Reach-1         ,25890
    1106    1533    1886    1691    2287    3093    3358
River Rch & RM=NORTH MINERAL CR,Reach-1         ,23097
    1939    2767    3472    3170    4287    5797    6527
River Rch & RM=NORTH MINERAL CR,Reach-1         ,20434
    2081    2975    3737    3414    4617    6245    7043
River Rch & RM=NORTH MINERAL CR,Reach-1         ,19056
    2337    3349    4214    3853    5211    7047    7961
River Rch & RM=NORTH MINERAL CR,Reach-1         ,13922
    2437    3488    4384    4004    5415    7323    8253
River Rch & RM=NORTH MINERAL CR,Reach-1         ,7781
    2534    3630    4565    4170    5640    7627    8602
Boundary for River Rch & Prof#=NORTH MINERAL CR,Reach-1         , 1
Up Type= 0
Dn Type= 3
Dn Slope=0.002
Boundary for River Rch & Prof#=NORTH MINERAL CR,Reach-1         , 2
Up Type= 0
Dn Type= 3
Dn Slope=0.002
Boundary for River Rch & Prof#=NORTH MINERAL CR,Reach-1         , 3
Up Type= 0
Dn Type= 3
Dn Slope=0.002
Boundary for River Rch & Prof#=NORTH MINERAL CR,Reach-1         , 4
Up Type= 0
Dn Type= 3
Dn Slope=0.002
Boundary for River Rch & Prof#=NORTH MINERAL CR,Reach-1         , 5
Up Type= 0
Dn Type= 3
Dn Slope=0.002
Boundary for River Rch & Prof#=NORTH MINERAL CR,Reach-1         , 6
Up Type= 0
Dn Type= 3
Dn Slope=0.002
Boundary for River Rch & Prof#=NORTH MINERAL CR,Reach-1         , 7
Up Type= 0
Dn Type= 3
Dn Slope=0.002
DSS Import GetInterval= 0
DSS Import GetPeak= 0
DSS Import FillOption= 0

--- NORTH MINERAL CR TRIB 8.g01 (geometry) ---

Geom Title=Existing Conditions
Program Version=4.10

River Reach=NORTH MINERAL CR,Reach-1
Reach XY= 30
      3494412.99     10402531.81      3495236.18     10401814.59
      3495015.18     10401583.28      3495671.17     10400591.11
      3495314.63     10400102.76      3496218.55     10399319.51
      3496284.91     10397752.44      3497027.02     10397514.59
      3497656.47     10395380.03      3498504.14      10395319.5
      3498957.23     10395861.74       3499094.7      10395207.9
      3500482.02     10394631.06      3501409.48     10393367.07
      3502275.68     10393971.58      3502495.49     10393488.84
      3502720.71     10393678.41      3503250.55     10393224.66
      3503849.35     10394137.31        3504339.     10393927.41
       3504511.7     10394451.34       3505348.9     10394587.54
      3505531.77     10394930.93      3507026.18     10394242.12
      3507967.29     10394648.25      3509357.82     10394184.21
      3509780.29     10394472.42      3509692.66     10394772.33
      3510291.36     10394971.59      3511022.11     10394531.64

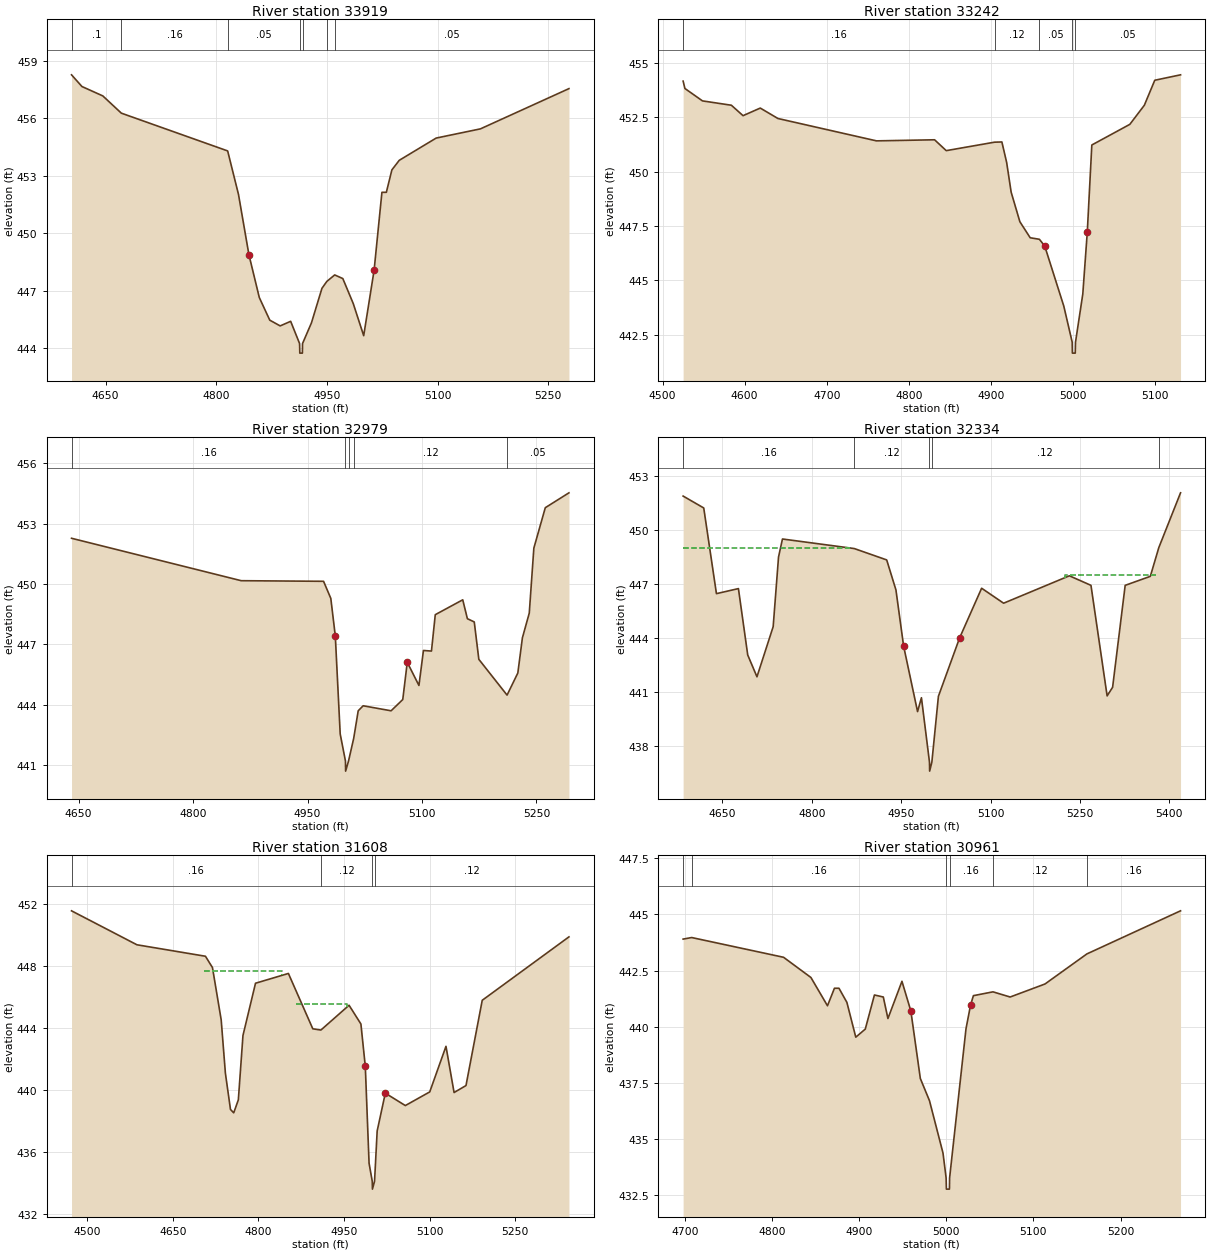
Type RM Length L Ch R = 1 ,33919   ,677,677,677
BEGIN DESCRIPTION:
NORTH MINERAL CR TRIB 8 60
END DESCRIPTION:
XS GIS Cut Line= 3
      3494742.09     10402791.63      3494442.11     10402491.64
      3494192.15     10402491.64
#Sta/Elev= 30
  4603.9  458.27    4618  457.66  4646.3  457.17  4671.4  456.27  4815.5   454.3
  4830.2  452.03  4844.3  448.89  4858.4  446.65  4872.6  445.47  4886.7  445.17
  4900.9  445.41    4913  444.25  4913.3  443.75  4916.8  443.75    4917  444.25
  4929.1  445.33  4943.3  447.13  4949.9  447.49  4960.6  447.83  4971.6  447.64
  4985.7  446.34  4999.9  444.66    5014  448.07  5024.6  452.14  5030.6  452.14
  5038.1  453.31  5048.1  453.81  5098.1  454.97  5158.1  455.45  5278.1  457.55
#Mann= 7 ,-1 , 0
  4603.9      .1       0  4671.4     .16       0  4815.5     .05       0
    4913    .035       0    4917     .05       0  4949.9     .16       0
  4960.6     .05       0
Bank Sta=4844.3,5014
XS Rating Curve= 0 ,0
Exp/Cntr=0.3,0.1

Type RM Length L Ch R = 1 ,33242   ,263,263,263
BEGIN DESCRIPTION:
NORTH MINERAL CR TRIB 8 63
END DESCRIPTION:
XS GIS Cut Line= 3
      3494927.38     10402479.52      3494686.09     10402224.35
      3494453.44     10402120.18
#Sta/Elev= 30
    4525  454.17  4527.2  453.83  4548.6  453.26  4583.8  453.06    4598  452.58
    4619  452.93  4640.5  452.45  4760.6  451.42  4831.4  451.47  4845.6  450.97
  4904.5  451.36  4913.4  451.37  4919.2  450.43  4924.7  449.06  4935.3   447.7
  4947.9  446.96  4959.1  446.89  4965.6  446.58  4988.8  443.82  4999.1  442.15
  4999.3  441.65  5002.8  441.65  5003.1  442.15    5012  444.37  5017.5  447.24
    5023  451.23  5069.3  452.18    5087  453.06  5099.7  454.21  5131.1  454.46
#Mann= 5 ,-1 , 0
    4525     .16       0  4904.5     .12       0  4959.1     .05       0
  4999.1    .035       0  5003.1     .05       0
Bank Sta=4965.6,5017.5
XS Rating Curve= 0 ,0
Exp/Cntr=0.3,0.1

Type RM Length L Ch R = 1 ,32979   ,645,645,645
BEGIN DESCRIPTION:
NORTH MINERAL CR TRIB 8 51 0
END DESCRIPTION:
XS GIS Cut Line= 3
        3494990.     10402370.25      3494740.02     10401970.29
      3494590.05      10401870.3
#Sta/Elev= 30
  4640.7  452.28  4863.1  450.17    4971  450.14  4980.5  449.29  4986.4  447.42
  4992.8  442.55  4999.7   441.2  4999.9   440.7  5003.7   441.2  5010.5  442.33
  5016.4   443.7  5022.9  443.95  5059.5   443.7  5074.8  444.26  5080.7  446.11
    5096  444.96  5101.9   446.7  5112.4  446.67  5117.4  448.48  5153.4  449.22
  5159.5  448.28  5168.5  448.12  5174.5  446.26  5211.5  444.48  5225.6  445.58
  5231.6  447.33  5240.6  448.56  5246.6  451.79  5261.6   453.8  5292.6  454.54
#Mann= 5 ,-1 , 0
  4640.7     .16       0  4999.7     .07       0  5003.7     .16       0
  5010.5     .12       0  5211.5     .05       0
Bank Sta=4986.4,5080.7
XS Rating Curve= 0 ,0
Exp/Cntr=0.3,0.1

Type RM Length L Ch R = 1 ,32334   ,726,726,726
BEGIN DESCRIPTION:
NORTH MINERAL CR TRIB 8 49 0
END DESCRIPTION:
XS GIS Cut Line= 3
      3495559.32     10402062.87      3495015.95      10401736.5
      3494847.51      10401627.1
#Sta/Elev= 30
  4584.2  451.87  4618.8  451.21  4640.1  446.46    4677  446.74  4692.6  443.06
  4708.1  441.85  4735.3  444.63  4744.3  448.49  4750.9  449.49  4871.4  448.96
  4925.8  448.33  4941.3  446.67  4954.2  443.55  4977.6  439.92  4984.1  440.69
  4997.6  437.12  4997.9  436.62  5001.6  437.12  5012.6  440.77  5048.2  444.01
  5085.1  446.76    5122  445.93  5232.4  447.45  5268.6  446.92  5295.7  440.79
  5304.9  441.27    5326  446.92  5368.2  447.42  5382.4  449.01  5418.9  452.05
#Mann= 5 ,-1 , 0
  4584.2     .16       0  4871.4     .12       0  4997.6     .07       0
  5001.6     .12       0  5382.4     .16       0
#XS Ineff= 2 ,-1
 4583.97 4867.64  449.01 5225.04 5377.41  447.48
Permanent Ineff=
       F       F
Bank Sta=4954.2,5048.2
XS Rating Curve= 0 ,0
Exp/Cntr=0.3,0.1

Type RM Length L Ch R = 1 ,31608   ,647,647,647
BEGIN DESCRIPTION:
NORTH MINERAL CR TRIB 8 50
END DESCRIPTION:
XS GIS Cut Line= 3
      3495700.02     10401859.79      3495382.27     10401689.63
      3494995.09     10401354.53
#Sta/Elev= 30
  4472.1  451.56  4586.8  449.37    4707  448.63  4719.3   447.9  4734.6  444.53
    4742  441.08  4750.9  438.75  4756.6  438.53  4764.7  439.37  4772.8  443.52
  4794.8  446.89  4852.5  447.52  4895.3  443.95  4909.5  443.87  4958.9  445.47
  4979.7  444.26  4987.4  441.52    4994  435.28  4999.6  434.11  4999.9  433.61
  5003.6  434.11  5008.2  437.36  5022.5   439.8  5057.6     439  5100.4  439.88
  5128.9  442.82  5143.1  439.84    5164  440.29  5192.5  445.79  5344.6  449.88
#Mann= 4 ,-1 , 0
  4472.1     .16       0  4909.5     .12       0  4999.6     .07       0
  5003.6     .12       0
#XS Ineff= 2 ,-1
 4703.69 4841.78  447.67 4865.18  4955.3  445.55
Permanent Ineff=
       F       F
Bank Sta=4987.4,5022.5
XS Rating Curve= 0 ,0
Exp/Cntr=0.3,0.1

Type RM Length L Ch R = 1 ,30961   ,705,705,705
BEGIN DESCRIPTION:
NORTH MINERAL CR TRIB 8 48 1
END DESCRIPTION:
XS GIS Cut Line= 5
      3495715.87     10401150.58      3495544.33      10401115.5
      3495394.33      10401065.5      3495294.33      10401065.5
      3495156.59     10401069.19
#Sta/Elev= 30
  4697.9   443.9  4707.7  443.97  4813.2  443.09  4844.6  442.19  4863.6  440.93
  4871.6  441.71  4876.8  441.71  4885.9  441.08  4896.1  439.53    4907  439.89
  4917.5  441.41  4927.7  441.32    4933  440.36  4949.1  442.02  4959.3   440.7
  4970.2  437.69  4980.7   436.7  4996.2  434.37  4999.8  433.26  5000.1  432.76
  5003.6  432.76  5003.8  433.26  5022.6   439.9  5027.8  440.95  5031.1  441.38
  5053.6  441.55  5073.3  441.32  5113.3   441.9  5161.4  443.24  5268.9  445.16
#Mann= 6 ,-1 , 0
  4697.9     .05       0  4707.7     .16       0  4999.8     .07       0
  5003.8     .16       0  5053.6     .12       0  5161.4     .16       0
Bank Sta=4959.3,5027.8
XS Rating Curve= 0 ,0
Exp/Cntr=0.3,0.1

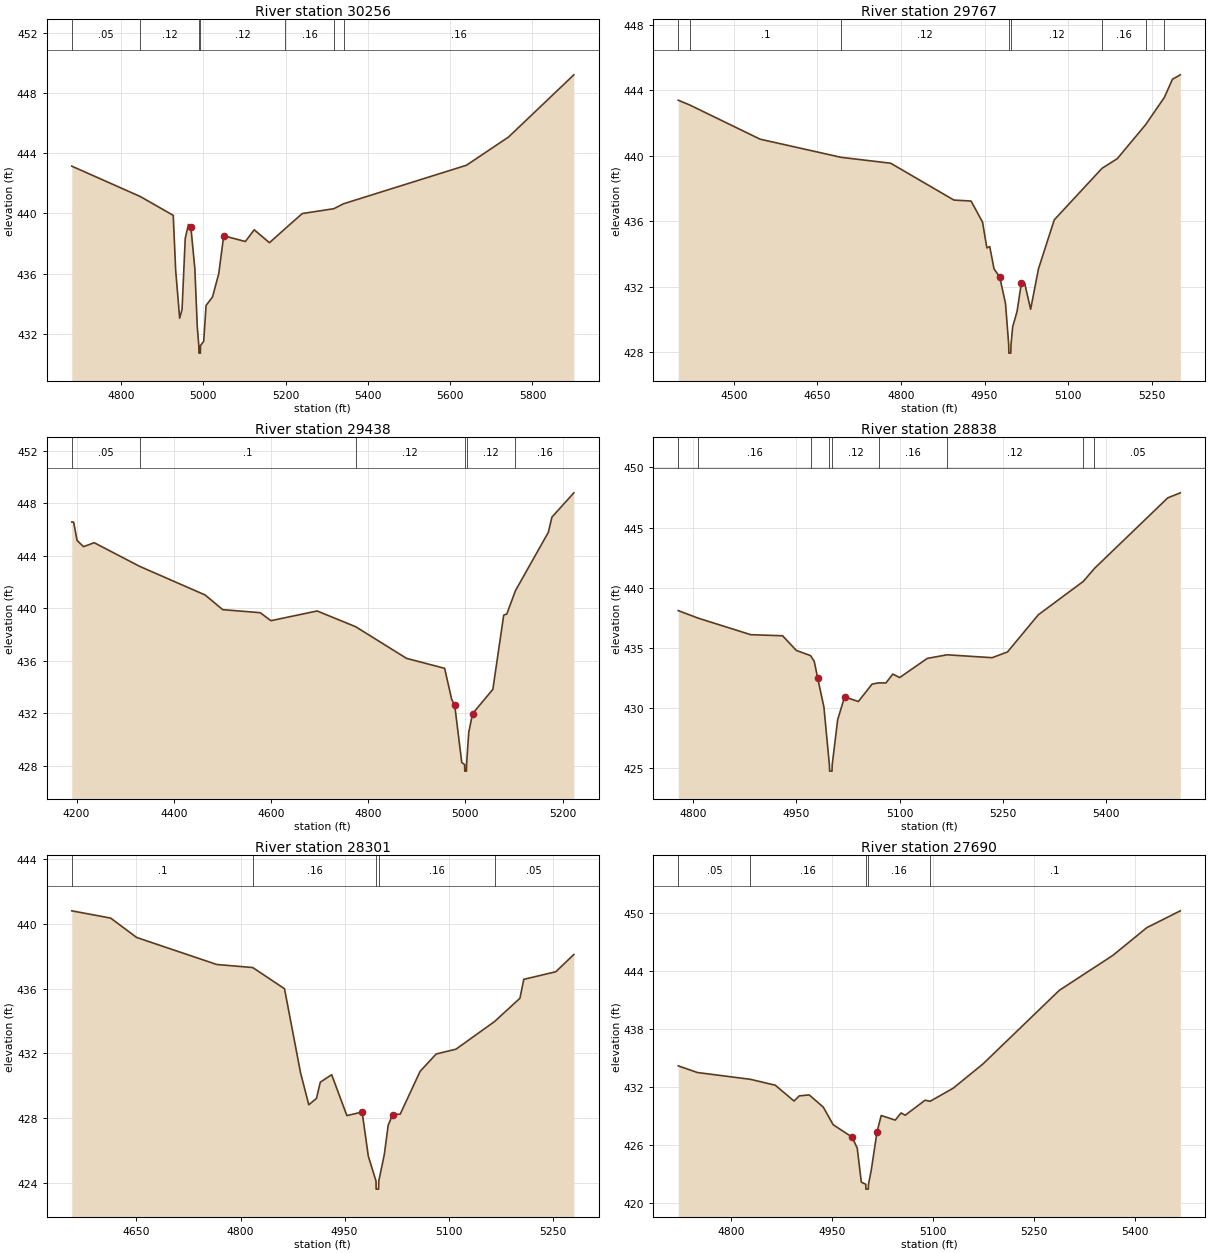
Type RM Length L Ch R = 1 ,30256   ,489,489,489
BEGIN DESCRIPTION:
NORTH MINERAL CR TRIB 8 48 2
END DESCRIPTION:
XS GIS Cut Line= 4
      3495932.58      10400467.4      3495764.21     10400456.99
      3495328.45     10400715.67      3495036.32     10401175.47
#Sta/Elev= 30
  4680.4  443.14  4846.9  441.12    4927  439.87  4932.9  436.23  4942.6  433.03
  4948.4  433.61  4956.2  438.35    4964  439.26  4969.8   439.1  4979.5  436.34
  4985.4  432.48  4989.2  431.21  4989.5  430.71    4993  430.71  4993.2  431.21
    5001   431.5  5006.8  433.88  5022.4  434.44  5037.6  435.99  5049.7  438.51
  5102.3  438.13  5123.8  438.91  5160.8  438.05  5199.6     439  5240.7  439.99
  5317.3  440.31    5341  440.64  5639.7   443.2  5742.1  445.08  5900.6  449.21
#Mann= 7 ,-1 , 0
  4680.4     .05       0  4846.9     .12       0  4989.2     .07       0
  4993.2     .12       0  5199.6     .16       0  5317.3     .12       0
    5341     .16       0
Bank Sta=4969.8,5049.7
XS Rating Curve= 0 ,0
Exp/Cntr=0.3,0.1

Type RM Length L Ch R = 1 ,29767   ,329,329,329
BEGIN DESCRIPTION:
NORTH MINERAL CR TRIB 8 47 0
END DESCRIPTION:
XS GIS Cut Line= 3
       3495942.1     10400441.64      3495342.11     10400291.64
      3495142.11     10400091.65
#Sta/Elev= 30
  4400.1  443.39  4420.6   443.1    4547  441.01  4692.5   439.9  4781.5  439.54
  4894.9  437.29  4925.8  437.23  4946.4  435.94  4954.1  434.37  4959.3  434.45
    4967  433.09  4977.3  432.58  4987.6  430.97  4993.4  428.44  4993.6  427.94
  4997.1  427.94  4997.4  428.44  5000.5  429.55  5008.3  430.48    5016   432.2
  5022.1   432.2  5032.7  430.62  5046.8  433.09  5075.1  436.08  5160.9  439.23
  5188.3  439.82    5239  441.89  5272.6  443.55  5287.3  444.67  5301.4  444.94
#Mann= 8 ,-1 , 0
  4400.1     .05       0  4420.6      .1       0  4692.5     .12       0
  4993.4     .07       0  4997.4     .12       0  5160.9     .16       0
    5239     .12       0  5272.6     .16       0
Bank Sta=4977.3,5016
XS Rating Curve= 0 ,0
Exp/Cntr=0.3,0.1

Type RM Length L Ch R = 1 ,29438   ,600,600,600
BEGIN DESCRIPTION:
NORTH MINERAL CR TRIB 8 46 0
END DESCRIPTION:
XS GIS Cut Line= 3
      3496094.03     10400432.66      3495680.88     10400241.71
      3495231.26     10399878.89
#Sta/Elev= 30
  4190.2  446.58    4194  446.58  4201.2  445.18  4214.4  444.71  4236.4  445.01
  4329.8  443.21  4464.5  441.03  4500.8  439.91  4577.9  439.68  4599.9  439.07
    4695  439.81  4774.3  438.61  4878.9   436.2  4957.3  435.44  4971.7  433.09
  4978.1  432.61  4992.5  428.27  4998.4  428.11  4998.7  427.61  5002.2  427.61
  5002.4  428.11  5006.9  430.57  5014.8  431.99  5056.5  433.84  5078.8  439.49
  5085.2  439.58    5103  441.36  5170.6   445.8    5178  446.96  5223.1  448.81
#Mann= 6 ,-1 , 0
  4190.2     .05       0  4329.8      .1       0  4774.3     .12       0
  4998.4     .07       0  5002.4     .12       0    5103     .16       0
Bank Sta=4978.1,5014.8
XS Rating Curve= 0 ,0
Exp/Cntr=0.3,0.1

Type RM Length L Ch R = 1 ,28838   ,537,537,537
BEGIN DESCRIPTION:
NORTH MINERAL CR TRIB 8 45 0
END DESCRIPTION:
XS GIS Cut Line= 4
      3496064.36     10399862.89      3495947.19     10399792.58
      3495668.55     10399810.81      3495387.32      10399670.2
#Sta/Elev= 30
    4778  438.11  4807.2  437.48  4883.5  436.11  4929.8  436.02  4949.8   434.8
  4970.5  434.37  4975.8   433.9  4980.8  432.52  4989.9   430.1  4997.9  425.28
  4998.2  424.78  5001.7  424.78  5001.9  425.28  5009.9  429.05    5020  430.95
    5040  430.56    5060  432.01  5069.8  432.11  5080.1   432.1  5090.1  432.84
  5100.1  432.55  5140.2  434.14  5169.1  434.44  5234.6   434.2    5257  434.68
  5301.7  437.76  5367.3  440.54  5383.4  441.61    5490  447.47  5508.3  447.89
#Mann= 9 ,-1 , 0
    4778      .1       0  4807.2     .16       0  4970.5     .12       0
  4997.9     .07       0  5001.9     .12       0  5069.8     .16       0
  5169.1     .12       0  5367.3     .16       0  5383.4     .05       0
Bank Sta=4980.8,5020
XS Rating Curve= 0 ,0
Exp/Cntr=0.3,0.1

Type RM Length L Ch R = 1 ,28301   ,611,611,611
BEGIN DESCRIPTION:
NORTH MINERAL CR TRIB 8 43 0
END DESCRIPTION:
XS GIS Cut Line= 2
      3496383.18       10399675.      3495724.25     10399375.48
#Sta/Elev= 30
  4556.7  440.81  4612.8  440.36  4650.3  439.16  4765.7  437.49  4817.6   437.3
  4863.4  435.99  4886.5  430.79  4898.4  428.81  4909.4   429.2    4915  430.21
  4931.4  430.67  4953.3  428.14  4975.3  428.36  4984.2  425.63  4995.3  424.09
  4995.5  423.59    4999  423.59  4999.3  424.09  5007.3  425.74  5012.8  427.53
  5019.2  428.19  5030.2  428.23  5058.9  430.88    5082  431.95  5110.6  432.25
  5166.2  433.96  5202.8   435.4  5208.3  436.57  5254.5  437.04  5280.5  438.11
#Mann= 5 ,-1 , 0
  4556.7      .1       0  4817.6     .16       0  4995.3     .07       0
  4999.3     .16       0  5166.2     .05       0
Bank Sta=4975.3,5019.2
XS Rating Curve= 0 ,0
Exp/Cntr=0.3,0.1

Type RM Length L Ch R = 1 ,27690   ,1128,1128,1128
BEGIN DESCRIPTION:
NORTH MINERAL CR TRIB 8 44 0
END DESCRIPTION:
XS GIS Cut Line= 2
      3496351.86     10399232.25      3495746.09     10398798.07
#Sta/Elev= 30
  4721.8  434.19  4750.4   433.5    4829   432.8  4865.9  432.19  4893.7  430.56
  4901.5  431.09  4916.2  431.19  4937.1  429.93  4951.8  428.11  4979.9  426.83
  4987.5   425.7  4993.6  422.18  5000.2  421.96  5000.4  421.46  5003.9  421.46
  5004.2  421.96  5008.4  423.44  5016.8  427.34  5023.1  429.06    5044  428.59
  5052.6  429.33  5058.7  429.09  5088.2  430.64  5095.7  430.53  5129.9  431.88
  5174.2  434.39  5287.5  441.99    5367   445.6  5417.3  448.46  5467.1   450.2
#Mann= 5 ,-1 , 0
  4721.8     .05       0    4829     .16       0  5000.2     .07       0
  5004.2     .16       0  5095.7      .1       0
Bank Sta=4979.9,5016.8
XS Rating Curve= 0 ,0
Exp/Cntr=0.3,0.1

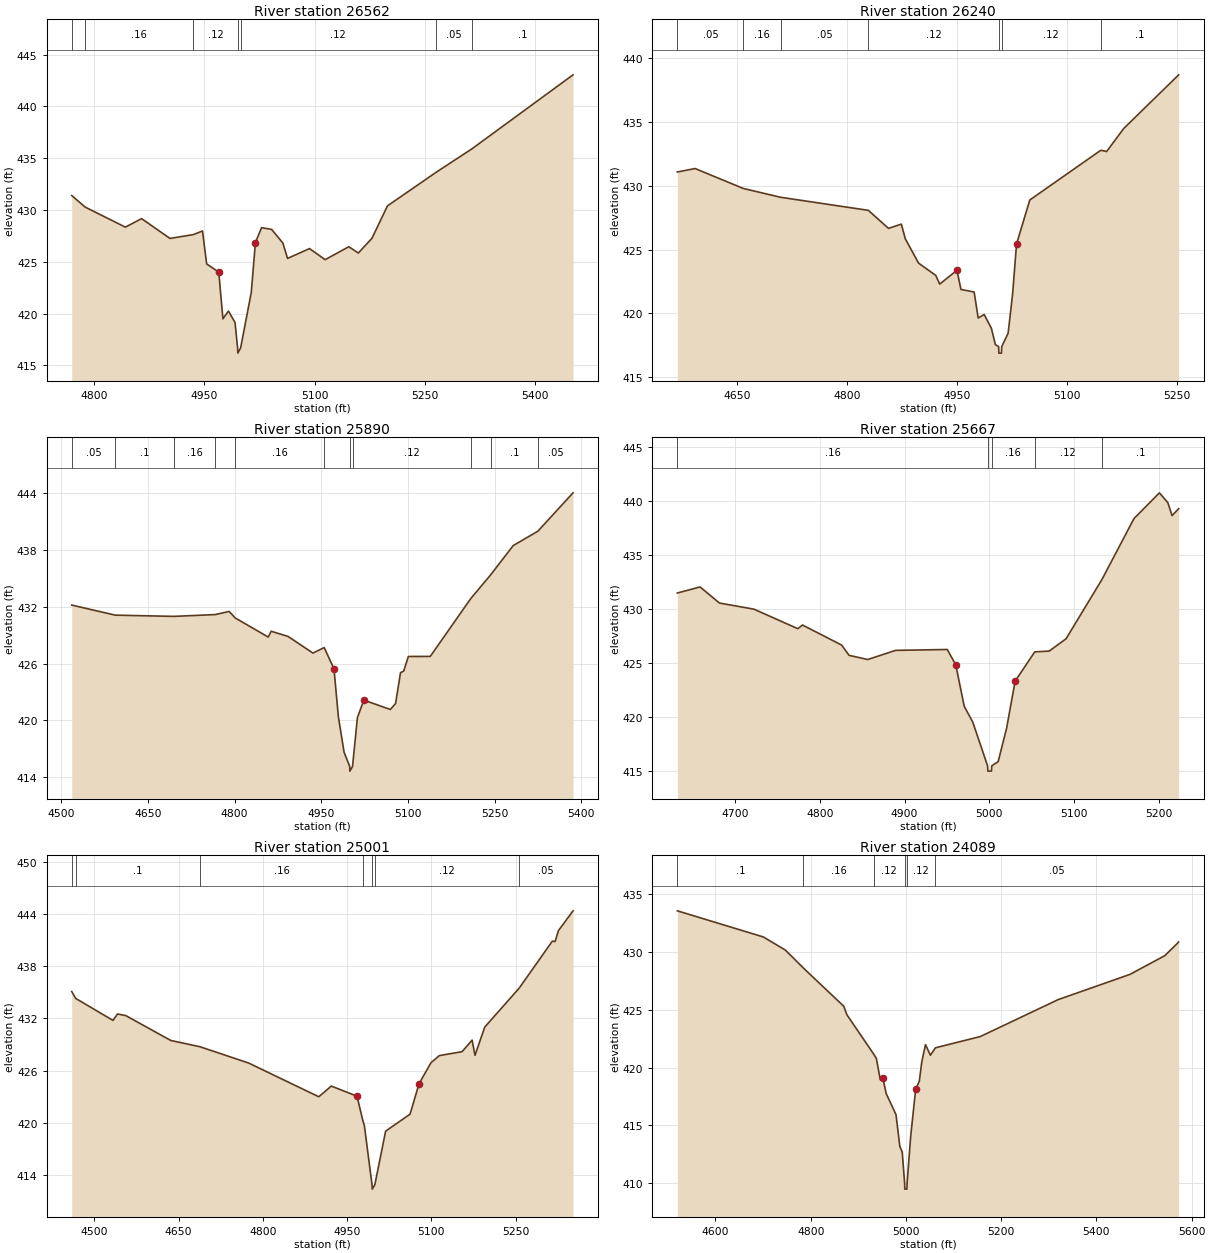
Type RM Length L Ch R = 1 ,26562   ,322,322,322
BEGIN DESCRIPTION:
NORTH MINERAL CR TRIB 8 42 1
END DESCRIPTION:
XS GIS Cut Line= 4
      3496431.12      10398880.6      3496308.77     10398645.58
      3496256.67      10398564.4      3495951.94     10398466.45
#Sta/Elev= 30
  4769.7   431.4  4788.1  430.28  4842.6  428.35  4864.7  429.17  4903.3  427.26
  4935.1  427.63  4947.5  427.98  4953.1   424.8  4969.6  424.01  4975.2   419.5
  4982.7  420.25  4991.7  419.15  4995.2  416.69  4995.5  416.19  4999.3  416.69
  5013.8  422.06  5019.4  426.86  5027.8   428.3  5041.5  428.13  5056.7  426.82
  5063.1  425.33    5093  426.28  5114.2  425.21  5146.4  426.46  5159.3  425.85
  5177.9  427.28  5198.9   430.4    5265  433.64  5313.6   435.9  5451.2  443.05
#Mann= 7 ,-1 , 0
  4769.7     .05       0  4788.1     .16       0  4935.1     .12       0
  4995.2     .07       0  4999.3     .12       0    5265     .05       0
  5313.6      .1       0
Bank Sta=4969.6,5019.4
XS Rating Curve= 0 ,0
Exp/Cntr=0.3,0.1

Type RM Length L Ch R = 1 ,26240   ,350,350,350
BEGIN DESCRIPTION:
NORTH MINERAL CR TRIB 8 42 0
END DESCRIPTION:
XS GIS Cut Line= 3
      3496644.43     10398652.87      3496449.32     10398500.18
       3496048.3     10398326.93
#Sta/Elev= 30
  4567.9  431.07  4592.1  431.34    4658  429.78    4709  429.09  4828.7  428.07
  4856.2  426.66  4873.8  426.99  4879.2  425.84  4897.3  423.94  4920.8  422.98
  4926.2   422.3  4949.7  423.38  4955.2  421.88  4973.2  421.68  4978.7  419.65
  4986.9  419.92  4996.7  418.85  5002.2  417.57  5006.7   417.4  5006.9   416.9
  5010.5   416.9  5010.8   417.4  5019.6  418.46  5025.7  421.51  5031.1  425.44
  5049.2  428.88  5146.2  432.77  5154.1  432.67  5177.6  434.48  5252.5  438.67
#Mann= 7 ,-1 , 0
  4567.9     .05       0    4658     .16       0    4709     .05       0
  4828.7     .12       0  5006.7     .07       0  5010.8     .12       0
  5146.2      .1       0
Bank Sta=4949.7,5031.1
XS Rating Curve= 0 ,0
Exp/Cntr=0.3,0.1

Type RM Length L Ch R = 1 ,25890   ,223,223,223
BEGIN DESCRIPTION:
NORTH MINERAL CR TRIB 8 41 0
END DESCRIPTION:
XS GIS Cut Line= 3
      3496919.41     10398160.92      3496542.62     10398234.83
       3496102.8      10398033.7
#Sta/Elev= 30
  4518.1  432.17  4593.6  431.11  4695.1  430.98  4766.6  431.17  4790.5   431.5
  4801.1  430.81  4858.2   428.8  4863.2  429.41  4892.4  428.87  4935.6  427.11
    4955  427.69    4972  425.45  4979.6  420.37  4989.5  416.64  4999.2  415.16
  4999.5  414.66  5004.1  415.16  5012.5   420.3  5023.6  422.15  5069.6  421.16
  5078.6   421.8  5087.1  425.04  5092.6  425.21  5100.6  426.75  5138.6  426.76
  5208.7  432.86  5243.1  435.36  5282.2  438.45  5324.8  439.96  5385.7  444.01
#Mann= 11 ,-1 , 0
  4518.1     .05       0  4593.6      .1       0  4695.1     .16       0
  4766.6     .12       0  4801.1     .16       0    4955     .12       0
  4999.2     .07       0  5004.1     .12       0  5208.7     .05       0
  5243.1      .1       0  5324.8     .05       0
Bank Sta=4972,5023.6
XS Rating Curve= 0 ,0
Exp/Cntr=0.3,0.1

Type RM Length L Ch R = 1 ,25667   ,666,666,666
BEGIN DESCRIPTION:
NORTH MINERAL CR TRIB 8 4 0
END DESCRIPTION:
XS GIS Cut Line= 3
      3496736.51     10398105.19      3496492.94     10397994.92
      3496169.42     10397986.43
#Sta/Elev= 30
  4632.2  431.47    4659  432.03  4681.8  430.54  4722.5  429.97  4774.2  428.16
  4779.7   428.5  4825.9  426.64  4834.6  425.69  4856.6   425.3  4889.5  426.15
  4950.4  426.23  4960.4  424.81  4970.4  420.96  4980.4  419.51  4997.9  415.45
  4998.3  414.95  5002.5  414.95  5002.9  415.45  5010.4  415.83  5020.4  418.95
  5030.4  423.29  5053.5  426.01  5070.5  426.08  5090.5  427.23  5132.8  432.73
  5170.5  438.37  5200.5  440.76  5210.4  439.85  5215.4  438.65  5223.2  439.29
#Mann= 5 ,-1 , 0
  4632.2     .16       0  4997.9     .07       0  5002.9     .16       0
  5053.5     .12       0  5132.8      .1       0
Bank Sta=4960.4,5030.4
XS Rating Curve= 0 ,0
Exp/Cntr=0.3,0.1

Type RM Length L Ch R = 1 ,25001   ,912,912,912
BEGIN DESCRIPTION:
NORTH MINERAL CR TRIB 8 39 0
END DESCRIPTION:
XS GIS Cut Line= 3
      3497056.35     10397997.33      3496496.58     10397687.15
      3496246.39      10397652.1
#Sta/Elev= 30
  4459.7  435.09  4466.8   434.3  4533.1  431.77  4541.3  432.51    4556  432.32
    4636  429.46  4687.9  428.74  4774.8  426.86  4899.6  422.98  4921.9  424.21
  4967.6  423.05  4978.1  420.23  4980.8  419.64  4994.4  412.85  4994.8  412.35
  4999.4  412.85  5018.6  419.02  5062.1  420.98  5078.1  424.48  5099.4   426.9
  5114.3  427.72  5154.7  428.17  5172.6   429.5  5177.7  427.75  5195.1     431
  5256.5  435.49  5315.4  440.89  5320.4  440.85  5326.3   442.1  5352.3  444.38
#Mann= 7 ,-1 , 0
  4459.7     .05       0  4466.8      .1       0  4687.9     .16       0
  4978.1     .12       0  4994.4     .07       0  4999.4     .12       0
  5256.5     .05       0
Bank Sta=4967.6,5078.1
XS Rating Curve= 0 ,0
Exp/Cntr=0.3,0.1

Type RM Length L Ch R = 1 ,24089   ,422,422,422
BEGIN DESCRIPTION:
NORTH MINERAL CR TRIB 8 38 0
END DESCRIPTION:
XS GIS Cut Line= 3
      3497427.15      10397442.4      3496764.35     10397273.98
      3496409.38     10397374.53
#Sta/Elev= 30
    4520  433.55  4700.6  431.29  4746.7  430.16  4784.8   428.6  4869.5   425.3
    4876  424.57  4932.7  421.14  4937.9  420.79  4946.2  418.95  4951.4  419.13
  4958.5  417.76  4979.2  415.93  4987.2  413.19  4992.3  412.69  4997.3  409.99
  4997.7  409.49    5002  409.49  5002.4  409.99  5010.1   414.1  5020.5  418.13
  5028.1  418.82  5033.3  420.49  5041.1  421.98  5051.4  421.07  5062.1  421.71
  5156.1  422.68  5319.5  425.87  5470.8  428.06  5543.9  429.68  5572.8  430.85
#Mann= 6 ,-1 , 0
    4520      .1       0  4784.8     .16       0  4932.7     .12       0
  4997.3     .07       0  5002.4     .12       0  5062.1     .05       0
Bank Sta=4951.4,5020.5
XS Rating Curve= 0 ,0
Exp/Cntr=0.3,0.1

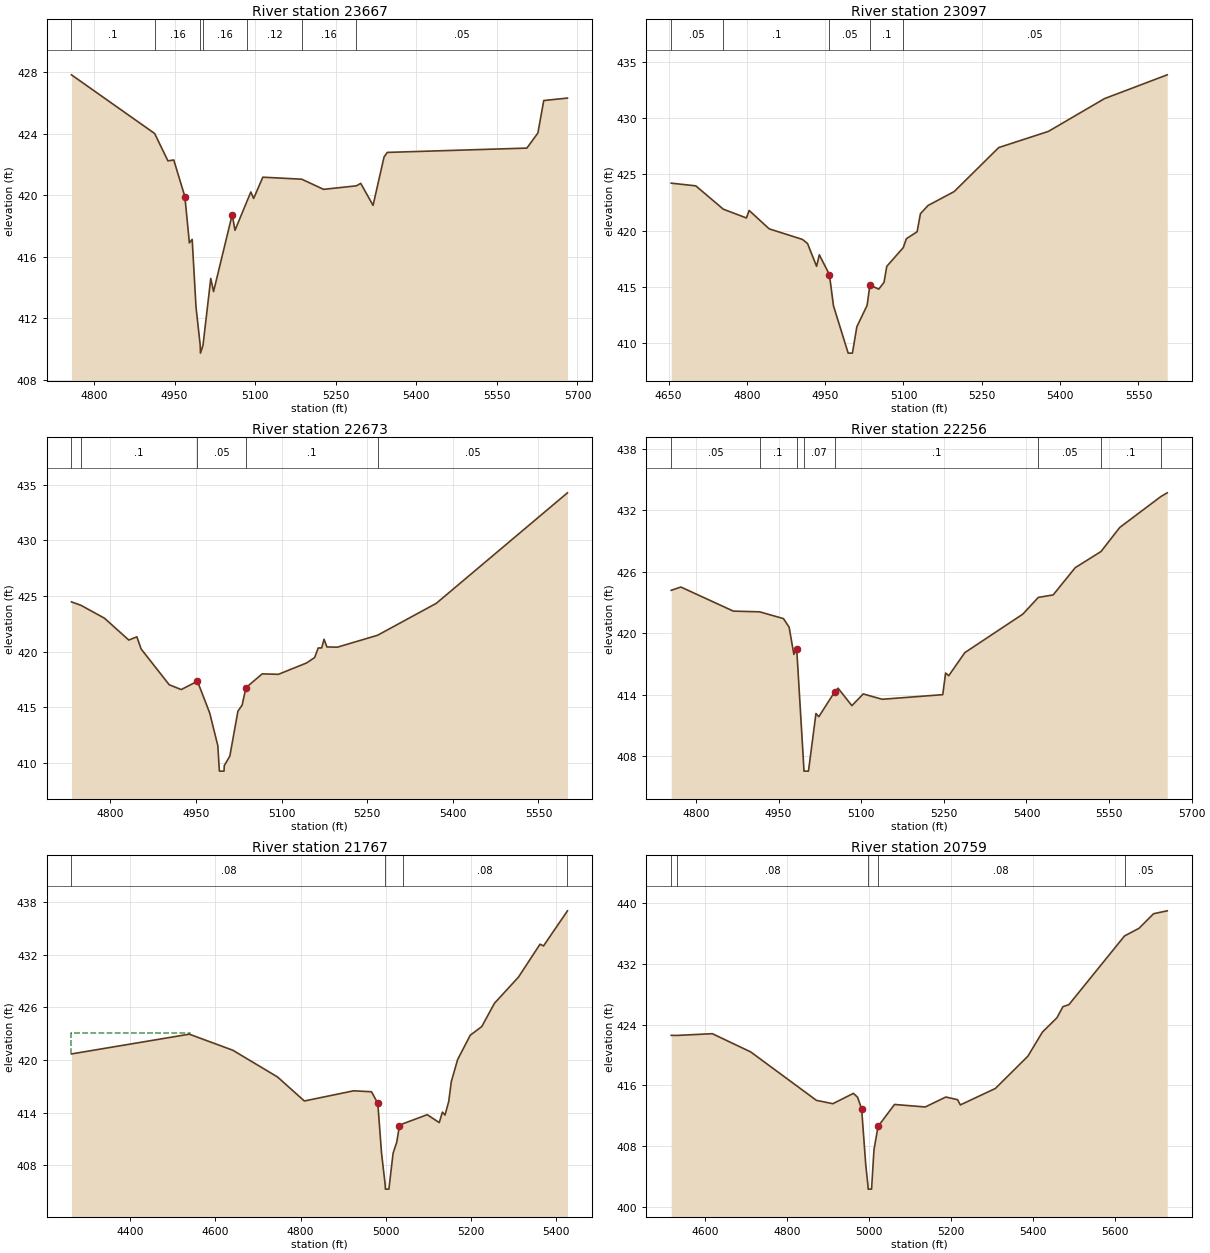
Type RM Length L Ch R = 1 ,23667   ,570,570,570
BEGIN DESCRIPTION:
NORTH MINERAL CR TRIB 8 37 0
END DESCRIPTION:
XS GIS Cut Line= 3
       3497405.9     10397074.83      3497013.13      10396968.5
      3496508.33     10397076.83
#Sta/Elev= 30
  4758.1  427.82  4912.9  424.01  4937.7  422.23  4948.5  422.29  4969.2  419.91
  4977.6   416.9  4982.8  417.13  4989.9  412.75  4997.8  410.24  4998.2  409.74
  5002.9  410.24  5017.4  414.59  5022.6  413.74  5057.3  418.74  5062.5  417.72
  5085.3  419.65    5092  420.21  5097.2  419.79  5114.3  421.17  5186.7  421.04
  5227.4  420.38  5288.6  420.61  5296.5  420.77  5319.5  419.34  5339.9  422.48
  5345.9  422.78  5605.8  423.06  5626.3  424.04  5637.2  426.15  5681.3  426.31
#Mann= 7 ,-1 , 0
  4758.1      .1       0  4912.9     .16       0  4997.8     .07       0
  5002.9     .16       0  5085.3     .12       0  5186.7     .16       0
  5288.6     .05       0
Bank Sta=4969.2,5057.3
XS Rating Curve= 0 ,0
Exp/Cntr=0.3,0.1

Type RM Length L Ch R = 1 ,23097   ,424,424,424
BEGIN DESCRIPTION:
NORTH MINERAL CR TRIB 8 56 0
END DESCRIPTION:
XS GIS Cut Line= 3
      3497520.98      10396671.2       3496993.6     10396504.09
      3496661.55     10396287.07
#Sta/Elev= 30
  4655.2  424.22  4702.3  423.98    4755   421.9  4799.2  421.12  4804.4  421.79
  4842.8  420.15  4906.5  419.21  4916.3  418.84  4933.6  416.81  4938.8  417.84
  4958.2  416.07  4965.9   413.3  4994.1  409.08  5002.2  409.08  5010.7  411.43
  5030.4  413.34  5035.7  415.15  5052.6  414.78  5062.7  415.38    5068  416.81
  5099.6  418.48  5105.5  419.27  5126.1  419.89  5132.5   421.5    5147  422.23
  5197.1  423.47  5282.4  427.39  5377.5  428.83    5485  431.75  5605.1  433.87
#Mann= 5 ,-1 , 0
  4655.2     .05       0    4755      .1       0  4958.2     .05       0
  5035.7      .1       0  5099.6     .05       0
Bank Sta=4958.2,5035.7
XS Rating Curve= 0 ,0
Exp/Cntr=0.3,0.1

Type RM Length L Ch R = 1 ,22673   ,417,417,417
BEGIN DESCRIPTION:
NORTH MINERAL CR TRIB 8 36 0
END DESCRIPTION:
XS GIS Cut Line= 3
      3497642.45     10396443.31      3497321.29     10396148.19
      3496896.56     10396065.84
#Sta/Elev= 30
    4732  424.47  4748.7  424.16  4789.9     423  4832.4  421.04  4846.6  421.33
    4854  420.24  4903.3  417.02  4924.3  416.59  4952.7  417.34  4974.2  414.48
  4988.4  411.54  4991.1  409.26  4999.2  409.26  4999.7  409.76  5009.4  410.61
  5023.6  414.65  5030.9  415.19  5037.7  416.76  5066.1     418  5094.5  417.96
  5143.8  418.98    5158  419.47  5164.2  420.33  5170.3  420.33  5174.4  421.11
  5179.5  420.42  5197.9   420.4  5268.2  421.47  5371.1  424.34  5600.8  434.27
#Mann= 5 ,-1 , 0
    4732     .05       0  4748.7      .1       0  4952.7     .05       0
  5037.7      .1       0  5268.2     .05       0
Bank Sta=4952.7,5037.7
XS Rating Curve= 0 ,0
Exp/Cntr=0.3,0.1

Type RM Length L Ch R = 1 ,22256   ,489,489,489
BEGIN DESCRIPTION:
NORTH MINERAL CR TRIB 8 35 1
END DESCRIPTION:
XS GIS Cut Line= 2
      3497878.98     10396004.95      3497008.83     10395772.77
#Sta/Elev= 30
    4755  424.18  4772.5   424.5  4867.8  422.15  4915.6  422.08  4958.8  421.42
  4969.1  420.58  4977.7  417.93  4982.9  418.43  4995.6  407.04  4996.1  406.54
  5004.2  406.54  5017.8  412.16    5023  411.85  5051.9  414.28  5057.9  414.63
    5083  412.93  5103.7  414.07  5138.1  413.55    5248     414  5253.2  416.11
  5258.9  415.85  5288.1   418.1  5393.5  421.86  5421.6  423.49  5448.5  423.73
  5488.6  426.39  5535.5  427.97  5569.4  430.31  5643.9  433.32  5655.6  433.69
#Mann= 8 ,-1 , 0
    4755     .05       0  4915.6      .1       0  4982.9     .05       0
  4995.6     .07       0  5051.9      .1       0  5421.6     .05       0
  5535.5      .1       0  5643.9     .05       0
Bank Sta=4982.9,5051.9
XS Rating Curve= 0 ,0
Exp/Cntr=0.3,0.1

Type RM Length L Ch R = 1 ,21767   ,1008,1008,1008
BEGIN DESCRIPTION:
NORTH MINERAL CR TRIB 8 34 0
END DESCRIPTION:
XS GIS Cut Line= 3
      3497967.99     10396187.27       3497931.1      10395740.2
      3497346.11     10395328.54
#Sta/Elev= 30
  4262.4  420.69    4539  422.94  4641.1  421.11  4746.1  418.06  4808.9  415.33
  4924.7  416.49  4966.5  416.38  4981.3  415.06    4990  409.41  4998.6  405.79
  4999.1  405.29  5007.3  405.29  5017.1  409.37  5025.8  410.65  5031.9  412.47
  5039.9  412.73  5097.2  413.77  5125.5  412.87  5132.9  414.06    5139  413.73
  5147.7  415.28  5153.8  417.54  5168.6  420.05  5198.2  422.82  5225.3  423.81
  5254.9  426.45  5311.5  429.45    5362  433.19  5370.1  432.99  5426.3  436.99
#Mann= 4 ,-1 , 0
  4262.4     .08       0  4998.6     .05       0  5039.9     .08       0
  5426.3     .16       0
#XS Ineff= 2 , 0
         4540.78  423.05
Permanent Ineff=
       F       F
Bank Sta=4981.3,5031.9
XS Rating Curve= 0 ,0
Exp/Cntr=0.3,0.1

Type RM Length L Ch R = 1 ,20759   ,325,325,325
BEGIN DESCRIPTION:
NORTH MINERAL CR TRIB 8 32 0
END DESCRIPTION:
XS GIS Cut Line= 3
      3498304.36     10395955.05      3498263.13     10395377.79
      3497886.33     10394871.06
#Sta/Elev= 30
  4517.2  422.58  4530.6  422.57  4617.5   422.8  4711.1   420.4  4871.5  414.02
  4911.6  413.58  4961.7  414.94  4971.8  414.44  4981.8  412.91  4991.8  405.56
  4997.2  402.83  4997.7  402.33    5006  402.33  5011.9  407.51  5021.9  410.59
    5062  413.48  5137.1  413.15  5187.2  414.46  5215.8  414.11  5222.7  413.42
  5308.2  415.59  5387.5  419.84  5422.9  423.01  5458.4   424.9    5473  426.36
  5487.6  426.63  5623.2  435.67  5658.6  436.68  5694.1   438.6  5727.4  438.98
#Mann= 5 ,-1 , 0
  4517.2     .05       0  4530.6     .08       0  4997.2     .05       0
  5021.9     .08       0  5623.2     .05       0
Bank Sta=4981.8,5021.9
XS Rating Curve= 0 ,0
Exp/Cntr=0.3,0.1

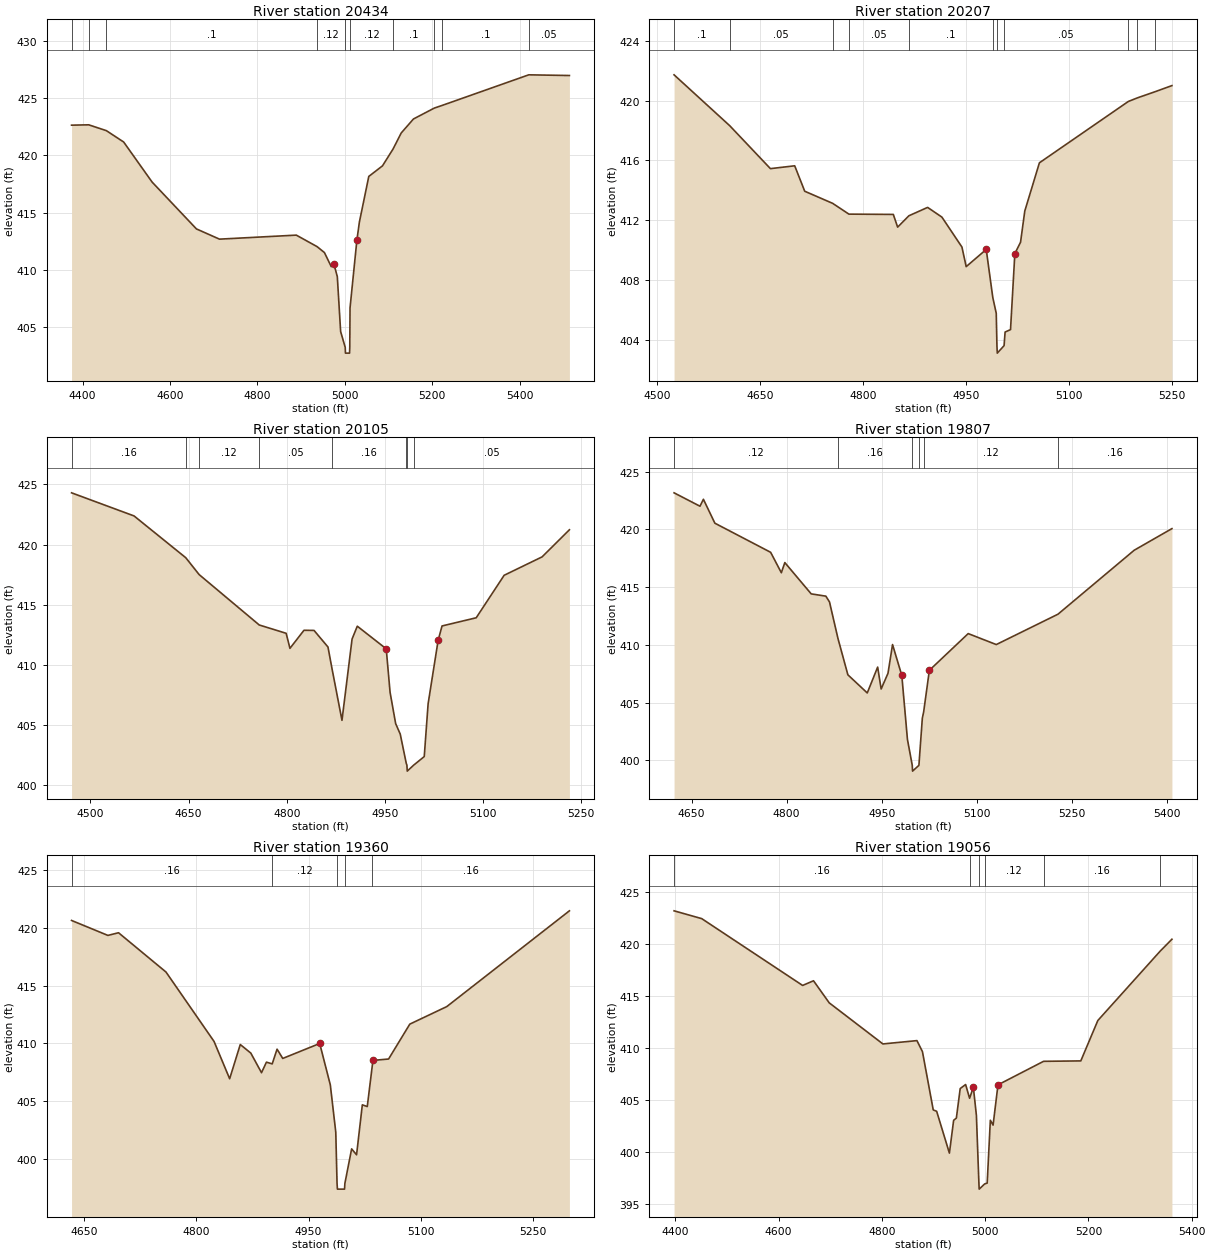
Type RM Length L Ch R = 1 ,20434   ,227,227,227
BEGIN DESCRIPTION:
NORTH MINERAL CR TRIB 8 29 4
END DESCRIPTION:
XS GIS Cut Line= 4
      3498321.72     10395900.78      3498317.11     10395716.64
      3498660.26     10395134.73      3498664.59     10394855.72
#Sta/Elev= 30
  4374.7  422.62    4414  422.65  4454.4  422.14  4493.9  421.15  4558.9  417.66
  4660.4  413.57  4713.1  412.68  4888.8  413.03  4936.2  412.03  4953.1  411.51
  4968.8  410.28  4974.6  410.55  4982.6  409.41  4990.2  404.62  5000.7  403.24
  5001.2  402.74  5010.6  402.74  5011.1  403.24  5011.7  406.68  5027.3  412.57
  5033.1  414.17  5054.6  418.15  5085.9  419.07  5110.1  420.54  5128.8  421.94
  5156.8  423.16  5204.5  424.11  5221.5  424.33  5420.6  427.01  5513.5  426.95
#Mann= 10 ,-1 , 0
  4374.7      .1       0    4414     .05       0  4454.4      .1       0
  4936.2     .12       0  5000.7     .07       0  5011.1     .12       0
  5110.1      .1       0  5204.5     .05       0  5221.5      .1       0
  5420.6     .05       0
Bank Sta=4974.6,5027.3
XS Rating Curve= 0 ,0
Exp/Cntr=0.3,0.1

Type RM Length L Ch R = 1 ,20207   ,102,102,102
BEGIN DESCRIPTION:
NORTH MINERAL CR TRIB 8 29 2
END DESCRIPTION:
XS GIS Cut Line= 3
      3498371.62     10395907.33      3498705.84     10395462.43
      3498742.74     10395297.46
#Sta/Elev= 30
  4524.5  421.72  4605.6  418.32  4664.9  415.45  4700.3  415.64  4714.9  413.94
  4755.6  413.13  4779.3  412.41    4844  412.39  4850.3  411.54  4866.7   412.3
    4894  412.86  4914.8  412.21    4944  410.21  4950.2   408.9  4979.4  410.05
    4989  406.83    4994  405.78    4995  403.62  4995.5  403.12  5005.4  403.62
  5006.9  404.53  5014.8  404.69  5021.1  409.77  5029.4  410.53  5035.6  412.62
  5056.9  415.84  5186.5  419.94  5199.7  420.18    5226   420.6    5250     421
#Mann= 11 ,-1 , 0
  4524.5      .1       0  4605.6     .05       0  4755.6      .1       0
  4779.3     .05       0  4866.7      .1       0    4989     .05       0
    4995     .04       0  5005.4     .05       0  5186.5      .1       0
  5199.7     .12       0    5226      .1       0
Bank Sta=4979.4,5021.1
XS Rating Curve= 0 ,0
Exp/Cntr=0.3,0.1

Type RM Length L Ch R = 1 ,20105   ,298,298,298
BEGIN DESCRIPTION:
NORTH MINERAL CR TRIB 8 3 0
END DESCRIPTION:
XS GIS Cut Line= 2
      3498415.04      10396074.4      3498811.18     10395424.99
#Sta/Elev= 30
  4471.2   424.3  4566.7  422.38  4645.7  418.91  4666.1  417.51    4758  413.32
  4799.1  412.63  4804.9  411.38  4826.3  412.88  4841.7  412.87    4863  411.49
  4869.1  409.71  4884.4   405.4  4899.8  412.15  4907.8  413.22    4952  411.34
  4957.9  407.72  4966.4  405.13  4973.4  404.26  4982.6  401.83  4983.6  401.68
  4984.1  401.18    4994  401.68  5010.1  402.39    5016  406.77  5031.4  412.07
  5037.3  413.24  5089.5  413.92  5132.2  417.45  5190.2  418.98  5231.9  421.23
#Mann= 8 ,-1 , 0
  4471.2     .16       0  4645.7     .05       0  4666.1     .12       0
    4758     .05       0  4869.1     .16       0  4982.6     .05       0
  4983.6     .04       0    4994     .05       0
Bank Sta=4952,5031.4
XS Rating Curve= 0 ,0
Exp/Cntr=0.3,0.1

Type RM Length L Ch R = 1 ,19807   ,447,447,447
BEGIN DESCRIPTION:
NORTH MINERAL CR TRIB 8 36 1
END DESCRIPTION:
XS GIS Cut Line= 3
      3498679.79     10396191.61      3498864.26     10395764.07
      3498818.69     10395447.27
#Sta/Elev= 30
  4622.3  423.16  4663.2     422  4668.6   422.6  4686.7  420.53  4774.7  418.01
  4791.6  416.24  4797.1  417.12  4838.7  414.41  4861.9  414.21  4867.6  413.71
  4880.9  410.56  4896.6   407.4  4927.2  405.83  4943.6  408.07  4949.1  406.17
  4959.9  407.53  4967.1  410.02  4981.7  407.35  4990.6  401.81  4998.2  399.56
  4998.7  399.06  5008.7  399.56  5014.1  403.64  5016.2  404.19  5025.2  407.79
  5086.5  410.97  5130.8  410.02  5228.2  412.65  5348.5  418.19    5408  420.06
#Mann= 6 ,-1 , 0
  4622.3     .12       0  4880.9     .16       0  4998.2     .07       0
  5008.7     .16       0  5016.2     .12       0  5228.2     .16       0
Bank Sta=4981.7,5025.2
XS Rating Curve= 0 ,0
Exp/Cntr=0.3,0.1

Type RM Length L Ch R = 1 ,19360   ,304,304,304
BEGIN DESCRIPTION:
NORTH MINERAL CR TRIB 8 29 1
END DESCRIPTION:
XS GIS Cut Line= 4
      3499293.53     10395888.92      3499119.07     10395730.08
      3498975.84     10395566.02      3498819.58     10395422.78
#Sta/Elev= 30
  4633.1  420.61  4681.7  419.32  4695.9  419.55  4759.4  416.16  4823.6  410.18
  4844.5  406.96  4858.7  409.91  4872.8  409.17  4887.1  407.48  4893.7  408.39
  4901.4  408.24  4907.9  409.51  4915.5  408.71  4964.9     410  4979.1  406.43
  4986.4  402.35  4988.1  397.94  4988.6  397.44  4998.1  397.44  4998.6  397.94
  5007.6  400.91  5014.2   400.4  5021.9  404.71  5028.5  404.56  5034.7  407.81
  5036.1  408.54    5057  408.66  5085.4  411.67  5134.8  413.18  5298.8  421.44
#Mann= 5 ,-1 , 0
  4633.1     .16       0  4901.4     .12       0  4988.1     .07       0
  4998.6     .12       0  5034.7     .16       0
Bank Sta=4964.9,5036.1
XS Rating Curve= 0 ,0
Exp/Cntr=0.3,0.1

Type RM Length L Ch R = 1 ,19056   ,334,334,334
BEGIN DESCRIPTION:
NORTH MINERAL CR TRIB 8 29 0
END DESCRIPTION:
XS GIS Cut Line= 3
      3499757.14     10395701.01      3499501.07     10395536.09
       3498869.6     10395345.13
#Sta/Elev= 30
  4397.5  423.15  4451.1   422.4  4646.5  415.98  4667.6  416.43    4698  414.31
    4802  410.36  4867.9  410.68  4878.6  409.62  4899.5  404.02  4906.1  403.89
  4930.8  399.87    4939  403.02  4944.3  403.24  4951.7  406.07  4962.2  406.46
  4969.9  405.14  4977.2  406.19  4983.1  403.49    4988  396.91  4988.5  396.41
  4999.1  396.91    5004  396.99  5010.1  403.03  5015.4  402.56  5024.9  406.43
  5113.2  408.69  5185.3  408.73  5218.3  412.61  5339.1  419.28  5361.8  420.42
#Mann= 6 ,-1 , 0
  4397.5     .16       0  4969.9     .12       0    4988     .07       0
  4999.1     .12       0  5113.2     .16       0  5339.1     .05       0
Bank Sta=4977.2,5024.9
XS Rating Curve= 0 ,0
Exp/Cntr=0.3,0.1