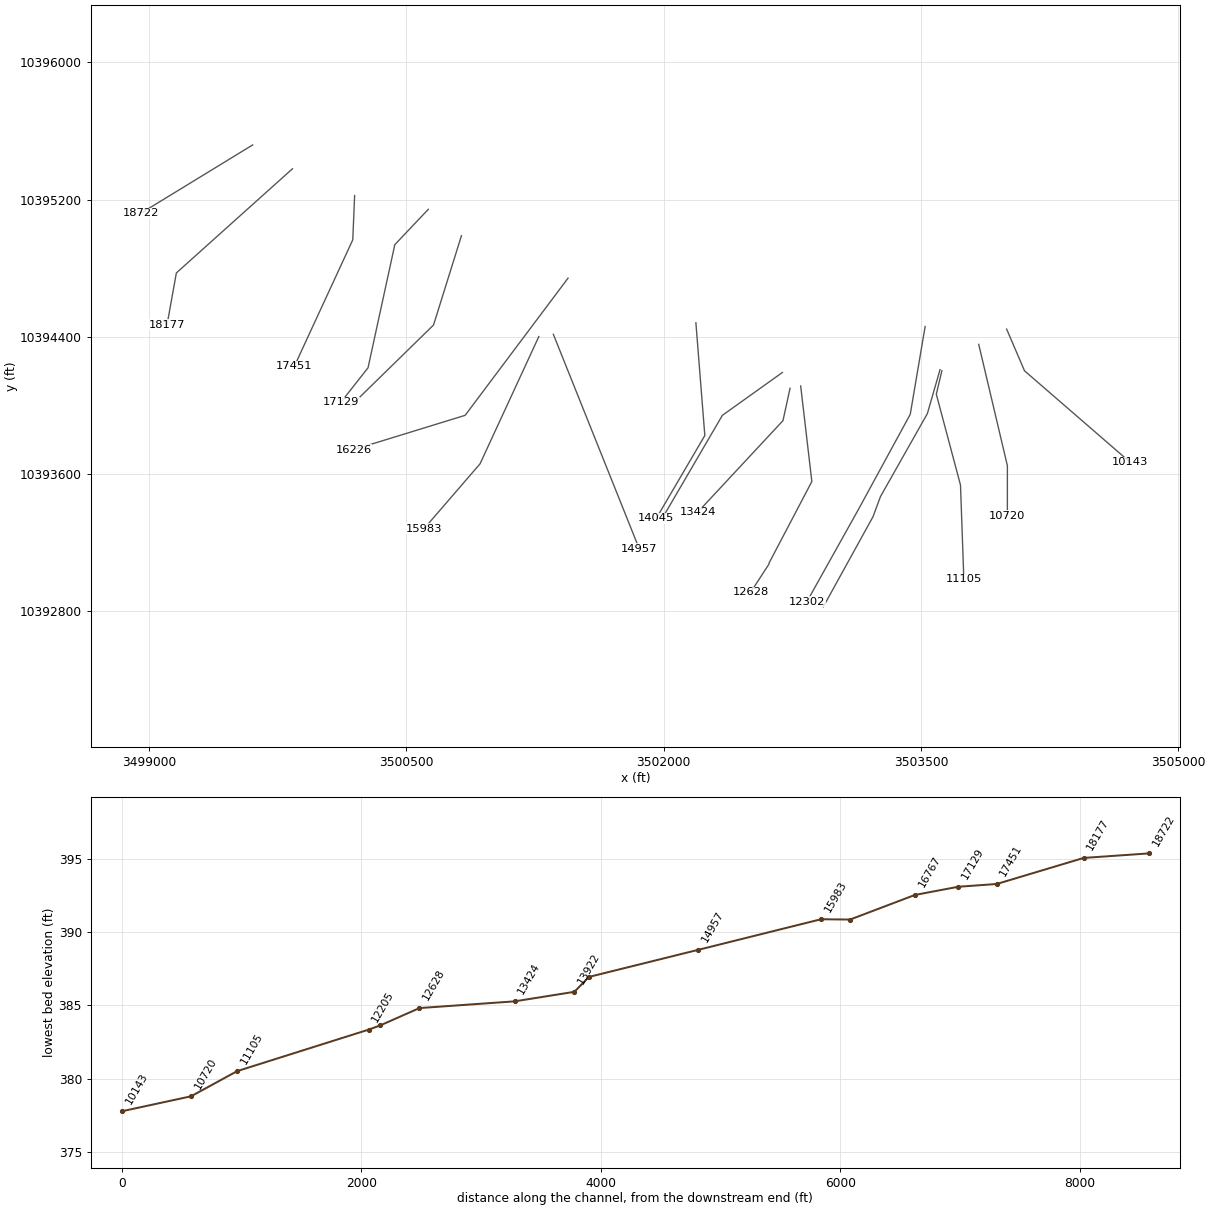
HEC-RAS study NORTH MINERAL CR TRIB 8.prj: NORTH MINERAL CR TRIB 8 Base Level Engineering

--- NORTH MINERAL CR TRIB 8.g01 (geometry) --- (continued)

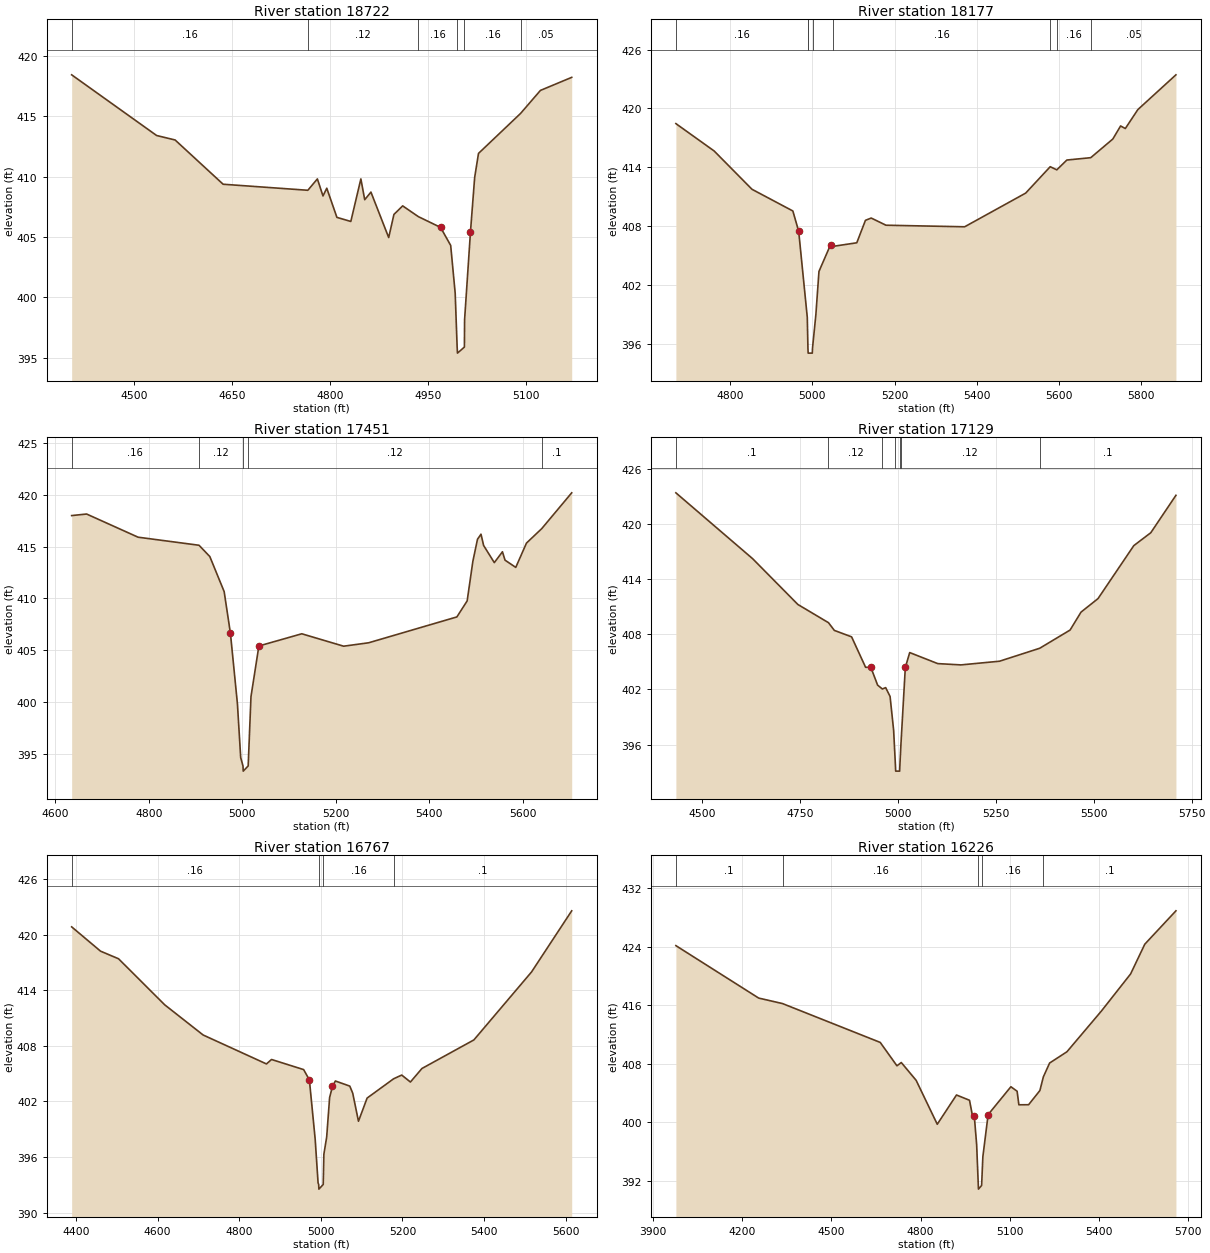
Type RM Length L Ch R = 1 ,18722   ,545,545,545
BEGIN DESCRIPTION:
NORTH MINERAL CR TRIB 8 28 0
END DESCRIPTION:
XS GIS Cut Line= 2
      3499603.09     10395518.74      3498949.87     10395119.43
#Sta/Elev= 30
  4404.1  418.41  4534.2  413.39  4562.5  413.02    4636  409.36  4765.7  408.86
  4780.3   409.8  4788.9  408.39  4794.7  409.03  4810.2  406.62  4831.5  406.28
  4846.9   409.8  4852.8  408.08  4862.3  408.71  4889.5  404.95  4897.5  406.86
  4910.9  407.57  4934.9  406.68  4968.9  405.79  4984.4   404.3  4991.3  400.35
  4994.3  395.89  4994.8  395.39  5005.4  395.89  5005.7  398.15  5014.7  405.42
  5021.1  409.91    5027  411.91  5091.3  415.21  5121.8  417.12  5169.7   418.2
#Mann= 6 ,-1 , 0
  4404.1     .16       0  4765.7     .12       0  4934.9     .16       0
  4994.3     .07       0  5005.4     .16       0  5091.3     .05       0
Bank Sta=4968.9,5014.7
XS Rating Curve= 0 ,0
Exp/Cntr=0.3,0.1

Type RM Length L Ch R = 1 ,18177   ,726,726,726
BEGIN DESCRIPTION:
NORTH MINERAL CR TRIB 8 27 0
END DESCRIPTION:
XS GIS Cut Line= 3
      3499835.29     10395379.85      3499158.19      10394772.2
      3499103.93     10394470.52
#Sta/Elev= 30
  4668.1  418.46  4761.2  415.67  4853.2  411.77  4952.6  409.56  4966.8  407.49
  4987.7  398.72  4988.5  397.15  4989.3  395.58  4989.8  395.08  4999.9  395.08
  5000.4  395.58  5008.6  399.01  5016.1   403.4  5044.5  406.14  5049.2  405.95
  5108.1  406.32  5129.2  408.61  5143.2  408.84  5179.1  408.11  5370.5  407.95
  5518.9  411.38  5578.6  414.07  5594.6  413.75  5619.1  414.75  5677.2  414.99
  5730.9  416.89  5749.8  418.22  5761.3  417.96  5791.8  419.89  5884.4  423.43
#Mann= 8 ,-1 , 0
  4668.1     .16       0  4988.5     .12       0  4989.3     .07       0
  5000.4     .12       0  5049.2     .16       0  5578.6     .05       0
  5594.6     .16       0  5677.2     .05       0
Bank Sta=4966.8,5044.5
XS Rating Curve= 0 ,0
Exp/Cntr=0.3,0.1

Type RM Length L Ch R = 1 ,17451   ,322,322,322
BEGIN DESCRIPTION:
NORTH MINERAL CR TRIB 8 26 0
END DESCRIPTION:
XS GIS Cut Line= 3
      3500197.69     10395223.59      3500186.84     10394965.34
      3499846.62     10394228.58
#Sta/Elev= 30
  4634.6  418.01  4666.6  418.16  4776.7  415.92  4907.1  415.14  4930.2  414.05
  4960.9  410.66  4974.3  406.64  4989.3  399.81  4996.3  394.61  5001.2   393.8
  5001.7   393.3  5012.3   393.8  5018.3   400.5  5035.2   405.4    5127  406.58
  5216.6  405.38  5270.1  405.71  5458.9  408.21  5480.9  409.76  5493.1  413.59
    5503  415.72  5510.5  416.21  5516.1  415.12    5539  413.46  5556.4  414.51
  5561.9   413.7  5584.9     413  5607.8  415.35  5640.5  416.75  5704.6  420.21
#Mann= 5 ,-1 , 0
  4634.6     .16       0  4907.1     .12       0  5001.2     .07       0
  5012.3     .12       0  5640.5      .1       0
#XS Ineff= 2 , 0
                          5509.3          415.75
Permanent Ineff=
       F       F
Bank Sta=4974.3,5035.2
XS Rating Curve= 0 ,0
Exp/Cntr=0.3,0.1

Type RM Length L Ch R = 1 ,17129   ,362,362,362
BEGIN DESCRIPTION:
NORTH MINERAL CR TRIB 8 25 0
END DESCRIPTION:
XS GIS Cut Line= 4
      3500627.41     10395143.33      3500432.06     10394937.13
      3500275.81     10394218.82      3500116.88     10394016.92
#Sta/Elev= 30
  4433.8  423.37  4629.6  416.21  4745.1  411.23  4823.2  409.25  4838.2  408.41
  4882.2  407.71  4917.9   404.4  4931.3   404.4  4948.6  402.46  4960.8  402.04
  4969.1  402.19  4980.4  401.23  4989.5  397.54  4994.2  393.61  4994.7  393.11
  5004.8  393.11  5005.3  393.61    5008  395.94  5019.3  404.38  5030.5     406
  5102.1   404.8  5161.5  404.66  5259.7  405.06  5362.3  406.47  5439.8  408.45
  5467.7   410.4  5511.1  411.87  5602.4  417.63  5645.7  419.03  5709.9   423.1
#Mann= 7 ,-1 , 0
  4433.8      .1       0  4823.2     .12       0  4960.8     .16       0
  4994.2     .07       0  5005.3     .16       0    5008     .12       0
  5362.3      .1       0
Bank Sta=4931.3,5019.3
XS Rating Curve= 0 ,0
Exp/Cntr=0.3,0.1

Type RM Length L Ch R = 1 ,16767   ,541,541,541
BEGIN DESCRIPTION:
NORTH MINERAL CR TRIB 8 24 0
END DESCRIPTION:
XS GIS Cut Line= 3
      3500820.51     10394989.17      3500657.76     10394468.38
      3500171.62      10393993.1
#Sta/Elev= 30
  4389.4  420.83  4460.2  418.21  4504.3  417.39  4617.3  412.43  4711.6  409.17
  4866.8  406.05  4879.2  406.53  4957.9  405.44    4972  404.33  4986.2  397.93
  4993.3  393.23  4994.8  393.05  4995.3  392.55  5005.9  393.05  5007.5  396.31
  5014.4  398.17  5021.6  402.43  5028.6  403.63  5035.7  404.21    5071  403.66
  5078.2   402.9  5092.3  399.87  5113.5  402.37  5178.5  404.45  5198.3  404.85
  5219.6   404.1  5247.9  405.56  5375.2  408.64  5516.5  415.97  5614.9  422.56
#Mann= 4 ,-1 , 0
  4389.4     .16       0  4994.8     .07       0  5005.9     .16       0
  5178.5      .1       0
Bank Sta=4972,5028.6
XS Rating Curve= 0 ,0
Exp/Cntr=0.3,0.1

Type RM Length L Ch R = 1 ,16226   ,243,243,243
BEGIN DESCRIPTION:
NORTH MINERAL CR TRIB 8 23 1
END DESCRIPTION:
XS GIS Cut Line= 3
      3501442.13     10394741.68      3500842.11     10393941.64
      3500192.12     10393741.65
#Sta/Elev= 30
  3977.9  424.16  4256.1  416.99  4336.1  416.24  4664.4  410.93  4720.7  407.73
  4735.2  408.18  4785.2  405.74  4856.1  399.74  4920.7  403.74  4964.4  403.02
  4974.8  400.82  4980.6  400.82  4988.4  396.98    4994  391.37  4994.5  390.87
  5005.1  391.37  5009.3   395.3    5027  401.06  5103.5  404.87  5124.4  404.25
  5130.3   402.4    5163  402.41  5200.9  404.35  5212.5  406.21  5233.6  408.11
  5291.8  409.65  5407.6  415.22  5505.7  420.29  5553.4  424.36    5658  428.92
#Mann= 5 ,-1 , 0
  3977.9      .1       0  4336.1     .16       0    4994     .07       0
  5005.1     .16       0  5212.5      .1       0
Bank Sta=4980.6,5027
XS Rating Curve= 0 ,0
Exp/Cntr=0.3,0.1

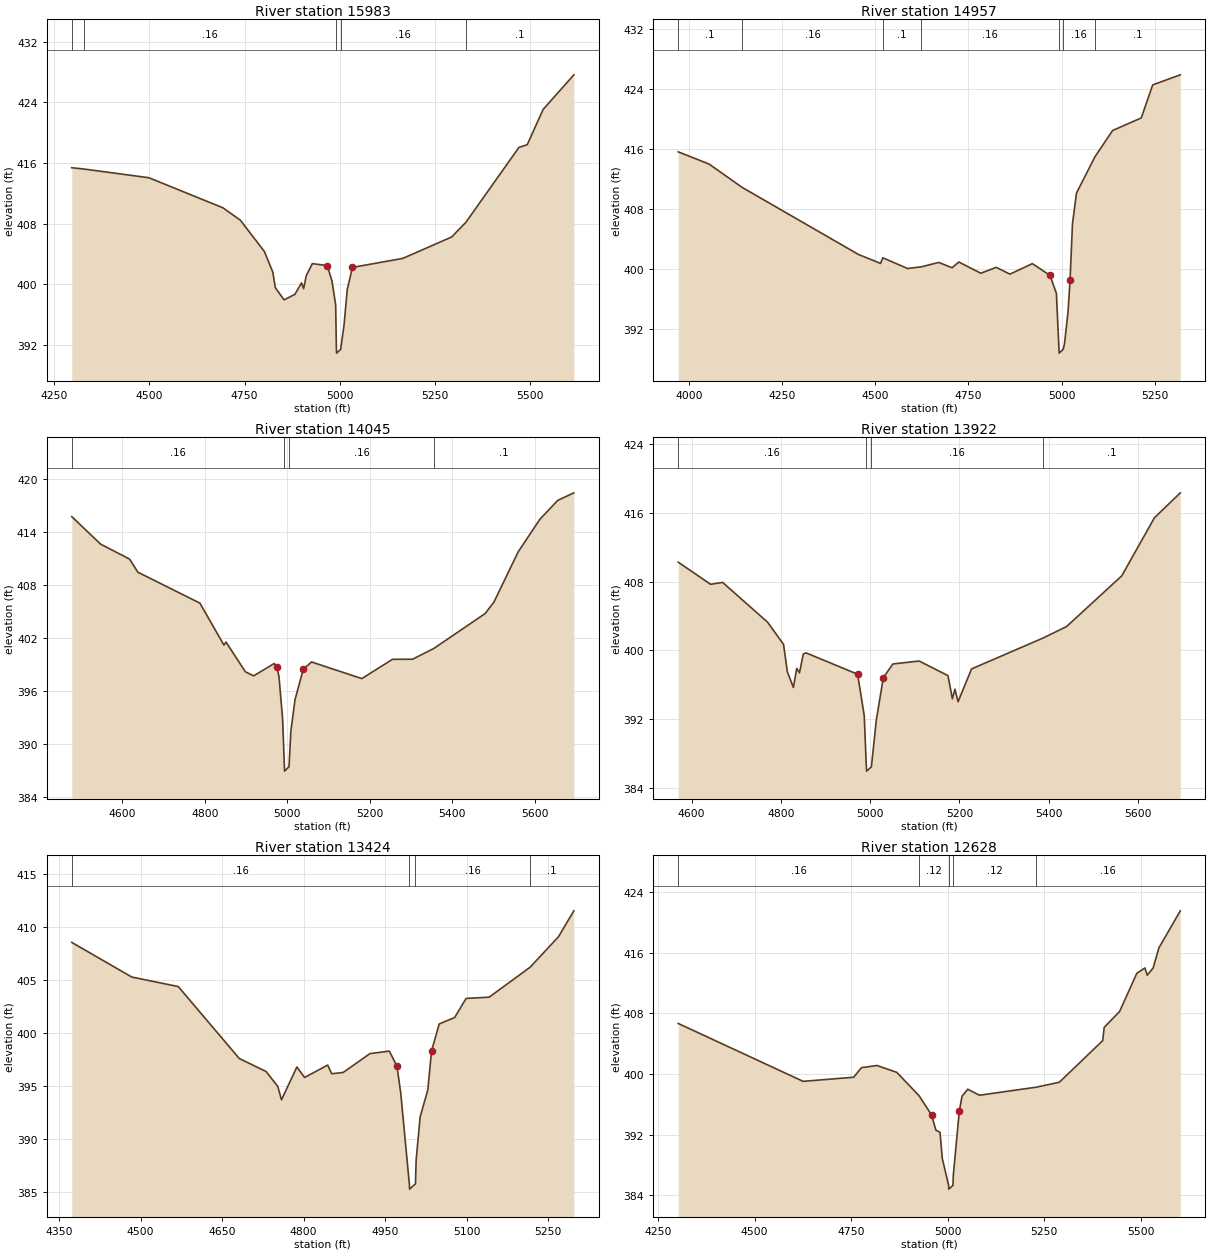
Type RM Length L Ch R = 1 ,15983   ,1026,1026,1026
BEGIN DESCRIPTION:
NORTH MINERAL CR TRIB 8 22 0
END DESCRIPTION:
XS GIS Cut Line= 3
      3501271.92     10394401.13      3500929.03     10393658.92
      3500601.33     10393279.14
#Sta/Elev= 30
    4296  415.37  4328.1   415.2  4498.7  414.05  4693.2  410.08  4739.1  408.44
  4802.1  404.31  4824.2  401.59  4830.9  399.54  4853.8  397.92  4882.2  398.65
  4899.7  400.16  4905.2   399.4  4912.3  401.14  4928.1  402.71  4967.4  402.45
  4979.5  400.45  4989.4  397.27  4991.3  391.39  4991.8  390.89  5002.5  391.39
  5011.4   394.6  5019.9   399.3  5033.5  402.21  5165.9   403.4  5294.3  406.23
  5331.8  408.18  5470.9  418.05  5492.8  418.42  5534.5  423.07  5615.2  427.64
#Mann= 5 ,-1 , 0
    4296      .1       0  4328.1     .16       0  4991.3     .07       0
  5002.5     .16       0  5331.8      .1       0
Bank Sta=4967.4,5033.5
XS Rating Curve= 0 ,0
Exp/Cntr=0.3,0.1

Type RM Length L Ch R = 1 ,14957   ,912,912,912
BEGIN DESCRIPTION:
NORTH MINERAL CR TRIB 8 27
END DESCRIPTION:
XS GIS Cut Line= 2
      3501356.54     10394414.14      3501857.47     10393162.89
#Sta/Elev= 30
  3970.9  415.61  4053.8  413.98  4142.3  410.88  4454.8  401.94  4514.1  400.75
    4520   401.5  4586.7  400.07  4623.8   400.3  4670.2  400.88  4706.1  400.17
    4724  400.94  4783.2  399.44  4824.6  400.23  4861.3  399.32  4921.5  400.72
    4969  399.16  4986.1  396.75    4993   389.3  4993.5   388.8  5004.2   389.3
  5007.7  390.01  5017.4  394.33  5022.8  398.59  5029.2  406.02    5040  410.12
  5089.5  414.95  5136.9  418.45  5213.9  420.13  5244.6  424.53  5318.7  425.87
#Mann= 7 ,-1 , 0
  3970.9      .1       0  4142.3     .16       0    4520      .1       0
  4623.8     .16       0    4993     .07       0  5004.2     .16       0
  5089.5      .1       0
Bank Sta=4969,5022.8
XS Rating Curve= 0 ,0
Exp/Cntr=0.3,0.1

Type RM Length L Ch R = 1 ,14045   ,123,123,123
BEGIN DESCRIPTION:
NORTH MINERAL CR TRIB 8 2 0
END DESCRIPTION:
XS GIS Cut Line= 3
       3502187.7     10394481.43      3502239.79     10393823.85
      3501957.69     10393342.11
#Sta/Elev= 30
  4477.5  415.72  4547.5  412.61  4617.7  410.92  4637.8  409.44  4788.3  405.94
  4846.6   401.2  4851.7  401.54  4898.6  398.18  4918.7  397.72  4968.8  399.12
  4975.2  398.67  4980.2  397.62  4988.9  392.87  4993.3  387.45  4993.8  386.95
  5004.5  387.45  5008.9  391.43    5019  395.02    5039  398.45  5059.1  399.29
  5181.1  397.41  5255.5  399.59  5304.2   399.6  5355.9  400.82  5480.2  404.76
  5501.7  406.07  5560.3  411.73  5613.2  415.43  5656.2  417.55  5695.4  418.41
#Mann= 4 ,-1 , 0
  4477.5     .16       0  4993.3     .07       0  5004.5     .16       0
  5355.9      .1       0
Bank Sta=4975.2,5039
XS Rating Curve= 0 ,0
Exp/Cntr=0.3,0.1

Type RM Length L Ch R = 1 ,13922   ,498,498,498
BEGIN DESCRIPTION:
NORTH MINERAL CR TRIB 8 19 0
END DESCRIPTION:
XS GIS Cut Line= 3
      3502692.08     10394191.62      3502342.11     10393941.64
      3501992.11     10393341.65
#Sta/Elev= 30
  4570.1  410.28  4642.6   407.7  4669.6  407.92  4770.4  403.28    4806   400.7
  4814.6  397.49  4828.1  395.68  4835.5   397.9  4841.7  397.38  4850.3  399.58
  4856.4  399.71  4971.9  397.22  4986.7  392.43  4991.5  386.43    4992  385.93
  5002.8  386.43  5013.8  391.86  5029.5  396.82    5051  398.42  5109.8  398.76
  5174.3  397.06  5184.2  394.36    5190  395.48    5197  394.02  5227.2  397.84
  5387.9  401.45  5440.1  402.78  5563.7  408.69  5636.9  415.46  5694.8  418.36
#Mann= 4 ,-1 , 0
  4570.1     .16       0  4991.5     .07       0  5002.8     .16       0
  5387.9      .1       0
Bank Sta=4971.9,5029.5
XS Rating Curve= 0 ,0
Exp/Cntr=0.3,0.1

Type RM Length L Ch R = 1 ,13424   ,796,796,796
BEGIN DESCRIPTION:
NORTH MINERAL CR TRIB 8 18 0
END DESCRIPTION:
XS GIS Cut Line= 3
      3502736.76     10394099.51      3502695.52     10393910.66
       3502197.7     10393376.05
#Sta/Elev= 30
  4373.5  408.57  4483.9   405.3  4569.5   404.4  4681.7  397.61  4731.1  396.38
  4752.6  394.97  4759.4  393.71  4787.7  396.81  4801.9  395.82  4844.4  396.99
  4851.8  396.17  4872.8  396.29  4922.1  398.07  4957.8  398.31  4971.9  396.88
  4978.8  394.35  4994.6  385.78  4995.1  385.28  5005.9  385.78  5007.1     388
  5014.5   392.1  5028.6  394.64  5035.5  398.32  5049.6  400.87    5078  401.48
    5099  403.28  5141.5   403.4  5216.7  406.22    5269   409.1  5297.3  411.55
#Mann= 4 ,-1 , 0
  4373.5     .16       0  4994.6     .07       0  5005.9     .16       0
  5216.7      .1       0
Bank Sta=4971.9,5035.5
XS Rating Curve= 0 ,0
Exp/Cntr=0.3,0.1

Type RM Length L Ch R = 1 ,12628   ,326,326,326
BEGIN DESCRIPTION:
NORTH MINERAL CR TRIB 8 17 0
END DESCRIPTION:
XS GIS Cut Line= 5
      3502798.76     10394112.87      3502863.86      10393555.6
      3502613.86     10393079.04      3502613.86     10393073.83
      3502507.12     10392909.82
#Sta/Elev= 30
  4302.3  406.66  4625.7  399.03  4756.6  399.57  4776.7  400.83    4817  401.12
  4868.4  400.21  4926.3  397.11  4958.2   394.6  4969.5   392.6  4980.3   392.3
    4986  388.88  5002.4  385.32  5002.9  384.82  5013.7  385.32  5014.6  386.64
  5030.1   395.1  5037.2  397.07  5052.1  397.99  5082.4   397.2  5229.5  398.26
  5289.1  398.91  5401.5   404.4  5405.3  406.15  5445.1  408.23  5489.7  413.27
  5510.8  413.98  5516.7  413.03  5531.9  413.96    5547  416.63  5602.4  421.51
#Mann= 5 ,-1 , 0
  4302.3     .16       0  4926.3     .12       0  5002.4     .07       0
  5013.7     .12       0  5229.5     .16       0
#XS Ineff= 2 , 0
          4815.1  401.08
Permanent Ineff=
       F       F
Bank Sta=4958.2,5030.1
XS Rating Curve= 0 ,0
Exp/Cntr=0.3,0.1

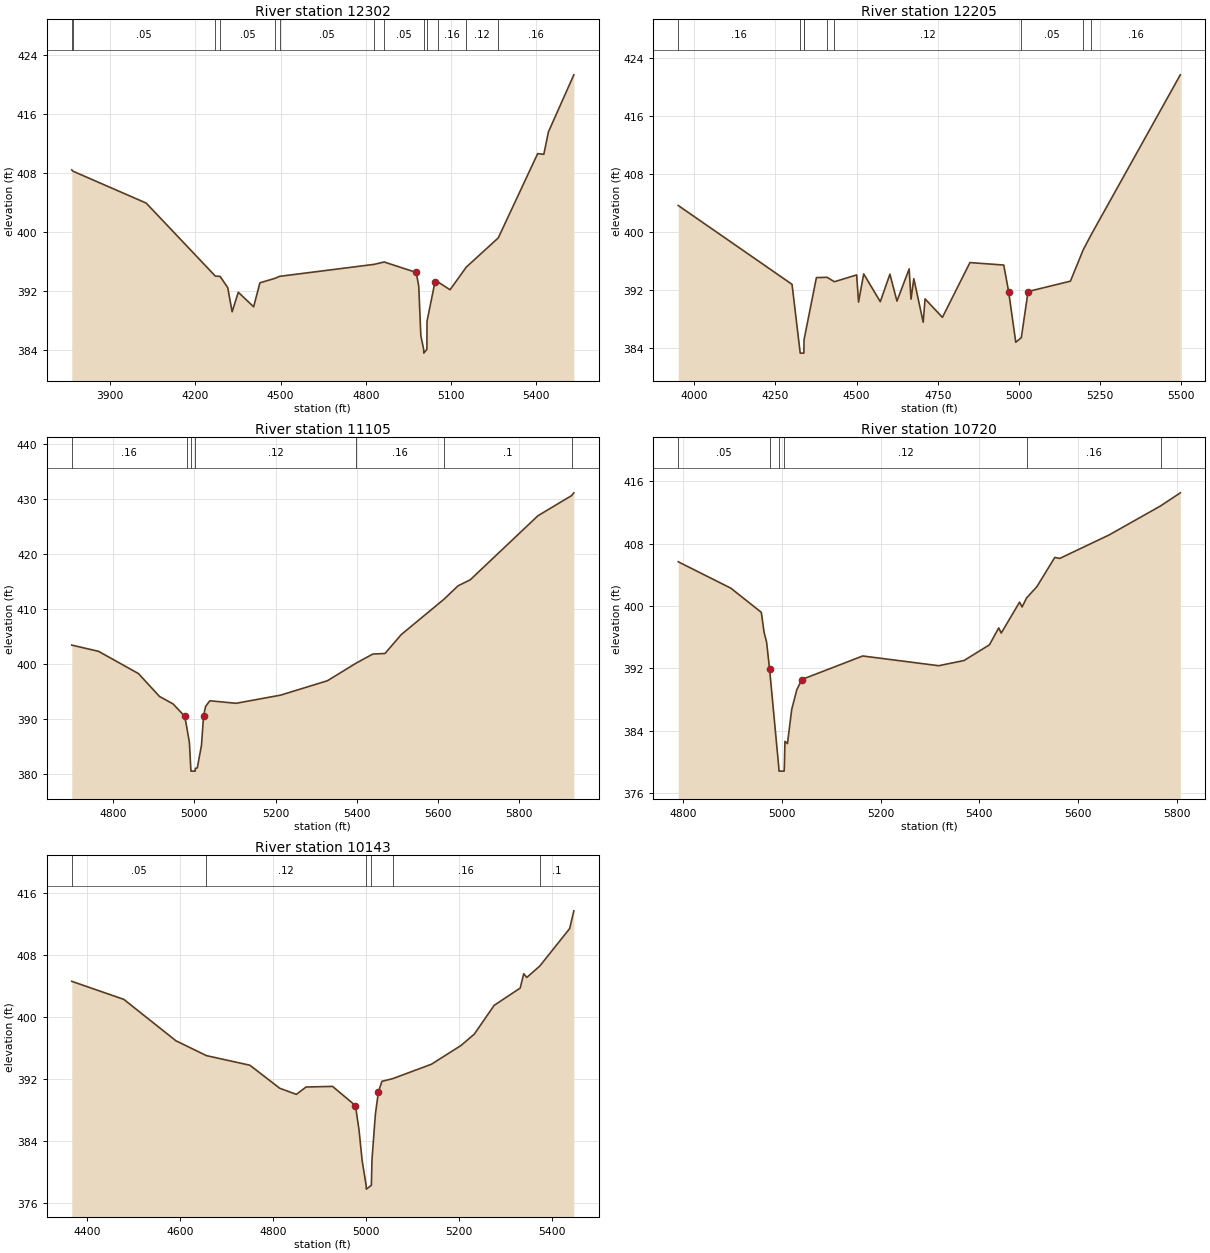
Type RM Length L Ch R = 1 ,12302   ,97,97,97
BEGIN DESCRIPTION:
NORTH MINERAL CR TRIB 8 16 0
END DESCRIPTION:
XS GIS Cut Line= 4
      3503524.51     10394459.72      3503437.71     10393947.55
      3503133.89     10393389.82      3502835.18     10392855.19
#Sta/Elev= 30
  3765.1  408.48  3769.2   408.3  4026.9  403.98  4270.4  394.08  4287.1  394.04
  4314.1  392.51  4329.4  389.24  4351.2  391.89  4405.2  389.92  4427.2  393.17
  4479.7  393.77    4497  394.05    4829  395.67  4864.7  395.99  4977.6  394.57
  4986.3  392.69  4993.6  386.01  5003.6  384.14  5004.1  383.64  5014.9  384.14
  5015.3  387.95  5043.6  393.32  5054.8  393.26  5096.4  392.23  5153.8  395.31
  5266.2  399.26  5404.8  410.68  5426.5  410.59  5442.5  413.61  5532.1  421.36
#Mann= 13 ,-1 , 0
  3765.1      .1       0  3769.2     .05       0  4270.4     .16       0
  4287.1     .05       0  4479.7     .16       0    4497     .05       0
    4829     .12       0  4864.7     .05       0  5003.6     .04       0
  5014.9     .05       0  5054.8     .16       0  5153.8     .12       0
  5266.2     .16       0
Bank Sta=4977.6,5043.6
XS Rating Curve= 0 ,0
Exp/Cntr=0.3,0.1

Type RM Length L Ch R = 1 ,12205   ,1100,1100,1100
BEGIN DESCRIPTION:
Mapping XS 1157dea7
END DESCRIPTION:
XS GIS Cut Line= 5
      3503611.31     10394207.94      3503537.53     10393951.89
       3503264.1     10393467.95      3503220.69     10393350.76
      3502930.81     10392825.07
#Sta/Elev= 30
  3950.2   403.7    4301  392.83  4326.2  383.35  4337.5  383.35  4337.9  385.17
  4376.1  393.76  4409.1   393.8  4431.5  393.19  4500.2  394.13    4506  390.38
  4521.9  394.27    4573  390.44  4602.7  394.23  4624.4  390.52    4662  394.96
  4667.7  390.79  4676.4  393.61  4705.3  387.61    4711  390.83  4764.5  388.28
  4849.4  395.83  4953.6  395.49  4968.9  391.76  4990.6  384.85  5007.7  385.48
  5028.5  391.84  5159.1  393.27  5198.5  397.59  5222.4  399.62  5497.8  421.71
#Mann= 9 ,-1 , 0
  3950.2     .16       0  4326.2     .07       0  4337.5     .16       0
  4337.9     .12       0  4409.1     .05       0  4431.5     .12       0
  5007.7     .05       0  5198.5     .12       0  5222.4     .16       0
Bank Sta=4968.9,5028.5
XS Rating Curve= 0 ,0
Exp/Cntr=0.3,0.1

Type RM Length L Ch R = 1 ,11105   ,385,385,385
BEGIN DESCRIPTION:
NORTH MINERAL CR TRIB 8 15 0
END DESCRIPTION:
XS GIS Cut Line= 4
      3503622.18     10394201.49      3503589.62     10394064.74
      3503730.67     10393535.22       3503750.2     10392986.43
#Sta/Elev= 30
  4697.7  403.42  4763.6  402.29  4862.2  398.24  4913.9  394.09  4947.6  392.72
    4976  390.49  4980.8  388.66  4987.7   385.7  4991.1  381.01  4991.6  380.51
  5001.9  380.51  5002.4  381.01  5007.1  381.09  5017.4  385.19  5022.7  390.62
  5027.8   392.3  5038.1   393.3  5102.9  392.84  5212.9  394.33  5327.9  396.94
  5399.1  400.16  5439.9  401.79  5469.9   401.9  5509.9  405.33  5615.3  411.76
    5650   414.2    5680  415.29  5846.8  426.93  5929.7  430.59  5935.4   431.1
#Mann= 7 ,-1 , 0
  4697.7     .16       0  4980.8     .12       0  4991.1     .07       0
  5002.4     .12       0  5399.1     .16       0  5615.3      .1       0
  5929.7     .16       0
Bank Sta=4976,5022.7
XS Rating Curve= 0 ,0
Exp/Cntr=0.3,0.1

Type RM Length L Ch R = 1 ,10720   ,577,577,577
BEGIN DESCRIPTION:
NORTH MINERAL CR TRIB 8 14 0
END DESCRIPTION:
XS GIS Cut Line= 3
      3503837.02     10394355.51      3504004.11     10393648.07
      3504004.11     10393357.28
#Sta/Elev= 30
  4789.9  405.66  4896.6  402.27  4958.3  399.17  4963.9  396.61    4969  395.36
  4975.1  391.86  4993.7  379.29  4994.2  378.79  5004.5  378.79    5005  379.29
  5006.2  382.61  5011.3  382.33  5019.9   386.7  5030.2  389.23  5040.5  390.55
  5163.8  393.57  5317.9  392.32  5369.3  392.99  5420.7     395  5439.5  397.17
  5444.6  396.51  5481.8  400.48  5486.9  399.86    5496  401.02  5516.8  402.46
  5553.2  406.22  5563.2  406.09  5663.2   409.1  5767.6  412.83  5807.6  414.51
#Mann= 6 ,-1 , 0
  4789.9     .05       0  4975.1     .12       0  4993.7     .07       0
    5005     .12       0    5496     .16       0  5767.6      .1       0
Bank Sta=4975.1,5040.5
XS Rating Curve= 0 ,0
Exp/Cntr=0.3,0.1

Type RM Length L Ch R = 1 ,10143   ,545,545,545
BEGIN DESCRIPTION:
NORTH MINERAL CR TRIB 8 13 0
END DESCRIPTION:
XS GIS Cut Line= 3
      3503999.76     10394444.54      3504103.94     10394201.46
      3504720.29     10393667.57
#Sta/Elev= 30
  4367.6  404.59  4479.6  402.26  4591.6  396.92  4657.3     395  4750.8  393.76
  4814.9  390.79  4850.6     390  4871.5  390.95  4928.5  391.03  4977.8  388.55
  4985.5  385.38  4992.1  381.49  5000.7  378.27  5001.2  377.77    5012  378.27
  5013.3  381.57  5020.6  387.41  5027.2  390.35  5034.8  391.69  5057.5  392.02
  5141.2  393.89  5204.8  396.31  5233.3  397.77  5276.1  401.49  5332.1  403.72
  5339.7  405.57  5346.3  405.09  5374.2  406.56  5438.5   411.4  5447.5  413.69
#Mann= 6 ,-1 , 0
  4367.6     .05       0  4657.3     .12       0  5000.7     .07       0
    5012     .12       0  5057.5     .16       0  5374.2      .1       0
Bank Sta=4977.8,5027.2
XS Rating Curve= 0 ,0
Exp/Cntr=0.3,0.1