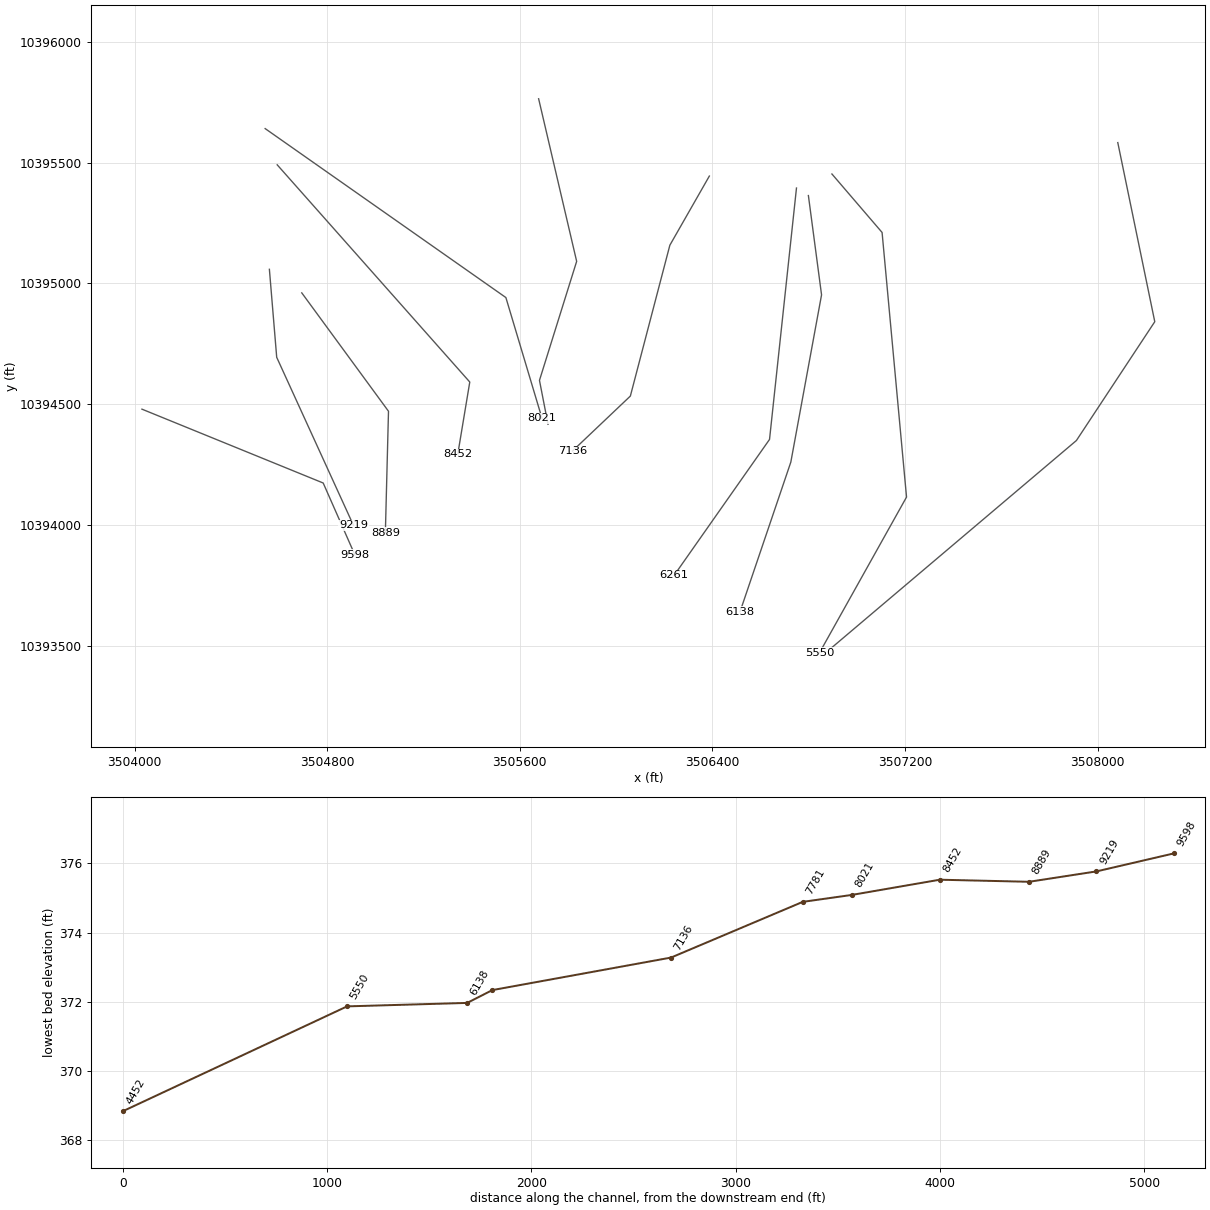
HEC-RAS study NORTH MINERAL CR TRIB 8.prj: NORTH MINERAL CR TRIB 8 Base Level Engineering

--- NORTH MINERAL CR TRIB 8.g01 (geometry) --- (continued)

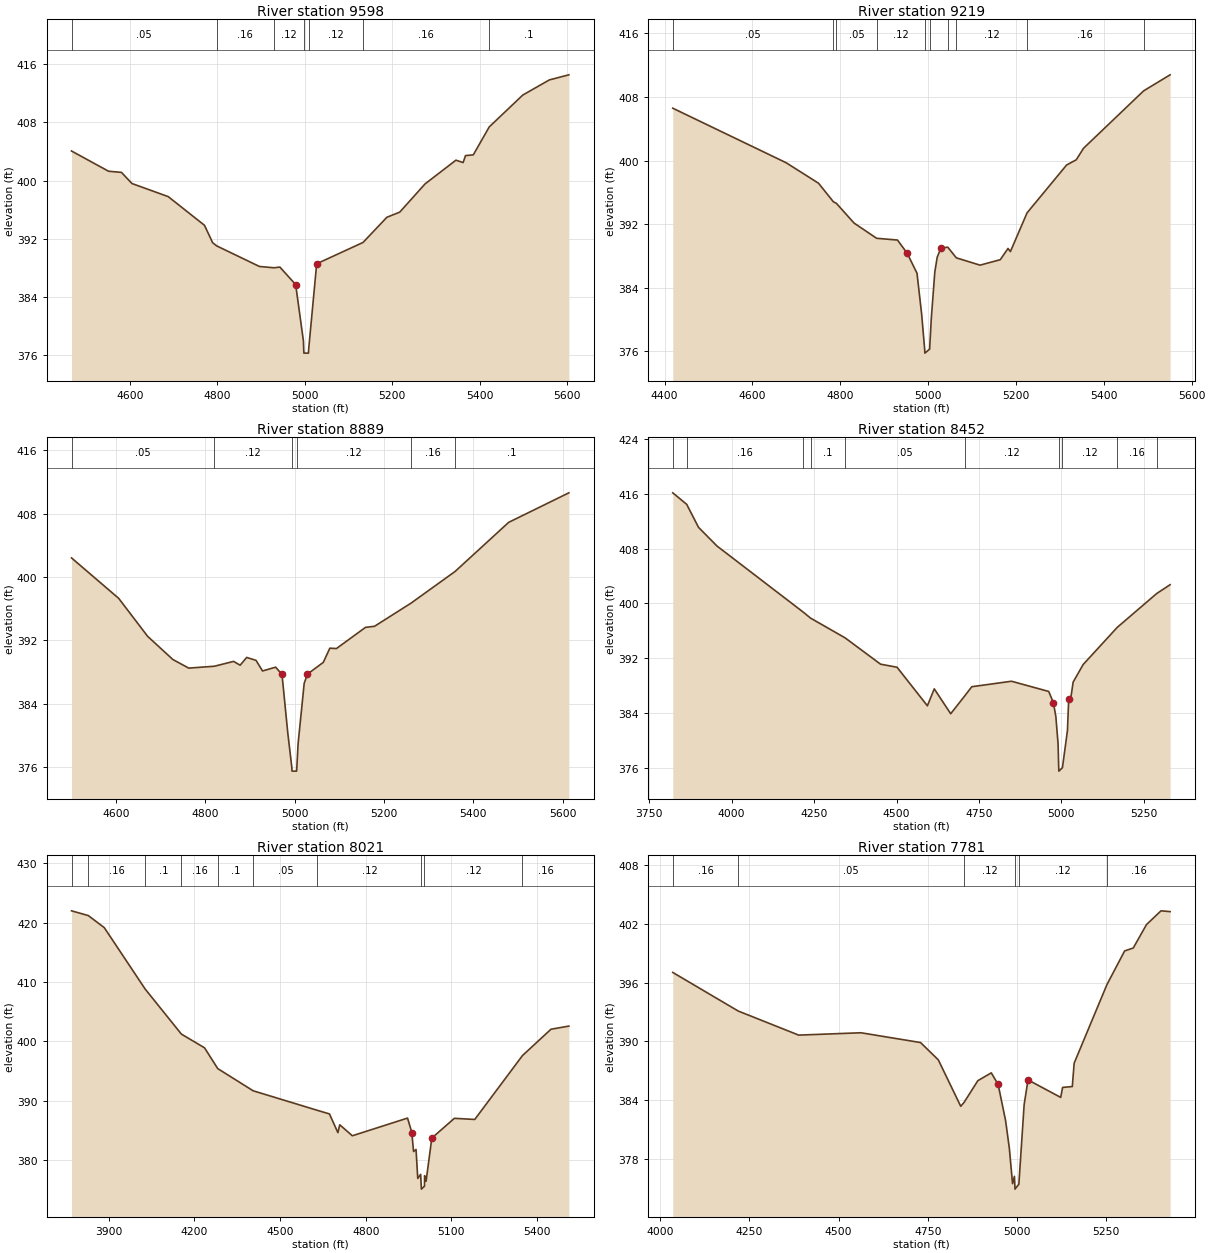
Type RM Length L Ch R = 1 ,9598    ,379,379,379
BEGIN DESCRIPTION:
NORTH MINERAL CR TRIB 8 12 0
END DESCRIPTION:
XS GIS Cut Line= 3
      3504030.17     10394479.23      3504783.19     10394173.24
      3504914.94     10393875.18
#Sta/Elev= 30
  4465.8  404.07  4550.6  401.29  4580.1  401.13  4604.2   399.6  4687.2   397.8
  4770.2  393.86  4788.9  391.47  4797.8  391.04    4896   388.2  4929.8  388.02
  4942.8  388.12    4979  385.71  4996.8  377.94  4997.4  376.79  4997.9  376.29
  5008.2  376.29  5008.7  376.79  5027.1  388.57  5133.2   391.5  5187.8  394.96
  5217.3  395.67  5275.3  399.55    5346  402.81  5362.4  402.48  5367.9  403.44
  5385.7  403.54  5422.2  407.38    5499  411.76  5559.8  413.84  5604.5  414.54
#Mann= 7 ,-1 , 0
  4465.8     .05       0  4797.8     .16       0  4929.8     .12       0
  4997.4     .07       0  5008.7     .12       0  5133.2     .16       0
  5422.2      .1       0
Bank Sta=4979,5027.1
XS Rating Curve= 0 ,0
Exp/Cntr=0.3,0.1

Type RM Length L Ch R = 1 ,9219    ,330,330,330
BEGIN DESCRIPTION:
NORTH MINERAL CR TRIB 8 48 0
END DESCRIPTION:
XS GIS Cut Line= 3
      3504559.66      10395058.7      3504590.05     10394694.08
      3504909.07     10393997.44
#Sta/Elev= 30
  4418.8  406.59  4676.8  399.73  4750.6  397.15  4784.5  394.81  4791.1  394.63
  4831.4  392.14  4882.9  390.22  4930.4     390  4952.4  388.34  4974.8  385.82
  4985.3   380.7  4992.2  376.27  4992.7  375.77  5003.5  376.27  5007.3  380.13
  5015.3  385.97  5020.8  387.85  5029.3     389  5044.8   389.1  5064.3  387.76
  5118.3  386.84  5164.4  387.53  5181.9  388.94  5187.4  388.55  5225.3  393.42
  5315.3  399.44  5337.3   400.1  5353.9  401.55  5490.6  408.77  5550.9  410.79
#Mann= 10 ,-1 , 0
  4418.8     .05       0  4784.5     .16       0  4791.1     .05       0
  4882.9     .12       0  4992.2     .07       0  5003.5     .12       0
  5044.8     .16       0  5064.3     .12       0  5225.3     .16       0
  5490.6      .1       0
Bank Sta=4952.4,5029.3
XS Rating Curve= 0 ,0
Exp/Cntr=0.3,0.1

Type RM Length L Ch R = 1 ,8889    ,437,437,437
BEGIN DESCRIPTION:
NORTH MINERAL CR TRIB 8 82 0
END DESCRIPTION:
XS GIS Cut Line= 3
      3504694.21     10394961.02      3505054.46     10394470.55
      3505041.44     10393967.08
#Sta/Elev= 30
  4501.2   402.4  4606.7  397.29  4671.5  392.49  4727.8  389.57  4763.3  388.48
  4820.9  388.72  4863.6  389.33  4878.3  388.85  4892.9  389.83  4913.8  389.46
  4928.4  388.12  4957.7   388.6  4971.9  387.68  4984.8  380.31  4993.8  375.97
  4994.3  375.47  5004.6  375.47  5005.1  375.97  5007.9  378.94  5021.5  386.56
  5028.8  387.72  5064.3  389.21  5078.9     391  5093.6  390.95  5158.7  393.63
  5178.7  393.76  5260.5  396.69  5358.8  400.68  5478.8  406.89  5613.4  410.62
#Mann= 6 ,-1 , 0
  4501.2     .05       0  4820.9     .12       0  4993.8     .07       0
  5005.1     .12       0  5260.5     .16       0  5358.8      .1       0
Bank Sta=4971.9,5028.8
XS Rating Curve= 0 ,0
Exp/Cntr=0.3,0.1

Type RM Length L Ch R = 1 ,8452    ,431,431,431
BEGIN DESCRIPTION:
NORTH MINERAL CR TRIB 8 72 0
END DESCRIPTION:
XS GIS Cut Line= 3
      3504592.12     10395491.62      3505392.11     10394591.64
       3505342.1     10394291.62
#Sta/Elev= 30
  3821.4  416.12  3863.7  414.44  3899.6  411.08  3955.6  408.36  4217.4  398.71
  4239.2  397.85  4344.3  394.96  4451.5  391.13  4501.6  390.68  4593.6  385.06
  4614.5  387.53  4664.3   383.9  4706.2  386.46  4728.3  387.84  4848.7  388.64
  4961.6  387.15  4975.8  385.52  4983.3  383.47    4990  379.49  4991.9  376.03
  4992.4  375.53  5003.2  376.03  5018.4  381.46  5022.2  386.05  5028.1  386.05
  5035.7  388.52  5066.1  391.08  5169.5   396.5    5289  401.43  5329.7  402.72
#Mann= 10 ,-1 , 0
  3821.4      .1       0  3863.7     .16       0  4217.4     .05       0
  4239.2      .1       0  4344.3     .05       0  4706.2     .12       0
  4991.9     .07       0  5003.2     .12       0  5169.5     .16       0
    5289      .1       0
Bank Sta=4975.8,5022.2
XS Rating Curve= 0 ,0
Exp/Cntr=0.3,0.1

Type RM Length L Ch R = 1 ,8021    ,240,240,240
BEGIN DESCRIPTION:
NORTH MINERAL CR TRIB 8 62
END DESCRIPTION:
XS GIS Cut Line= 3
      3504542.08     10395641.66      3505542.11     10394941.64
       3505692.1     10394441.65
#Sta/Elev= 30
  3769.2  421.98    3828  421.18  3883.9  419.15  4027.1  408.81  4154.2  401.21
  4235.3   398.9  4281.5   395.4  4405.6  391.66  4631.1  388.36    4673  387.76
  4702.6  384.61  4709.1  385.93  4753.2  384.08  4946.7  387.06  4961.6  384.62
  4967.7  381.43  4976.4  381.77  4982.5  376.89  4992.5  377.58  4994.7  375.59
  4995.2  375.09    5006  375.59  5006.4  377.36  5011.6  376.42  5031.7  383.69
  5110.8  387.02  5182.2  386.83  5349.3  397.59  5449.3  402.03  5511.9  402.56
#Mann= 10 ,-1 , 0
  3769.2      .1       0    3828     .16       0  4027.1      .1       0
  4154.2     .16       0  4281.5      .1       0  4405.6     .05       0
  4631.1     .12       0  4994.7     .07       0    5006     .12       0
  5349.3     .16       0
Bank Sta=4961.6,5031.7
XS Rating Curve= 0 ,0
Exp/Cntr=0.3,0.1

Type RM Length L Ch R = 1 ,7781    ,645,645,645
BEGIN DESCRIPTION:
NORTH MINERAL CR TRIB 8 52 0
END DESCRIPTION:
XS GIS Cut Line= 4
      3505678.15     10395765.28      3505836.14     10395091.65
      3505681.63     10394598.59      3505717.11     10394416.63
#Sta/Elev= 30
  4035.3  397.05  4218.9   393.1  4388.3  390.64  4562.9  390.88  4729.8  389.88
  4779.6  388.11  4842.5  383.36  4852.2  383.78  4890.4  385.98  4928.1  386.78
  4947.3  385.59  4968.2   381.9  4978.7  379.08  4987.7  375.45    4993   376.2
    4994  375.39  4994.5  374.89  5005.4  375.39  5020.2  383.53  5031.1  386.06
  5122.7  384.27    5128  385.29  5155.2  385.38  5160.4  387.77  5252.2   395.8
  5301.9  399.25  5326.1  399.55  5363.1  401.94  5403.8  403.35  5429.3  403.27
#Mann= 6 ,-1 , 0
  4035.3     .16       0  4218.9     .05       0  4852.2     .12       0
    4994     .07       0  5005.4     .12       0  5252.2     .16       0
Bank Sta=4947.3,5031.1
XS Rating Curve= 0 ,0
Exp/Cntr=0.3,0.1

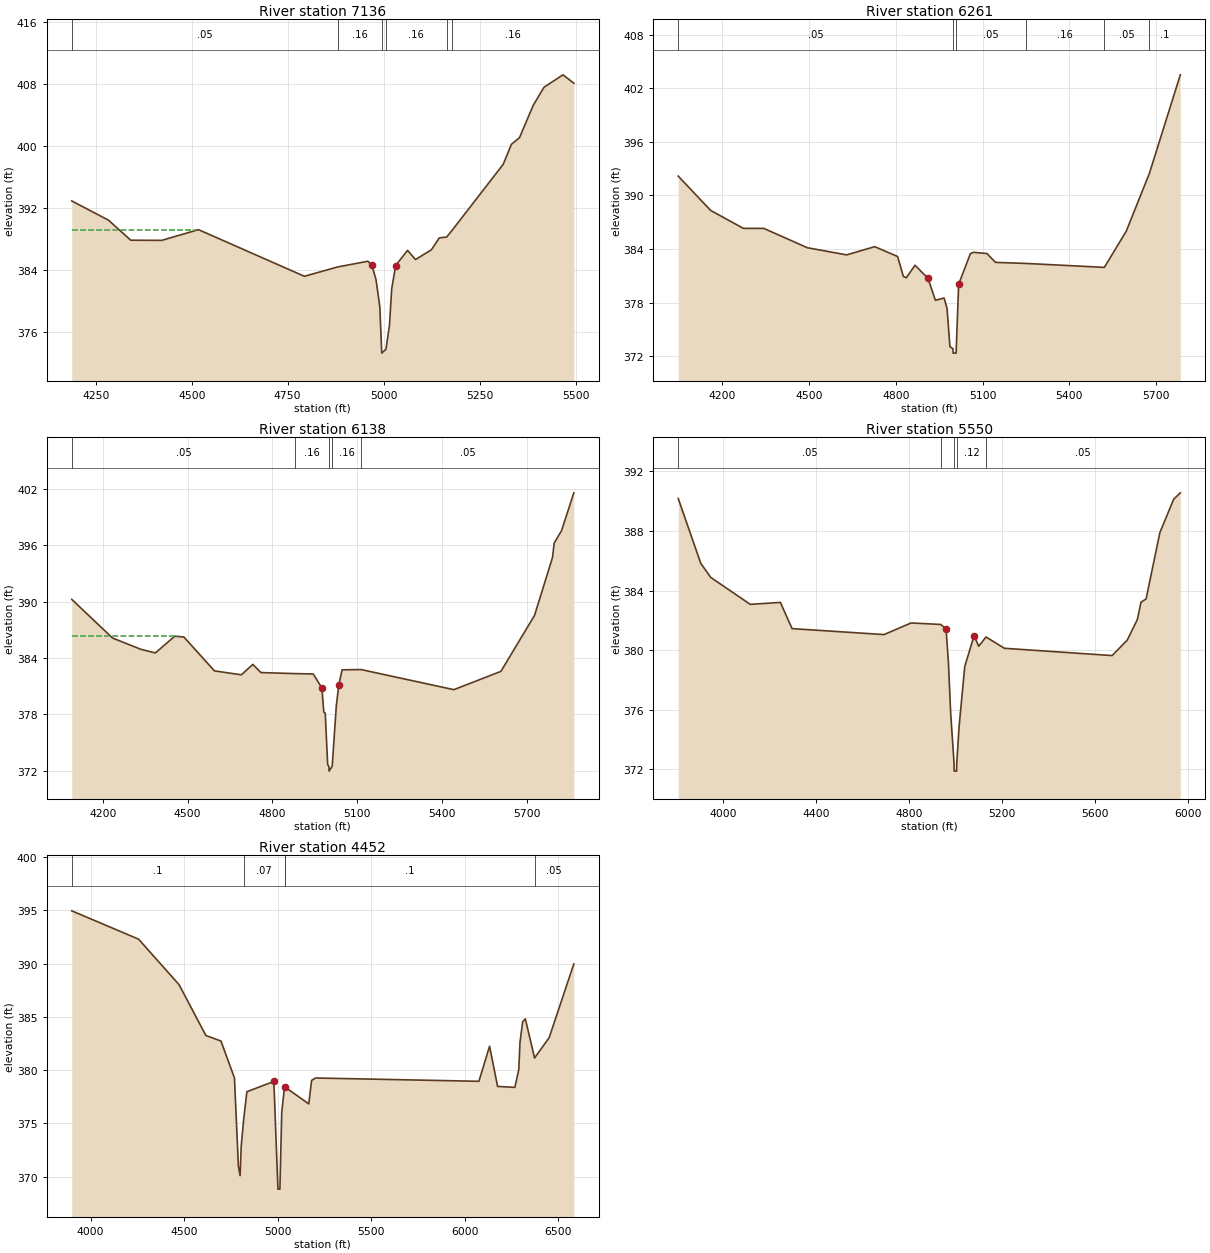
Type RM Length L Ch R = 1 ,7136    ,875,875,875
BEGIN DESCRIPTION:
NORTH MINERAL CR TRIB 8 421 0
END DESCRIPTION:
XS GIS Cut Line= 4
      3506387.38     10395444.98       3506223.3     10395158.49
      3506059.23     10394533.49      3505818.32     10394305.53
#Sta/Elev= 30
  4187.5  392.89  4283.2  390.41  4341.2  387.83  4421.8  387.81  4517.7  389.19
  4793.5  383.18  4879.8  384.38    4959  385.12  4969.3  384.59    4980  382.78
    4990  379.27  4994.6  373.78  4995.1  373.28    5006  373.78  5015.2  376.89
    5021  381.56  5031.3  384.57  5062.3  386.52    5083  385.34  5124.4   386.6
  5145.1  388.13  5164.1  388.24  5177.5  389.05  5311.5  397.61  5332.9  400.19
  5353.9  401.04  5389.5  405.19  5417.8  407.54  5467.2  409.14  5495.5  408.06
#Mann= 6 ,-1 , 0
  4187.5     .05       0  4879.8     .16       0  4994.6     .07       0
    5006     .16       0  5164.1     .12       0  5177.5     .16       0
#XS Ineff= 2 , 0
         4508.37   389.2
Permanent Ineff=
       F       F
Bank Sta=4969.3,5031.3
XS Rating Curve= 0 ,0
Exp/Cntr=0.3,0.1

Type RM Length L Ch R = 1 ,6261    ,123,123,123
BEGIN DESCRIPTION:
NORTH MINERAL CR TRIB 8 35 0
END DESCRIPTION:
XS GIS Cut Line= 3
      3506749.33     10395395.42      3506637.36      10394353.8
      3506241.55     10393791.33
#Sta/Elev= 30
  4048.3  392.16  4160.2  388.32  4273.4  386.31  4343.8  386.31  4494.6  384.14
  4630.5  383.34  4727.5  384.26  4806.4  383.16  4826.5  380.93  4836.6  380.78
  4866.8  382.18  4911.6  380.71  4937.2  378.26  4967.3  378.51  4977.4  377.35
  4987.5  373.06  4997.9  372.84  4998.4  372.34  5008.8  372.34  5009.3  372.84
  5017.6  380.05  5057.9  383.46  5067.9  383.63  5115.3  383.49  5144.9   382.5
  5251.4  382.38  5521.2  381.94    5597     386  5676.8  392.46  5783.7   403.5
#Mann= 6 ,-1 , 0
  4048.3     .05       0  4997.9     .04       0  5009.3     .05       0
  5251.4     .16       0  5521.2     .05       0  5676.8      .1       0
Bank Sta=4911.6,5017.6
XS Rating Curve= 0 ,0
Exp/Cntr=0.3,0.1

Type RM Length L Ch R = 1 ,6138    ,588,588,588
BEGIN DESCRIPTION:
NORTH MINERAL CR TRIB 8 25
END DESCRIPTION:
XS GIS Cut Line= 4
      3506798.82      10395364.2       3506853.5     10394952.76
       3506725.9     10394260.05      3506514.97     10393640.28
#Sta/Elev= 30
  4090.8  390.25  4234.6  386.14  4335.5  384.93  4386.2  384.55  4454.4  386.32
  4486.8  386.25  4594.9  382.64    4690  382.22  4730.7  383.33  4759.1  382.46
  4879.8  382.35  4944.2  382.31  4974.7  380.81  4981.3  378.25  4986.4  378.14
  4995.1  372.67  4999.5  372.47    5000  371.97  5010.9  372.47  5025.6  378.92
  5034.3  381.12  5045.9  382.75    5113  382.78  5440.9  380.64  5607.3  382.59
  5726.1  388.55  5789.5  394.71  5795.5  396.25  5821.2  397.55  5864.9  401.59
#Mann= 5 ,-1 , 0
  4090.8     .05       0  4879.8     .16       0  4999.5     .07       0
  5010.9     .16       0    5113     .05       0
#XS Ineff= 2 , 0
          4464.6  386.34
Permanent Ineff=
       F       F
Bank Sta=4974.7,5034.3
XS Rating Curve= 0 ,0
Exp/Cntr=0.3,0.1

Type RM Length L Ch R = 1 ,5550    ,1098,1098,1098
BEGIN DESCRIPTION:
NORTH MINERAL CR TRIB 8 1 0
END DESCRIPTION:
XS GIS Cut Line= 4
      3506896.61     10395453.54      3507104.96     10395211.32
      3507206.53     10394114.97      3506844.55     10393469.14
#Sta/Elev= 30
  3807.2  390.18  3904.3  385.82  3947.1  384.88  4117.2  383.07  4246.9   383.2
  4297.1  381.44  4692.9  381.04  4809.3  381.82  4937.1  381.72  4959.9  381.41
    4970  379.19    4980   375.7  4994.4  372.37  4994.9  371.87  5005.3  371.87
  5005.8  372.37  5016.2   374.9  5040.3  378.89  5080.4  380.96  5100.5  380.26
  5132.1  380.88    5211  380.12  5674.7  379.63  5739.8  380.67  5783.2  382.05
  5799.1  383.22  5820.8  383.43  5880.2  387.89  5939.5  390.13  5968.1  390.56
#Mann= 5 ,-1 , 0
  3807.2     .05       0  4937.1     .12       0  4994.4     .07       0
  5005.8     .12       0  5132.1     .05       0
Bank Sta=4959.9,5080.4
XS Rating Curve= 0 ,0
Exp/Cntr=0.3,0.1

Type RM Length L Ch R = 1 ,4452    ,0,0,0
BEGIN DESCRIPTION:
NORTH MINERAL CR TRIB 8 23 0
END DESCRIPTION:
XS GIS Cut Line= 4
      3508084.14     10395583.68      3508237.78     10394841.53
      3507912.25     10394349.34      3506891.39     10393487.34
#Sta/Elev= 30
  3899.2  394.96  4256.4   392.3  4473.2  388.02  4616.1  383.26  4696.7  382.74
    4769  379.27    4790     371  4799.1  370.11  4805.1  372.88  4817.5  375.26
  4835.2  377.98  4979.6  378.95  5001.4  368.84  5011.9  368.84  5021.7  376.06
  5036.8  378.45  5166.2  376.84  5181.2  379.04  5202.3  379.27  6075.7  378.96
  6132.8  382.25  6175.7  378.48    6268  378.39  6288.9  380.07  6295.4  382.62
  6309.7  384.54    6324  384.82  6373.4  381.15  6451.5  383.06  6583.3  389.98
#Mann= 5 ,-1 , 0
  3899.2      .1       0  4817.5     .07       0  5036.8     .03       0
  5036.8      .1       0  6373.4     .05       0
#XS Ineff= 2 , 0
                         6322.12           384.7
Permanent Ineff=
       F       F
Bank Sta=4979.6,5036.8
XS Rating Curve= 0 ,0
Exp/Cntr=0.3,0.1

Chan Stop Cuts=-1
Use User Specified Reach Order=0
Composite Channel Slope=5