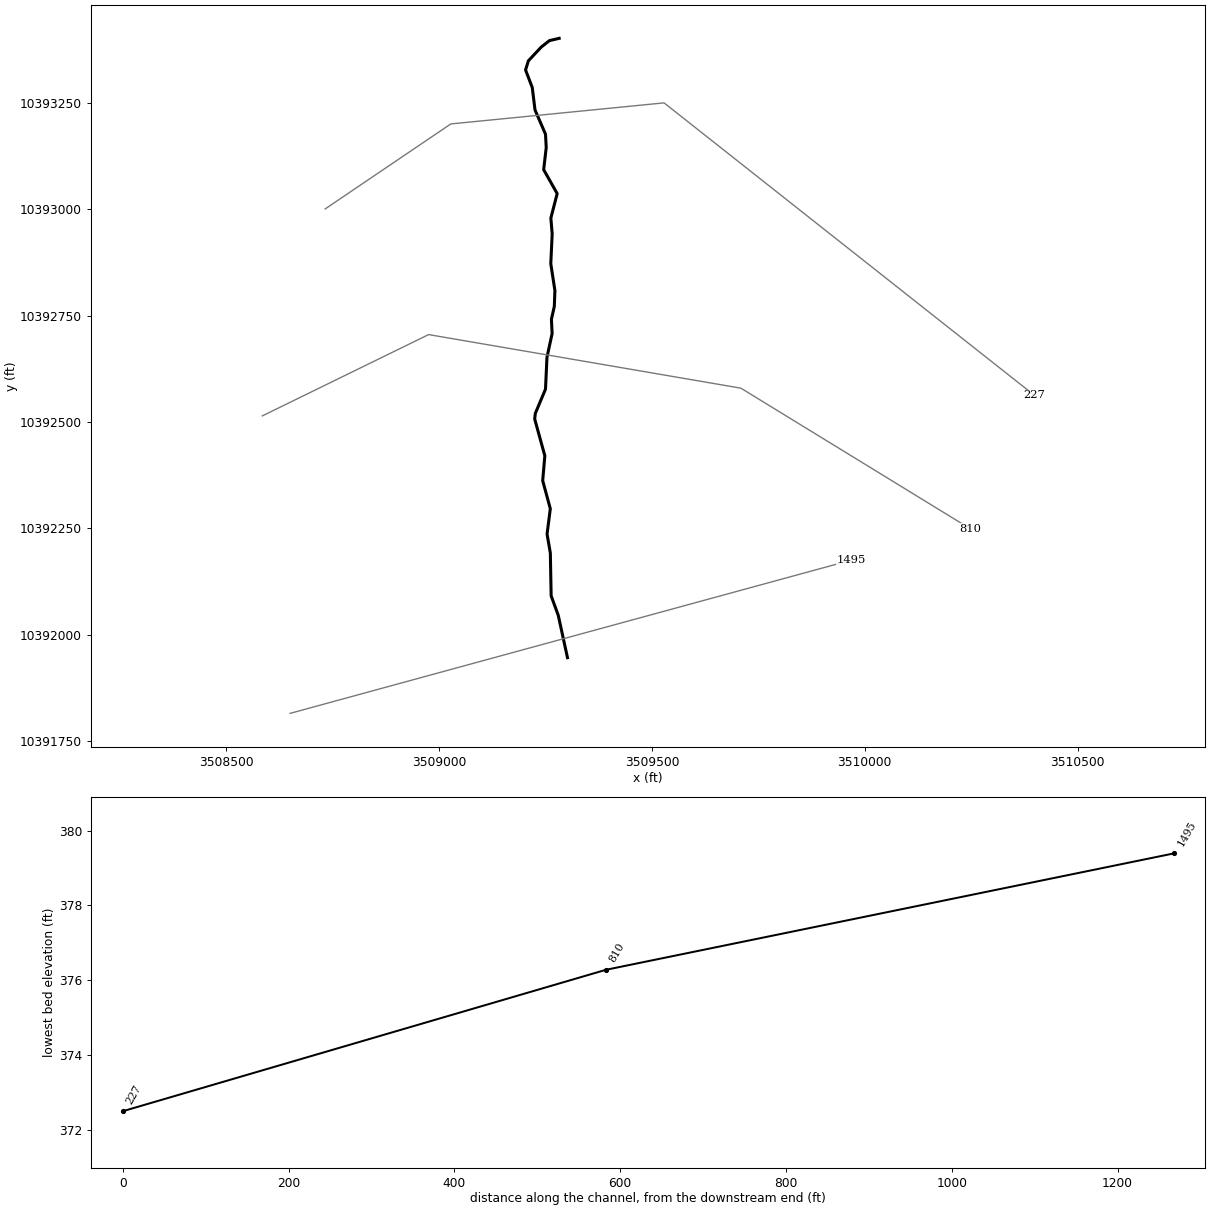
--- NORTH MINERAL CR TRIB 9.prj (project) ---

Proj Title=NORTH MINERAL CR TRIB 9 Base Level Engineering
Current Plan=p01
Default Exp/Contr=0.3,0.1
English Units
Geom File=g01
Flow File=f01
Plan File=p01
BEGIN DESCRIPTION:
NORTH MINERAL CR TRIB 9
END DESCRIPTION:

--- NORTH MINERAL CR TRIB 9.p01 (plan) ---

Plan Title=Multiple Run
Short Identifier=Multiple
Geom File=g01
Flow File=f01
Subcritical Flow
K Sum by GR= 0
Std Step Tol= 0.01
Critical Tol= 0.01
Num of Std Step Trials= 20
Max Error Tol= 0.3
Flow Tol Ratio= 0.001
Split Flow NTrial= 30
Split Flow Tol= 0.02
Split Flow Ratio= 0.02
Log Output Level= 0
Friction Slope Method= 1
Unsteady Friction Slope Method= 2
Unsteady Bridges Friction Slope Method= 1
Parabolic Critical Depth
Global Vel Dist=  1 , 1 , 1
Global Log Level= 0
CheckData=True
Encroach Param= -1, 0, 0, 0
BEGIN DESCRIPTION:
Multiple Run
END DESCRIPTION:

--- NORTH MINERAL CR TRIB 9.f01 (steady flow) ---

Flow Title=Multiple
Number of Profiles=7
Profile Names=10-year,25-year,50-year,1pct_min,100-year,1pct_plu,500-year
River Rch & RM= NORTH MINERAL CR,Reach-1,1495
     506     680     822     728     985    1331    1406
Boundary for River Rch & Prof#=NORTH MINERAL CR,Reach-1,1
Up Type=0
Dn Type=3
Dn Slope=0.005
Boundary for River Rch & Prof#=NORTH MINERAL CR,Reach-1,2
Up Type=0
Dn Type=3
Dn Slope=0.005
Boundary for River Rch & Prof#=NORTH MINERAL CR,Reach-1,3
Up Type=0
Dn Type=3
Dn Slope=0.005
Boundary for River Rch & Prof#=NORTH MINERAL CR,Reach-1,4
Up Type=0
Dn Type=3
Dn Slope=0.005
Boundary for River Rch & Prof#=NORTH MINERAL CR,Reach-1,5
Up Type=0
Dn Type=3
Dn Slope=0.005
Boundary for River Rch & Prof#=NORTH MINERAL CR,Reach-1,6
Up Type=0
Dn Type=3
Dn Slope=0.005
Boundary for River Rch & Prof#=NORTH MINERAL CR,Reach-1,7
Up Type=0
Dn Type=3
Dn Slope=0.005

--- NORTH MINERAL CR TRIB 9.g01 (geometry) ---

Geom Title=Existing Conditions

River Reach=NORTH MINERAL CR,Reach-1
Reach XY= 30
      3509301.73     10391946.49      3509280.09     10392045.81
      3509263.35     10392091.79      3509261.48     10392192.22
      3509253.79     10392236.68      3509261.39     10392296.34
      3509243.53     10392362.17      3509248.56     10392420.57
      3509224.71     10392507.09      3509226.19     10392520.19
      3509250.11     10392577.15      3509253.53     10392651.66
      3509265.67     10392707.87      3509264.00     10392741.25
      3509270.82     10392771.56      3509272.22     10392808.62
      3509262.52     10392871.91      3509265.81     10392941.71
      3509262.71     10392978.94      3509277.54     10393036.52
      3509245.81     10393092.71      3509251.82     10393144.83
      3509250.11     10393176.09      3509225.46     10393233.05
      3509219.01     10393285.63      3509203.28     10393326.90
      3509209.88     10393348.36      3509240.31     10393380.90
      3509259.35     10393395.81      3509282.26     10393401.19

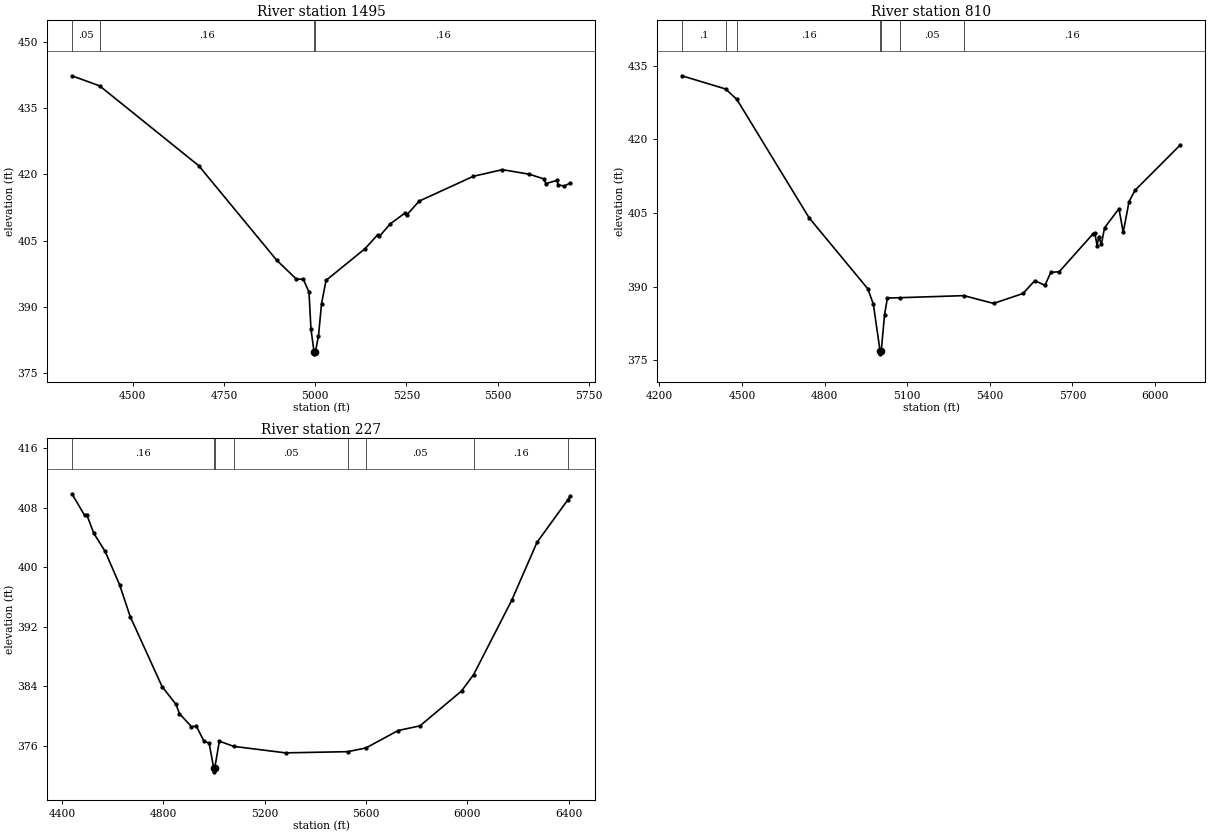
Type RM Length L Ch R = 1,1495,685,685,685
BEGIN DESCRIPTION:
NORTH MINERAL CR TRIB 9 3 0
END DESCRIPTION:
XS GIS Cut Line= 2
      3508650.08     10391815.57      3509968.33     10392175.48
#Sta/Elev= 30
  4333.3  442.33  4409.4  440.04  4680.9  421.98  4895.2  400.53  4948.5  396.32
  4967.7  396.26  4983.1  393.38  4988.5  385.10  4996.8  379.89  4997.1  379.39
  5000.8  379.89  5009.2  383.49  5017.6  390.78  5029.9  396.02  5136.7  403.19
  5171.3  406.33  5176.4  406.00  5205.8  408.80  5245.5  411.22  5250.7  410.79
  5285.2  413.96  5433.7  419.58  5513.2  421.08  5587.4  420.04  5627.1  418.98
  5632.3  417.91  5661.7  418.63  5666.8  417.64  5683.0  417.35  5699.8  418.10
#Mann=4,-1,0
  4333.3    0.05       0  4409.4    0.16       0  4996.8    0.07       0
  5000.8    0.16       0
Bank Sta=4996.8,5000.8
Exp/Cntr=0.3,0.1

Type RM Length L Ch R = 1,810,583,583,583
BEGIN DESCRIPTION:
NORTH MINERAL CR TRIB 9 2 0
END DESCRIPTION:
XS GIS Cut Line= 4
      3508584.99     10392514.36      3508975.58     10392705.32
      3509709.09     10392579.45      3510247.17     10392249.66
#Sta/Elev= 30
  4282.2  432.99  4441.0  430.29  4481.6  428.17  4743.9  404.02  4957.0  389.55
  4977.2  386.40  5001.7  376.78  5001.9  376.28  5005.7  376.78  5017.8  384.25
  5028.0  387.65  5073.4  387.73  5306.1  388.15  5413.5  386.56  5520.7  388.59
  5563.3  391.21  5600.1  390.25  5621.4  392.89  5652.2  393.04  5774.2  400.72
  5781.4  400.87  5789.6  398.35  5795.4  400.20  5804.9  398.59  5816.7  402.01
  5868.9  405.88  5884.3  401.07  5905.6  407.33  5926.9  409.62  6092.3  418.93
#Mann=7,-1,0
  4282.2     0.1       0  4441.0    0.05       0  4481.6    0.16       0
  5001.7    0.07       0  5005.7    0.16       0  5073.4    0.05       0
  5306.1    0.16       0
Bank Sta=5001.7,5005.7
Exp/Cntr=0.3,0.1

Type RM Length L Ch R = 1,227,0,0,0
BEGIN DESCRIPTION:
NORTH MINERAL CR TRIB 9 1 0
END DESCRIPTION:
XS GIS Cut Line= 4
      3508732.50     10393000.44      3509027.66     10393200.11
      3509528.63     10393249.59      3510398.13     10392562.93
#Sta/Elev= 30
  4439.5  409.86  4489.8  406.95  4498.7  407.00  4525.8  404.56  4570.6  402.12
  4627.6  397.65  4669.6  393.36  4795.5  383.95  4850.6  381.55  4864.0  380.31
  4910.9  378.59  4930.9  378.63  4960.1  376.66  4981.2  376.33  4999.3  373.00
  4999.5  372.50  5003.3  373.00  5021.4  376.62  5078.3  375.92  5282.7  375.05
  5528.4  375.21  5600.1  375.71  5727.0  378.05  5813.4  378.68  5977.2  383.36
  6025.1  385.57  6175.9  395.58  6275.3  403.34  6397.7  409.09  6407.2  409.61
#Mann=8,-1,0
  4439.5    0.16       0  4999.3    0.07       0  5003.3    0.16       0
  5078.3    0.05       0  5528.4    0.16       0  5600.1    0.05       0
  6025.1    0.16       0  6397.7     0.1       0
Bank Sta=4999.3,5003.3
Exp/Cntr=0.3,0.1

Chan Stop Cuts=-1