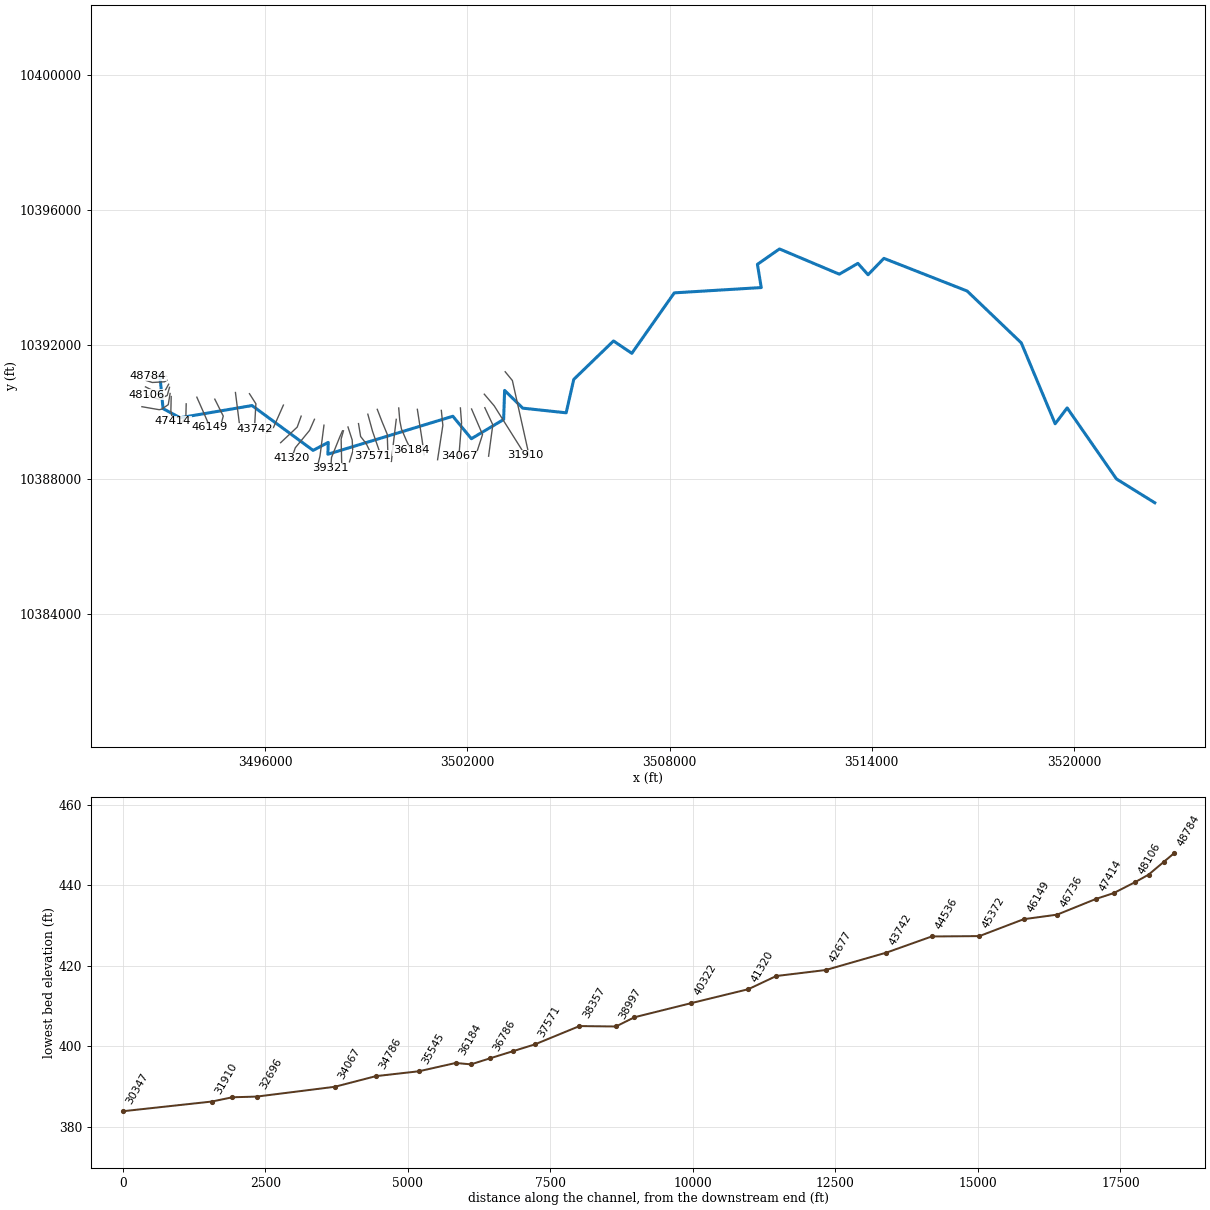
--- NORTH MINERAL CREEK.prj (project) ---

Proj Title=NORTH MINERAL CREEK Base Level Engineering
Current Plan=p01
Default Exp/Contr=0.3,0.1
English Units
Geom File=g01
Flow File=f01
Plan File=p01
Y Axis Title=Elevation
X Axis Title(PF)=Main Channel Distance
X Axis Title(XS)=Station
BEGIN DESCRIPTION:
NORTH MINERAL CREEK
END DESCRIPTION:
DSS Export Rating Curves= 0
DSS Export Rating Curve Sorted= 0
DSS Export Volume Flow Curves= 0
DXF OffsetX= 0
DXF OffsetY= 0
DXF ScaleX= 1
DXF ScaleY= 10

--- NORTH MINERAL CREEK.p01 (plan) ---

Plan Title=Multiple Run
Short Identifier=Multiple
Geom File=g01
Flow File=f01
Subcritical Flow
K Sum by GR= 0
Std Step Tol= 0.01
Critical Tol= 0.01
Num of Std Step Trials= 20
Max Error Tol= 0.3
Flow Tol Ratio= 0.001
Split Flow NTrial= 30
Split Flow Tol= 0.02
Split Flow Ratio= 0.02
Log Output Level= 0
Friction Slope Method= 1
Unsteady Friction Slope Method= 2
Unsteady Bridges Friction Slope Method= 1
Parabolic Critical Depth
Global Vel Dist=  1 , 1 , 1
Global Log Level= 0
CheckData=True
Encroach Param= -1, 0, 0, 0
BEGIN DESCRIPTION:
Multiple Run
END DESCRIPTION:

--- NORTH MINERAL CREEK.f01 (steady flow) ---

Flow Title=Multiple
Program Version=4.10
Number of Profiles= 7
Profile Names=10-year,25-year,50-year,1pct_min,100-year,1pct_plu,500-year
River Rch & RM=NORTH MINERAL CR,Reach-1         ,48784
     216     269     309     260     352     476     454
River Rch & RM=NORTH MINERAL CR,Reach-1         ,47414
    1057    1469    1812    1631    2205    2983    3260
River Rch & RM=NORTH MINERAL CR,Reach-1         ,43742
    1376    1936    2408    2181    2950    3990    4423
River Rch & RM=NORTH MINERAL CR,Reach-1         ,37571
    2754    4039    5165    4804    6497    8787   10274
River Rch & RM=NORTH MINERAL CR,Reach-1         ,36184
    2768    4037    5141    4760    6438    8706   10087
River Rch & RM=NORTH MINERAL CR,Reach-1         ,31910
    3446    5068    6490    6039    8167   11045   12922
River Rch & RM=NORTH MINERAL CR,Reach-1         ,29860
    3446    5068    6490    6039    8167   11045   12922
River Rch & RM=NORTH MINERAL CR,Reach-1         ,26193
    3947    5819    7465    6954    9405   12719   14914
River Rch & RM=NORTH MINERAL CR,Reach-1         ,22338
    5578    8225   10551    9811   13268   17944   20962
River Rch & RM=NORTH MINERAL CR,Reach-1         ,20433
    5578    8225   10551    9811   13268   17944   20962
River Rch & RM=NORTH MINERAL CR,Reach-1         ,17790
    5578    8225   10551    9811   13268   17944   20962
River Rch & RM=NORTH MINERAL CR,Reach-1         ,16445
    5919    8758   11260   10495   14193   19195   22528
River Rch & RM=NORTH MINERAL CR,Reach-1         ,15815
    5993    8850   11363   10575   14301   19340   22628
River Rch & RM=NORTH MINERAL CR,Reach-1         ,14272
    6125    9050   11625   10822   14635   19793   23171
River Rch & RM=NORTH MINERAL CR,Reach-1         ,12215
    6260    9232   11841   11006   14885   20130   23491
River Rch & RM=NORTH MINERAL CR,Reach-1         ,9424
    6260    9232   11841   11006   14885   20130   23491
River Rch & RM=NORTH MINERAL CR,Reach-1         ,7186
    6352    9360   11999   11147   15074   20386   23761
River Rch & RM=NORTH MINERAL CR,Reach-1         ,4266
    6474    9546   12243   11377   15386   20808   24270
River Rch & RM=NORTH MINERAL CR,Reach-1         ,3536
    6474    9546   12243   11377   15386   20808   24270
Boundary for River Rch & Prof#=NORTH MINERAL CR,Reach-1         , 1
Up Type= 0
Dn Type= 1
Dn Known WS=346.97
Boundary for River Rch & Prof#=NORTH MINERAL CR,Reach-1         , 2
Up Type= 0
Dn Type= 1
Dn Known WS=348.2
Boundary for River Rch & Prof#=NORTH MINERAL CR,Reach-1         , 3
Up Type= 0
Dn Type= 1
Dn Known WS=349.13
Boundary for River Rch & Prof#=NORTH MINERAL CR,Reach-1         , 4
Up Type= 0
Dn Type= 1
Dn Known WS=348.88
Boundary for River Rch & Prof#=NORTH MINERAL CR,Reach-1         , 5
Up Type= 0
Dn Type= 1
Dn Known WS=350.11
Boundary for River Rch & Prof#=NORTH MINERAL CR,Reach-1         , 6
Up Type= 0
Dn Type= 1
Dn Known WS=351.11
Boundary for River Rch & Prof#=NORTH MINERAL CR,Reach-1         , 7
Up Type= 0
Dn Type= 1
Dn Known WS=352.54
DSS Import GetInterval= 0
DSS Import GetPeak= 0
DSS Import FillOption= 0

--- NORTH MINERAL CREEK.g01 (geometry) ---

Geom Title=Existing Conditions
Program Version=4.10

River Reach=NORTH MINERAL CR,Reach-1
Reach XY= 30
      3492868.33     10391104.51      3492964.69       10390098.
      3493469.46     10389827.38      3495606.12     10390188.96
      3497418.78     10388857.61      3497868.23     10389094.56
      3497857.61     10388743.35      3501567.54      10389871.6
      3502116.58     10389203.78       3503074.6     10389775.16
      3503103.39     10390638.83      3503642.11     10390111.64
      3504930.56     10389973.81       3505155.4     10390965.29
      3506335.78     10392107.92      3506879.53     10391740.73
       3508140.2      10393536.8      3510721.08     10393694.17
      3510607.44     10394384.58      3511262.46     10394841.08
      3513037.51     10394091.62      3513589.82     10394412.51
      3513890.81     10394075.27      3514362.11     10394561.64
      3516832.45     10393591.39      3518439.72     10392050.65
      3519445.57     10389647.98      3519800.91     10390119.32
      3521265.24     10388008.19      3522402.11     10387301.64

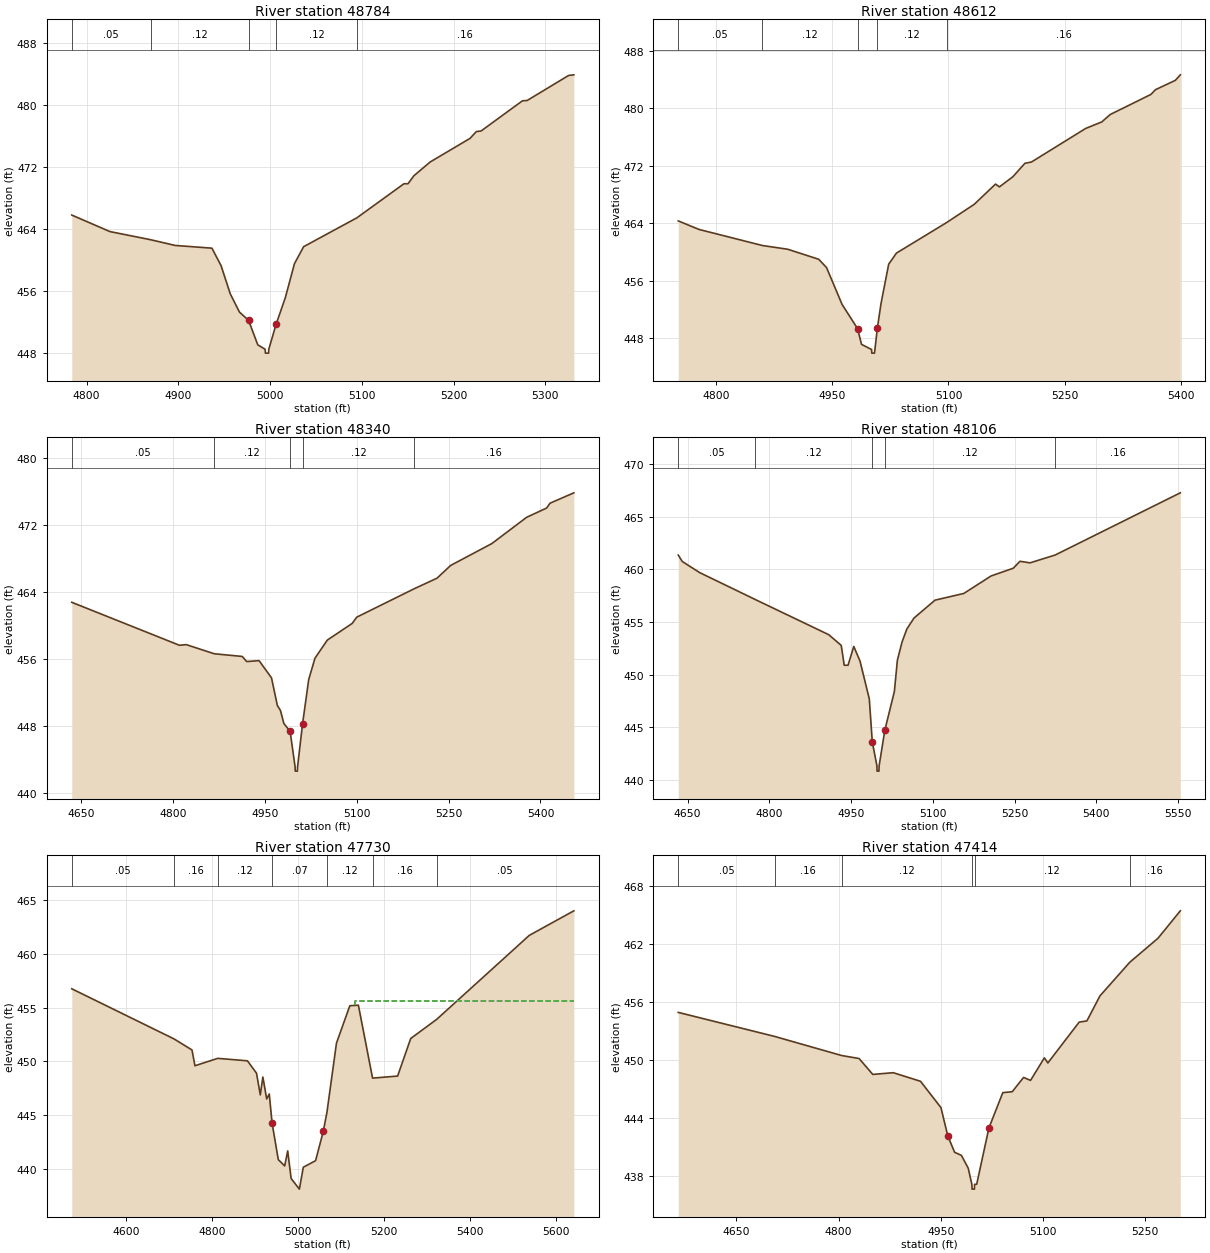
Type RM Length L Ch R = 1 ,48784   ,172,172,172
BEGIN DESCRIPTION:
NORTH MINERAL CREEK 7 1
END DESCRIPTION:
XS GIS Cut Line= 4
      3493062.89      10391062.1      3492958.76     10391041.27
      3492698.34     10391041.27      3492521.27     10391077.73
#Sta/Elev= 30
  4783.8  465.75  4825.4  463.62  4869.7  462.57  4896.6  461.83  4936.6  461.48
  4946.6  459.22  4956.6  455.59  4966.6  453.24  4976.6  452.16  4986.6  449.01
  4994.6  448.44  4994.9  447.94  4998.4  447.94  4998.6  448.44  5006.6  451.67
  5016.6  455.08  5026.6  459.48  5036.6  461.67  5094.6  465.39    5146  469.79
  5150.4  469.79  5156.8  470.82  5174.6   472.6    5218  475.64  5224.9  476.52
    5230  476.59  5275.2  480.49  5280.3  480.53  5325.5  483.76  5331.2  483.84
#Mann= 5 ,-1 , 0
  4783.8     .05       0  4869.7     .12       0  4976.6     .07       0
  5006.6     .12       0  5094.6     .16       0
Bank Sta=4976.6,5006.6
XS Rating Curve= 0 ,0
Exp/Cntr=0.3,0.1

Type RM Length L Ch R = 1 ,48612   ,272,272,272
BEGIN DESCRIPTION:
NORTH MINERAL CREEK 7 0
END DESCRIPTION:
XS GIS Cut Line= 4
      3493078.54      10390942.3      3493010.84     10390895.44
      3492646.26      10390874.6      3492456.03      10390936.3
#Sta/Elev= 30
  4751.5  464.33  4778.3  463.14    4860   460.9  4892.7  460.38  4932.7  458.98
  4942.8  457.82  4962.8  452.69  4982.8  449.31  4987.9  447.12  5000.9   446.4
  5001.1   445.9  5004.6   445.9 5008.38  449.42  5012.9  452.74  5022.9  458.29
  5032.9  459.84  5097.5  464.09  5133.1  466.63  5160.7  469.46  5165.7  469.07
  5183.1  470.49  5198.6  472.36  5207.1  472.54    5277  477.22  5297.8  478.13
  5308.5  479.15  5361.1  481.96    5367  482.62  5392.6  483.92    5399  484.69
#Mann= 5 ,-1 , 0
  4751.5     .05       0    4860     .12       0  4982.8     .07       0
 5008.38     .12       0  5097.5     .16       0
Bank Sta=4982.8,5008.38
XS Rating Curve= 0 ,0
Exp/Cntr=0.3,0.1

Type RM Length L Ch R = 1 ,48340   ,234,234,234
BEGIN DESCRIPTION:
NORTH MINERAL CREEK 64 0
END DESCRIPTION:
XS GIS Cut Line= 4
      3493130.64     10390822.52      3493042.09     10390661.06
      3492713.97     10390608.98      3492443.12      10390744.4
#Sta/Elev= 30
  4635.3  462.77    4811  457.65    4822  457.73  4867.8  456.64  4913.5  456.32
  4920.7  455.71  4940.9  455.82  4961.2  453.77  4970.7  450.49  4975.8  449.88
  4981.4  448.33  4991.6  447.39  4999.7  443.16  4999.9  442.66  5003.4  442.66
  5003.7  443.16  5011.8  448.26  5021.9  453.57  5032.1  456.11  5052.3  458.27
  5092.8  460.25  5100.3     461  5194.2  464.39  5231.2  465.64  5253.5  467.16
  5320.6  469.76  5377.4  472.89  5410.1     474  5415.6  474.57  5454.5  475.81
#Mann= 5 ,-1 , 0
  4635.3     .05       0  4867.8     .12       0  4991.6     .07       0
  5011.8     .12       0  5194.2     .16       0
Bank Sta=4991.6,5011.8
XS Rating Curve= 0 ,0
Exp/Cntr=0.3,0.1

Type RM Length L Ch R = 1 ,48106   ,376,376,376
BEGIN DESCRIPTION:
NORTH MINERAL CREEK 63 0
END DESCRIPTION:
XS GIS Cut Line= 4
      3493156.67     10390728.73      3493088.97     10390489.19
      3492838.97      10390374.6      3492465.51     10390509.46
#Sta/Elev= 30
  4632.9  461.36  4640.3  460.75  4672.3  459.69  4774.3  457.13  4908.9  453.79
  4931.9  452.77  4937.4  450.88  4944.4  450.88  4954.9  452.67  4966.4  451.27
  4983.4  447.67  4988.9  443.57  4997.4  441.31  4997.6  440.81  5001.1  440.81
  5001.4  441.31  5011.9  444.71  5029.4  448.39  5034.9  451.36  5043.4  453.08
  5052.4  454.34  5065.4  455.37  5103.9  457.07  5156.8  457.71  5206.7  459.37
  5247.5  460.11  5259.8  460.77  5278.2  460.62  5324.2  461.36  5553.9  467.28
#Mann= 5 ,-1 , 0
  4632.9     .05       0  4774.3     .12       0  4988.9     .07       0
  5011.9     .12       0  5324.2     .16       0
Bank Sta=4988.9,5011.9
XS Rating Curve= 0 ,0
Exp/Cntr=0.3,0.1

Type RM Length L Ch R = 1 ,47730   ,316,316,316
BEGIN DESCRIPTION:
NORTH MINERAL CREEK 62 0
END DESCRIPTION:
XS GIS Cut Line= 5
       3493173.6     10390547.76      3493119.35     10390215.75
      3492921.87      10390081.2      3492850.25     10390066.01
      3492338.11     10390154.98
#Sta/Elev= 30
  4474.2  456.75  4712.2  452.08    4754  451.05  4760.8  449.58  4813.8  450.27
    4883  450.04  4904.1  448.89  4912.9  446.87  4918.9  448.53  4927.8  446.49
  4933.8  446.95  4940.4  444.23  4954.8  440.84  4969.7  440.25  4976.7  441.65
  4984.7  439.08  5003.9  438.09    5013  440.13  5041.6  440.74  5059.6  443.48
  5068.1  445.26  5090.2  451.69  5121.3  455.17  5141.2  455.22  5174.2  448.43
  5232.5  448.62    5263  452.12  5323.4   453.9  5538.8  461.72  5642.6  464.01
#Mann= 7 ,-1 , 0
  4474.2     .05       0  4712.2     .16       0  4813.8     .12       0
  4940.4     .07       0  5068.1     .12       0  5174.2     .16       0
  5323.4     .05       0
#XS Ineff= 2 , 0
       0                 5132.58       0  455.58
Permanent Ineff=
       F       T
Bank Sta=4940.4,5059.6
XS Rating Curve= 0 ,0
Exp/Cntr=0.3,0.1

Type RM Length L Ch R = 1 ,47414   ,678,678,678
BEGIN DESCRIPTION:
NORTH MINERAL CREEK 60 0
END DESCRIPTION:
XS GIS Cut Line= 3
      3493206.72     10390456.92      3493197.11     10390021.93
      3493253.46     10389725.84
#Sta/Elev= 30
  4564.9  454.93  4706.3  452.44  4804.6  450.46  4830.2  450.15  4850.3   448.5
  4880.3  448.68  4920.3  447.79  4950.3  445.06  4960.3  442.13  4970.3  440.43
  4980.3  440.11  4990.3  438.78  4995.6  437.11  4995.9  436.61  4999.4  436.61
  4999.6  437.11  5002.7  437.11  5020.7  442.96    5041  446.61  5054.9  446.71
  5071.5  448.19  5081.7  447.88    5102  450.22  5107.1  449.69    5153  453.92
  5164.4  454.05  5183.5  456.64  5227.3  460.13  5268.7  462.62  5301.4  465.46
#Mann= 6 ,-1 , 0
  4564.9     .05       0  4706.3     .16       0  4804.6     .12       0
  4995.6     .07       0  4999.6     .12       0  5227.3     .16       0
Bank Sta=4960.3,5020.7
XS Rating Curve= 0 ,0
Exp/Cntr=0.3,0.1

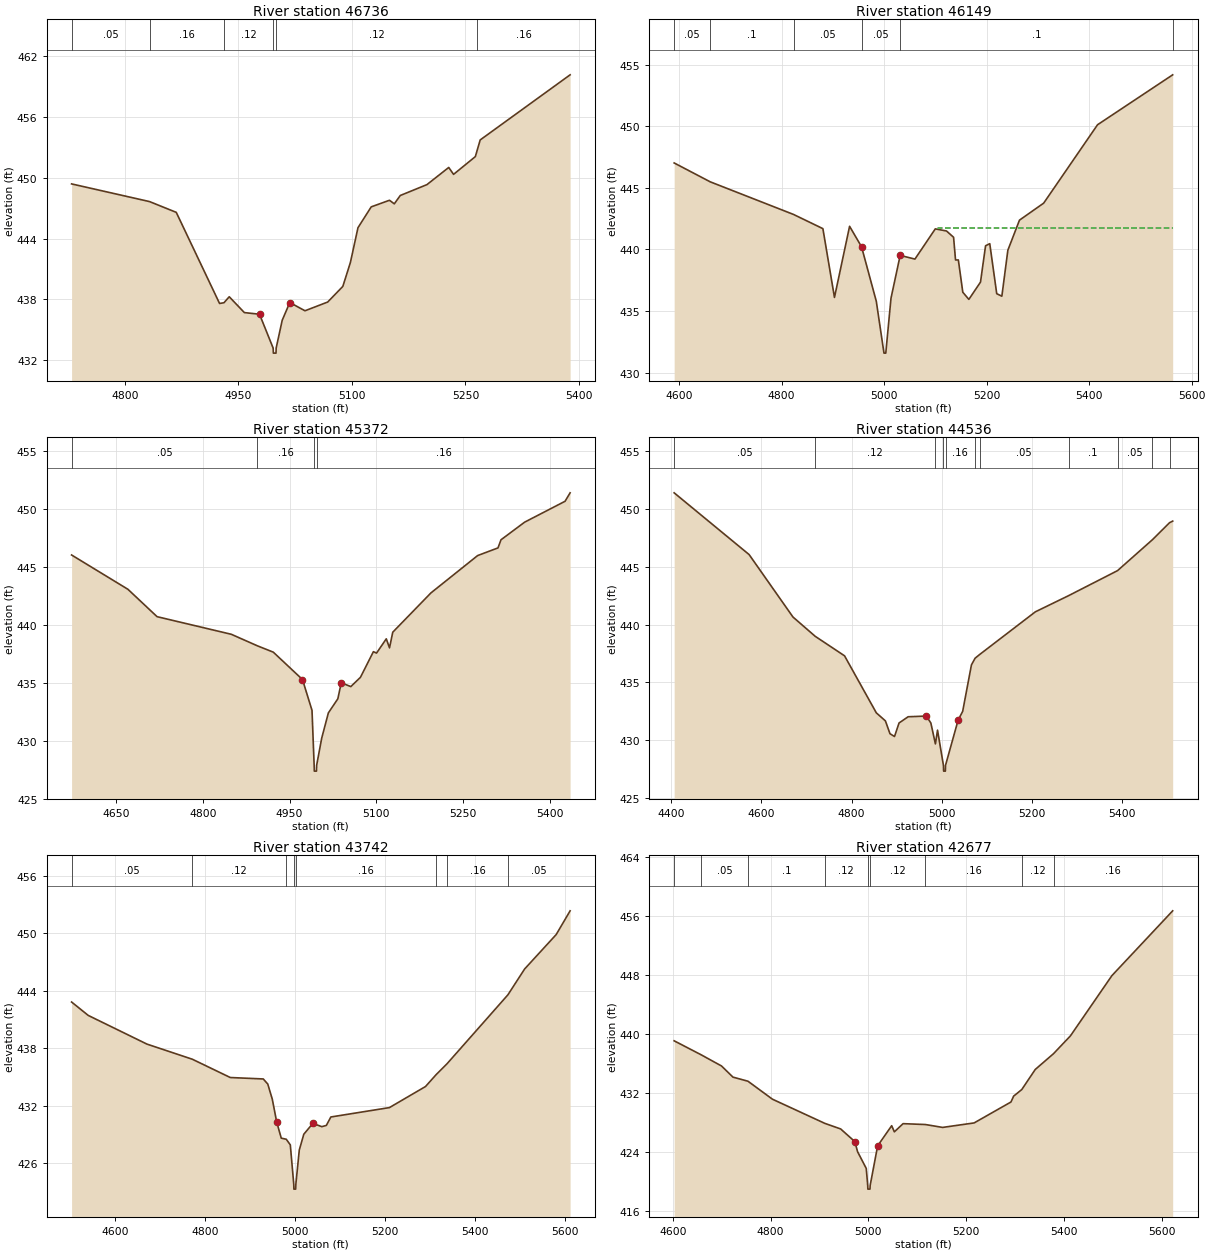
Type RM Length L Ch R = 1 ,46736   ,587,587,587
BEGIN DESCRIPTION:
NORTH MINERAL CREEK 6 0
END DESCRIPTION:
XS GIS Cut Line= 3
      3493652.03      10390239.9      3493642.11     10389841.64
      3493478.44     10389639.21
#Sta/Elev= 30
  4729.7  449.38  4832.7  447.64    4868  446.58  4925.2  437.61    4931  437.68
    4938  438.27    4958  436.71    4978  436.55    4996  433.22  4996.3  432.72
  4999.8  432.72    5000  433.22    5008  435.96    5018   437.7  5038.1  436.89
  5068.1  437.75  5088.1  439.29  5098.1  441.65  5108.1  445.07  5125.6  447.12
  5149.7  447.77  5156.1  447.42    5164  448.24  5199.2  449.31    5228     451
  5234.4  450.32  5263.2  452.07  5265.6  452.69  5269.6  453.71  5388.4  460.12
#Mann= 6 ,-1 , 0
  4729.7     .05       0  4832.7     .16       0    4931     .12       0
    4996     .07       0    5000     .12       0  5265.6     .16       0
Bank Sta=4978,5018
XS Rating Curve= 0 ,0
Exp/Cntr=0.3,0.1

Type RM Length L Ch R = 1 ,46149   ,777,777,777
BEGIN DESCRIPTION:
NORTH MINERAL CREEK 59 0
END DESCRIPTION:
XS GIS Cut Line= 3
      3493968.02     10390437.76      3494190.23     10389934.32
      3494356.62     10389546.07
#Sta/Elev= 30
  4590.3  447.02  4660.6  445.49  4823.3  442.84  4880.5  441.69  4903.1  436.11
  4932.6  441.88  4955.9  440.22  4984.7   435.8  4999.7  431.59  5003.2  431.59
  5013.4  436.05  5031.3  439.52  5060.1  439.22  5099.8  441.67  5121.7   441.5
  5135.5  440.99  5139.3  439.15  5144.8  439.15  5153.5  436.53  5165.3  435.95
    5188  437.35  5197.9   440.3  5206.1  440.47  5219.7  436.41  5229.7  436.21
  5241.4  439.94  5264.1  442.38  5311.3  443.76  5416.4  450.12    5563  454.17
#Mann= 6 ,-1 , 0
  4590.3     .05       0  4660.6      .1       0  4823.3     .05       0
  4955.9     .05       0  5031.3      .1       0    5563      .1       0
#XS Ineff= 2 , 0
         4932.94  441.85 5105.67          441.74
Permanent Ineff=
       F       F
Bank Sta=4955.9,5031.3
XS Rating Curve= 0 ,0
Exp/Cntr=0.3,0.1

Type RM Length L Ch R = 1 ,45372   ,836,836,836
BEGIN DESCRIPTION:
NORTH MINERAL CREEK 58 0
END DESCRIPTION:
XS GIS Cut Line= 3
      3494500.79      10390378.8       3494752.1     10389877.48
      3494675.55     10389585.54
#Sta/Elev= 30
  4572.9  446.03  4670.4  443.07  4720.8  440.71  4849.3  439.19  4894.2   438.2
  4921.9  437.65  4972.4  435.29  4988.9  432.63  4992.6  427.89  4992.9  427.39
  4996.6  427.39  4996.9  427.89  5005.7  430.24  5017.2  432.41  5033.6  433.63
  5039.5  435.01    5056  434.68  5072.7  435.48  5095.1  437.69  5100.6  437.57
  5117.4   438.8    5123  438.02  5128.6  439.37  5194.7  442.76  5275.5  445.98
  5310.7  446.64  5315.9  447.34  5356.8  448.86  5426.7  450.66  5435.5  451.39
#Mann= 4 ,-1 , 0
  4572.9     .05       0  4894.2     .16       0  4992.6     .07       0
  4996.9     .16       0
Bank Sta=4972.4,5039.5
XS Rating Curve= 0 ,0
Exp/Cntr=0.3,0.1

Type RM Length L Ch R = 1 ,44536   ,794,794,794
BEGIN DESCRIPTION:
NORTH MINERAL CREEK 56 0
END DESCRIPTION:
XS GIS Cut Line= 3
      3495113.84     10390576.64      3495228.42     10389670.43
      3495336.05     10389510.73
#Sta/Elev= 30
  4406.5  451.41  4572.8  446.06  4670.1  440.65  4719.4  438.98  4784.5  437.29
    4855  432.35  4875.2  431.65  4885.3  430.54  4895.4   430.3  4905.4  431.47
  4925.6  432.01  4965.9  432.07    4976  431.47  4986.1  429.66  4990.8  430.85
  5003.9   427.8  5004.3   427.3  5008.2   427.3  5008.5   427.8  5036.5  431.72
  5046.6  432.48    5066   436.5  5074.1  437.08  5084.5  437.41  5207.8   441.1
  5281.5   442.5  5390.2  444.67  5467.6  447.35  5505.5  448.82  5512.5  448.96
#Mann= 11 ,-1 , 0
  4406.5     .05       0  4719.4     .12       0  4986.1     .16       0
  5003.9     .07       0  5008.5     .16       0  5074.1     .12       0
  5084.5     .05       0  5281.5      .1       0  5390.2     .05       0
  5467.6      .1       0  5505.5     .05       0
Bank Sta=4965.9,5036.5
XS Rating Curve= 0 ,0
Exp/Cntr=0.3,0.1

Type RM Length L Ch R = 1 ,43742   ,1065,1065,1065
BEGIN DESCRIPTION:
NORTH MINERAL CREEK 55 0
END DESCRIPTION:
XS GIS Cut Line= 3
      3495529.44     10390541.55      3495720.85     10390242.06
      3495677.88     10389490.73
#Sta/Elev= 30
  4503.1  442.82  4540.2  441.42  4670.5  438.43  4771.4  436.85  4855.8  434.94
  4929.1  434.79  4939.1  434.26  4949.1  432.69  4959.1  430.27  4969.1  428.61
  4980.1   428.5  4989.2  427.91  4996.9  423.79  4997.2  423.29  5001.1  423.29
  5001.5  423.79  5009.2  427.38  5019.2  429.02  5039.3  430.15  5059.3  429.81
  5069.3  429.94  5079.3  430.82  5209.5   431.8  5289.7     434  5313.5  435.25
  5337.4  436.37  5472.8  443.57    5510  446.27  5580.1  449.86  5611.1  452.34
#Mann= 8 ,-1 , 0
  4503.1     .05       0  4771.4     .12       0  4980.1     .16       0
  4996.9     .07       0  5001.5     .16       0  5313.5     .05       0
  5337.4     .16       0  5472.8     .05       0
Bank Sta=4959.1,5039.3
XS Rating Curve= 0 ,0
Exp/Cntr=0.3,0.1

Type RM Length L Ch R = 1 ,42677   ,868,868,868
BEGIN DESCRIPTION:
NORTH MINERAL CREEK 54 0
END DESCRIPTION:
XS GIS Cut Line= 3
      3496537.28     10390203.04      3496246.89     10389546.75
      3496012.55     10389356.68
#Sta/Elev= 30
  4602.9   439.1  4658.1   437.2  4699.8  435.68  4723.1  434.17  4753.9  433.61
  4803.9  431.17    4911  427.89  4943.4  427.13  4972.4  425.41  4977.9  424.05
  4995.7  421.77  4998.7  419.46    4999  418.96  5003.3  418.96  5003.7  419.46
    5019  424.84  5047.7  427.57  5053.2  426.74    5071  427.85  5116.8  427.73
  5151.8  427.34  5216.3  427.95  5291.6  430.79  5297.1  431.59  5313.7  432.48
  5341.3  435.21  5378.6  437.35  5413.2  439.77    5498  447.95  5622.3  456.75
#Mann= 9 ,-1 , 0
  4602.9     .16       0  4658.1     .05       0  4753.9      .1       0
    4911     .12       0  4998.7     .07       0  5003.7     .12       0
  5116.8     .16       0  5313.7     .12       0  5378.6     .16       0
Bank Sta=4972.4,5019
XS Rating Curve= 0 ,0
Exp/Cntr=0.3,0.1

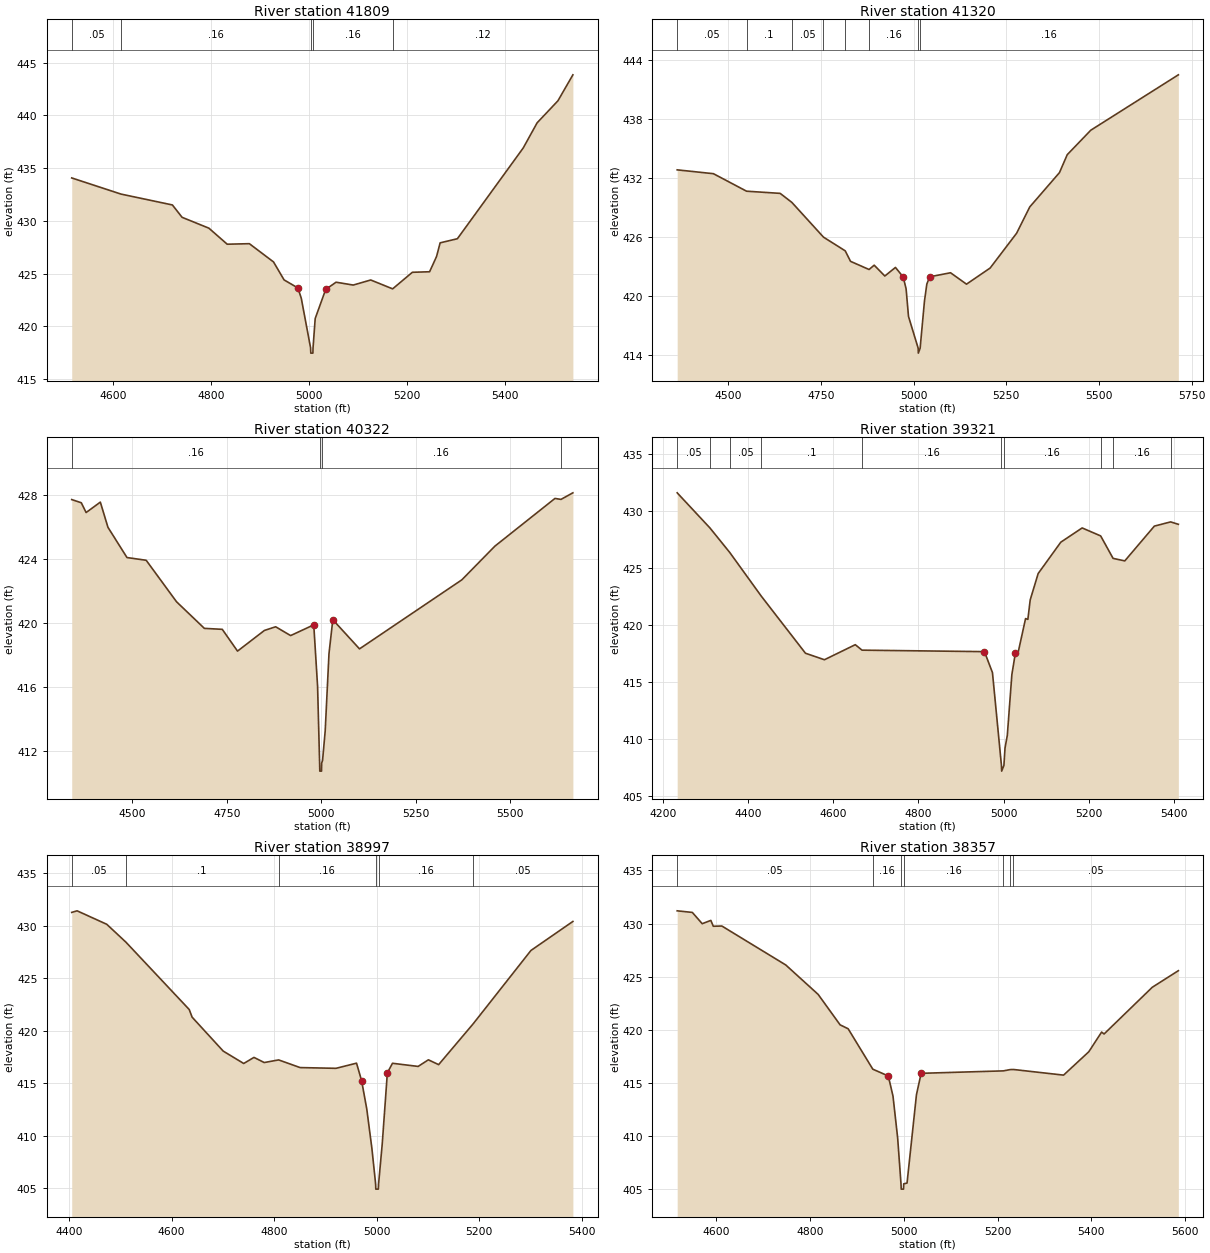
Type RM Length L Ch R = 1 ,41809   ,489,489,489
BEGIN DESCRIPTION:
NORTH MINERAL CREEK 53 0
END DESCRIPTION:
XS GIS Cut Line= 3
      3497064.61      10389874.9      3496947.41     10389549.36
      3496455.05     10389085.57
#Sta/Elev= 30
  4516.3  434.07  4616.8  432.54  4721.7  431.51  4741.4  430.34  4796.1  429.31
  4833.5  427.79  4878.7  427.84    4928  426.11  4949.5  424.41  4977.8  423.64
  4984.6  422.67  5003.6  417.97    5004  417.47  5008.3  417.47  5008.6  417.97
    5013  420.75  5034.4   423.5  5055.5  424.19  5090.6  423.92  5126.3   424.4
    5171  423.56  5211.2  425.13  5246.4  425.18  5260.6  426.63  5267.9  427.92
  5303.1  428.31  5437.4  436.91  5465.7  439.29  5508.2  441.38  5538.7  443.84
#Mann= 5 ,-1 , 0
  4516.3     .05       0  4616.8     .16       0  5003.6     .07       0
  5008.6     .16       0    5171     .12       0
Bank Sta=4977.8,5034.4
XS Rating Curve= 0 ,0
Exp/Cntr=0.3,0.1

Type RM Length L Ch R = 1 ,41320   ,998,998,998
BEGIN DESCRIPTION:
NORTH MINERAL CREEK 51 0
END DESCRIPTION:
XS GIS Cut Line= 4
      3497459.12     10389781.09       3497313.3      10389450.4
      3496891.42     10388936.07      3496783.34     10388628.76
#Sta/Elev= 30
  4361.8  432.83  4459.6  432.44    4549  430.66  4639.7  430.44  4671.3  429.52
  4756.6  425.99  4815.2   424.6  4829.6  423.53  4879.6   422.7  4893.4  423.14
  4922.1  422.04  4950.8  422.91  4971.7  421.94  4979.5  420.74    4986  417.93
  5012.1   414.7  5012.5   414.2  5017.4   414.7  5029.1   419.5  5035.5  421.23
  5043.4  421.96  5099.4  422.37  5142.5  421.21  5206.3  422.85  5277.8  426.39
  5313.2  429.06  5393.4  432.55  5414.3  434.37  5477.9  436.86  5714.2  442.49
#Mann= 8 ,-1 , 0
  4361.8     .05       0    4549      .1       0  4671.3     .05       0
  4756.6     .16       0  4815.2      .1       0  4879.6     .16       0
  5012.1     .07       0  5017.4     .16       0
Bank Sta=4971.7,5043.4
XS Rating Curve= 0 ,0
Exp/Cntr=0.3,0.1

Type RM Length L Ch R = 1 ,40322   ,1001,1001,1001
BEGIN DESCRIPTION:
NORTH MINERAL CREEK 49 0
END DESCRIPTION:
XS GIS Cut Line= 3
      3497741.69     10389606.69       3497623.2     10388687.38
      3497525.53     10388300.64
#Sta/Elev= 30
    4340   427.7  4365.3   427.5  4378.1  426.89  4415.7  427.54  4435.8  425.97
  4486.2  424.08    4537  423.91  4617.3  421.32  4690.9  419.66  4738.3   419.6
  4778.6  418.24  4849.7  419.53  4879.5  419.76  4919.1  419.21  4980.3  419.88
  4990.4  416.05  4995.8  411.25  4996.3  410.75  5000.8  410.75  5001.2  411.25
  5003.6  411.42  5010.6  413.28  5020.6  418.09  5030.7   420.2  5101.3  418.38
  5372.1  422.69  5459.4  424.79  5618.4  427.77  5634.3  427.71  5665.8  428.12
#Mann= 4 ,-1 , 0
    4340     .16       0  4995.8     .07       0  5001.2     .16       0
  5634.3     .05       0
Bank Sta=4980.3,5030.7
XS Rating Curve= 0 ,0
Exp/Cntr=0.3,0.1

Type RM Length L Ch R = 1 ,39321   ,324,324,324
BEGIN DESCRIPTION:
NORTH MINERAL CREEK 48 0
END DESCRIPTION:
XS GIS Cut Line= 4
      3498291.16     10389438.68      3498205.23     10389243.37
      3497965.64     10388648.31      3497943.55     10388326.02
#Sta/Elev= 30
    4233  431.63  4310.2  428.54  4356.5   426.4  4430.6  422.57  4534.5  417.56
  4579.1  416.99  4651.6  418.31  4667.4  417.83  4955.2   417.7    4974  415.86
  4995.1  407.72  4995.6  407.22  5000.9  407.72  5003.5  409.24  5008.9  410.36
  5019.6  415.69  5027.7  417.54  5033.1  417.42  5051.8   420.6  5057.2  420.53
  5062.7  422.24  5081.4  424.55  5134.6   427.3  5184.8  428.55  5228.3  427.85
  5257.5  425.88    5285  425.66  5354.5  428.71  5392.8  429.08  5410.9  428.87
#Mann= 10 ,-1 , 0
    4233     .05       0  4310.2      .1       0  4356.5     .05       0
  4430.6      .1       0  4667.4     .16       0  4995.1     .07       0
  5000.9     .16       0  5228.3     .05       0  5257.5     .16       0
  5392.8     .05       0
Bank Sta=4955.2,5027.7
XS Rating Curve= 0 ,0
Exp/Cntr=0.3,0.1

Type RM Length L Ch R = 1 ,38997   ,640,640,640
BEGIN DESCRIPTION:
NORTH MINERAL CREEK 47 0
END DESCRIPTION:
XS GIS Cut Line= 3
      3498319.81     10389437.36       3498250.8     10389195.19
      3498267.73      10388469.9
#Sta/Elev= 30
  4405.4  431.25  4415.9   431.4  4473.7  430.12  4510.9  428.43  4634.6  422.01
  4640.1  421.29  4700.8  418.06  4740.8  416.88  4760.8  417.46  4780.8  416.97
  4808.9  417.22  4850.8  416.49  4920.8  416.42  4960.8  416.91  4970.8  415.22
  4980.8  412.54  4990.8  408.78    4998  405.43  4998.4  404.93  5003.3  404.93
  5003.8  405.43  5010.9  409.22  5020.9  415.99  5030.9   416.9  5080.9   416.6
  5100.9  417.23  5120.9  416.77  5188.2  420.65  5300.9  427.63  5382.7  430.39
#Mann= 6 ,-1 , 0
  4405.4     .05       0  4510.9      .1       0  4808.9     .16       0
    4998     .07       0  5003.8     .16       0  5188.2     .05       0
Bank Sta=4970.8,5020.9
XS Rating Curve= 0 ,0
Exp/Cntr=0.3,0.1

Type RM Length L Ch R = 1 ,38357   ,786,786,786
BEGIN DESCRIPTION:
NORTH MINERAL CREEK 46 0
END DESCRIPTION:
XS GIS Cut Line= 4
      3498454.11      10389552.4      3498579.12     10389166.96
      3498596.48     10388830.16      3498499.26     10388517.69
#Sta/Elev= 30
  4516.1   431.2  4548.4  431.05  4569.5  429.99  4587.9   430.3  4593.2  429.75
  4611.5  429.77  4747.8  426.11    4817  423.34  4863.8  420.48    4881  420.11
  4933.6  416.31  4966.7  415.67  4976.7  413.78  4986.7  409.83  4993.8  405.53
  4994.3  405.03  4999.2  405.03  4999.6  405.53  5006.7   405.6  5026.8  413.91
  5036.8  415.92  5212.4  416.15  5226.8  416.27  5233.9  416.28  5340.8  415.75
  5394.7  417.95    5422   419.8  5427.3  419.62  5530.1  424.01  5585.8  425.57
#Mann= 7 ,-1 , 0
  4516.1     .05       0  4933.6     .16       0  4993.8     .07       0
  4999.6     .16       0  5212.4     .05       0  5226.8     .16       0
  5233.9     .05       0
Bank Sta=4966.7,5036.8
XS Rating Curve= 0 ,0
Exp/Cntr=0.3,0.1

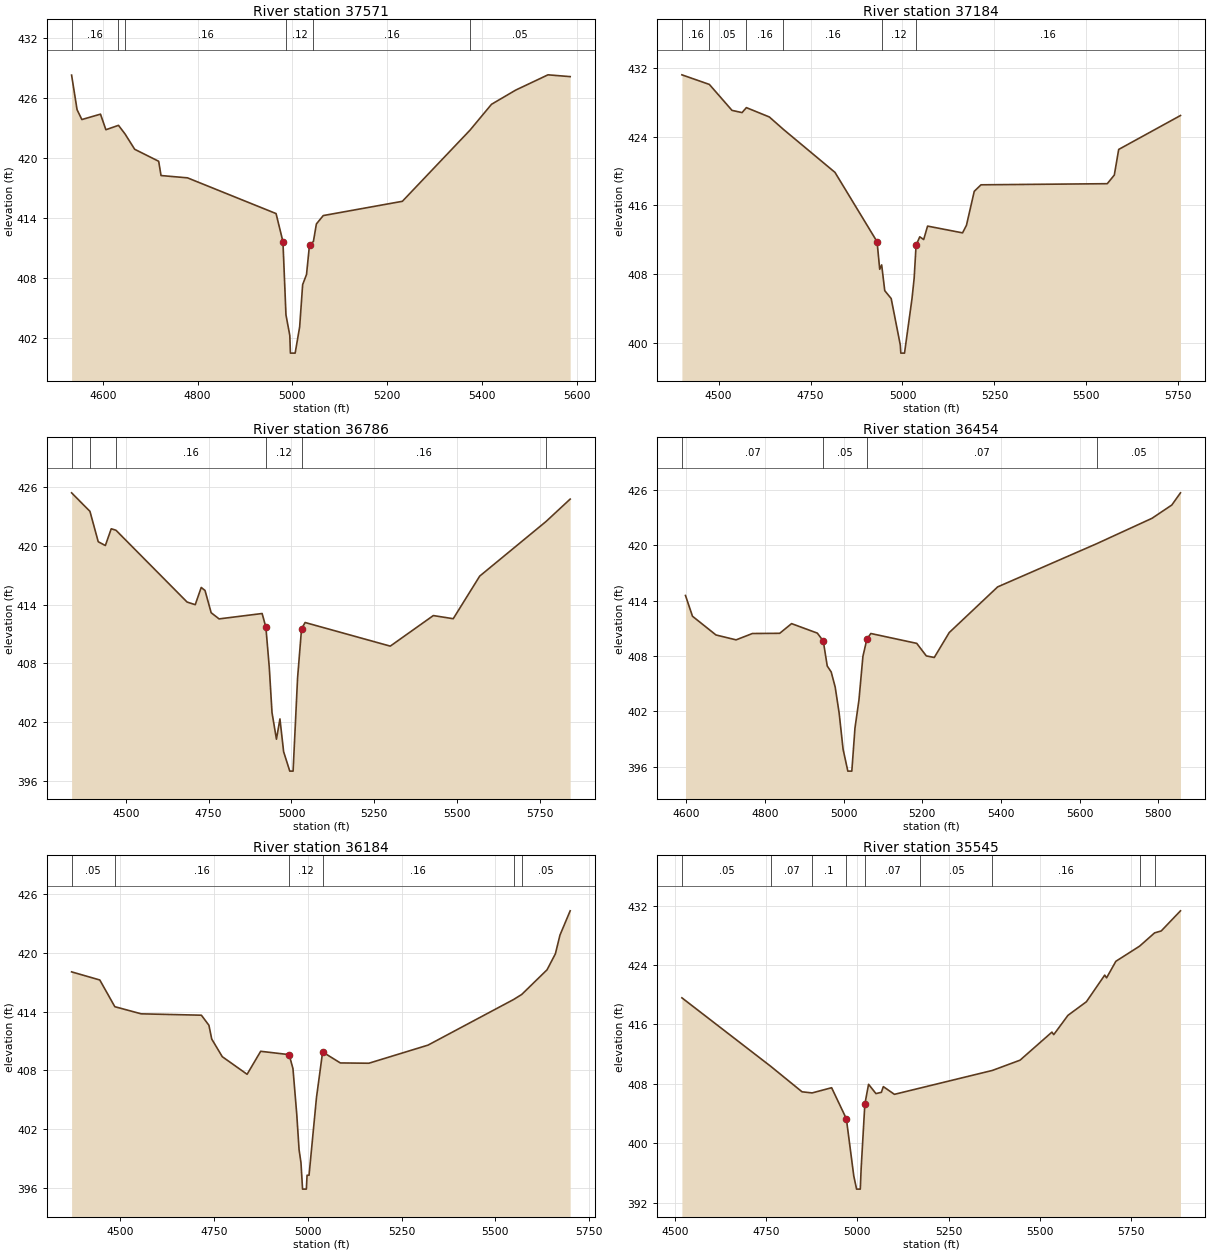
Type RM Length L Ch R = 1 ,37571   ,387,387,387
BEGIN DESCRIPTION:
NORTH MINERAL CREEK 45 0
END DESCRIPTION:
XS GIS Cut Line= 4
      3498766.62     10389653.05      3498829.12     10389271.13
      3498999.25     10389052.38      3499165.92     10388701.69
#Sta/Elev= 30
    4534  428.31  4545.6  424.84  4555.7  423.86    4595   424.4  4606.4  422.84
    4633  423.28  4646.9  422.41  4667.2  420.88  4717.8  419.68  4722.8  418.25
  4778.6  418.02  4965.6  414.44  4980.1  411.63  4986.5  404.29  4994.6  402.23
  4995.9  400.46  5005.9  400.46  5015.4  403.09  5021.7  407.32  5029.9  408.34
  5036.2  411.31  5044.4  411.64  5050.7   413.4  5065.2  414.24  5232.2  415.67
    5375   422.8  5420.4  425.39  5471.4  426.81  5539.6  428.34  5586.4  428.16
#Mann= 6 ,-1 , 0
    4534     .16       0    4633     .05       0  4646.9     .16       0
  4986.5     .12       0  5044.4     .16       0    5375     .05       0
Bank Sta=4980.1,5036.2
XS Rating Curve= 0 ,0
Exp/Cntr=0.3,0.1

Type RM Length L Ch R = 1 ,37184   ,398,398,398
BEGIN DESCRIPTION:
NORTH MINERAL CREEK 44 0
END DESCRIPTION:
XS GIS Cut Line= 4
      3499043.53     10389933.01      3499182.41     10389426.08
      3499418.53     10388742.05      3499439.36     10388637.86
#Sta/Elev= 30
  4400.3  431.25  4474.9  430.13  4536.5   427.1  4563.8  426.84  4575.6  427.42
    4638  426.33  4676.3  424.88  4816.5  419.86  4930.9  411.77  4938.1  408.55
  4943.4  409.06  4951.8  406.05  4969.3  405.13  4994.1   399.7  4995.5  398.76
  5005.5  398.76  5025.8   405.1  5031.7  407.49    5037  411.37    5047  412.34
  5057.6  412.02  5068.2  413.59  5163.3   412.8  5173.9  413.68  5195.1  417.65
  5213.5  418.41  5556.7  418.54  5575.9  419.55  5587.8  422.54  5755.8   426.5
#Mann= 6 ,-1 , 0
  4400.3     .16       0  4474.9     .05       0  4575.6     .16       0
  4676.3     .16       0  4943.4     .12       0    5037     .16       0
Bank Sta=4930.9,5037
XS Rating Curve= 0 ,0
Exp/Cntr=0.3,0.1

Type RM Length L Ch R = 1 ,36786   ,332,332,332
BEGIN DESCRIPTION:
NORTH MINERAL CREEK 42 0
END DESCRIPTION:
XS GIS Cut Line= 4
      3499323.36     10390076.67      3499461.67     10389718.41
      3499619.41     10389336.25      3499643.68     10388628.73
#Sta/Elev= 30
  4336.1  425.42  4391.5  423.53  4416.5  420.43    4438  420.04  4455.8  421.75
  4470.1   421.6  4684.8  414.27  4709.4     414  4727.5  415.76    4739  415.45
  4757.5  413.18  4781.5  412.55  4911.4   413.1  4922.7  411.71    4933   407.6
  4941.2     403  4954.6  400.27  4965.2  402.34  4976.3  398.99  4994.9  397.01
  5004.9  397.01  5018.4   406.5  5030.4  411.54  5041.2  412.18  5298.3  409.77
  5428.3  412.89  5488.4  412.57  5568.4  416.92  5768.5  422.49  5841.5  424.78
#Mann= 6 ,-1 , 0
  4336.1     .16       0  4391.5     .05       0  4470.1     .16       0
  4922.7     .12       0  5030.4     .16       0  5768.5     .05       0
Bank Sta=4922.7,5030.4
XS Rating Curve= 0 ,0
Exp/Cntr=0.3,0.1

Type RM Length L Ch R = 1 ,36454   ,270,270,270
BEGIN DESCRIPTION:
NORTH MINERAL CREEK 41 1
END DESCRIPTION:
XS GIS Cut Line= 3
3499886.7924896410389779.3544114      3499798.74     10389040.98
      3499742.64     10388529.75
#Sta/Elev= 30
  4598.3  414.56  4616.1  412.31  4675.8  410.28  4726.9  409.75  4768.4  410.44
  4837.7  410.46  4867.9  411.51  4933.4  410.48  4948.5  409.62  4958.5  406.92
  4968.6  406.27  4978.7  404.64  4988.8  401.81  4998.8  397.89  5010.9  395.52
    5021  395.52    5029  400.19  5039.1  403.22  5049.2  407.96  5059.3  409.83
  5069.3  410.44    5186  409.37  5210.3  408.01  5230.5  407.84  5268.5  410.54
  5391.5  415.49    5643  420.17  5783.9  422.93  5834.2  424.37  5856.2  425.69
#Mann= 4 ,-1 , 0
  4589.2     .07       0  4948.5     .05       0  5059.3     .07       0
    5643     .05       0
Bank Sta=4948.5,5059.3
XS Rating Curve= 0 ,0
Exp/Cntr=0.3,0.1

Type RM Length L Ch R = 1 ,36184   ,639,639,639
BEGIN DESCRIPTION:
NORTH MINERAL CREEK 41 2
END DESCRIPTION:
XS GIS Cut Line= 5
      3499960.14     10390116.53      3499992.11     10389741.64
      3500041.42     10389492.94      3500192.11     10389141.64
      3500330.99     10388856.18
#Sta/Elev= 30
  4370.2  418.07  4445.4  417.24  4485.5  414.51  4555.8  413.78  4716.3  413.64
  4736.4  412.61  4743.9   411.2    4772   409.4  4838.2   407.6  4874.4  409.95
  4950.3  409.61  4960.5  408.18  4970.7  403.47  4976.8  399.89  4981.9  398.55
  4986.1  395.86  4996.2  395.86  4998.1  397.28  5003.4  397.28  5023.2  405.22
  5039.6  409.88  5086.8  408.76  5162.9  408.73  5320.6  410.58  5548.6  415.24
  5570.5  415.76    5638  418.28  5660.3  419.92  5672.5  421.83  5699.7  424.31
#Mann= 6 ,-1 , 0
  4370.2     .05       0  4485.5     .16       0  4950.3     .12       0
  5039.6     .16       0  5548.6      .1       0  5570.5     .05       0
Bank Sta=4950.3,5039.6
XS Rating Curve= 0 ,0
Exp/Cntr=0.3,0.1

Type RM Length L Ch R = 1 ,35545   ,759,759,759
BEGIN DESCRIPTION:
NORTH MINERAL CREEK 40 0
END DESCRIPTION:
XS GIS Cut Line= 3
      3500513.14     10390076.73      3500652.03     10389184.32
      3500714.49     10388726.31
#Sta/Elev= 30
  4519.7  419.58  4763.3  410.34  4848.7  406.92  4876.3  406.77  4929.7  407.47
  4970.1  403.29  4990.4  395.58  4998.1  393.81  5008.2  393.81  5010.6   396.6
  5020.7  405.26  5030.9  407.93  5051.1  406.68    5066  406.85  5071.3  407.62
  5101.7  406.58  5172.5  407.43    5370   409.8  5445.7  411.18    5533  414.96
    5538  414.62  5576.9  417.22  5627.4  419.05  5677.6  422.64  5682.7  422.27
  5708.1   424.5  5773.1  426.54  5814.2  428.33  5832.4  428.59  5885.1   431.3
#Mann= 9 ,-1 , 0
  4519.7     .05       0  4763.3     .07       0  4876.3      .1       0
  4970.1     .03       0  5020.7     .07       0  5172.5     .05       0
    5370     .16       0  5773.1     .05       0  5814.2     .16       0
Bank Sta=4970.1,5020.7
XS Rating Curve= 0 ,0
Exp/Cntr=0.3,0.1

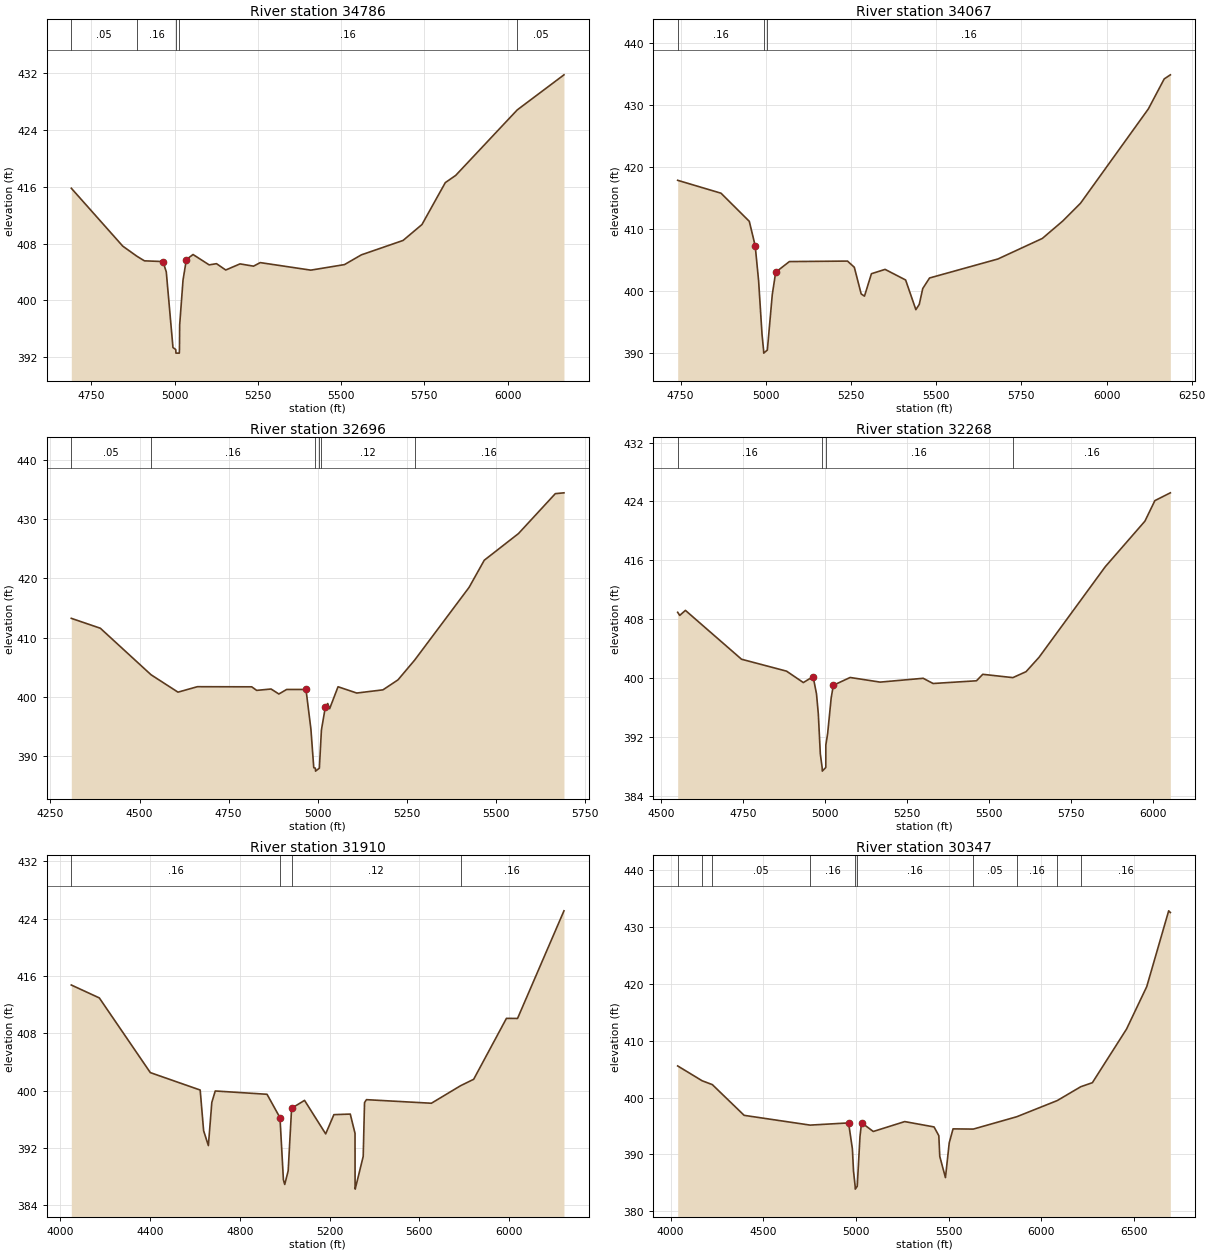
Type RM Length L Ch R = 1 ,34786   ,719,719,719
BEGIN DESCRIPTION:
NORTH MINERAL CREEK 4 0
END DESCRIPTION:
XS GIS Cut Line= 3
      3501224.95     10390045.39      3501270.09     10389600.99
      3501113.84     10388580.16
#Sta/Elev= 30
  4689.9   415.8  4844.4  407.65  4887.4  406.21  4909.5  405.58  4965.1  405.48
  4975.1  404.03  4995.2  393.38  5003.6  393.09  5004.1  392.59  5014.2  392.59
  5014.7  393.09  5015.3  396.54  5025.4  402.87  5035.4  405.76  5055.5  406.47
  5103.9  405.01  5125.9  405.18  5153.7  404.29  5196.6  405.15  5237.1  404.83
  5257.3  405.33  5409.1  404.27  5510.2  405.05  5560.8  406.42  5686.2  408.45
  5742.9  410.69    5813  416.59  5844.1   417.6  6028.9  426.82  6169.3  431.76
#Mann= 5 ,-1 , 0
  4689.9     .05       0  4887.4     .16       0  5003.6     .07       0
  5014.7     .16       0  6028.9     .05       0
Bank Sta=4965.1,5035.4
XS Rating Curve= 0 ,0
Exp/Cntr=0.3,0.1

Type RM Length L Ch R = 1 ,34067   ,1371,1371,1371
BEGIN DESCRIPTION:
NORTH MINERAL CREEK 39 0
END DESCRIPTION:
XS GIS Cut Line= 3
      3501790.92     10390118.39      3501825.64     10389673.91
      3501745.78     10388677.34
#Sta/Elev= 30
  4741.7  417.85  4868.8  415.77  4951.8  411.23  4969.1   407.3  4979.2   401.6
  4989.2  392.97  4993.7  390.45  4994.2  389.95  5004.8  390.45  5019.3  399.41
  5029.3  403.01  5069.4  404.73    5240  404.81    5260  403.81  5280.1  399.51
  5289.8  399.15  5310.2  402.77  5350.3  403.47  5410.5  401.76  5440.6  396.97
  5450.6  397.82  5460.7  400.37  5480.7  402.08  5681.4  405.15  5811.8  408.47
    5872   411.3  5923.7  414.15  6122.8  429.38  6169.3  434.22  6187.3  434.88
#Mann= 3 ,-1 , 0
  4741.7     .16       0  4993.7     .07       0  5004.8     .16       0
Bank Sta=4969.1,5029.3
XS Rating Curve= 0 ,0
Exp/Cntr=0.3,0.1

Type RM Length L Ch R = 1 ,32696   ,428,428,428
BEGIN DESCRIPTION:
NORTH MINERAL CREEK 38 0
END DESCRIPTION:
XS GIS Cut Line= 3
      3502122.81     10390086.62      3502448.33     10389328.82
      3502276.77     10388798.54
#Sta/Elev= 30
  4308.6  413.28  4390.1  411.61  4532.4  403.76  4607.9  400.83  4662.3  401.75
  4814.7  401.73  4828.6  401.13  4869.1  401.36  4890.9  400.52  4912.6  401.28
    4967  401.28  4980.8  394.59  4988.8  388.09  4993.3  388.01  4993.8  387.51
  5004.5  388.01  5010.3  394.45  5021.5  398.39  5027.9  398.91  5033.3  398.04
  5056.9  401.74  5109.4  400.68  5182.9  401.22    5225   402.9  5271.6  406.22
  5424.6  418.51  5467.1  423.08  5563.1  427.58  5666.4  434.31  5690.7  434.45
#Mann= 6 ,-1 , 0
  4308.6     .05       0  4532.4     .16       0  4993.3     .07       0
  5004.5     .16       0  5010.3     .12       0  5271.6     .16       0
Bank Sta=4967,5021.5
XS Rating Curve= 0 ,0
Exp/Cntr=0.3,0.1

Type RM Length L Ch R = 1 ,32268   ,358,358,358
BEGIN DESCRIPTION:
NORTH MINERAL CREEK 37 0
END DESCRIPTION:
XS GIS Cut Line= 3
      3502516.04     10390125.69      3502753.02     10389617.88
      3502628.27     10388684.86
#Sta/Elev= 30
  4551.1  408.93  4557.4  408.51  4574.7  409.19  4745.7  402.55  4882.9  400.93
  4934.1  399.38  4963.9  400.19  4974.3  397.82  4979.8   395.1  4985.9  389.69
  4991.4  387.84  4991.9  387.34  5002.6  387.84  5002.7  390.89  5008.2  392.44
    5019   397.3  5025.6  399.01  5076.8  400.07  5168.2  399.44  5299.4  399.96
  5329.6  399.25  5461.9  399.62    5481   400.5  5572.8  400.05    5613  400.86
  5652.5  402.81  5854.3  415.12  5975.3  421.32  6005.6  424.11  6052.8  425.17
#Mann= 4 ,-1 , 0
  4551.1     .16       0  4991.4     .07       0  5002.6     .16       0
  5572.8     .16       0
Bank Sta=4963.9,5025.6
XS Rating Curve= 0 ,0
Exp/Cntr=0.3,0.1

Type RM Length L Ch R = 1 ,31910   ,1563,1563,1563
BEGIN DESCRIPTION:
NORTH MINERAL CREEK 36 0
END DESCRIPTION:
XS GIS Cut Line= 3
      3502500.42     10390526.72      3502794.68     10390180.38
      3503721.69     10388706.54
#Sta/Elev= 30
  4048.6  414.73  4173.5  412.93  4400.8  402.52    4623  400.09  4638.3  394.42
  4659.5  392.35  4674.8  398.36  4690.1  399.96  4920.9   399.5  4978.6  396.24
  4993.9  387.58  4999.8  386.93  5015.1  388.83  5030.4  397.55  5088.1  398.65
  5182.3  393.98  5218.8  396.66  5291.8  396.74    5313  394.06  5313.3  386.78
  5313.8  386.28  5349.5  390.84  5355.4  398.34    5364  398.75  5653.4  398.25
  5783.2  400.69  5841.8  401.59  5987.8  410.08  6037.3  410.07  6244.2  425.07
#Mann= 4 ,-1 , 0
  4048.6     .16       0  4978.6     .07       0  5030.4     .12       0
  5783.2     .16       0
Bank Sta=4978.6,5030.4
XS Rating Curve= 0 ,0
Exp/Cntr=0.3,0.1

Type RM Length L Ch R = 1 ,30347   ,487,487,487
BEGIN DESCRIPTION:
NORTH MINERAL CREEK 34 0
END DESCRIPTION:
XS GIS Cut Line= 3
      3503120.23     10391193.37      3503333.74     10390932.99
      3503838.95     10388667.36
#Sta/Elev= 30
    4038  405.56  4169.9  402.95    4225  402.27  4396.6  396.86  4752.7  395.14
  4960.1  395.53  4980.6  390.95  4986.6  387.07  4995.5  384.37    4996  383.87
  5006.7  384.37  5021.6  393.15  5030.1  395.56  5093.3  394.02  5262.8  395.76
  5421.2  394.82  5446.9  393.28    5452  389.63  5482.6   385.9  5503.1  392.03
  5523.6  394.48  5632.7  394.44    5867  396.61  6085.7  399.46  6212.6   401.9
  6275.3  402.61  6459.4  412.04  6568.7  419.53    6687  432.87    6696  432.57
#Mann= 10 ,-1 , 0
    4038     .05       0  4169.9     .16       0    4225     .05       0
  4752.7     .16       0  4995.5     .07       0  5006.7     .16       0
  5632.7     .05       0    5867     .16       0  6085.7     .12       0
  6212.6     .16       0
Bank Sta=4960.1,5030.1
XS Rating Curve= 0 ,0
Exp/Cntr=0.3,0.1