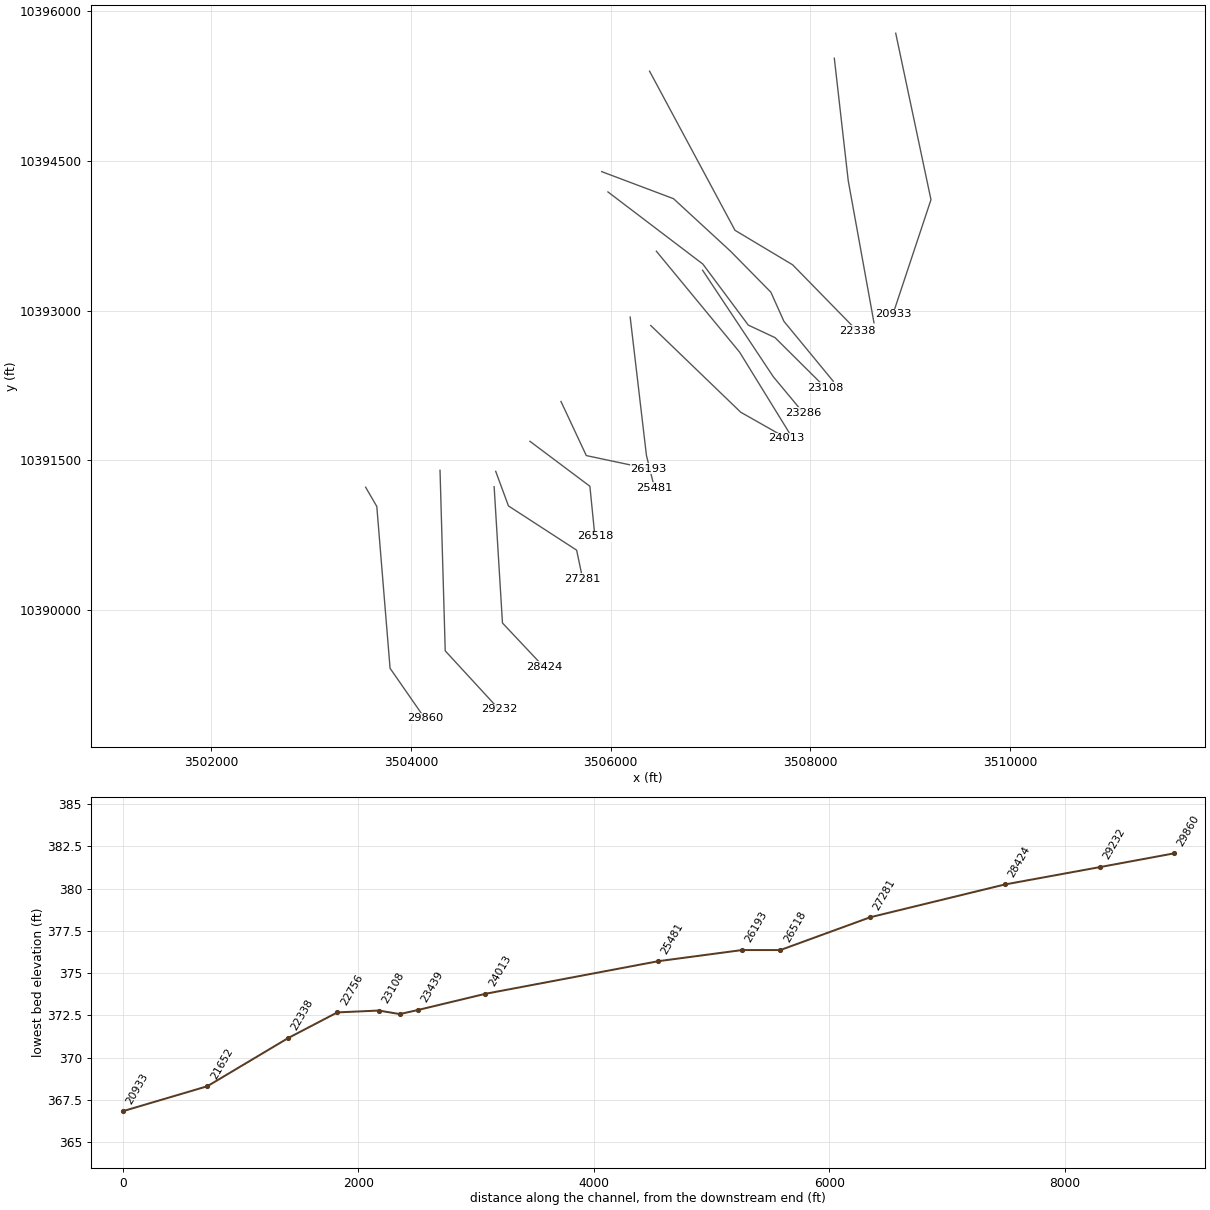
HEC-RAS study NORTH MINERAL CREEK.prj: NORTH MINERAL CREEK Base Level Engineering

--- NORTH MINERAL CREEK.g01 (geometry) --- (continued)

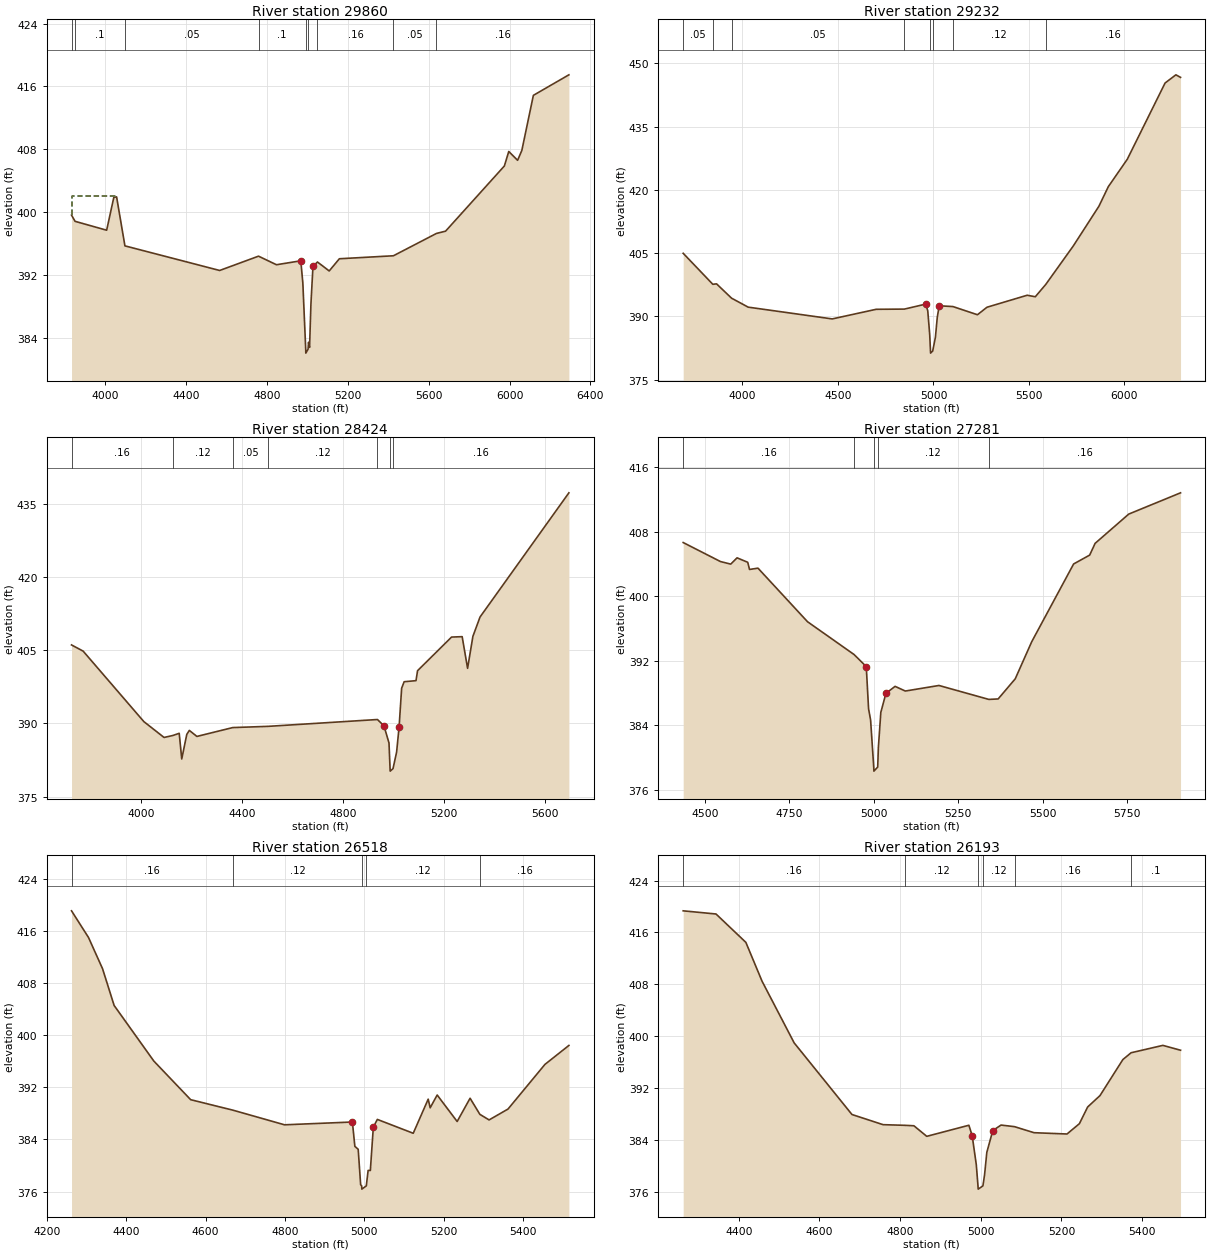
Type RM Length L Ch R = 1 ,29860   ,628,628,628
BEGIN DESCRIPTION:
NORTH MINERAL CREEK 32 0
END DESCRIPTION:
XS GIS Cut Line= 4
       3503547.3     10391232.44      3503659.27     10391039.76
      3503792.08     10389419.96      3504141.06     10388917.32
#Sta/Elev= 30
  3833.7  399.64  3851.2  398.85  4007.4  397.72  4042.8  401.89  4056.6  401.96
  4097.8  395.73  4566.4   392.6  4758.5  394.42  4847.3  393.33  4967.7  393.83
  4977.8  391.01    4992  382.59  4992.5  382.09  5003.6  382.59    5006  383.47
    5011  382.82  5017.9  388.41  5027.9  393.11    5050  393.68  5108.2  392.54
  5158.4  394.09  5425.8  394.47  5638.7  397.31  5683.8   397.6  5974.6  405.89
  5996.3  407.73  6040.1  406.61    6061  407.87    6118  414.87  6293.7  417.48
#Mann= 9 ,-1 , 0
  3833.7     .16       0  3851.2      .1       0  4097.8     .05       0
  4758.5      .1       0    4992     .07       0  5003.6      .1       0
    5050     .16       0  5425.8     .05       0  5638.7     .16       0
#XS Ineff= 2 , 0
         4047.69  402.07
Permanent Ineff=
       F       F
Bank Sta=4967.7,5027.9
XS Rating Curve= 0 ,0
Exp/Cntr=0.3,0.1

Type RM Length L Ch R = 1 ,29232   ,808,808,808
BEGIN DESCRIPTION:
NORTH MINERAL CREEK 33 0
END DESCRIPTION:
XS GIS Cut Line= 3
      3504292.08     10391401.77      3504344.16     10389594.44
      3504883.25     10389008.48
#Sta/Elev= 30
  3689.6  404.95  3844.7   397.6  3864.5   397.7  3942.8  394.31  4029.9  392.18
    4470  389.39  4700.1  391.67  4848.1  391.72  4960.3  392.91  4970.3  391.28
  4980.3  385.81  4984.5  381.78    4985  381.28  4996.1  381.78  5010.3  385.04
  5020.3  389.85  5030.3   392.5  5102.2  392.32  5230.4  390.38  5280.4  392.16
  5490.5     395  5533.5  394.65    5588  397.56    5732  406.67  5866.4   416.1
  5915.8  420.75    6015  427.24  6212.9  445.32  6269.6  447.26  6293.9  446.66
#Mann= 8 ,-1 , 0
  3689.6     .05       0  3844.7      .1       0  3942.8     .05       0
  4848.1     .16       0  4984.5     .07       0  4996.1     .16       0
  5102.2     .12       0    5588     .16       0
Bank Sta=4960.3,5030.3
XS Rating Curve= 0 ,0
Exp/Cntr=0.3,0.1

Type RM Length L Ch R = 1 ,28424   ,1143,1143,1143
BEGIN DESCRIPTION:
NORTH MINERAL CREEK 31 1
END DESCRIPTION:
XS GIS Cut Line= 3
      3504833.75     10391237.63      3504917.08     10389873.09
      3505331.11     10389433.02
#Sta/Elev= 30
  3724.3  406.07  3770.4   404.8  4010.8  390.39    4091  387.14  4125.9  387.54
  4151.1  387.99  4161.1  382.74  4181.1  387.77  4191.2  388.58  4221.2  387.35
  4363.2  389.16  4503.4  389.41  4936.8  390.81  4962.6  389.52  4982.6  386.01
  4986.8  380.75  4987.3  380.25  4998.4  380.75  5012.7  384.12  5022.7  389.34
  5032.7  397.22  5042.7  398.54  5089.6  398.76  5095.8   400.8  5230.6  407.68
  5272.6  407.76  5294.1  401.28  5315.1  407.82  5343.4  411.78  5695.6  437.19
#Mann= 7 ,-1 , 0
  3724.3     .16       0  4125.9     .12       0  4363.2     .05       0
  4503.4     .12       0  4936.8     .16       0  4986.8     .07       0
  4998.4     .16       0
Bank Sta=4962.6,5022.7
XS Rating Curve= 0 ,0
Exp/Cntr=0.3,0.1

Type RM Length L Ch R = 1 ,27281   ,763,763,763
BEGIN DESCRIPTION:
NORTH MINERAL CREEK 3 0
END DESCRIPTION:
XS GIS Cut Line= 4
      3504849.36     10391391.34      3504976.97     10391044.96
      3505659.27     10390602.26      3505719.17     10390318.38
#Sta/Elev= 30
  4435.8  406.68  4546.2  404.32  4576.6     404  4595.3  404.78  4626.9  404.23
  4632.2  403.34  4657.3   403.5    4804  396.85  4941.8  392.78  4977.9  391.28
  4984.7  386.04  4990.7  384.66    5000  378.81  5000.5  378.31  5011.7  378.81
  5013.7  381.23    5021  385.61  5036.1  387.96  5063.2  388.83  5093.5  388.25
  5193.1  388.94  5340.8  387.21  5368.4  387.27    5419  389.77  5467.9  394.38
  5591.8  404.02  5639.3  405.12  5655.5  406.58    5755  410.21  5908.4  412.85
#Mann= 5 ,-1 , 0
  4435.8     .16       0  4941.8     .12       0    5000     .07       0
  5011.7     .12       0  5340.8     .16       0
Bank Sta=4977.9,5036.1
XS Rating Curve= 0 ,0
Exp/Cntr=0.3,0.1

Type RM Length L Ch R = 1 ,26518   ,325,325,325
BEGIN DESCRIPTION:
NORTH MINERAL CREEK 29 0
END DESCRIPTION:
XS GIS Cut Line= 3
      3505192.12     10391691.63      3505792.11     10391241.64
      3505842.11     10390741.62
#Sta/Elev= 30
  4262.5  419.12  4305.2  415.03  4340.6  410.23  4369.8  404.58  4469.8  396.04
  4562.5  390.11  4669.5  388.49  4798.9  386.25  4969.8  386.68    4976  382.94
  4984.4  382.49  4990.6  377.05  4993.1  376.87  4993.6  376.37  5004.8  376.87
  5009.4  379.24    5015  379.24  5022.5  385.88  5032.6  387.08    5123  384.95
  5160.7  390.19  5165.7  388.86  5183.3  390.83  5233.6  386.76  5266.2  390.33
  5290.8  387.86    5314     387  5361.7  388.67  5454.7  395.53    5515  398.44
#Mann= 5 ,-1 , 0
  4262.5     .16       0  4669.5     .12       0  4993.1     .07       0
  5004.8     .12       0  5290.8     .16       0
Bank Sta=4969.8,5022.5
XS Rating Curve= 0 ,0
Exp/Cntr=0.3,0.1

Type RM Length L Ch R = 1 ,26193   ,712,712,712
BEGIN DESCRIPTION:
NORTH MINERAL CREEK 27 0
END DESCRIPTION:
XS GIS Cut Line= 3
      3505502.73     10392090.57       3505756.2     10391548.91
      3506377.42     10391417.03
#Sta/Elev= 30
  4262.1  419.33  4343.5  418.84  4417.5  414.46  4457.6  408.47  4537.2  398.95
  4680.5  387.89  4757.7  386.32  4811.6  386.22  4834.1  386.15    4866  384.52
  4970.4  386.23  4978.6  384.63  4988.8  380.14    4993  376.87  4993.5  376.37
  5005.2  376.87  5009.3  378.57  5014.9  382.05  5029.7  385.41  5050.2  386.26
  5083.7  386.01    5132  385.08  5213.7  384.88  5244.4  386.47  5264.9  389.05
  5295.5  390.81  5352.2  396.37  5372.6  397.42  5451.4  398.56  5495.2  397.81
#Mann= 6 ,-1 , 0
  4262.1     .16       0  4811.6     .12       0    4993     .07       0
  5005.2     .12       0  5083.7     .16       0  5372.6      .1       0
Bank Sta=4978.6,5029.7
XS Rating Curve= 0 ,0
Exp/Cntr=0.3,0.1

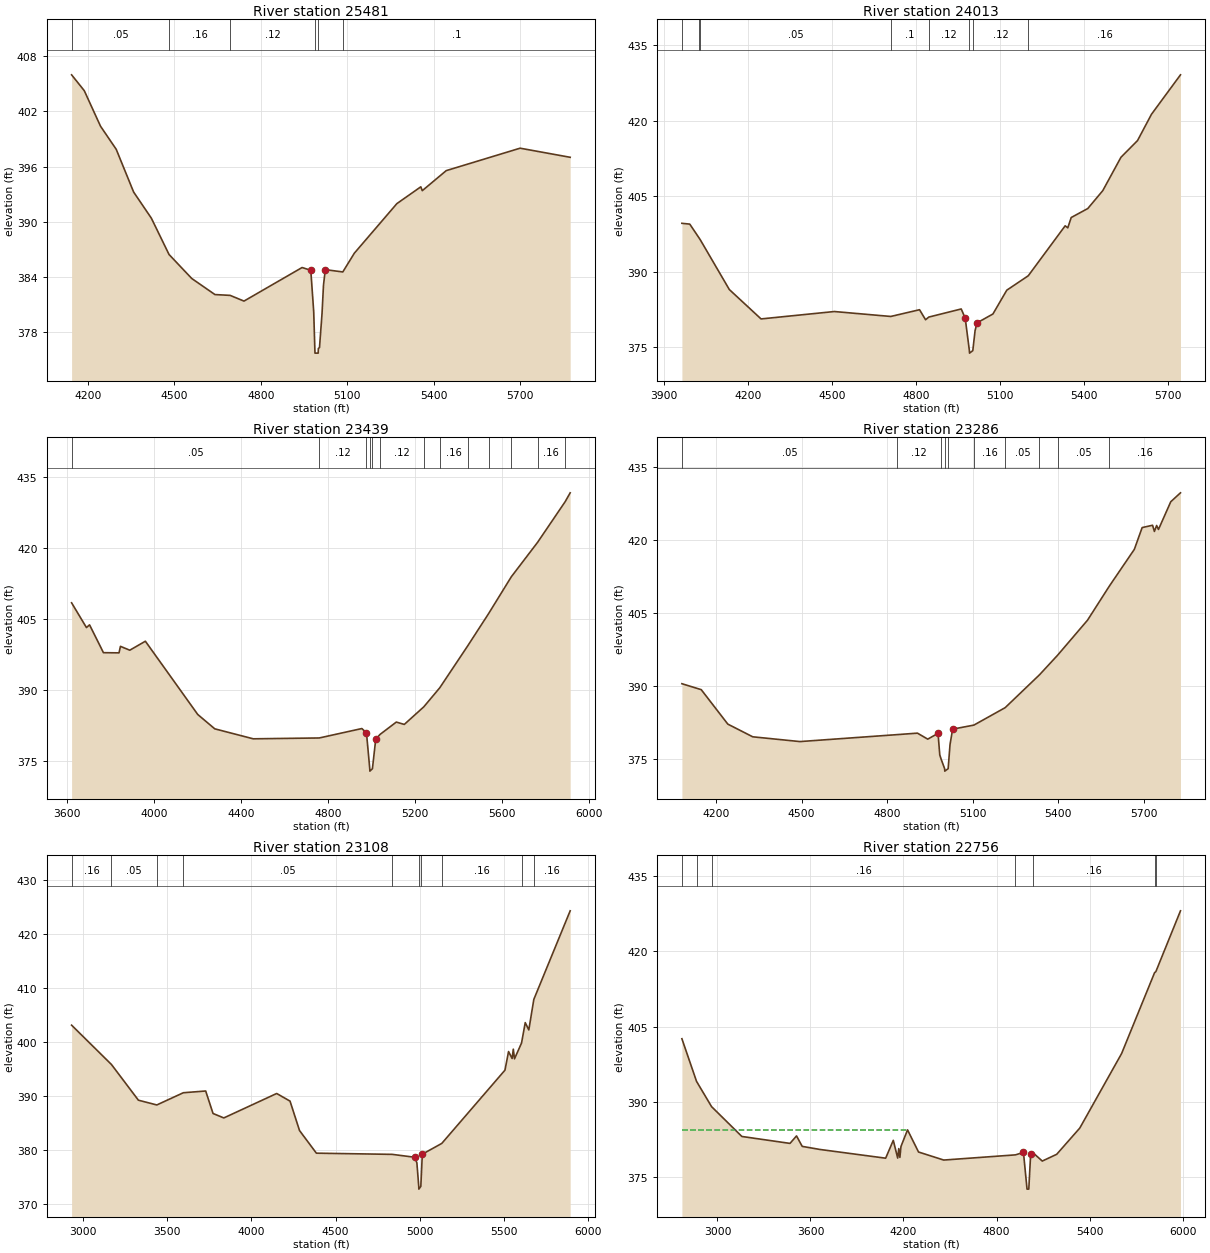
Type RM Length L Ch R = 1 ,25481   ,1468,1468,1468
BEGIN DESCRIPTION:
NORTH MINERAL CREEK 26 0
END DESCRIPTION:
XS GIS Cut Line= 3
      3506195.29     10392935.25      3506358.05     10391550.68
      3506438.16     10391225.92
#Sta/Elev= 30
  4144.3  405.98  4188.2  404.26  4244.6  400.39    4299  397.88  4359.4  393.23
  4420.8  390.39  4482.1  386.44  4560.8  383.83  4641.3  382.08    4694  381.99
    4742  381.37  4943.4  385.02  4973.6  384.72  4983.7  380.23  4987.6  376.21
  4988.1  375.71  4999.3  375.71  4999.8  376.21  5003.8  376.32  5012.6  380.03
  5017.6   383.1  5023.9  384.79  5084.6  384.54  5124.6  386.58    5272  391.97
  5355.1   393.8  5360.1  393.38  5443.2  395.56  5699.3     398  5872.9  397.01
#Mann= 6 ,-1 , 0
  4144.3     .05       0  4482.1     .16       0    4694     .12       0
  4987.6     .07       0  4999.8     .12       0  5084.6      .1       0
Bank Sta=4973.6,5023.9
XS Rating Curve= 0 ,0
Exp/Cntr=0.3,0.1

Type RM Length L Ch R = 1 ,24013   ,574,574,574
BEGIN DESCRIPTION:
NORTH MINERAL CREEK 25 0
END DESCRIPTION:
XS GIS Cut Line= 3
      3506401.48     10392850.56      3507302.06     10391982.54
      3507762.16      10391722.1
#Sta/Elev= 30
  3965.2  399.59  3993.3  399.43  4027.2  396.62  4031.4  396.26  4134.5  386.42
  4247.7  380.58  4509.3  382.05  4710.7  381.07  4813.4  382.41  4834.8  380.42
  4846.6  380.95  4962.1  382.56  4976.3  380.75  4991.3  374.28  4991.8  373.78
  5003.5  374.28  5011.5  378.23  5018.7   379.8  5075.3  381.56  5124.7  386.29
  5201.4  389.16  5333.1  399.09  5342.5  398.69  5354.7  400.74  5413.9  402.53
  5467.3  406.08  5532.3  412.72  5591.4  416.04  5641.2  421.27  5744.7  429.11
#Mann= 8 ,-1 , 0
  3965.2     .05       0  4027.2     .16       0  4031.4     .05       0
  4710.7      .1       0  4846.6     .12       0  4991.3     .07       0
  5003.5     .12       0  5201.4     .16       0
Bank Sta=4976.3,5018.7
XS Rating Curve= 0 ,0
Exp/Cntr=0.3,0.1

Type RM Length L Ch R = 1 ,23439   ,153,153,153
BEGIN DESCRIPTION:
NORTH MINERAL CREEK 24 0
END DESCRIPTION:
XS GIS Cut Line= 3
      3506457.56     10393594.07      3507290.92     10392583.63
      3507806.69     10391745.94
#Sta/Elev= 30
  3619.8   408.4  3688.1  403.17  3702.4  403.74  3766.3  397.86    3838  397.82
  3844.5   399.2  3887.5  398.38  3959.2  400.28  4200.2  384.79  4278.4  381.76
  4455.5  379.65    4759  379.83    4955  381.82  4975.5  380.95  4976.3  380.89
  4991.4  373.32  4991.9  372.82  5003.6  373.32  5018.8  379.55  5038.4  380.57
  5113.5  383.19  5150.2  382.69  5239.9  386.41  5313.1  390.42  5441.4  399.26
  5538.2  406.13  5642.8  413.92  5763.3  421.18  5890.1  429.77  5913.3  431.65
#Mann= 13 ,-1 , 0
  3619.8     .05       0    4759     .12       0  4975.5      .1       0
  4991.4     .07       0  5003.6      .1       0  5038.4     .12       0
  5239.9     .05       0  5313.1     .16       0  5441.4     .05       0
  5538.2     .16       0  5642.8     .05       0  5763.3     .16       0
  5890.1     .05       0
Bank Sta=4976.3,5018.8
XS Rating Curve= 0 ,0
Exp/Cntr=0.3,0.1

Type RM Length L Ch R = 1 ,23286   ,178,178,178
BEGIN DESCRIPTION:
NORTH MINERAL CREEK 23 0
END DESCRIPTION:
XS GIS Cut Line= 3
      3506920.13     10393403.96      3507627.58     10392338.44
      3507927.08     10391978.17
#Sta/Elev= 30
  4080.6  390.51  4148.4  389.29  4241.6  382.22  4328.8  379.62  4494.2  378.64
  4833.6  380.06  4906.2  380.37  4942.3  379.14  4978.4  380.33  4984.4  375.91
  4989.3  375.02  5001.5  373.08    5002  372.58  5013.8  373.08  5020.4  378.05
  5029.5  381.19  5104.1  382.02  5213.7   385.6  5333.8  392.33  5397.2  396.34
  5502.3  403.54    5579  410.55  5666.4  418.07  5693.7  422.53  5730.2  423.01
  5736.7  421.74  5744.5  422.96    5751  422.15    5794  427.83  5828.1  429.66
#Mann= 10 ,-1 , 0
  4080.6     .05       0  4833.6     .12       0  4989.3     .05       0
  5001.5     .04       0  5013.8     .05       0  5104.1     .16       0
  5213.7     .05       0  5333.8     .16       0  5397.2     .05       0
    5579     .16       0
Bank Sta=4978.4,5029.5
XS Rating Curve= 0 ,0
Exp/Cntr=0.3,0.1

Type RM Length L Ch R = 1 ,23108   ,352,352,352
BEGIN DESCRIPTION:
NORTH MINERAL CREEK 21 4
END DESCRIPTION:
XS GIS Cut Line= 5
      3505972.88     10394187.68      3506922.87     10393465.57
      3507377.73     10392854.46      3507645.09     10392729.46
      3508147.86     10392230.16
#Sta/Elev= 30
  2932.9  403.12  3169.6  395.84  3329.4  389.24  3438.7  388.36  3596.1  390.62
  3728.7  390.94  3772.3  386.78  3836.3  385.96  4149.9  390.48  4229.2  389.07
  4285.5  383.63  4385.6  379.44  4835.6  379.22  4970.1  378.68    4982  377.64
  4993.1  373.29  4993.6  372.79  5005.4  373.29  5014.2  379.25  5129.9  381.25
  5504.7   394.8    5526  398.24  5547.2  396.95  5554.2  398.68  5561.3  396.89
  5603.2  399.83    5625  403.59  5646.2  402.24  5675.9  407.88  5891.7  424.27
#Mann= 10 ,-1 , 0
  2932.9     .16       0  3169.6     .05       0  3438.7      .1       0
  3596.1     .05       0  4835.6     .12       0  4993.1     .07       0
  5005.4     .12       0  5129.9     .16       0  5603.2     .05       0
  5675.9     .16       0
Bank Sta=4970.1,5014.2
XS Rating Curve= 0 ,0
Exp/Cntr=0.3,0.1

Type RM Length L Ch R = 1 ,22756   ,418,418,418
BEGIN DESCRIPTION:
NORTH MINERAL CREEK 20 0
END DESCRIPTION:
XS GIS Cut Line= 6
      3505910.33     10394390.83      3506629.13     10394119.98
      3507198.58     10393595.49      3507603.42     10393184.32
      3507733.95     10392892.87      3508227.79     10392292.72
#Sta/Elev= 30
  2770.7  402.58  2865.2   394.1  2962.1  389.08  3157.3  383.15  3467.9  381.77
    3510  383.26  3546.7  381.18  3660.1  380.57  4084.9  378.83  4134.2  382.38
  4162.6  378.85  4169.4  380.74  4176.8  378.99  4183.6  381.15  4226.1  384.46
    4297  380.06  4459.6  378.46  4921.9  379.49  4973.8  379.97  4996.9  372.68
  5008.2  372.68  5020.2  379.66  5035.4   379.9  5095.2  378.26    5188   379.6
  5337.1  384.82  5606.9  399.64  5819.6  415.72  5827.6  415.91  5986.6  428.01
#Mann= 7 ,-1 , 0
  2770.7     .16       0  2865.2     .05       0  2962.1     .16       0
  4921.9     .12       0  5035.4     .16       0  5819.6     .05       0
  5827.6     .16       0
#XS Ineff= 2 , 0
       0 4228.12  384.49               0
Permanent Ineff=
       T       F
Bank Sta=4973.8,5020.2
XS Rating Curve= 0 ,0
Exp/Cntr=0.3,0.1

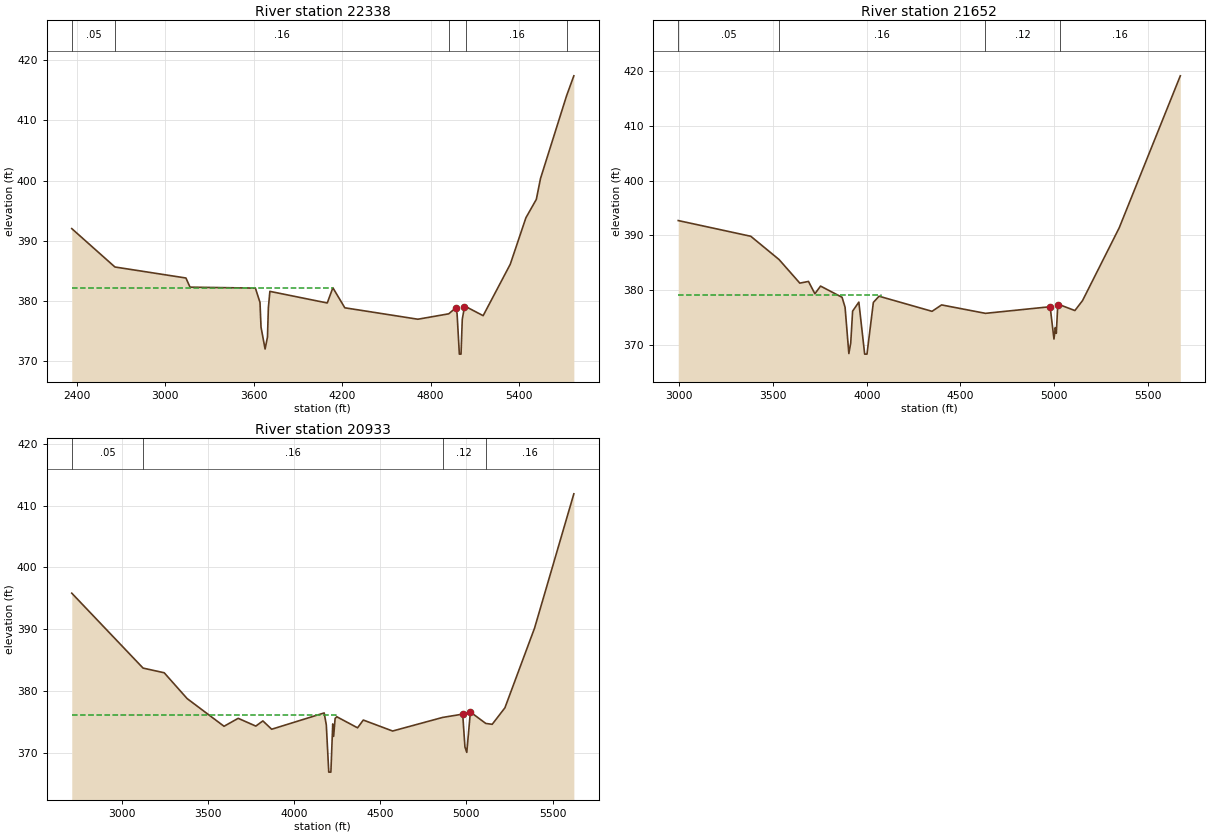
Type RM Length L Ch R = 1 ,22338   ,686,686,686
BEGIN DESCRIPTION:
NORTH MINERAL CREEK 20 2
END DESCRIPTION:
XS GIS Cut Line= 4
      3506389.56     10395395.98      3507244.51     10393803.55
      3507821.27     10393458.31      3508467.38     10392797.36
#Sta/Elev= 30
  2366.9  392.02  2659.5  385.64  3140.9  383.81  3168.5  382.29  3611.8  382.13
    3643  379.75    3650  375.64  3677.6  372.01  3693.8  374.01  3699.8  378.88
  3710.1  381.59    4099  379.66  4137.1  382.19  4218.1  378.86  4713.5  376.96
  4922.6  377.86    4972  378.88  4979.2  377.86  4994.6  371.16  5005.9  371.16
  5014.4  376.94  5028.6  378.93  5042.7     379  5155.9  377.55  5339.8   386.1
  5445.8  393.82  5516.5  396.88  5544.8  400.35  5721.7  414.11  5770.8  417.41
#Mann= 5 ,-1 , 0
  2366.9     .05       0  2659.5     .16       0  4922.6     .12       0
  5042.7     .16       0  5721.7     .05       0
#XS Ineff= 2 , 0
       0 4136.36   382.2               0
Permanent Ineff=
       T       F
Bank Sta=4972,5028.6
XS Rating Curve= 0 ,0
Exp/Cntr=0.3,0.1

Type RM Length L Ch R = 1 ,21652   ,719,719,719
BEGIN DESCRIPTION:
NORTH MINERAL CREEK 19 2
END DESCRIPTION:
XS GIS Cut Line= 3
      3508238.51     10395526.19      3508377.84     10394300.14
      3508635.66     10392878.27
#Sta/Elev= 30
  2993.9  392.71  3380.9  389.84  3531.9  385.59  3642.6  381.28  3688.9  381.59
  3723.1  379.34  3753.3  380.74  3868.1  378.69  3884.1  376.87  3904.3  368.41
  3914.3  370.34  3924.4  376.17  3957.6  377.81  3988.7  368.31    4001  368.31
  4035.1  377.76  4065.3  378.89  4348.3  376.13  4399.1   377.3  4633.1  375.76
  4978.4  376.97  4998.7  371.07  5006.1  373.16  5011.2  372.11    5019  377.25
  5029.9  377.32  5110.5  376.27  5151.2  378.09    5347  391.39  5672.9  419.15
#Mann= 4 ,-1 , 0
  2993.9     .05       0  3531.9     .16       0  4633.1     .12       0
  5029.9     .16       0
#XS Ineff= 2 , 0
       0    4075  379.15               0
Permanent Ineff=
       T       F
Bank Sta=4978.4,5019
XS Rating Curve= 0 ,0
Exp/Cntr=0.3,0.1

Type RM Length L Ch R = 1 ,20933   ,500,500,500
BEGIN DESCRIPTION:
NORTH MINERAL CREEK 19 0
END DESCRIPTION:
XS GIS Cut Line= 3
      3508853.08     10395776.28      3509205.97     10394110.04
      3508824.77     10392962.07
#Sta/Elev= 30
  2710.6  395.83  3124.2  383.69  3246.9  382.93  3379.8  378.75    3594  374.26
  3676.2  375.55  3778.4  374.29  3819.3  375.13  3870.4  373.78    4175  376.42
  4187.3  374.48  4201.6  366.83  4213.9  366.83  4224.6  374.64  4229.8  372.62
  4238.4  375.54  4248.6   375.8  4368.6  374.01  4401.9  375.27  4572.1  373.49
  4861.4  375.69  4978.6  376.23  4991.6  370.91  5002.2  370.03  5023.2  376.57
  5112.6  374.72  5149.7  374.58  5223.5  377.25  5395.6  390.18  5623.4  411.93
#Mann= 4 ,-1 , 0
  2710.6     .05       0  3124.2     .16       0  4861.4     .12       0
  5112.6     .16       0
#XS Ineff= 2 , 0
       0 4242.05  376.07               0
Permanent Ineff=
       T       F
Bank Sta=4978.6,5023.2
XS Rating Curve= 0 ,0
Exp/Cntr=0.3,0.1