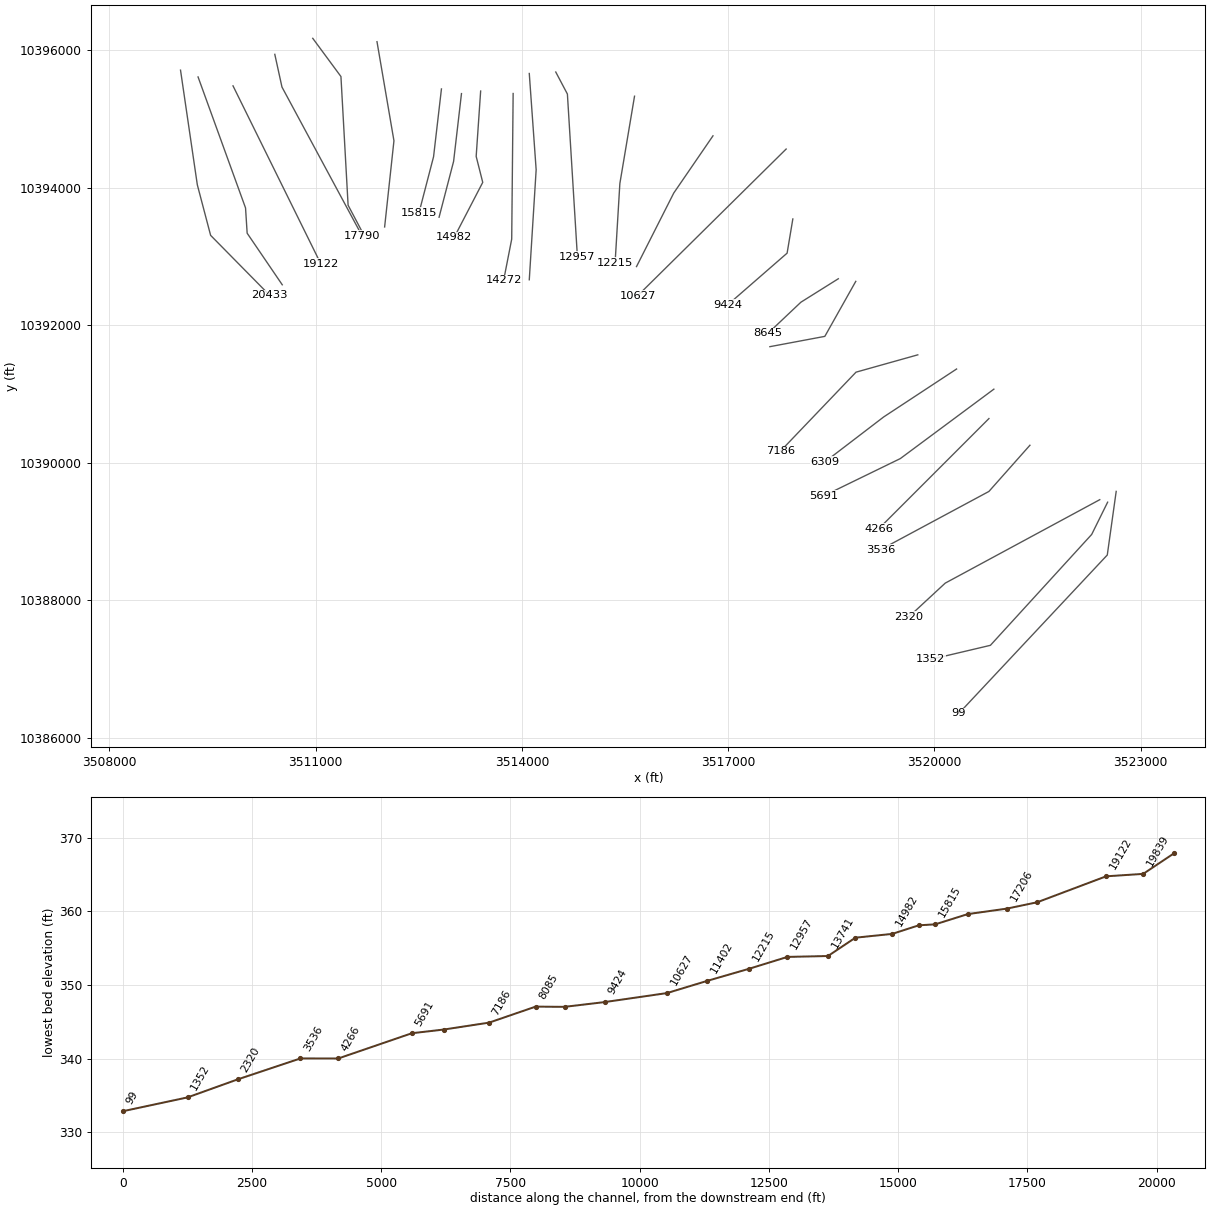
HEC-RAS study NORTH MINERAL CREEK.prj: NORTH MINERAL CREEK Base Level Engineering

--- NORTH MINERAL CREEK.g01 (geometry) --- (continued)

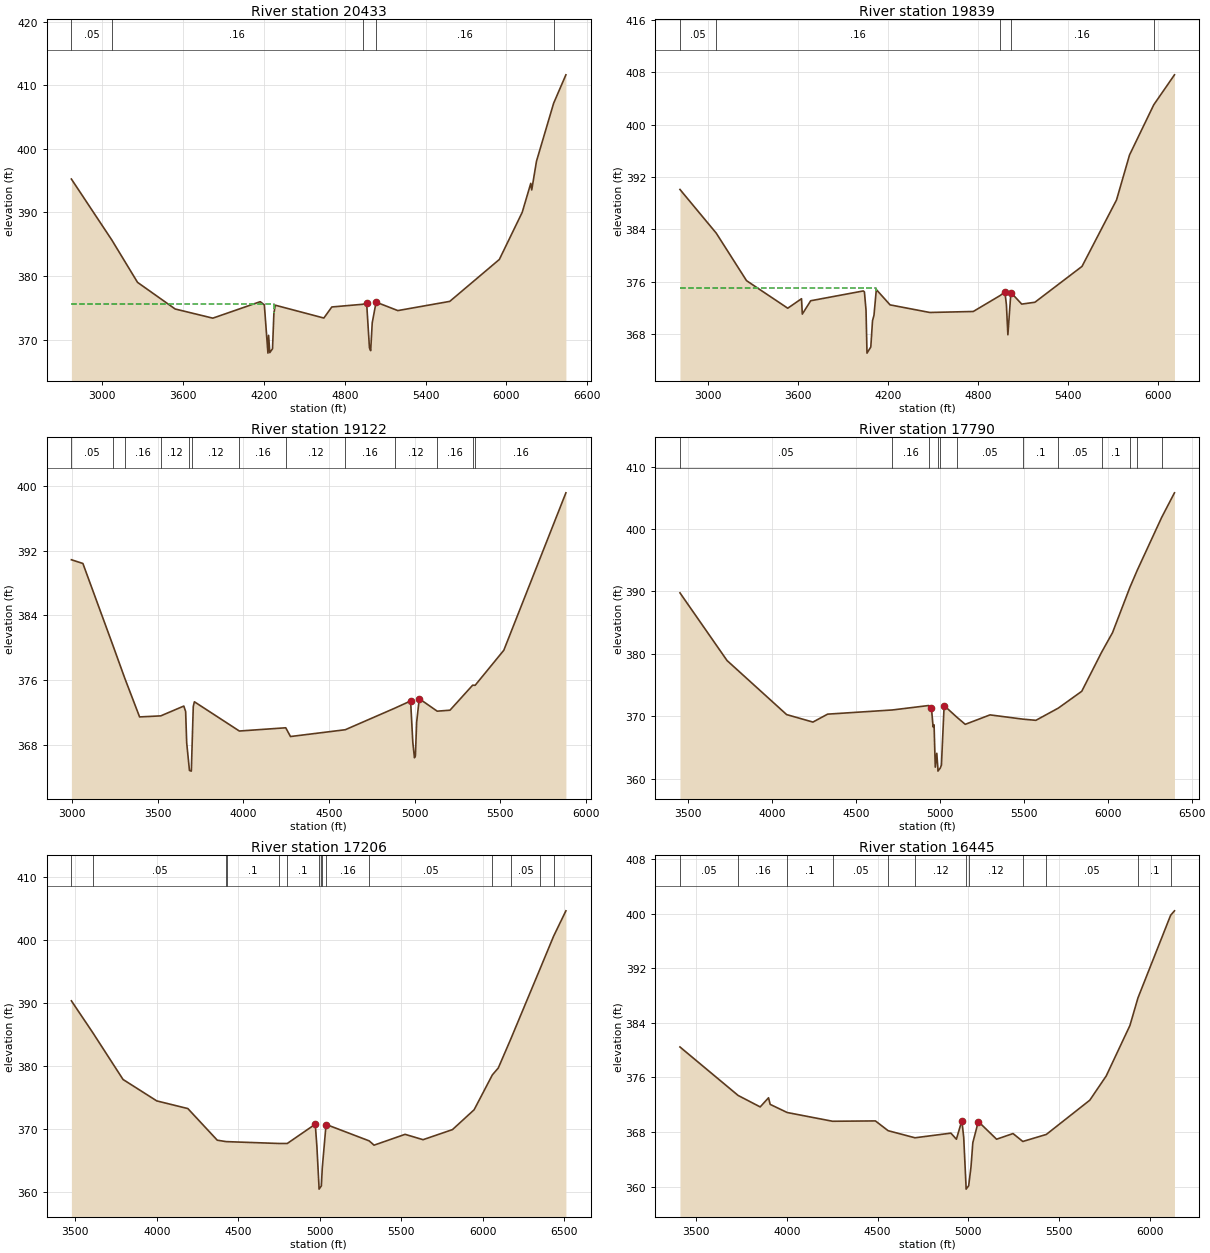
Type RM Length L Ch R = 1 ,20433   ,594,594,594
BEGIN DESCRIPTION:
NORTH MINERAL CREEK 2 0
END DESCRIPTION:
XS GIS Cut Line= 4
      3509035.37     10395708.57      3509279.86     10394040.55
      3509473.21     10393305.85      3510332.56     10392433.48
#Sta/Elev= 30
  2771.1  395.26  3071.2  385.67    3262  379.01  3541.4  374.82  3820.8  373.38
  4172.8  375.97  4203.2  375.46  4229.8  367.88  4234.8  370.68  4243.6  367.96
  4263.8  368.57  4273.9  374.07    4284  375.42  4644.8   373.4    4704  375.14
  4932.2  375.56  4962.5  375.72  4983.2  368.72  4992.3  368.27  5003.9  372.66
  5032.6   375.9  5193.9  374.57  5579.5  376.02  5947.2  382.61  6116.9  390.02
  6180.5  394.58  6187.6  393.54  6222.9  398.06  6350.2  407.18  6441.2  411.65
#Mann= 5 ,-1 , 0
  2771.1     .05       0  3071.2     .16       0  4932.2     .12       0
  5032.6     .16       0  6350.2     .16       0
#XS Ineff= 2 , 0
       0    4275  375.62               0
Permanent Ineff=
       T       F
Bank Sta=4962.5,5032.6
XS Rating Curve= 0 ,0
Exp/Cntr=0.3,0.1

Type RM Length L Ch R = 1 ,19839   ,717,717,717
BEGIN DESCRIPTION:
NORTH MINERAL CREEK 21 3
END DESCRIPTION:
XS GIS Cut Line= 4
      3509290.58     10395609.59      3509981.03     10393704.29
      3510004.46      10393337.1      3510514.88     10392587.09
#Sta/Elev= 30
  2810.5   390.1    3053  383.42    3255  376.17  3530.2  371.96  3622.1  373.41
  3627.4  371.06  3683.3   373.1  4034.9   374.6  4042.1  374.45  4052.8  371.68
  4059.3   365.1  4084.7  366.04  4096.2  370.06    4106  370.89  4121.5  374.81
  4213.4  372.47  4478.4  371.31  4768.8  371.46  4949.9  373.92    4980  374.45
    4990  372.52    5000   367.9  5020.1  374.36  5092.4  372.59  5180.4  372.87
    5495  378.35  5725.4   388.5  5812.2  395.37  5973.9  403.03  6112.2  407.61
#Mann= 5 ,-1 , 0
  2810.5     .05       0    3053     .16       0  4949.9     .12       0
  5020.1     .16       0  5973.9      .1       0
#XS Ineff= 2 , 0
       0 4120.45  375.08               0
Permanent Ineff=
       T       F
Bank Sta=4980,5020.1
XS Rating Curve= 0 ,0
Exp/Cntr=0.3,0.1

Type RM Length L Ch R = 1 ,19122   ,1332,1332,1332
BEGIN DESCRIPTION:
NORTH MINERAL CREEK 19 1
END DESCRIPTION:
XS GIS Cut Line= 2
       3509798.9     10395480.05      3511076.68     10392889.77
#Sta/Elev= 30
  2995.5  390.86  3062.7   390.4  3237.4  380.33  3306.9  376.26  3393.9  371.46
  3517.5  371.59  3652.1   372.8  3662.8  372.13  3668.9  368.28  3685.1  364.85
 3696.02  364.77  3707.4  372.75  3713.9  373.33  3976.5  369.72  4247.5  370.12
  4275.2  369.04  4595.2  369.88  4883.4  372.53  4976.8  373.43  4989.7  368.33
  4999.2  366.42  5004.8  366.64    5012  370.79  5027.3  373.71  5132.1  372.17
  5206.9  372.29  5339.3  375.38  5353.6  375.36  5521.2  379.69  5883.8  399.12
#Mann= 13 ,-1 , 0
  2995.5     .05       0  3237.4      .1       0  3306.9     .16       0
  3517.5     .12       0  3685.2     .07       0  3697.7     .12       0
  3976.5     .16       0  4247.5     .12       0  4595.2     .16       0
  4883.4     .12       0  5132.1     .16       0  5339.3     .05       0
  5353.6     .16       0
Bank Sta=4976.8,5027.3
XS Rating Curve= 0 ,0
Exp/Cntr=0.3,0.1

Type RM Length L Ch R = 1 ,17790   ,584,584,584
BEGIN DESCRIPTION:
NORTH MINERAL CREEK 17 0
END DESCRIPTION:
XS GIS Cut Line= 3
      3510406.56     10395938.32      3510510.73     10395462.65
      3511677.08     10393296.55
#Sta/Elev= 30
  3450.5  389.78  3731.1  378.95  4086.2   370.3  4242.9   369.1  4330.5  370.37
    4717  371.04  4932.9  371.75  4949.4  371.31  4959.2  368.32  4964.9  368.66
  4972.1  361.88  4981.1  364.11  4987.5  361.75    4988  361.25  5002.1  361.75
  5008.7  362.22  5024.9  371.74    5102  369.85  5150.7  368.74  5298.3  370.25
  5494.3  369.57  5571.7  369.38  5705.6  371.34  5845.1  374.03  5962.8  380.25
  6028.4  383.41  6131.7  390.64  6176.7  393.45  6321.2  401.85  6397.6  405.79
#Mann= 12 ,-1 , 0
  3450.5     .05       0    4717     .16       0  4932.9     .12       0
  4987.5     .07       0  5002.1     .12       0    5102     .05       0
  5494.3      .1       0  5705.6     .05       0  5962.8      .1       0
  6131.7     .05       0  6176.7      .1       0  6321.2     .05       0
Bank Sta=4949.4,5024.9
XS Rating Curve= 0 ,0
Exp/Cntr=0.3,0.1

Type RM Length L Ch R = 1 ,17206   ,761,761,761
BEGIN DESCRIPTION:
NORTH MINERAL CREEK 18 0
END DESCRIPTION:
XS GIS Cut Line= 4
      3510958.61     10396171.02      3511368.36     10395615.43
      3511472.53      10393743.9      3511691.28     10393330.71
#Sta/Elev= 30
  3476.5  390.29  3606.3  385.29  3793.3   377.8    4000   374.4  4190.7  373.18
    4371  368.16  4426.4  367.93  4430.4  367.93    4747  367.64  4800.4  367.64
  4971.9   370.7  4981.9  367.18  4994.6  360.89  4995.1  360.39  5009.2  360.89
    5015  363.77  5035.5  369.88  5040.5  370.64  5302.7  368.05  5332.4  367.37
  5522.7  369.09  5632.9  368.24  5813.2  369.84    5946  372.99  6057.9  378.53
  6094.3  379.63  6170.1  384.18  6350.4  395.37  6433.4  400.55  6508.8  404.58
#Mann= 15 ,-1 , 0
  3476.5     .16       0  3606.3     .05       0  4426.4     .16       0
  4430.4      .1       0    4747     .05       0  4800.4      .1       0
  4994.6     .07       0  5009.2      .1       0    5015     .12       0
  5035.5     .16       0  5302.7     .05       0  6057.9      .1       0
  6170.1     .05       0  6350.4      .1       0  6433.4     .05       0
Bank Sta=4971.9,5040.5
XS Rating Curve= 0 ,0
Exp/Cntr=0.3,0.1

Type RM Length L Ch R = 1 ,16445   ,630,630,630
BEGIN DESCRIPTION:
Mapping XS 18696b6a
END DESCRIPTION:
XS GIS Cut Line= 3
      3511892.67     10396122.38       3512139.2      10394681.4
      3512003.78     10393427.91
#Sta/Elev= 30
  3412.3  380.46  3732.6  373.36    3854  371.68    3900  373.02  3909.1  372.05
  4002.8  370.86  4252.5  369.58  4488.4  369.63  4558.4   368.2  4706.2  367.16
  4904.1  367.84  4934.3  366.95  4964.5  369.68  4974.6  367.24  4987.3  360.14
  4987.8  359.64    5002  360.14  5014.8  362.92  5024.8  366.44    5055  369.54
  5155.6  366.95  5246.1  367.78    5300  366.62  5429.5  367.65  5668.6  372.66
  5759.1  376.21  5889.8  383.61  5933.9  387.64  6113.9  399.75    6135   400.4
#Mann= 12 ,-1 , 0
  3412.3     .05       0  3732.6     .16       0  4002.8      .1       0
  4252.5     .05       0  4558.4     .16       0  4706.2     .12       0
  4987.3     .07       0    5002     .12       0    5300      .1       0
  5429.5     .05       0  5933.9      .1       0  6113.9     .05       0
Bank Sta=4964.5,5055
XS Rating Curve= 0 ,0
Exp/Cntr=0.3,0.1

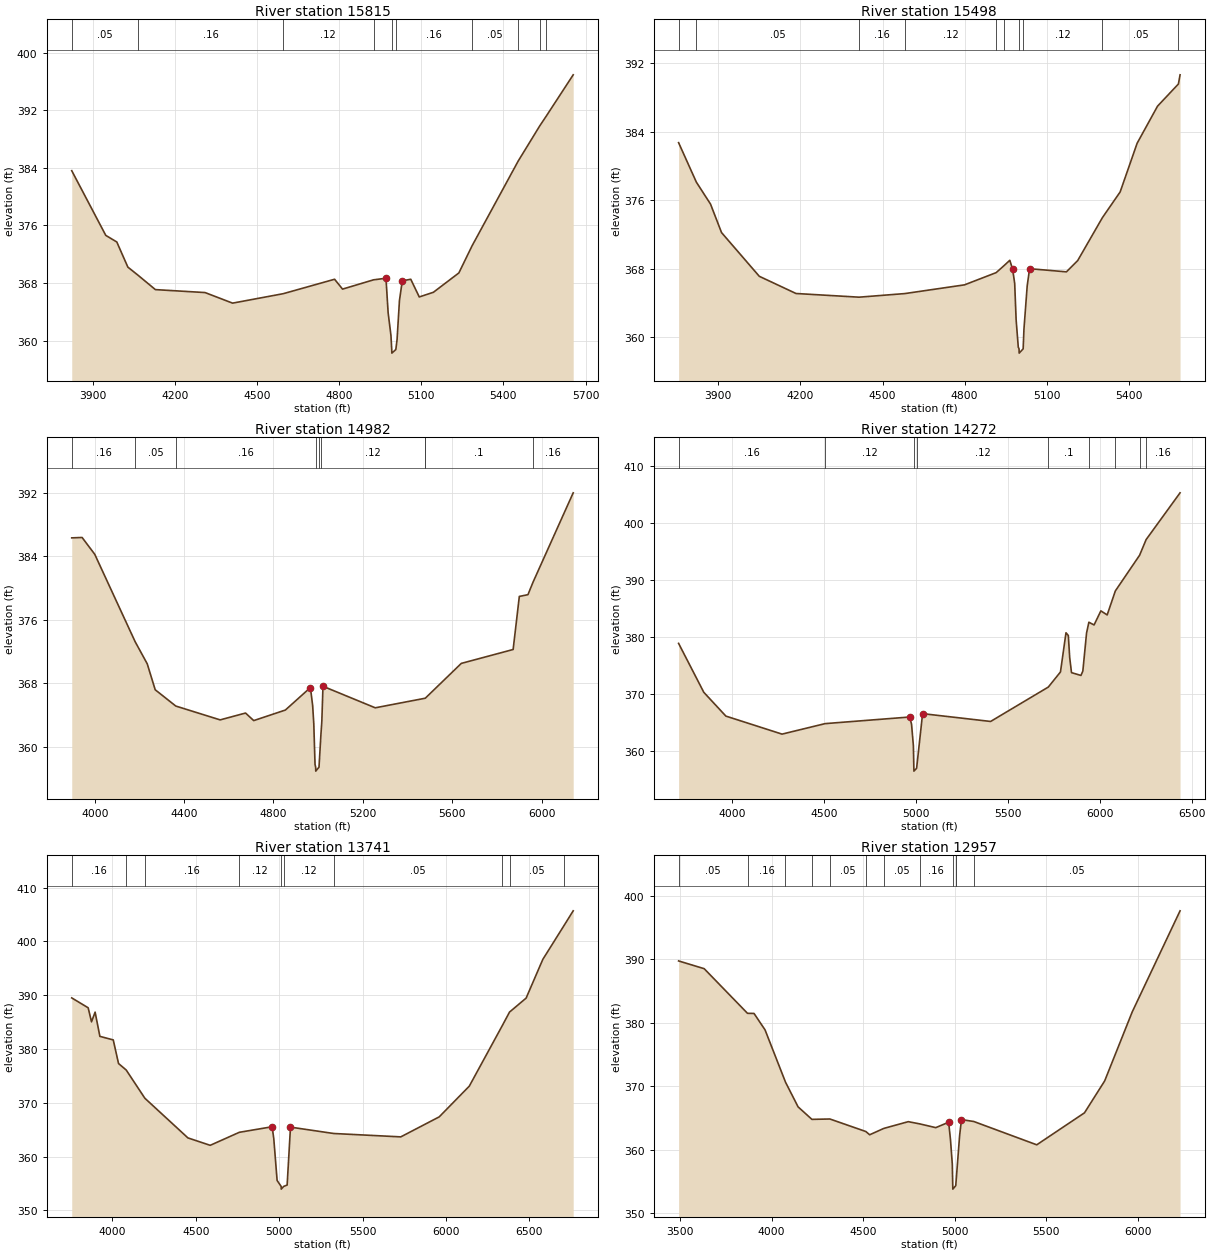
Type RM Length L Ch R = 1 ,15815   ,317,317,317
BEGIN DESCRIPTION:
NORTH MINERAL CREEK 16 1
END DESCRIPTION:
XS GIS Cut Line= 3
      3512829.98     10395435.14       3512715.4     10394449.08
      3512504.28     10393637.59
#Sta/Elev= 30
  3823.8  383.61  3948.1  374.62  3988.4   373.7  4028.7  370.21  4065.2   369.1
  4129.3  367.08  4310.6  366.67  4411.2   365.2  4595.8  366.51  4783.7  368.52
  4812.7  367.15  4925.9  368.44  4971.3  368.66  4979.2  363.86  4989.5   360.7
  4992.3  358.75  4992.8  358.25  5007.3  358.75  5011.8  360.13  5020.5  365.55
  5030.8   368.3  5061.8  368.52  5092.9  366.06  5144.5  366.71  5237.5   369.4
  5285.6  373.16  5454.1  384.95  5533.3  389.87  5556.6   391.2    5655  396.94
#Mann= 10 ,-1 , 0
  3823.8     .05       0  4065.2     .16       0  4595.8     .12       0
  4925.9     .16       0  4992.3     .07       0  5007.3     .16       0
  5285.6     .05       0  5454.1     .16       0  5533.3     .05       0
  5556.6     .16       0
Bank Sta=4971.3,5030.8
XS Rating Curve= 0 ,0
Exp/Cntr=0.3,0.1

Type RM Length L Ch R = 1 ,15498   ,516,516,516
BEGIN DESCRIPTION:
NORTH MINERAL CREEK 16
END DESCRIPTION:
XS GIS Cut Line= 3
      3513121.36     10395367.43      3513006.78     10394381.37
      3512795.66     10393569.88
#Sta/Elev= 30
  3755.4  382.72  3820.2  378.11    3872  375.54  3912.2  372.21  4050.1   367.1
  4184.1  365.09  4414.3  364.66  4581.4  365.08  4799.5   366.1  4915.1  367.53
  4944.6  368.37  4964.8  368.97  4975.1  367.94  4982.7  366.28  4987.9  362.04
  4995.8  358.82  4998.6  358.62  4999.1  358.12  5013.6  358.62  5016.5  360.91
  5028.4  365.99  5037.1  367.99  5171.5  367.62  5212.8  368.94  5302.9  373.95
  5367.8  376.96  5429.8  382.65  5504.4  386.99  5580.6  389.58  5586.6  390.65
#Mann= 10 ,-1 , 0
  3755.4     .16       0  3820.2     .05       0  4414.3     .16       0
  4581.4     .12       0  4915.1     .16       0  4944.6     .12       0
  4998.6     .07       0  5013.6     .12       0  5302.9     .05       0
  5580.6     .16       0
Bank Sta=4975.1,5037.1
XS Rating Curve= 0 ,0
Exp/Cntr=0.3,0.1

Type RM Length L Ch R = 1 ,14982   ,710,710,710
BEGIN DESCRIPTION:
NORTH MINERAL CREEK 16 0
END DESCRIPTION:
XS GIS Cut Line= 4
      3513400.17     10395404.46      3513335.07     10394453.95
      3513430.55     10394076.35      3513014.74     10393275.04
#Sta/Elev= 30
  3896.8  386.31  3943.2  386.36  3999.9  384.24  4180.5  373.25  4234.9  370.45
  4270.5  367.19  4362.7  365.14  4561.2   363.4  4674.9  364.26  4711.5  363.31
  4853.3  364.64  4965.4  367.47  4975.4  365.19  4980.5  362.88    4986  357.79
  4988.8  357.45  4989.3  356.95  5003.8  357.45  5012.6  361.66  5016.4  363.19
  5021.6  367.63  5255.6  364.92  5478.3  366.12  5480.1  366.14  5640.8  370.51
  5872.9  372.26  5900.6  378.94  5939.2  379.16  5961.9  380.73  6141.8  391.98
#Mann= 9 ,-1 , 0
  3896.8     .16       0  4180.5     .05       0  4362.7     .16       0
  4988.8     .07       0  5003.8     .16       0  5012.6     .12       0
  5478.3     .05       0  5480.1      .1       0  5961.9     .16       0
Bank Sta=4965.4,5021.6
XS Rating Curve= 0 ,0
Exp/Cntr=0.3,0.1

Type RM Length L Ch R = 1 ,14272   ,531,531,531
BEGIN DESCRIPTION:
NORTH MINERAL CREEK 15 0
END DESCRIPTION:
XS GIS Cut Line= 3
      3513872.65     10395368.69      3513851.81     10393251.46
      3513734.63     10392652.54
#Sta/Elev= 30
  3709.7  378.84  3846.8  370.26  3966.8  366.09  4272.3  362.93  4506.7  364.77
  4966.8  365.93  4976.8  364.66  4986.8  360.87  4989.3  356.94  4989.8  356.44
  5004.3  356.94  5036.8  366.52  5406.8  365.15  5720.7  371.18  5786.8  373.83
  5816.8   380.7  5829.5  380.22    5837  376.36  5846.8  373.71  5898.2  373.22
  5908.5  373.99  5928.7  380.66  5941.3  382.55  5969.5  382.07  6006.5  384.54
  6040.8  383.83  6085.3  388.04  6217.1  394.29  6252.7  397.04  6437.3  405.24
#Mann= 9 ,-1 , 0
  3709.7     .16       0  4506.7     .12       0  4989.3    .035       0
  5004.3     .12       0  5720.7      .1       0  5941.3     .05       0
  6085.3     .16       0  6217.1      .1       0  6252.7     .16       0
#XS Ineff= 2 , 0
                         5825.92          380.17
Permanent Ineff=
       F       F
Bank Sta=4966.8,5036.8
XS Rating Curve= 0 ,0
Exp/Cntr=0.3,0.1

Type RM Length L Ch R = 1 ,13741   ,784,784,784
BEGIN DESCRIPTION:
NORTH MINERAL CREEK 14 1
END DESCRIPTION:
XS GIS Cut Line= 3
      3514107.35     10395659.87      3514207.36     10394259.84
      3514107.36     10392659.86
#Sta/Elev= 30
  3756.5  389.49    3855  387.65    3875  385.04  3896.7  386.84  3925.2  382.34
  4005.4  381.68  4037.1  377.29    4083  376.09    4195  370.84  4453.1  363.47
  4586.8  362.09  4761.3  364.51  4957.8  365.54  4967.8  363.38  4987.9  355.56
  5012.1  354.45  5012.6  353.95  5027.1  354.45    5048  354.71  5068.1  365.47
  5326.8  364.29  5729.4  363.66  5959.9  367.38  6140.2  373.09  6338.1  384.34
  6381.3  386.85  6480.9  389.45  6581.1  396.65  6707.3  402.89  6763.2  405.67
#Mann= 10 ,-1 , 0
  3756.5     .16       0    4083     .05       0    4195     .16       0
  4761.3     .12       0  5012.1     .07       0  5027.1     .12       0
  5326.8     .05       0  6338.1      .1       0  6381.3     .05       0
  6707.3      .1       0
Bank Sta=4957.8,5068.1
XS Rating Curve= 0 ,0
Exp/Cntr=0.3,0.1

Type RM Length L Ch R = 1 ,12957   ,742,742,742
BEGIN DESCRIPTION:
NORTH MINERAL CREEK 12 0
END DESCRIPTION:
XS GIS Cut Line= 3
      3514492.44     10395681.15      3514661.71     10395360.83
      3514807.54     10392991.01
#Sta/Elev= 30
  3492.9  389.72  3632.5   388.5  3868.9  381.48  3904.5  381.46  3964.6  378.88
  4076.2  370.66  4144.9  366.77  4220.4   364.8  4318.5  364.86  4514.8  362.89
  4535.7  362.38  4612.9  363.38  4746.1  364.44  4809.1  364.09  4896.3   363.5
  4966.5  364.35  4976.5  361.65  4986.5  357.77    4989  354.33  4989.5  353.83
    5004  354.33  5005.4  354.37  5026.6  362.29  5036.6  364.76  5103.5  364.47
  5447.4   360.8  5707.9  365.83  5818.1  370.85  5968.4   381.7  6229.5   397.6
#Mann= 12 ,-1 , 0
  3492.9     .05       0  3868.9     .16       0  4076.2     .05       0
  4220.4     .07       0  4318.5     .05       0  4514.8     .16       0
  4612.9     .05       0  4809.1     .16       0    4989     .07       0
    5004     .16       0  5005.4     .12       0  5103.5     .05       0
Bank Sta=4966.5,5036.6
XS Rating Curve= 0 ,0
Exp/Cntr=0.3,0.1

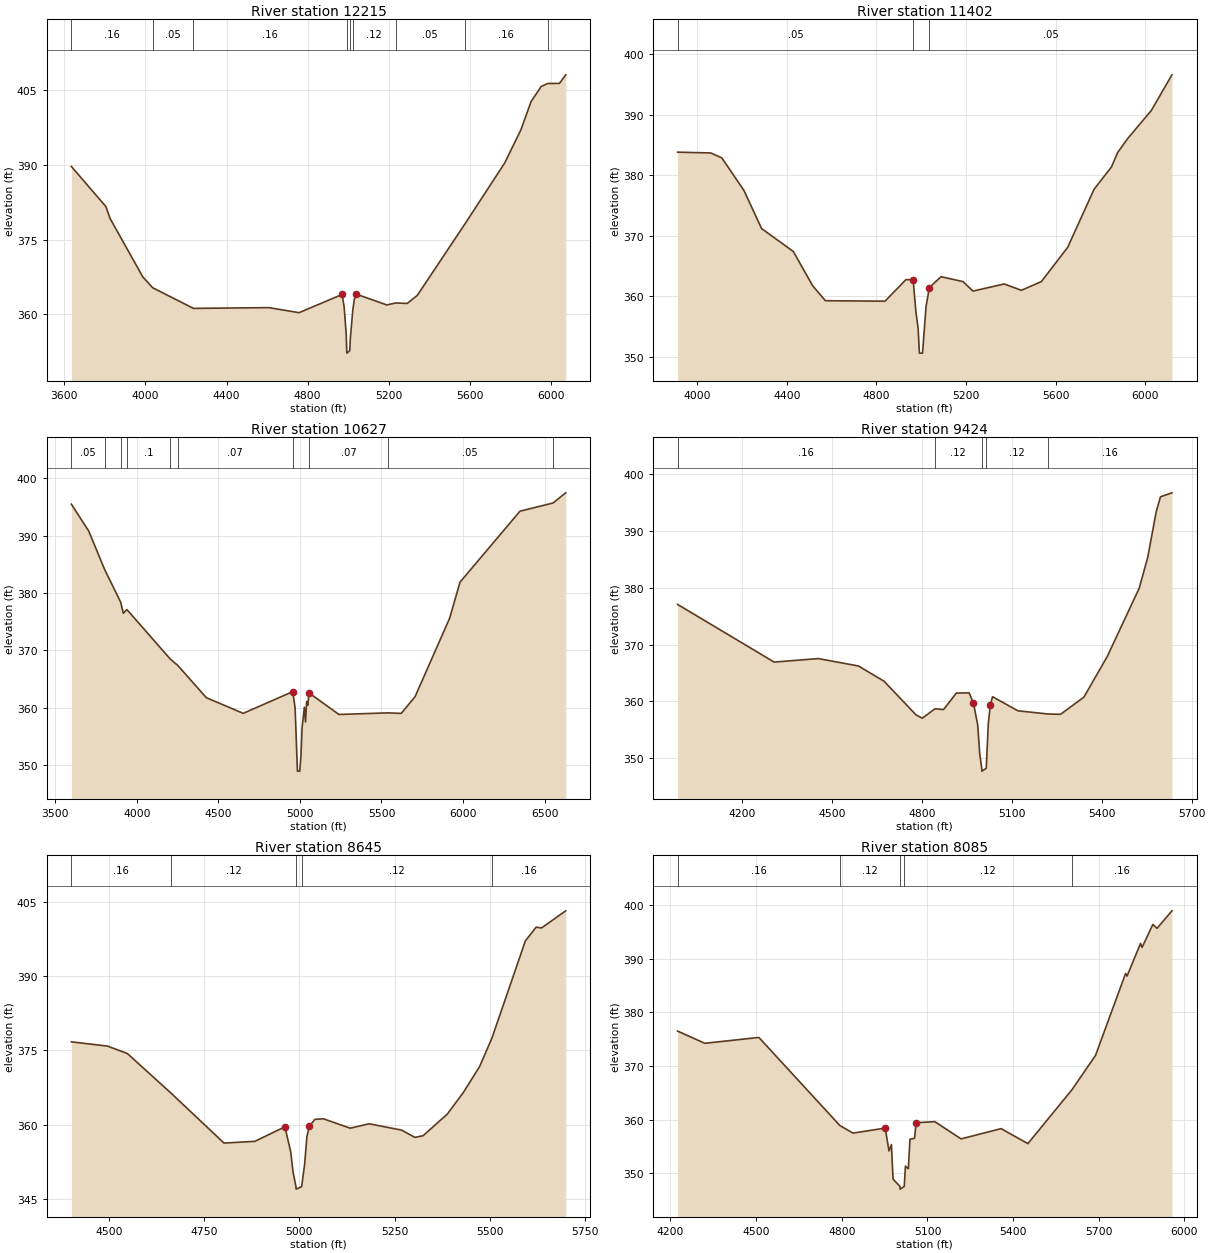
Type RM Length L Ch R = 1 ,12215   ,813,813,813
BEGIN DESCRIPTION:
NORTH MINERAL CREEK 15 1
END DESCRIPTION:
XS GIS Cut Line= 3
      3515637.99     10395329.35      3515424.56     10394058.81
      3515355.65     10392910.91
#Sta/Elev= 30
  3634.9  389.68    3805  381.64  3825.8  379.24  3987.5   367.5  4036.5  365.33
    4237   361.2  4608.6  361.35  4758.1  360.34  4970.5     364  4980.5   361.4
  4990.5  355.99    4993  352.72  4993.5  352.22    5008  352.72  5010.6  355.02
  5022.8  360.82  5030.6  363.06  5040.6  364.05  5190.9  361.89  5233.9  362.28
  5291.1  362.19  5341.2  363.81  5576.5  378.17  5771.9  390.36  5852.1  397.03
  5902.2  402.69  5952.3  405.74  5984.1  406.33  6042.4  406.35  6073.2  408.07
#Mann= 9 ,-1 , 0
  3634.9     .16       0  4036.5     .05       0    4237     .16       0
    4993     .07       0    5008     .16       0  5022.8     .12       0
  5233.9     .05       0  5576.5     .16       0  5984.1     .05       0
Bank Sta=4970.5,5040.6
XS Rating Curve= 0 ,0
Exp/Cntr=0.3,0.1

Type RM Length L Ch R = 1 ,11402   ,775,775,775
BEGIN DESCRIPTION:
NORTH MINERAL CREEK 14 0
END DESCRIPTION:
XS GIS Cut Line= 4
 3516778.870367910394753.2220725      3516566.81     10394443.94
      3516208.46      10393921.3      3515666.77     10392851.64
#Sta/Elev= 30
    3912  383.78 4059.99  383.65 4109.32  382.84 4207.97  377.47    4287  371.16
  4428.6  367.37  4515.2   361.7  4572.1  359.23  4838.1  359.15  4931.5  362.71
  4963.8   362.7  4976.4   357.3    4986  354.72  4991.8  350.57  5005.8  350.57
  5021.2  358.19  5036.2  361.41  5088.5   363.2  5186.5  362.39  5231.1  360.82
  5370.3     362  5447.1  360.95  5536.8   362.4  5654.3  368.07  5772.2  377.67
  5849.2  381.31  5877.1  383.71  5921.6  386.01  6027.4  390.66  6119.7  396.56
#Mann= 3 , 0 , 0
    3912     .05       0  4963.8     .03       0  5036.2     .05       0
Bank Sta=4963.8,5036.2
XS Rating Curve= 0 ,0
Exp/Cntr=0.3,0.1

Type RM Length L Ch R = 1 ,10627   ,1203,1203,1203
BEGIN DESCRIPTION:
NORTH MINERAL CREEK 13 0
END DESCRIPTION:
XS GIS Cut Line= 2
      3517842.84     10394561.11      3515686.41     10392430.72
#Sta/Elev= 30
  3598.4  395.48  3704.6   390.8  3802.5  384.08  3900.4   378.4  3916.8  376.46
  3939.3  377.09  4205.6  368.44    4250  367.38  4425.9  361.73  4652.2     359
  4956.2  362.79  4970.4  359.88  4984.5  348.92  4998.5  348.92  5005.7  351.36
  5012.8  356.43  5026.9  360.07    5034  357.48  5041.1  361.07  5048.1  360.42
  5055.2  362.57  5239.1   358.8  5537.9  359.08  5620.9  358.99  5705.8   361.9
  5917.9  375.59  5981.5  381.88  6349.3  394.26  6551.3  395.68  6629.7  397.46
#Mann= 10 ,-1 , 0
  3598.4     .05       0  3802.5      .1       0  3900.4     .05       0
  3939.3      .1       0  4205.6     .05       0    4250     .07       0
  4956.2     .03       0  5055.2     .07       0  5537.9     .05       0
  6551.3     .16       0
Bank Sta=4956.2,5055.2
XS Rating Curve= 0 ,0
Exp/Cntr=0.3,0.1

Type RM Length L Ch R = 1 ,9424    ,779,779,779
BEGIN DESCRIPTION:
NORTH MINERAL CREEK 11 1
END DESCRIPTION:
XS GIS Cut Line= 3
      3517940.25      10393544.5      3517856.92     10393047.12
      3516993.53     10392295.55
#Sta/Elev= 30
  3985.3  377.07  4307.3  366.91  4454.6  367.53  4588.8  366.22    4674  363.53
  4780.4  357.62  4801.3  357.02  4843.8  358.68  4872.5  358.55  4915.2  361.46
  4957.9  361.48  4972.2  359.67  4986.4  355.81  4993.1  350.73  4999.8   348.2
  5000.3   347.7  5014.8   348.2  5021.5   355.9  5028.2  359.36  5035.8  360.81
  5120.3  358.33  5219.6  357.77  5262.7  357.71  5340.6  360.74  5418.4  367.89
  5524.8  379.89  5553.2  385.29  5581.7  393.38    5596  396.03  5634.3  396.73
#Mann= 5 ,-1 , 0
  3985.3     .16       0  4843.8     .12       0  4999.8     .07       0
  5014.8     .12       0  5219.6     .16       0
Bank Sta=4972.2,5028.2
XS Rating Curve= 0 ,0
Exp/Cntr=0.3,0.1

Type RM Length L Ch R = 1 ,8645    ,560,560,560
BEGIN DESCRIPTION:
NORTH MINERAL CREEK 9 0
END DESCRIPTION:
XS GIS Cut Line= 3
      3518601.68      10392674.7      3518057.44     10392333.57
      3517580.89     10391883.06
#Sta/Elev= 30
  4401.4  376.74  4496.6  375.87  4548.4  374.38  4662.6  366.43  4802.2  356.33
  4883.1  356.68  4962.1  359.61  4977.4  354.54  4983.3  350.59  4991.1  347.55
  4991.6  347.05  5006.1  347.55  5013.9  352.07  5019.8   357.6  5026.4  359.73
  5040.8  361.11  5063.1  361.23  5133.6  359.33  5183.3  360.22  5268.3  358.95
  5303.4  357.48  5324.9  357.81  5388.4  362.16  5430.9  366.55  5473.4  371.76
  5505.8   377.5  5593.5  397.07  5621.8  399.85    5636  399.69  5699.5  403.14
#Mann= 5 ,-1 , 0
  4401.4     .16       0  4662.6     .12       0  4991.1     .07       0
  5006.1     .12       0  5505.8     .16       0
Bank Sta=4962.1,5026.4
XS Rating Curve= 0 ,0
Exp/Cntr=0.3,0.1

Type RM Length L Ch R = 1 ,8085    ,899,899,899
BEGIN DESCRIPTION:
NORTH MINERAL CREEK 8 0
END DESCRIPTION:
XS GIS Cut Line= 3
      3518855.45     10392636.78      3518405.45     10391836.79
      3517606.24     10391686.94
#Sta/Elev= 30
  4225.2  376.52  4320.5  374.25  4509.8  375.34  4793.2  358.94  4839.3  357.52
  4952.1  358.45  4965.4  354.19  4973.8  355.38  4979.6  348.95  5003.8  347.58
  5004.3  347.08  5018.8  347.58  5022.9  351.37  5033.1  350.87  5038.8  356.37
  5054.8  356.56  5060.5  359.45    5126  359.65  5217.7  356.44    5358  358.35
  5451.7  355.56  5606.1   365.6  5688.6     372  5793.8  387.26  5798.9  386.77
  5846.3  392.87  5851.4   392.1  5889.2  396.39    5904  395.67  5956.2  398.93
#Mann= 5 ,-1 , 0
  4225.2     .16       0  4793.2     .12       0  5003.8     .07       0
  5018.8     .12       0  5606.1     .16       0
Bank Sta=4952.1,5060.5
XS Rating Curve= 0 ,0
Exp/Cntr=0.3,0.1

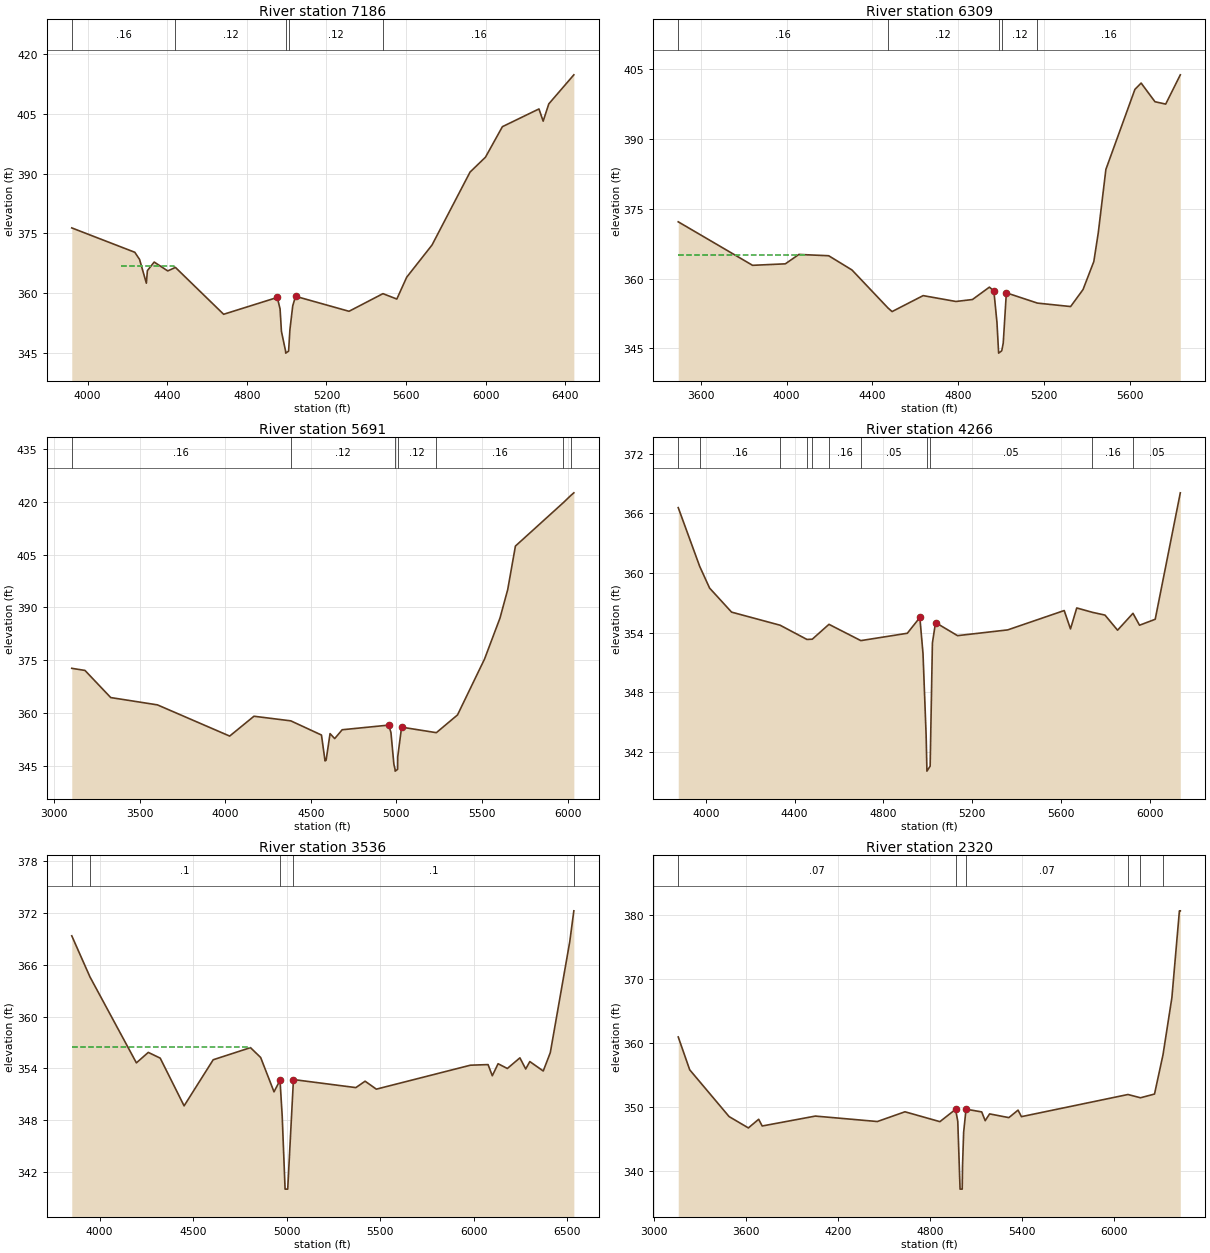
Type RM Length L Ch R = 1 ,7186    ,877,877,877
BEGIN DESCRIPTION:
NORTH MINERAL CREEK 29 1
END DESCRIPTION:
XS GIS Cut Line= 3
      3519757.14     10391568.23      3518859.12      10391316.3
      3517759.31     10390166.49
#Sta/Elev= 30
  3920.1  376.37  4236.9  370.25    4261  368.44  4295.1  362.48  4300.3  365.64
  4334.4  367.79  4402.6  365.56  4441.2  366.44  4683.5  354.67  4953.1   358.9
  4967.2  356.01  4974.1  350.35    4995  345.41  4995.5  344.91    5010  345.41
  5016.6  350.77  5030.8  356.78  5044.9  359.19  5313.8  355.42  5484.3  359.85
  5554.1   358.5  5603.8  363.99    5731  372.07  5922.1  390.39  5999.7  394.14
  6084.7   401.8  6268.6  406.26  6289.7  403.19    6318  407.53  6443.9  414.83
#Mann= 5 ,-1 , 0
  3920.1     .16       0  4441.2     .12       0    4995     .07       0
    5010     .12       0  5484.3     .16       0
#XS Ineff= 1 ,-1
 4169.34 4432.84  366.88
Permanent Ineff=
       F
Bank Sta=4953.1,5044.9
XS Rating Curve= 0 ,0
Exp/Cntr=0.3,0.1

Type RM Length L Ch R = 1 ,6309    ,618,618,618
BEGIN DESCRIPTION:
NORTH MINERAL CREEK 19 3
END DESCRIPTION:
XS GIS Cut Line= 3
       3520321.4     10391362.07       3519261.2     10390664.91
      3518412.33     10390015.77
#Sta/Elev= 30
  3495.8  372.19    3842  362.84  3994.4  363.16  4057.6  365.18  4196.2   364.9
  4304.7  361.84  4472.6  353.66  4491.4   352.9    4636  356.33  4788.6  355.07
  4865.6  355.49  4944.5  358.15  4965.3  357.34  4979.8  350.51  4986.9  344.47
  4987.4  343.97  5001.9  344.47  5008.9  346.12  5023.4  356.93  5168.3  354.72
  5322.6  353.98  5380.4  357.63  5430.6  363.65  5451.4  369.84  5486.8  383.45
  5621.9  400.65  5650.9  402.01  5715.3     398  5765.2  397.49  5833.3  403.78
#Mann= 5 ,-1 , 0
  3495.8     .16       0  4472.6     .12       0  4986.9     .07       0
  5001.9     .12       0  5168.3     .16       0
#XS Ineff= 2 , 0
         4098.89  365.14
Permanent Ineff=
       F       F
Bank Sta=4965.3,5023.4
XS Rating Curve= 0 ,0
Exp/Cntr=0.3,0.1

Type RM Length L Ch R = 1 ,5691    ,1425,1425,1425
BEGIN DESCRIPTION:
NORTH MINERAL CREEK 8 1
END DESCRIPTION:
XS GIS Cut Line= 3
      3520863.94     10391069.11      3519503.51     10390059.58
      3518389.96     10389517.44
#Sta/Elev= 30
  3104.2  372.69  3181.4  372.09  3331.7  364.38  3604.6   362.3  4026.5  353.43
  4168.4  359.07  4383.5  357.76  4562.7  353.73  4583.6  346.36  4589.8  346.57
  4612.8  354.13  4639.9  352.72  4683.7  355.23  4955.6  356.55  4968.6  354.42
  4985.6  345.47  4992.5  343.97    4993  343.47  5007.5  343.97  5008.1  347.53
  5030.7  355.97  5233.8   354.4  5357.4  359.45  5515.2  375.33  5605.4  386.97
  5650.5  395.06  5695.6  407.44  5974.8  419.75  6019.7  421.85  6036.8  422.57
#Mann= 7 ,-1 , 0
  3104.2     .16       0  4383.5     .12       0  4992.5     .07       0
  5007.5     .12       0  5233.8     .16       0  5974.8      .1       0
  6019.7     .16       0
Bank Sta=4955.6,5030.7
XS Rating Curve= 0 ,0
Exp/Cntr=0.3,0.1

Type RM Length L Ch R = 1 ,4266    ,730,730,730
BEGIN DESCRIPTION:
NORTH MINERAL CREEK 61 0
END DESCRIPTION:
XS GIS Cut Line= 3
       3520792.1     10390641.63      3519992.11     10389841.64
      3519192.13     10389041.66
#Sta/Elev= 30
  3875.7  366.59  3972.4  360.67  4017.1  358.48  4116.1  356.06    4335  354.74
  4455.5  353.31  4479.6  353.33    4555  354.83  4698.6  353.19  4908.1  353.93
  4964.6  355.52  4978.8  351.89  4992.9  343.64    4996  340.54  4996.5  340.04
    5011  340.54  5021.2  352.95  5035.3  355.01  5134.3  353.69  5360.6  354.27
  5615.2  356.22  5643.5  354.37  5671.7  356.48  5742.3  356.04    5799  355.76
  5855.6  354.24  5925.1  355.94  5954.6  354.74  6025.3  355.34  6138.4  368.08
#Mann= 11 ,-1 , 0
  3875.7     .05       0  3972.4     .16       0    4335      .1       0
  4455.5     .16       0  4479.6     .05       0    4555     .16       0
  4698.6     .05       0    4996     .03       0    5011     .05       0
  5742.3     .16       0  5925.1     .05       0
Bank Sta=4964.6,5035.3
XS Rating Curve= 0 ,0
Exp/Cntr=0.3,0.1

Type RM Length L Ch R = 1 ,3536    ,1216,1216,1216
BEGIN DESCRIPTION:
NORTH MINERAL CREEK 41 0
END DESCRIPTION:
XS GIS Cut Line= 3
       3521388.1      10390253.4      3520791.73     10389581.51
      3519218.01     10388736.13
#Sta/Elev= 30
  3851.3  369.34  3948.6  364.59  4196.9  354.65  4260.5  355.86  4324.1   355.2
    4452  349.68  4607.6  355.01    4807  356.41  4861.4  355.27  4932.8   351.3
  4964.9  352.64  4976.6  348.49    4992  340.05    5006  340.05  5036.7  352.72
  5370.4  351.79  5419.9  352.53  5479.9  351.61  5983.2  354.38  6077.4  354.45
  6100.1  353.16    6131  354.55  6180.5     354  6247.7  355.23  6278.7  353.94
  6300.7   354.8  6372.5  353.71  6410.2  355.83  6514.1  368.64  6536.1  372.23
#Mann= 5 ,-1 , 0
  3851.3     .05       0  3948.6      .1       0  4964.9     .05       0
  5036.7      .1       0  6536.1     .05       0
#XS Ineff= 2 , 0
         4802.56  356.51
Permanent Ineff=
       F       F
Bank Sta=4964.9,5036.7
XS Rating Curve= 0 ,0
Exp/Cntr=0.3,0.1

Type RM Length L Ch R = 1 ,2320    ,968,968,968
BEGIN DESCRIPTION:
NORTH MINERAL CREEK 31 0
END DESCRIPTION:
XS GIS Cut Line= 3
      3522403.74     10389461.74      3520156.31     10388248.18
      3519627.65     10387758.58
#Sta/Elev= 30
  3155.4  360.97  3230.2  355.84  3487.2  348.53  3612.8  346.76    3680  348.11
  3702.8  347.06  4049.7  348.61  4454.2  347.76  4634.2  349.28    4862  347.74
  4964.3  349.66  4978.7  347.79  4993.6   337.2  5007.6   337.2  5009.7  340.85
  5016.8  346.04  5032.4  349.69  5134.7  349.26  5157.5  347.89  5186.2  348.95
  5311.9  348.37  5371.9  349.54  5393.8  348.52  6088.7  351.98  6170.4  351.47
  6261.8  352.05  6317.4  358.21  6375.2  367.12  6424.2  380.67  6430.1  380.67
#Mann= 6 ,-1 , 0
  3155.4     .07       0  4964.3     .05       0  5032.4     .07       0
  6088.7      .1       0  6170.4     .05       0  6317.4      .1       0
Bank Sta=4964.3,5032.4
XS Rating Curve= 0 ,0
Exp/Cntr=0.3,0.1

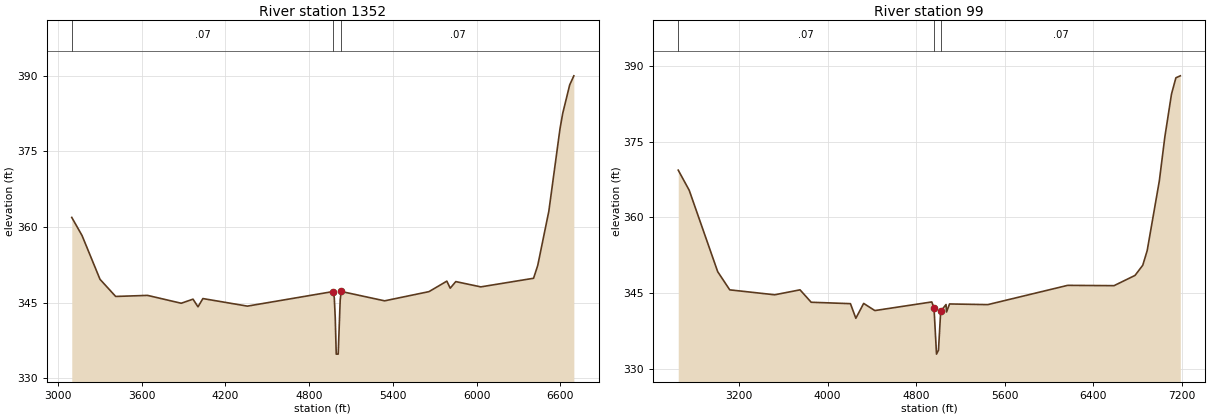
Type RM Length L Ch R = 1 ,1352    ,1253,1253,1253
BEGIN DESCRIPTION:
NORTH MINERAL CREEK 20 1
END DESCRIPTION:
XS GIS Cut Line= 4
       3522518.3     10389425.29      3522286.52     10388956.51
     3520813.219    10387343.639     3519945.164    10387138.778
#Sta/Elev= 30
  3098.7   361.9  3172.2  358.31  3301.2  349.61  3413.4  346.21  3642.1  346.42
  3883.2  344.86  3967.7  345.67  4003.5  344.15  4038.6  345.79  4357.5  344.29
    4973  347.19  4980.4  345.93  4987.2  342.01  4994.4  334.76  5008.4  334.76
  5022.8  345.52  5029.8   347.2  5341.2  345.34  5659.4  347.17  5787.1  349.25
 5811.36  347.85 5851.18  349.16  6030.4  348.11 6408.74  349.82 6438.61  352.36
 6518.27  363.14 6597.92  379.44 6617.83  382.57 6667.61   388.2 6697.48  390.01
#Mann= 3 , 0 , 0
  3098.7     .07       0    4973     .05       0  5029.8     .07       0
Bank Sta=4973,5029.8
XS Rating Curve= 0 ,0
Exp/Cntr=0.3,0.1

Type RM Length L Ch R = 1 ,99      ,0,0,0
BEGIN DESCRIPTION:
NORTH MINERAL CREEK 20 3
END DESCRIPTION:
XS GIS Cut Line= 3
 3522642.704953210389582.3661994      3522513.09     10388657.05
     3520354.886    10386354.055
#Sta/Elev= 30
 2648.45  369.37 2747.55  365.39 3005.21  349.24 3114.23  345.63 3520.54  344.65
  3749.8  345.63  3850.8  343.17  4205.9  342.89  4254.7  339.99  4325.4  342.94
  4426.4  341.52  4941.3  343.23  4961.5  342.07  4984.2  332.88  5001.9  333.66
  5022.1  341.38  5070.3  342.72  5075.3  341.24  5101.8  342.83  5448.5   342.7
 6170.05  346.52 6589.61  346.46 6779.42  348.49 6849.35  350.51  6889.3   353.4
 6999.19  367.23 7049.14  375.96 7109.08  384.44 7149.04  387.69 7188.99  388.08
#Mann= 3 , 0 , 0
 2648.45     .07       0  4961.5     .03       0  5022.1     .07       0
Bank Sta=4961.5,5022.1
XS Rating Curve= 0 ,0
Exp/Cntr=0.3,0.1

Chan Stop Cuts=-1
Use User Specified Reach Order=0
Composite Channel Slope=5