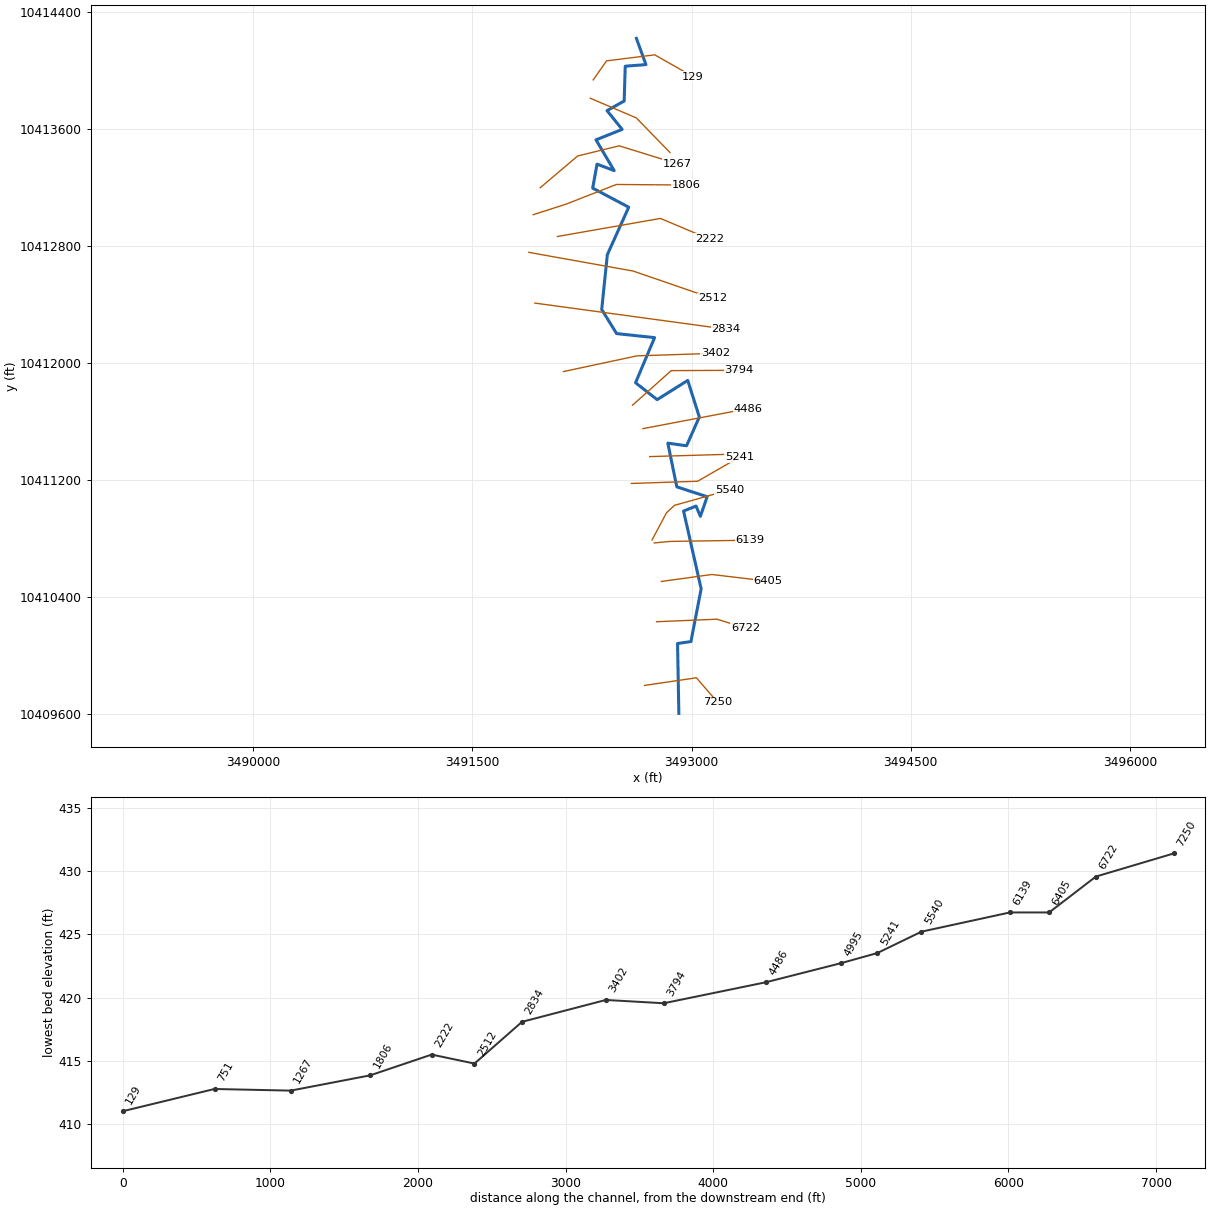
--- OLIVER BRANCH TRIB 2.prj (project) ---

Proj Title=OLIVER BRANCH TRIB 2 Base Level Engineering
Current Plan=p01
Default Exp/Contr=0.3,0.1
English Units
Geom File=g01
Flow File=f01
Plan File=p01
BEGIN DESCRIPTION:
OLIVER BRANCH TRIB 2
END DESCRIPTION:

--- OLIVER BRANCH TRIB 2.p01 (plan) ---

Plan Title=Multiple Run
Short Identifier=Multiple
Geom File=g01
Flow File=f01
Subcritical Flow
K Sum by GR= 0
Std Step Tol= 0.01
Critical Tol= 0.01
Num of Std Step Trials= 20
Max Error Tol= 0.3
Flow Tol Ratio= 0.001
Split Flow NTrial= 30
Split Flow Tol= 0.02
Split Flow Ratio= 0.02
Log Output Level= 0
Friction Slope Method= 1
Unsteady Friction Slope Method= 2
Unsteady Bridges Friction Slope Method= 1
Parabolic Critical Depth
Global Vel Dist=  1 , 1 , 1
Global Log Level= 0
CheckData=True
Encroach Param= -1, 0, 0, 0
BEGIN DESCRIPTION:
Multiple Run
END DESCRIPTION:

--- OLIVER BRANCH TRIB 2.f01 (steady flow) ---

Flow Title=Multiple
Number of Profiles=7
Profile Names=10-year,25-year,50-year,1pct_min,100-year,1pct_plu,500-year
River Rch & RM= OLIVER BRANCH TR,Reach-1,7250
     802    1094    1334    1186    1604    2170    2316
Boundary for River Rch & Prof#=OLIVER BRANCH TR,Reach-1,1
Up Type=0
Dn Type=3
Dn Slope=0.005
Boundary for River Rch & Prof#=OLIVER BRANCH TR,Reach-1,2
Up Type=0
Dn Type=3
Dn Slope=0.005
Boundary for River Rch & Prof#=OLIVER BRANCH TR,Reach-1,3
Up Type=0
Dn Type=3
Dn Slope=0.005
Boundary for River Rch & Prof#=OLIVER BRANCH TR,Reach-1,4
Up Type=0
Dn Type=3
Dn Slope=0.005
Boundary for River Rch & Prof#=OLIVER BRANCH TR,Reach-1,5
Up Type=0
Dn Type=3
Dn Slope=0.005
Boundary for River Rch & Prof#=OLIVER BRANCH TR,Reach-1,6
Up Type=0
Dn Type=3
Dn Slope=0.005
Boundary for River Rch & Prof#=OLIVER BRANCH TR,Reach-1,7
Up Type=0
Dn Type=3
Dn Slope=0.005

--- OLIVER BRANCH TRIB 2.g01 (geometry) ---

Geom Title=Existing Conditions

River Reach=OLIVER BRANCH TR,Reach-1
Reach XY= 30
      3492912.83     10409601.28      3492903.98     10410079.40
      3492995.65     10410092.94      3493065.44     10410453.88
      3492945.13     10410986.17      3493030.54     10411020.03
      3493060.23     10410950.24      3493106.58     10411084.09
      3492898.77     10411151.80      3492837.31     10411450.76
      3492965.44     10411433.05      3493052.94     10411629.92
      3492973.77     10411880.44      3492764.40     10411748.67
      3492616.48     10411864.30      3492746.69     10412173.15
      3492486.79     10412200.76      3492384.83     10412365.74
      3492423.37     10412740.74      3492569.72     10413065.88
      3492323.12     10413196.38      3492352.77     10413360.49
      3492470.12     10413316.20      3492345.72     10413526.99
      3492524.75     10413598.33      3492421.40     10413726.91
      3492538.64     10413792.66      3492545.79     10414031.00
      3492687.53     10414041.94      3492622.11     10414221.64

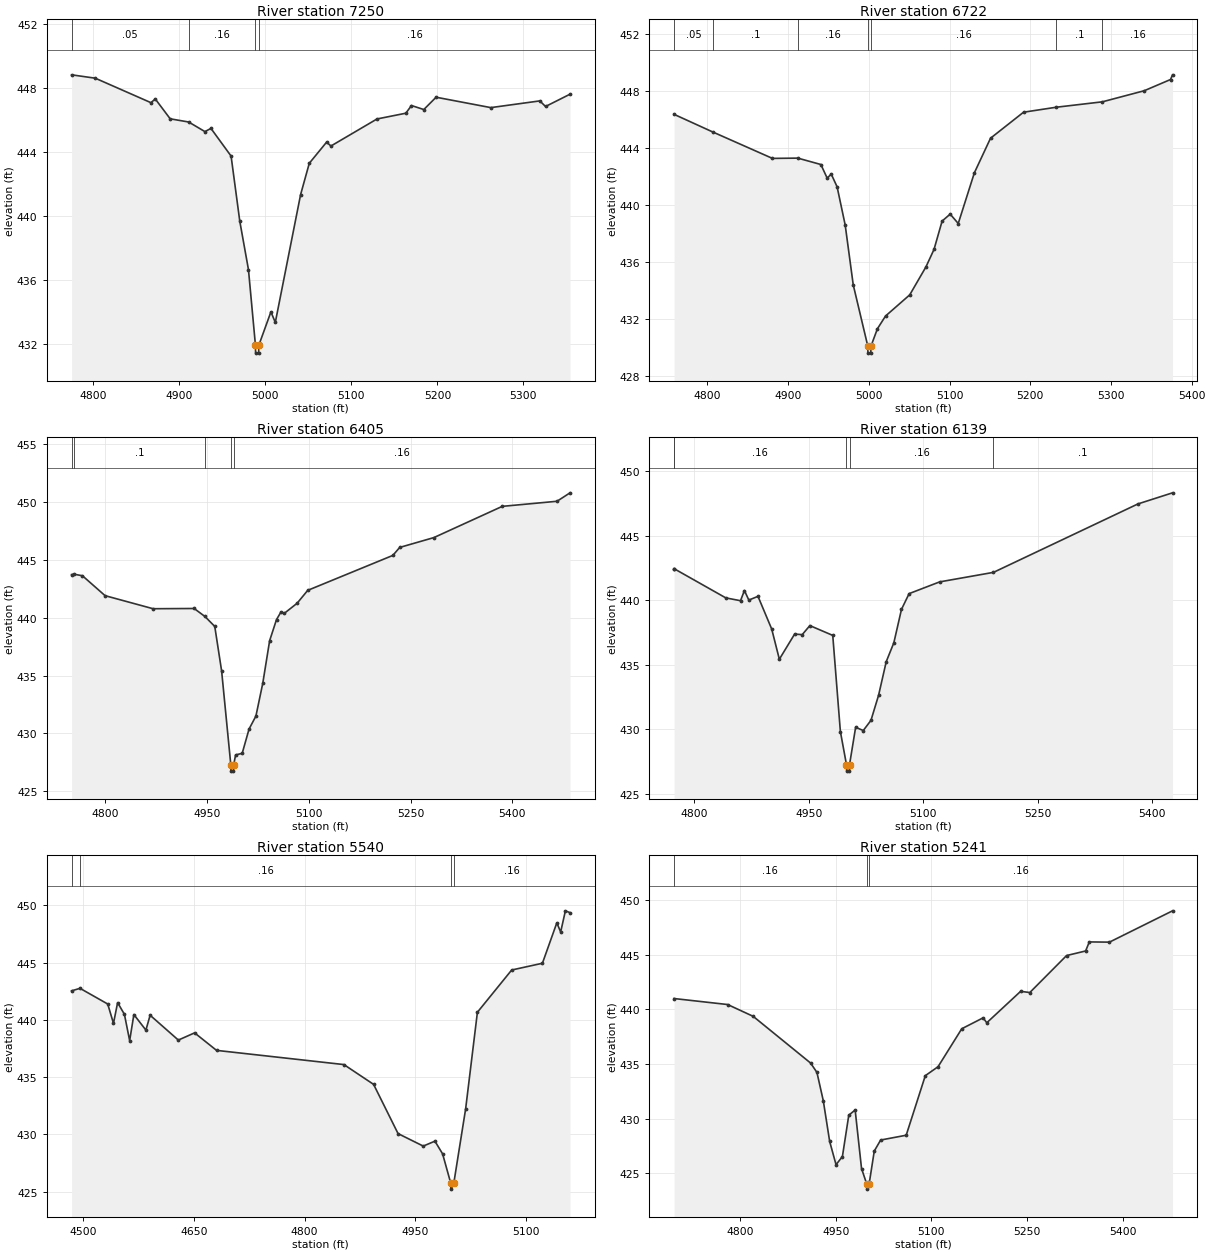
Type RM Length L Ch R = 1,7250,528,528,528
BEGIN DESCRIPTION:
OLIVER BRANCH TRIB 2 3 0
END DESCRIPTION:
XS GIS Cut Line= 3
      3492678.72     10409792.80      3493032.86     10409844.88
      3493177.83     10409677.48
#Sta/Elev= 30
  4774.8  448.81  4802.3  448.60  4867.0  447.07  4872.1  447.30  4889.4  446.06
  4910.9  445.86  4929.8  445.26  4936.8  445.46  4960.2  443.73  4970.3  439.66
  4980.4  436.63  4988.5  431.91  4988.7  431.41  4992.2  431.41  4992.5  431.91
  5006.5  433.99  5011.6  433.33  5041.0  441.32  5051.1  443.28  5071.2  444.60
  5076.3  444.36  5129.8  446.05  5163.3  446.41  5169.9  446.89  5184.2  446.64
  5198.5  447.41  5262.1  446.76  5319.1  447.18  5325.7  446.83  5354.2  447.60
#Mann=4,-1,0
  4774.8    0.05       0  4910.9    0.16       0  4988.5    0.07       0
  4992.5    0.16       0
Bank Sta=4988.5,4992.5
Exp/Cntr=0.3,0.1

Type RM Length L Ch R = 1,6722,317,317,317
BEGIN DESCRIPTION:
OLIVER BRANCH TRIB 2 2 0
END DESCRIPTION:
XS GIS Cut Line= 3
      3492760.32     10410228.56      3493173.48     10410245.92
      3493368.42     10410185.54
#Sta/Elev= 30
  4758.7  446.38  4806.6  445.14  4880.6  443.28  4912.0  443.30  4940.6  442.85
  4948.4  441.89  4953.4  442.18  4960.7  441.28  4970.7  438.60  4980.7  434.38
  4998.7  430.08  4998.9  429.58  5002.4  429.58  5002.7  430.08  5010.7  431.30
  5020.7  432.19  5050.7  433.68  5070.8  435.65  5080.8  436.88  5090.8  438.87
  5100.8  439.36  5110.8  438.70  5130.8  442.27  5150.8  444.70  5191.7  446.53
  5232.2  446.88  5289.3  447.26  5341.2  448.04  5373.8  448.83  5376.3  449.16
#Mann=7,-1,0
  4758.7    0.05       0  4806.6     0.1       0  4912.0    0.16       0
  4998.7    0.07       0  5002.7    0.16       0  5232.2     0.1       0
  5289.3    0.16       0
Bank Sta=4998.7,5002.7
Exp/Cntr=0.3,0.1

Type RM Length L Ch R = 1,6405,266,266,266
BEGIN DESCRIPTION:
OLIVER BRANCH TRIB 2 13 0
END DESCRIPTION:
XS GIS Cut Line= 3
      3492793.27     10410504.17      3493138.35     10410551.91
      3493521.20     10410506.49
#Sta/Elev= 30
  4751.0  443.73  4755.1  443.76  4767.0  443.63  4800.3  441.91  4871.0  440.78
  4931.5  440.80  4947.3  440.11  4961.8  439.25  4971.9  435.40  4985.5  427.24
  4985.7  426.74  4989.2  426.74  4989.5  427.24  4992.5  428.14  5002.2  428.28
  5012.3  430.38  5022.4  431.50  5032.5  434.34  5042.6  438.02  5052.7  439.84
  5059.3  440.50  5064.4  440.39  5083.0  441.25  5098.7  442.37  5224.0  445.39
  5234.1  446.08  5284.4  446.93  5385.1  449.63  5465.7  450.07  5484.9  450.80
#Mann=5,-1,0
  4751.0    0.05       0  4755.1     0.1       0  4947.3    0.16       0
  4985.5    0.07       0  4989.5    0.16       0
Bank Sta=4985.5,4989.5
Exp/Cntr=0.3,0.1

Type RM Length L Ch R = 1,6139,599,599,599
BEGIN DESCRIPTION:
OLIVER BRANCH TRIB 2 12 0
END DESCRIPTION:
XS GIS Cut Line= 3
      3492744.58     10410767.79      3492851.07     10410778.16
      3493397.41     10410786.64
#Sta/Elev= 30
  4773.3  442.44  4773.5  442.44  4841.1  440.18  4860.4  439.96  4865.5  440.75
  4871.3  440.01  4883.3  440.30  4901.3  437.76  4911.3  435.42  4931.3  437.37
  4941.3  437.33  4951.3  438.03  4981.3  437.27  4991.3  429.81  4999.3  427.24
  4999.6  426.74  5003.1  426.74  5003.3  427.24  5011.3  430.14  5021.3  429.89
  5031.4  430.68  5041.4  432.63  5051.4  435.23  5061.4  436.70  5071.4  439.29
  5081.4  440.51  5121.4  441.42  5192.0  442.16  5381.4  447.47  5426.7  448.33
#Mann=5,-1,0
  4773.3     0.1       0  4773.5    0.16       0  4999.3    0.07       0
  5003.3    0.16       0  5192.0     0.1       0
Bank Sta=4999.3,5003.3
Exp/Cntr=0.3,0.1

Type RM Length L Ch R = 1,5540,299,299,299
BEGIN DESCRIPTION:
Mapping XS 36a5480b
END DESCRIPTION:
XS GIS Cut Line= 4
      3492729.45     10410788.51      3492828.44     10410974.24
      3492883.12     10411025.15      3493258.16     10411130.42
#Sta/Elev= 30
  4484.7  442.54  4496.1  442.76  4533.6  441.39  4541.4  439.70  4547.0  441.51
  4556.2  440.49  4563.3  438.19  4569.0  440.47  4585.3  439.11  4591.0  440.41
  4629.2  438.24  4651.2  438.87  4680.9  437.34  4853.3  436.10  4893.5  434.37
  4926.6  430.07  4960.7  428.98  4976.5  429.41  4986.9  428.30  4998.0  425.72
  4998.2  425.22  5002.0  425.72  5018.1  432.24  5034.0  440.67  5080.4  444.36
  5122.0  444.95  5141.5  448.48  5146.7  447.68  5153.1  449.53  5159.4  449.37
#Mann=4,-1,0
  4484.7     0.1       0  4496.1    0.16       0  4998.0    0.07       0
  5002.0    0.16       0
Bank Sta=4998,5002
Exp/Cntr=0.3,0.1

Type RM Length L Ch R = 1,5241,246,246,246
BEGIN DESCRIPTION:
OLIVER BRANCH TRIB 2 11 0
END DESCRIPTION:
XS GIS Cut Line= 3
      3492588.05     10411175.03      3493041.49     10411190.12
      3493326.22     10411354.17
#Sta/Elev= 30
  4696.1  441.00  4780.2  440.45  4820.2  439.37  4910.3  435.09  4920.3  434.23
  4930.3  431.63  4940.3  427.90  4950.3  425.77  4960.3  426.52  4970.3  430.31
  4980.3  430.78  4990.3  425.42  4998.3  424.03  4998.6  423.53  5002.3  424.03
  5010.3  427.02  5020.3  428.03  5060.4  428.47  5090.4  433.93  5110.4  434.75
  5147.6  438.23  5181.1  439.23  5186.9  438.78  5240.0  441.66  5254.4  441.55
  5312.1  444.94  5342.0  445.36  5347.8  446.19  5379.4  446.17  5478.4  449.04
#Mann=3,-1,0
  4696.1    0.16       0  4998.3    0.07       0  5002.3    0.16       0
Bank Sta=4998.3,5002.3
Exp/Cntr=0.3,0.1

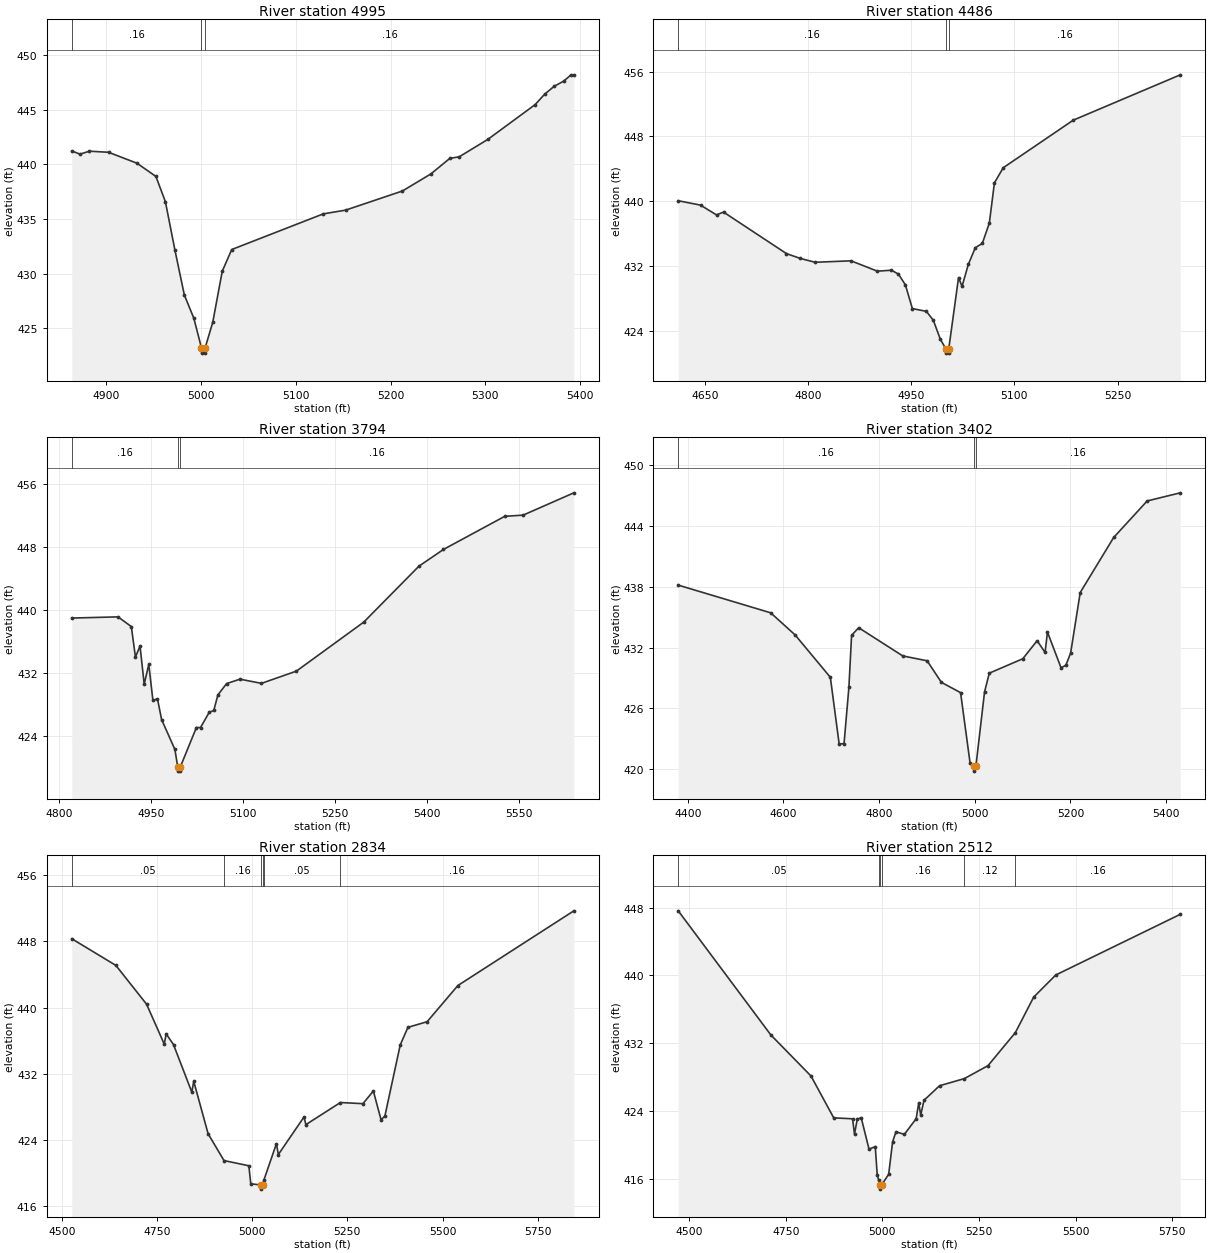
Type RM Length L Ch R = 1,4995,509,509,509
BEGIN DESCRIPTION:
OLIVER BRANCH TRIB 2 10 0
END DESCRIPTION:
XS GIS Cut Line= 2
      3492713.36     10411358.77      3493242.93     10411374.40
#Sta/Elev= 30
  4863.6  441.21  4872.3  440.92  4882.3  441.19  4902.4  441.09  4932.4  440.09
  4952.4  438.88  4962.4  436.57  4972.4  432.17  4982.4  428.04  4992.4  425.92
  5000.4  423.23  5000.7  422.73  5004.2  422.73  5004.4  423.23  5012.4  425.56
  5022.4  430.22  5032.4  432.20  5129.0  435.46  5152.5  435.80  5212.5  437.55
  5242.5  439.11  5262.5  440.53  5272.5  440.68  5302.5  442.26  5352.6  445.45
  5362.6  446.40  5372.6  447.12  5382.6  447.59  5390.5  448.17  5393.4  448.17
#Mann=3,-1,0
  4863.6    0.16       0  5000.4    0.07       0  5004.4    0.16       0
Bank Sta=5000.4,5004.4
Exp/Cntr=0.3,0.1

Type RM Length L Ch R = 1,4486,692,692,692
BEGIN DESCRIPTION:
OLIVER BRANCH TRIB 2 9 0
END DESCRIPTION:
XS GIS Cut Line= 2
      3492667.40     10411550.17      3493385.12     10411686.78
#Sta/Elev= 30
  4610.8  440.04  4643.2  439.50  4666.5  438.29  4676.7  438.64  4768.3  433.51
  4788.6  432.91  4810.0  432.44  4862.2  432.62  4900.6  431.34  4921.0  431.46
  4931.2  430.98  4941.3  429.66  4951.5  426.72  4971.9  426.38  4982.0  425.27
  4992.2  422.94  5000.4  421.72  5000.7  421.22  5004.2  421.22  5004.4  421.72
  5018.7  430.55  5023.8  429.46  5032.9  432.17  5043.1  434.24  5053.3  434.77
  5063.5  437.28  5070.9  442.25  5083.8  444.12  5185.6  449.99  5341.4  455.59
#Mann=3,-1,0
  4610.8    0.16       0  5000.4    0.07       0  5004.4    0.16       0
Bank Sta=5000.4,5004.4
Exp/Cntr=0.3,0.1

Type RM Length L Ch R = 1,3794,392,392,392
BEGIN DESCRIPTION:
OLIVER BRANCH TRIB 2 8 1
END DESCRIPTION:
XS GIS Cut Line= 3
      3492595.81     10411710.77      3492860.57     10411947.31
      3493324.93     10411949.48
#Sta/Elev= 30
  4820.4  438.97  4895.9  439.12  4917.6  437.89  4924.3  434.03  4931.8  435.41
  4938.6  430.59  4946.1  433.09  4952.8  428.53  4960.3  428.72  4967.0  426.10
  4988.7  422.31  4993.4  420.06  4993.6  419.56  4997.1  419.56  4997.4  420.06
  5023.8  425.09  5030.5  425.09  5044.7  427.01  5052.2  427.26  5058.9  429.23
  5073.1  430.66  5094.9  431.22  5130.0  430.69  5187.0  432.24  5297.0  438.46
  5387.0  445.55  5427.0  447.67  5527.0  451.87  5557.0  452.02  5639.8  454.85
#Mann=3,-1,0
  4820.4    0.16       0  4993.4    0.07       0  4997.4    0.16       0
Bank Sta=4993.4,4997.4
Exp/Cntr=0.3,0.1

Type RM Length L Ch R = 1,3402,568,568,568
BEGIN DESCRIPTION:
OLIVER BRANCH TRIB 2 8 0
END DESCRIPTION:
XS GIS Cut Line= 3
      3492123.09     10411940.76      3492626.60     10412048.41
      3493161.33     10412065.77
#Sta/Elev= 30
  4379.9  438.16  4573.2  435.43  4624.3  433.25  4698.0  429.07  4716.4  422.50
  4726.6  422.53  4736.8  428.10  4742.4  433.21  4757.3  433.96  4849.3  431.18
  4900.3  430.70  4930.3  428.57  4970.3  427.56  4990.3  420.58  4998.4  420.32
  4998.6  419.82  5002.4  420.32  5020.4  427.62  5030.4  429.48  5100.4  430.90
  5130.4  432.68  5147.0  431.52  5152.0  433.53  5180.4  430.01  5190.5  430.26
  5200.5  431.47  5220.5  437.43  5290.5  442.86  5360.5  446.46  5429.8  447.26
#Mann=3,-1,0
  4379.9    0.16       0  4998.4    0.07       0  5002.4    0.16       0
Bank Sta=4998.4,5002.4
Exp/Cntr=0.3,0.1

Type RM Length L Ch R = 1,2834,322,322,322
BEGIN DESCRIPTION:
OLIVER BRANCH TRIB 2 6 1
END DESCRIPTION:
XS GIS Cut Line= 2
      3491927.39     10412409.56      3493233.83     10412231.60
#Sta/Elev= 30
  4526.3  448.33  4642.1  445.11  4722.8  440.42  4769.2  435.60  4774.2  436.84
  4793.5  435.54  4841.6  429.80  4846.6  431.11  4884.3  424.78  4926.1  421.54
  4991.3  420.91  4996.4  418.73  5023.6  418.59  5023.8  418.09  5027.6  418.59
  5031.3  419.25  5063.7  423.57  5068.8  422.27  5136.1  426.80  5141.1  425.88
  5231.8  428.55  5290.9  428.41  5318.3  429.94  5338.4  426.48  5348.5  426.90
  5388.9  435.51  5409.1  437.63  5459.5  438.31  5540.3  442.68  5844.8  451.70
#Mann=6,-1,0
  4526.3    0.05       0  4926.1    0.16       0  5023.6    0.07       0
  5027.6    0.16       0  5031.3    0.05       0  5231.8    0.16       0
Bank Sta=5023.6,5027.6
Exp/Cntr=0.3,0.1

Type RM Length L Ch R = 1,2512,290,290,290
BEGIN DESCRIPTION:
OLIVER BRANCH TRIB 2 7 0
END DESCRIPTION:
XS GIS Cut Line= 3
      3491886.15     10412756.78      3492600.15     10412628.74
      3493142.66     10412442.12
#Sta/Elev= 30
  4471.7  447.63  4711.4  432.98  4815.2  428.14  4874.0  423.20  4922.7  423.09
  4927.8  421.29  4934.9  423.04  4945.1  423.22  4965.4  419.50  4981.5  419.81
  4986.6  416.46  4990.6  415.82  4993.9  415.29  4994.1  414.79  4997.9  415.29
  5016.2  416.54  5026.4  420.38  5035.2  421.56  5056.8  421.25  5087.3  423.10
  5094.0  424.97  5099.1  423.53  5107.6  425.27  5147.8  426.99  5211.9  427.83
  5273.2  429.36  5344.0  433.26  5391.4  437.45  5448.6  440.06  5770.8  447.22
#Mann=6,-1,0
  4471.7    0.05       0  4990.6    0.16       0  4993.9    0.07       0
  4997.9    0.16       0  5211.9    0.12       0  5344.0    0.16       0
Bank Sta=4993.9,4997.9
Exp/Cntr=0.3,0.1

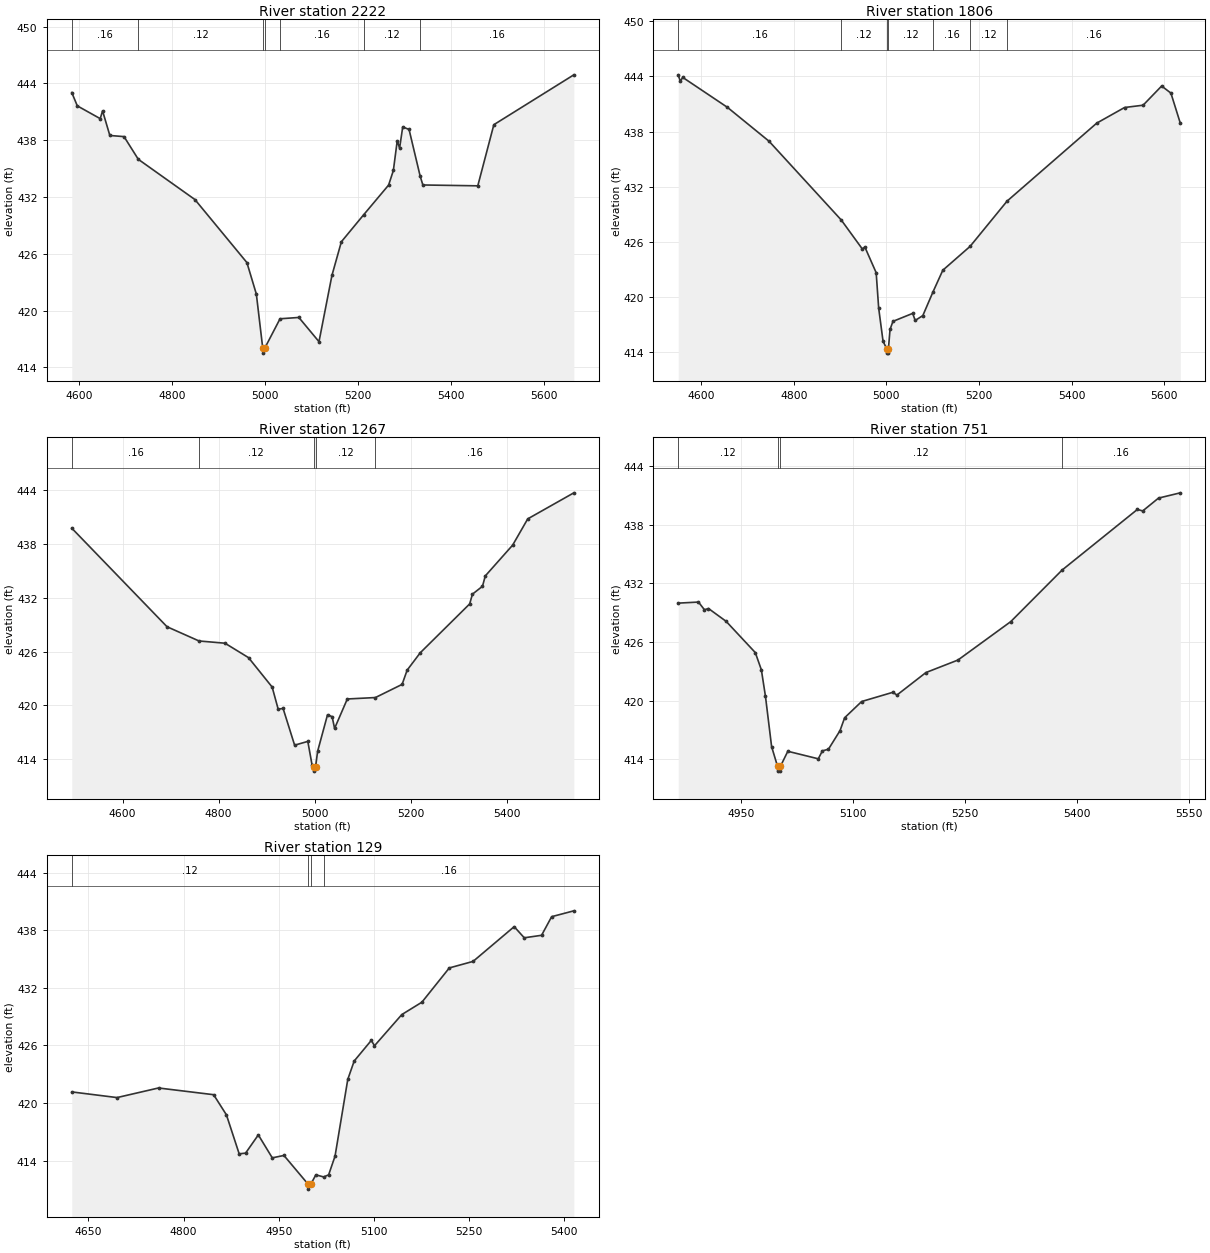
Type RM Length L Ch R = 1,2222,416,416,416
BEGIN DESCRIPTION:
OLIVER BRANCH TRIB 2 6 0
END DESCRIPTION:
XS GIS Cut Line= 3
      3492081.49     10412865.28      3492786.78     10412988.98
      3493120.98     10412847.92
#Sta/Elev= 30
  4584.8  443.04  4596.7  441.63  4645.9  440.28  4651.0  441.10  4666.6  438.50
  4697.1  438.38  4727.8  435.98  4849.4  431.73  4961.1  425.07  4981.4  421.74
  4995.2  416.00  4995.5  415.50  4999.2  416.00  5032.3  419.13  5072.7  419.27
  5116.0  416.71  5143.8  423.71  5164.1  427.27  5211.8  430.11  5265.6  433.26
  5275.8  434.80  5284.1  437.94  5289.2  437.17  5295.9  439.40  5309.5  439.14
  5333.4  434.20  5339.2  433.27  5457.2  433.18  5491.7  439.64  5663.6  444.91
#Mann=7,-1,0
  4584.8    0.16       0  4727.8    0.12       0  4995.2    0.07       0
  4999.2    0.12       0  5032.3    0.16       0  5211.8    0.12       0
  5333.4    0.16       0
Bank Sta=4995.2,4999.2
Exp/Cntr=0.3,0.1

Type RM Length L Ch R = 1,1806,539,539,539
BEGIN DESCRIPTION:
OLIVER BRANCH TRIB 2 5 1
END DESCRIPTION:
XS GIS Cut Line= 4
      3491915.56     10413014.44      3492138.90     10413085.98
      3492485.26     10413221.40      3492962.43     10413217.57
#Sta/Elev= 30
  4550.7  444.18  4555.1  443.47  4560.4  443.90  4656.8  440.64  4746.6  436.95
  4902.6  428.36  4948.1  425.20  4953.4  425.43  4977.9  422.62  4983.3  418.76
  4992.7  415.17  5000.4  414.36  5000.6  413.86  5004.1  413.86  5004.4  414.36
  5007.8  416.44  5014.1  417.32  5056.7  418.19  5062.1  417.42  5078.6  417.95
  5100.8  420.56  5121.7  422.89  5180.6  425.49  5260.4  430.42  5454.0  438.92
  5514.0  440.62  5554.0  440.87  5594.0  442.96  5614.0  442.19  5634.3  438.91
#Mann=7,-1,0
  4550.7    0.16       0  4902.6    0.12       0  5000.4    0.07       0
  5004.4    0.12       0  5100.8    0.16       0  5180.6    0.12       0
  5260.4    0.16       0
Bank Sta=5000.4,5004.4
Exp/Cntr=0.3,0.1

Type RM Length L Ch R = 1,1267,516,516,516
BEGIN DESCRIPTION:
OLIVER BRANCH TRIB 2 5 0
END DESCRIPTION:
XS GIS Cut Line= 4
      3491964.30     10413199.49      3492220.38     10413416.50
      3492504.67     10413485.94      3492903.94     10413362.25
#Sta/Elev= 30
  4493.9  439.79  4692.4  428.78  4759.1  427.19  4813.2  426.94  4862.2  425.33
  4911.5  422.04  4924.0  419.58  4934.3  419.65  4958.3  415.55  4985.8  415.97
  4994.8  413.30  4998.0  413.15  4998.2  412.65  5002.0  413.15  5006.3  414.88
  5026.9  418.95  5036.5  418.73  5041.6  417.42  5068.1  420.71  5126.7  420.87
  5182.3  422.34  5192.8  423.93  5220.1  425.87  5323.1  431.33  5328.9  432.42
  5349.8  433.30  5355.7  434.46  5412.7  437.90  5444.1  440.83  5540.2  443.74
#Mann=5,-1,0
  4493.9    0.16       0  4759.1    0.12       0  4998.0    0.07       0
  5002.0    0.12       0  5126.7    0.16       0
Bank Sta=4998,5002
Exp/Cntr=0.3,0.1

Type RM Length L Ch R = 1,751,622,622,622
BEGIN DESCRIPTION:
Mapping XS 4c52134a
END DESCRIPTION:
XS GIS Cut Line= 3
      3492307.20     10413811.46      3492621.85     10413676.91
      3492851.91     10413440.34
#Sta/Elev= 30
  4866.3  429.96  4893.4  430.07  4901.4  429.28  4906.8  429.41  4930.4  428.10
  4969.5  424.90  4977.6  423.14  4983.1  420.42  4991.3  415.29  4999.2  413.28
  4999.5  412.78  5003.0  412.78  5003.2  413.28  5013.0  414.81  5053.8  414.04
  5059.3  414.85  5067.4  415.02  5082.9  416.92  5089.1  418.24  5111.9  419.90
  5153.6  420.84  5159.1  420.56  5197.9  422.86  5240.8  424.14  5311.5  428.07
  5380.2  433.34  5481.0  439.54  5488.2  439.39  5509.3  440.70  5538.5  441.24
#Mann=4,-1,0
  4866.3    0.12       0  4999.2    0.07       0  5003.2    0.12       0
  5380.2    0.16       0
Bank Sta=4999.2,5003.2
Exp/Cntr=0.3,0.1

Type RM Length L Ch R = 1,129,0,0,0
BEGIN DESCRIPTION:
OLIVER BRANCH TRIB 2 1 0
END DESCRIPTION:
XS GIS Cut Line= 4
      3492326.71     10413937.32      3492417.86     10414067.54
      3492747.72     10414108.77      3493008.69     10413959.96
#Sta/Elev= 30
  4623.7  421.15  4695.1  420.56  4760.5  421.56  4847.4  420.86  4867.6  418.76
  4887.7  414.70  4897.8  414.77  4917.9  416.67  4939.9  414.28  4958.3  414.53
  4996.6  411.52  4996.8  411.02  5000.6  411.52  5008.6  412.51  5021.0  412.29
  5028.8  412.51  5038.9  414.46  5059.0  422.46  5069.1  424.37  5096.1  426.52
  5101.1  425.96  5144.2  429.21  5175.9  430.50  5219.1  434.07  5256.6  434.75
  5321.4  438.37  5337.3  437.21  5364.6  437.47  5380.5  439.41  5415.5  440.02
#Mann=4,-1,0
  4623.7    0.12       0  4996.6    0.07       0  5000.6    0.12       0
  5021.0    0.16       0
Bank Sta=4996.6,5000.6
Exp/Cntr=0.3,0.1

Chan Stop Cuts=-1