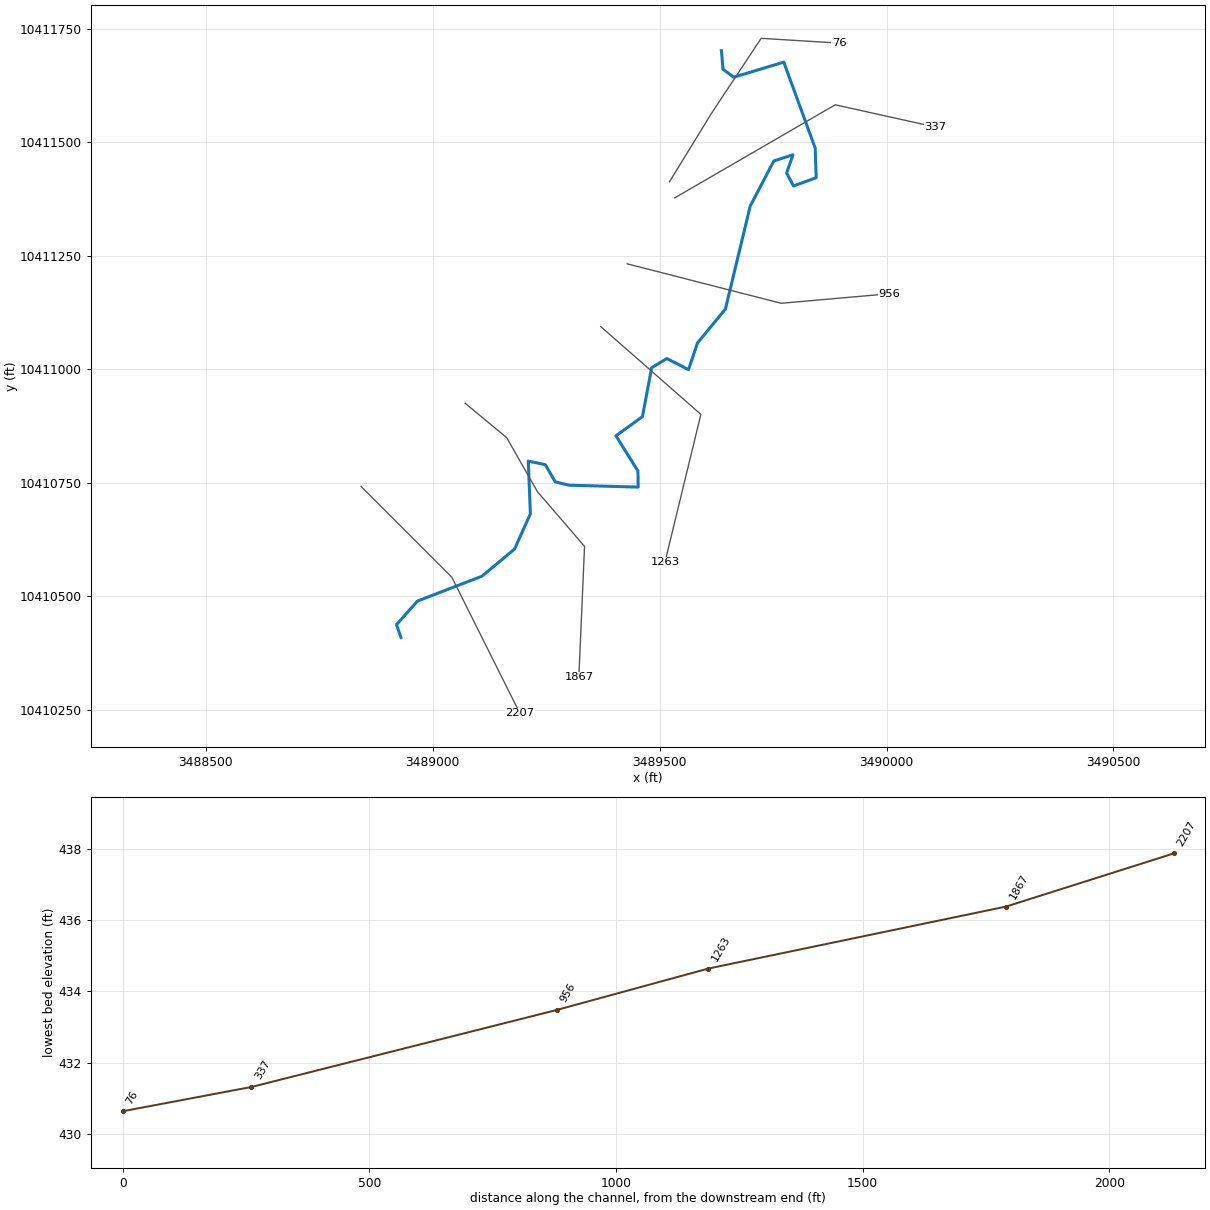
--- OLIVER BRANCH TRIB 4.prj (project) ---

Proj Title=OLIVER BRANCH TRIB 4 Base Level Engineering
Current Plan=p01
Default Exp/Contr=0.3,0.1
English Units
Geom File=g01
Flow File=f01
Plan File=p01
Y Axis Title=Elevation
X Axis Title(PF)=Main Channel Distance
X Axis Title(XS)=Station
BEGIN DESCRIPTION:
OLIVER BRANCH TRIB 4
END DESCRIPTION:
DSS Export Rating Curves= 0
DSS Export Rating Curve Sorted= 0
DSS Export Volume Flow Curves= 0
DXF OffsetX= 0
DXF OffsetY= 0
DXF ScaleX= 1
DXF ScaleY= 10

--- OLIVER BRANCH TRIB 4.p01 (plan) ---

Plan Title=Multiple Run
Short Identifier=Multiple
Geom File=g01
Flow File=f01
Subcritical Flow
K Sum by GR= 0
Std Step Tol= 0.01
Critical Tol= 0.01
Num of Std Step Trials= 20
Max Error Tol= 0.3
Flow Tol Ratio= 0.001
Split Flow NTrial= 30
Split Flow Tol= 0.02
Split Flow Ratio= 0.02
Log Output Level= 0
Friction Slope Method= 1
Unsteady Friction Slope Method= 2
Unsteady Bridges Friction Slope Method= 1
Parabolic Critical Depth
Global Vel Dist=  1 , 1 , 1
Global Log Level= 0
CheckData=True
Encroach Param= -1, 0, 0, 0
BEGIN DESCRIPTION:
Multiple Run
END DESCRIPTION:

--- OLIVER BRANCH TRIB 4.f01 (steady flow) ---

Flow Title=Multiple
Number of Profiles=7
Profile Names=10-year,25-year,50-year,1pct_min,100-year,1pct_plu,500-year
River Rch & RM= OLIVER BRANCH TR,Reach-1,2207
     493     653     781     682     923    1248    1285
Boundary for River Rch & Prof#=OLIVER BRANCH TR,Reach-1,1
Up Type=0
Dn Type=3
Dn Slope=0.005
Boundary for River Rch & Prof#=OLIVER BRANCH TR,Reach-1,2
Up Type=0
Dn Type=3
Dn Slope=0.005
Boundary for River Rch & Prof#=OLIVER BRANCH TR,Reach-1,3
Up Type=0
Dn Type=3
Dn Slope=0.005
Boundary for River Rch & Prof#=OLIVER BRANCH TR,Reach-1,4
Up Type=0
Dn Type=3
Dn Slope=0.005
Boundary for River Rch & Prof#=OLIVER BRANCH TR,Reach-1,5
Up Type=0
Dn Type=3
Dn Slope=0.005
Boundary for River Rch & Prof#=OLIVER BRANCH TR,Reach-1,6
Up Type=0
Dn Type=3
Dn Slope=0.005
Boundary for River Rch & Prof#=OLIVER BRANCH TR,Reach-1,7
Up Type=0
Dn Type=3
Dn Slope=0.005

--- OLIVER BRANCH TRIB 4.g01 (geometry) ---

Geom Title=Existing Conditions
Program Version=4.10

River Reach=OLIVER BRANCH TR,Reach-1
Reach XY= 30
      3488930.08     10410408.84      3488920.16     10410437.05
      3488966.34     10410489.13       3489108.7     10410543.99
      3489180.32      10410603.8      3489215.21      10410681.4
      3489210.52     10410797.55      3489248.02     10410789.74
       3489269.9     10410751.72      3489300.63     10410744.43
      3489452.71     10410740.26      3489452.19     10410775.68
      3489403.75     10410853.28      3489462.09     10410895.47
       3489482.4     10411003.28      3489515.73     10411023.59
      3489563.65     10410999.11      3489583.44     10411057.97
       3489644.9     10411132.45      3489699.59     10411359.53
      3489751.67     10411459.01      3489793.86     10411472.55
       3489779.8     10411432.45       3489794.9      10411403.8
       3489844.9     10411422.03      3489842.82     10411487.13
      3489773.55     10411676.72      3489663.13     10411643.38
      3489639.69     10411661.09      3489636.11     10411701.99

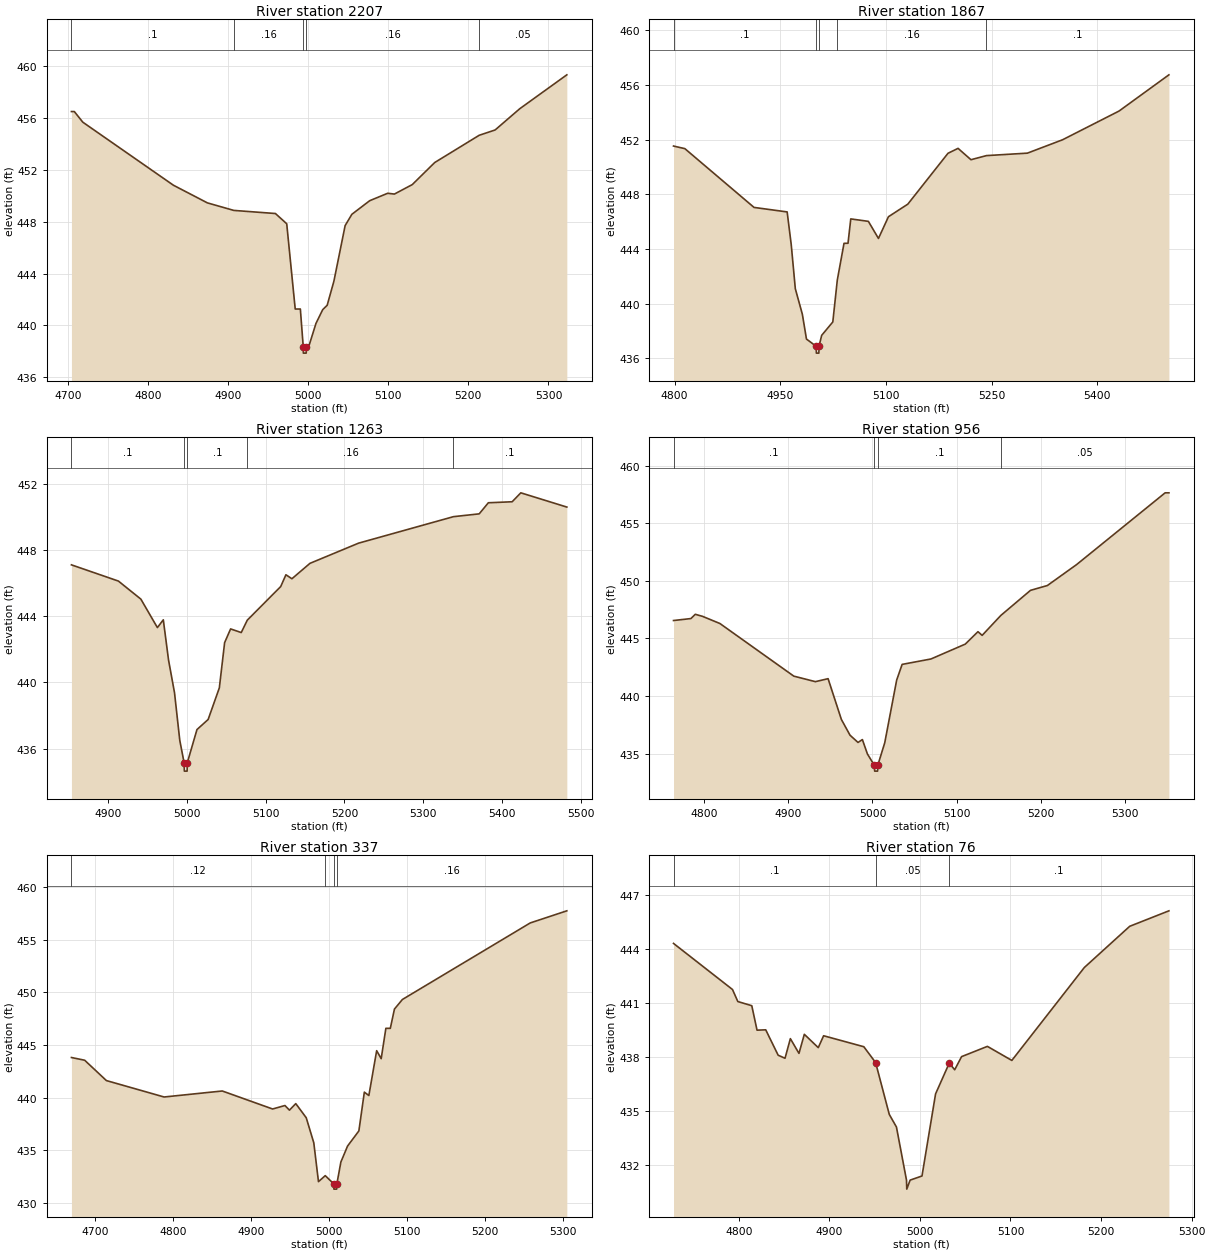
Type RM Length L Ch R = 1 ,2207    ,340,340,340
BEGIN DESCRIPTION:
OLIVER BRANCH TRIB 4 2 0
END DESCRIPTION:
XS GIS Cut Line= 3
      3488842.08     10410741.67      3489042.11     10410541.64
      3489192.11     10410241.63
#Sta/Elev= 30
  4704.6  456.49  4708.2  456.49  4718.8  455.67  4831.9  450.81  4874.3  449.45
  4907.2  448.87  4959.2  448.63  4973.3  447.84  4983.9  441.27  4990.3  441.27
  4993.9  438.37  4994.1  437.87  4997.6  437.87  4997.9  438.37  5001.5  438.52
  5009.8  440.16  5018.2  441.22  5023.8  441.56  5032.2  443.42  5046.2   447.7
  5054.6  448.57  5076.9  449.62  5099.3  450.19  5107.7  450.13    5130  450.86
    5158  452.56  5213.5  454.66  5233.4  455.07  5264.2  456.71  5322.9  459.32
#Mann= 5 ,-1 , 0
  4704.6      .1       0  4907.2     .16       0  4993.9     .07       0
  4997.9     .16       0  5213.5     .05       0
Bank Sta=4993.9,4997.9
XS Rating Curve= 0 ,0
Exp/Cntr=0.3,0.1

Type RM Length L Ch R = 1 ,1867    ,604,604,604
BEGIN DESCRIPTION:
Mapping XS f36b7980
END DESCRIPTION:
XS GIS Cut Line= 5
      3489071.92     10410924.57      3489162.93     10410849.25
      3489230.93     10410729.98      3489334.51     10410609.66
      3489321.96     10410320.92
#Sta/Elev= 30
  4798.4  451.53  4814.5  451.34  4912.7  447.04  4959.7  446.71  4965.5  444.31
  4971.3  441.09  4981.3  439.22  4987.1  437.41  5000.9  436.88  5001.2  436.38
  5004.7  436.38  5004.9  436.88  5008.7  437.68  5024.5  438.66  5030.9  441.73
  5040.4  444.41  5046.1  444.42    5050   446.2    5075  446.02  5089.3  444.77
  5103.5  446.36    5131  447.28    5188     451  5202.3  451.36  5220.6  450.53
  5242.6  450.83  5300.7  451.01  5350.7  451.99  5430.8  454.09  5501.6  456.74
#Mann= 5 ,-1 , 0
  4798.4      .1       0  5000.9     .07       0  5004.9      .1       0
  5030.9     .16       0  5242.6      .1       0
Bank Sta=5000.9,5004.9
XS Rating Curve= 0 ,0
Exp/Cntr=0.3,0.1

Type RM Length L Ch R = 1 ,1263    ,307,307,307
BEGIN DESCRIPTION:
OLIVER BRANCH TRIB 4 3 0
END DESCRIPTION:
XS GIS Cut Line= 3
       3489370.1     10411094.06      3489590.84     10410900.52
      3489511.77     10410574.85
#Sta/Elev= 30
  4853.6   447.1  4913.2  446.12  4941.7  445.03  4962.7  443.31  4970.2  443.78
  4976.8  441.36  4984.4  439.38  4991.1   436.5  4996.6  435.14  4996.9  434.64
  5000.4  434.64  5000.6  435.14  5012.9  437.15  5027.1  437.76  5041.3  439.67
    5048   442.4  5055.6  443.23  5069.1  443.01  5076.8  443.76  5119.2  445.79
  5125.8   446.5  5133.4  446.26  5156.3  447.19    5218  448.41  5338.4  450.01
  5371.1  450.18  5382.7  450.85  5412.9  450.91  5423.9  451.45  5482.3  450.59
#Mann= 5 ,-1 , 0
  4853.6      .1       0  4996.6     .07       0  5000.6      .1       0
  5076.8     .16       0  5338.4      .1       0
Bank Sta=4996.6,5000.6
XS Rating Curve= 0 ,0
Exp/Cntr=0.3,0.1

Type RM Length L Ch R = 1 ,956     ,619,619,619
BEGIN DESCRIPTION:
OLIVER BRANCH TRIB 4 4 0
END DESCRIPTION:
XS GIS Cut Line= 3
      3489428.63     10411232.19      3489767.66     10411145.34
      3490006.16     10411166.26
#Sta/Elev= 30
  4763.3  446.56    4784  446.73  4789.2   447.1  4797.9  446.92  4818.5   446.3
  4906.4  441.73  4932.1  441.25  4947.2  441.51    4963  437.97  4973.3   436.6
  4982.8  435.97    4988  436.22    4994  434.97  5002.3  433.98  5002.6  433.48
  5006.1  433.48  5006.3  433.98  5014.6  435.94  5028.8  441.39  5035.3  442.75
  5069.6  443.22  5110.4  444.51  5125.5  445.59  5130.5  445.27  5152.7     447
    5188  449.18  5208.1   449.6  5242.9  451.42  5348.2  457.65  5352.7  457.65
#Mann= 4 ,-1 , 0
  4763.3      .1       0  5002.3     .07       0  5006.3      .1       0
  5152.7     .05       0
Bank Sta=5002.3,5006.3
XS Rating Curve= 0 ,0
Exp/Cntr=0.3,0.1

Type RM Length L Ch R = 1 ,337     ,261,261,261
BEGIN DESCRIPTION:
Mapping XS 23615304
END DESCRIPTION:
XS GIS Cut Line= 3
      3489533.33     10411377.62      3489886.93     10411582.66
      3490107.91     10411533.67
#Sta/Elev= 30
  4669.9  443.82  4686.9  443.56  4714.7  441.63  4788.7  440.07  4863.3  440.64
  4927.8  438.93  4943.6  439.26  4949.4  438.82  4957.5  439.44  4970.9   438.1
  4980.6  435.72  4986.6  432.03  4995.3   432.6  5006.2  431.82  5006.4  431.32
  5009.9  431.32  5010.2  431.82  5015.3  433.89  5023.9  435.41  5038.4  436.85
  5045.4  440.53  5051.2  440.21  5061.2  444.47    5067  443.71    5073  446.59
  5078.7  446.59    5084  448.42  5094.2  449.33  5258.1   456.6    5305  457.75
#Mann= 4 ,-1 , 0
  4669.9     .12       0  4995.3     .16       0  5006.2     .07       0
  5010.2     .16       0
Bank Sta=5006.2,5010.2
XS Rating Curve= 0 ,0
Exp/Cntr=0.3,0.1

Type RM Length L Ch R = 1 ,76      ,0,0,0
BEGIN DESCRIPTION:
OLIVER BRANCH TRIB 4 1 0
END DESCRIPTION:
XS GIS Cut Line= 4
      3489521.81      10411413.2       3489614.9     10411564.88
      3489723.71     10411729.14       3489895.3     10411718.68
#Sta/Elev= 30
    4728  444.29  4793.1  441.73    4799  441.06  4814.4  440.83  4820.2  439.47
  4829.8  439.49  4843.5  438.08  4851.1  437.91    4857     439  4866.5  438.18
  4872.4  439.24  4887.8   438.5  4893.7  439.16  4938.1  438.55  4951.1  437.67
  4966.2  434.79  4974.1  434.09  4985.2  431.14  4985.5  430.64  4989.2  431.14
  5002.3  431.37  5017.3  435.93  5032.4  437.64  5038.4  437.27    5046     438
  5074.5  438.57  5101.5  437.79  5181.5  442.95  5231.6  445.24  5274.9   446.1
#Mann= 3 , 0 , 0
    4728      .1       0  4951.1     .05       0  5032.4      .1       0
Bank Sta=4951.1,5032.4
XS Rating Curve= 0 ,0
Exp/Cntr=0.3,0.1

Chan Stop Cuts=-1
Use User Specified Reach Order=0
Composite Channel Slope=5