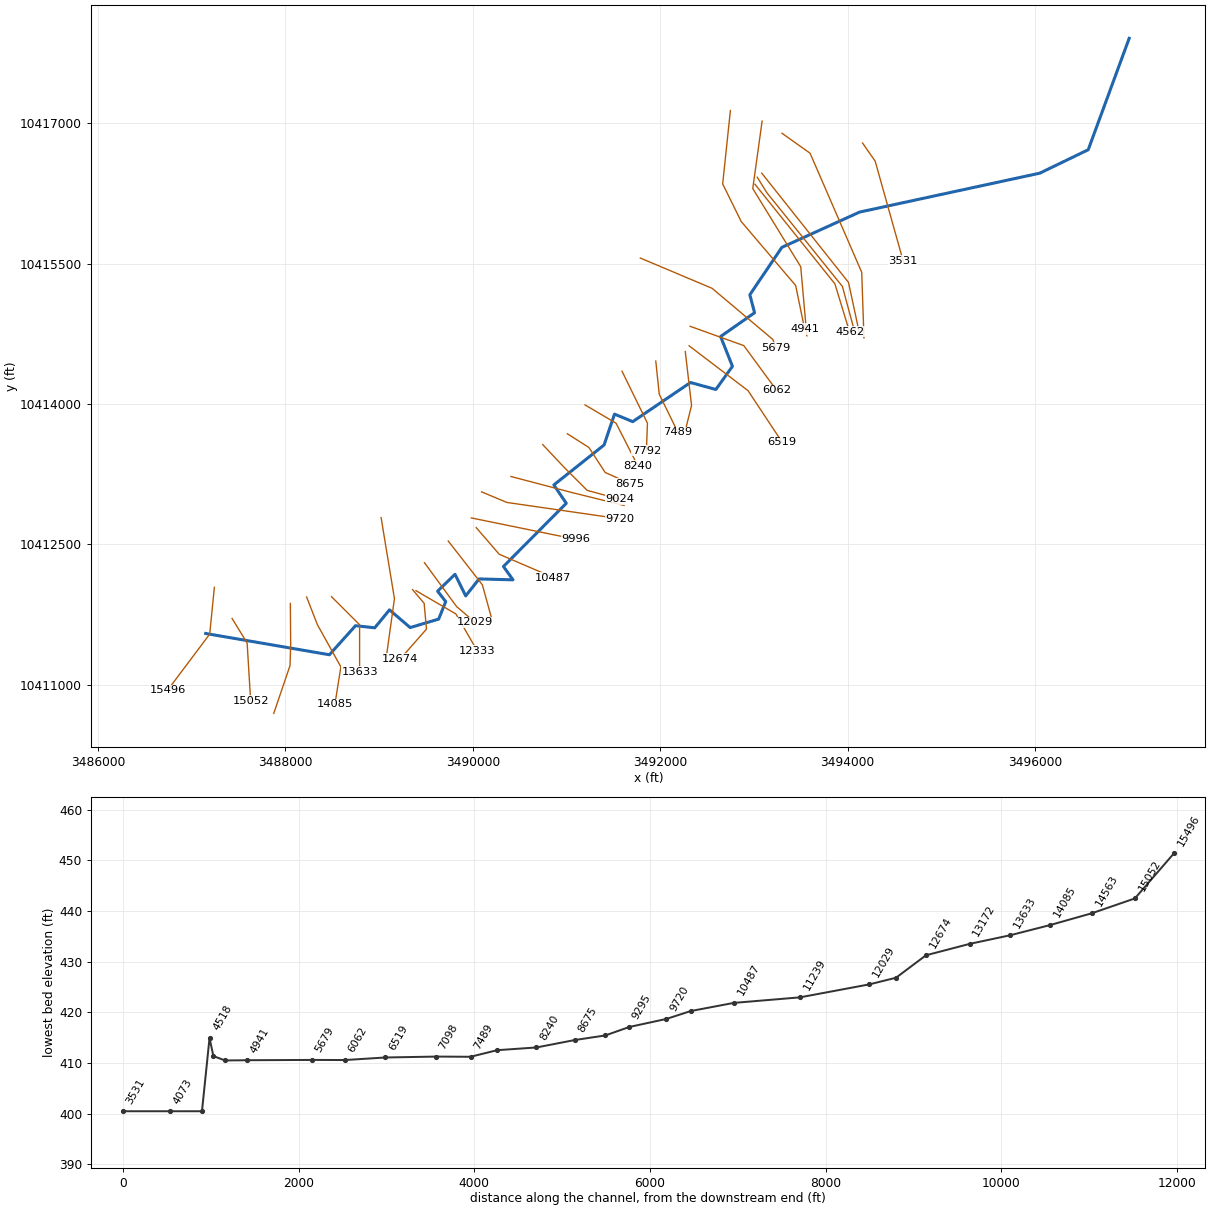
--- OLIVER BRANCH.prj (project) ---

Proj Title=OLIVER BRANCH Base Level Engineering
Current Plan=p01
Default Exp/Contr=0.3,0.1
English Units
Geom File=g01
Flow File=f01
Plan File=p01
Y Axis Title=Elevation
X Axis Title(PF)=Main Channel Distance
X Axis Title(XS)=Station
BEGIN DESCRIPTION:
OLIVER BRANCH
END DESCRIPTION:
DSS Export Rating Curves= 0
DSS Export Rating Curve Sorted= 0
DSS Export Volume Flow Curves= 0
DXF OffsetX= 0
DXF OffsetY= 0
DXF ScaleX= 1
DXF ScaleY= 10

--- OLIVER BRANCH.p01 (plan) ---

Plan Title=Multiple Run
Short Identifier=Multiple
Geom File=g01
Flow File=f01
Subcritical Flow
K Sum by GR= 0
Std Step Tol= 0.01
Critical Tol= 0.01
Num of Std Step Trials= 20
Max Error Tol= 0.3
Flow Tol Ratio= 0.001
Split Flow NTrial= 30
Split Flow Tol= 0.02
Split Flow Ratio= 0.02
Log Output Level= 0
Friction Slope Method= 1
Unsteady Friction Slope Method= 2
Unsteady Bridges Friction Slope Method= 1
Parabolic Critical Depth
Global Vel Dist=  1 , 1 , 1
Global Log Level= 0
CheckData=True
Encroach Param= -1, 0, 0, 0
BEGIN DESCRIPTION:
Multiple Run
END DESCRIPTION:

--- OLIVER BRANCH.f01 (steady flow) ---

Flow Title=Multiple
Number of Profiles=7
Profile Names=10-year,25-year,50-year,1pct_min,100-year,1pct_plu,500-year
River Rch & RM= OLIVER BRANCH,Reach-1,15496
     447     590     703     614     831    1123    1153
River Rch & RM= OLIVER BRANCH,Reach-1,12333
     935    1284    1570    1401    1894    2562    2752
River Rch & RM= OLIVER BRANCH,Reach-1,6519
    1550    2184    2716    2460    3327    4499    4983
River Rch & RM= OLIVER BRANCH,Reach-1,4518
    1605    2263    2816    2551    3450    4666    5172
River Rch & RM= OLIVER BRANCH,Reach-1,1518
    1701    2400    2988    2706    3660    4950    5486
Boundary for River Rch & Prof#=OLIVER BRANCH,Reach-1,1
Up Type=0
Dn Type=3
Dn Slope=0.005
Boundary for River Rch & Prof#=OLIVER BRANCH,Reach-1,2
Up Type=0
Dn Type=3
Dn Slope=0.005
Boundary for River Rch & Prof#=OLIVER BRANCH,Reach-1,3
Up Type=0
Dn Type=3
Dn Slope=0.005
Boundary for River Rch & Prof#=OLIVER BRANCH,Reach-1,4
Up Type=0
Dn Type=3
Dn Slope=0.005
Boundary for River Rch & Prof#=OLIVER BRANCH,Reach-1,5
Up Type=0
Dn Type=3
Dn Slope=0.005
Boundary for River Rch & Prof#=OLIVER BRANCH,Reach-1,6
Up Type=0
Dn Type=3
Dn Slope=0.005
Boundary for River Rch & Prof#=OLIVER BRANCH,Reach-1,7
Up Type=0
Dn Type=3
Dn Slope=0.005

--- OLIVER BRANCH.g01 (geometry) ---

Geom Title=Existing Conditions
Program Version=4.10

River Reach=OLIVER BRANCH   ,Reach-1
Reach XY= 30
      3487149.29     10411548.38      3488469.83     10411321.13
      3488748.48     10411631.46      3488953.77     10411608.89
      3489111.32     10411800.73      3489331.81     10411611.49
      3489636.11     10411701.99      3489711.42     10411888.78
      3489624.61     10412000.58      3489810.73     10412180.44
      3489924.61     10411949.89      3490067.67     10412131.14
      3490429.48     10412121.42      3490327.39     10412263.78
      3490998.05     10412938.95      3490865.41     10413134.78
      3491401.23     10413561.17      3491512.95     10413891.43
      3491707.23     10413810.98      3492323.61     10414228.92
       3492594.9     10414154.61      3492771.73     10414402.09
      3492645.34     10414720.13      3493007.85     10414974.01
       3492957.5     10415166.72      3493299.52     10415672.79
      3494129.23     10416049.41      3496052.86     10416465.17
      3496569.33     10416715.21      3497006.29     10417905.17

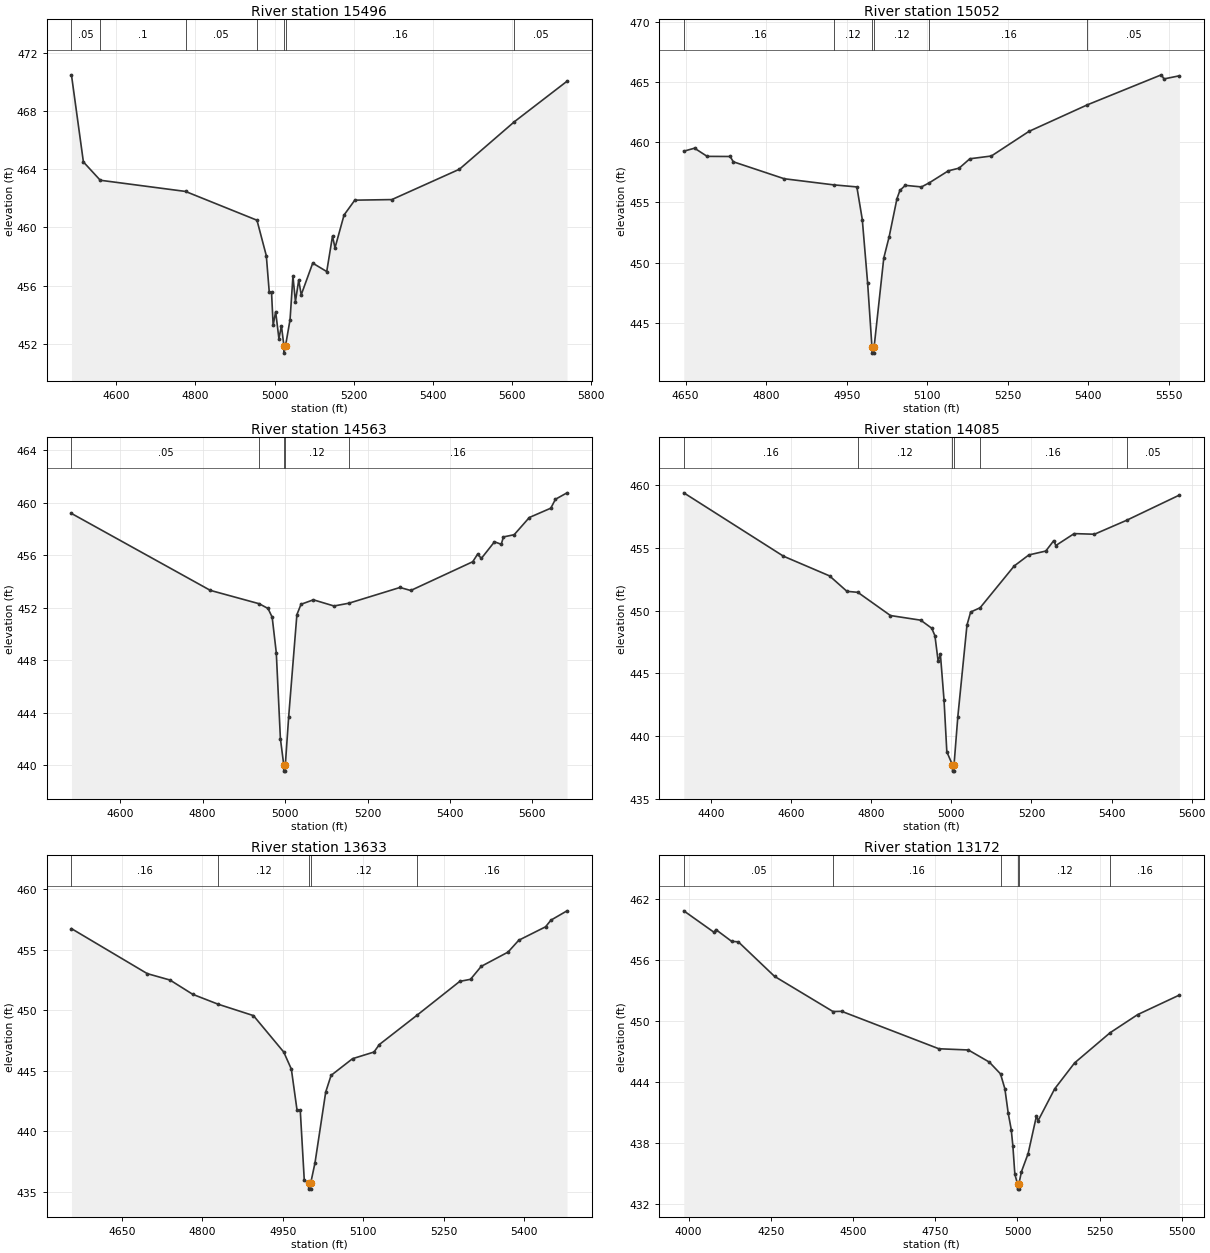
Type RM Length L Ch R = 1 ,15496   ,444,444,444
BEGIN DESCRIPTION:
OLIVER BRANCH 5 0
END DESCRIPTION:
XS GIS Cut Line= 3
      3487242.11     10412041.69      3487192.11     10411541.64
      3486742.13     10410941.68
#Sta/Elev= 30
  4486.7  470.49  4516.9   464.5  4559.5  463.24    4775  462.47  4955.6  460.49
  4979.2  458.05  4986.7  455.52  4992.4  455.52  4996.5  453.26  5002.8   454.2
  5011.1  452.34  5017.4  453.23  5023.7  451.85  5023.9  451.35  5027.7  451.85
  5039.2  453.65  5046.5  456.64  5052.8  454.89  5061.1  456.38  5067.4  455.36
  5096.5  457.54  5131.9  456.96  5146.5   459.4  5152.8  458.59  5175.7  460.85
  5202.8  461.87  5296.5  461.91  5467.4     464  5606.4  467.27  5739.2  470.05
#Mann= 7 ,-1 , 0
  4486.7     .05       0  4559.5      .1       0    4775     .05       0
  4955.6     .16       0  5023.7     .07       0  5027.7     .16       0
  5606.4     .05       0
Bank Sta=5023.7,5027.7
XS Rating Curve= 0 ,0
Exp/Cntr=0.3,0.1

Type RM Length L Ch R = 1 ,15052   ,489,489,489
BEGIN DESCRIPTION:
OLIVER BRANCH 4 0
END DESCRIPTION:
XS GIS Cut Line= 4
      3487431.11     10411708.74      3487560.52     10411497.13
      3487591.71     10411446.13      3487629.09     10410832.19
#Sta/Elev= 30
  4646.5  459.26  4666.5  459.51    4690  458.83  4732.8  458.82  4738.7  458.38
  4833.5  456.97  4925.7  456.46  4968.8  456.29  4978.9  453.58  4988.9  448.27
  4996.9  442.97  4997.1  442.47  5000.6  442.47  5000.9  442.97  5018.9  450.37
    5029  452.16  5043.5  455.32    5049     456    5059  456.42  5089.1  456.29
    5104  456.64  5139.2  457.63  5159.2  457.85  5179.2  458.63  5219.3  458.86
  5289.4  460.91  5398.3  463.12  5535.8  465.61  5540.8  465.27  5569.4  465.53
#Mann= 6 ,-1 , 0
  4646.5     .16       0  4925.7     .12       0  4996.9     .07       0
  5000.9     .12       0    5104     .16       0  5398.3     .05       0
Bank Sta=4996.9,5000.9
XS Rating Curve= 0 ,0
Exp/Cntr=0.3,0.1

Type RM Length L Ch R = 1 ,14563   ,478,478,478
BEGIN DESCRIPTION:
OLIVER BRANCH 33 0
END DESCRIPTION:
XS GIS Cut Line= 4
      3488052.96     10411868.56      3488056.44     10411424.13
      3488049.49     10411205.38      3487875.89       10410695.
#Sta/Elev= 30
  4481.6  459.18  4818.5  453.32  4937.2   452.3  4958.5  451.94  4968.6  451.28
  4978.6  448.57  4988.6  442.02  4996.6  440.05  4996.8  439.55  5000.3  439.55
  5000.6  440.05  5008.6  443.67  5028.6  451.47  5038.6  452.26  5068.6   452.6
  5118.6  452.13  5154.6  452.34  5278.7  453.54  5304.8  453.31  5455.2   455.5
  5466.9  456.07  5476.3  455.76    5508  457.02  5524.4  456.83  5529.7  457.39
  5555.8  457.56  5592.5  458.87  5644.6  459.58  5655.9  460.26    5684  460.75
#Mann= 5 ,-1 , 0
  4481.6     .05       0  4937.2     .12       0  4996.6     .07       0
  5000.6     .12       0  5154.6     .16       0
Bank Sta=4996.6,5000.6
XS Rating Curve= 0 ,0
Exp/Cntr=0.3,0.1

Type RM Length L Ch R = 1 ,14085   ,452,452,452
BEGIN DESCRIPTION:
OLIVER BRANCH 32 0
END DESCRIPTION:
XS GIS Cut Line= 4
      3488226.57     10411938.02      3488342.11     10411641.64
      3488592.11     10411191.64      3488528.67     10410792.23
#Sta/Elev= 30
  4332.1  459.39  4580.9  454.34    4696  452.77  4739.4  451.54  4766.6  451.46
  4848.1  449.61  4923.6  449.24  4951.1   448.6  4959.1     448  4967.1  445.98
  4972.8  446.51  4981.9  442.84  4988.8  438.75  5002.8  437.71  5003.1  437.21
  5006.6  437.21  5006.8  437.71  5016.3  441.56  5039.1  448.85  5048.3  449.89
  5071.9  450.23    5157  453.56  5193.6  454.44  5235.9  454.75  5255.8  455.58
  5260.9  455.19  5306.7  456.14  5357.4  456.09  5437.6   457.2  5569.4  459.21
#Mann= 6 ,-1 , 0
  4332.1     .16       0  4766.6     .12       0  5002.8     .07       0
  5006.8     .12       0  5071.9     .16       0  5437.6     .05       0
Bank Sta=5002.8,5006.8
XS Rating Curve= 0 ,0
Exp/Cntr=0.3,0.1

Type RM Length L Ch R = 1 ,13633   ,461,461,461
BEGIN DESCRIPTION:
OLIVER BRANCH 30 0
END DESCRIPTION:
XS GIS Cut Line= 3
      3488492.13     10411941.62      3488792.11     10411641.64
      3488792.11     10411141.67
#Sta/Elev= 30
    4556  456.74  4697.4  453.02  4739.8  452.49  4782.2  451.31  4829.7  450.49
  4895.4  449.55  4951.9  446.54  4966.1  445.13  4976.7  441.74  4982.7  441.74
  4990.2  435.95  4998.2  435.71  4998.5  435.21    5002  435.21  5002.2  435.71
  5010.2  437.38  5030.2  443.24  5040.2  444.61  5080.2  445.99  5120.2  446.54
  5130.2  447.16  5200.1  449.57  5280.2  452.38  5300.2  452.55  5320.2  453.62
  5370.2   454.8  5390.2  455.78  5440.2  456.89  5450.2  457.44  5480.2  458.21
#Mann= 5 ,-1 , 0
    4556     .16       0  4829.7     .12       0  4998.2     .07       0
  5002.2     .12       0  5200.1     .16       0
Bank Sta=4998.2,5002.2
XS Rating Curve= 0 ,0
Exp/Cntr=0.3,0.1

Type RM Length L Ch R = 1 ,13172   ,498,498,498
BEGIN DESCRIPTION:
OLIVER BRANCH 3 0
END DESCRIPTION:
XS GIS Cut Line= 3
      3489021.71     10412785.25      3489164.07     10411920.65
      3489077.34     10411296.19
#Sta/Elev= 30
  3985.5  460.87  4077.8  458.75  4082.8  459.03    4131  457.87  4151.3  457.82
  4261.3  454.43  4439.1  450.97  4465.5  450.99  4760.9  447.31  4850.6  447.19
  4914.3     446  4948.4  444.84  4961.7  443.37  4971.8  440.98    4981  439.37
    4986  437.75    4992  434.98  5000.1  434.01  5000.3  433.51  5003.8  433.51
  5004.1  434.01  5012.2  435.24  5032.4  437.01  5057.7   440.7  5062.7  440.24
  5113.1  443.37  5173.7  445.92  5281.4  448.88  5365.5  450.67  5492.2  452.59
#Mann= 6 ,-1 , 0
  3985.5     .05       0  4439.1     .16       0  4948.4     .12       0
  5000.1     .07       0  5004.1     .12       0  5281.4     .16       0
Bank Sta=5000.1,5004.1
XS Rating Curve= 0 ,0
Exp/Cntr=0.3,0.1

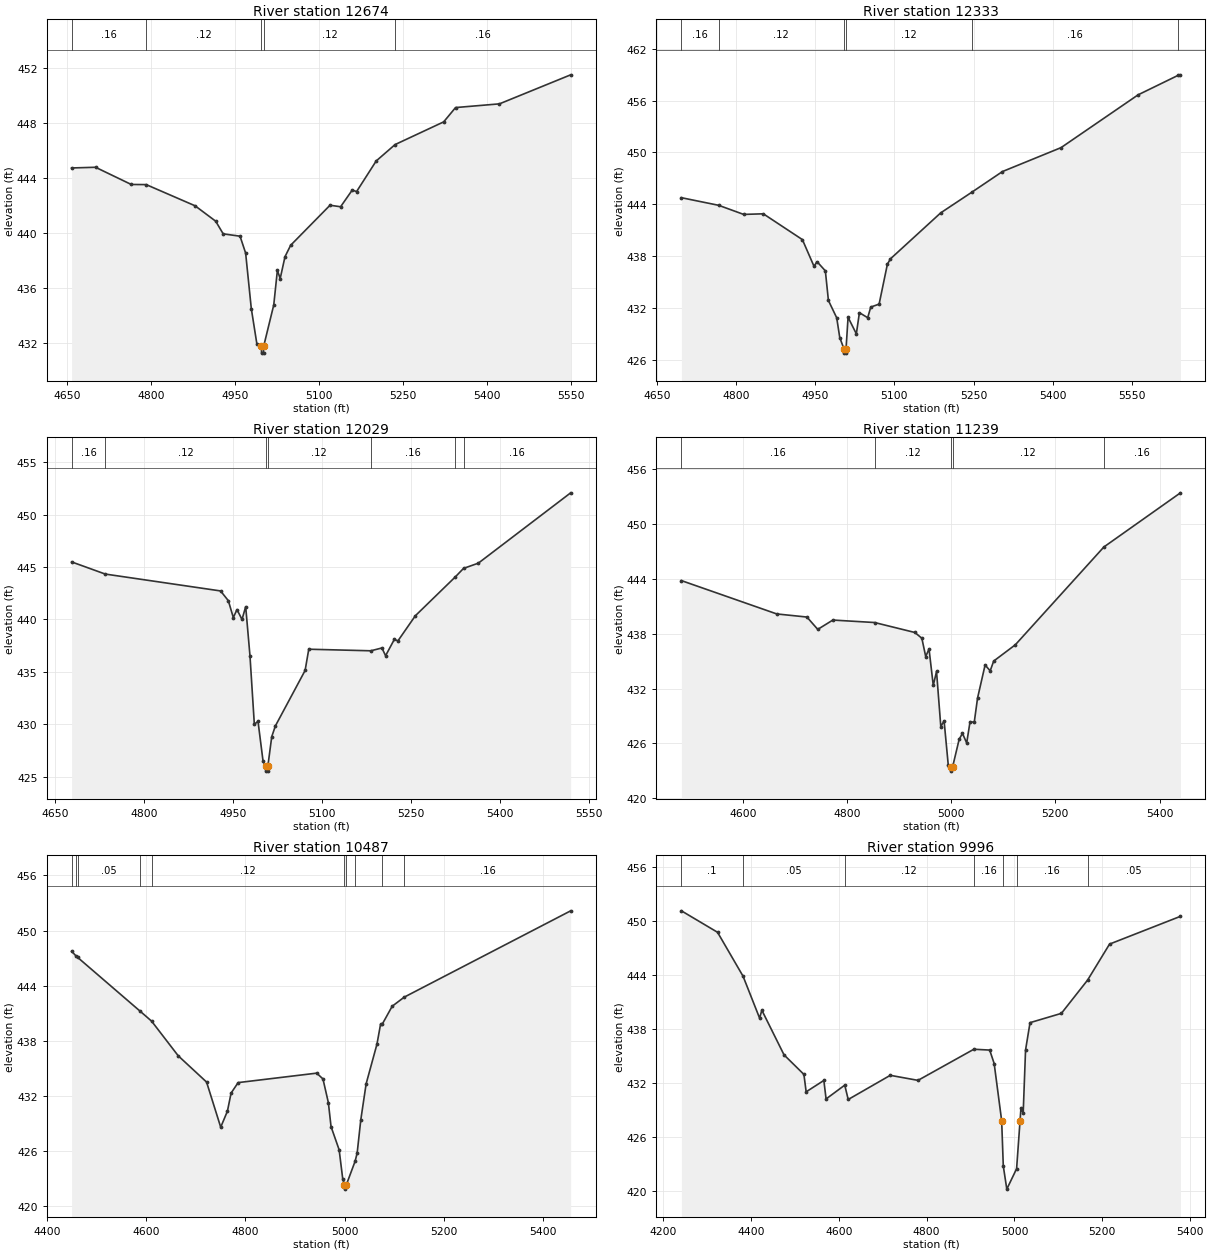
Type RM Length L Ch R = 1 ,12674   ,341,341,341
BEGIN DESCRIPTION:
OLIVER BRANCH 28 0
END DESCRIPTION:
XS GIS Cut Line= 4
       3489357.5     10412016.89      3489480.99     10411870.38
       3489506.1     10411595.22      3489226.63     10411277.17
#Sta/Elev= 30
  4658.4  444.72  4701.1  444.77  4764.9  443.52  4791.6  443.51  4878.9  441.97
  4915.7  440.85  4929.1  439.93  4959.2  439.76  4969.2  438.53  4979.3   434.5
  4989.3  431.92  4997.4  431.76  4997.6  431.26  5001.1  431.26  5001.4  431.76
  5019.4  434.76  5025.9  437.28  5030.9  436.68  5039.5  438.27  5049.6   439.1
  5119.9  442.01  5138.8   441.9  5159.7  443.12  5167.3     443  5202.4  445.23
  5236.1  446.42  5322.9  448.07  5344.1  449.11  5422.5  449.38  5549.7  451.49
#Mann= 5 ,-1 , 0
  4658.4     .16       0  4791.6     .12       0  4997.4     .07       0
  5001.4     .12       0  5236.1     .16       0
Bank Sta=4997.4,5001.4
XS Rating Curve= 0 ,0
Exp/Cntr=0.3,0.1

Type RM Length L Ch R = 1 ,12333   ,304,304,304
BEGIN DESCRIPTION:
OLIVER BRANCH 29 0
END DESCRIPTION:
XS GIS Cut Line= 3
      3489394.16     10412005.34      3489819.97     10411757.39
      3490046.53     10411365.86
#Sta/Elev= 30
  4696.6  444.78  4767.2   443.9  4814.5  442.85  4851.7  442.92  4925.7  439.94
  4947.7  436.86  4953.5  437.39  4969.2  436.33    4975  432.91  4990.7  430.91
  4996.5  428.62  5004.4  427.33  5004.7  426.83  5008.2  426.83  5008.4  427.33
  5012.2  430.97  5027.9  429.06  5033.7   431.5  5049.4  430.92  5055.2  432.15
    5071  432.49  5086.7   437.1  5092.5  437.72  5187.7  443.03    5246  445.39
  5304.6   447.8  5415.5  450.56  5561.5  456.66  5637.9  458.93  5641.7  458.97
#Mann= 6 ,-1 , 0
  4696.6     .16       0  4767.2     .12       0  5004.4     .07       0
  5008.4     .12       0    5246     .16       0  5637.9     .05       0
Bank Sta=5004.4,5008.4
XS Rating Curve= 0 ,0
Exp/Cntr=0.3,0.1

Type RM Length L Ch R = 1 ,12029   ,790,790,790
BEGIN DESCRIPTION:
OLIVER BRANCH 27 1
END DESCRIPTION:
XS GIS Cut Line= 3
       3489484.1      10412304.6      3489827.29     10411835.85
      3490026.25     10411665.91
#Sta/Elev= 30
  4677.3  445.48  4734.1  444.32  4928.8  442.71  4941.9  441.78  4950.3  440.17
  4956.5  440.93    4965  439.99  4971.2  441.21  4978.4  436.55  4985.8  429.99
    4992  430.27  5000.5  426.48  5004.7  426.02    5005  425.52  5008.5  425.52
  5008.7  426.02  5015.2  428.81  5021.4  429.84  5071.5  435.12  5077.7  437.15
  5182.5     437  5201.2  437.27  5207.4  436.53  5222.1  438.08  5228.3  437.95
  5257.6  440.34  5324.8  444.03    5339  444.86    5364  445.36  5519.9  452.07
#Mann= 7 ,-1 , 0
  4677.3     .16       0  4734.1     .12       0  5004.7     .07       0
  5008.7     .12       0  5182.5     .16       0  5324.8     .12       0
    5339     .16       0
Bank Sta=5004.7,5008.7
XS Rating Curve= 0 ,0
Exp/Cntr=0.3,0.1

Type RM Length L Ch R = 1 ,11239   ,752,752,752
BEGIN DESCRIPTION:
OLIVER BRANCH 27 0
END DESCRIPTION:
XS GIS Cut Line= 3
      3489738.37     10412535.78      3490102.45     10412068.12
      3490199.61     10411716.06
#Sta/Elev= 30
  4482.3  443.82  4665.3  440.17  4723.2  439.83    4744  438.48    4773   439.5
  4853.1  439.23  4930.4  438.14  4943.8  437.51  4951.2  435.51  4957.6  436.33
  4965.7  432.34    4972  433.87  4980.2  427.83  4986.5  428.47  4994.5  423.62
    4999  423.46  4999.2  422.96    5003  423.46  5015.5  426.46  5021.8  427.09
  5029.9  426.04  5036.3  428.37  5044.4  428.31  5050.7  430.95  5065.2  434.58
    5075  433.94  5081.7  435.01  5123.2  436.79  5293.2   447.5  5440.2  453.43
#Mann= 5 ,-1 , 0
  4482.3     .16       0  4853.1     .12       0    4999     .07       0
    5003     .12       0  5293.2     .16       0
Bank Sta=4999,5003
XS Rating Curve= 0 ,0
Exp/Cntr=0.3,0.1

Type RM Length L Ch R = 1 ,10487   ,491,491,491
BEGIN DESCRIPTION:
OLIVER BRANCH 25 0
END DESCRIPTION:
XS GIS Cut Line= 3
      3490036.53     10412679.14      3490282.41     10412394.55
       3490860.7     10412146.11
#Sta/Elev= 30
    4450  447.75  4459.6   447.2  4462.2  447.08  4587.6  441.25  4611.1  440.15
  4664.9  436.37  4721.9  433.52  4750.4  428.61  4763.9  430.35  4771.3  432.32
  4785.5  433.46  4943.8  434.49  4956.4  433.86  4967.3  431.28  4972.7  428.67
    4989  426.15  4996.3  422.96  4999.7  422.37    5000  421.87  5003.7  422.37
  5021.1  424.89  5025.3  425.79  5032.6   429.4  5043.4  433.33  5065.2  437.64
  5072.4  439.79  5076.2  439.85  5095.9  441.77  5120.2  442.76  5455.5  452.15
#Mann= 10 ,-1 , 0
    4450     .05       0  4459.6      .1       0  4462.2     .05       0
  4587.6     .16       0  4611.1     .12       0  4999.7     .07       0
  5003.7     .12       0  5021.1     .16       0  5076.2     .12       0
  5120.2     .16       0
Bank Sta=4999.7,5003.7
XS Rating Curve= 0 ,0
Exp/Cntr=0.3,0.1

Type RM Length L Ch R = 1 ,9996    ,276,276,276
BEGIN DESCRIPTION:
OLIVER BRANCH 22 0
END DESCRIPTION:
XS GIS Cut Line= 2
      3489984.25      10412782.7      3491097.76     10412554.77
#Sta/Elev= 30
  4241.4  451.12  4323.7  448.74  4381.8  443.87  4419.5  439.22  4424.6   440.1
  4475.1  435.15  4520.4  432.98  4525.5  431.05  4565.8  432.31  4570.9  430.26
  4613.4  431.79  4621.3   430.2  4717.1  432.88  4780.2  432.32  4907.4  435.77
  4943.5  435.68  4953.7  434.19  4970.8  427.84  4974.5  422.82  4982.5  420.26
  5004.8  422.52 5012.55  427.76  5014.7  429.22  5019.8  428.68  5025.2  435.69
  5035.4  438.72  5106.8  439.75  5166.5  443.44  5216.5  447.43    5378  450.51
#Mann= 7 ,-1 , 0
  4241.4      .1       0  4381.8     .05       0  4613.4     .12       0
  4907.4     .16       0  4974.5     .07       0  5004.8     .16       0
  5166.5     .05       0
Bank Sta=4970.8,5012.55
XS Rating Curve= 0 ,0
Exp/Cntr=0.3,0.1

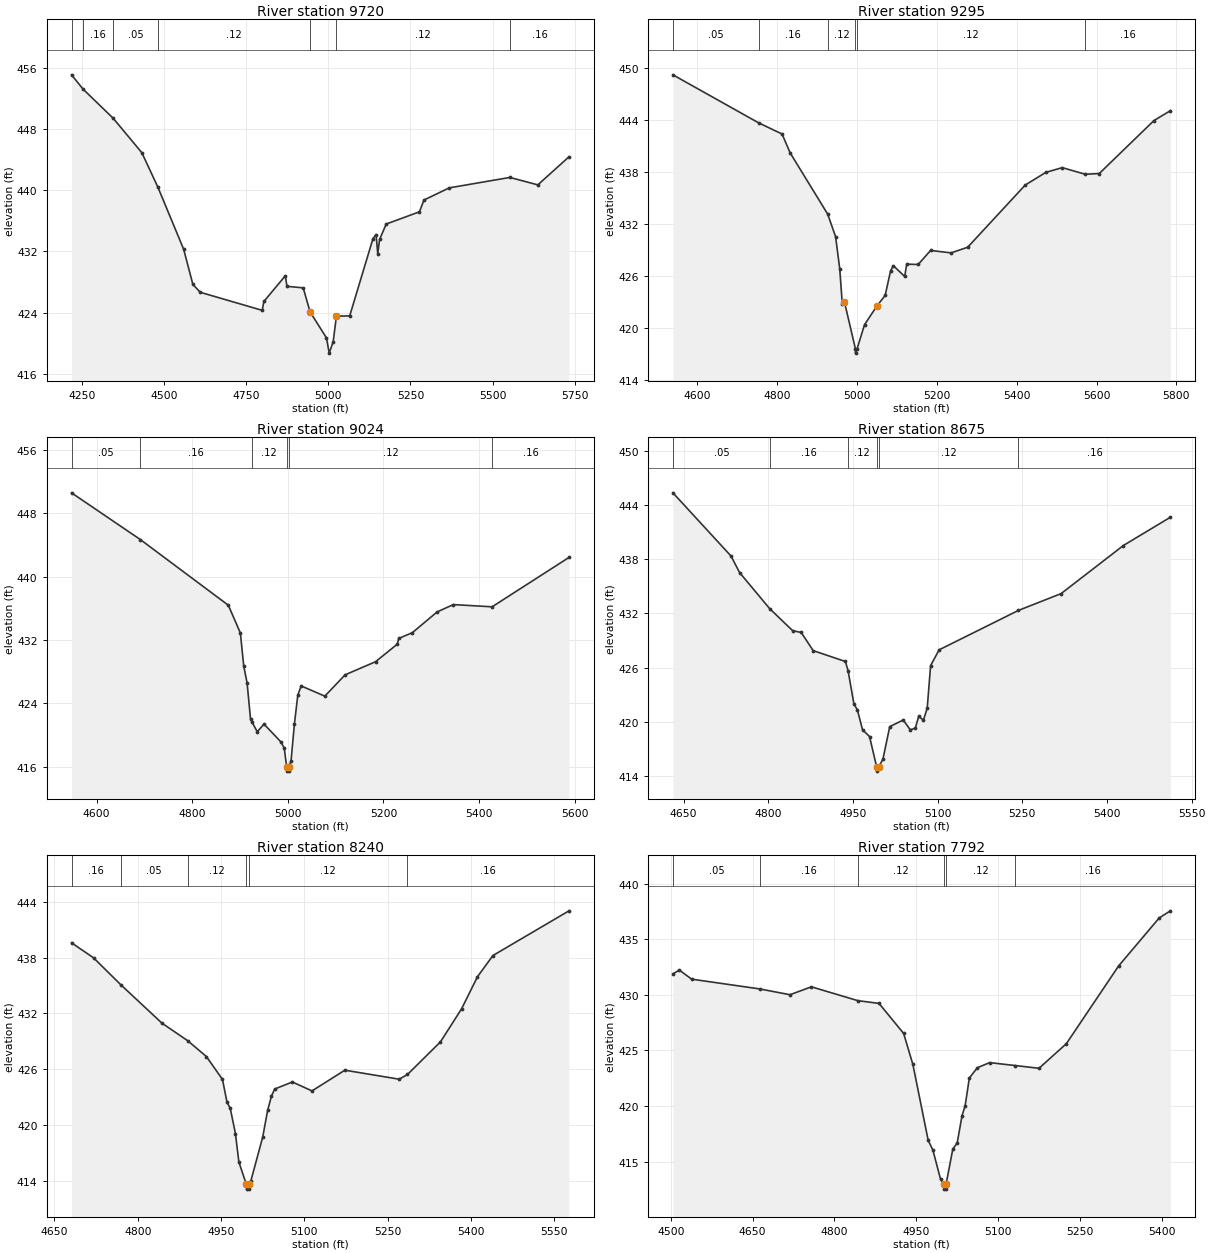
Type RM Length L Ch R = 1 ,9720    ,425,425,425
BEGIN DESCRIPTION:
OLIVER BRANCH 22 2
END DESCRIPTION:
XS GIS Cut Line= 3
       3490094.1     10413060.99      3490364.01     10412948.01
      3491572.44     10412773.28
#Sta/Elev= 30
  4218.8  455.08  4254.1   453.2  4345.4  449.41  4432.6  444.91    4481  440.45
    4560  432.28    4588  427.69  4610.5  426.66    4799   424.3    4804  425.46
  4869.3  428.82  4874.3  427.44  4923.7  427.24  4944.6   424.1  4994.5   420.7
  5002.8  418.71  5014.9   420.2  5024.8  423.54  5065.2  423.58  5135.9  433.67
  5145.4  434.21  5150.5   431.7  5156.1  433.56  5176.3  435.58  5277.4  437.18
  5291.1  438.72  5368.3  440.31  5552.5  441.67  5637.6   440.7  5732.4  444.37
#Mann= 7 ,-1 , 0
  4218.8      .1       0  4254.1     .16       0  4345.4     .05       0
    4481     .12       0  4944.6     .07       0  5024.8     .12       0
  5552.5     .16       0
Bank Sta=4944.6,5024.8
XS Rating Curve= 0 ,0
Exp/Cntr=0.3,0.1

Type RM Length L Ch R = 1 ,9295    ,271,271,271
BEGIN DESCRIPTION:
OLIVER BRANCH 23 0
END DESCRIPTION:
XS GIS Cut Line= 3
      3490408.14     10413224.95       3491067.9     10413051.32
      3491615.05     10412916.27
#Sta/Elev= 30
  4539.2  449.23  4754.1  443.68  4812.5   442.4  4832.8  440.22  4926.7  433.16
  4946.6  430.55  4956.9  426.86  4963.4  422.78  4968.6  423.05  4996.2  417.61
  4996.5  417.11  5000.4  417.61    5019  420.39    5050  422.55  5070.7  423.77
  5084.4  426.63  5091.3   427.2  5119.6  425.96  5124.7  427.38  5153.4  427.34
  5184.4  428.96  5235.9  428.68  5277.3  429.33  5421.5  436.51    5473  437.97
  5514.2  438.52    5572  437.75  5606.9  437.84  5743.8  443.95    5785  445.09
#Mann= 6 ,-1 , 0
  4539.2     .05       0  4754.1     .16       0  4926.7     .12       0
  4996.2     .07       0  5000.4     .12       0    5572     .16       0
Bank Sta=4968.6,5050
XS Rating Curve= 0 ,0
Exp/Cntr=0.3,0.1

Type RM Length L Ch R = 1 ,9024    ,349,349,349
BEGIN DESCRIPTION:
OLIVER BRANCH 21 1
END DESCRIPTION:
XS GIS Cut Line= 4
      3490746.88     10413565.78      3490971.57     10413326.67
      3491221.57     10413076.67      3491568.43      10412982.8
#Sta/Elev= 30
  4547.4  450.56  4691.5  444.66  4875.5  436.38  4900.7  432.88  4907.7  428.73
  4914.8  426.56  4921.9  422.05  4924.8  421.67    4936  420.42  4950.2  421.38
  4985.5  419.14  4992.6  418.35  4997.6  415.95  4997.8  415.45  5001.5  415.45
  5001.8  415.95  5006.7  416.72  5013.8   421.4  5020.9  425.04  5027.9   426.2
  5077.4  424.91  5119.9   427.6  5183.5  429.25  5229.1  431.47    5232  432.19
  5260.7  432.92  5312.5  435.54  5346.4  436.46  5427.5  436.18  5588.4  442.41
#Mann= 6 ,-1 , 0
  4547.4     .05       0  4691.5     .16       0  4924.8     .12       0
  4997.6     .07       0  5001.8     .12       0  5427.5     .16       0
Bank Sta=4997.6,5001.8
XS Rating Curve= 0 ,0
Exp/Cntr=0.3,0.1

Type RM Length L Ch R = 1 ,8675    ,435,435,435
BEGIN DESCRIPTION:
OLIVER BRANCH 20 0
END DESCRIPTION:
XS GIS Cut Line= 4
      3491009.57      10413681.4      3491239.71     10413534.95
      3491413.39     10413268.16      3491678.12     10413149.34
#Sta/Elev= 30
    4631  445.33  4733.9  438.34  4749.1  436.51  4802.5  432.51  4843.1  430.08
  4858.3  429.88  4879.5  427.87  4936.6  426.67  4941.4  425.62  4951.7  421.95
  4957.7  421.34  4966.9  419.12  4979.3  418.37  4991.8  415.04  4992.1  414.54
    4996  415.04  5003.1  415.88  5015.1  419.46    5039   420.2  5051.3  419.12
  5060.4  419.28  5066.4   420.6  5074.8  420.18  5081.5   421.5  5087.5  426.21
  5102.6  427.96  5243.1  432.32  5318.7  434.18    5429   439.5  5512.3  442.63
#Mann= 6 ,-1 , 0
    4631     .05       0  4802.5     .16       0  4941.4     .12       0
  4991.8     .07       0    4996     .12       0  5243.1     .16       0
Bank Sta=4991.8,4996
XS Rating Curve= 0 ,0
Exp/Cntr=0.3,0.1

Type RM Length L Ch R = 1 ,8240    ,448,448,448
BEGIN DESCRIPTION:
OLIVER BRANCH 2 0
END DESCRIPTION:
XS GIS Cut Line= 3
      3491197.89     10413990.05      3491529.52     10413794.41
      3491761.79     10413339.29
#Sta/Elev= 30
  4680.8  439.59  4720.5  437.97  4769.1   435.1  4843.7  430.94  4890.1  429.05
  4923.7  427.35  4952.7  424.88  4960.8  422.43  4966.6  421.79    4976  419.06
  4982.2     416  4995.7  413.58    4996  413.08  4999.7  413.08    5000  413.58
  5003.7  413.95  5025.1  418.67    5034  421.56  5040.8  423.07  5046.6  423.85
  5078.5  424.61  5113.9  423.65  5173.1  425.88    5271  424.91  5285.9  425.42
  5345.3  428.93  5383.3  432.48  5411.9  435.93  5439.8  438.22  5576.8  443.03
#Mann= 6 ,-1 , 0
  4680.8     .16       0  4769.1     .05       0  4890.1     .12       0
  4995.7     .07       0    5000     .12       0  5285.9     .16       0
Bank Sta=4995.7,5000
XS Rating Curve= 0 ,0
Exp/Cntr=0.3,0.1

Type RM Length L Ch R = 1 ,7792    ,303,303,303
BEGIN DESCRIPTION:
OLIVER BRANCH 19 0
END DESCRIPTION:
XS GIS Cut Line= 3
      3491593.21     10414349.66      3491864.47      10413794.1
      3491853.62     10413501.15
#Sta/Elev= 30
    4504  431.88  4515.7  432.23  4538.2  431.41  4663.2  430.53  4718.4  430.01
  4757.7  430.72  4842.6  429.48  4881.6  429.23  4926.7  426.53  4943.6  423.75
  4971.7  416.92  4980.3  416.05  4994.3  413.43  5000.4  413.04  5000.7  412.54
  5004.4  412.54  5004.7  413.04  5016.8  416.15  5024.8  416.68  5033.7  419.15
  5039.3  420.01  5047.1  422.53  5061.8  423.45  5084.3  423.91  5130.3  423.65
  5174.7   423.4  5224.8  425.61  5320.6   432.6  5394.9  436.91  5415.4  437.55
#Mann= 6 ,-1 , 0
    4504     .05       0  4663.2     .16       0  4842.6     .12       0
  5000.4     .07       0  5004.7     .12       0  5130.3     .16       0
Bank Sta=5000.4,5004.7
XS Rating Curve= 0 ,0
Exp/Cntr=0.3,0.1

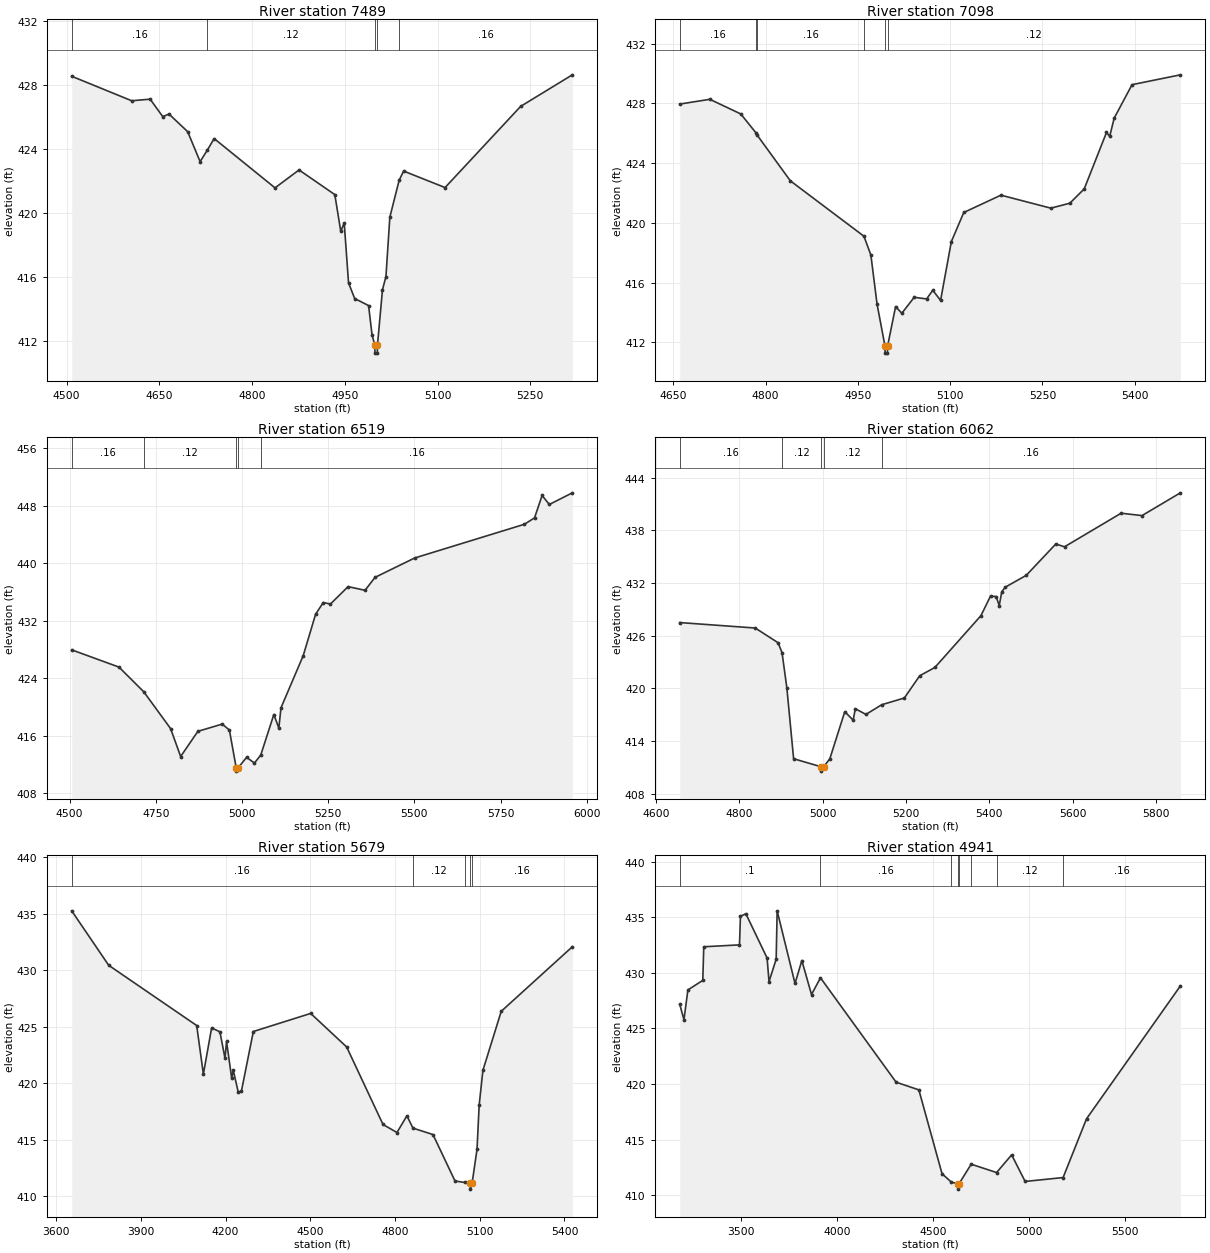
Type RM Length L Ch R = 1 ,7489    ,391,391,391
BEGIN DESCRIPTION:
OLIVER BRANCH 18 0
END DESCRIPTION:
XS GIS Cut Line= 3
      3491953.45     10414458.18      3491990.34     10414104.43
      3492189.96     10413696.52
#Sta/Elev= 30
  4508.2  428.53  4605.3     427  4635.1   427.1  4655.5  426.01  4665.6  426.17
  4695.8  425.07  4715.9   423.2  4727.5  423.91  4738.6  424.64  4837.1  421.56
  4875.9  422.68  4933.8  421.14  4943.4  418.85    4949  419.37    4956  415.63
  4965.9  414.65  4988.4  414.21    4994  412.39  4998.4  411.74  4998.7  411.24
  5002.5  411.24  5002.8  411.74  5010.9   415.2  5016.5  416.02  5022.8  419.73
  5037.9  422.04  5045.1  422.61  5112.1  421.58  5234.4  426.65    5318  428.62
#Mann= 5 ,-1 , 0
  4508.2     .16       0  4727.5     .12       0  4998.4     .07       0
  5002.8     .12       0  5037.9     .16       0
Bank Sta=4998.4,5002.8
XS Rating Curve= 0 ,0
Exp/Cntr=0.3,0.1

Type RM Length L Ch R = 1 ,7098    ,579,579,579
BEGIN DESCRIPTION:
OLIVER BRANCH 17 0
END DESCRIPTION:
XS GIS Cut Line= 3
      3492268.12      10414560.2      3492335.39     10413985.07
      3492278.97      10413757.2
#Sta/Elev= 30
  4660.5  427.96  4709.4  428.28  4759.7   427.3  4784.3  426.04  4786.2  425.89
  4840.3  422.82  4959.9  419.11  4971.2  417.85  4981.2  414.57    4994  411.78
  4994.3  411.28  4998.1  411.28  4998.5  411.78  5011.4   414.4  5021.5  413.95
  5041.6  415.02  5061.8  414.91  5071.8  415.49  5084.5  414.81    5102  418.75
  5122.2   420.7  5182.6  421.86  5263.7  420.99  5294.6  421.32    5318  422.28
  5354.2  426.06  5359.4   425.8  5366.7  427.02  5395.7  429.26  5474.3  429.92
#Mann= 6 ,-1 , 0
  4660.5     .16       0  4784.3     .05       0  4786.2     .16       0
  4959.9     .12       0    4994     .07       0  4998.5     .12       0
Bank Sta=4994,4998.5
XS Rating Curve= 0 ,0
Exp/Cntr=0.3,0.1

Type RM Length L Ch R = 1 ,6519    ,457,457,457
BEGIN DESCRIPTION:
OLIVER BRANCH 16 0
END DESCRIPTION:
XS GIS Cut Line= 3
      3492309.38      10414620.9      3492938.69     10414141.32
      3493303.28     10413590.11
#Sta/Elev= 30
  4506.1  427.96  4643.3  425.56  4715.3  422.12    4793  417.01  4822.1  413.13
    4872  416.63  4942.7  417.64  4963.5  416.81  4983.1   411.6  4983.6   411.1
  4989.5   411.6  5013.4  413.02  5036.2  412.22  5054.5  413.34  5092.4  418.97
  5106.9  417.09  5113.2  419.91  5177.6  427.15  5213.6  432.92  5235.8  434.54
  5256.6  434.33  5307.8  436.75  5356.9  436.24    5386  438.04  5500.8  440.73
  5819.3  445.42  5848.5  446.31  5870.5  449.42  5891.5  448.17  5958.2  449.79
#Mann= 5 ,-1 , 0
  4506.1     .16       0  4715.3     .12       0  4983.1     .07       0
  4989.5     .12       0  5054.5     .16       0
Bank Sta=4983.1,4989.5
XS Rating Curve= 0 ,0
Exp/Cntr=0.3,0.1

Type RM Length L Ch R = 1 ,6062    ,383,383,383
BEGIN DESCRIPTION:
OLIVER BRANCH 15 0
END DESCRIPTION:
XS GIS Cut Line= 3
      3492320.18     10414829.27      3492893.12      10414623.1
      3493243.52     10414145.07
#Sta/Elev= 30
  4656.7   427.5  4837.9  426.88  4892.6  425.21  4902.2  424.09  4913.8  420.06
    4930  412.01  4995.6   411.1  4996.1   410.6    5002   411.1  5016.8  411.99
  5052.8  417.36  5072.9   416.4  5078.2   417.7  5103.6  417.05  5141.3  418.15
  5195.8  418.92  5232.6  421.45    5269  422.39  5379.5  428.28  5402.6  430.51
  5416.2  430.46  5423.5  429.43  5429.7  431.02  5438.1  431.53  5488.3  432.87
  5559.3  436.44  5580.2  436.12    5716  439.94  5766.2  439.67  5858.3  442.26
#Mann= 5 ,-1 , 0
  4656.7     .16       0  4902.2     .12       0  4995.6     .07       0
    5002     .12       0  5141.3     .16       0
Bank Sta=4995.6,5002
XS Rating Curve= 0 ,0
Exp/Cntr=0.3,0.1

Type RM Length L Ch R = 1 ,5679    ,738,738,738
BEGIN DESCRIPTION:
OLIVER BRANCH 14 0
END DESCRIPTION:
XS GIS Cut Line= 4
      3491788.51     10415558.43      3492554.58     10415235.07
      3493203.45      10414688.2        3493236.     10414601.41
#Sta/Elev= 30
  3655.1  435.25  3786.1  430.43  4097.7   425.1  4121.4   420.8  4150.6  424.89
    4180  424.54    4198  422.19  4203.4  423.69  4221.7  420.43  4227.1  421.15
  4245.1  419.18  4256.3  419.32  4298.3  424.57  4501.4  426.17  4628.8   423.2
  4757.5  416.34  4806.9  415.63  4842.1  417.11  4863.5  416.02  4934.4  415.45
  5012.4  411.34  5046.1  411.21  5066.4  411.12  5066.9  410.62  5072.8  411.12
  5090.4  414.15    5098  418.06  5111.3  421.14  5176.2  426.36  5427.9  432.07
#Mann= 5 ,-1 , 0
  3655.1     .16       0  4863.5     .12       0  5046.1     .16       0
  5066.4     .07       0  5072.8     .16       0
Bank Sta=5066.4,5072.8
XS Rating Curve= 0 ,0
Exp/Cntr=0.3,0.1

Type RM Length L Ch R = 1 ,4941    ,246,246,246
BEGIN DESCRIPTION:
OLIVER BRANCH 13 0
END DESCRIPTION:
XS GIS Cut Line= 5
      3492749.89     10417133.94      3492667.43     10416350.53
      3492864.91     10415949.05      3493446.51     10415265.46
      3493541.99     10414801.06
#Sta/Elev= 30
  3181.4  427.16  3203.4  425.79  3223.9  428.46  3301.4  429.32  3306.5  432.34
  3492.5  432.51  3497.5  435.07  3525.6  435.31  3636.2  431.33  3646.3  429.21
  3683.5  431.22  3688.6  435.57  3781.6  429.04  3817.2   431.1  3867.5  428.05
  3914.2  429.55    4308  420.17  4426.4  419.48  4547.2  411.94  4596.4  411.18
  4629.6  411.06  4630.1  410.56  4636.2  411.06    4699   412.8  4831.2  412.05
  4909.6  413.64  4979.9  411.25  5177.5   411.6  5299.5  416.88  5788.2  428.82
#Mann= 8 ,-1 , 0
  3181.4      .1       0  3914.2     .16       0  4596.4      .1       0
  4629.6     .07       0  4636.2      .1       0    4699     .16       0
  4831.2     .12       0  5177.5     .16       0
Bank Sta=4629.6,4636.2
XS Rating Curve= 0 ,0
Exp/Cntr=0.3,0.1

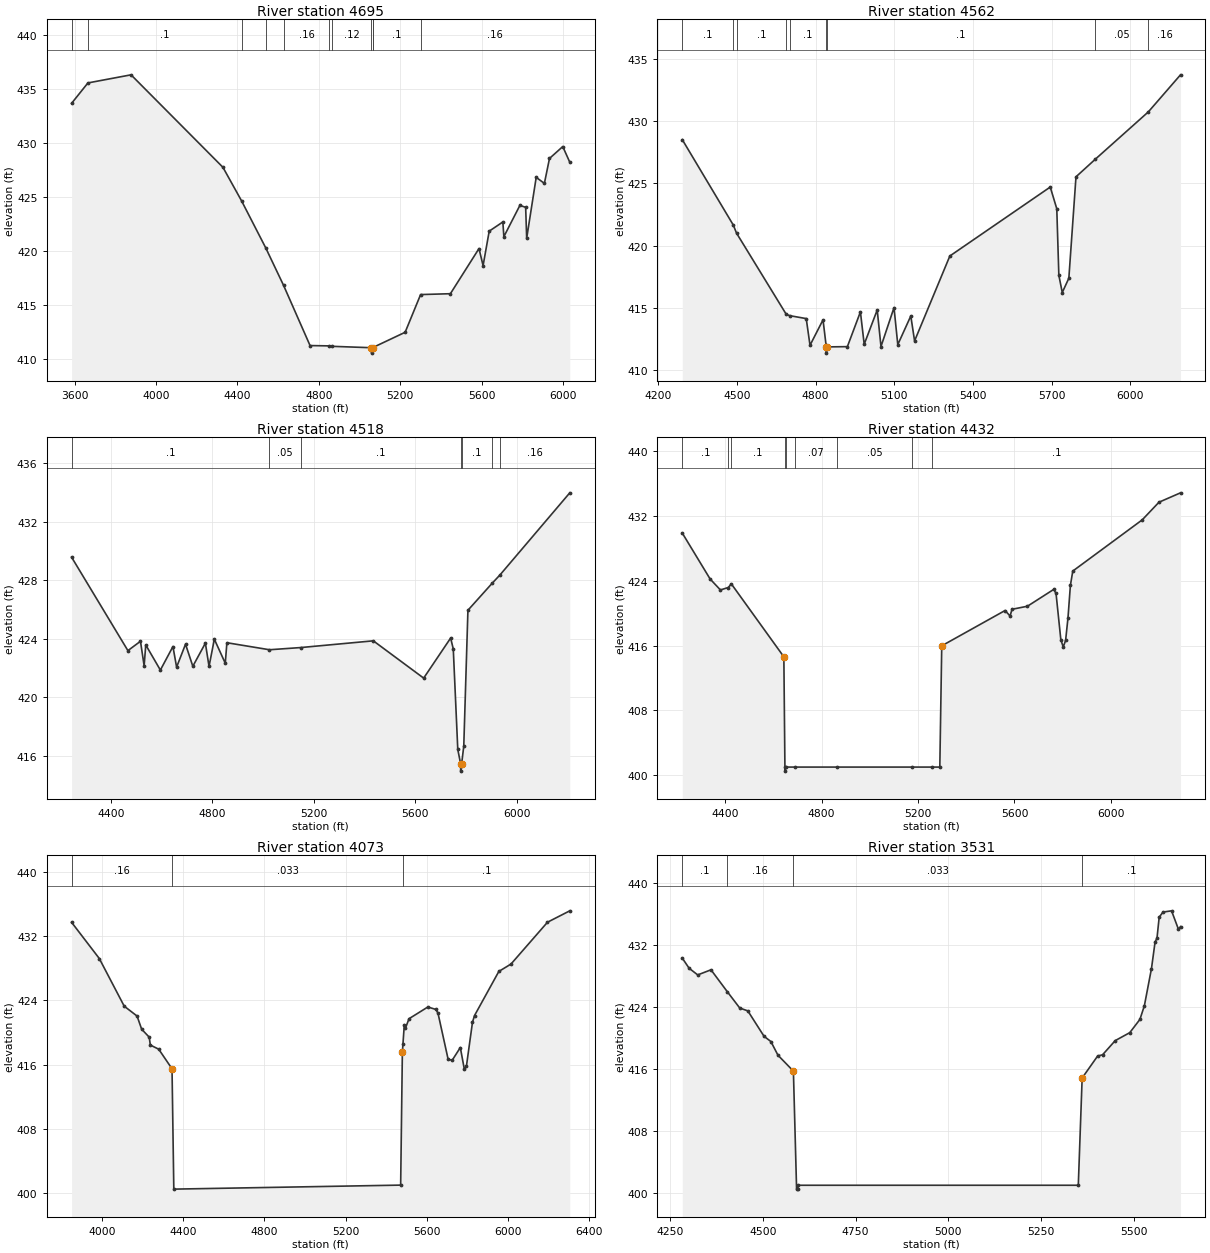
Type RM Length L Ch R = 1 ,4695    ,133,133,133
BEGIN DESCRIPTION:
OLIVER BRANCH 12 0
END DESCRIPTION:
XS GIS Cut Line= 4
      3493088.43     10417021.07      3492988.61     10416300.61
      3493500.76     10415465.11      3493565.86     10414727.29
#Sta/Elev= 30
  3584.8  433.63  3665.1  435.52    3877  436.27  4328.5  427.71  4419.9  424.61
  4538.6  420.26  4626.5  416.78  4756.6  411.21  4851.3  411.18  4864.4  411.14
  5058.1  411.01  5058.6  410.51  5065.1  411.01  5066.6  411.04  5223.8  412.44
  5299.8  415.93  5446.2  416.01  5586.7  420.19  5606.8  418.61  5636.9   421.8
  5703.9  422.65  5708.9  421.29  5787.5  424.18    5816  424.01    5821  421.14
  5867.8  426.78    5908  426.22  5933.1  428.53  5998.3  429.63  6032.8  428.18
#Mann= 11 ,-1 , 0
  3584.8     .16       0  3665.1      .1       0  4419.9     .16       0
  4538.6      .1       0  4626.5     .16       0  4851.3      .1       0
  4864.4     .12       0  5058.1     .07       0  5065.1     .12       0
  5066.6      .1       0  5299.8     .16       0
Bank Sta=5058.1,5065.1
XS Rating Curve= 0 ,0
Exp/Cntr=0.3,0.1

Type RM Length L Ch R = 1 ,4562    ,44,44,44
BEGIN DESCRIPTION:
OLIVER BRANCH 10 0
END DESCRIPTION:
XS GIS Cut Line= 3
      3493012.47     10416346.19      3493865.34     10415282.82
      3494021.59     10414770.66
#Sta/Elev= 30
    4292   428.5  4486.4  421.65  4498.8     421  4688.5  414.48  4702.7  414.38
  4764.3  414.15  4778.7  412.01  4828.3  414.05  4840.7  411.88    4841  411.38
  4844.7  411.88  4921.1   411.9  4970.8  414.69  4985.2  412.09  5034.8  414.84
  5049.2  411.91  5098.8  415.03  5113.2  412.06  5162.8  414.36  5177.2  412.36
  5311.6  419.17  5694.2   424.7  5719.1  422.96    5727  417.62    5740  416.24
  5765.1  417.39  5792.3  425.52  5865.3  426.92  6068.1  430.73  6190.6   433.7
#Mann= 9 ,-1 , 0
    4292      .1       0  4486.4     .16       0  4498.8      .1       0
  4688.5     .16       0  4702.7      .1       0  4840.7     .07       0
  4844.7      .1       0  5865.3     .05       0  6068.1     .16       0
Bank Sta=4840.7,4844.7
XS Rating Curve= 0 ,0
Exp/Cntr=0.3,0.1

Type RM Length L Ch R = 1 ,4518    ,86,86,86
BEGIN DESCRIPTION:
Mapping XS fcee53ce
END DESCRIPTION:
XS GIS Cut Line= 4
      3493036.34     10416422.16      3493138.35     10416257.21
      3493945.64     10415254.61       3494071.5     10414788.05
#Sta/Elev= 30
  4244.6  429.57  4466.7  423.18  4516.3  423.82  4530.7  422.14  4537.1  423.57
  4594.7  421.85  4644.3  423.46  4658.7  422.05  4693.9  423.62  4722.7  422.11
  4772.2  423.69  4786.6   422.1  4807.5  423.96  4850.6  422.32    4857  423.72
  5024.9  423.24  5148.4  423.39  5434.3  423.85  5632.9   421.3  5739.2  424.04
  5749.6   423.3  5767.4  416.42  5778.6  415.44  5778.9  414.94  5782.6  415.44
    5791  416.65  5807.4  425.94  5902.1  427.77    5934  428.36    6209  433.97
#Mann= 7 ,-1 , 0
  4244.6      .1       0  5024.9     .05       0  5148.4      .1       0
  5778.6     .07       0  5782.6      .1       0  5902.1     .05       0
    5934     .16       0
Bank Sta=5778.6,5782.6
XS Rating Curve= 0 ,0
Exp/Cntr=0.3,0.1

Type RM Length L Ch R = 1 ,4432    ,359,359,359
BEGIN DESCRIPTION:
OLIVER BRANCH 9 3
END DESCRIPTION:
XS GIS Cut Line= 3
      3493084.08     10416465.56      3494010.74     10415298.01
     3494131.235    10414735.376
#Sta/Elev= 30
  4221.5  429.89    4337  424.22  4379.7  422.87  4412.4  423.17    4425  423.62
    4643  414.61  4647.4     401  4647.6   400.5  4651.4     401  4689.3     401
    4862     401  5175.2     401    5259     401  5290.3     401  5298.3  415.97
  5561.1  420.33  5581.9  419.65  5589.9  420.48    5654  420.86 5762.67  422.93
 5772.61  422.45 5792.48  416.75 5802.41  415.82 5812.35  416.63 5822.28  419.44
 5832.22  423.43 5842.15   425.2 6130.26  431.52 6199.81   433.7 6289.22  434.86
#Mann= 9 ,-1 , 0
  4221.5      .1       0  4412.4     .16       0    4425      .1       0
  4647.4    .033       0  4651.4      .1       0  4689.3     .07       0
    4862     .05       0  5175.2     .07       0    5259      .1       0
Bank Sta=4643,5298.3
XS Rating Curve= 0 ,0
Exp/Cntr=0.3,0.1

Type RM Length L Ch R = 1 ,4073    ,542,542,542
BEGIN DESCRIPTION:
OLIVER BRANCH 9 2
END DESCRIPTION:
XS GIS Cut Line= 4
      3493300.88     10416890.85      3493600.36     10416678.17
      3494151.52      10415406.6     3494175.505     10414706.73
#Sta/Elev= 30
  3851.6  433.74    3988  429.23  4110.7  423.29  4173.9  422.06  4196.5  420.42
  4233.7  419.43  4239.1  418.45  4280.5  417.93  4345.9  415.49  4354.7   400.5
    5471     401  5479.4  417.55  5482.1  418.52    5489  420.99  5494.4  420.54
  5512.1  421.73  5604.8  423.19  5644.9  422.88 5654.87   422.4 5704.75  416.66
  5724.7  416.56 5764.59  418.14 5784.54  415.41 5794.52   415.8 5824.44  421.29
 5834.42  422.12 5954.11  427.62 6013.96  428.54 6193.51  433.75 6303.23  435.17
#Mann= 3 ,-1 , 0
  3851.6     .16       0  4345.9    .033       0  5482.1      .1       0
Bank Sta=4345.9,5479.4
XS Rating Curve= 0 ,0
Exp/Cntr=0.3,0.1

Type RM Length L Ch R = 1 ,3531    ,554,554,554
BEGIN DESCRIPTION:
OLIVER BRANCH 9 1
END DESCRIPTION:
XS GIS Cut Line= 3
       3494160.5      10416786.7      3494295.03     10416593.58
      3494594.41     10415526.23
#Sta/Elev= 30
  4282.4  430.35  4300.8  429.04    4324  428.18  4359.8  428.84  4403.5  426.03
  4437.4   423.9  4459.2  423.53  4502.9  420.25  4521.4  419.57  4540.5   417.8
  4582.1  415.75  4590.7   400.5  4594.2   400.5  4594.5     401  5350.6     401
    5361  414.86  5402.6  417.69  5416.1  417.86  5450.2  419.69  5489.5  420.72
  5516.8  422.43  5528.8  424.19    5548     429  5557.7  432.43  5562.9  432.94
  5568.8  435.64  5579.1   436.3  5602.2  436.46  5620.7  434.08  5626.3  434.42
#Mann= 4 ,-1 , 0
  4282.4      .1       0  4403.5     .16       0  4582.1    .033       0
    5361      .1       0
Bank Sta=4582.1,5361
XS Rating Curve= 0 ,0
Exp/Cntr=0.3,0.1