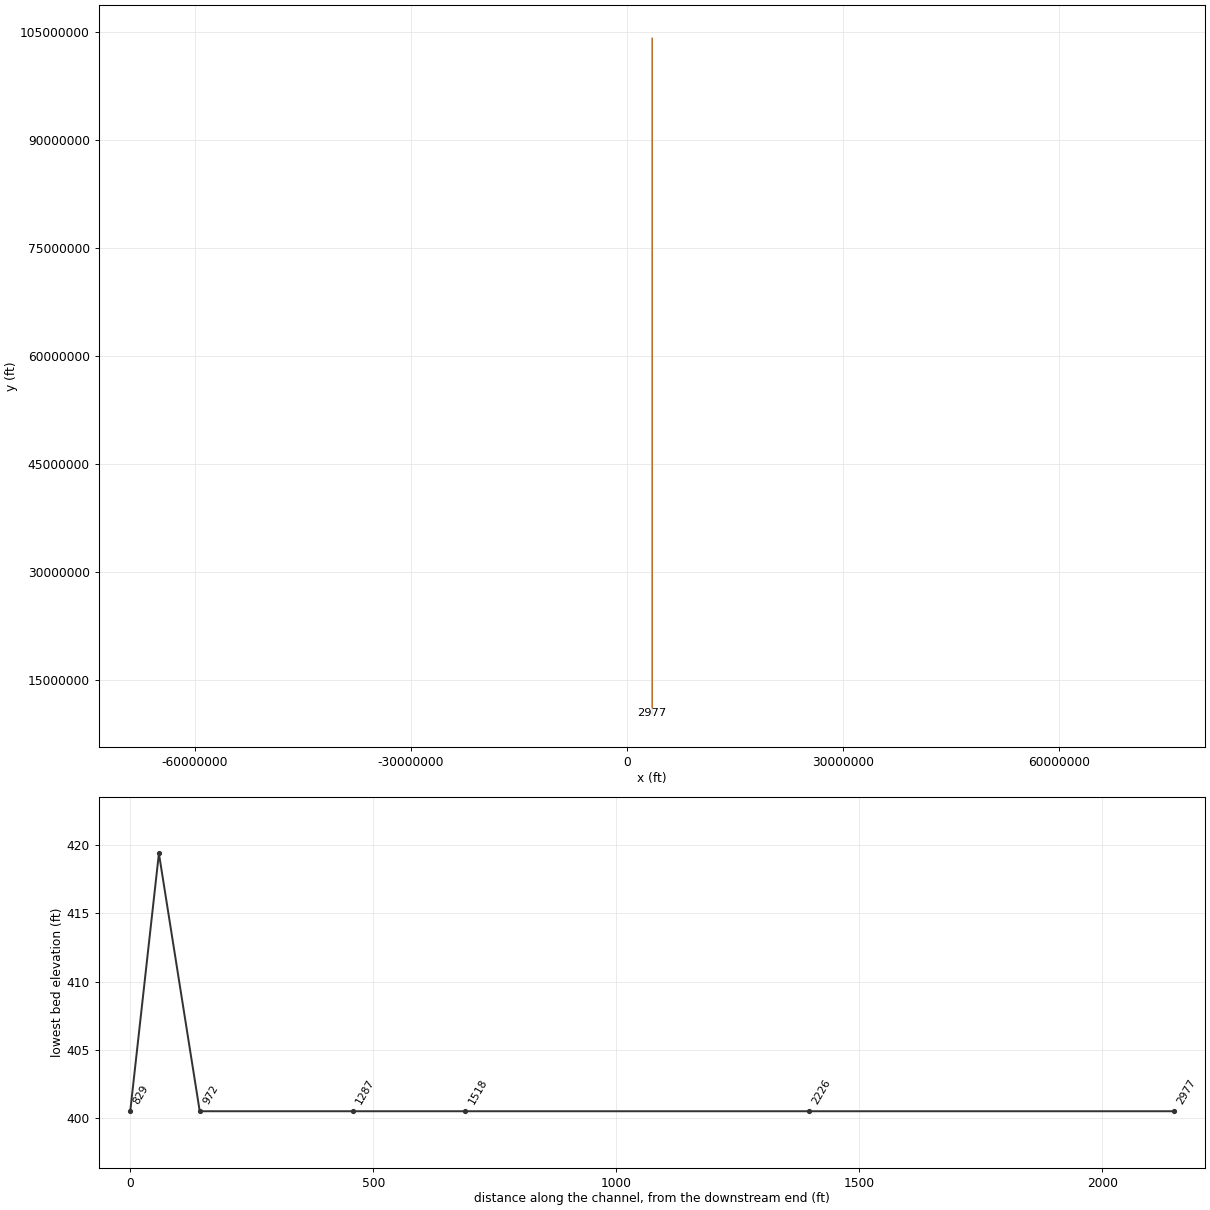
HEC-RAS study OLIVER BRANCH.prj: OLIVER BRANCH Base Level Engineering

--- OLIVER BRANCH.g01 (geometry) --- (continued)

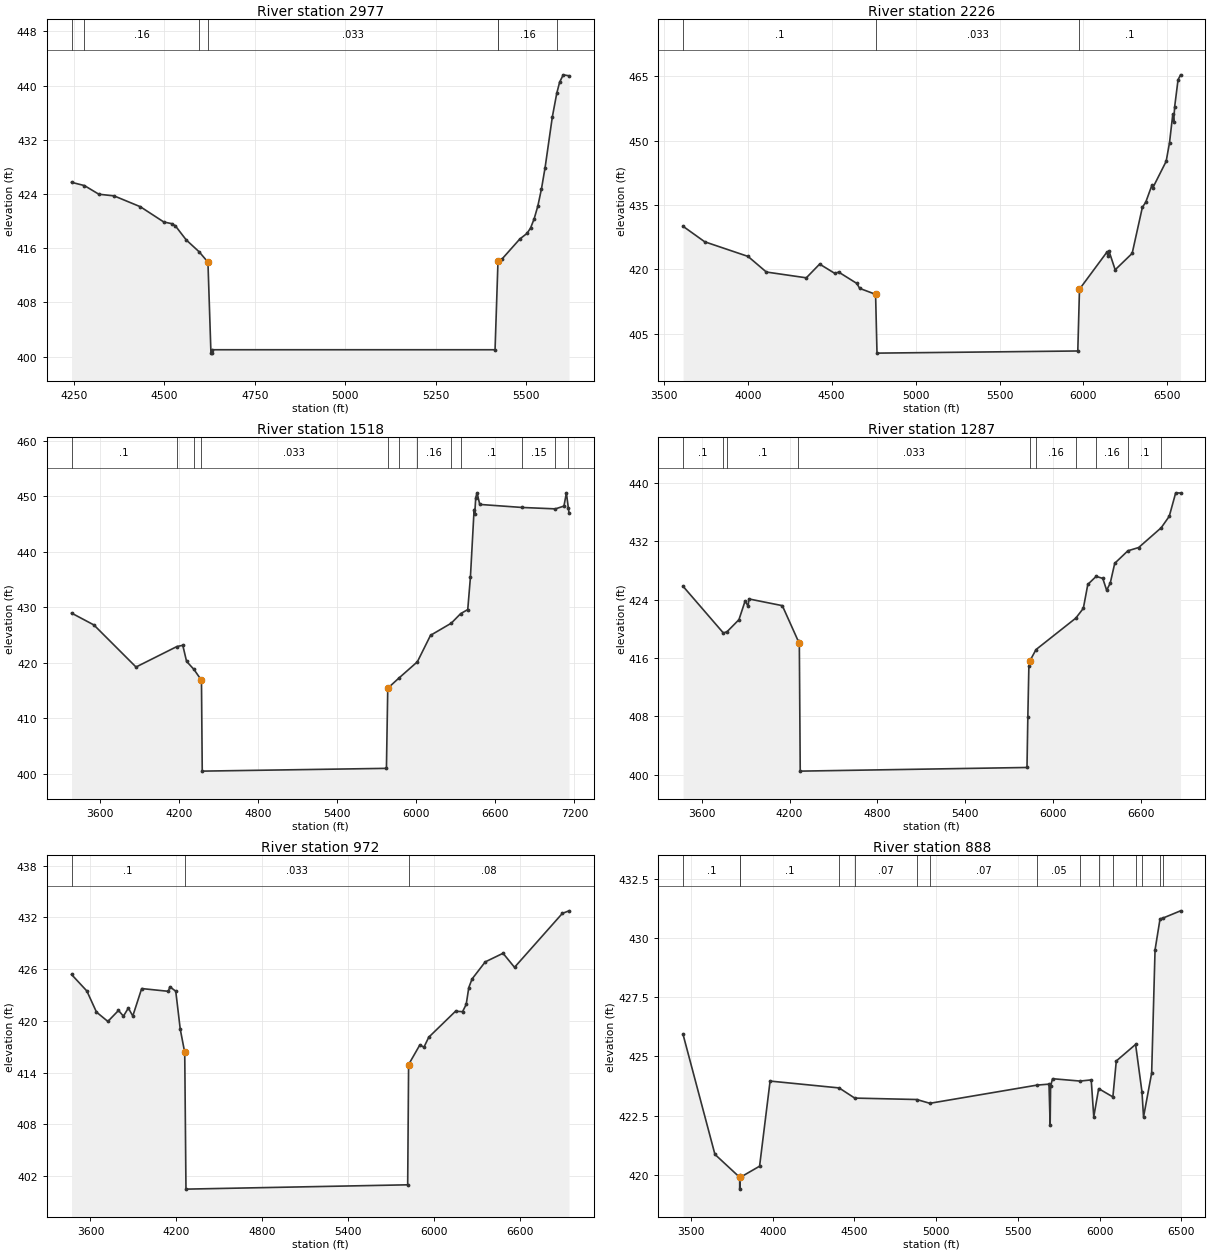
Type RM Length L Ch R = 1 ,2977    ,751,751,751
BEGIN DESCRIPTION:
OLIVER BRANCH 8 0
END DESCRIPTION:
XS GIS Cut Line= 3
      3494802.95     10416945.03      3494948.33     10416721.53
      3494996.04     10415615.68
#Sta/Elev= 30
  4244.2  425.73  4279.9  425.24  4319.5  423.97  4361.7  423.72  4434.2  422.12
  4498.8  419.87  4520.7  419.62  4530.7  419.31  4560.8  417.22  4596.4  415.47
  4620.8  413.94  4629.1   400.5  4632.6   400.5  4632.8     401  5413.5     401
  5421.6  414.06  5422.2  414.08  5431.6  414.33  5481.6  417.34  5501.6  418.18
  5511.6  418.98  5521.6  420.36  5531.7  422.24  5541.7  424.77  5551.7  427.91
  5571.7   435.4  5583.9  438.88  5591.7   440.5  5601.7   441.6  5617.7  441.46
#Mann= 7 ,-1 , 0
  4244.2      .1       0  4279.9     .16       0  4596.4     .05       0
  4620.8    .033       0  5422.2     .05       0  5422.2     .16       0
  5583.9      .1       0
Bank Sta=4620.8,5421.6
XS Rating Curve= 0 ,0
Exp/Cntr=0.3,0.1

Type RM Length L Ch R = 1 ,2226    ,708,708,708
BEGIN DESCRIPTION:
OLIVER BRANCH 6 0
END DESCRIPTION:
XS GIS Cut Line= 3
     3494868.214    10417378.605      3495601.54     10416990.64
      3495933.57     10414876.96
#Sta/Elev= 30
  3614.9  430.07 3743.89  426.46 4001.87  423.05 4111.01  419.41 4349.15  418.06
 4428.52  421.26  4518.9  419.09  4541.7   419.4  4650.5  416.74  4666.9   415.6
  4761.8  414.21  4770.2   400.5  5966.4     401  5976.5  415.41  6138.5  423.98
  6146.9  423.23  6151.9  424.34  6189.1  419.93  6290.3  423.76  6351.1   434.5
  6371.3   435.7  6407.4  439.59  6412.4  438.98  6492.8  445.22    6513  449.61
  6532.5  456.26  6537.6  454.49  6543.4  457.92  6563.6  464.22  6578.5  465.39
#Mann= 3 , 0 , 0
  3614.9      .1       0  4761.8    .033       0  5976.5      .1       0
Bank Sta=4761.8,5976.5
XS Rating Curve= 0 ,0
Exp/Cntr=0.3,0.1

Type RM Length L Ch R = 1 ,1518    ,231,231,231
BEGIN DESCRIPTION:
OLIVER BRANCH 31 0
END DESCRIPTION:
XS GIS Cut Line= 4
      3495003.63   104174543.126      3495743.07     10417145.98
      3496886.27     10416161.63      3497103.28     10414711.97
#Sta/Elev= 30
    3386  428.98 3555.68  426.84 3875.07  419.26    4185  422.95  4229.9  423.17
  4258.5  420.28  4314.4  418.83  4364.9   417.1  4371.5  416.93  4377.4   400.5
  5774.5     401  5784.6  415.44  5871.6  417.32  6009.1   420.2  6108.9  424.97
  6266.3  427.16  6337.6  428.88  6391.3  429.61  6411.5  435.42  6439.5  447.64
  6444.6  446.92  6451.9  449.79    6462  450.65  6482.3  448.56  6804.7  448.01
  7055.6  447.76    7121  448.26  7139.5  450.63  7154.3  447.92  7159.4  447.03
#Mann= 12 ,-1 , 0
    3386      .1       0    4185      .1       0  4314.4     .16       0
  4364.9    .033       0  5784.6     .16       0  5871.6      .1       0
  6009.1     .16       0  6266.3     .05       0  6337.6      .1       0
  6804.7     .15       0  7055.6     .05       0  7154.3      .1       0
Bank Sta=4371.5,5784.6
XS Rating Curve= 0 ,0
Exp/Cntr=0.3,0.1

Type RM Length L Ch R = 1 ,1287    ,315,315,315
BEGIN DESCRIPTION:
OLIVER BRANCH 2 1
END DESCRIPTION:
XS GIS Cut Line= 4
      3495222.81     10417419.41      3495798.34     10417211.07
      3497355.63     10416208.47      3497553.55      10415291.8
#Sta/Elev= 30
  3471.5  425.81  3747.4  419.41  3773.7  419.62  3853.6  421.24  3896.2  423.82
  3916.2  423.07  3921.5  424.08  4150.3  423.16  4259.3   418.3  4266.5  418.06
  4272.7   400.5  5823.4     401  5829.3  407.98  5836.4  414.96  5844.5  415.64
  5884.9  417.14  6157.2  421.45  6208.7  422.79  6239.4  426.07  6296.4  427.17
  6341.7  426.89  6368.2  425.27  6392.8  426.25  6423.5  428.96  6513.3  430.67
  6587.2  431.12  6741.4  433.83  6796.3   435.4  6840.4  438.61  6873.5  438.58
#Mann= 10 ,-1 , 0
  3471.5      .1       0  3747.4     .16       0  3773.7      .1       0
  4259.3    .033       0  5844.5     .05       0  5884.9     .16       0
  6157.2      .1       0  6296.4     .16       0  6513.3      .1       0
  6741.4     .05       0
Bank Sta=4266.5,5844.5
XS Rating Curve= 0 ,0
Exp/Cntr=0.3,0.1

Type RM Length L Ch R = 1 ,972     ,84,84,84
BEGIN DESCRIPTION:
OLIVER BRANCH 21 0
END DESCRIPTION:
XS GIS Cut Line= 6
      3495248.83     10417432.43       3495957.2     10417239.72
      3496665.53     10417026.17      3497063.97     10416768.36
      3497527.51     10416190.24      3497696.78     10415419.42
#Sta/Elev= 30
  3467.5  425.38  3574.5  423.47  3641.9  421.02  3721.5  419.94  3795.8  421.21
  3830.4  420.55  3864.7  421.49  3895.8  420.57    3958  423.75  4144.5  423.43
  4154.9  423.96  4196.3  423.44  4227.6  419.05    4259  416.34  4267.7   400.5
  5818.1     401  5824.5  414.94  5902.9  417.21  5931.7  416.95  5965.4  418.11
  6152.6  421.12  6201.7  421.07  6227.2  421.91  6245.5  423.87  6268.2  424.86
  6360.3  426.84  6484.9  427.84  6565.1  426.21  6899.5  432.46  6946.2  432.76
#Mann= 3 , 0 , 0
  3467.5      .1       0    4259    .033       0  5824.5     .08       0
Bank Sta=4259,5824.5
XS Rating Curve= 0 ,0
Exp/Cntr=0.3,0.1

Type RM Length L Ch R = 1 ,888     ,59,59,59
BEGIN DESCRIPTION:
Mapping XS 0b628b3d
END DESCRIPTION:
XS GIS Cut Line= 6
      3495251.49     10417455.86       3496709.8     10417093.88
      3497113.45     10416828.26      3497300.95     10416643.36
      3497574.38     10416213.67      3497795.73      10416036.6
#Sta/Elev= 30
    3451  425.93    3646  420.86  3797.5  419.89  3797.7  419.39  3801.5  419.89
  3919.3  420.36  3983.6  423.96    4406  423.67  4501.6  423.24  4880.8  423.18
  4961.5  423.02  5617.9  423.79  5690.5  423.83  5697.6  422.09  5700.3  423.74
  5712.2  424.06  5881.2  423.96  5948.9  424.01  5964.5  422.45  5994.6  423.64
  6081.5  423.29  6102.4  424.81  6220.5  425.51  6259.6   423.5  6269.1  422.44
  6318.8   424.3  6339.6  429.51  6370.2  430.82  6390.3  430.86  6495.6  431.16
#Mann= 15 ,-1 , 0
    3451      .1       0  3797.5     .07       0  3801.5      .1       0
    4406     .05       0  4501.6     .07       0  4880.8     .05       0
  4961.5     .07       0  5617.9     .05       0  5881.2     .05       0
  5994.6      .1       0  6081.5     .05       0  6220.5      .1       0
  6259.6     .05       0  6370.2      .1       0  6390.3     .05       0
Bank Sta=3797.5,3801.5
XS Rating Curve= 0 ,0
Exp/Cntr=0.3,0.1

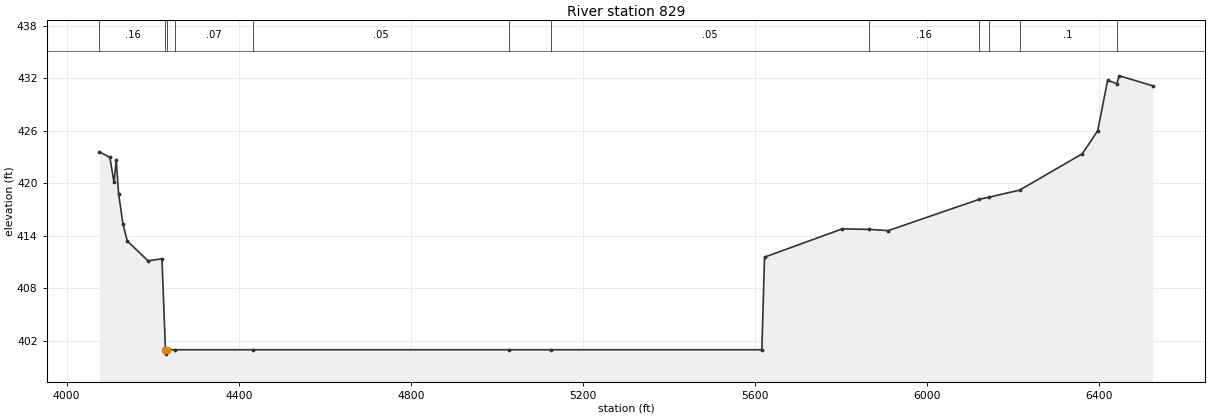
Type RM Length L Ch R = 1 ,829     ,0,0,0
BEGIN DESCRIPTION:
OLIVER BRANCH 11 0
END DESCRIPTION:
XS GIS Cut Line= 4
      3495907.67      10417411.6      3496329.59      10417356.9
      3497259.28     10416869.92      3497824.01     10416076.18
#Sta/Elev= 30
    4076  423.61  4100.6  422.95  4110.1   420.1  4115.2  422.64  4120.8   418.8
  4130.9  415.36    4141  413.41  4189.3  411.15  4221.6  411.38  4229.7     401
    4230   400.5  4233.7     401  4250.9     401  4433.6     401  5028.2     401
  5125.3     401  5616.3     401  5622.5  411.57  5803.2   414.8  5865.4  414.74
  5910.2   414.6  6121.4  418.17  6144.6  418.42  6215.7  419.22  6361.5  423.38
  6397.1     426  6420.2  431.76  6441.3  431.37  6447.5  432.27  6525.1  431.13
#Mann= 12 ,-1 , 0
    4076     .16       0  4229.7    .033       0  4233.7     .16       0
  4250.9     .07       0  4433.6     .05       0  5028.2     .07       0
  5125.3     .05       0  5865.4     .16       0  6121.4     .05       0
  6144.6     .16       0  6215.7      .1       0  6441.3     .05       0
Bank Sta=4229.7,4233.7
XS Rating Curve= 0 ,0
Exp/Cntr=0.3,0.1

Chan Stop Cuts=-1
Use User Specified Reach Order=0
Composite Channel Slope=5