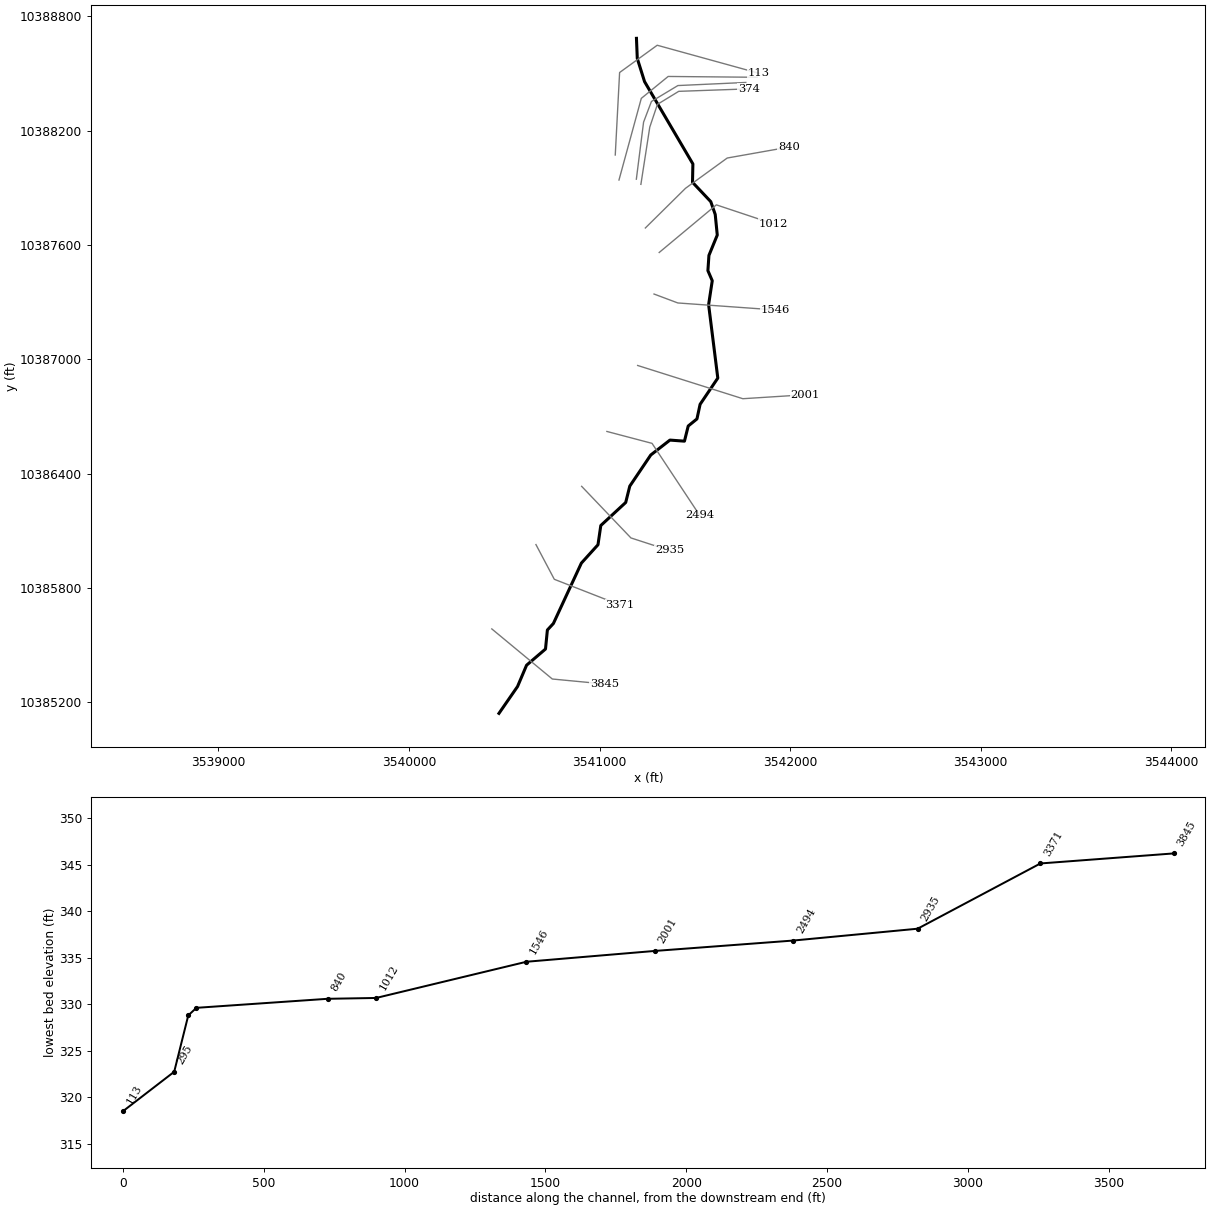
--- PEPPER BRANCH TRIB 1.prj (project) ---

Proj Title=PEPPER BRANCH TRIB 1 Base Level Engineering
Current Plan=p01
Default Exp/Contr=0.3,0.1
English Units
Geom File=g01
Flow File=f01
Plan File=p01
BEGIN DESCRIPTION:
PEPPER BRANCH TRIB 1
END DESCRIPTION:

--- PEPPER BRANCH TRIB 1.p01 (plan) ---

Plan Title=Multiple Run
Short Identifier=Multiple
Geom File=g01
Flow File=f01
Subcritical Flow
K Sum by GR= 0
Std Step Tol= 0.01
Critical Tol= 0.01
Num of Std Step Trials= 20
Max Error Tol= 0.3
Flow Tol Ratio= 0.001
Split Flow NTrial= 30
Split Flow Tol= 0.02
Split Flow Ratio= 0.02
Log Output Level= 0
Friction Slope Method= 1
Unsteady Friction Slope Method= 2
Unsteady Bridges Friction Slope Method= 1
Parabolic Critical Depth
Global Vel Dist=  1 , 1 , 1
Global Log Level= 0
CheckData=True
Encroach Param= -1, 0, 0, 0
BEGIN DESCRIPTION:
Multiple Run
END DESCRIPTION:

--- PEPPER BRANCH TRIB 1.f01 (steady flow) ---

Flow Title=Multiple
Number of Profiles=7
Profile Names=10-year,25-year,50-year,1pct_min,100-year,1pct_plu,500-year
River Rch & RM= PEPPER BRANCH TR,Reach-1,3845
     815    1120    1371    1228    1661    2246    2427
Boundary for River Rch & Prof#=PEPPER BRANCH TR,Reach-1,1
Up Type=0
Dn Type=3
Dn Slope=0.005
Boundary for River Rch & Prof#=PEPPER BRANCH TR,Reach-1,2
Up Type=0
Dn Type=3
Dn Slope=0.005
Boundary for River Rch & Prof#=PEPPER BRANCH TR,Reach-1,3
Up Type=0
Dn Type=3
Dn Slope=0.005
Boundary for River Rch & Prof#=PEPPER BRANCH TR,Reach-1,4
Up Type=0
Dn Type=3
Dn Slope=0.005
Boundary for River Rch & Prof#=PEPPER BRANCH TR,Reach-1,5
Up Type=0
Dn Type=3
Dn Slope=0.005
Boundary for River Rch & Prof#=PEPPER BRANCH TR,Reach-1,6
Up Type=0
Dn Type=3
Dn Slope=0.005
Boundary for River Rch & Prof#=PEPPER BRANCH TR,Reach-1,7
Up Type=0
Dn Type=3
Dn Slope=0.005

--- PEPPER BRANCH TRIB 1.g01 (geometry) ---

Geom Title=Existing Conditions

River Reach=PEPPER BRANCH TR,Reach-1
Reach XY= 30
      3540472.11     10385141.64      3540569.71     10385282.63
      3540617.07     10385394.39      3540716.46     10385479.41
      3540726.35     10385579.26      3540757.91     10385613.46
      3540904.77     10385930.45      3540991.94     10386026.70
      3541006.77     10386127.74      3541137.44     10386248.65
      3541158.88     10386334.49      3541269.03     10386497.87
      3541369.67     10386576.13      3541445.83     10386570.51
      3541465.61     10386650.05      3541511.49     10386687.32
      3541527.97     10386763.89      3541620.89     10386901.65
      3541572.68     10387287.02      3541591.79     10387412.64
      3541568.92     10387465.68      3541574.36     10387545.63
      3541618.10     10387652.29      3541607.35     10387760.75
      3541584.02     10387827.76      3541488.10     10387929.39
      3541490.12     10388025.77      3541236.45     10388457.75
      3541198.25     10388579.28      3541193.93     10388685.00

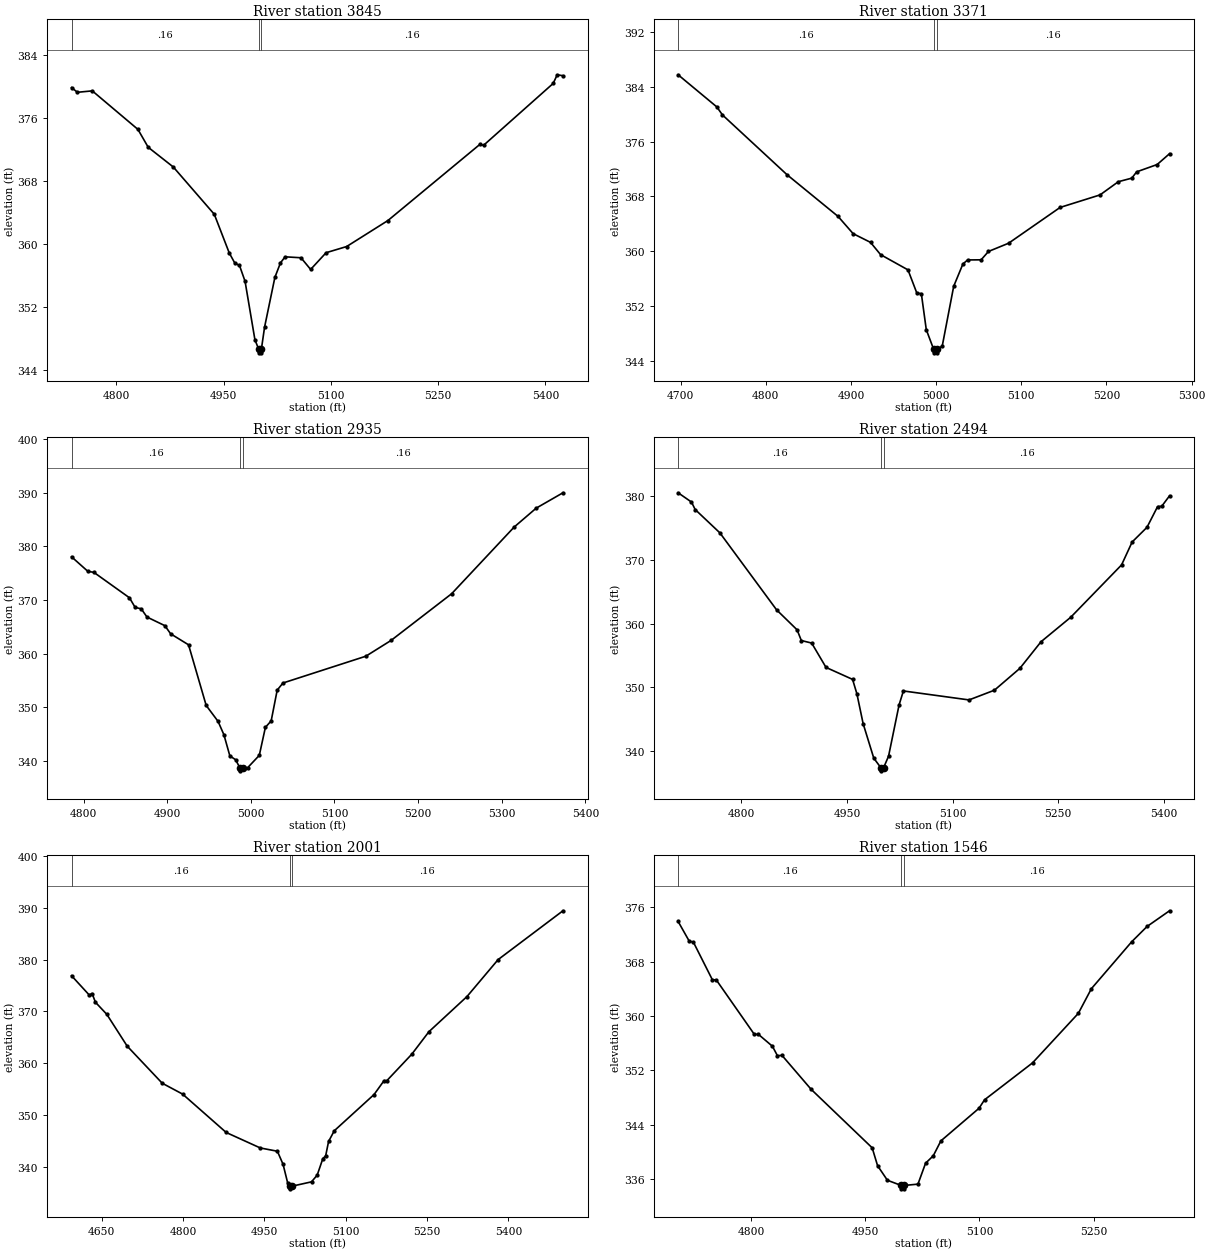
Type RM Length L Ch R = 1,3845,474,474,474
BEGIN DESCRIPTION:
PEPPER BRANCH TRIB 1 13 0
END DESCRIPTION:
XS GIS Cut Line= 3
      3540434.59     10385585.00      3540752.29     10385321.99
      3541025.71     10385295.95
#Sta/Elev= 30
  4737.4  379.84  4745.6  379.24  4766.4  379.42  4830.2  374.54  4844.6  372.27
  4879.7  369.77  4937.0  363.78  4957.9  358.88  4965.7  357.59  4972.2  357.30
  4980.0  355.29  4993.8  347.88  4998.9  346.72  4999.1  346.22  5002.6  346.22
  5002.9  346.72  5007.3  349.48  5021.7  355.78  5029.5  357.62  5036.0  358.39
  5058.2  358.27  5071.7  356.79  5093.3  358.91  5122.0  359.69  5179.8  362.99
  5308.5  372.65  5313.5  372.52  5410.8  380.36  5416.5  381.46  5424.5  381.34
#Mann=3,-1,0
  4737.4    0.16       0  4998.9    0.07       0  5002.9    0.16       0
Bank Sta=4998.9,5002.9
Exp/Cntr=0.3,0.1

Type RM Length L Ch R = 1,3371,436,436,436
BEGIN DESCRIPTION:
PEPPER BRANCH TRIB 1 9 0
END DESCRIPTION:
XS GIS Cut Line= 3
      3540666.36     10386027.68      3540762.70     10385845.43
      3541108.09     10385710.39
#Sta/Elev= 30
  4697.0  385.76  4742.4  381.07  4749.1  379.89  4824.8  371.17  4884.8  365.07
  4902.5  362.55  4922.9  361.28  4934.7  359.49  4966.9  357.26  4977.3  353.87
  4982.6  353.78  4988.4  348.52  4997.1  345.64  4997.4  345.14  5000.9  345.14
  5001.1  345.64  5007.1  346.11  5020.6  354.87  5031.4  358.12  5036.9  358.71
  5052.8  358.73  5061.4  359.95  5085.0  361.15  5145.5  366.38  5192.4  368.21
  5213.9  370.14  5229.7  370.66  5235.4  371.58  5259.5  372.65  5274.0  374.23
#Mann=3,-1,0
  4697.0    0.16       0  4997.1    0.07       0  5001.1    0.16       0
Bank Sta=4997.1,5001.1
Exp/Cntr=0.3,0.1

Type RM Length L Ch R = 1,2935,441,441,441
BEGIN DESCRIPTION:
PEPPER BRANCH TRIB 1 8 0
END DESCRIPTION:
XS GIS Cut Line= 3
      3540906.22     10386333.41      3541164.89     10386062.59
      3541367.57     10385996.76
#Sta/Elev= 30
  4785.6  378.07  4805.1  375.36  4812.3  375.17  4854.8  370.43  4861.7  368.62
  4868.9  368.37  4875.8  366.83  4897.2  365.22  4904.1  363.70  4925.5  361.65
  4946.6  350.33  4960.8  347.36  4967.8  344.86  4974.9  340.92  4981.8  340.20
  4987.1  338.63  4987.3  338.13  4991.1  338.63  4996.0  338.69  5010.1  341.02
  5017.4  346.25  5024.3  347.45  5031.5  353.19  5038.4  354.52  5137.5  359.52
  5167.7  362.47  5240.1  371.18  5314.9  383.63  5341.2  387.15  5373.2  390.02
#Mann=3,-1,0
  4785.6    0.16       0  4987.1    0.07       0  4991.1    0.16       0
Bank Sta=4987.1,4991.1
Exp/Cntr=0.3,0.1

Type RM Length L Ch R = 1,2494,493,493,493
BEGIN DESCRIPTION:
PEPPER BRANCH TRIB 1 7 0
END DESCRIPTION:
XS GIS Cut Line= 3
      3541038.71     10386621.47      3541275.72     10386558.97
      3541525.74     10386181.34
#Sta/Elev= 30
  4710.2  380.58  4729.2  379.12  4734.4  377.95  4769.5  374.28  4850.1  362.17
  4879.2  359.03  4885.2  357.35  4899.9  356.95  4920.3  353.12  4958.0  351.24
  4964.1  348.99  4973.0  344.28  4988.1  338.86  4998.1  337.36  4998.3  336.86
  5002.1  337.36  5009.1  339.16  5024.1  347.25  5030.2  349.42  5123.4  348.01
  5159.5  349.54  5195.6  352.97  5225.7  357.16  5267.8  361.00  5340.1  369.24
  5355.1  372.84  5376.2  375.15  5391.2  378.40  5397.2  378.47  5408.2  380.10
#Mann=3,-1,0
  4710.2    0.16       0  4998.1    0.07       0  5002.1    0.16       0
Bank Sta=4998.1,5002.1
Exp/Cntr=0.3,0.1

Type RM Length L Ch R = 1,2001,455,455,455
BEGIN DESCRIPTION:
PEPPER BRANCH TRIB 1 6 0
END DESCRIPTION:
XS GIS Cut Line= 3
      3541200.16     10386967.83      3541752.29     10386793.34
      3542078.79     10386814.07
#Sta/Elev= 30
  4594.5  376.88  4627.2  373.15  4632.4  373.45  4638.5  371.77  4659.5  369.43
  4697.1  363.29  4761.7  356.13  4799.3  354.03  4879.7  346.62  4942.6  343.63
  4974.1  343.00  4984.6  340.46  4993.2  336.82  4996.5  336.24  4996.7  335.74
  5000.5  336.24  5037.0  337.09  5047.5  338.39  5057.9  341.57  5063.1  342.11
  5068.5  344.89  5079.0  346.95  5152.4  353.95  5170.8  356.63  5176.0  356.63
  5222.0  361.74  5253.5  366.07  5323.7  372.86  5381.1  379.99  5500.7  389.42
#Mann=3,-1,0
  4594.5    0.16       0  4996.5    0.07       0  5000.5    0.16       0
Bank Sta=4996.5,5000.5
Exp/Cntr=0.3,0.1

Type RM Length L Ch R = 1,1546,534,534,534
BEGIN DESCRIPTION:
PEPPER BRANCH TRIB 1 5 0
END DESCRIPTION:
XS GIS Cut Line= 3
      3541286.15     10387342.82      3541411.14     10387295.95
      3541921.55     10387259.49
#Sta/Elev= 30
  4704.3  373.90  4718.9  371.00  4724.3  370.87  4749.2  365.34  4754.5  365.29
  4804.4  357.29  4809.7  357.30  4828.1  355.55  4834.6  354.18  4840.8  354.19
  4878.9  349.22  4959.1  340.61  4966.2  337.98  4979.1  335.84  4997.2  335.08
  4997.4  334.58  5000.9  334.58  5001.2  335.08  5019.2  335.27  5029.2  338.35
  5039.3  339.44  5049.3  341.63  5099.4  346.43  5106.6  347.67  5169.6  353.10
  5229.8  360.39  5246.9  364.01  5299.9  370.92  5320.0  373.16  5349.5  375.47
#Mann=3,-1,0
  4704.3    0.16       0  4997.2    0.07       0  5001.2    0.16       0
Bank Sta=4997.2,5001.2
Exp/Cntr=0.3,0.1

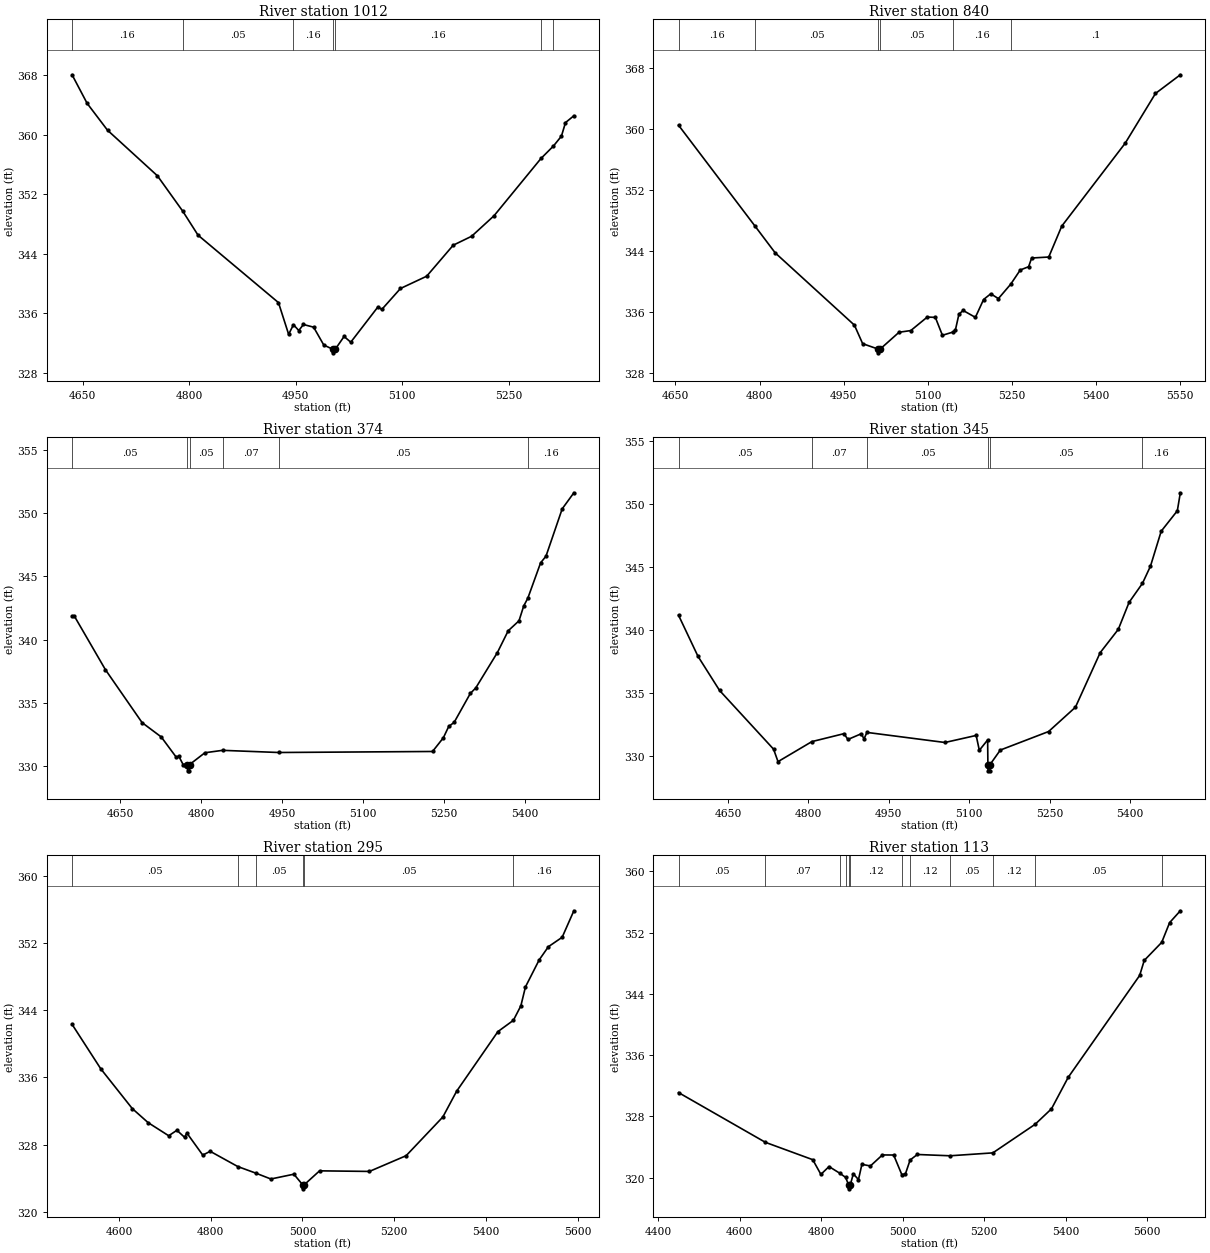
Type RM Length L Ch R = 1,1012,172,172,172
BEGIN DESCRIPTION:
PEPPER BRANCH TRIB 1 2 1
END DESCRIPTION:
XS GIS Cut Line= 3
      3541313.30     10387560.95      3541613.29     10387810.94
      3541913.27     10387710.95
#Sta/Elev= 30
  4635.0  368.07  4656.2  364.23  4684.9  360.62  4755.2  354.49  4790.9  349.73
  4812.4  346.51  4925.7  337.44  4940.0  333.18  4946.8  334.47  4954.3  333.69
  4960.8  334.50  4975.2  334.14  4989.5  331.74  5001.8  331.19  5002.0  330.69
  5005.8  331.19  5018.1  332.89  5027.5  332.12  5065.9  336.88  5071.2  336.52
  5097.5  339.34  5134.4  340.99  5171.8  345.16  5197.7  346.36  5229.3  349.12
  5295.4  356.82  5313.0  358.50  5324.2  359.82  5329.9  361.64  5341.7  362.56
#Mann=7,-1,0
  4635.0    0.16       0  4790.9    0.05       0  4946.8    0.16       0
  5001.8    0.07       0  5005.8    0.16       0  5295.4     0.1       0
  5313.0    0.16       0
Bank Sta=5001.8,5005.8
Exp/Cntr=0.3,0.1

Type RM Length L Ch R = 1,840,466,466,466
BEGIN DESCRIPTION:
PEPPER BRANCH TRIB 1 4 0
END DESCRIPTION:
XS GIS Cut Line= 4
      3541240.57     10387689.53      3541451.45     10387897.86
      3541670.23     10388056.68      3541993.11     10388113.97
#Sta/Elev= 30
  4655.6  360.44  4792.1  347.20  4827.9  343.71  4969.2  334.23  4983.9  331.80
  5011.2  331.10  5011.5  330.60  5015.2  331.10  5048.8  333.30  5069.7  333.52
  5099.1  335.29  5113.5  335.25  5126.1  332.90  5145.2  333.33  5149.3  333.61
  5155.5  335.65  5162.9  336.16  5184.9  335.25  5199.5  337.59  5212.3  338.34
  5225.9  337.71  5247.9  339.60  5264.9  341.46  5279.8  341.89  5285.2  343.03
  5315.7  343.16  5338.9  347.21  5452.0  358.08  5506.0  364.60  5550.3  367.05
#Mann=6,-1,0
  4655.6    0.16       0  4792.1    0.05       0  5011.2   0.035       0
  5015.2    0.05       0  5145.2    0.16       0  5247.9     0.1       0
Bank Sta=5011.2,5015.2
Exp/Cntr=0.3,0.1

Type RM Length L Ch R = 1,374,29,29,29
BEGIN DESCRIPTION:
PEPPER BRANCH TRIB 1 10 0
END DESCRIPTION:
XS GIS Cut Line= 5
      3541217.20     10387918.51      3541263.85     10388219.05
      3541304.00     10388338.41      3541415.76     10388406.77
      3541783.64     10388419.79
#Sta/Elev= 30
  4561.0  341.87  4565.1  341.87  4622.7  337.63  4690.7  333.44  4726.1  332.31
  4753.7  330.72  4758.7  330.78  4766.6  330.13  4774.7  330.13  4774.9  329.63
  4778.4  329.63  4778.7  330.13  4807.0  331.06  4839.7  331.25  4943.4  331.08
  5228.5  331.16  5248.5  332.24  5258.5  333.14  5268.5  333.46  5298.5  335.75
  5308.5  336.18  5348.6  338.98  5368.6  340.70  5388.6  341.49  5397.4  342.67
  5404.9  343.27  5428.6  346.07  5438.6  346.60  5468.6  350.34  5490.2  351.61
#Mann=6,-1,0
  4561.0    0.05       0  4774.7   0.035       0  4778.7    0.05       0
  4839.7    0.07       0  4943.4    0.05       0  5404.9    0.16       0
Bank Sta=4774.7,4778.7
Exp/Cntr=0.3,0.1

Type RM Length L Ch R = 1,345,50,50,50
BEGIN DESCRIPTION:
PEPPER BRANCH TRIB 1 3 0
END DESCRIPTION:
XS GIS Cut Line= 5
      3541193.33     10387945.65      3541231.30     10388245.10
      3541272.53     10388353.60      3541411.42     10388437.15
      3541767.75     10388453.40
#Sta/Elev= 30
  4557.5  341.17  4593.8  337.91  4634.1  335.20  4734.9  330.54  4743.2  329.55
  4806.4  331.14  4866.3  331.77  4873.7  331.31  4898.4  331.76  4903.8  331.36
  4909.2  331.87  5054.8  331.07  5113.1  331.63  5119.0  330.45  5134.5  331.27
  5135.0  329.32  5135.3  328.82  5138.8  328.82  5139.0  329.32  5158.2  330.47
  5248.3  331.94  5298.4  333.87  5344.6  338.20  5378.4  340.05  5398.5  342.19
  5423.5  343.70  5438.5  345.07  5458.5  347.84  5488.6  349.46  5494.2  350.89
#Mann=6,-1,0
  4557.5    0.05       0  4806.4    0.07       0  4909.2    0.05       0
  5135.0    0.04       0  5139.0    0.05       0  5423.5    0.16       0
Bank Sta=5135,5139
Exp/Cntr=0.3,0.1

Type RM Length L Ch R = 1,295,182,182,182
BEGIN DESCRIPTION:
PEPPER BRANCH TRIB 1 2 0
END DESCRIPTION:
XS GIS Cut Line= 4
      3541102.18     10387941.31      3541219.36     10388369.88
      3541360.42     10388484.90      3541827.59     10388480.56
#Sta/Elev= 30
  4497.9  342.31  4560.4  337.03  4629.1  332.30  4663.6  330.63  4708.5  329.07
  4726.3  329.72  4743.0  328.89  4748.1  329.39  4782.7  326.77  4798.9  327.22
  4859.0  325.41  4898.6  324.62  4931.1  323.93  4981.3  324.50  5000.1  323.26
  5000.3  322.76  5004.1  323.26  5037.3  324.90  5145.9  324.83  5225.9  326.70
  5305.9  331.30  5335.9  334.36  5425.9  341.45  5459.6  342.79  5475.9  344.51
  5485.9  346.76  5515.9  349.98  5535.9  351.54  5565.9  352.66  5591.4  355.81
#Mann=6,-1,0
  4497.9    0.05       0  4859.0    0.07       0  4898.6    0.05       0
  5000.1   0.035       0  5004.1    0.05       0  5459.6    0.16       0
Bank Sta=5000.1,5004.1
Exp/Cntr=0.3,0.1

Type RM Length L Ch R = 1,113,0,0,0
BEGIN DESCRIPTION:
PEPPER BRANCH TRIB 1 1 0
END DESCRIPTION:
XS GIS Cut Line= 4
      3541082.65     10388072.60      3541105.43     10388505.51
      3541302.91     10388648.74      3541837.48     10388501.27
#Sta/Elev= 30
  4449.4  331.10  4662.6  324.60  4778.9  322.33  4798.9  320.41  4818.9  321.43
  4845.9  320.54  4859.7  320.01  4867.0  319.02  4867.3  318.52  4871.0  319.02
  4878.5  320.48  4891.2  319.73  4899.6  321.72  4920.5  321.51  4949.9  322.95
  4977.6  322.94  4997.5  320.39  5006.3  320.45  5018.0  322.29  5035.7  323.01
  5116.1  322.84  5221.1  323.22  5324.8  326.95  5365.1  328.98  5406.1  333.09
  5581.6  346.41  5592.8  348.37  5635.7  350.73  5655.1  353.31  5681.4  354.86
#Mann=12,-1,0
  4449.4    0.05       0  4662.6    0.07       0  4845.9    0.05       0
  4859.7    0.12       0  4867.0    0.07       0  4871.0    0.12       0
  4997.5    0.16       0  5018.0    0.12       0  5116.1    0.05       0
  5221.1    0.12       0  5324.8    0.05       0  5635.7    0.16       0
Bank Sta=4867,4871
Exp/Cntr=0.3,0.1

Chan Stop Cuts=-1