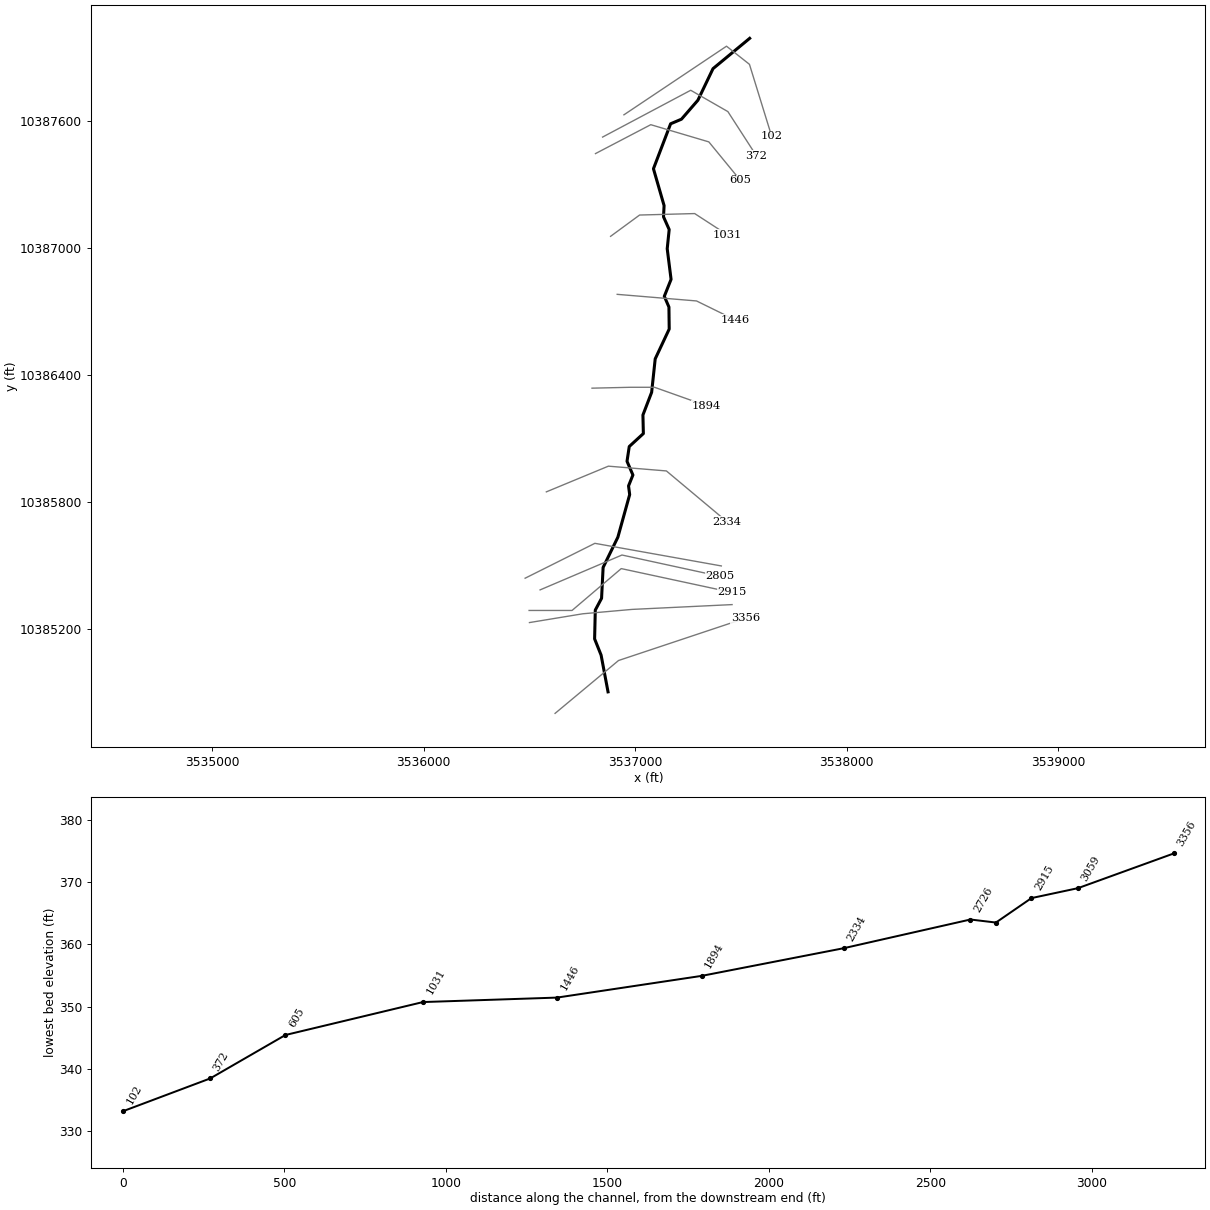
--- PEPPER BRANCH TRIB 2.prj (project) ---

Proj Title=PEPPER BRANCH TRIB 2 Base Level Engineering
Current Plan=p01
Default Exp/Contr=0.3,0.1
English Units
Geom File=g01
Flow File=f01
Plan File=p01
Y Axis Title=Elevation
X Axis Title(PF)=Main Channel Distance
X Axis Title(XS)=Station
BEGIN DESCRIPTION:
PEPPER BRANCH TRIB 2
END DESCRIPTION:
DSS Export Rating Curves= 0
DSS Export Rating Curve Sorted= 0
DSS Export Volume Flow Curves= 0
DXF OffsetX= 0
DXF OffsetY= 0
DXF ScaleX= 1
DXF ScaleY= 10

--- PEPPER BRANCH TRIB 2.p01 (plan) ---

Plan Title=Multiple Run
Short Identifier=Multiple
Geom File=g01
Flow File=f01
Subcritical Flow
K Sum by GR= 0
Std Step Tol= 0.01
Critical Tol= 0.01
Num of Std Step Trials= 20
Max Error Tol= 0.3
Flow Tol Ratio= 0.001
Split Flow NTrial= 30
Split Flow Tol= 0.02
Split Flow Ratio= 0.02
Log Output Level= 0
Friction Slope Method= 1
Unsteady Friction Slope Method= 2
Unsteady Bridges Friction Slope Method= 1
Parabolic Critical Depth
Global Vel Dist=  1 , 1 , 1
Global Log Level= 0
CheckData=True
Encroach Param= -1, 0, 0, 0
BEGIN DESCRIPTION:
Multiple Run
END DESCRIPTION:

--- PEPPER BRANCH TRIB 2.f01 (steady flow) ---

Flow Title=Multiple
Number of Profiles=7
Profile Names=10-year,25-year,50-year,1pct_min,100-year,1pct_plu,500-year
River Rch & RM= PEPPER BRANCH TR,Reach-1,3356
     551     738     888     783    1059    1432    1497
Boundary for River Rch & Prof#=PEPPER BRANCH TR,Reach-1,1
Up Type=0
Dn Type=3
Dn Slope=0.005
Boundary for River Rch & Prof#=PEPPER BRANCH TR,Reach-1,2
Up Type=0
Dn Type=3
Dn Slope=0.005
Boundary for River Rch & Prof#=PEPPER BRANCH TR,Reach-1,3
Up Type=0
Dn Type=3
Dn Slope=0.005
Boundary for River Rch & Prof#=PEPPER BRANCH TR,Reach-1,4
Up Type=0
Dn Type=3
Dn Slope=0.005
Boundary for River Rch & Prof#=PEPPER BRANCH TR,Reach-1,5
Up Type=0
Dn Type=3
Dn Slope=0.005
Boundary for River Rch & Prof#=PEPPER BRANCH TR,Reach-1,6
Up Type=0
Dn Type=3
Dn Slope=0.005
Boundary for River Rch & Prof#=PEPPER BRANCH TR,Reach-1,7
Up Type=0
Dn Type=3
Dn Slope=0.005

--- PEPPER BRANCH TRIB 2.g01 (geometry) ---

Geom Title=Existing Conditions
Program Version=4.10

River Reach=PEPPER BRANCH TR,Reach-1
Reach XY= 30
      3536872.33     10384901.39      3536839.59     10385075.16
      3536808.89     10385151.88      3536812.12     10385288.16
      3536841.81     10385343.89       3536849.1     10385489.72
      3536918.94     10385632.95       3536974.7     10385834.18
      3536969.35     10385875.27      3536989.99     10385926.79
      3536962.11     10385991.64       3536972.7     10386061.42
      3537039.41     10386122.72      3537037.38     10386210.54
      3537078.55     10386317.81      3537095.42     10386475.92
      3537161.63     10386616.96      3537160.31      10386721.1
      3537138.44     10386771.69      3537170.45     10386851.95
      3537152.19     10386996.69      3537161.52     10387087.47
      3537134.72     10387147.75      3537137.41     10387200.78
      3537087.13     10387374.91      3537168.26     10387587.55
      3537219.63     10387609.34      3537297.24     10387698.93
      3537368.78     10387848.31      3537542.11     10387991.64

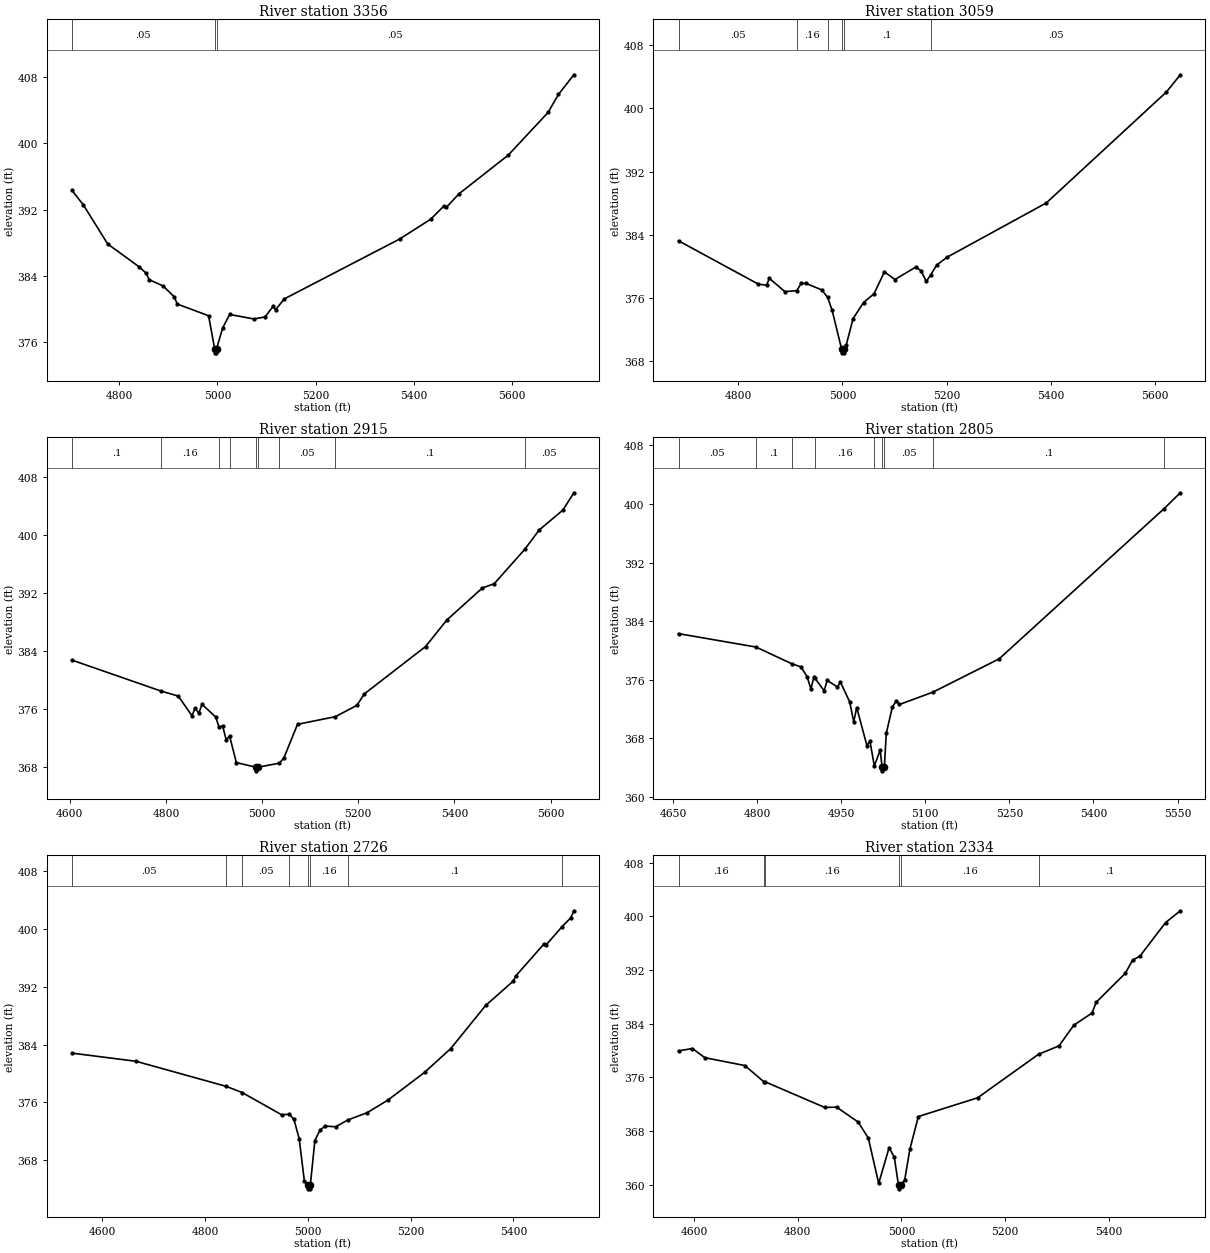
Type RM Length L Ch R = 1 ,3356    ,297,297,297
BEGIN DESCRIPTION:
PEPPER BRANCH TRIB 2 9 0
END DESCRIPTION:
XS GIS Cut Line= 3
      3536621.98     10384799.64      3536921.97     10385049.63
      3537521.92     10385249.61
#Sta/Elev= 30
  4703.6  394.31  4726.7  392.56  4776.2  387.84    4840  385.09  4854.3  384.32
  4860.8  383.52  4889.4  382.75  4911.6  381.46  4918.1  380.57  4981.9  379.16
  4994.2  375.17  4994.4  374.67  4997.9  374.67  4998.2  375.17  5010.5  377.67
  5024.8  379.31  5074.3  378.77  5096.8  379.01  5113.2  380.28  5118.4  379.89
  5136.4   381.2  5371.4  388.44  5434.7  390.84    5461   392.4  5466.3  392.26
  5492.6  393.92  5592.8  398.59    5674  403.76  5695.1  405.93  5726.5  408.31
#Mann= 3 ,-1 , 0
  4703.6     .05       0  4994.2     .03       0  4998.2     .05       0
Bank Sta=4994.2,4998.2
XS Rating Curve= 0 ,0
Exp/Cntr=0.3,0.1

Type RM Length L Ch R = 1 ,3059    ,144,144,144
BEGIN DESCRIPTION:
PEPPER BRANCH TRIB 2 8 0
END DESCRIPTION:
XS GIS Cut Line= 4
      3536500.84     10385229.03      3536752.75     10385270.56
      3536985.52     10385291.24      3537458.97       10385314.
#Sta/Elev= 30
  4685.5  383.25  4838.8  377.76  4854.6  377.63  4859.7   378.5  4889.5  376.82
  4912.5  376.94  4920.8  377.86    4930  377.86  4960.2  377.04  4971.6  376.09
  4980.3  374.44  4998.4  369.57  4998.7  369.07  5002.2  369.07  5002.4  369.57
  5007.5  370.11  5020.5  373.41  5040.6  375.44  5060.6  376.54  5080.7  379.32
  5100.8  378.35    5141  379.93    5151  379.45    5161   378.1  5169.3  378.93
  5181.1  380.19  5201.1  381.18  5391.3  388.04  5621.6  402.07  5648.5  404.26
#Mann= 6 ,-1 , 0
  4685.5     .05       0  4912.5     .16       0  4971.6      .1       0
  4998.4     .07       0  5002.4      .1       0  5169.3     .05       0
Bank Sta=4998.4,5002.4
XS Rating Curve= 0 ,0
Exp/Cntr=0.3,0.1

Type RM Length L Ch R = 1 ,2915    ,110,110,110
BEGIN DESCRIPTION:
PEPPER BRANCH TRIB 2 10 0
END DESCRIPTION:
XS GIS Cut Line= 4
      3536499.09     10385286.31      3536702.18     10385286.31
      3536934.82     10385484.23      3537458.11      10385371.6
#Sta/Elev= 30
  4604.6  382.76  4789.6  378.49  4825.5   377.8    4854  375.08  4860.6  376.13
  4868.3  375.43  4874.9  376.66  4903.4   374.9  4910.3   373.5  4917.7  373.69
  4925.4  371.72  4932.2   372.3  4946.3  368.61  4987.1  367.97  4987.4  367.47
  4991.1  367.97  5035.8  368.53  5045.1  369.24  5073.6   373.9  5152.2  374.95
    5197  376.51  5212.6   378.1  5339.9  384.64  5384.1   388.3  5458.1  392.73
  5482.8  393.32  5546.4  398.08  5576.3  400.74  5625.7   403.5  5648.4  405.88
#Mann= 9 ,-1 , 0
  4604.6      .1       0  4789.6     .16       0  4910.3      .1       0
  4932.2     .16       0  4987.1     .07       0  4991.1     .16       0
  5035.8     .05       0  5152.2      .1       0  5546.4     .05       0
Bank Sta=4987.1,4991.1
XS Rating Curve= 0 ,0
Exp/Cntr=0.3,0.1

Type RM Length L Ch R = 1 ,2805    ,79,79,79
BEGIN DESCRIPTION:
PEPPER BRANCH TRIB 2 12 0
END DESCRIPTION:
XS GIS Cut Line= 3
      3536551.12     10385383.53      3536938.29     10385548.47
      3537401.84     10385447.77
#Sta/Elev= 30
  4659.8  382.28  4797.9  380.45    4862  378.16  4878.3  377.73  4889.1  376.41
    4896   374.7  4901.4   376.4  4903.5  376.16  4919.6  374.47    4925  375.89
  4943.2  374.99  4948.7  375.66  4965.2  372.94  4972.3  370.22  4977.7  372.18
  4995.9  366.97  5001.3   367.6  5009.1  364.19  5019.5  366.37    5023  364.03
  5023.2  363.53    5027  364.03  5030.4  368.65  5041.3  372.26  5048.6  373.13
    5054   372.6  5113.5  374.28  5231.7  378.83    5526  399.36    5555  401.53
#Mann= 9 ,-1 , 0
  4659.8     .05       0  4797.9      .1       0    4862     .05       0
  4903.5     .16       0  5009.1     .05       0    5023     .07       0
    5027     .05       0  5113.5      .1       0    5526     .05       0
Bank Sta=5023,5027
XS Rating Curve= 0 ,0
Exp/Cntr=0.3,0.1

Type RM Length L Ch R = 1 ,2726    ,392,392,392
BEGIN DESCRIPTION:
PEPPER BRANCH TRIB 2 11 0
END DESCRIPTION:
XS GIS Cut Line= 3
      3536480.31     10385438.81      3536810.17     10385603.74
      3537408.09     10385496.82
#Sta/Elev= 30
  4541.5  382.82  4665.9  381.69  4841.2  378.22  4872.4  377.36  4949.2  374.28
  4964.4  374.35  4973.2  373.63  4983.4  370.94  4993.5  365.05    5001  364.52
  5001.3  364.02  5004.8  364.02    5005  364.52  5013.8  370.69    5024  372.19
  5034.2  372.71  5054.5  372.62  5077.6  373.55  5115.4  374.56  5156.1  376.32
  5227.2  380.15    5278  383.44  5346.1  389.42  5399.9   392.8    5405  393.54
  5458.8  397.88  5463.9  397.83  5494.4  400.31  5511.6  401.56  5517.7  402.54
#Mann= 8 ,-1 , 0
  4541.5     .05       0  4841.2     .16       0  4872.4     .05       0
  4964.4     .16       0    5001     .07       0    5005     .16       0
  5077.6      .1       0  5494.4     .05       0
Bank Sta=5001,5005
XS Rating Curve= 0 ,0
Exp/Cntr=0.3,0.1

Type RM Length L Ch R = 1 ,2334    ,440,440,440
BEGIN DESCRIPTION:
PEPPER BRANCH TRIB 2 7 0
END DESCRIPTION:
XS GIS Cut Line= 4
      3536580.67     10385847.08      3536874.06     10385968.61
      3537148.36     10385946.04      3537435.42     10385705.67
#Sta/Elev= 30
  4570.4  379.96  4597.2  380.32  4621.1  378.95  4698.2  377.78  4734.4  375.39
  4737.4  375.35  4852.3  371.53    4875  371.58  4916.5  369.37  4936.2  366.97
  4956.2  360.22  4976.3  365.54  4986.3  364.11  4994.4   359.9  4994.6   359.4
  4998.4   359.9  5006.4  360.76  5016.4  365.34  5032.7  370.18  5146.9  372.97
  5264.3  379.46  5303.7  380.71  5332.4   383.8  5367.5  385.61  5375.3   387.2
  5431.3  391.51  5445.6  393.48  5459.9  394.11  5509.3   399.1  5537.6  400.85
#Mann= 6 ,-1 , 0
  4570.4     .16       0  4734.4     .05       0  4737.4     .16       0
  4994.4     .07       0  4998.4     .16       0  5264.3      .1       0
Bank Sta=4994.4,4998.4
XS Rating Curve= 0 ,0
Exp/Cntr=0.3,0.1

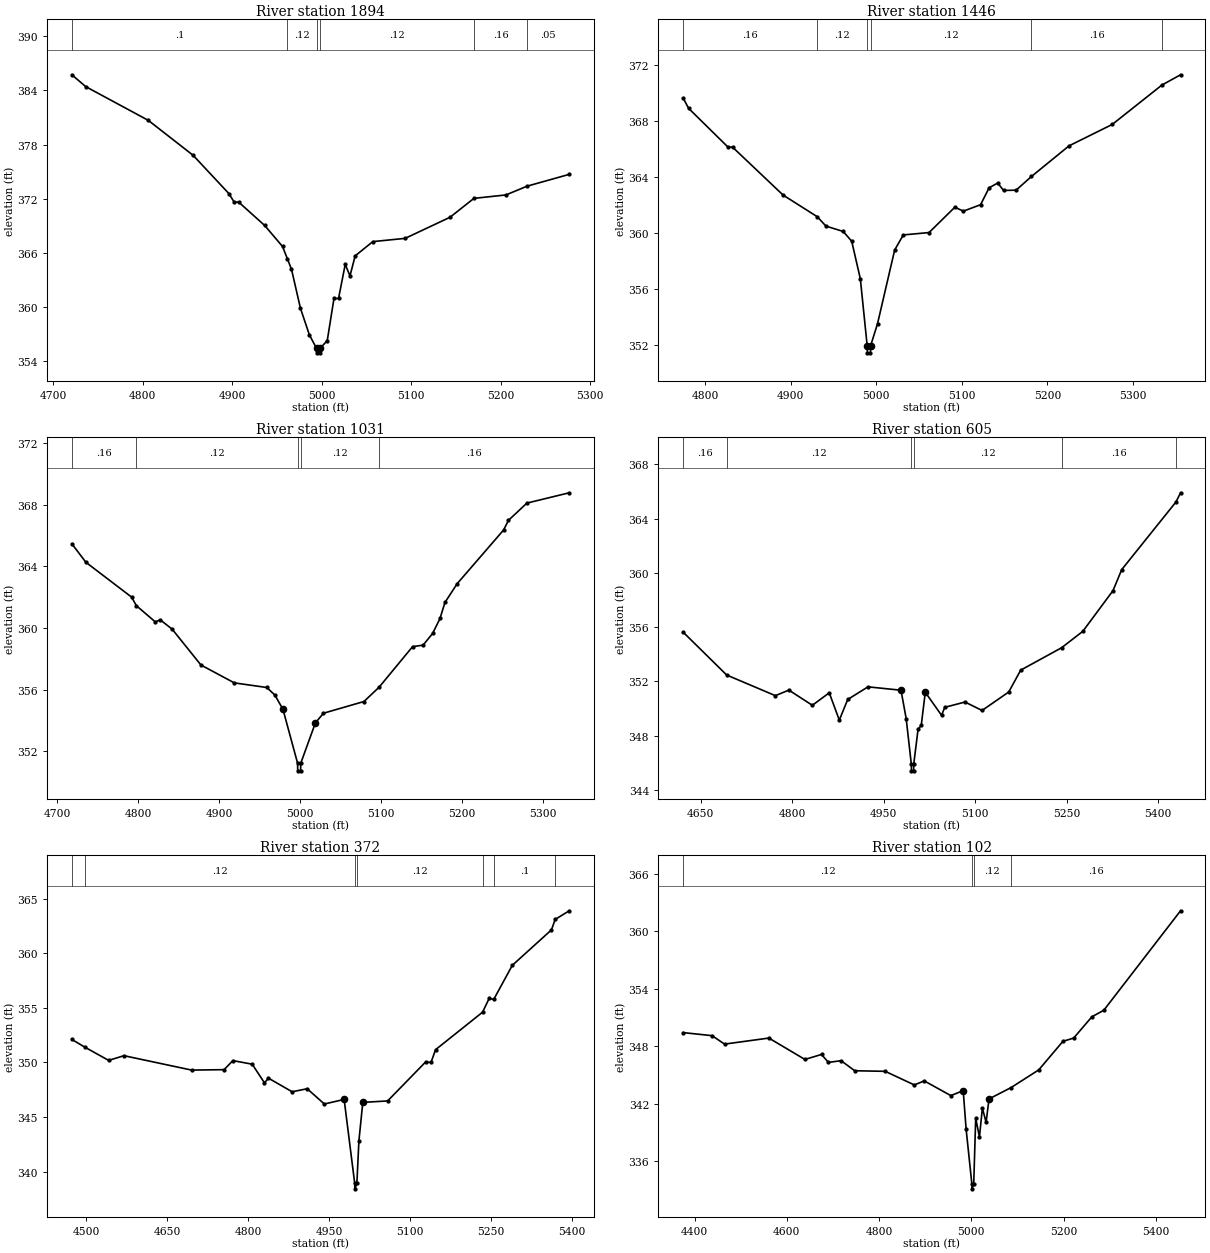
Type RM Length L Ch R = 1 ,1894    ,448,448,448
BEGIN DESCRIPTION:
PEPPER BRANCH TRIB 2 6 0
END DESCRIPTION:
XS GIS Cut Line= 4
      3536796.59     10386337.42      3536978.92     10386341.64
      3537092.11     10386341.64      3537337.67     10386254.31
#Sta/Elev= 30
  4720.6  385.74  4736.1  384.43  4806.1  380.69  4856.2  376.82  4896.2  372.58
  4902.1  371.64  4907.1  371.64  4936.2  369.05  4956.2  366.72  4961.7  365.33
  4966.2   364.2  4976.2  359.88  4986.2  356.93  4994.2  355.44  4994.4  354.94
  4997.9  354.94  4998.2  355.44  5006.2   356.3  5013.7  360.96  5018.8  360.96
  5026.3  364.74  5031.6  363.46  5037.4  365.68  5057.1  367.26  5093.3  367.62
  5143.5  369.96  5170.2  372.05    5206  372.43  5229.6   373.4  5276.8  374.71
#Mann= 6 ,-1 , 0
  4720.6      .1       0  4961.7     .12       0  4994.2     .07       0
  4998.2     .12       0  5170.2     .16       0  5229.6     .05       0
Bank Sta=4994.2,4998.2
XS Rating Curve= 0 ,0
Exp/Cntr=0.3,0.1

Type RM Length L Ch R = 1 ,1446    ,415,415,415
BEGIN DESCRIPTION:
PEPPER BRANCH TRIB 2 5 0
END DESCRIPTION:
XS GIS Cut Line= 3
      3536915.74      10386781.1      3537290.72     10386749.86
      3537474.78     10386659.56
#Sta/Elev= 30
  4774.3  369.66  4780.7  368.92  4826.9  366.14    4832  366.15  4891.1  362.72
  4931.1  361.17  4941.2   360.5  4961.3  360.12  4971.3  359.42  4981.4  356.73
  4989.4  351.94  4989.7  351.44  4993.2  351.44  4993.4  351.94  5001.5  353.53
  5021.5  358.79  5031.6  359.87  5061.7  360.04  5091.8  361.85  5101.8  361.57
  5121.9  362.03  5131.9  363.24  5141.9  363.58  5148.8  363.05  5163.4  363.07
  5181.4  364.05  5225.3  366.24  5275.8  367.77  5333.7  370.58  5355.6  371.32
#Mann= 6 ,-1 , 0
  4774.3     .16       0  4931.1     .12       0  4989.4     .07       0
  4993.4     .12       0  5181.4     .16       0  5333.7     .05       0
Bank Sta=4989.4,4993.4
XS Rating Curve= 0 ,0
Exp/Cntr=0.3,0.1

Type RM Length L Ch R = 1 ,1031    ,426,426,426
BEGIN DESCRIPTION:
PEPPER BRANCH TRIB 2 4 0
END DESCRIPTION:
XS GIS Cut Line= 4
      3536884.47     10387055.41      3537021.63     10387156.11
      3537282.04     10387163.05      3537435.96     10387063.07
#Sta/Elev= 30
  4718.2  365.46  4735.5  364.26  4791.9     362  4797.9  361.44  4821.2  360.39
  4827.4  360.52    4842  359.92  4877.6  357.59  4918.8  356.43  4958.9  356.13
  4968.9  355.64  4978.9  354.71  4996.9  351.22  4997.1  350.72  5000.6  350.72
  5000.9  351.22  5018.9  353.83  5028.9  354.46  5078.9  355.22  5097.6  356.15
  5138.9  358.78  5151.9  358.88  5163.7  359.64  5172.8  360.61  5178.9  361.65
    5194  362.87  5251.4  366.36  5257.3  366.98  5280.1   368.1  5332.4  368.77
#Mann= 5 ,-1 , 0
  4718.2     .16       0  4797.9     .12       0  4996.9     .07       0
  5000.9     .12       0  5097.6     .16       0
Bank Sta=4978.9,5018.9
XS Rating Curve= 0 ,0
Exp/Cntr=0.3,0.1

Type RM Length L Ch R = 1 ,605     ,233,233,233
BEGIN DESCRIPTION:
PEPPER BRANCH TRIB 2 3 0
END DESCRIPTION:
XS GIS Cut Line= 4
      3536813.02     10387446.62      3537074.51     10387583.33
      3537349.03     10387501.95      3537497.38     10387321.12
#Sta/Elev= 30
  4621.2  355.63  4692.6  352.47  4772.4  350.95  4794.5  351.36    4833  350.24
  4860.7  351.16  4877.2  349.15    4891  350.67  4924.2   351.6  4978.3  351.35
  4986.8  349.26  4995.2  345.91  4995.5  345.41    4999  345.41  4999.2  345.91
  5006.3  348.48  5011.5  348.76  5018.1   351.2  5044.8   349.5    5050  350.09
  5083.2  350.48  5111.2  349.86  5154.9  351.22  5174.5  352.83  5241.5  354.48
  5276.3  355.69  5325.8  358.69  5340.1  360.24  5429.1  365.23  5436.5   365.9
#Mann= 6 ,-1 , 0
  4621.2     .16       0  4692.6     .12       0  4995.2     .07       0
  4999.2     .12       0  5241.5     .16       0  5429.1      .1       0
Bank Sta=4978.3,5018.1
XS Rating Curve= 0 ,0
Exp/Cntr=0.3,0.1

Type RM Length L Ch R = 1 ,372     ,270,270,270
BEGIN DESCRIPTION:
PEPPER BRANCH TRIB 2 2 0
END DESCRIPTION:
XS GIS Cut Line= 4
      3536846.68     10387524.76      3537263.31     10387746.09
      3537439.09     10387645.18      3537573.66     10387436.82
#Sta/Elev= 30
  4473.3  352.11  4496.8  351.42  4541.5  350.19    4570  350.62  4695.4   349.3
  4755.6  349.34    4772  350.17  4807.8  349.84  4830.5  348.13  4837.9  348.56
  4881.9  347.31  4909.7  347.59  4941.6  346.19  4978.3  346.61  4997.9  338.91
  4998.2  338.41  5001.9  338.91  5005.7  342.83  5012.9  346.34  5058.9  346.47
  5129.3  350.04  5139.4     350  5147.8  351.17    5235  354.61  5247.2  355.87
  5255.8  355.79  5290.2  358.91  5362.8  362.16  5369.7  363.12  5395.8  363.91
#Mann= 7 ,-1 , 0
  4473.3     .16       0  4496.8     .12       0  4997.9     .07       0
  5001.9     .12       0    5235     .16       0  5255.8      .1       0
  5369.7     .16       0
Bank Sta=4978.3,5012.9
XS Rating Curve= 0 ,0
Exp/Cntr=0.3,0.1

Type RM Length L Ch R = 1 ,102     ,0,0,0
BEGIN DESCRIPTION:
PEPPER BRANCH TRIB 2 1 0
END DESCRIPTION:
XS GIS Cut Line= 4
      3536947.54     10387629.98      3537432.58     10387954.43
      3537541.09     10387868.71      3537646.33     10387528.03
#Sta/Elev= 30
  4375.2  349.43    4438  349.11    4465  348.23  4561.1  348.86  4639.2  346.63
  4675.2  347.15  4690.2  346.32  4717.6   346.5  4747.3  345.45  4813.3  345.39
  4876.4  343.97    4898  344.39  4955.5  342.86  4982.4  343.37  4988.7  339.37
  5001.2  333.63  5001.4  333.13  5005.2  333.63  5009.5   340.5  5017.6  338.54
    5024  341.56    5032  340.07  5038.4  342.51    5086  343.69  5146.2  345.54
  5198.6  348.52  5221.9  348.86  5261.4  351.08  5287.2  351.76  5453.6  362.14
#Mann= 4 ,-1 , 0
  4375.2     .12       0  5001.2     .07       0  5005.2     .12       0
    5086     .16       0
Bank Sta=4982.4,5038.4
XS Rating Curve= 0 ,0
Exp/Cntr=0.3,0.1

Chan Stop Cuts=-1
Use User Specified Reach Order=0
Composite Channel Slope=5