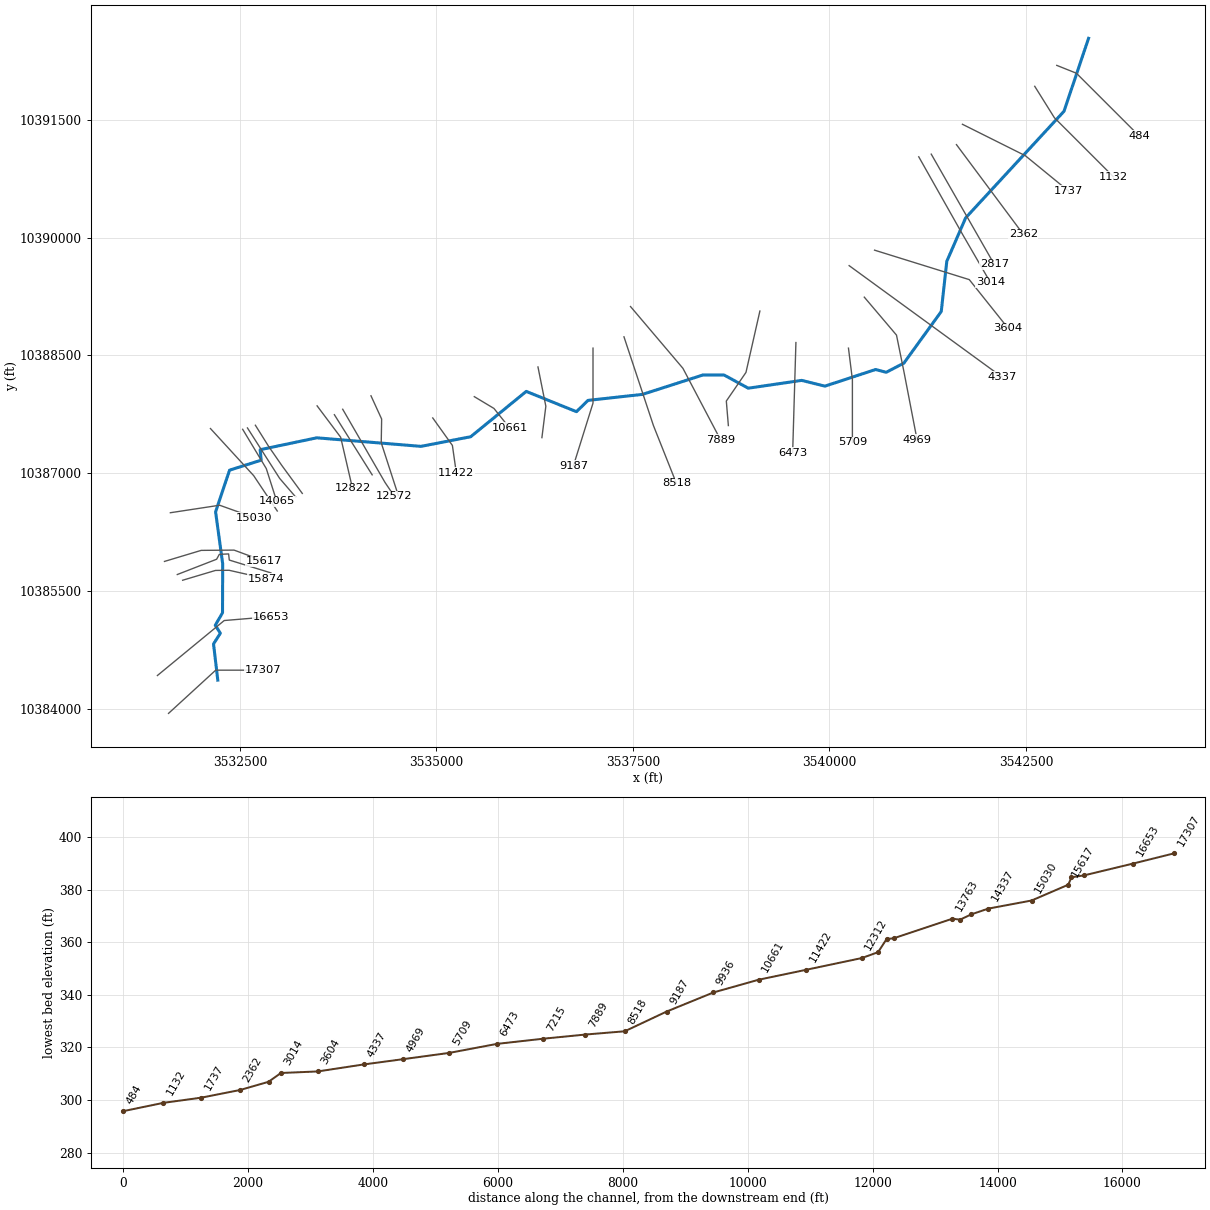
--- PEPPER BRANCH.prj (project) ---

Proj Title=PEPPER BRANCH Base Level Engineering
Current Plan=p01
Default Exp/Contr=0.3,0.1
English Units
Geom File=g01
Flow File=f01
Plan File=p01
BEGIN DESCRIPTION:
PEPPER BRANCH
END DESCRIPTION:

--- PEPPER BRANCH.p01 (plan) ---

Plan Title=Multiple Run
Short Identifier=Multiple
Geom File=g01
Flow File=f01
Subcritical Flow
K Sum by GR= 0
Std Step Tol= 0.01
Critical Tol= 0.01
Num of Std Step Trials= 20
Max Error Tol= 0.3
Flow Tol Ratio= 0.001
Split Flow NTrial= 30
Split Flow Tol= 0.02
Split Flow Ratio= 0.02
Log Output Level= 0
Friction Slope Method= 1
Unsteady Friction Slope Method= 2
Unsteady Bridges Friction Slope Method= 1
Parabolic Critical Depth
Global Vel Dist=  1 , 1 , 1
Global Log Level= 0
CheckData=True
Encroach Param= -1, 0, 0, 0
BEGIN DESCRIPTION:
Multiple Run
END DESCRIPTION:

--- PEPPER BRANCH.f01 (steady flow) ---

Flow Title=Multiple
Number of Profiles=7
Profile Names=10-year,25-year,50-year,1pct_min,100-year,1pct_plu,500-year
River Rch & RM= PEPPER BRANCH,Reach-1,17307
    1014    1399    1716    1536    2078    2810    3038
River Rch & RM= PEPPER BRANCH,Reach-1,14337
    1627    2307    2884    2626    3551    4803    5376
River Rch & RM= PEPPER BRANCH,Reach-1,8518
    1990    2843    3572    3265    4416    5972    6740
River Rch & RM= PEPPER BRANCH,Reach-1,4337
    2378    3424    4324    3972    5371    7264    8276
River Rch & RM= PEPPER BRANCH,Reach-1,1132
    2458    3544    4479    4118    5568    7531    8594
Boundary for River Rch & Prof#=PEPPER BRANCH,Reach-1,1
Up Type=0
Dn Type=3
Dn Slope=0.005
Boundary for River Rch & Prof#=PEPPER BRANCH,Reach-1,2
Up Type=0
Dn Type=3
Dn Slope=0.005
Boundary for River Rch & Prof#=PEPPER BRANCH,Reach-1,3
Up Type=0
Dn Type=3
Dn Slope=0.005
Boundary for River Rch & Prof#=PEPPER BRANCH,Reach-1,4
Up Type=0
Dn Type=3
Dn Slope=0.005
Boundary for River Rch & Prof#=PEPPER BRANCH,Reach-1,5
Up Type=0
Dn Type=3
Dn Slope=0.005
Boundary for River Rch & Prof#=PEPPER BRANCH,Reach-1,6
Up Type=0
Dn Type=3
Dn Slope=0.005
Boundary for River Rch & Prof#=PEPPER BRANCH,Reach-1,7
Up Type=0
Dn Type=3
Dn Slope=0.005

--- PEPPER BRANCH.g01 (geometry) ---

Geom Title=Existing Conditions

River Reach=PEPPER BRANCH,Reach-1
Reach XY= 30
      3532218.76     10384364.99      3532164.38     10384825.99
      3532251.67     10384962.26      3532186.37     10385062.08
      3532278.82     10385222.58      3532280.98     10385845.60
      3532190.61     10386507.84      3532368.76     10387037.97
      3532770.49     10387165.12      3532757.82     10387298.55
      3533477.64     10387449.94      3534804.27     10387341.08
      3535436.31     10387463.79      3536142.71     10388040.73
      3536781.87     10387782.72      3536928.88     10387926.62
      3537621.65     10388002.75      3538392.33     10388250.53
      3538660.97     10388248.90      3538966.95     10388081.66
      3539647.32     10388181.08      3539942.02     10388107.56
      3540588.07     10388319.83      3540721.58     10388284.03
      3540946.51     10388400.34      3541422.73     10389058.27
      3541492.87     10389696.46      3541733.15     10390250.63
      3542983.99     10391607.08      3543296.50     10392535.88

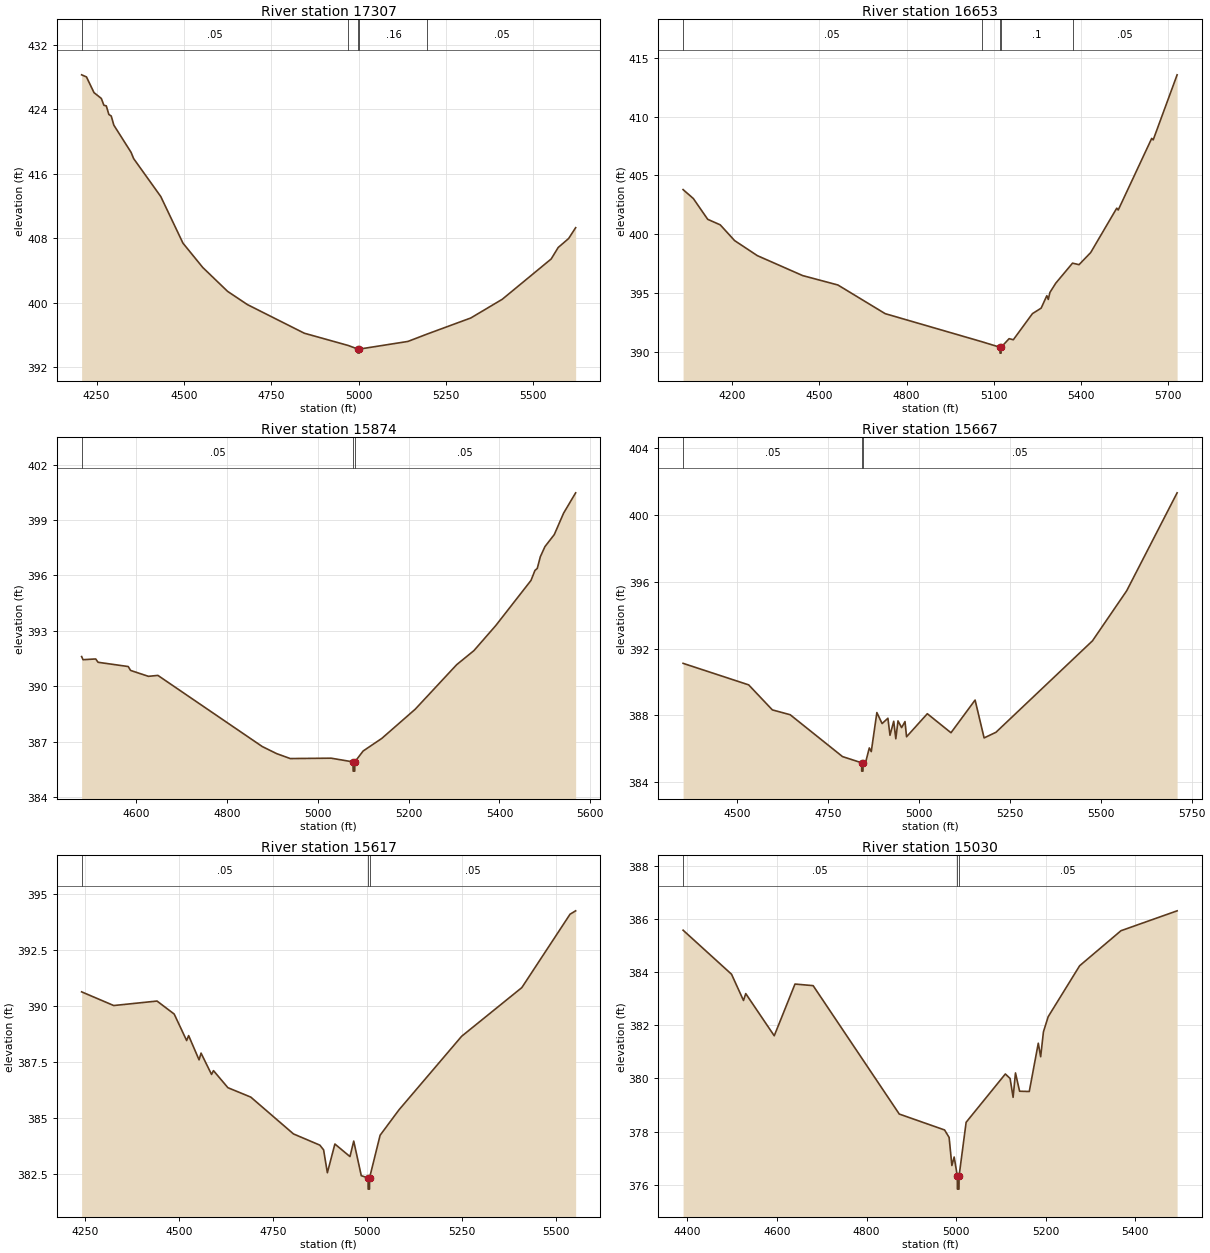
Type RM Length L Ch R = 1,17307,654,654,654
BEGIN DESCRIPTION:
PEPPER BRANCH 5 0
END DESCRIPTION:
XS GIS Cut Line= 3
      3531592.11     10383941.64      3532192.11     10384491.64
      3532792.07     10384491.64
#Sta/Elev= 30
  4207.3  428.26  4221.2  428.00  4242.8  426.05  4263.7  425.33  4271.1  424.48
  4277.9  424.41  4285.3  423.34  4292.1  423.15  4299.5  422.02  4348.8  418.65
  4356.2  417.87  4433.9  413.16  4497.4  407.38  4554.1  404.36  4625.1  401.40
  4681.8  399.76  4844.6  396.21  4970.2  394.69  4998.0  394.24  4998.2  393.74
  5001.7  393.74  5002.0  394.24  5141.2  395.19  5197.1  396.12  5321.2  398.10
  5411.2  400.42  5551.2  405.42  5571.2  406.84  5601.2  407.96  5621.2  409.30
#Mann=5,-1,0
  4207.3    0.05       0  4970.2    0.16       0  4998.0    0.07       0
  5002.0    0.16       0  5197.1    0.05       0
Bank Sta=4998,5002
Exp/Cntr=0.3,0.1

Type RM Length L Ch R = 1,16653,779,779,779
BEGIN DESCRIPTION:
PEPPER BRANCH 4 0
END DESCRIPTION:
XS GIS Cut Line= 3
      3531450.48     10384423.65      3532300.51     10385123.68
      3532898.76     10385173.53
#Sta/Elev= 30
  4030.4  403.79  4065.7  403.03  4115.2  401.26  4158.3  400.79  4207.8  399.45
  4286.0  398.17  4442.3  396.47  4563.6  395.67  4726.4  393.23  5058.2  390.85
  5121.8  390.37  5122.1  389.87  5125.6  389.87  5125.8  390.37  5153.2  391.10
  5167.8  391.01  5233.5  393.23  5263.6  393.70  5283.2  394.76  5288.2  394.44
  5293.7  395.03  5313.8  395.82  5371.7  397.53  5394.1  397.40  5434.2  398.43
  5524.0  402.21  5529.0  402.05  5644.4  408.15  5649.5  408.02  5731.9  413.56
#Mann=5,-1,0
  4030.4    0.05       0  5058.2     0.1       0  5121.8    0.03       0
  5125.8     0.1       0  5371.7    0.05       0
Bank Sta=5121.8,5125.8
Exp/Cntr=0.3,0.1

Type RM Length L Ch R = 1,15874,207,207,207
BEGIN DESCRIPTION:
PEPPER BRANCH 38 0
END DESCRIPTION:
XS GIS Cut Line= 4
      3531771.36     10385636.58      3532189.74     10385761.57
      3532363.35     10385763.31      3532827.90     10385657.57
#Sta/Elev= 30
  4480.8  391.61  4483.9  391.44  4511.8  391.48  4517.0  391.30  4583.3  391.07
  4588.5  390.86  4627.7  390.54  4648.6  390.59  4878.2  386.74  4909.5  386.36
  4939.8  386.09  5029.8  386.11  5077.8  385.91  5078.1  385.41  5081.6  385.41
  5081.8  385.91  5100.1  386.50  5141.1  387.18  5214.6  388.76  5305.8  391.17
  5343.7  391.93  5391.9  393.29  5469.3  395.73  5478.0  396.27  5483.1  396.38
  5489.8  397.01  5500.0  397.56  5520.5  398.21  5541.0  399.37  5567.5  400.47
#Mann=3,-1,0
  4480.8    0.05       0  5077.8    0.03       0  5081.8    0.05       0
Bank Sta=5077.8,5081.8
Exp/Cntr=0.3,0.1

Type RM Length L Ch R = 1,15667,50,50,50
BEGIN DESCRIPTION:
PEPPER BRANCH 37 0
END DESCRIPTION:
XS GIS Cut Line= 6
      3531703.60     10385709.48      3532203.63     10385903.94
      3532238.35     10385966.44      3532356.41     10385971.64
      3532365.09     10385893.52      3532894.62     10385730.32
#Sta/Elev= 30
  4351.2  391.12  4531.6  389.83  4596.7  388.33  4645.8  388.04  4789.8  385.53
  4842.3  385.16  4842.5  384.66  4846.0  384.66  4846.3  385.16  4853.9  385.24
  4863.4  386.05  4868.8  385.83  4884.2  388.17  4898.6  387.51  4914.6  387.83
  4920.3  386.81  4930.6  387.65  4936.3  386.60  4942.3  387.67  4952.3  387.27
  4961.6  387.63  4965.9  386.72  5023.0  388.10  5088.1  386.96  5154.4  388.92
  5179.2  386.65  5211.9  386.99  5477.3  392.47  5571.4  395.47  5710.1  401.34
#Mann=3,-1,0
  4351.2    0.05       0  4842.3    0.03       0  4846.3    0.05       0
Bank Sta=4842.3,4846.3
Exp/Cntr=0.3,0.1

Type RM Length L Ch R = 1,15617,587,587,587
BEGIN DESCRIPTION:
PEPPER BRANCH 36 0
END DESCRIPTION:
XS GIS Cut Line= 4
      3531540.42     10385876.15      3532007.45     10386016.78
      3532425.85     10386020.26      3532806.02     10385879.65
#Sta/Elev= 30
  4241.3  390.63  4326.6  390.02  4441.5  390.22  4487.1  389.64  4520.1  388.46
  4525.4  388.68  4553.1  387.60  4558.4  387.90  4586.2  386.95  4591.4  387.12
  4629.6  386.36  4690.4  385.94  4803.7  384.30  4873.7  383.80  4883.7  383.59
  4893.7  382.57  4913.7  383.85  4953.7  383.29  4963.7  383.98  4983.7  382.44
  5001.7  382.34  5002.0  381.84  5005.5  381.84  5005.7  382.34  5033.7  384.24
  5083.7  385.37  5250.1  388.65  5410.0  390.82  5538.0  394.09  5552.8  394.24
#Mann=3,-1,0
  4241.3    0.05       0  5001.7    0.03       0  5005.7    0.05       0
Bank Sta=5001.7,5005.7
Exp/Cntr=0.3,0.1

Type RM Length L Ch R = 1,15030,693,693,693
BEGIN DESCRIPTION:
PEPPER BRANCH 35 0
END DESCRIPTION:
XS GIS Cut Line= 3
      3531615.24     10386496.14      3532242.11     10386591.64
      3532682.95     10386433.64
#Sta/Elev= 30
  4390.7  385.59  4498.8  383.93  4525.5  382.94  4530.5  383.20  4594.1  381.61
  4640.4  383.56  4680.9  383.50  4873.1  378.66  4974.2  378.06  4984.3  377.78
  4990.5  376.72  4995.6  377.04  5002.6  376.33  5002.8  375.83  5006.3  375.83
  5006.6  376.33  5022.3  378.35  5109.8  380.17  5120.4  380.00  5127.1  379.29
  5132.4  380.21  5141.6  379.52  5163.2  379.51  5183.3  381.33  5188.6  380.82
  5194.8  381.76  5205.4  382.33  5275.6  384.25  5367.8  385.57  5493.1  386.32
#Mann=3,-1,0
  4390.7    0.05       0  5002.6   0.035       0  5006.6    0.05       0
Bank Sta=5002.6,5006.6
Exp/Cntr=0.3,0.1

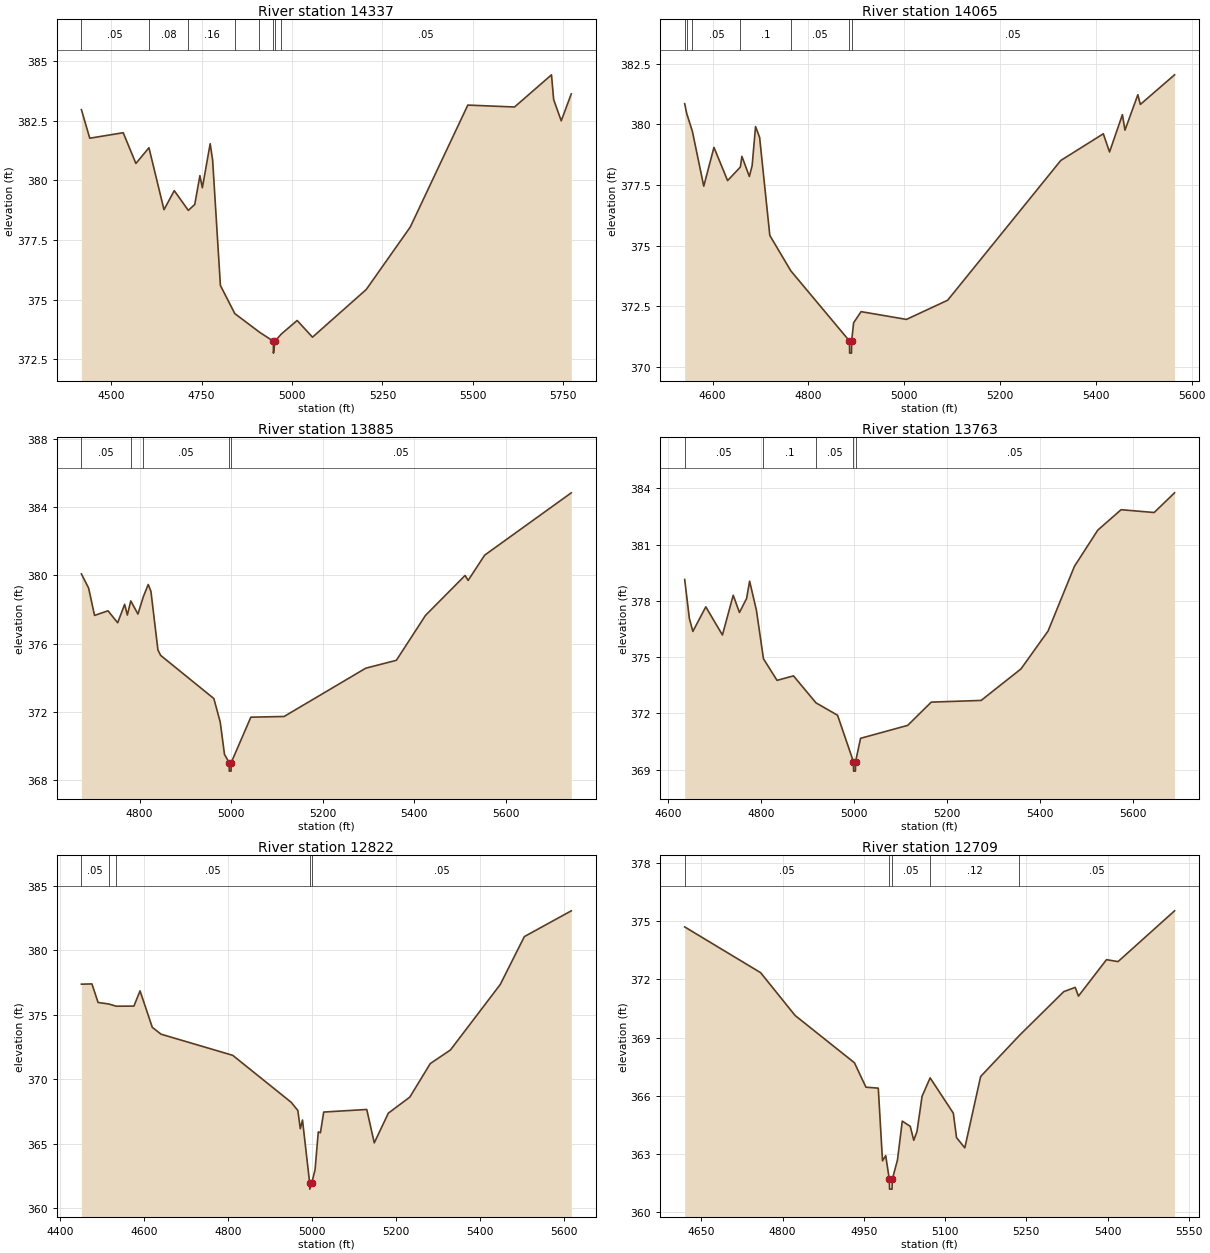
Type RM Length L Ch R = 1,14337,272,272,272
BEGIN DESCRIPTION:
PEPPER BRANCH 34 0
END DESCRIPTION:
XS GIS Cut Line= 3
      3532125.43     10387567.96      3532675.40     10386968.00
      3532975.39     10386518.02
#Sta/Elev= 30
  4417.5  382.97  4440.6  381.77  4533.1  382.00  4568.2  380.71  4604.3  381.37
  4645.9  378.77  4674.3  379.57  4713.2  378.74  4731.0  378.99  4745.2  380.20
  4752.0  379.69  4773.6  381.54  4780.4  380.85  4801.9  375.59  4841.7  374.41
  4909.9  373.63  4948.3  373.25  4948.6  372.75  4952.8  373.25  4970.2  373.55
  5014.1  374.12  5056.6  373.42  5205.2  375.42  5326.9  378.04  5486.1  383.16
  5615.3  383.08  5717.5  384.43  5723.5  383.39  5744.5  382.50  5772.2  383.63
#Mann=8,-1,0
  4417.5    0.05       0  4604.3    0.08       0  4713.2    0.16       0
  4841.7    0.05       0  4909.9     0.1       0  4948.3    0.03       0
  4952.8     0.1       0  4970.2    0.05       0
Bank Sta=4948.3,4952.8
Exp/Cntr=0.3,0.1

Type RM Length L Ch R = 1,14065,180,180,180
BEGIN DESCRIPTION:
PEPPER BRANCH 32 2
END DESCRIPTION:
XS GIS Cut Line= 3
      3532535.24     10387558.43      3532835.57     10387058.45
      3532969.26     10386640.04
#Sta/Elev= 30
  4541.8  380.85  4546.1  380.44  4557.9  379.71  4581.6  377.45  4602.9  379.05
  4631.4  377.68  4658.0  378.24  4661.2  378.68  4676.8  377.85  4682.6  378.30
  4689.7  379.91  4698.2  379.46  4719.5  375.42  4763.4  373.96  4885.8  371.07
  4886.1  370.57  4890.0  370.57  4890.3  371.07  4894.4  371.82  4910.0  372.28
  5004.7  371.96  5090.7  372.75  5326.8  378.51  5415.6  379.61  5428.6  378.86
  5455.5  380.40  5460.8  379.76  5487.7  381.22  5492.9  380.82  5564.3  382.04
#Mann=7,-1,0
  4541.8    0.05       0  4546.1    0.08       0  4557.9    0.05       0
  4658.0     0.1       0  4763.4    0.05       0  4885.8    0.04       0
  4890.3    0.05       0
Bank Sta=4885.8,4890.3
Exp/Cntr=0.3,0.1

Type RM Length L Ch R = 1,13885,122,122,122
BEGIN DESCRIPTION:
PEPPER BRANCH 32 3
END DESCRIPTION:
XS GIS Cut Line= 3
      3532595.98     10387575.82      3533005.71     10386933.45
      3533207.08     10386699.10
#Sta/Elev= 30
  4672.7  380.09  4688.5  379.26  4701.4  377.66  4730.8  377.93  4752.0  377.23
  4767.2  378.31  4773.1  377.68  4780.6  378.51  4796.3  377.74  4808.0  378.75
  4818.8  379.47  4824.7  379.07  4840.0  375.64  4845.9  375.32  4962.3  372.79
  4976.2  371.41  4985.5  369.52  4995.7  369.04  4996.0  368.54  4999.9  368.54
  5000.2  369.04  5043.1  371.70  5115.8  371.74  5294.4  374.57  5361.2  375.03
  5424.9  377.66  5511.5  380.00  5518.1  379.71  5554.3  381.19  5743.6  384.84
#Mann=5,-1,0
  4672.7    0.05       0  4780.6     0.1       0  4808.0    0.05       0
  4995.7    0.04       0  5000.2    0.05       0
Bank Sta=4995.7,5000.2
Exp/Cntr=0.3,0.1

Type RM Length L Ch R = 1,13763,941,941,941
BEGIN DESCRIPTION:
PEPPER BRANCH 33 0
END DESCRIPTION:
XS GIS Cut Line= 4
      3532696.89     10387610.09      3532864.00     10387343.15
      3533033.27     10387097.92      3533293.68     10386742.03
#Sta/Elev= 30
  4636.3  379.14  4646.3  377.07  4653.9  376.37  4681.7  377.68  4717.5  376.18
  4740.7  378.30  4754.1  377.38  4769.4  378.12  4776.0  379.05  4790.6  377.50
  4805.8  374.91  4835.0  373.76  4870.4  374.00  4918.8  372.56  4965.2  371.90
  4999.4  369.42  4999.7  368.92  5003.6  368.92  5003.9  369.42  5014.7  370.67
  5116.1  371.36  5166.8  372.60  5274.1  372.69  5359.8  374.37  5418.1  376.39
  5474.8  379.84  5525.0  381.77  5575.2  382.86  5646.3  382.71  5690.2  383.76
#Mann=5,-1,0
  4636.3    0.05       0  4805.8     0.1       0  4918.8    0.05       0
  4999.4   0.035       0  5003.9    0.05       0
Bank Sta=4999.4,5003.9
Exp/Cntr=0.3,0.1

Type RM Length L Ch R = 1,12822,113,113,113
BEGIN DESCRIPTION:
PEPPER BRANCH 32 1
END DESCRIPTION:
XS GIS Cut Line= 3
      3533482.10     10387856.84      3533782.07     10387456.88
      3533932.06     10386806.91
#Sta/Elev= 30
  4450.6  377.37  4475.7  377.39  4490.3  375.95  4516.0  375.83  4533.6  375.66
  4575.7  375.67  4590.3  376.85  4619.5  374.02  4640.3  373.49  4811.1  371.85
  4950.6  368.20  4966.2  367.57  4972.1  366.16  4977.3  366.83  4994.3  361.97
  4994.7  361.47  4999.6  361.97  5007.2  362.97  5014.9  365.91  5020.0  365.84
  5027.8  367.45  5130.4  367.65  5148.3  365.06  5181.7  367.36  5233.0  368.61
  5281.7  371.21  5329.6  372.26  5448.5  377.35  5505.8  381.06  5617.6  383.06
#Mann=5,-1,0
  4450.6    0.05       0  4516.0    0.08       0  4533.6    0.05       0
  4994.3   0.035       0  4999.6    0.05       0
Bank Sta=4994.3,4999.6
Exp/Cntr=0.3,0.1

Type RM Length L Ch R = 1,12709,137,137,137
BEGIN DESCRIPTION:
PEPPER BRANCH 32 0
END DESCRIPTION:
XS GIS Cut Line= 2
      3533701.91     10387744.19      3534182.80     10386978.59
#Sta/Elev= 30
  4619.4  374.71  4759.5  372.35  4823.2  370.14  4932.7  367.70  4953.9  366.44
  4976.7  366.39  4984.5  362.64  4990.4  362.91  4997.1  361.68  4997.5  361.18
  5002.1  361.18  5002.5  361.68  5012.1  362.68  5021.0  364.69  5035.7  364.42
  5042.2  363.70  5048.1  364.15  5057.5  365.97  5072.4  366.92  5115.2  365.10
  5121.1  363.84  5136.4  363.31  5165.6  366.99  5237.1  369.11  5319.0  371.37
  5340.2  371.59  5346.1  371.14  5397.9  373.02  5419.2  372.92  5523.5  375.54
#Mann=5,-1,0
  4619.4    0.05       0  4997.1    0.04       0  5002.5    0.05       0
  5072.4    0.12       0  5237.1    0.05       0
Bank Sta=4997.1,5002.5
Exp/Cntr=0.3,0.1

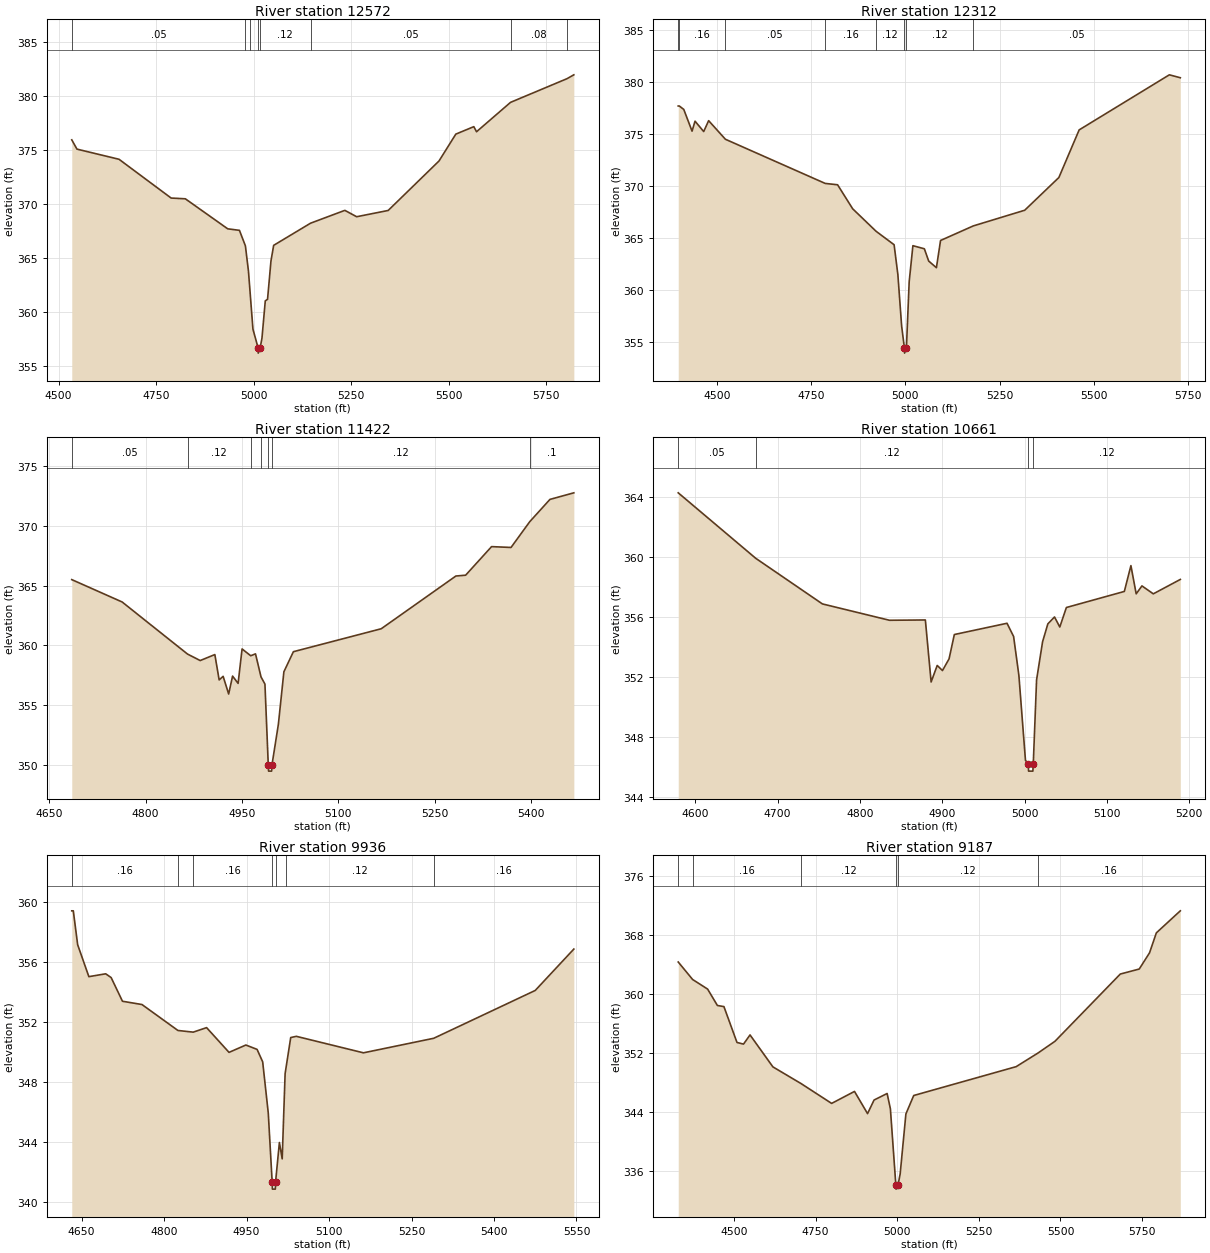
Type RM Length L Ch R = 1,12572,260,260,260
BEGIN DESCRIPTION:
PEPPER BRANCH 29 0
END DESCRIPTION:
XS GIS Cut Line= 3
      3533807.80     10387813.65      3534345.53     10386882.66
      3534463.39     10386707.31
#Sta/Elev= 30
  4533.9  375.93  4547.2  375.07  4655.0  374.13  4788.5  370.54  4824.9  370.47
  4933.5  367.69  4963.5  367.55  4978.8  366.11  4986.6  363.78  4991.2  361.63
  4998.1  358.40  5011.2  356.68  5011.6  356.18  5016.6  356.68  5021.2  357.56
  5029.7  361.02  5035.5  361.16  5044.3  364.72  5051.2  366.16  5145.6  368.21
  5233.6  369.40  5263.8  368.81  5344.6  369.39  5474.8  373.97  5517.9  376.46
  5564.0  377.15  5571.0  376.68  5658.1  379.40  5802.6  381.59  5820.3  381.95
#Mann=8,-1,0
  4533.9    0.05       0  4978.8    0.16       0  4991.2    0.12       0
  5011.2    0.07       0  5016.6    0.12       0  5145.6    0.05       0
  5658.1    0.08       0  5802.6    0.05       0
Bank Sta=5011.2,5016.6
Exp/Cntr=0.3,0.1

Type RM Length L Ch R = 1,12312,890,890,890
BEGIN DESCRIPTION:
PEPPER BRANCH 28 1
END DESCRIPTION:
XS GIS Cut Line= 4
      3534167.58     10387985.02      3534303.18     10387688.85
      3534297.97     10387386.77      3534515.18     10386716.24
#Sta/Elev= 30
  4397.2  377.73  4400.0  377.73  4411.9  377.40  4433.9  375.31  4441.8  376.27
  4464.8  375.27  4477.9  376.32  4522.4  374.53  4787.3  370.28  4820.2  370.15
  4860.2  367.84  4922.2  365.68  4970.2  364.38  4980.2  361.51  4990.2  356.56
  4997.5  354.45  4997.9  353.95  5002.9  354.45  5010.2  360.81  5020.1  364.29
  5050.5  363.99  5062.0  362.81  5082.5  362.17  5093.5  364.79  5180.3  366.19
  5316.9  367.70  5407.6  370.85  5461.4  375.43  5700.8  380.73  5729.9  380.45
#Mann=8,-1,0
  4397.2    0.05       0  4400.0    0.16       0  4522.4    0.05       0
  4787.3    0.16       0  4922.2    0.12       0  4997.5    0.07       0
  5002.9    0.12       0  5180.3    0.05       0
Bank Sta=4997.5,5002.9
Exp/Cntr=0.3,0.1

Type RM Length L Ch R = 1,11422,761,761,761
BEGIN DESCRIPTION:
PEPPER BRANCH 27 0
END DESCRIPTION:
XS GIS Cut Line= 3
      3534953.36     10387702.96      3535203.33     10387352.99
      3535253.07     10387004.80
#Sta/Elev= 30
  4685.0  365.51  4763.4  363.64  4865.3  359.28  4885.0  358.74  4907.8  359.24
  4914.5  357.12  4920.7  357.42  4929.3  355.94  4935.4  357.44  4944.0  356.83
  4950.2  359.71  4963.7  359.14  4971.1  359.30  4979.7  357.37  4985.8  356.77
  4991.0  349.99  4991.5  349.49  4996.2  349.49  4996.7  349.99  5006.7  353.40
  5015.3  357.80  5030.1  359.48  5166.9  361.40  5283.1  365.81  5298.3  365.88
  5338.7  368.27  5369.0  368.20  5398.2  370.36  5429.6  372.22  5466.8  372.77
#Mann=7,-1,0
  4685.0    0.05       0  4865.3    0.12       0  4963.7    0.16       0
  4979.7    0.12       0  4991.0    0.07       0  4996.7    0.12       0
  5398.2     0.1       0
Bank Sta=4991,4996.7
Exp/Cntr=0.3,0.1

Type RM Length L Ch R = 1,10661,725,725,725
BEGIN DESCRIPTION:
PEPPER BRANCH 26 0
END DESCRIPTION:
XS GIS Cut Line= 3
      3535482.09     10387973.85      3535732.11     10387823.84
      3535930.97     10387575.27
#Sta/Elev= 30
  4579.3  364.25  4673.4  359.89  4754.4  356.85  4835.9  355.76  4879.5  355.78
  4886.5  351.65  4893.9  352.75  4900.3  352.41  4908.3  353.19  4914.7  354.81
  4978.7  355.56  4986.7  354.68  4993.1  352.09  5001.1  346.43  5004.4  346.21
  5004.9  345.71  5010.1  345.71  5010.6  346.21  5014.6  351.79  5021.9  354.33
  5028.3  355.52  5036.4  355.98  5042.8  355.31  5050.8  356.61  5121.2  357.68
  5129.2  359.40  5135.6  357.52  5142.6  358.05  5156.4  357.52  5189.2  358.48
#Mann=4,-1,0
  4579.3    0.05       0  4673.4    0.12       0  5004.4    0.07       0
  5010.6    0.12       0
Bank Sta=5004.4,5010.6
Exp/Cntr=0.3,0.1

Type RM Length L Ch R = 1,9936,749,749,749
BEGIN DESCRIPTION:
PEPPER BRANCH 25 0
END DESCRIPTION:
XS GIS Cut Line= 3
      3536292.10     10388352.10      3536392.11     10387852.06
      3536342.10     10387452.01
#Sta/Elev= 30
  4632.1  359.42  4634.9  359.42  4642.8  357.16  4663.2  355.03  4693.8  355.22
  4703.7  354.97  4724.3  353.39  4759.8  353.17  4825.2  351.44  4853.0  351.33
  4877.3  351.63  4918.1  349.98  4948.7  350.47  4969.1  350.18  4979.3  349.35
  4989.5  345.92  4996.5  341.36  4997.0  340.86  5002.3  340.86  5002.8  341.36
  5009.7  343.97  5014.8  342.88  5020.1  348.56  5022.5  349.13  5030.3  350.97
  5040.5  351.05  5162.6  349.95  5290.4  350.92  5475.0  354.11  5545.2  356.87
#Mann=7,-1,0
  4632.1    0.16       0  4825.2    0.12       0  4853.0    0.16       0
  4996.5    0.07       0  5002.8    0.16       0  5022.5    0.12       0
  5290.4    0.16       0
Bank Sta=4996.5,5002.8
Exp/Cntr=0.3,0.1

Type RM Length L Ch R = 1,9187,669,669,669
BEGIN DESCRIPTION:
PEPPER BRANCH 23 0
END DESCRIPTION:
XS GIS Cut Line= 3
      3536992.11     10388591.64      3536992.11     10387891.64
      3536742.09     10387091.60
#Sta/Elev= 30
  4329.0  364.31  4373.2  361.94  4419.0  360.65  4449.0  358.43  4469.0  358.28
  4509.0  353.43  4529.0  353.21  4549.0  354.45  4619.0  350.13  4705.4  347.87
  4799.0  345.19  4869.0  346.81  4909.0  343.81  4929.0  345.65  4969.0  346.53
  4979.0  344.46  4995.8  334.10  4996.3  333.60  5002.2  334.10  5009.0  335.69
  5026.5  343.77  5050.5  346.26  5364.3  350.16  5431.8  352.02  5483.2  353.59
  5683.3  362.68  5741.4  363.36  5772.9  365.55  5793.8  368.25  5867.2  371.23
#Mann=6,-1,0
  4329.0    0.05       0  4373.2    0.16       0  4705.4    0.12       0
  4995.8    0.07       0  5002.2    0.12       0  5431.8    0.16       0
Bank Sta=4995.8,5002.2
Exp/Cntr=0.3,0.1

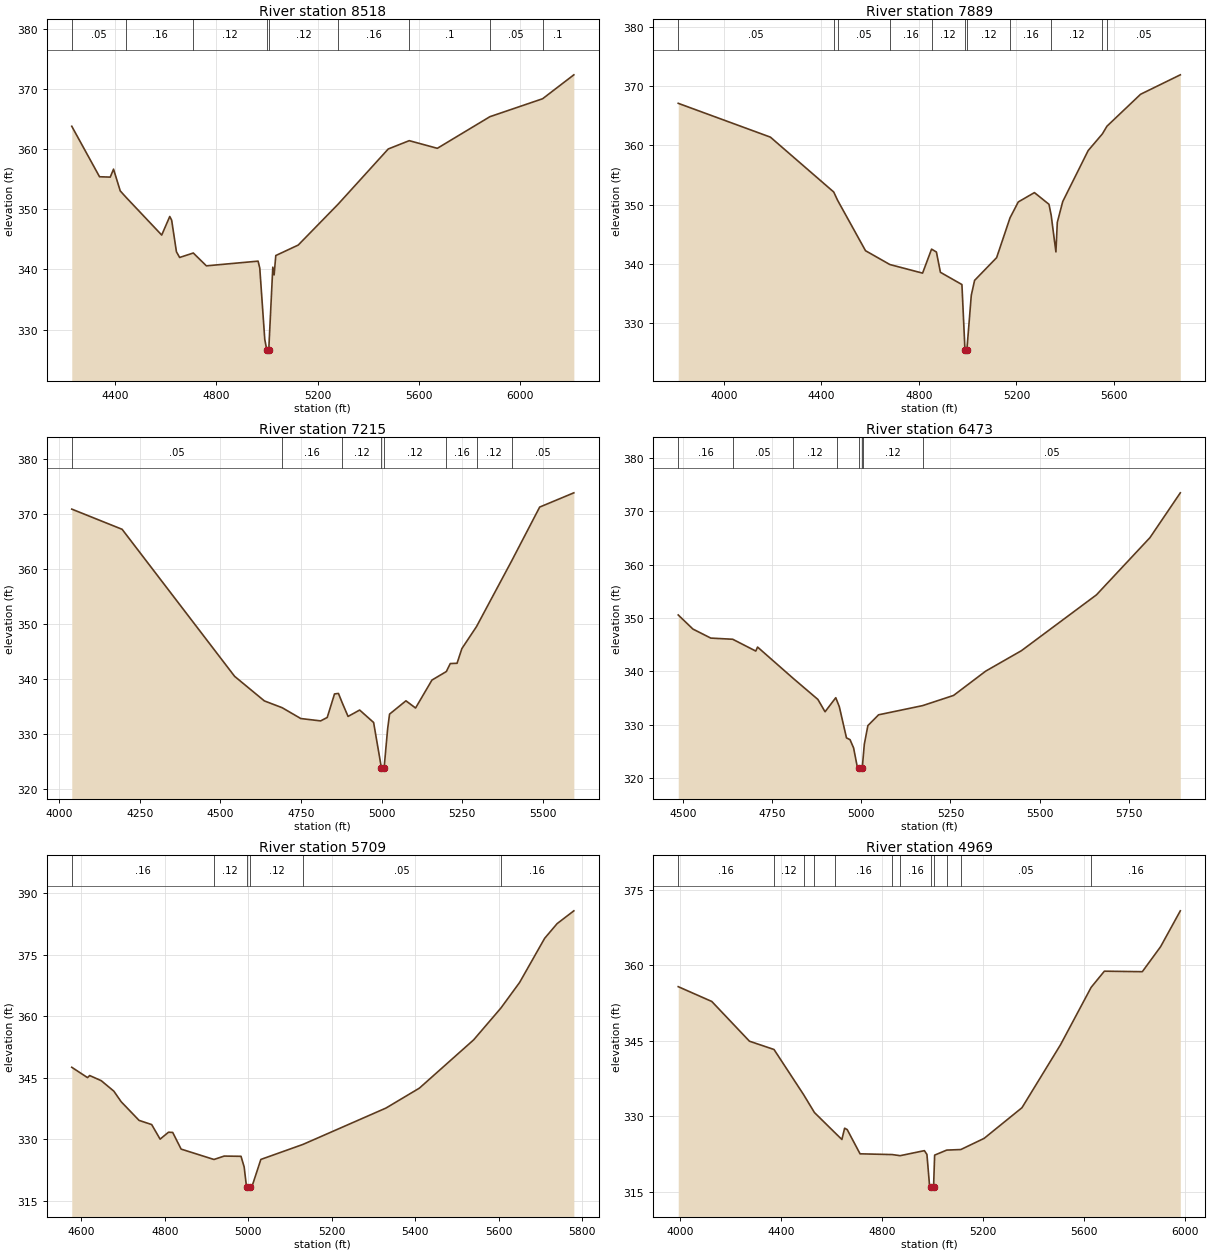
Type RM Length L Ch R = 1,8518,629,629,629
BEGIN DESCRIPTION:
PEPPER BRANCH 20 0
END DESCRIPTION:
XS GIS Cut Line= 3
      3537386.08     10388735.71      3537761.07     10387605.52
      3538052.76     10386871.10
#Sta/Elev= 30
  4229.7  363.77  4339.3  355.39  4381.5  355.33  4394.5  356.65  4420.9  353.05
  4441.8  352.07  4584.6  345.71  4616.3  348.79  4623.8  348.19  4642.7  342.93
  4655.4  341.99  4709.2  342.73  4760.8  340.60  4964.8  341.38  4971.5  340.23
  4991.2  328.40  4999.3  326.61  4999.8  326.11  5006.9  326.61  5022.9  340.38
  5028.1  339.09  5034.7  342.31  5123.2  344.05  5280.7  350.84  5478.4  360.00
  5561.2  361.38  5672.1  360.11  5879.5  365.36  6087.5  368.34  6210.7  372.31
#Mann=9,-1,0
  4229.7    0.05       0  4441.8    0.16       0  4709.2    0.12       0
  4999.3    0.07       0  5006.9    0.12       0  5280.7    0.16       0
  5561.2     0.1       0  5879.5    0.05       0  6087.5     0.1       0
Bank Sta=4999.3,5006.9
Exp/Cntr=0.3,0.1

Type RM Length L Ch R = 1,7889,674,674,674
BEGIN DESCRIPTION:
PEPPER BRANCH 2 0
END DESCRIPTION:
XS GIS Cut Line= 3
      3537469.40     10389121.16      3538136.07     10388334.68
      3538614.33     10387424.96
#Sta/Elev= 30
  3813.2  367.12  4191.2  361.40  4450.8  352.12  4466.3  350.75  4581.2  342.19
  4681.2  339.85  4815.2  338.40  4852.0  342.46  4871.9  341.97  4888.3  338.54
  4976.5  336.47  4989.0  325.37  4989.5  324.87  4996.7  325.37  5014.9  334.66
  5028.4  337.17  5118.8  341.02  5173.7  347.75  5207.6  350.44  5273.8  352.02
  5333.5  350.04  5342.5  348.19  5361.9  341.99  5367.6  346.99  5389.9  350.51
  5494.2  359.13  5552.6  361.96  5571.2  363.25  5709.0  368.65  5872.0  371.94
#Mann=11,-1,0
  3813.2    0.05       0  4450.8    0.16       0  4466.3    0.05       0
  4681.2    0.16       0  4852.0    0.12       0  4989.0    0.07       0
  4996.7    0.12       0  5173.7    0.16       0  5342.5    0.12       0
  5552.6    0.16       0  5571.2    0.05       0
Bank Sta=4989,4996.7
Exp/Cntr=0.3,0.1

Type RM Length L Ch R = 1,7215,742,742,742
BEGIN DESCRIPTION:
PEPPER BRANCH 19 0
END DESCRIPTION:
XS GIS Cut Line= 4
      3539115.25     10389063.89      3538938.16     10388282.60
      3538688.16     10387918.02      3538714.15     10387606.07
#Sta/Elev= 30
  4039.5  370.91  4195.6  367.24  4544.2  340.52  4636.5  336.05  4691.5  334.82
  4749.3  332.85  4810.8  332.42  4831.3  333.04  4853.9  337.32  4866.1  337.41
  4878.0  335.68  4895.9  333.23  4931.8  334.39  4975.1  332.13  4999.5  323.79
  5000.0  323.29  5007.5  323.79  5018.4  330.89  5024.5  333.65  5075.3  336.07
  5105.1  334.76  5155.9  339.84  5200.5  341.39  5212.7  342.84  5233.7  342.89
  5248.6  345.55  5294.0  349.56  5402.9  361.49  5489.8  371.28  5595.7  373.87
#Mann=8,-1,0
  4039.5    0.05       0  4691.5    0.16       0  4878.0    0.12       0
  4999.5    0.07       0  5007.5    0.12       0  5200.5    0.16       0
  5294.0    0.12       0  5402.9    0.05       0
Bank Sta=4999.5,5007.5
Exp/Cntr=0.3,0.1

Type RM Length L Ch R = 1,6473,764,764,764
BEGIN DESCRIPTION:
PEPPER BRANCH 18 1
END DESCRIPTION:
XS GIS Cut Line= 2
      3539573.57     10388662.81      3539531.91     10387256.63
#Sta/Elev= 30
  4487.4  350.57  4528.6  347.93  4578.6  346.24  4640.1  346.02  4704.7  343.81
  4709.7  344.56  4808.9  338.73  4878.7  334.75  4898.8  332.44  4928.8  335.07
  4933.2  334.33  4938.8  333.38  4958.8  327.55  4968.8  327.21  4978.8  325.66
  4988.8  322.21  4994.6  321.82  4995.1  321.32  5002.9  321.82  5006.4  324.51
  5008.8  326.36  5018.8  329.85  5048.8  331.87  5172.2  333.59  5258.9  335.50
  5348.9  340.05  5449.0  343.88  5659.1  354.33  5809.2  365.06  5894.2  373.45
#Mann=8,-1,0
  4487.4    0.16       0  4640.1    0.05       0  4808.9    0.12       0
  4933.2    0.16       0  4994.6    0.07       0  5002.9    0.16       0
  5006.4    0.12       0  5172.2    0.05       0
Bank Sta=4994.6,5002.9
Exp/Cntr=0.3,0.1

Type RM Length L Ch R = 1,5709,740,740,740
BEGIN DESCRIPTION:
PEPPER BRANCH 16 0
END DESCRIPTION:
XS GIS Cut Line= 3
      3540242.10     10388591.67      3540292.11     10388191.64
      3540292.11     10387391.68
#Sta/Elev= 30
  4576.7  347.56  4614.5  345.04  4619.6  345.55  4647.3  344.30  4677.5  341.75
  4695.1  339.17  4738.0  334.63  4768.2  333.61  4788.4  330.06  4808.5  331.75
  4818.6  331.69  4838.7  327.64  4917.4  325.11  4942.0  325.94  4982.3  325.88
  4989.8  323.28  4995.5  318.39  4996.0  317.89  5004.1  318.39  5009.8  318.92
  5029.8  325.12  5130.8  328.78  5329.8  337.64  5409.8  342.49  5539.8  354.25
  5604.8  361.96  5649.8  368.21  5709.8  378.96  5739.8  382.55  5779.8  385.66
#Mann=6,-1,0
  4576.7    0.16       0  4917.4    0.12       0  4995.5    0.07       0
  5004.1    0.12       0  5130.8    0.05       0  5604.8    0.16       0
Bank Sta=4995.5,5004.1
Exp/Cntr=0.3,0.1

Type RM Length L Ch R = 1,4969,632,632,632
BEGIN DESCRIPTION:
PEPPER BRANCH 15 0
END DESCRIPTION:
XS GIS Cut Line= 4
      3540443.39     10389240.90      3540853.10     10388757.65
      3540948.57     10388287.81      3541114.92     10387424.89
#Sta/Elev= 30
  3991.2  355.75  4124.3  352.81  4273.7  344.91  4371.2  343.26  4488.5  334.29
  4531.5  330.73  4613.0  326.71  4640.4  325.37  4651.3  327.61  4661.5  327.34
  4712.5  322.52  4840.1  322.37  4871.7  322.15  4967.6  323.15  4977.8  322.40
  4988.0  316.33  4995.5  316.00  4996.0  315.50  5004.2  316.00  5008.4  322.26
  5056.2  323.26  5112.3  323.37  5204.7  325.59  5354.9  331.69  5507.7  344.20
  5629.3  355.62  5681.7  358.83  5832.3  358.73  5904.8  363.70  5983.0  370.83
#Mann=12,-1,0
  3991.2    0.16       0  4371.2    0.12       0  4488.5    0.16       0
  4531.5    0.12       0  4613.0    0.16       0  4840.1    0.12       0
  4871.7    0.16       0  4995.5    0.07       0  5004.2    0.16       0
  5056.2    0.07       0  5112.3    0.05       0  5629.3    0.16       0
Bank Sta=4995.5,5004.2
Exp/Cntr=0.3,0.1

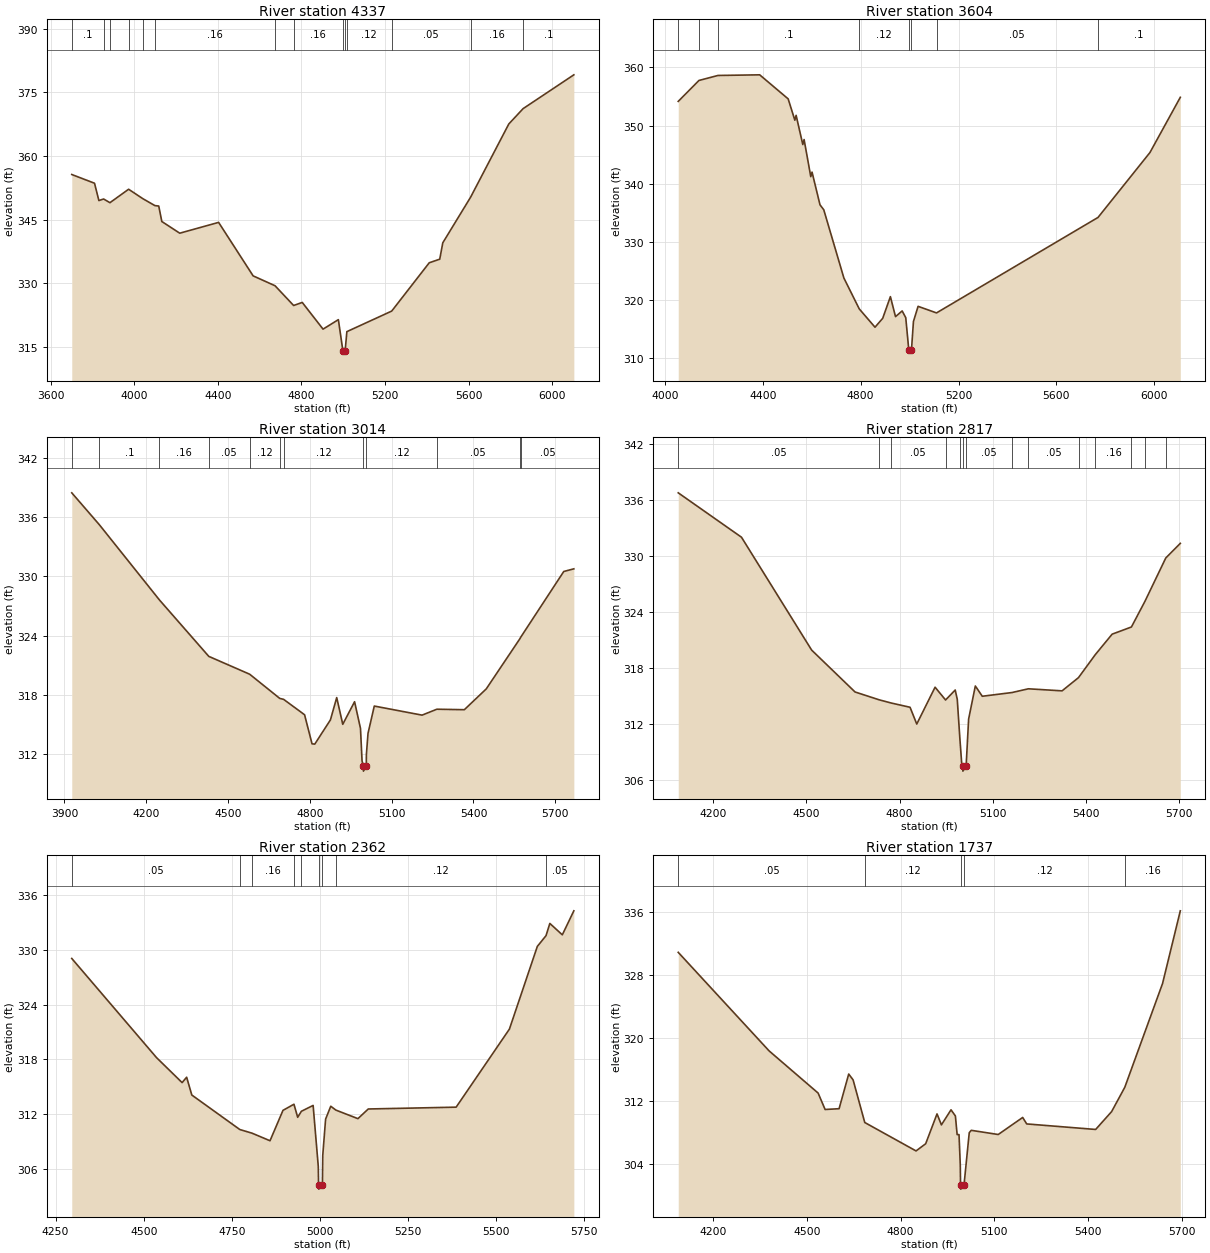
Type RM Length L Ch R = 1,4337,733,733,733
BEGIN DESCRIPTION:
PEPPER BRANCH 13 0
END DESCRIPTION:
XS GIS Cut Line= 2
      3540250.70     10389641.95      3542192.45     10388225.98
#Sta/Elev= 30
  3700.7  355.64  3809.6  353.58  3830.5  349.49  3853.1  349.86  3883.4  348.99
  3972.8  352.16  4041.4  349.92  4098.7  348.30  4117.0  348.20  4131.7  344.55
  4217.5  341.79  4403.6  344.34  4568.8  331.72  4673.7  329.39  4762.6  324.73
  4803.9  325.45  4903.5  319.15  4976.8  321.39  4998.6  313.99  4999.1  313.49
  5009.1  313.99  5017.5  318.56  5232.1  323.41  5411.8  334.81  5462.0  335.66
  5476.6  339.52  5609.8  350.29  5792.6  367.56  5861.0  371.18  6103.9  379.16
#Mann=14,-1,0
  3700.7     0.1       0  3853.1    0.16       0  3883.4    0.05       0
  3972.8    0.16       0  4041.4    0.05       0  4098.7    0.16       0
  4673.7    0.12       0  4762.6    0.16       0  4998.6    0.07       0
  5009.1    0.16       0  5017.5    0.12       0  5232.1    0.05       0
  5609.8    0.16       0  5861.0     0.1       0
Bank Sta=4998.6,5009.1
Exp/Cntr=0.3,0.1

Type RM Length L Ch R = 1,3604,590,590,590
BEGIN DESCRIPTION:
PEPPER BRANCH 18 0
END DESCRIPTION:
XS GIS Cut Line= 3
      3540574.20     10389838.94      3541779.05     10389463.94
      3542271.80     10388846.27
#Sta/Elev= 30
  4054.4  354.16  4139.1  357.76  4216.7  358.62  4387.3  358.73  4503.7  354.59
  4531.0  350.92  4536.2  351.76  4563.5  346.73  4568.8  347.59  4596.1  341.21
  4601.3  341.99  4633.8  336.36  4649.2  335.51  4731.4  323.77  4794.2  318.45
  4858.6  315.30  4890.1  316.83  4921.5  320.56  4942.4  317.12  4969.6  318.10
  4984.3  316.94  4996.8  311.34  4997.3  310.84  5007.6  311.34  5015.7  316.28
  5034.7  318.89  5110.0  317.76  5770.1  334.19  5982.3  345.36  6106.4  354.86
#Mann=8,-1,0
  4054.4     0.1       0  4139.1    0.16       0  4216.7     0.1       0
  4794.2    0.12       0  4996.8    0.07       0  5007.6    0.12       0
  5110.0    0.05       0  5770.1     0.1       0
Bank Sta=4996.8,5007.6
Exp/Cntr=0.3,0.1

Type RM Length L Ch R = 1,3014,197,197,197
BEGIN DESCRIPTION:
PEPPER BRANCH 3 0
END DESCRIPTION:
XS GIS Cut Line= 3
      3541136.23     10391027.79      3541695.61     10390036.60
      3542047.56     10389427.97
#Sta/Elev= 30
  3926.8  338.48  4027.8  335.25  4248.4  327.61  4429.3  321.89  4579.2  320.08
  4689.4  317.63  4703.7  317.53  4780.5  315.97  4807.9  313.02  4818.0  312.99
  4875.4  315.45  4898.4  317.71  4920.6  315.00  4963.9  317.29  4985.6  314.58
  4991.3  311.30  4996.0  310.75  4996.5  310.25  5006.9  310.75  5007.2  311.92
  5013.2  314.08  5036.2  316.85  5211.4  315.93  5265.7  316.53  5366.4  316.48
  5446.8  318.59  5569.2  323.64  5574.3  323.88  5731.0  330.50  5768.0  330.77
#Mann=12,-1,0
  3926.8    0.05       0  4027.8     0.1       0  4248.4    0.16       0
  4429.3    0.05       0  4579.2    0.12       0  4689.4     0.1       0
  4703.7    0.12       0  4996.0    0.07       0  5006.9    0.12       0
  5265.7    0.05       0  5569.2    0.16       0  5574.3    0.05       0
Bank Sta=4996,5006.9
Exp/Cntr=0.3,0.1

Type RM Length L Ch R = 1,2817,455,455,455
BEGIN DESCRIPTION:
PEPPER BRANCH 7 0
END DESCRIPTION:
XS GIS Cut Line= 2
      3541295.08     10391061.64      3542097.14     10389658.04
#Sta/Elev= 30
  4087.1  336.76  4290.7  332.00  4516.7  319.89  4656.4  315.40  4734.0  314.56
  4772.3  314.22  4833.5  313.76  4855.1  311.96  4914.1  315.91  4947.9  314.54
  4978.9  315.61  4985.5  314.62  4993.5  310.61  5000.5  307.42  5003.1  307.41
  5003.6  306.91  5014.0  307.41  5022.1  312.49  5043.7  316.04  5066.1  314.94
  5161.9  315.34  5214.6  315.74  5323.0  315.52  5375.9  316.94  5430.1  319.41
  5484.2  321.60  5546.3  322.37  5589.8  325.12  5656.9  329.77  5703.7  331.34
#Mann=14,-1,0
  4087.1    0.05       0  4734.0     0.1       0  4772.3    0.05       0
  4947.9     0.1       0  4993.5    0.05       0  5003.1    0.04       0
  5014.0    0.05       0  5161.9    0.12       0  5214.6    0.05       0
  5375.9    0.12       0  5430.1    0.16       0  5546.3    0.05       0
  5589.8    0.16       0  5656.9    0.05       0
Bank Sta=5003.1,5014
Exp/Cntr=0.3,0.1

Type RM Length L Ch R = 1,2362,625,625,625
BEGIN DESCRIPTION:
PEPPER BRANCH 8 0
END DESCRIPTION:
XS GIS Cut Line= 2
      3541615.87     10391182.68      3542466.55     10390040.33
#Sta/Elev= 30
  4295.9  329.06  4536.3  318.20  4608.9  315.46  4621.8  316.05  4636.4  314.10
  4772.6  310.32  4807.3  309.92  4858.3  309.09  4895.1  312.42  4926.2  313.09
  4936.8  311.66  4947.3  312.32  4980.6  312.96  4995.2  306.28  4996.0  304.29
  4996.5  303.79  5006.9  304.29  5007.9  307.48  5016.0  311.46  5030.6  312.87
  5045.1  312.45  5107.7  311.51  5137.0  312.57  5386.3  312.77  5537.4  321.32
  5616.6  330.38  5641.3  331.56  5652.1  332.90  5687.5  331.65  5720.2  334.28
#Mann=9,-1,0
  4295.9    0.05       0  4772.6     0.1       0  4807.3    0.16       0
  4926.2    0.12       0  4947.3    0.16       0  4996.0    0.07       0
  5006.9    0.16       0  5045.1    0.12       0  5641.3    0.05       0
Bank Sta=4996,5006.9
Exp/Cntr=0.3,0.1

Type RM Length L Ch R = 1,1737,605,605,605
BEGIN DESCRIPTION:
PEPPER BRANCH 6 0
END DESCRIPTION:
XS GIS Cut Line= 3
      3541692.15     10391441.62      3542492.11     10391041.64
      3543042.10     10390591.65
#Sta/Elev= 30
  4089.2  330.86  4379.8  318.37  4536.4  313.03  4558.7  310.95  4603.4  311.05
  4634.2  315.44  4648.2  314.70  4685.5  309.30  4849.4  305.70  4880.2  306.61
  4916.5  310.39  4930.5  309.00  4961.2  310.91  4975.2  310.13  4980.8  307.77
  4986.8  307.77  4990.8  303.94  4991.7  301.36  4992.2  300.86  5002.7  301.36
  5019.5  308.01  5025.9  308.31  5112.1  307.78  5190.3  309.94  5203.2  309.12
  5423.6  308.42  5474.6  310.68  5516.7  313.76  5637.5  326.92  5694.2  336.12
#Mann=5,-1,0
  4089.2    0.05       0  4685.5    0.12       0  4991.7    0.07       0
  5002.7    0.12       0  5516.7    0.16       0
Bank Sta=4991.7,5002.7
Exp/Cntr=0.3,0.1

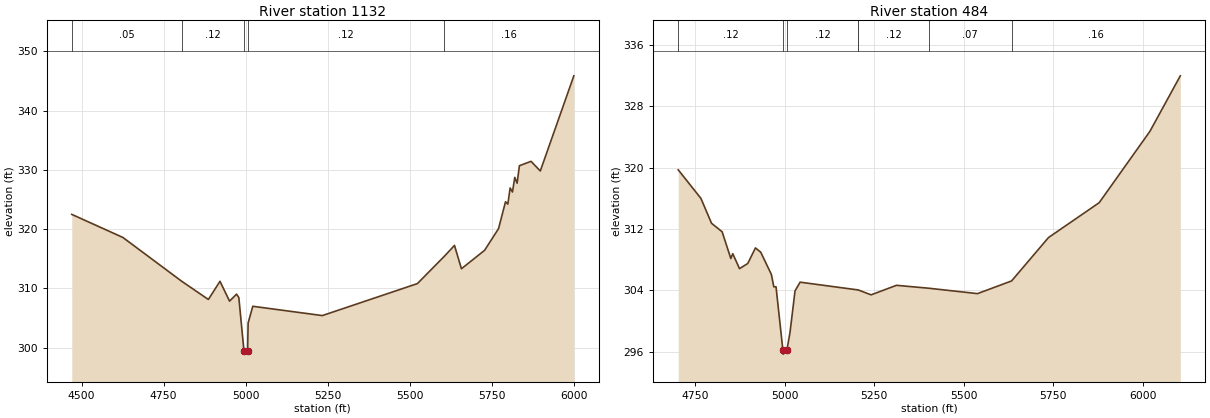
Type RM Length L Ch R = 1,1132,648,648,648
BEGIN DESCRIPTION:
PEPPER BRANCH 21 0
END DESCRIPTION:
XS GIS Cut Line= 3
      3542611.91     10391924.95      3542861.90     10391524.98
      3543611.03     10390775.84
#Sta/Elev= 30
  4469.8  322.49  4625.8  318.59  4805.7  311.17  4886.4  308.12  4921.8  311.19
  4951.0  307.84  4972.3  309.02  4979.3  308.43  4995.0  299.39  4995.5  298.89
  5006.0  299.39  5007.6  304.14  5021.8  306.97  5233.9  305.40  5523.8  310.80
  5605.9  315.41  5636.9  317.25  5658.1  313.31  5728.9  316.43  5771.3  320.09
  5792.5  324.62  5799.6  324.23  5806.6  326.95  5813.7  326.27  5820.8  328.74
  5827.9  327.76  5834.9  330.71  5870.3  331.45  5898.6  329.82  6000.9  345.89
#Mann=5,-1,0
  4469.8    0.05       0  4805.7    0.12       0  4995.0    0.07       0
  5006.0    0.12       0  5605.9    0.16       0
Bank Sta=4995,5006
Exp/Cntr=0.3,0.1

Type RM Length L Ch R = 1,484,0,0,0
BEGIN DESCRIPTION:
PEPPER BRANCH 1 0
END DESCRIPTION:
XS GIS Cut Line= 3
      3542892.11     10392191.64      3543142.11     10392091.64
      3543942.09     10391291.66
#Sta/Elev= 30
  4703.5  319.71  4766.8  315.99  4796.4  312.75  4826.0  311.64  4850.2  308.16
  4855.6  308.79  4874.5  306.84  4897.4  307.51  4918.9  309.54  4933.7  308.98
  4963.3  306.09  4970.1  304.48  4976.3  304.48  4995.5  296.21  4996.0  295.71
  5006.5  296.21  5015.2  298.50  5029.3  303.94  5043.5  305.08  5205.0  304.07
  5205.4  304.07  5241.5  303.43  5312.2  304.67  5402.5  304.29  5538.4  303.59
  5633.4  305.24  5736.4  310.89  5877.8  315.43  6019.3  324.72  6104.1  331.95
#Mann=7,-1,0
  4703.5    0.12       0  4995.5    0.07       0  5006.5    0.12       0
  5205.0    0.05       0  5205.4    0.12       0  5402.5    0.07       0
  5633.4    0.16       0
Bank Sta=4995.5,5006.5
Exp/Cntr=0.3,0.1

Chan Stop Cuts=-1