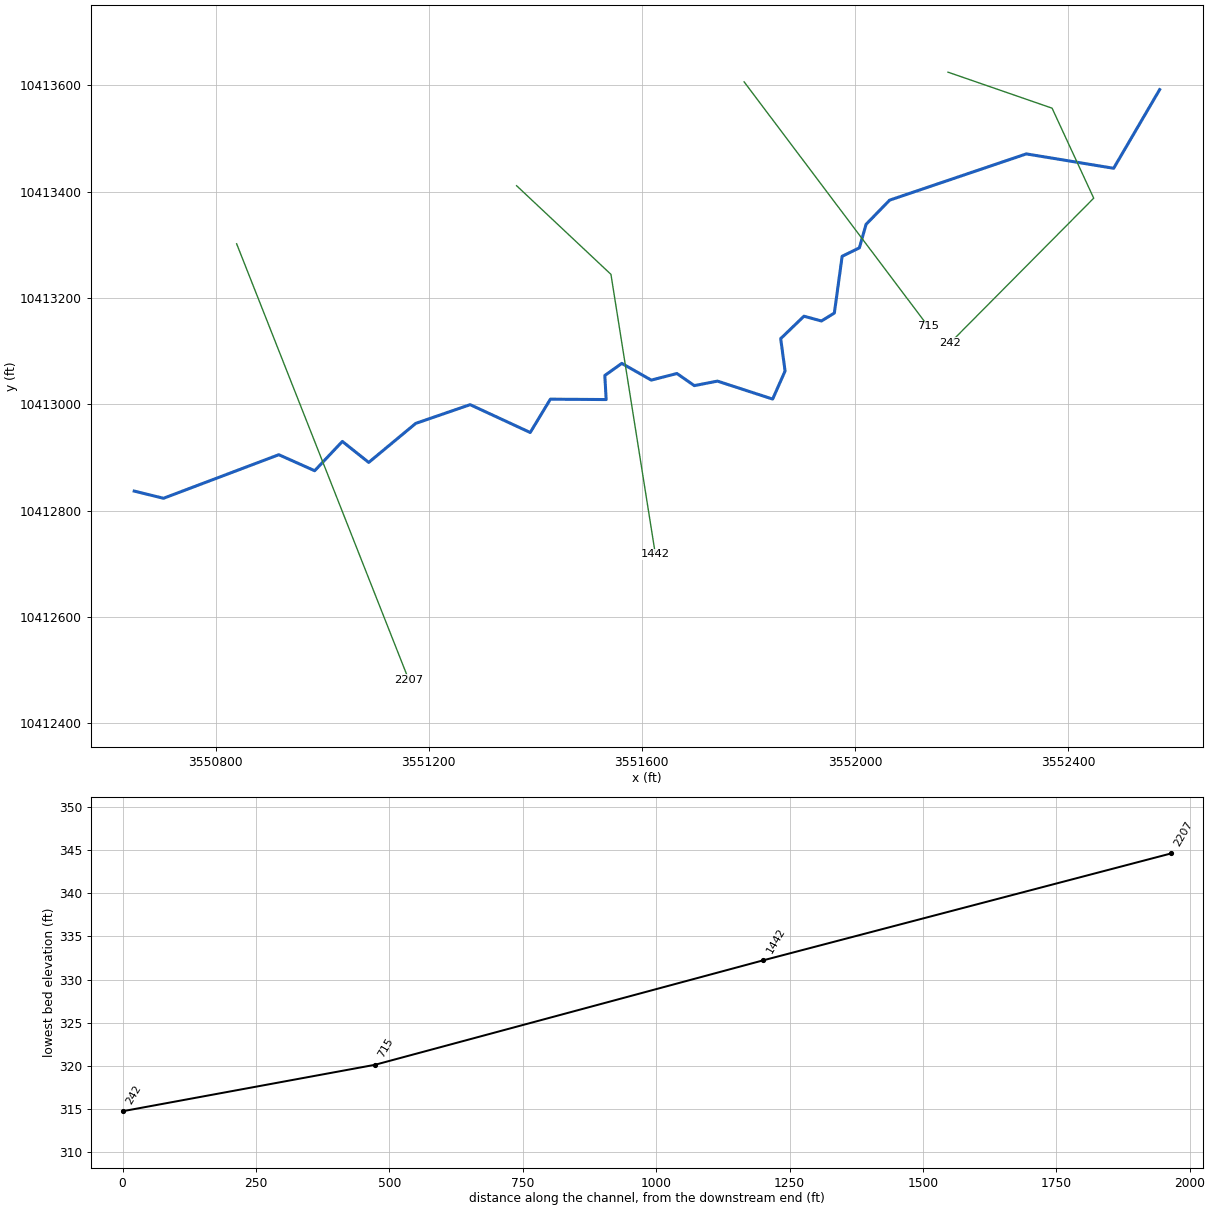
--- RED OAK CR TRIB 1.prj (project) ---

Proj Title=RED OAK CR TRIB 1 Base Level Engineering
Current Plan=p01
Default Exp/Contr=0.3,0.1
English Units
Geom File=g01
Flow File=f01
Plan File=p01
BEGIN DESCRIPTION:
RED OAK CR TRIB 1
END DESCRIPTION:

--- RED OAK CR TRIB 1.p01 (plan) ---

Plan Title=Multiple Run
Short Identifier=Multiple
Geom File=g01
Flow File=f01
Subcritical Flow
K Sum by GR= 0
Std Step Tol= 0.01
Critical Tol= 0.01
Num of Std Step Trials= 20
Max Error Tol= 0.3
Flow Tol Ratio= 0.001
Split Flow NTrial= 30
Split Flow Tol= 0.02
Split Flow Ratio= 0.02
Log Output Level= 0
Friction Slope Method= 1
Unsteady Friction Slope Method= 2
Unsteady Bridges Friction Slope Method= 1
Parabolic Critical Depth
Global Vel Dist=  1 , 1 , 1
Global Log Level= 0
CheckData=True
Encroach Param= -1, 0, 0, 0
BEGIN DESCRIPTION:
Multiple Run
END DESCRIPTION:

--- RED OAK CR TRIB 1.f01 (steady flow) ---

Flow Title=Multiple
Number of Profiles=7
Profile Names=10-year,25-year,50-year,1pct_min,100-year,1pct_plu,500-year
River Rch & RM= RED OAK CR TRIB ,Reach-1,2207
     370     482     571     497     672     908     922
Boundary for River Rch & Prof#=RED OAK CR TRIB ,Reach-1,1
Up Type=0
Dn Type=3
Dn Slope=0.005
Boundary for River Rch & Prof#=RED OAK CR TRIB ,Reach-1,2
Up Type=0
Dn Type=3
Dn Slope=0.005
Boundary for River Rch & Prof#=RED OAK CR TRIB ,Reach-1,3
Up Type=0
Dn Type=3
Dn Slope=0.005
Boundary for River Rch & Prof#=RED OAK CR TRIB ,Reach-1,4
Up Type=0
Dn Type=3
Dn Slope=0.005
Boundary for River Rch & Prof#=RED OAK CR TRIB ,Reach-1,5
Up Type=0
Dn Type=3
Dn Slope=0.005
Boundary for River Rch & Prof#=RED OAK CR TRIB ,Reach-1,6
Up Type=0
Dn Type=3
Dn Slope=0.005
Boundary for River Rch & Prof#=RED OAK CR TRIB ,Reach-1,7
Up Type=0
Dn Type=3
Dn Slope=0.005

--- RED OAK CR TRIB 1.g01 (geometry) ---

Geom Title=Existing Conditions

River Reach=RED OAK CR TRIB ,Reach-1
Reach XY= 30
      3550647.11     10412836.64      3550702.16     10412823.13
      3550918.57     10412905.04      3550985.94     10412874.91
      3551037.88     10412930.04      3551087.33     10412890.52
      3551175.63     10412963.93      3551277.73     10412999.18
      3551390.56     10412946.79      3551428.36     10413009.48
      3551533.09     10413008.76      3551530.60     10413054.04
      3551562.47     10413076.79      3551617.77     10413045.36
      3551665.95     10413057.71      3551698.60     10413034.98
      3551742.00     10413043.44      3551845.66     10413009.67
      3551868.96     10413062.43      3551860.71     10413123.32
      3551904.41     10413165.51      3551937.25     10413156.51
      3551961.47     10413171.47      3551976.07     10413278.22
      3552008.47     10413294.05      3552020.98     10413338.21
      3552065.20     10413383.74      3552321.78     10413470.74
      3552485.77     10413443.69      3552572.11     10413591.64

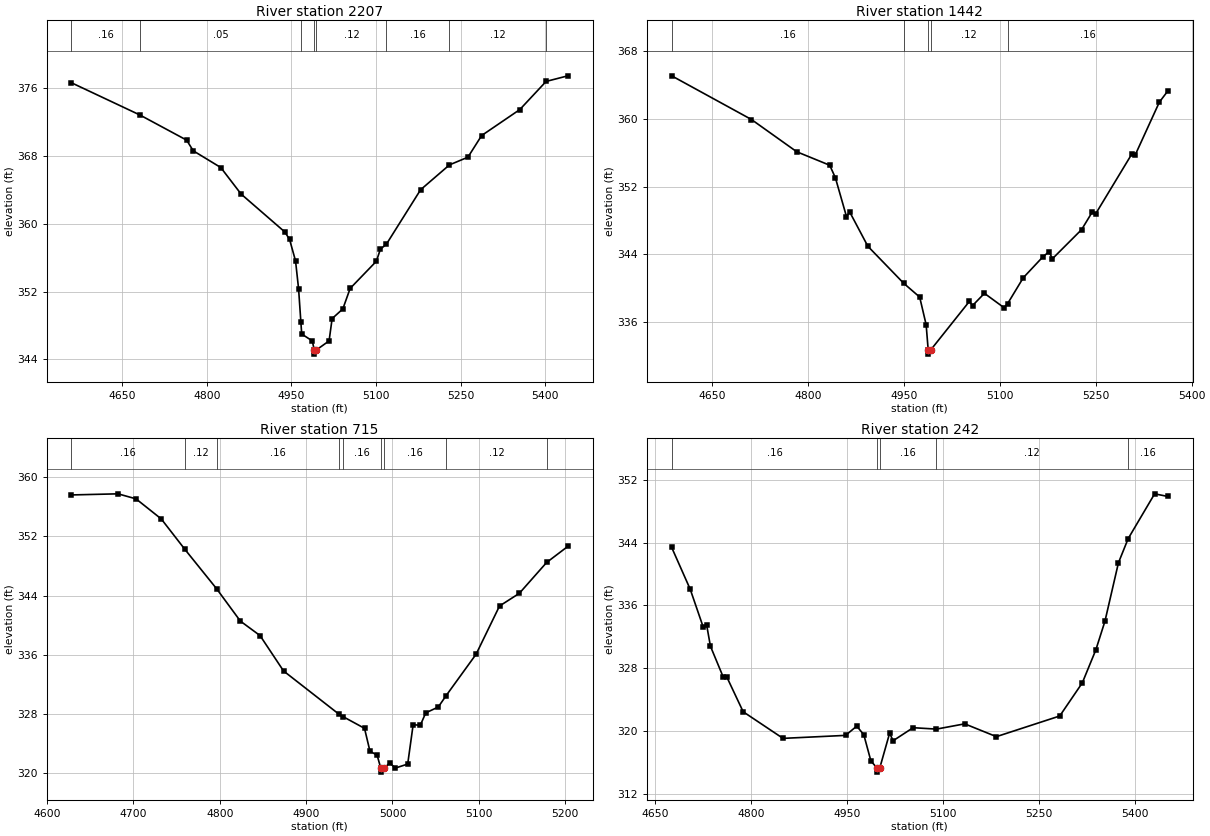
Type RM Length L Ch R = 1,2207,765,765,765
BEGIN DESCRIPTION:
RED OAK CR TRIB 1 5 0
END DESCRIPTION:
XS GIS Cut Line= 2
      3550839.43     10413301.71      3551162.36     10412482.24
#Sta/Elev= 30
  4559.6  376.61  4681.1  372.81  4763.9  369.85  4775.7  368.59  4824.5  366.62
  4860.6  363.49  4938.2  359.02  4946.6  358.14  4957.2  355.60  4962.6  352.31
  4966.6  348.44  4968.1  346.99  4986.9  346.18  4990.3  345.12  4990.6  344.62
  4994.3  345.12  5016.7  346.18  5022.1  348.81  5041.1  349.95  5054.1  352.37
  5100.6  355.57  5107.8  357.00  5118.3  357.57  5179.1  364.00  5230.3  366.93
  5263.1  367.84  5287.4  370.39  5355.1  373.45  5401.8  376.77  5440.4  377.43
#Mann=8,-1,0
  4559.6    0.16       0  4681.1    0.05       0  4966.6    0.12       0
  4990.3    0.07       0  4994.3    0.12       0  5118.3    0.16       0
  5230.3    0.12       0  5401.8    0.16       0
Bank Sta=4990.3,4994.3
Exp/Cntr=0.3,0.1

Type RM Length L Ch R = 1,1442,727,727,727
BEGIN DESCRIPTION:
RED OAK CR TRIB 1 2 0
END DESCRIPTION:
XS GIS Cut Line= 3
      3551364.98     10413410.90      3551542.08     10413244.21
      3551625.42     10412718.18
#Sta/Elev= 30
  4587.3  365.10  4712.0  359.94  4782.8  356.13  4834.3  354.54  4843.2  353.05
  4860.5  348.48  4865.6  349.01  4893.9  344.97  4949.9  340.60  4974.9  338.97
  4985.0  335.71  4988.2  332.73  4988.5  332.23  4992.2  332.73  5052.6  338.46
  5057.6  337.97  5076.1  339.41  5106.5  337.73  5112.4  338.20  5136.9  341.26
  5167.2  343.70  5177.2  344.34  5182.3  343.49  5228.0  346.94  5244.6  349.01
  5249.7  348.77  5306.9  355.92  5312.0  355.79  5349.5  361.99  5363.1  363.35
#Mann=5,-1,0
  4587.3    0.16       0  4949.9    0.12       0  4988.2    0.07       0
  4992.2    0.12       0  5112.4    0.16       0
Bank Sta=4988.2,4992.2
Exp/Cntr=0.3,0.1

Type RM Length L Ch R = 1,715,473,473,473
BEGIN DESCRIPTION:
Mapping XS 00965bc1
END DESCRIPTION:
XS GIS Cut Line= 2
      3551792.08     10413606.20      3552137.25     10413146.83
#Sta/Elev= 30
  4628.4  357.60  4682.3  357.75  4703.1  357.07  4732.3  354.36  4759.7  350.24
  4796.4  344.92  4823.9  340.55  4846.7  338.59  4873.9  333.81  4937.8  327.99
  4942.9  327.63  4967.6  326.06  4973.9  322.97  4982.2  322.43  4986.5  320.64
  4986.7  320.14  4990.5  320.64  4996.8  321.42  5003.0  320.68  5017.6  321.23
  5023.9  326.55  5032.2  326.47  5038.5  328.15  5053.0  328.94  5062.1  330.48
  5096.8  336.08  5123.9  342.59  5146.8  344.30  5178.4  348.47  5203.0  350.65
#Mann=9,-1,0
  4628.4    0.16       0  4759.7    0.12       0  4796.4    0.16       0
  4937.8    0.12       0  4942.9    0.16       0  4986.5    0.07       0
  4990.5    0.16       0  5062.1    0.12       0  5178.4    0.16       0
Bank Sta=4986.5,4990.5
Exp/Cntr=0.3,0.1

Type RM Length L Ch R = 1,242,0,0,0
BEGIN DESCRIPTION:
RED OAK CR TRIB 1 1 0
END DESCRIPTION:
XS GIS Cut Line= 4
      3552174.87     10413624.43      3552370.21     10413556.71
      3552448.33     10413387.44      3552178.79     10413115.31
#Sta/Elev= 30
  4675.9  343.38  4704.9  338.05  4725.4  333.19  4730.7  333.45  4736.5  330.80
  4756.5  326.87  4761.8  326.93  4787.7  322.45  4850.0  319.06  4947.8  319.44
  4965.3  320.62  4976.3  319.53  4987.4  316.19  4997.2  315.26  4997.5  314.76
  5001.2  315.26  5016.7  319.72  5022.2  318.76  5053.4  320.42  5089.9  320.24
  5134.1  320.91  5183.7  319.28  5282.7  321.91  5318.0  326.13  5339.2  330.34
  5353.4  333.98  5374.5  341.42  5389.7  344.50  5431.1  350.21  5452.1  349.87
#Mann=5,-1,0
  4675.9    0.16       0  4997.2    0.07       0  5001.2    0.16       0
  5089.9    0.12       0  5389.7    0.16       0
Bank Sta=4997.2,5001.2
Exp/Cntr=0.3,0.1

Chan Stop Cuts=-1