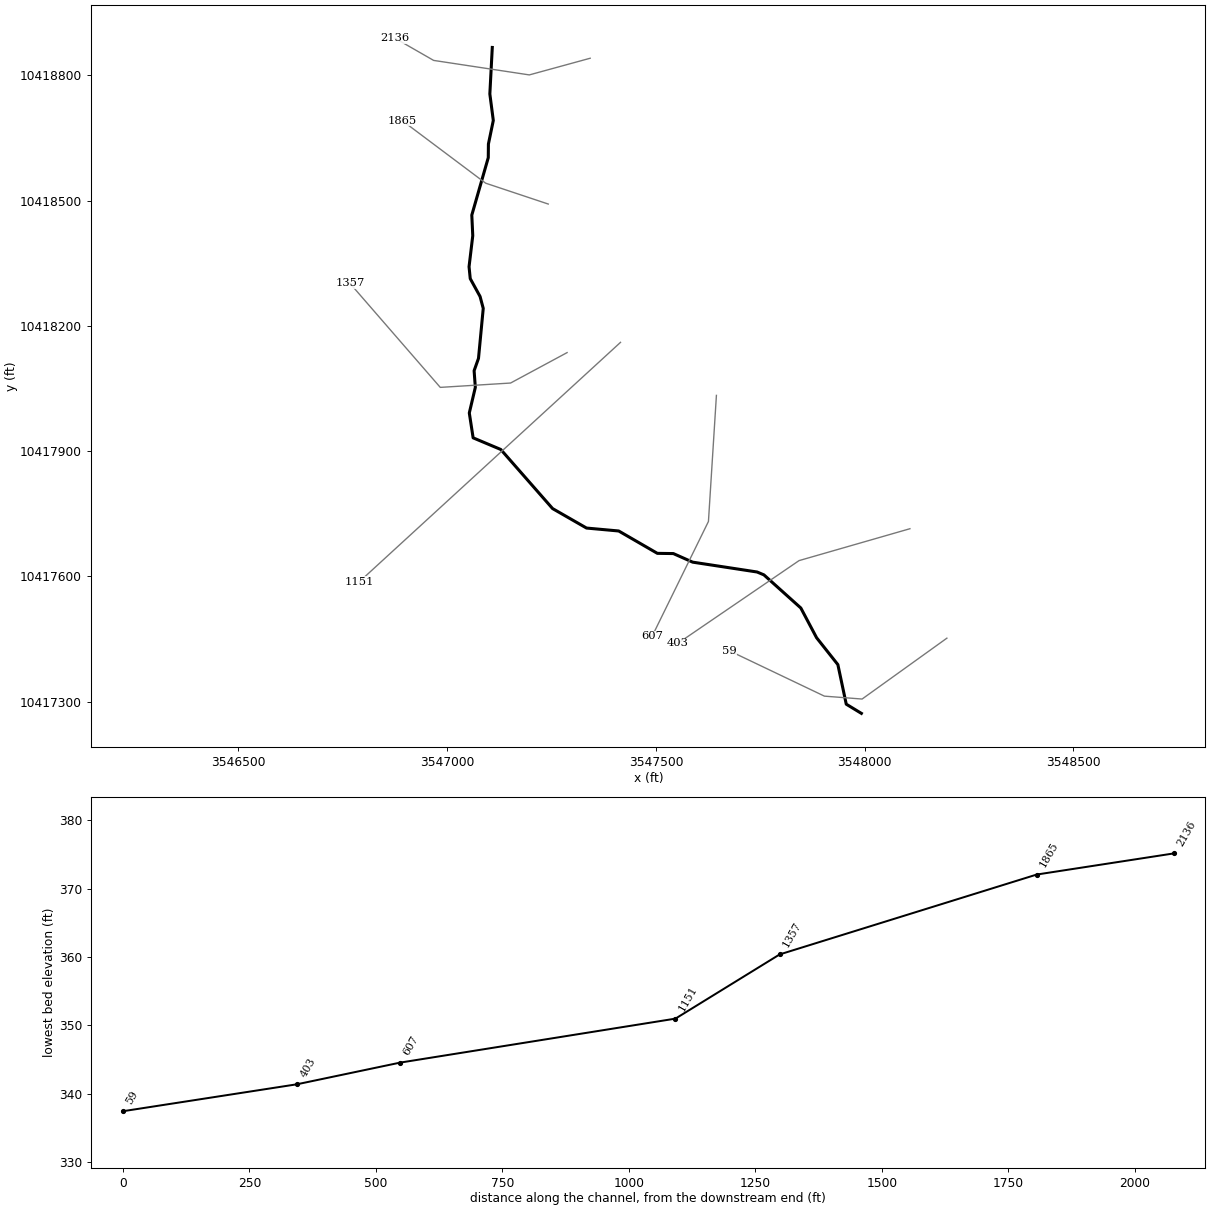
--- RED OAK CR TRIB 4.prj (project) ---

Proj Title=RED OAK CR TRIB 4 Base Level Engineering
Current Plan=p01
Default Exp/Contr=0.3,0.1
English Units
Geom File=g01
Flow File=f01
Plan File=p01
Y Axis Title=Elevation
X Axis Title(PF)=Main Channel Distance
X Axis Title(XS)=Station
BEGIN DESCRIPTION:
RED OAK CR TRIB 4
END DESCRIPTION:
DSS Export Rating Curves= 0
DSS Export Rating Curve Sorted= 0
DSS Export Volume Flow Curves= 0
DXF OffsetX= 0
DXF OffsetY= 0
DXF ScaleX= 1
DXF ScaleY= 10

--- RED OAK CR TRIB 4.p01 (plan) ---

Plan Title=Multiple Run
Short Identifier=Multiple
Geom File=g01
Flow File=f01
Subcritical Flow
K Sum by GR= 0
Std Step Tol= 0.01
Critical Tol= 0.01
Num of Std Step Trials= 20
Max Error Tol= 0.3
Flow Tol Ratio= 0.001
Split Flow NTrial= 30
Split Flow Tol= 0.02
Split Flow Ratio= 0.02
Log Output Level= 0
Friction Slope Method= 1
Unsteady Friction Slope Method= 2
Unsteady Bridges Friction Slope Method= 1
Parabolic Critical Depth
Global Vel Dist=  1 , 1 , 1
Global Log Level= 0
CheckData=True
Encroach Param= -1, 0, 0, 0
BEGIN DESCRIPTION:
Multiple Run
END DESCRIPTION:

--- RED OAK CR TRIB 4.f01 (steady flow) ---

Flow Title=Multiple
Program Version=4.10
Number of Profiles= 7
Profile Names=10-year,25-year,50-year,1pct_min,100-year,1pct_plu,500-year
River Rch & RM=RED OAK CR TRIB,Reach-1         ,2136
     663     894    1082     958    1296    1752    1850
Boundary for River Rch & Prof#=RED OAK CR TRIB,Reach-1         , 1
Up Type= 0
Dn Type= 3
Dn Slope=0.005
Boundary for River Rch & Prof#=RED OAK CR TRIB,Reach-1         , 2
Up Type= 0
Dn Type= 3
Dn Slope=0.005
Boundary for River Rch & Prof#=RED OAK CR TRIB,Reach-1         , 3
Up Type= 0
Dn Type= 3
Dn Slope=0.005
Boundary for River Rch & Prof#=RED OAK CR TRIB,Reach-1         , 4
Up Type= 0
Dn Type= 3
Dn Slope=0.005
Boundary for River Rch & Prof#=RED OAK CR TRIB,Reach-1         , 5
Up Type= 0
Dn Type= 3
Dn Slope=0.005
Boundary for River Rch & Prof#=RED OAK CR TRIB,Reach-1         , 6
Up Type= 0
Dn Type= 3
Dn Slope=0.005
Boundary for River Rch & Prof#=RED OAK CR TRIB,Reach-1         , 7
Up Type= 0
Dn Type= 3
Dn Slope=0.005
DSS Import GetInterval= 0
DSS Import GetPeak= 0
DSS Import FillOption= 0

--- RED OAK CR TRIB 4.g01 (geometry) ---

Geom Title=Existing Conditions
Program Version=4.10

River Reach=RED OAK CR TRIB ,Reach-1
Reach XY= 30
        3547108.     10418866.75      3547102.14     10418755.32
      3547110.43     10418691.88      3547098.72      10418635.4
      3547098.39     10418602.82      3547058.94      10418465.2
      3547061.23     10418415.76      3547052.34     10418341.47
      3547055.19     10418313.03      3547078.73     10418270.23
      3547086.33      10418241.7      3547074.95     10418121.96
      3547064.46      10418092.4      3547067.38     10418052.48
      3547052.94     10417991.21      3547062.11     10417931.64
      3547128.31     10417903.78      3547252.42     10417762.21
      3547333.72     10417715.55      3547410.82     10417708.53
      3547503.43     10417654.95      3547541.66     10417654.44
      3547587.92     10417633.88      3547742.31     10417610.28
      3547758.61     10417603.43      3547847.03     10417524.07
      3547884.82     10417452.78      3547935.78     10417388.44
      3547955.86     10417293.67      3547992.11     10417271.64

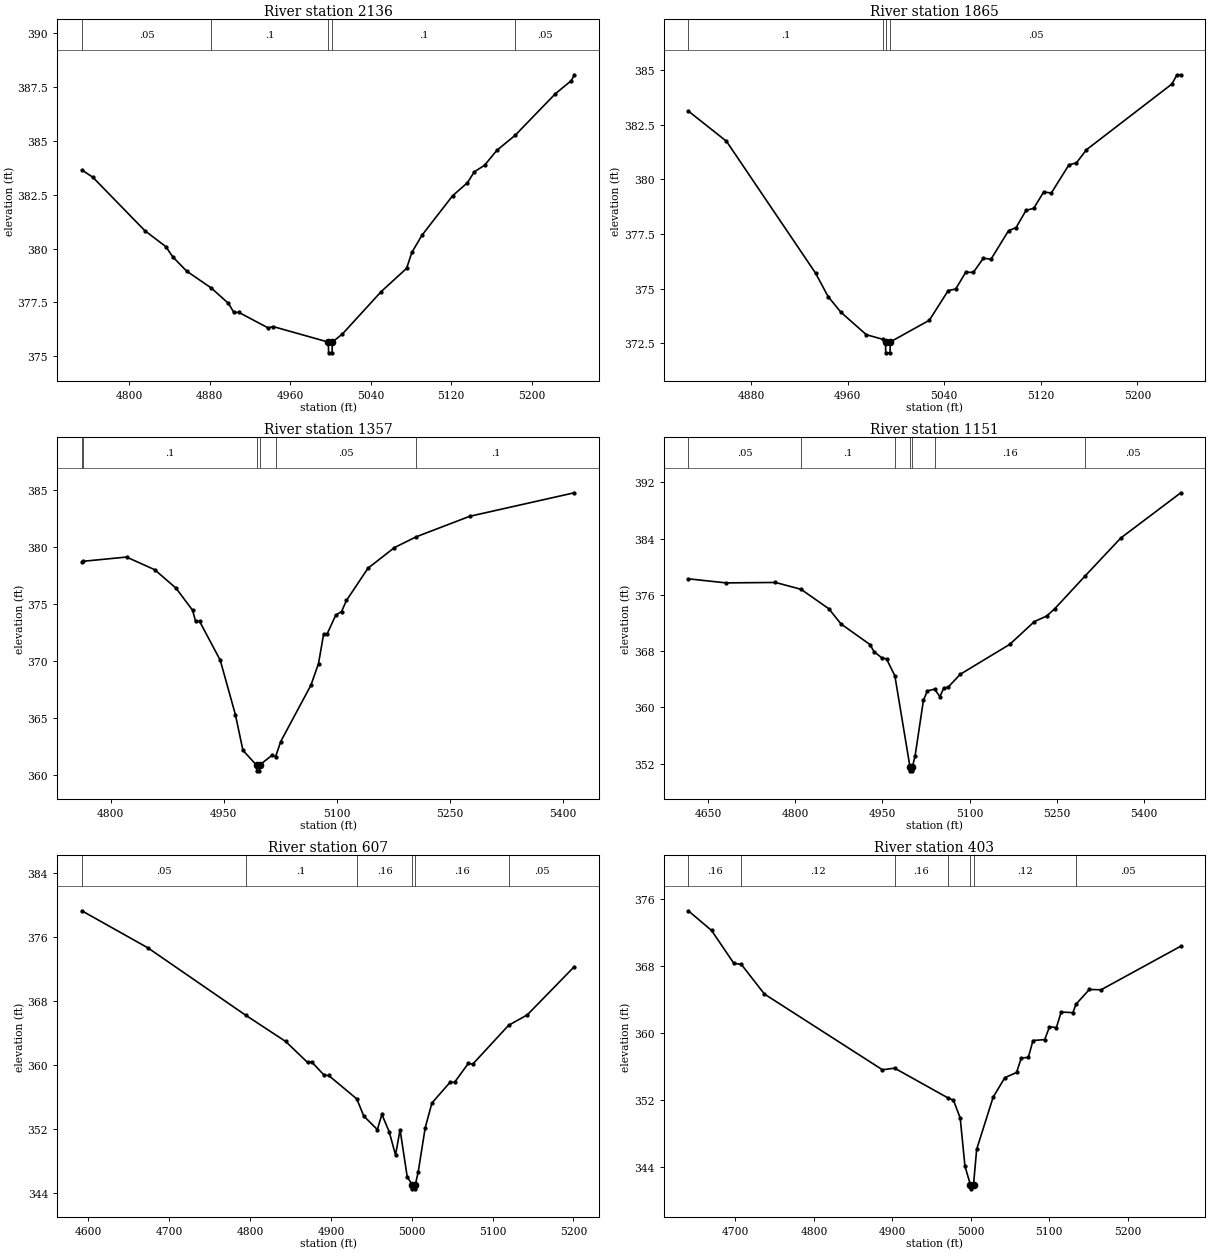
Type RM Length L Ch R = 1 ,2136    ,271,271,271
BEGIN DESCRIPTION:
RED OAK CR TRIB 4 4 1
END DESCRIPTION:
XS GIS Cut Line= 4
       3547342.5     10418840.92      3547196.66     10418800.98
      3546967.49     10418835.71      3546875.38     10418888.59
#Sta/Elev= 30
  4753.2  383.65    4764  383.32  4815.8  380.83  4836.6  380.09  4843.4  379.62
  4857.3  378.95  4881.9  378.16  4898.8  377.45  4904.2  377.03  4909.2  377.03
  4938.2  376.31  4943.3  376.37    4998  375.65  4998.3  375.15  5001.8  375.15
    5002  375.65  5012.1  376.03  5050.6     378  5075.8  379.08    5081  379.82
  5091.1  380.62  5121.4  382.45  5136.2  383.06  5143.1  383.57  5153.2  383.87
  5165.5  384.57  5183.5  385.26  5223.6   387.2  5239.5  387.81  5242.4  388.08
#Mann= 5 ,-1 , 0
  4753.2     .05       0  4881.9      .1       0    4998     .07       0
    5002      .1       0  5183.5     .05       0
Bank Sta=4998,5002
XS Rating Curve= 0 ,0
Exp/Cntr=0.3,0.1

Type RM Length L Ch R = 1 ,1865    ,508,508,508
BEGIN DESCRIPTION:
RED OAK CR TRIB 4 4 1
END DESCRIPTION:
XS GIS Cut Line= 3
      3547242.06     10418491.66      3547092.11     10418541.64
      3546892.08     10418691.66
#Sta/Elev= 30
  4827.9  383.12  4859.5  381.74  4933.3  375.71  4943.8  374.63  4954.3  373.92
  4975.4  372.89    4989  372.68  4991.3  372.56  4991.5  372.06    4995  372.06
  4995.3  372.56  5027.6  373.55  5043.3  374.91  5049.5  374.98  5057.8  375.75
  5064.1  375.74  5072.4  376.39  5078.7  376.34  5093.3  377.65  5099.5  377.79
  5107.8  378.58  5114.1  378.67  5122.4  379.42  5128.7  379.37  5143.3  380.66
  5149.5  380.75  5157.8  381.35  5228.7  384.36  5232.8  384.78    5236  384.78
#Mann= 4 ,-1 , 0
  4827.9      .1       0    4989     .05       0  4991.3     .03       0
  4995.3     .05       0
Bank Sta=4991.3,4995.3
XS Rating Curve= 0 ,0
Exp/Cntr=0.3,0.1

Type RM Length L Ch R = 1 ,1357    ,206,206,206
BEGIN DESCRIPTION:
Mapping XS 84ada8b6
END DESCRIPTION:
XS GIS Cut Line= 4
       3547287.2     10418135.82      3547151.81     10418062.92
       3546983.4      10418052.5      3546766.75     10418302.09
#Sta/Elev= 30
    4762  378.69  4764.1  378.74  4821.2  379.11  4858.6     378  4886.9  376.38
  4908.8  374.45  4912.8  373.48  4918.1  373.48  4945.5  370.07  4965.6   365.3
  4975.6  362.17  4993.6  360.88  4993.9  360.38  4997.4  360.38  4997.6  360.88
  5014.1  361.74  5018.9  361.62  5025.7  362.95  5065.8  367.89  5075.8  369.78
  5082.6  372.37  5087.2  372.37  5098.7  374.03  5106.3  374.33  5112.9  375.31
  5141.4  378.13  5176.5  379.94  5205.6  380.89  5276.3  382.68    5415  384.74
#Mann= 6 ,-1 , 0
    4762     .05       0  4764.1      .1       0  4993.6     .07       0
  4997.6      .1       0  5018.9     .05       0  5205.6      .1       0
Bank Sta=4993.6,4997.6
XS Rating Curve= 0 ,0
Exp/Cntr=0.3,0.1

Type RM Length L Ch R = 1 ,1151    ,544,544,544
BEGIN DESCRIPTION:
RED OAK CR TRIB 4 4 0
END DESCRIPTION:
XS GIS Cut Line= 2
      3547415.14     10418160.37      3546790.18     10417587.49
#Sta/Elev= 30
  4615.9  378.29  4680.8  377.71  4765.9  377.77  4809.9   376.8  4857.8  374.03
  4878.8  371.87  4928.7  368.94  4935.5  367.94  4949.7  367.01  4957.1  366.91
  4971.5  364.49  4997.6  351.49  4997.9  350.99  5001.4  350.99  5001.6  351.49
  5006.4  353.16  5020.6     361  5027.4  362.36  5039.8   362.6    5049  361.54
  5055.7  362.76  5063.1  362.88  5084.1  364.72  5169.2  368.97  5211.7  372.21
  5232.7  372.99  5246.9  374.05  5298.7  378.67  5360.4  384.09  5463.7  390.52
#Mann= 7 ,-1 , 0
  4615.9     .05       0  4809.9      .1       0  4971.5     .05       0
  4997.6     .03       0  5001.6     .05       0  5039.8     .16       0
  5298.7     .05       0
Bank Sta=4997.6,5001.6
XS Rating Curve= 0 ,0
Exp/Cntr=0.3,0.1

Type RM Length L Ch R = 1 ,607     ,204,204,204
BEGIN DESCRIPTION:
Mapping XS 89f45af3
END DESCRIPTION:
XS GIS Cut Line= 3
      3547644.86     10418033.36      3547625.76     10417731.32
       3547490.7     10417456.01
#Sta/Elev= 30
  4591.9  379.26  4673.8  374.62  4794.4  366.24  4844.1  362.95  4871.2  360.33
  4876.2   360.4  4891.9  358.72  4897.1  358.72  4932.1  355.78  4940.6  353.66
  4957.5  351.95  4963.1  353.85  4972.2  351.67    4980  348.77  4985.6  351.94
  4994.4  346.09  5000.5  345.06  5000.8  344.56  5004.3  344.56  5004.5  345.06
  5008.1   346.7  5016.7  352.18    5025  355.27  5047.5  357.86  5053.1  357.86
    5070  360.21  5075.6  360.13  5119.9  364.97    5143  366.27  5201.2  372.29
#Mann= 6 ,-1 , 0
  4591.9     .05       0  4794.4      .1       0  4932.1     .16       0
  5000.5     .07       0  5004.5     .16       0  5119.9     .05       0
Bank Sta=5000.5,5004.5
XS Rating Curve= 0 ,0
Exp/Cntr=0.3,0.1

Type RM Length L Ch R = 1 ,403     ,344,344,344
BEGIN DESCRIPTION:
Mapping XS 5bb987ad
END DESCRIPTION:
XS GIS Cut Line= 3
      3548108.44     10417713.97      3547842.78     10417637.57
      3547552.82     10417439.64
#Sta/Elev= 30
    4640  374.61  4669.6  372.26  4698.1  368.32  4707.5  368.21    4737  364.66
  4887.4  355.61  4902.8  355.81  4970.9  352.25  4977.8  351.98  4986.4  349.86
  4992.5  344.09  4999.4  341.89  4999.6  341.39  5003.4  341.89  5007.4  346.11
  5028.4  352.34  5043.3  354.67  5058.2  355.29  5064.3  357.02  5073.2  357.09
  5079.2  359.11  5094.1  359.22  5100.2  360.75    5109  360.66  5115.1  362.51
    5130  362.44  5133.9  363.44    5151  365.21  5165.9  365.17  5267.5  370.38
#Mann= 7 ,-1 , 0
    4640     .16       0  4707.5     .12       0  4902.8     .16       0
  4970.9     .12       0  4999.4     .07       0  5003.4     .12       0
  5133.9     .05       0
Bank Sta=4999.4,5003.4
XS Rating Curve= 0 ,0
Exp/Cntr=0.3,0.1

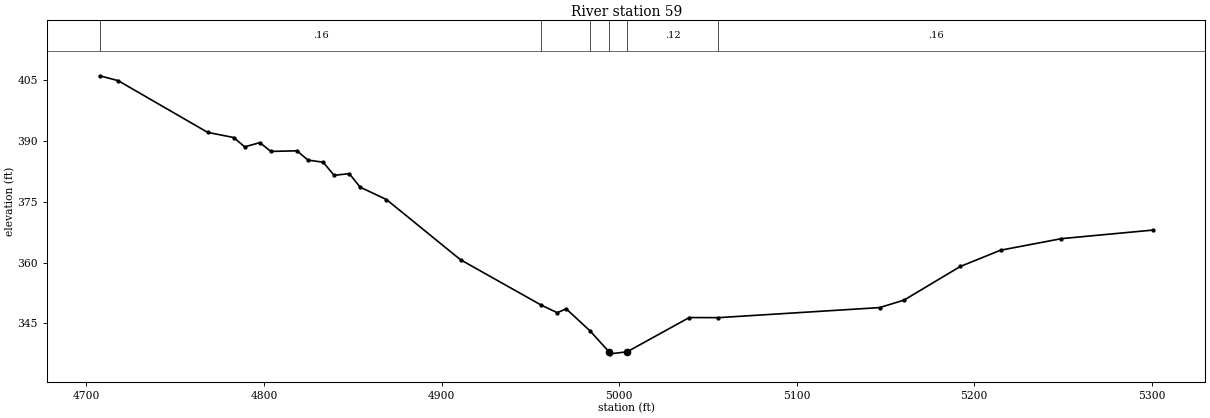
Type RM Length L Ch R = 1 ,59      ,0,0,0
BEGIN DESCRIPTION:
RED OAK CR TRIB 4 1 0
END DESCRIPTION:
XS GIS Cut Line= 4
      3548196.91     10417451.79      3547993.82     10417305.98
      3547903.54     10417312.92      3547675.72     10417421.65
#Sta/Elev= 30
  4707.5  406.12  4717.9  404.92  4768.3  392.15    4783  390.87  4789.2  388.57
  4797.7  389.61  4803.9  387.44  4818.6  387.59  4824.8   385.3  4833.4  384.77
  4839.5  381.54  4848.1  381.95  4854.2  378.61    4869  375.56  4910.7  360.69
  4956.3  349.45  4965.2  347.61  4970.2  348.57  4983.6  343.14  4994.3  337.95
  4994.8  337.45  5004.5  337.95  5039.5  346.41  5055.9  346.39  5146.7  348.87
  5160.5  350.73  5192.1  359.02  5214.8  363.04  5249.1   365.9  5300.5  368.01
#Mann= 6 ,-1 , 0
  4707.5     .16       0  4956.3      .1       0  4983.6     .12       0
  4994.3     .07       0  5004.5     .12       0  5055.9     .16       0
Bank Sta=4994.3,5004.5
XS Rating Curve= 0 ,0
Exp/Cntr=0.3,0.1

Chan Stop Cuts=-1
Use User Specified Reach Order=0
Composite Channel Slope=5