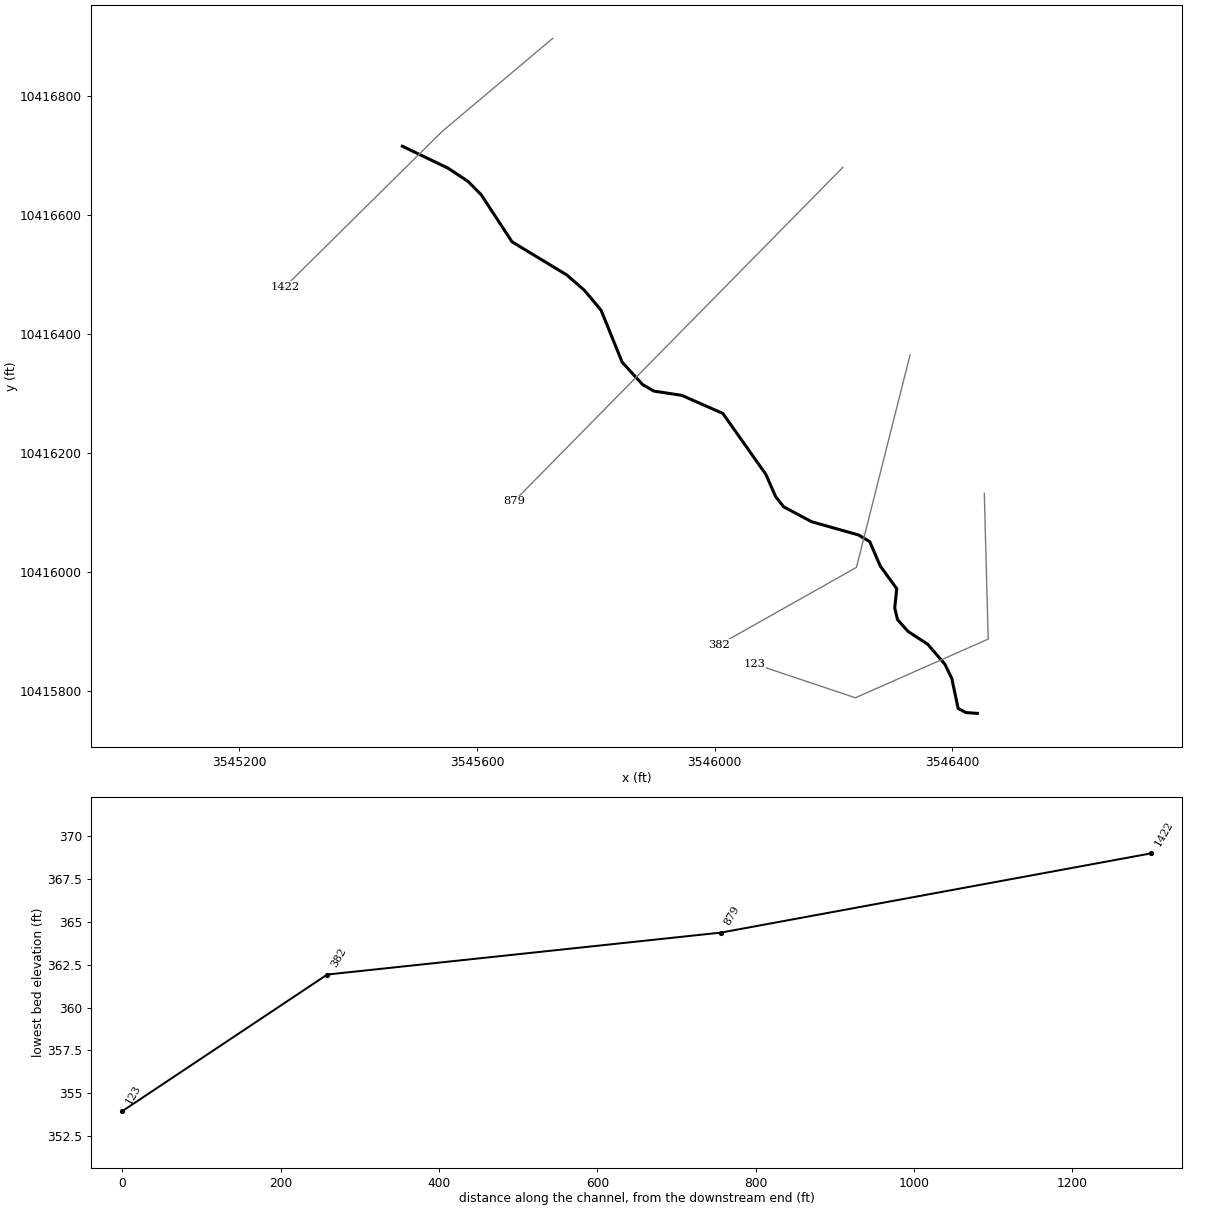
--- RED OAK CR TRIB 5.prj (project) ---

Proj Title=RED OAK CR TRIB 5 Base Level Engineering
Current Plan=p01
Default Exp/Contr=0.3,0.1
English Units
Geom File=g01
Flow File=f01
Plan File=p01
Y Axis Title=Elevation
X Axis Title(PF)=Main Channel Distance
X Axis Title(XS)=Station
BEGIN DESCRIPTION:
RED OAK CR TRIB 5
END DESCRIPTION:
DSS Export Rating Curves= 0
DSS Export Rating Curve Sorted= 0
DSS Export Volume Flow Curves= 0
DXF OffsetX= 0
DXF OffsetY= 0
DXF ScaleX= 1
DXF ScaleY= 10

--- RED OAK CR TRIB 5.p01 (plan) ---

Plan Title=Multiple Run
Short Identifier=Multiple
Geom File=g01
Flow File=f01
Subcritical Flow
K Sum by GR= 0
Std Step Tol= 0.01
Critical Tol= 0.01
Num of Std Step Trials= 20
Max Error Tol= 0.3
Flow Tol Ratio= 0.001
Split Flow NTrial= 30
Split Flow Tol= 0.02
Split Flow Ratio= 0.02
Log Output Level= 0
Friction Slope Method= 1
Unsteady Friction Slope Method= 2
Unsteady Bridges Friction Slope Method= 1
Parabolic Critical Depth
Global Vel Dist=  1 , 1 , 1
Global Log Level= 0
CheckData=True
Encroach Param= -1, 0, 0, 0
BEGIN DESCRIPTION:
Multiple Run
END DESCRIPTION:

--- RED OAK CR TRIB 5.f01 (steady flow) ---

Flow Title=Multiple
Program Version=4.10
Number of Profiles= 7
Profile Names=10-year,25-year,50-year,1pct_min,100-year,1pct_plu,500-year
River Rch & RM=RED OAK CR TRIB,Reach-1         ,1422
     790    1077    1312    1169    1581    2139    2287
Boundary for River Rch & Prof#=RED OAK CR TRIB,Reach-1         , 1
Up Type= 0
Dn Type= 3
Dn Slope=0.03
Boundary for River Rch & Prof#=RED OAK CR TRIB,Reach-1         , 2
Up Type= 0
Dn Type= 3
Dn Slope=0.03
Boundary for River Rch & Prof#=RED OAK CR TRIB,Reach-1         , 3
Up Type= 0
Dn Type= 3
Dn Slope=0.03
Boundary for River Rch & Prof#=RED OAK CR TRIB,Reach-1         , 4
Up Type= 0
Dn Type= 3
Dn Slope=0.03
Boundary for River Rch & Prof#=RED OAK CR TRIB,Reach-1         , 5
Up Type= 0
Dn Type= 3
Dn Slope=0.03
Boundary for River Rch & Prof#=RED OAK CR TRIB,Reach-1         , 6
Up Type= 0
Dn Type= 3
Dn Slope=0.03
Boundary for River Rch & Prof#=RED OAK CR TRIB,Reach-1         , 7
Up Type= 0
Dn Type= 3
Dn Slope=0.03
DSS Import GetInterval= 0
DSS Import GetPeak= 0
DSS Import FillOption= 0

--- RED OAK CR TRIB 5.g01 (geometry) ---

Geom Title=Existing Conditions
Program Version=4.10

River Reach=RED OAK CR TRIB ,Reach-1
Reach XY= 30
      3545474.48     10416716.06      3545551.17     10416679.23
      3545584.99     10416656.91      3545607.11      10416634.4
      3545658.98     10416555.27      3545751.25     10416499.38
      3545780.72      10416473.7      3545808.75     10416440.31
      3545844.45     10416352.43      3545878.64     10416315.09
      3545897.56     10416304.05      3545944.84     10416296.79
      3546013.82     10416266.36      3546086.19     10416163.83
      3546102.49     10416126.63      3546116.06      10416109.3
      3546163.09     10416084.21      3546242.39     10416061.77
      3546260.99     10416050.63      3546278.65     10416009.65
      3546306.45     10415971.48      3546303.06     10415939.11
      3546307.76     10415919.33      3546325.58     10415899.46
      3546358.56     10415877.95      3546387.35     10415844.51
       3546399.1     10415820.39       3546409.7     10415770.03
      3546422.97       10415763.      3546442.11     10415761.64

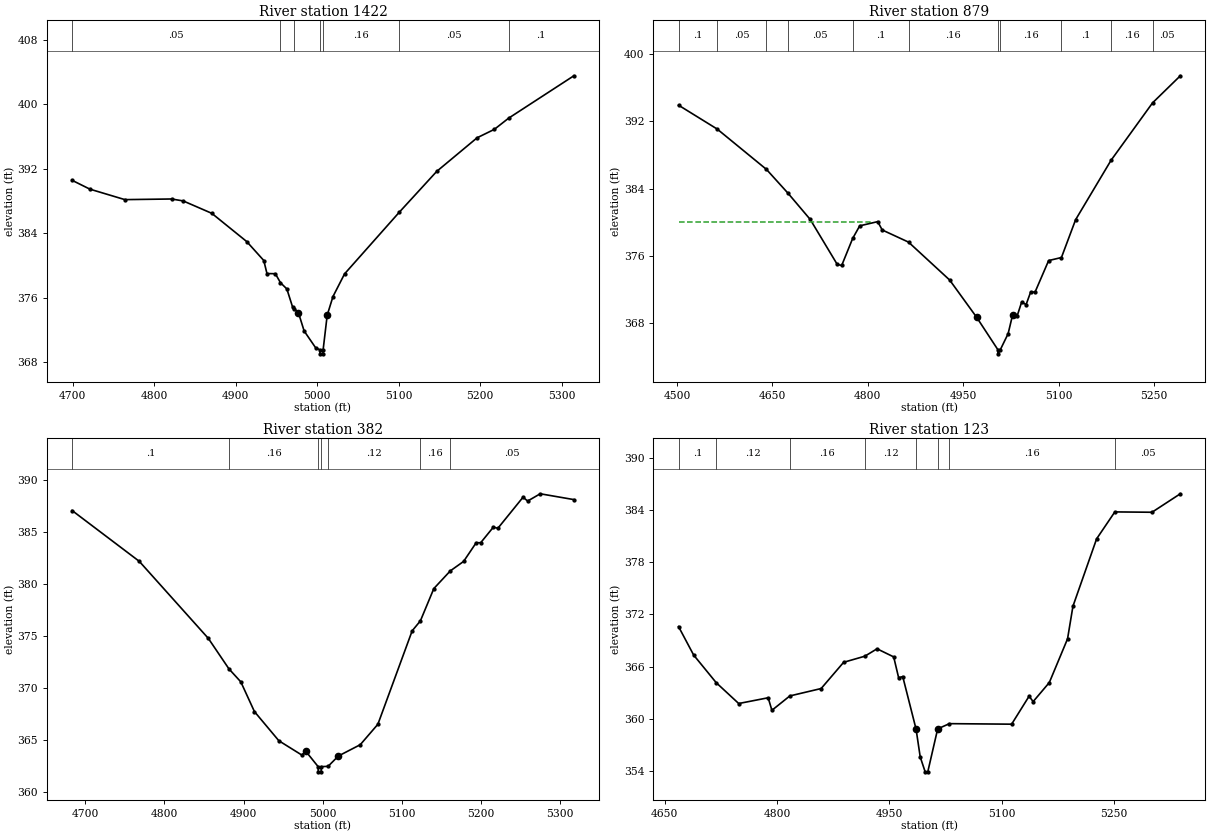
Type RM Length L Ch R = 1 ,1422    ,543,543,543
BEGIN DESCRIPTION:
RED OAK CR TRIB 5 3 1
END DESCRIPTION:
XS GIS Cut Line= 3
      3545727.53     10416897.66      3545542.11     10416741.64
      3545276.59     10416479.27
#Sta/Elev= 30
  4699.3  390.56  4721.2  389.46  4764.1  388.16  4821.3  388.24  4835.6     388
  4870.7  386.46  4913.6  382.95  4934.5   380.6  4938.4  378.98  4948.7  378.96
    4955  377.84  4962.8  377.07  4969.9   374.8  4972.1  374.59    4977  374.12
    4984  371.85  4998.2  369.75  5003.3  369.51  5003.5  369.01    5007  369.01
  5007.3  369.51  5012.3  373.81  5019.4  376.13  5033.6  378.94  5100.5  386.57
  5146.7  391.67  5196.2  395.84  5217.4  396.89  5234.8  398.27  5314.9  403.54
#Mann= 7 ,-1 , 0
  4699.3     .05       0    4955      .1       0  4972.1     .16       0
  5003.3     .07       0  5007.3     .16       0  5100.5     .05       0
  5234.8      .1       0
Bank Sta=4977,5012.3
XS Rating Curve= 0 ,0
Exp/Cntr=0.3,0.1

Type RM Length L Ch R = 1 ,879     ,497,497,497
BEGIN DESCRIPTION:
RED OAK CR TRIB 5 3 0
END DESCRIPTION:
XS GIS Cut Line= 2
      3546215.82     10416680.65      3545662.41     10416118.56
#Sta/Elev= 30
  4502.5  393.89  4563.2  391.06  4640.7  386.27  4674.5  383.45  4709.5  380.33
    4752  374.99    4759  374.87  4776.2  378.07  4787.3  379.57  4815.6  380.07
  4822.7  379.08    4864  377.64  4928.7  373.14  4971.1  368.72  5004.4  364.88
  5004.7  364.38  5008.4  364.88  5020.6  366.77  5027.7  369.02  5034.7  368.85
  5041.8  370.51  5048.9  370.23    5056  371.71    5063  371.72  5084.3  375.45
  5104.4  375.81  5126.7   380.3  5182.4  387.35  5247.7  394.17  5291.3  397.38
#Mann= 11 ,-1 , 0
  4502.5      .1       0  4563.2     .05       0  4640.7      .1       0
  4674.5     .05       0  4776.2      .1       0    4864     .16       0
  5004.4     .07       0  5008.4     .16       0  5104.4      .1       0
  5182.4     .16       0  5247.7     .05       0
#XS Ineff= 2 , 0
         4803.16     380
Permanent Ineff=
       F       F
Bank Sta=4971.1,5027.7
XS Rating Curve= 0 ,0
Exp/Cntr=0.3,0.1

Type RM Length L Ch R = 1 ,382     ,259,259,259
BEGIN DESCRIPTION:
Mapping XS cb11b22a
END DESCRIPTION:
XS GIS Cut Line= 3
      3546328.89     10416365.01      3546238.61     10416007.36
      3546007.67     10415877.13
#Sta/Elev= 30
  4683.4  387.08  4768.3  382.19  4855.6  374.77  4881.6  371.84  4896.6  370.59
  4913.8  367.73  4944.7  364.92  4973.6  363.55  4978.8   363.9  4994.3  362.43
  4994.5  361.93    4998  361.93  4998.3  362.43  5006.9  362.46  5019.8  363.45
  5047.5  364.54  5069.8  366.51  5113.1   375.5  5123.5  376.46  5140.5  379.57
  5161.3  381.27  5178.1  382.18    5194  383.98  5199.7  383.98  5215.7  385.48
  5221.4  385.37  5253.2  388.36    5259  387.99  5274.9  388.69  5317.4  388.13
#Mann= 7 ,-1 , 0
  4683.4      .1       0  4881.6     .16       0  4994.3     .07       0
  4998.3     .16       0  5006.9     .12       0  5123.5     .16       0
  5161.3     .05       0
Bank Sta=4978.8,5019.8
XS Rating Curve= 0 ,0
Exp/Cntr=0.3,0.1

Type RM Length L Ch R = 1 ,123     ,0,0,0
BEGIN DESCRIPTION:
RED OAK CR TRIB 5 1 0
END DESCRIPTION:
XS GIS Cut Line= 4
      3546453.82     10416131.88      3546460.33     10415886.63
       3546236.8     10415787.89      3546066.24     10415845.11
#Sta/Elev= 30
  4668.7  370.61  4688.9  367.34  4719.1  364.16    4749  361.78  4788.3  362.44
  4793.3     361  4817.2  362.65    4859   363.5    4889  366.51  4917.3  367.21
  4933.6  368.06  4955.8  367.13  4962.4  364.74  4967.9  364.87  4985.7  358.83
  4991.2  355.65  4997.8  353.94  5001.3  353.94  5014.5  358.87  5030.2  359.47
  5113.2  359.41  5136.5  362.62  5141.9     362  5163.5  364.19  5187.8   369.2
    5195  372.94  5226.6  380.68  5250.9  383.77  5300.5  383.73  5338.3  385.85
#Mann= 8 ,-1 , 0
  4668.7      .1       0  4719.1     .12       0  4817.2     .16       0
  4917.3     .12       0  4985.7     .07       0  5014.5     .12       0
  5030.2     .16       0  5250.9     .05       0
Bank Sta=4985.7,5014.5
XS Rating Curve= 0 ,0
Exp/Cntr=0.3,0.1

Chan Stop Cuts=-1
Use User Specified Reach Order=0
Composite Channel Slope=5