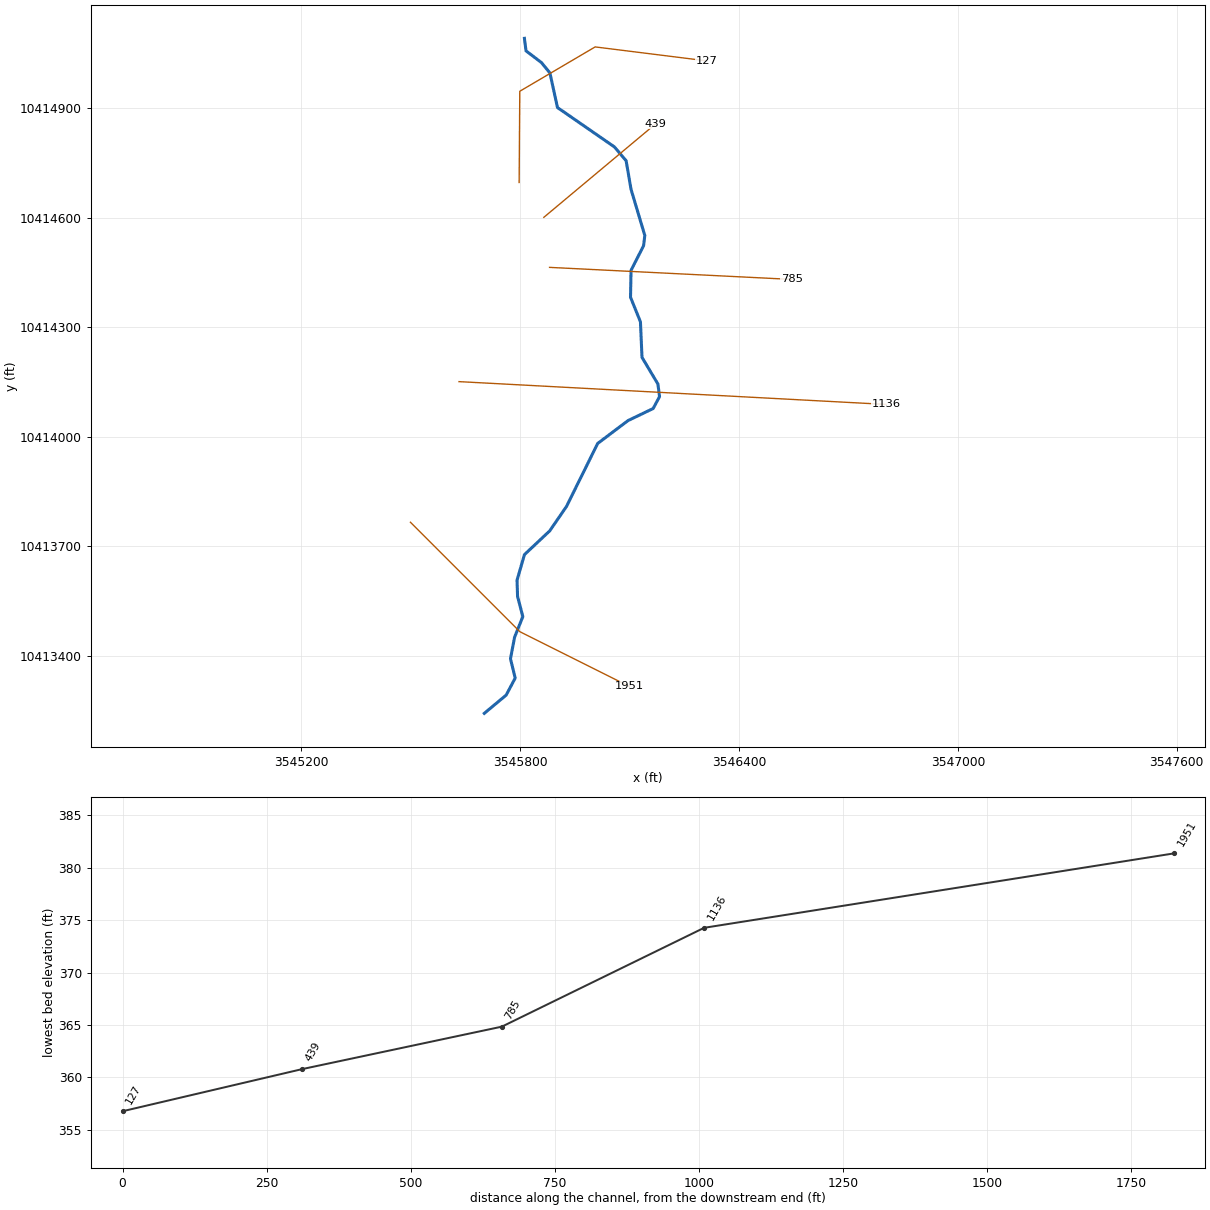
--- RED OAK CR TRIB 6.prj (project) ---

Proj Title=RED OAK CR TRIB 6 Base Level Engineering
Current Plan=p01
Default Exp/Contr=0.3,0.1
English Units
Geom File=g01
Flow File=f01
Plan File=p01
BEGIN DESCRIPTION:
RED OAK CR TRIB 6
END DESCRIPTION:

--- RED OAK CR TRIB 6.p01 (plan) ---

Plan Title=Multiple Run
Short Identifier=Multiple
Geom File=g01
Flow File=f01
Subcritical Flow
K Sum by GR= 0
Std Step Tol= 0.01
Critical Tol= 0.01
Num of Std Step Trials= 20
Max Error Tol= 0.3
Flow Tol Ratio= 0.001
Split Flow NTrial= 30
Split Flow Tol= 0.02
Split Flow Ratio= 0.02
Log Output Level= 0
Friction Slope Method= 1
Unsteady Friction Slope Method= 2
Unsteady Bridges Friction Slope Method= 1
Parabolic Critical Depth
Global Vel Dist=  1 , 1 , 1
Global Log Level= 0
CheckData=True
Encroach Param= -1, 0, 0, 0
BEGIN DESCRIPTION:
Multiple Run
END DESCRIPTION:

--- RED OAK CR TRIB 6.f01 (steady flow) ---

Flow Title=Multiple
Number of Profiles=7
Profile Names=10-year,25-year,50-year,1pct_min,100-year,1pct_plu,500-year
River Rch & RM= RED OAK CR TRIB ,Reach-1,1951
     537     712     852     746    1009    1365    1408
Boundary for River Rch & Prof#=RED OAK CR TRIB ,Reach-1,1
Up Type=0
Dn Type=3
Dn Slope=0.005
Boundary for River Rch & Prof#=RED OAK CR TRIB ,Reach-1,2
Up Type=0
Dn Type=3
Dn Slope=0.005
Boundary for River Rch & Prof#=RED OAK CR TRIB ,Reach-1,3
Up Type=0
Dn Type=3
Dn Slope=0.005
Boundary for River Rch & Prof#=RED OAK CR TRIB ,Reach-1,4
Up Type=0
Dn Type=3
Dn Slope=0.005
Boundary for River Rch & Prof#=RED OAK CR TRIB ,Reach-1,5
Up Type=0
Dn Type=3
Dn Slope=0.005
Boundary for River Rch & Prof#=RED OAK CR TRIB ,Reach-1,6
Up Type=0
Dn Type=3
Dn Slope=0.005
Boundary for River Rch & Prof#=RED OAK CR TRIB ,Reach-1,7
Up Type=0
Dn Type=3
Dn Slope=0.005

--- RED OAK CR TRIB 6.g01 (geometry) ---

Geom Title=Existing Conditions

River Reach=RED OAK CR TRIB ,Reach-1
Reach XY= 30
      3545702.11     10413241.64      3545762.12     10413291.75
      3545786.84     10413338.38      3545773.91     10413391.24
      3545785.14     10413450.40      3545807.77     10413506.82
      3545793.33     10413562.12      3545791.87     10413606.59
      3545812.18     10413676.68      3545881.49     10413741.84
      3545927.49     10413808.83      3546012.86     10413981.31
      3546095.91     10414043.94      3546164.93     10414077.14
      3546182.41     10414109.73      3546178.00     10414144.21
      3546134.34     10414217.34      3546130.05     10414314.81
      3546102.88     10414382.08      3546104.30     10414455.70
      3546138.65     10414523.25      3546142.05     10414551.45
      3546104.36     10414677.58      3546090.81     10414756.20
      3546058.71     10414794.13      3545902.71     10414901.91
      3545882.01     10414996.71      3545858.98     10415025.00
      3545816.50     10415057.31      3545812.11     10415091.64

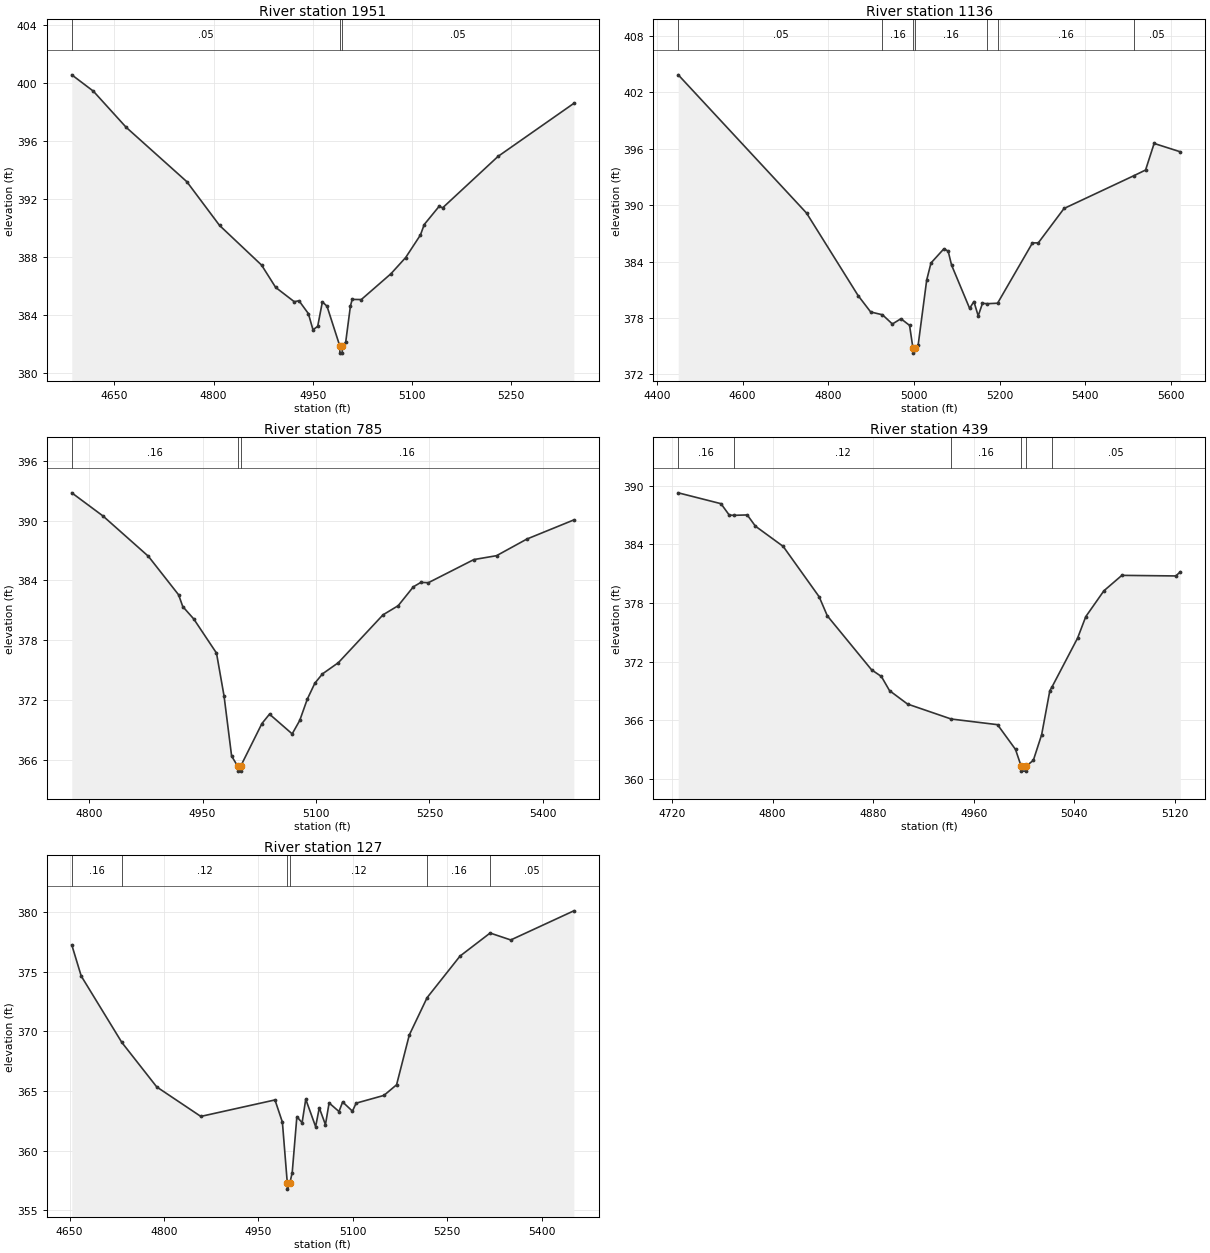
Type RM Length L Ch R = 1,1951,815,815,815
BEGIN DESCRIPTION:
RED OAK CR TRIB 6 5 0
END DESCRIPTION:
XS GIS Cut Line= 3
      3545499.71     10413765.48      3545799.73     10413465.46
      3546099.73     10413315.46
#Sta/Elev= 30
  4585.4  400.57  4618.1  399.44  4667.6  396.95  4759.5  393.19  4809.0  390.17
  4872.6  387.43  4893.9  385.89  4922.1  384.90  4929.2  384.97  4943.4  384.08
  4950.4  382.96  4957.5  383.20  4964.6  384.89  4971.6  384.59  4990.9  381.85
  4991.1  381.35  4994.6  381.35  4994.9  381.85  4999.9  382.11  5007.0  384.59
  5009.7  385.06  5023.5  385.05  5068.3  386.83  5090.6  387.95  5113.0  389.51
  5118.7  390.23  5141.1  391.48  5146.7  391.39  5230.5  394.94  5345.1  398.60
#Mann=3,-1,0
  4585.4    0.05       0  4990.9   0.035       0  4994.9    0.05       0
Bank Sta=4990.9,4994.9
Exp/Cntr=0.3,0.1

Type RM Length L Ch R = 1,1136,351,351,351
BEGIN DESCRIPTION:
RED OAK CR TRIB 6 2 0
END DESCRIPTION:
XS GIS Cut Line= 2
      3545633.00     10414150.82      3546803.13     10414088.32
#Sta/Elev= 30
  4449.7  403.87  4749.2  389.16  4869.4  380.39  4898.8  378.64  4926.4  378.34
  4949.5  377.36  4969.5  377.92  4989.6  377.21  4997.6  374.76  4997.8  374.26
  5001.6  374.76  5009.6  375.10  5029.6  382.04  5039.6  383.85  5069.7  385.36
  5079.7  385.11  5087.6  383.63  5129.8  379.02  5139.8  379.75  5149.8  378.22
  5159.8  379.56  5170.8  379.52  5195.0  379.57  5276.5  385.99  5290.0  385.99
  5350.1  389.65  5512.3  393.12  5540.4  393.74  5560.4  396.57  5621.5  395.68
#Mann=7,-1,0
  4449.7    0.05       0  4926.4    0.16       0  4997.6    0.07       0
  5001.6    0.16       0  5170.8    0.05       0  5195.0    0.16       0
  5512.3    0.05       0
Bank Sta=4997.6,5001.6
Exp/Cntr=0.3,0.1

Type RM Length L Ch R = 1,785,346,346,346
BEGIN DESCRIPTION:
Mapping XS 0b38660b
END DESCRIPTION:
XS GIS Cut Line= 2
      3545880.97     10414463.96      3546544.15     10414430.98
#Sta/Elev= 30
  4777.0  392.78  4818.2  390.46  4878.3  386.41  4918.3  382.54  4923.8  381.36
  4938.3  380.12  4968.4  376.69  4978.4  372.38  4988.4  366.35  4996.4  365.34
  4996.7  364.84  5000.2  364.84  5000.4  365.34  5028.5  369.62  5038.5  370.56
  5068.5  368.58  5078.5  369.93  5088.5  372.07  5098.5  373.67  5108.5  374.60
  5129.6  375.73  5188.6  380.53  5208.7  381.45  5228.7  383.34  5238.7  383.79
  5248.7  383.76  5308.8  386.08  5338.8  386.47  5378.9  388.14  5441.0  390.06
#Mann=3,-1,0
  4777.0    0.16       0  4996.4    0.07       0  5000.4    0.16       0
Bank Sta=4996.4,5000.4
Exp/Cntr=0.3,0.1

Type RM Length L Ch R = 1,439,312,312,312
BEGIN DESCRIPTION:
Mapping XS cf1aca05
END DESCRIPTION:
XS GIS Cut Line= 2
      3545865.38     10414601.14      3546171.78     10414857.34
#Sta/Elev= 30
  4725.0  389.26  4759.0  388.15  4765.6  386.98  4769.5  386.96  4779.9  387.00
  4786.4  385.85  4808.5  383.78  4837.1  378.63  4843.6  376.68  4878.8  371.16
  4886.6  370.48  4893.1  369.03  4907.4  367.66  4942.1  366.13  4979.0  365.55
  4993.3  363.02  4997.8  361.30  4998.0  360.80  5001.5  360.80  5001.8  361.30
  5007.5  361.91  5014.1  364.53  5020.6  369.03  5022.3  369.40  5042.7  374.41
  5049.2  376.60  5063.6  379.24  5077.9  380.82  5120.8  380.76  5124.4  381.18
#Mann=6,-1,0
  4725.0    0.16       0  4769.5    0.12       0  4942.1    0.16       0
  4997.8    0.07       0  5001.8    0.16       0  5022.3    0.05       0
Bank Sta=4997.8,5001.8
Exp/Cntr=0.3,0.1

Type RM Length L Ch R = 1,127,0,0,0
BEGIN DESCRIPTION:
RED OAK CR TRIB 6 1 0
END DESCRIPTION:
XS GIS Cut Line= 4
      3545797.64     10414696.62      3545799.38     10414946.60
      3546005.97     10415068.13      3546311.52     10415029.94
#Sta/Elev= 30
  4653.5  377.24  4668.5  374.63  4733.0  369.07  4788.5  365.34  4858.5  362.87
  4976.3  364.25  4988.1  362.39  4995.9  357.28  4996.2  356.78  4999.9  357.28
  5003.7  358.17  5011.1  362.85  5019.4  362.34  5025.2  364.31  5040.9  362.01
  5046.7  363.59  5056.5  362.18  5062.3  364.00  5078.0  363.28  5083.8  364.08
  5099.4  363.31  5105.2  363.98  5149.4  364.63  5169.5  365.52  5189.7  369.69
  5218.0  372.82  5270.3  376.30  5318.1  378.23  5350.9  377.65  5451.1  380.09
#Mann=6,-1,0
  4653.5    0.16       0  4733.0    0.12       0  4995.9    0.07       0
  4999.9    0.12       0  5218.0    0.16       0  5318.1    0.05       0
Bank Sta=4995.9,4999.9
Exp/Cntr=0.3,0.1

Chan Stop Cuts=-1