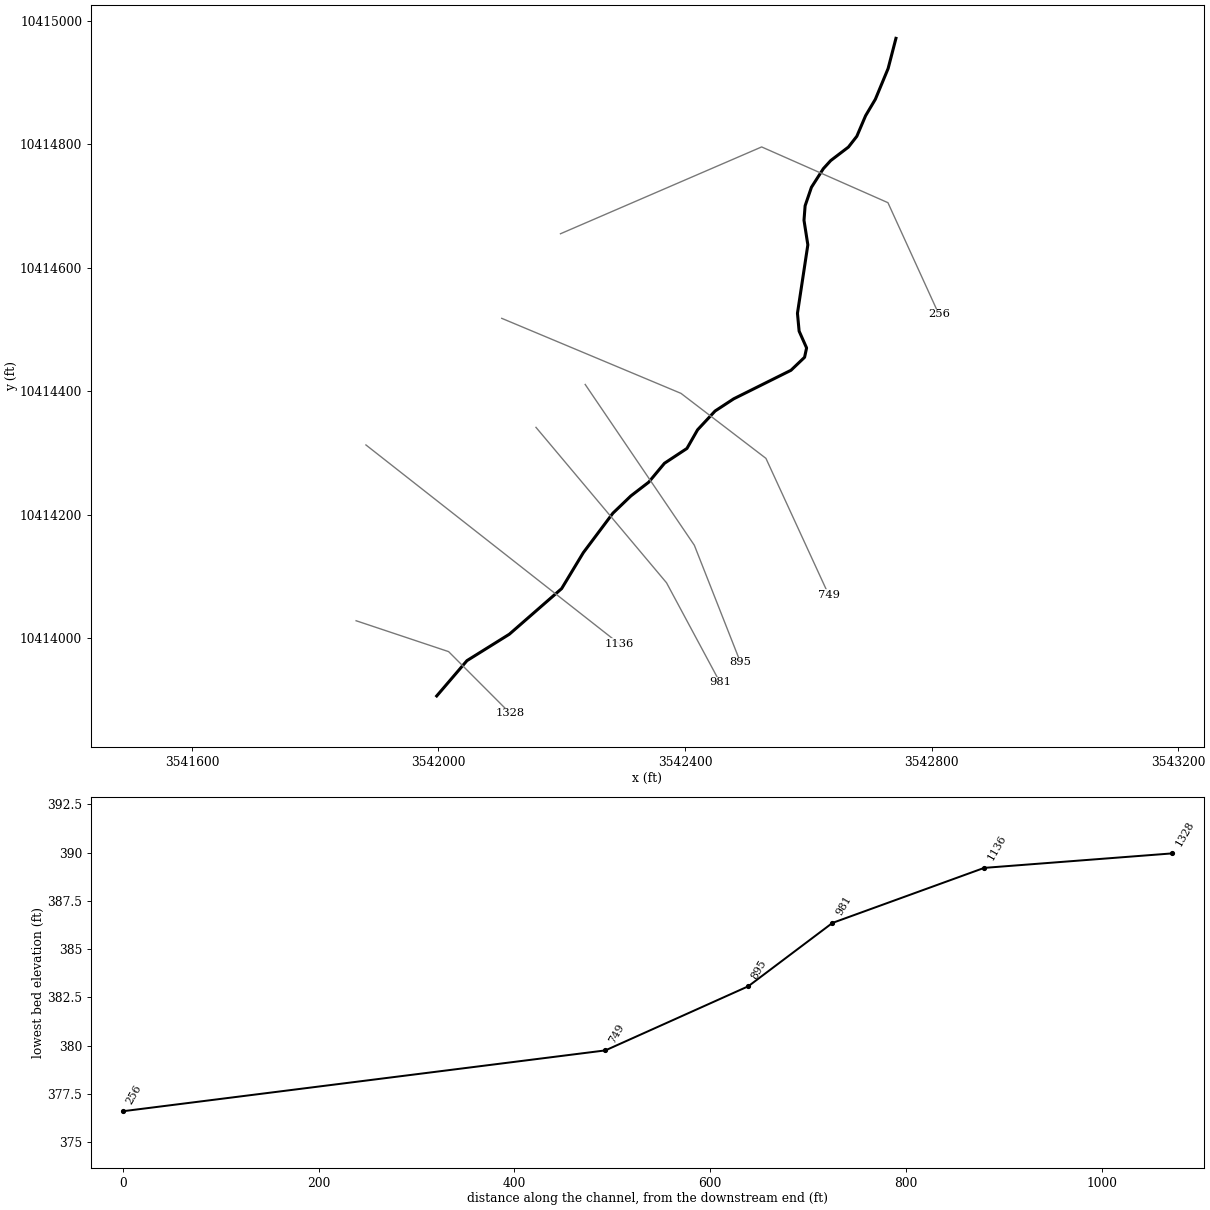
--- RED OAK CR TRIB 7 1.prj (project) ---

Proj Title=RED OAK CR TRIB 7 1 Base Level Engineering
Current Plan=p01
Default Exp/Contr=0.3,0.1
English Units
Geom File=g01
Flow File=f01
Plan File=p01
Y Axis Title=Elevation
X Axis Title(PF)=Main Channel Distance
X Axis Title(XS)=Station
BEGIN DESCRIPTION:
RED OAK CR TRIB 7 1
END DESCRIPTION:
DSS Export Rating Curves= 0
DSS Export Rating Curve Sorted= 0
DSS Export Volume Flow Curves= 0
DXF OffsetX= 0
DXF OffsetY= 0
DXF ScaleX= 1
DXF ScaleY= 10

--- RED OAK CR TRIB 7 1.p01 (plan) ---

Plan Title=Multiple Run
Short Identifier=Multiple
Geom File=g01
Flow File=f01
Subcritical Flow
K Sum by GR= 0
Std Step Tol= 0.01
Critical Tol= 0.01
Num of Std Step Trials= 20
Max Error Tol= 0.3
Flow Tol Ratio= 0.001
Split Flow NTrial= 30
Split Flow Tol= 0.02
Split Flow Ratio= 0.02
Log Output Level= 0
Friction Slope Method= 1
Unsteady Friction Slope Method= 2
Unsteady Bridges Friction Slope Method= 1
Parabolic Critical Depth
Global Vel Dist=  1 , 1 , 1
Global Log Level= 0
CheckData=True
Encroach Param= -1, 0, 0, 0
BEGIN DESCRIPTION:
Multiple Run
END DESCRIPTION:

--- RED OAK CR TRIB 7 1.f01 (steady flow) ---

Flow Title=Multiple
Program Version=4.10
Number of Profiles= 7
Profile Names=10-year,25-year,50-year,1pct_min,100-year,1pct_plu,500-year
River Rch & RM=RED OAK CR TRIB,Reach-1         ,1328
     337     434     510     439     594     803     801
Boundary for River Rch & Prof#=RED OAK CR TRIB,Reach-1         , 1
Up Type= 0
Dn Type= 3
Dn Slope=0.0078
Boundary for River Rch & Prof#=RED OAK CR TRIB,Reach-1         , 2
Up Type= 0
Dn Type= 3
Dn Slope=0.0078
Boundary for River Rch & Prof#=RED OAK CR TRIB,Reach-1         , 3
Up Type= 0
Dn Type= 3
Dn Slope=0.0078
Boundary for River Rch & Prof#=RED OAK CR TRIB,Reach-1         , 4
Up Type= 0
Dn Type= 3
Dn Slope=0.0078
Boundary for River Rch & Prof#=RED OAK CR TRIB,Reach-1         , 5
Up Type= 0
Dn Type= 3
Dn Slope=0.0078
Boundary for River Rch & Prof#=RED OAK CR TRIB,Reach-1         , 6
Up Type= 0
Dn Type= 3
Dn Slope=0.0078
Boundary for River Rch & Prof#=RED OAK CR TRIB,Reach-1         , 7
Up Type= 0
Dn Type= 3
Dn Slope=0.0078
DSS Import GetInterval= 0
DSS Import GetPeak= 0
DSS Import FillOption= 0

--- RED OAK CR TRIB 7 1.g01 (geometry) ---

Geom Title=Existing Conditions
Program Version=4.10

River Reach=RED OAK CR TRIB ,Reach-1
Reach XY= 30
      3541997.11     10413906.64      3542046.18     10413963.83
      3542114.92     10414006.61      3542199.77      10414080.5
      3542234.92     10414138.66      3542282.93     10414202.63
      3542312.16     10414230.64      3542341.04     10414252.83
      3542366.58     10414283.47      3542403.04     10414307.48
      3542420.31     10414337.67       3542448.7     10414368.09
      3542478.92     10414387.85       3542571.8     10414434.05
      3542593.88      10414455.1      3542597.15     10414470.27
      3542585.02     10414497.48      3542582.34     10414526.39
      3542599.18     10414637.19      3542592.95     10414676.96
      3542594.76     10414700.48      3542605.02     10414730.43
      3542624.36      10414760.6      3542636.27     10414773.67
      3542664.99     10414795.53      3542678.64     10414813.01
      3542692.85     10414846.29      3542708.73     10414873.03
      3542729.41     10414922.76      3542742.11     10414971.64

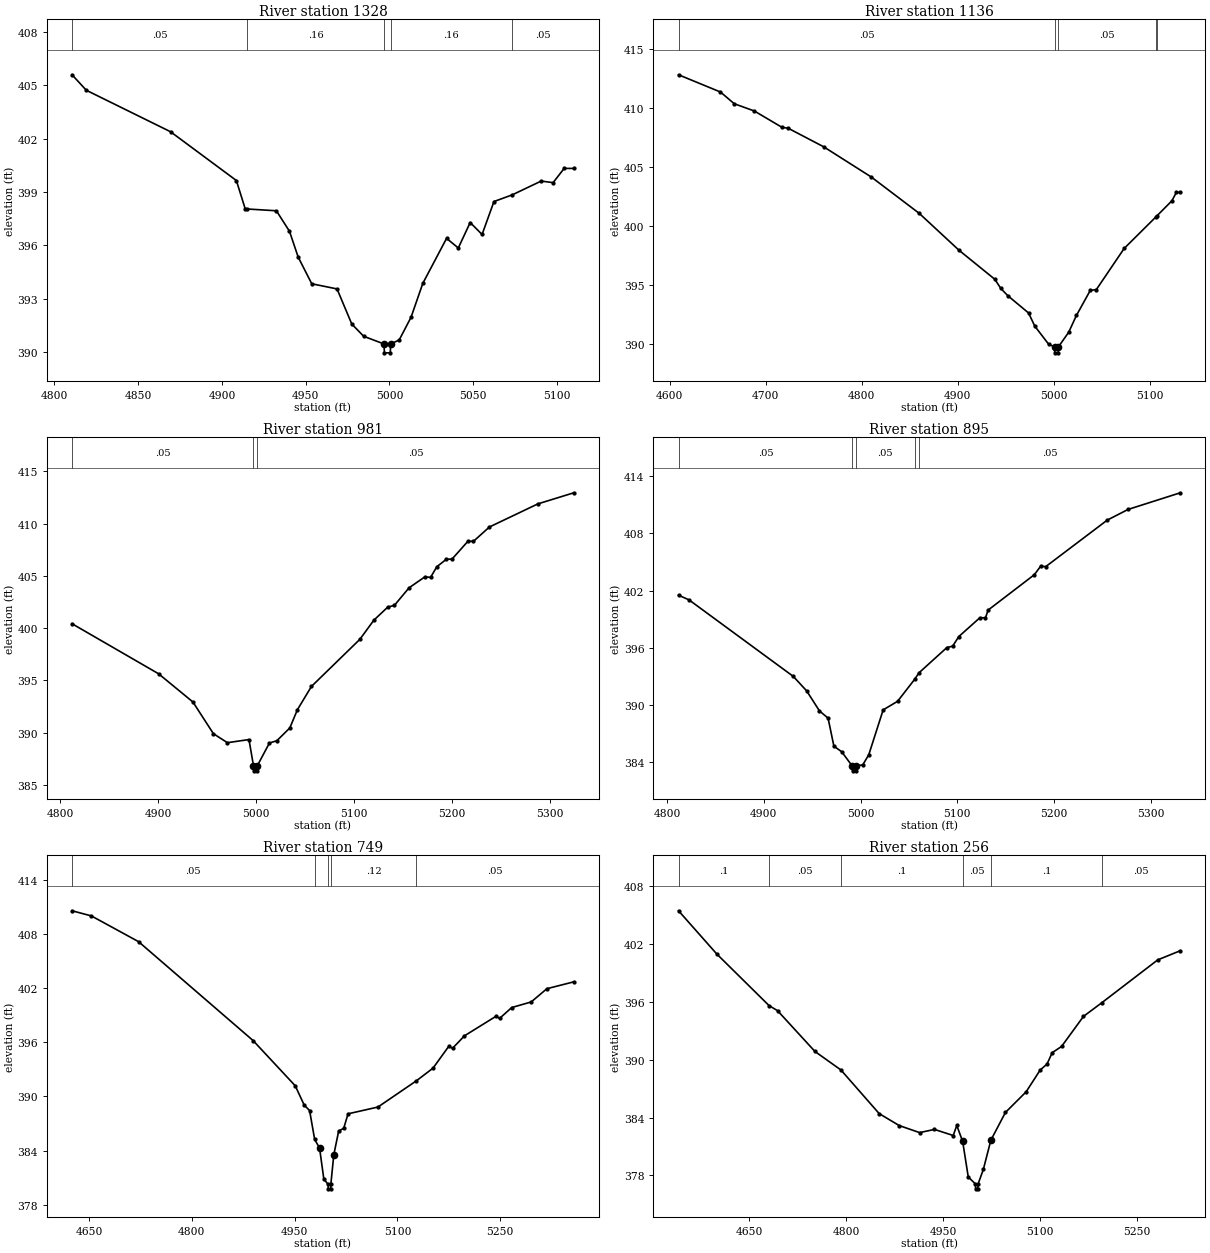
Type RM Length L Ch R = 1 ,1328    ,192,192,192
BEGIN DESCRIPTION:
RED OAK CR TRIB 7 1 2 0
END DESCRIPTION:
XS GIS Cut Line= 3
      3541866.36     10414028.46      3542016.41     10413978.45
      3542116.42     10413878.44
#Sta/Elev= 30
  4810.5  405.58    4819  404.71  4869.3  402.38  4908.6  399.64  4913.9  398.04
  4915.2  398.04  4932.5  397.94  4940.3  396.79  4945.5  395.34  4953.6  393.84
  4968.7  393.55  4977.5  391.58  4984.6  390.89  4996.7  390.46    4997  389.96
  5000.5  389.96  5000.7  390.46  5005.8  390.68  5012.9  391.96  5019.9  393.86
  5034.1  396.39  5041.1  395.85  5048.2  397.28  5055.3  396.61  5062.4  398.46
  5073.2  398.83  5090.6  399.61  5097.7  399.52  5104.3  400.32  5110.1  400.32
#Mann= 5 ,-1 , 0
  4810.5     .05       0  4915.2     .16       0  4996.7     .07       0
  5000.7     .16       0  5073.2     .05       0
Bank Sta=4996.7,5000.7
XS Rating Curve= 0 ,0
Exp/Cntr=0.3,0.1

Type RM Length L Ch R = 1 ,1136    ,155,155,155
BEGIN DESCRIPTION:
RED OAK CR TRIB 7 1 2 4
END DESCRIPTION:
XS GIS Cut Line= 2
      3541882.29     10414313.16      3542293.56     10413990.87
#Sta/Elev= 30
  4609.2  412.79  4652.8  411.33  4667.3  410.33  4688.1  409.72    4717  408.33
  4723.3  408.26  4760.4  406.68  4810.1  404.11  4859.8  401.04  4901.4   397.9
  4938.5  395.45  4944.8  394.67    4952  394.06  4973.7  392.59  4980.1  391.48
  4994.5  389.95  5000.7  389.71  5000.9  389.21  5004.4  389.21  5004.7  389.71
  5015.5  390.96  5023.5  392.38  5037.9   394.5  5044.3  394.58  5073.2  398.06
  5106.2  400.73  5106.9  400.79  5122.9   402.1  5127.6  402.82  5131.7  402.82
#Mann= 5 ,-1 , 0
  4609.2     .05       0  5000.7     .03       0  5004.7     .05       0
  5106.2     .16       0  5106.9     .05       0
Bank Sta=5000.7,5004.7
XS Rating Curve= 0 ,0
Exp/Cntr=0.3,0.1

Type RM Length L Ch R = 1 ,981     ,86,86,86
BEGIN DESCRIPTION:
RED OAK CR TRIB 7 1 2 3
END DESCRIPTION:
XS GIS Cut Line= 3
      3542158.14     10414341.66      3542369.94     10414089.92
      3542456.75     10413928.46
#Sta/Elev= 30
  4812.1  400.42  4900.4  395.64  4935.5  392.94  4956.4  389.91  4970.7  389.05
  4992.7  389.35  4997.3  386.86  4997.5  386.36    5001  386.36  5001.3  386.86
  5013.6  389.02  5021.2  389.24  5034.4  390.46  5042.2  392.21  5056.5  394.43
  5105.9  398.93  5120.2  400.76  5134.5  402.02  5141.1  402.17  5156.2  403.86
  5172.4  404.91  5178.1  404.85  5184.5  405.87  5194.3  406.59    5200   406.6
  5216.3  408.31  5221.9   408.3  5238.2  409.67  5287.7  411.88  5324.4  412.94
#Mann= 3 ,-1 , 0
  4812.1     .05       0  4997.3     .03       0  5001.3     .05       0
Bank Sta=4997.3,5001.3
XS Rating Curve= 0 ,0
Exp/Cntr=0.3,0.1

Type RM Length L Ch R = 1 ,895     ,146,146,146
BEGIN DESCRIPTION:
RED OAK CR TRIB 7 1 2 2
END DESCRIPTION:
XS GIS Cut Line= 3
        3542238.      10414411.1      3542415.08     10414150.68
      3542489.75      10413961.4
#Sta/Elev= 30
    4812  401.52  4822.8  401.03  4930.6  392.99  4944.4  391.47  4957.6  389.37
  4966.5  388.61  4972.5  385.67  4980.6  385.08  4991.5  383.58  4991.8  383.08
  4995.3  383.08  4995.5  383.58  5002.4  383.72  5008.5  384.76  5023.4  389.48
  5038.3  390.38  5055.8  392.67  5060.5  393.38  5089.2  396.02  5095.2  396.17
  5101.6  397.18  5123.3  399.15  5129.1  399.15  5131.9  399.96  5179.6  403.67
    5186  404.55  5191.4  404.52  5254.9   409.4  5276.4  410.52  5330.4  412.27
#Mann= 5 ,-1 , 0
    4812     .05       0  4991.5     .03       0  4995.5     .05       0
  5055.8     .12       0  5060.5     .05       0
Bank Sta=4991.5,4995.5
XS Rating Curve= 0 ,0
Exp/Cntr=0.3,0.1

Type RM Length L Ch R = 1 ,749     ,493,493,493
BEGIN DESCRIPTION:
RED OAK CR TRIB 7 1 2 1
END DESCRIPTION:
XS GIS Cut Line= 4
      3542102.63     10414518.19      3542393.39     10414396.68
      3542531.19     10414291.43      3542633.17     10414070.12
#Sta/Elev= 30
  4625.3  410.56  4653.5  409.99  4722.3  407.14  4889.5  396.18    4951  391.17
    4964  389.04  4971.9  388.43  4979.3  385.23  4986.4  384.29  4992.7  380.83
  4998.9  380.26  4999.2  379.76  5002.7  379.76  5002.9  380.26  5007.2  383.53
  5014.3  386.16  5021.7  386.47    5028  388.07  5071.6  388.82  5127.8  391.73
    5152  393.13  5174.9  395.54  5180.5  395.33  5197.9  396.71  5243.8  398.87
  5249.3  398.65  5266.8  399.84  5295.2  400.46  5318.2  401.93  5357.5  402.69
#Mann= 5 ,-1 , 0
  4625.3     .05       0  4979.3     .12       0  4998.9     .07       0
  5002.9     .12       0  5127.8     .05       0
Bank Sta=4986.4,5007.2
XS Rating Curve= 0 ,0
Exp/Cntr=0.3,0.1

Type RM Length L Ch R = 1 ,256     ,0,0,0
BEGIN DESCRIPTION:
RED OAK CR TRIB 7 1 1 0
END DESCRIPTION:
XS GIS Cut Line= 4
       3542197.9     10414655.16      3542524.25     10414795.77
      3542729.11     10414705.49      3542811.67     10414524.89
#Sta/Elev= 30
  4540.1  405.44  4599.5  400.95  4680.4  395.61  4693.6  395.08  4751.6  390.85
  4791.9  388.93  4851.1  384.41  4882.2  383.17  4913.8  382.44  4936.8  382.77
  4965.9  382.14  4971.4  383.18  4980.5  381.53  4989.2  377.84  5000.4  377.11
  5000.6  376.61  5004.1  376.61  5004.4  377.11  5012.6  378.63  5024.2  381.65
  5046.8  384.53  5078.9  386.67  5100.7  388.93  5111.3  389.55  5119.3  390.73
  5133.8  391.37  5167.8  394.49  5196.3  395.91  5282.9  400.35  5317.9   401.3
#Mann= 6 ,-1 , 0
  4540.1      .1       0  4680.4     .05       0  4791.9      .1       0
  4980.5     .05       0  5024.2      .1       0  5196.3     .05       0
Bank Sta=4980.5,5024.2
XS Rating Curve= 0 ,0
Exp/Cntr=0.3,0.1

Chan Stop Cuts=-1
Use User Specified Reach Order=0
Composite Channel Slope=5