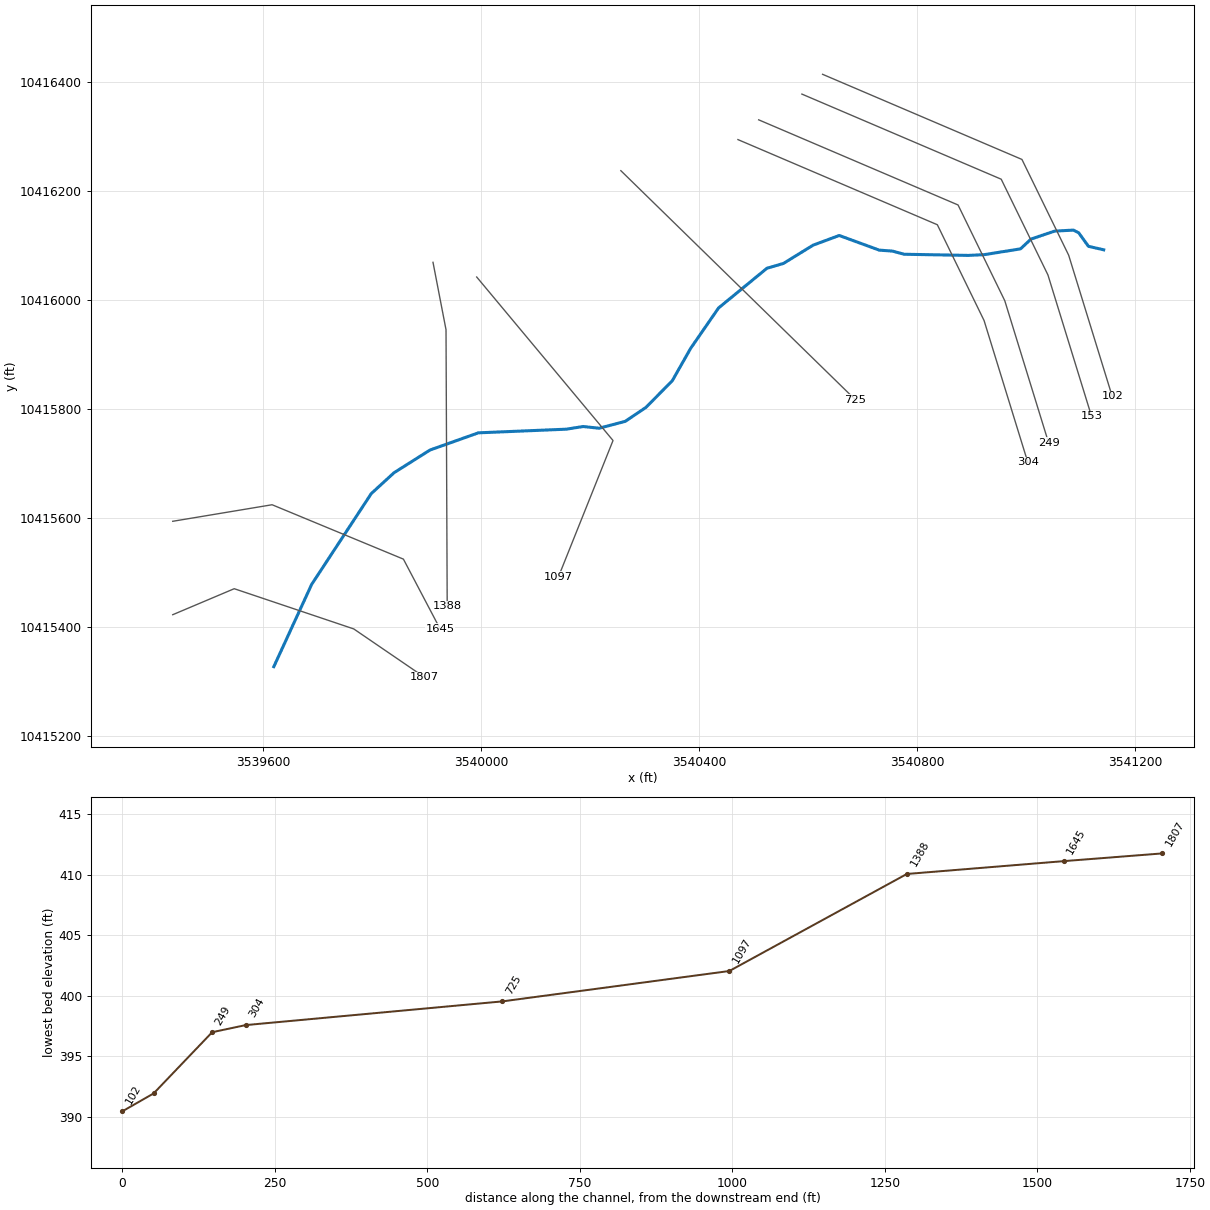
--- RED OAK CR TRIB 7 2.prj (project) ---

Proj Title=RED OAK CR TRIB 7 2 Base Level Engineering
Current Plan=p01
Default Exp/Contr=0.3,0.1
English Units
Geom File=g01
Flow File=f01
Plan File=p01
Y Axis Title=Elevation
X Axis Title(PF)=Main Channel Distance
X Axis Title(XS)=Station
BEGIN DESCRIPTION:
RED OAK CR TRIB 7 2
END DESCRIPTION:
DSS Export Rating Curves= 0
DSS Export Rating Curve Sorted= 0
DSS Export Volume Flow Curves= 0
DXF OffsetX= 0
DXF OffsetY= 0
DXF ScaleX= 1
DXF ScaleY= 10

--- RED OAK CR TRIB 7 2.p01 (plan) ---

Plan Title=Multiple Run
Short Identifier=Multiple
Geom File=g01
Flow File=f01
Subcritical Flow
K Sum by GR= 0
Std Step Tol= 0.01
Critical Tol= 0.01
Num of Std Step Trials= 20
Max Error Tol= 0.3
Flow Tol Ratio= 0.001
Split Flow NTrial= 30
Split Flow Tol= 0.02
Split Flow Ratio= 0.02
Log Output Level= 0
Friction Slope Method= 1
Unsteady Friction Slope Method= 2
Unsteady Bridges Friction Slope Method= 1
Parabolic Critical Depth
Global Vel Dist=  1 , 1 , 1
Global Log Level= 0
CheckData=True
Encroach Param= -1, 0, 0, 0
BEGIN DESCRIPTION:
Multiple Run
END DESCRIPTION:

--- RED OAK CR TRIB 7 2.f01 (steady flow) ---

Flow Title=Multiple
Program Version=4.10
Number of Profiles= 7
Profile Names=10-year,25-year,50-year,1pct_min,100-year,1pct_plu,500-year
River Rch & RM=RED OAK CR TRIB,Reach-1         ,1807
     621     835    1009     891    1205    1630    1714
Boundary for River Rch & Prof#=RED OAK CR TRIB,Reach-1         , 1
Up Type= 0
Dn Type= 3
Dn Slope=0.005
Boundary for River Rch & Prof#=RED OAK CR TRIB,Reach-1         , 2
Up Type= 0
Dn Type= 3
Dn Slope=0.005
Boundary for River Rch & Prof#=RED OAK CR TRIB,Reach-1         , 3
Up Type= 0
Dn Type= 3
Dn Slope=0.005
Boundary for River Rch & Prof#=RED OAK CR TRIB,Reach-1         , 4
Up Type= 0
Dn Type= 3
Dn Slope=0.005
Boundary for River Rch & Prof#=RED OAK CR TRIB,Reach-1         , 5
Up Type= 0
Dn Type= 3
Dn Slope=0.005
Boundary for River Rch & Prof#=RED OAK CR TRIB,Reach-1         , 6
Up Type= 0
Dn Type= 3
Dn Slope=0.005
Boundary for River Rch & Prof#=RED OAK CR TRIB,Reach-1         , 7
Up Type= 0
Dn Type= 3
Dn Slope=0.005
DSS Import GetInterval= 0
DSS Import GetPeak= 0
DSS Import FillOption= 0

--- RED OAK CR TRIB 7 2.g01 (geometry) ---

Geom Title=Existing Conditions
Program Version=4.10

River Reach=RED OAK CR TRIB ,Reach-1
Reach XY= 30
      3539619.93     10415326.59      3539689.37     10415477.63
      3539798.75      10415644.3      3539840.42     10415682.49
      3539906.39     10415724.16      3539995.12     10415755.74
      3540156.85     10415762.45       3540187.2     10415767.34
      3540216.71     10415764.19      3540264.59     10415776.84
      3540302.55     10415802.44      3540350.87     10415851.39
      3540384.43     10415910.68      3540435.73     10415984.94
      3540524.38      10416057.7      3540554.76     10416066.63
      3540609.21     10416100.18      3540657.02     10416117.89
      3540730.44     10416091.02      3540754.92      10416089.2
      3540776.01     10416083.47      3540893.41     10416081.34
      3540922.89     10416082.69      3540989.55     10416093.37
      3541008.82     10416111.34       3541052.2     10416125.95
      3541086.57     10416127.73      3541096.26     10416122.85
      3541114.17     10416097.96      3541142.11     10416091.64

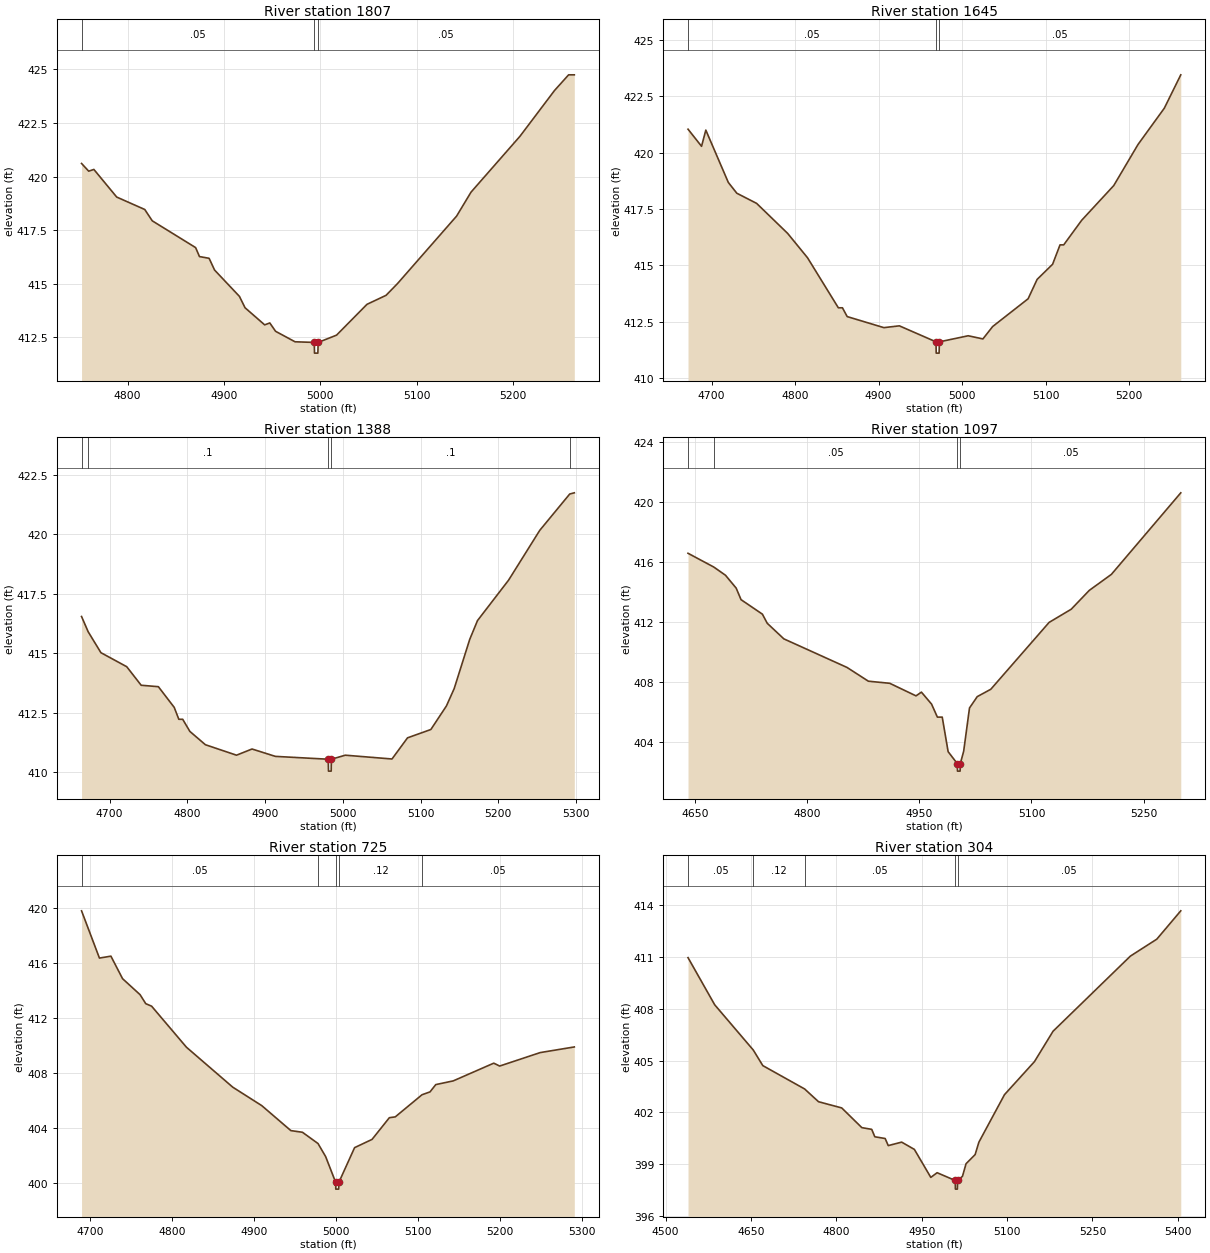
Type RM Length L Ch R = 1 ,1807    ,162,162,162
BEGIN DESCRIPTION:
RED OAK CR TRIB 7 2 6 0
END DESCRIPTION:
XS GIS Cut Line= 4
      3539434.54     10415421.97      3539547.34     10415469.69
      3539766.53     10415395.91      3539896.77     10415306.91
#Sta/Elev= 30
  4752.3  420.61  4759.7  420.25  4765.1  420.33  4788.8  419.04  4817.9  418.46
  4825.7  417.93  4870.7  416.68  4874.7  416.26  4884.7  416.18  4890.4  415.63
  4916.2   414.4    4922  413.87  4942.4  413.07  4947.7  413.16  4953.7  412.77
  4973.9  412.28  4993.9  412.25  4994.1  411.75  4997.6  411.75  4997.9  412.25
    5017  412.59  5048.6  414.03  5068.4  414.45  5080.3     415  5141.6  418.15
  5156.6  419.27  5207.4  421.88  5243.3  424.02  5257.9  424.75  5263.8  424.75
#Mann= 3 ,-1 , 0
  4752.3     .05       0  4993.9    .035       0  4997.9     .05       0
Bank Sta=4993.9,4997.9
XS Rating Curve= 0 ,0
Exp/Cntr=0.3,0.1

Type RM Length L Ch R = 1 ,1645    ,257,257,257
BEGIN DESCRIPTION:
Mapping XS 48b6ade6
END DESCRIPTION:
XS GIS Cut Line= 4
      3539434.53      10415593.4      3539616.79     10415623.77
      3539857.67     10415523.95      3539924.73     10415396.31
#Sta/Elev= 30
  4671.9  421.04  4688.1  420.28  4693.2     421  4720.1  418.68  4730.3   418.2
    4754  417.75  4791.1  416.42  4814.9  415.34  4851.8  413.12  4856.7  413.12
  4862.4  412.73  4906.3  412.24  4924.8  412.32  4968.7  411.61  4968.9  411.11
  4972.4  411.11  4972.7  411.61  5007.2  411.88  5024.8  411.74  5036.5  412.29
  5078.9  413.52  5089.7  414.38  5108.2  415.05  5117.1  415.91  5121.5  415.91
    5143     417  5181.4  418.54  5210.4  420.36  5241.9  421.97  5261.6  423.45
#Mann= 3 ,-1 , 0
  4671.9     .05       0  4968.7    .035       0  4972.7     .05       0
Bank Sta=4968.7,4972.7
XS Rating Curve= 0 ,0
Exp/Cntr=0.3,0.1

Type RM Length L Ch R = 1 ,1388    ,291,291,291
BEGIN DESCRIPTION:
Mapping XS eb22682b
END DESCRIPTION:
XS GIS Cut Line= 3
      3539911.92     10416068.66       3539935.8     10415944.95
      3539937.97     10415437.15
#Sta/Elev= 30
    4664  416.55  4672.5  415.91  4688.9  415.03  4722.1  414.44  4740.7  413.66
  4762.8   413.6  4783.2  412.73  4789.1  412.23  4794.1  412.23  4803.3  411.72
  4823.3  411.16  4863.3  410.72  4883.3  410.98  4913.3  410.67  4981.3  410.55
  4981.6  410.05  4985.1  410.05  4985.3  410.55  5003.3  410.72  5063.3  410.56
  5083.3  411.45  5113.3   411.8  5133.3  412.79  5143.3  413.52  5163.3  415.59
  5173.3  416.38  5213.3  418.08  5253.3  420.17  5291.9   421.7  5297.8  421.75
#Mann= 5 ,-1 , 0
    4664     .05       0  4672.5      .1       0  4981.3     .07       0
  4985.3      .1       0  5291.9     .05       0
Bank Sta=4981.3,4985.3
XS Rating Curve= 0 ,0
Exp/Cntr=0.3,0.1

Type RM Length L Ch R = 1 ,1097    ,372,372,372
BEGIN DESCRIPTION:
RED OAK CR TRIB 7 2 6 0
END DESCRIPTION:
XS GIS Cut Line= 3
      3539992.08     10416041.68      3540242.11     10415741.64
      3540142.11     10415491.66
#Sta/Elev= 30
  4640.1  416.59  4674.6  415.67  4690.3  415.12  4704.6  414.26  4711.1  413.49
  4739.7  412.52  4746.2  411.91  4768.4  410.87    4853  408.96  4881.6  408.04
  4910.2   407.9  4945.4  407.06  4952.6  407.31  4966.2  406.51    4974  405.64
  4980.5  405.64  4988.4  403.33  5000.7  402.53  5000.9  402.03  5004.4  402.03
  5004.7  402.53  5009.2  403.36    5017  406.25  5027.4  407.01  5045.5   407.5
  5123.6  411.97  5153.2  412.85  5177.4  414.11    5207  415.18  5299.9  420.63
#Mann= 4 ,-1 , 0
  4640.1      .1       0  4674.6     .05       0  5000.7    .035       0
  5004.7     .05       0
Bank Sta=5000.7,5004.7
XS Rating Curve= 0 ,0
Exp/Cntr=0.3,0.1

Type RM Length L Ch R = 1 ,725     ,421,421,421
BEGIN DESCRIPTION:
RED OAK CR TRIB 7 2 5 0
END DESCRIPTION:
XS GIS Cut Line= 2
      3540256.48     10416236.82      3540686.17      10415816.9
#Sta/Elev= 30
  4689.6  419.78  4711.4  416.34  4725.4  416.48  4739.6  414.84  4760.9  413.68
  4767.9  413.02    4775  412.84  4817.5  409.85    4874  406.94  4909.3   405.6
  4944.8  403.78  4958.9  403.66  4977.9  402.84  4987.2  401.89  4999.4  400.02
  4999.6  399.52  5003.1  399.52  5003.4  400.02  5022.5  402.54  5043.8  403.14
  5064.9  404.72  5072.1  404.78  5104.7  406.39  5114.5   406.6  5121.5  407.13
  5142.8   407.4  5192.2  408.69  5199.4  408.48  5248.8  409.46  5290.4  409.87
#Mann= 5 ,-1 , 0
  4689.6     .05       0  4977.9     .12       0  4999.4     .07       0
  5003.4     .12       0  5104.7     .05       0
Bank Sta=4999.4,5003.4
XS Rating Curve= 0 ,0
Exp/Cntr=0.3,0.1

Type RM Length L Ch R = 1 ,304     ,55,55,55
BEGIN DESCRIPTION:
RED OAK CR TRIB 7 2 2 0
END DESCRIPTION:
XS GIS Cut Line= 4
      3540471.26     10416293.87      3540836.97     10416137.61
      3540922.69     10415961.83      3541002.99     10415701.39
#Sta/Elev= 30
  4539.5  410.96  4586.4  408.23  4654.2  405.61  4670.9  404.71  4744.3  403.36
  4768.8  402.62  4809.6  402.26  4844.9  401.12  4862.3  401.02  4867.7  400.59
  4885.9  400.49  4891.3  400.08  4914.9  400.28  4937.2  399.86  4966.1  398.24
  4977.2  398.51    5009  398.06  5009.3  397.56  5012.8  397.56    5013  398.06
  5021.7   398.3    5028  399.03    5044  399.56  5050.6  400.28  5095.6  403.03
  5148.2  404.94  5180.9   406.7  5316.8  411.05  5363.2  412.03  5405.3  413.67
#Mann= 5 ,-1 , 0
  4539.5     .05       0  4654.2     .12       0  4744.3     .05       0
    5009     .03       0    5013     .05       0
Bank Sta=5009,5013
XS Rating Curve= 0 ,0
Exp/Cntr=0.3,0.1

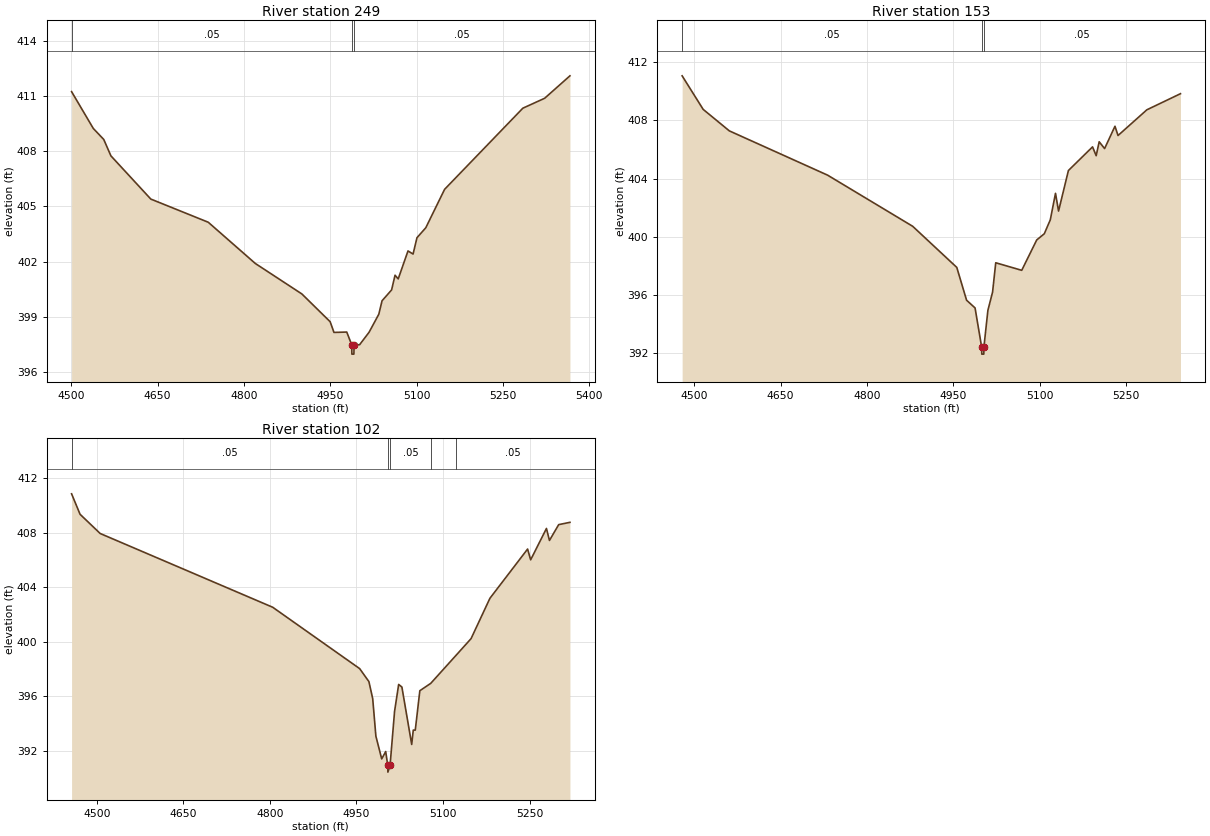
Type RM Length L Ch R = 1 ,249     ,96,96,96
BEGIN DESCRIPTION:
RED OAK CR TRIB 7 2 4 0
END DESCRIPTION:
XS GIS Cut Line= 4
       3540509.3     10416330.14      3540874.97     10416173.89
       3540960.7     10415998.11      3541040.98     10415737.73
#Sta/Elev= 30
  4500.7  411.24  4538.4  409.24  4556.6  408.64    4569  407.75  4638.3   405.4
  4738.1  404.14  4819.8   401.9  4900.8  400.24  4949.9  398.73  4956.5  398.15
  4978.7  398.17  4987.4  397.47  4987.6  396.97  4991.1  396.97  4991.4  397.47
    5001  397.48  5017.5  398.16  5034.4  399.14    5040  399.87  5056.6  400.46
  5062.6  401.26  5068.1  401.06  5085.1  402.58  5093.9  402.41  5100.7   403.3
    5116  403.84  5148.7  405.93  5284.6  410.34  5322.5  410.88  5366.4   412.1
#Mann= 3 ,-1 , 0
  4500.7     .05       0  4987.4     .03       0  4991.4     .05       0
Bank Sta=4987.4,4991.4
XS Rating Curve= 0 ,0
Exp/Cntr=0.3,0.1

Type RM Length L Ch R = 1 ,153     ,51,51,51
BEGIN DESCRIPTION:
RED OAK CR TRIB 7 2 3 0
END DESCRIPTION:
XS GIS Cut Line= 4
      3540588.53     10416377.39      3540954.15     10416221.16
      3541039.87     10416045.38      3541119.91     10415785.81
#Sta/Elev= 30
  4479.3  411.07  4515.8  408.76  4561.2  407.28  4731.8  404.23  4879.4  400.71
  4955.9  397.88  4972.9  395.62  4987.6  395.09    4999  392.41  4999.3  391.91
  5002.8  391.91    5003  392.41  5009.9  394.93    5018  396.18  5023.5   398.2
  5068.6  397.68  5094.6  399.77  5107.8   400.2  5118.2  401.16  5127.2  402.98
  5132.5  401.76  5149.6  404.55  5191.5  406.18  5197.8  405.57    5203  406.53
  5212.4  406.06  5230.4   407.6  5235.7  406.96  5285.7  408.73  5344.1  409.84
#Mann= 3 ,-1 , 0
  4479.3     .05       0    4999     .03       0    5003     .05       0
Bank Sta=4999,5003
XS Rating Curve= 0 ,0
Exp/Cntr=0.3,0.1

Type RM Length L Ch R = 1 ,102     ,0,0,0
BEGIN DESCRIPTION:
RED OAK CR TRIB 7 2 1 0
END DESCRIPTION:
XS GIS Cut Line= 4
      3540626.49     10416413.69      3540992.16     10416257.44
      3541077.88     10416081.66      3541157.64       10415823.
#Sta/Elev= 30
  4456.2  410.85  4470.9  409.35  4505.8  407.94  4804.9  402.53  4955.6  398.03
  4971.6  397.08  4978.2  395.83  4983.7  393.08  4993.8  391.41  5000.7  391.95
  5004.3  390.94  5004.5  390.44  5008.3  390.94  5016.1   394.9  5023.2  396.87
  5028.8  396.68  5045.8  392.47  5048.5  393.52    5052  393.52  5059.9  396.41
  5078.8  396.95  5123.4  399.04  5148.7  400.23  5181.4  403.19  5246.7   406.8
    5252  406.01  5279.4  408.31  5284.6  407.43  5300.6  408.59  5320.1  408.76
#Mann= 5 ,-1 , 0
  4456.2     .05       0  5004.3     .03       0  5008.3     .05       0
  5078.8     .12       0  5123.4     .05       0
Bank Sta=5004.3,5008.3
XS Rating Curve= 0 ,0
Exp/Cntr=0.3,0.1

Chan Stop Cuts=-1
Use User Specified Reach Order=0
Composite Channel Slope=5