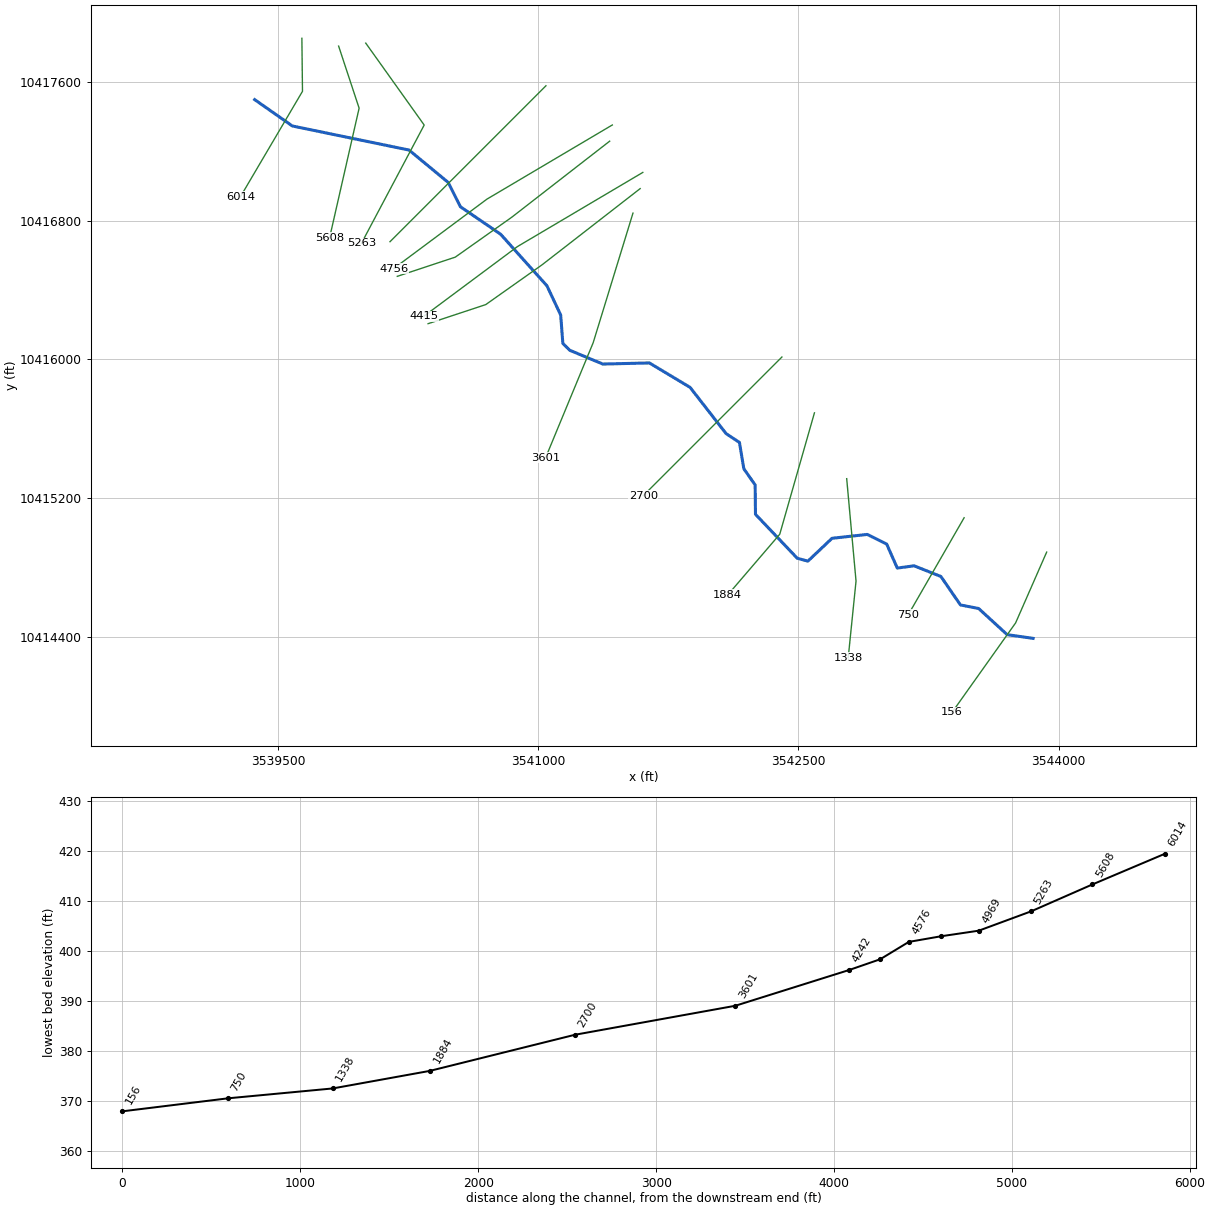
--- RED OAK CR TRIB 7.prj (project) ---

Proj Title=RED OAK CR TRIB 7 Base Level Engineering
Current Plan=p01
Default Exp/Contr=0.3,0.1
English Units
Geom File=g01
Flow File=f01
Plan File=p01
Y Axis Title=Elevation
X Axis Title(PF)=Main Channel Distance
X Axis Title(XS)=Station
BEGIN DESCRIPTION:
RED OAK CR TRIB 7
END DESCRIPTION:
DSS Export Rating Curves= 0
DSS Export Rating Curve Sorted= 0
DSS Export Volume Flow Curves= 0
DXF OffsetX= 0
DXF OffsetY= 0
DXF ScaleX= 1
DXF ScaleY= 10

--- RED OAK CR TRIB 7.p01 (plan) ---

Plan Title=Multiple Run
Short Identifier=Multiple
Geom File=g01
Flow File=f01
Subcritical Flow
K Sum by GR= 0
Std Step Tol= 0.01
Critical Tol= 0.01
Num of Std Step Trials= 20
Max Error Tol= 0.3
Flow Tol Ratio= 0.001
Split Flow NTrial= 30
Split Flow Tol= 0.02
Split Flow Ratio= 0.02
Log Output Level= 0
Friction Slope Method= 1
Unsteady Friction Slope Method= 2
Unsteady Bridges Friction Slope Method= 1
Parabolic Critical Depth
Global Vel Dist=  1 , 1 , 1
Global Log Level= 0
CheckData=True
Encroach Param= -1, 0, 0, 0
BEGIN DESCRIPTION:
Multiple Run
END DESCRIPTION:

--- RED OAK CR TRIB 7.f01 (steady flow) ---

Flow Title=Multiple
Program Version=4.10
Number of Profiles= 7
Profile Names=10-year,25-year,50-year,1pct_min,100-year,1pct_plu,500-year
River Rch & RM=RED OAK CR TRIB,Reach-1         ,6014
     653     882    1068     947    1281    1732    1832
River Rch & RM=RED OAK CR TRIB,Reach-1         ,3601
    1173    1641    2033    1840    2488    3364    3713
River Rch & RM=RED OAK CR TRIB,Reach-1         ,1338
    1430    2021    2522    2296    3105    4199    4695
Boundary for River Rch & Prof#=RED OAK CR TRIB,Reach-1         , 1
Up Type= 0
Dn Type= 3
Dn Slope=0.00385
Boundary for River Rch & Prof#=RED OAK CR TRIB,Reach-1         , 2
Up Type= 0
Dn Type= 3
Dn Slope=0.00385
Boundary for River Rch & Prof#=RED OAK CR TRIB,Reach-1         , 3
Up Type= 0
Dn Type= 3
Dn Slope=0.00385
Boundary for River Rch & Prof#=RED OAK CR TRIB,Reach-1         , 4
Up Type= 0
Dn Type= 3
Dn Slope=0.00385
Boundary for River Rch & Prof#=RED OAK CR TRIB,Reach-1         , 5
Up Type= 0
Dn Type= 3
Dn Slope=0.00385
Boundary for River Rch & Prof#=RED OAK CR TRIB,Reach-1         , 6
Up Type= 0
Dn Type= 3
Dn Slope=0.00385
Boundary for River Rch & Prof#=RED OAK CR TRIB,Reach-1         , 7
Up Type= 0
Dn Type= 3
Dn Slope=0.00385
DSS Import GetInterval= 0
DSS Import GetPeak= 0
DSS Import FillOption= 0

--- RED OAK CR TRIB 7.g01 (geometry) ---

Geom Title=Existing Conditions
Program Version=4.10

River Reach=RED OAK CR TRIB ,Reach-1
Reach XY= 30
      3539366.01     10417496.82      3539583.02     10417344.91
      3540255.77     10417206.03      3540481.53     10417019.35
      3540551.74     10416879.39      3540783.07      10416721.4
      3541050.44     10416423.66       3541129.6      10416255.6
      3541142.11     10416091.64      3541182.23     10416051.94
       3541372.6     10415972.63      3541640.88     10415979.08
      3541875.25     10415838.34       3542082.8      10415571.9
      3542159.78     10415520.84      3542185.05     10415369.29
      3542250.44     10415275.75      3542252.22     10415106.71
      3542493.06     10414853.36      3542554.41     10414836.75
      3542693.47     10414968.35       3542896.6     10414990.71
      3543008.53     10414934.93      3543069.39     10414796.82
      3543166.75     10414809.81      3543320.79     10414748.38
       3543433.5     10414584.12      3543538.33     10414563.76
      3543702.78     10414413.08      3543852.11     10414391.64

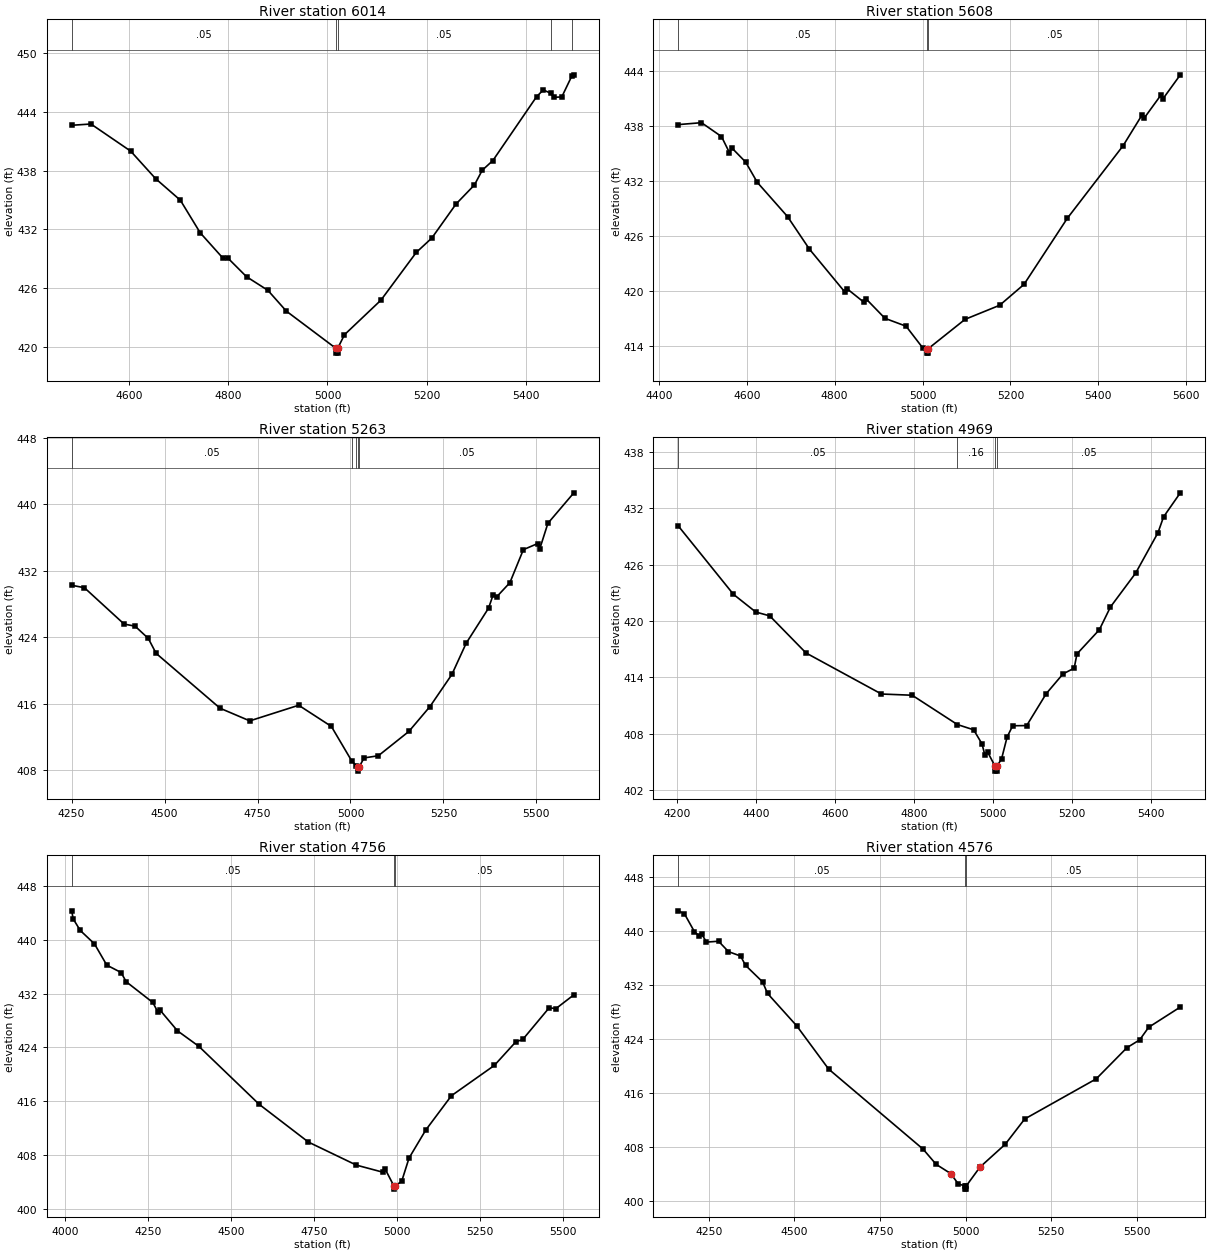
Type RM Length L Ch R = 1 ,6014    ,406,406,406
BEGIN DESCRIPTION:
RED OAK CR TRIB 7 2 1 1
END DESCRIPTION:
XS GIS Cut Line= 3
      3539638.17     10417850.24      3539641.64     10417544.67
      3539283.98       10416937.
#Sta/Elev= 30
  4485.3  442.62  4523.9  442.75  4603.9  439.98  4653.9  437.18  4703.9  434.97
  4743.9  431.64  4789.9  429.04    4800  429.04  4837.1  427.16  4880.1  425.77
  4917.2  423.65  5016.7  419.86  5016.9  419.36  5020.4  419.36  5020.7  419.86
  5034.3  421.24  5107.7  424.77  5178.8  429.64  5210.1  431.11  5258.8  434.58
  5295.9  436.53  5311.6  438.03    5333  439.02    5421  445.54  5434.5  446.23
  5449.3  445.89    5456  445.48  5471.7  445.51  5492.4   447.7    5496  447.77
#Mann= 5 ,-1 , 0
  4485.3     .05       0  5016.7     .03       0  5020.7     .05       0
  5449.3     .08       0  5492.4     .05       0
Bank Sta=5016.7,5020.7
XS Rating Curve= 0 ,0
Exp/Cntr=0.3,0.1

Type RM Length L Ch R = 1 ,5608    ,345,345,345
BEGIN DESCRIPTION:
Mapping XS 2add3640
END DESCRIPTION:
XS GIS Cut Line= 3
      3539849.96     10417805.13      3539968.03     10417447.45
      3539797.89     10416700.95
#Sta/Elev= 30
  4444.1  438.13    4497  438.34  4542.5  436.83  4560.5  435.09  4565.7  435.61
  4597.5  434.05    4624  431.84  4692.7  428.12  4742.6  424.57  4823.2   419.9
  4828.4  420.25  4866.3   418.8  4871.4  419.16  4914.4  417.04  4962.5  416.18
  5000.4  413.82  5009.3  413.75  5009.6  413.25  5013.1  413.25  5013.3  413.75
  5096.7  416.93  5175.4  418.46  5230.9  420.74  5329.3  427.93  5456.2  435.83
  5499.2  439.17  5504.4  438.85  5542.2  441.34  5547.4  440.97  5586.4  443.55
#Mann= 3 ,-1 , 0
  4444.1     .05       0  5009.3     .03       0  5013.3     .05       0
Bank Sta=5009.3,5013.3
XS Rating Curve= 0 ,0
Exp/Cntr=0.3,0.1

Type RM Length L Ch R = 1 ,5263    ,294,294,294
BEGIN DESCRIPTION:
Mapping XS ef6560e4
END DESCRIPTION:
XS GIS Cut Line= 3
      3540006.21     10417822.47      3540343.03     10417350.23
      3539981.91     10416669.66
#Sta/Elev= 30
  4250.4  430.24  4284.3  429.95  4391.2  425.57  4420.7  425.32  4456.3  423.84
  4477.2  422.05  4649.3  415.44  4729.2  413.92  4860.8   415.8  4948.7  413.25
  5003.5  409.09  5015.5  408.54  5019.3  408.37  5019.6  407.87  5023.3  408.37
  5036.7  409.46    5075  409.72  5157.2  412.65  5213.8  415.64  5272.9  419.51
  5311.2  423.26  5371.5  427.49  5383.6  429.06  5393.5  428.86  5428.8  430.55
  5465.1  434.53  5503.4  435.26  5509.1  434.61  5531.1   437.7  5600.9  441.37
#Mann= 5 ,-1 , 0
  4250.4     .05       0  5003.5     .16       0  5015.5     .05       0
  5019.3     .03       0  5023.3     .05       0
Bank Sta=5019.3,5023.3
XS Rating Curve= 0 ,0
Exp/Cntr=0.3,0.1

Type RM Length L Ch R = 1 ,4969    ,213,213,213
BEGIN DESCRIPTION:
RED OAK CR TRIB 7 11 1
END DESCRIPTION:
XS GIS Cut Line= 3
       3541044.7     10417576.53      3540444.71     10416976.54
      3540145.97      10416677.8
#Sta/Elev= 30
  4203.7  430.12  4343.3  422.84  4399.9  420.95  4435.3  420.54  4527.2  416.59
  4718.1  412.22  4795.9  412.09  4910.3  408.97  4951.5  408.41  4972.7  406.91
  4979.7  405.76  4986.8  406.05    5006  404.51  5006.3  404.01  5009.8  404.01
    5010  404.51  5022.2  405.31  5036.3  407.65  5050.4  408.84  5085.8  408.86
  5135.3  412.26  5177.7  414.36    5206  414.97  5213.1  416.49  5269.7  419.06
  5297.9  421.49  5361.6  425.09  5418.1  429.39  5432.3  431.08  5474.7  433.64
#Mann= 4 ,-1 , 0
  4203.7     .05       0  4910.3     .16       0    5006     .07       0
    5010     .05       0
Bank Sta=5006,5010
XS Rating Curve= 0 ,0
Exp/Cntr=0.3,0.1

Type RM Length L Ch R = 1 ,4756    ,180,180,180
BEGIN DESCRIPTION:
RED OAK CR TRIB 7 11 4
END DESCRIPTION:
XS GIS Cut Line= 3
      3541427.17     10417350.59      3540704.53     10416923.09
      3540166.73      10416522.7
#Sta/Elev= 30
  4021.3  444.36  4025.2  443.19  4046.7  441.44  4089.5  439.44  4126.6  436.27
  4169.5  435.17  4185.1  433.79  4265.1   430.7  4280.7  429.24  4286.5  429.58
  4339.2  426.48  4403.5  424.17  4584.9  415.53  4733.1   409.9  4877.2  406.47
  4956.4  405.42  4963.7  405.89  4989.9  403.39  4990.1  402.89  4993.9  403.39
  5013.5  404.04  5035.7  407.52  5085.8  411.68  5163.2  416.81  5292.2  421.32
  5356.9  424.84  5377.7  425.19    5457   429.9  5477.8   429.8  5531.4  431.84
#Mann= 3 ,-1 , 0
  4021.3     .05       0  4989.9     .03       0  4993.9     .05       0
Bank Sta=4989.9,4993.9
XS Rating Curve= 0 ,0
Exp/Cntr=0.3,0.1

Type RM Length L Ch R = 1 ,4576    ,161,161,161
BEGIN DESCRIPTION:
RED OAK CR TRIB 7 11 3
END DESCRIPTION:
XS GIS Cut Line= 4
      3541411.99     10417257.28      3540847.76     10416818.92
      3540522.24     10416588.89      3540187.99     10416478.19
#Sta/Elev= 30
  4161.3  442.96  4179.4  442.52  4208.4  439.89  4222.8  439.22  4229.2  439.58
  4243.7  438.33  4278.9  438.46  4307.9  436.92  4343.2  436.27  4357.7  434.89
  4407.5  432.44  4421.9  430.73    4507  425.94  4600.2  419.54  4875.8  407.69
  4913.9  405.44  4956.2  404.08  4979.1  402.51  4998.1  402.27  4998.3  401.77
  5001.8  401.77  5002.1  402.27  5041.9  405.03  5115.4   408.4  5172.4  412.15
  5381.1  418.09  5470.9  422.71  5507.9  423.86  5534.3  425.73  5626.5  428.72
#Mann= 3 ,-1 , 0
  4161.3     .05       0  4998.1     .03       0  5002.1     .05       0
Bank Sta=4956.2,5041.9
XS Rating Curve= 0 ,0
Exp/Cntr=0.3,0.1

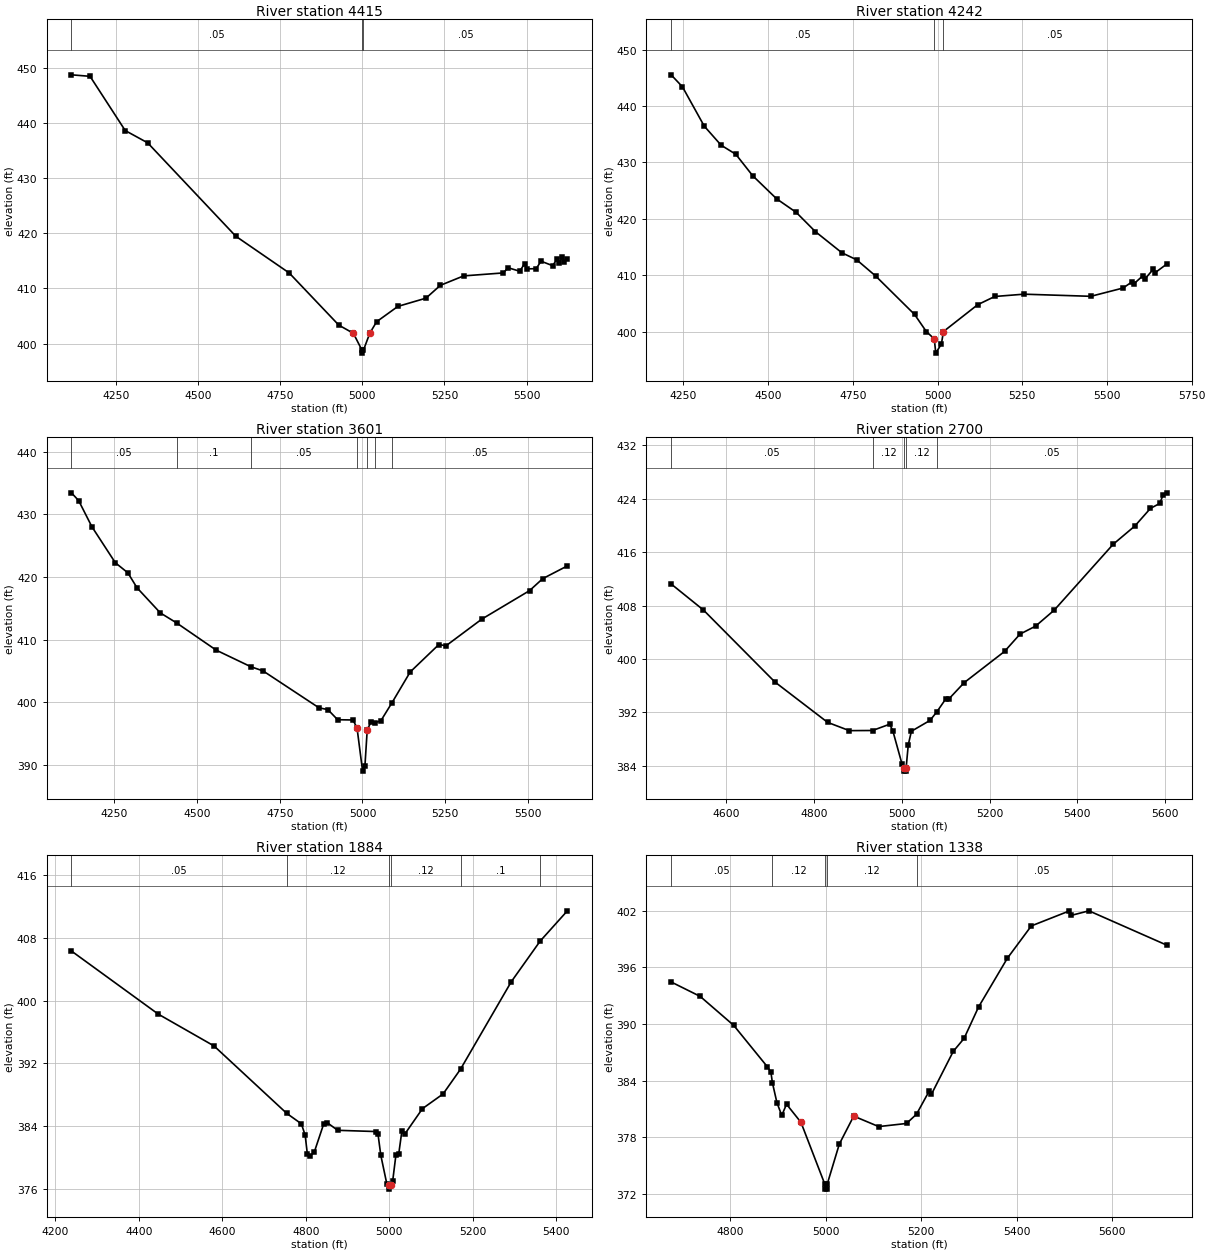
Type RM Length L Ch R = 1 ,4415    ,173,173,173
BEGIN DESCRIPTION:
RED OAK CR TRIB 7 2 0
END DESCRIPTION:
XS GIS Cut Line= 3
      3541602.94     10417077.15      3540880.31     10416649.65
      3540342.19     10416249.02
#Sta/Elev= 30
  4113.8  448.68  4170.4  448.41  4277.6  438.59  4345.9  436.37  4614.4  419.46
  4776.9  412.82  4928.1  403.37  4972.5  401.89    4999   398.8  4999.3   398.3
    5003   398.8  5022.6  401.92  5043.4  403.99  5108.1  406.76  5193.6  408.25
  5237.4  410.57  5308.3  412.28  5429.2  412.82  5443.9  413.76  5479.3  413.12
  5493.9  414.49  5500.1  413.55  5529.4  413.59    5544  414.95  5579.4  414.13
    5594  415.42  5600.2  414.65  5608.6  415.73  5614.8  414.77  5624.3  415.42
#Mann= 3 ,-1 , 0
  4113.8     .05       0    4999     .03       0    5003     .05       0
Bank Sta=4972.5,5022.6
XS Rating Curve= 0 ,0
Exp/Cntr=0.3,0.1

Type RM Length L Ch R = 1 ,4242    ,641,641,641
BEGIN DESCRIPTION:
RED OAK CR TRIB 7 12 0
END DESCRIPTION:
XS GIS Cut Line= 4
      3541587.75     10416983.83      3541023.54     10416545.48
      3540698.02     10416315.45      3540365.46     10416205.32
#Sta/Elev= 30
  4213.9  445.55  4247.3  443.42  4311.6  436.45  4361.3  433.07  4404.8  431.45
  4454.6  427.65  4525.2  423.55  4583.1  421.14  4639.2  417.75  4717.9  413.97
  4761.4  412.73  4817.5  409.85  4932.3  403.03    4967     400  4990.5  398.69
  4994.8  396.17  5011.4  397.78  5017.5     400  5118.5  404.76  5168.9  406.22
  5255.1  406.63  5452.4  406.25  5547.5  407.72  5573.9  408.81  5579.2  408.45
  5605.6  409.88  5610.9  409.25  5637.3  411.09  5642.6  410.46  5677.3  412.01
#Mann= 3 , 0 , 0
  4213.9     .05       0  4990.5     .03       0  5017.5     .05       0
Bank Sta=4990.5,5017.5
XS Rating Curve= 0 ,0
Exp/Cntr=0.3,0.1

Type RM Length L Ch R = 1 ,3601    ,901,901,901
BEGIN DESCRIPTION:
RED OAK CR TRIB 7 10 0
END DESCRIPTION:
XS GIS Cut Line= 3
      3541546.23     10416842.53      3541317.06     10416095.99
      3541042.75      10415432.8
#Sta/Elev= 30
  4120.5  433.46  4142.3  432.21  4182.3  428.04    4253   422.3    4291  420.68
  4318.5   418.3  4389.1  414.28    4438  412.69    4558  408.33  4662.8  405.68
  4699.4  405.02  4868.3  399.13  4895.5  398.83  4924.9  397.22  4971.1  397.18
  4983.5  395.92  5000.3  389.01  5007.4  389.88  5014.3   395.6  5025.2  396.81
  5036.6  396.74  5055.2  397.03  5089.2  399.94  5144.2  404.85  5230.8  409.23
  5252.4  409.03  5360.6  413.29  5504.9  417.84  5544.6  419.75  5619.1  421.79
#Mann= 7 ,-1 , 0
  4120.5     .05       0    4438      .1       0  4662.8     .05       0
  4983.5     .03       0  5014.3     .05       0  5036.6     .12       0
  5089.2     .05       0
Bank Sta=4983.5,5014.3
XS Rating Curve= 0 ,0
Exp/Cntr=0.3,0.1

Type RM Length L Ch R = 1 ,2700    ,816,816,816
BEGIN DESCRIPTION:
RED OAK CR TRIB 7 9 0
END DESCRIPTION:
XS GIS Cut Line= 3
       3542404.6     10416013.17      3542004.61     10415613.17
      3541605.85     10415214.42
#Sta/Elev= 30
  4474.7  411.23  4548.3  407.33  4710.9  396.57  4831.1  390.52  4880.6  389.28
  4933.4   389.3  4972.5  390.24  4979.6  389.27  5000.8  384.24  5005.8  383.72
  5006.1  383.22  5009.7  383.22    5010  383.72  5014.9  387.17    5022  389.19
  5064.4  390.81  5079.9  392.09  5099.8  393.98  5106.9  393.99  5142.2  396.46
  5234.1  401.13  5269.5  403.73  5304.9  404.92  5347.3  407.31  5481.6  417.17
  5531.1  419.91  5566.5  422.54  5587.7  423.28  5594.8  424.47  5604.3  424.87
#Mann= 5 ,-1 , 0
  4474.7     .05       0  4933.4     .12       0  5005.8     .07       0
    5010     .12       0  5079.9     .05       0
Bank Sta=5005.8,5010
XS Rating Curve= 0 ,0
Exp/Cntr=0.3,0.1

Type RM Length L Ch R = 1 ,1884    ,546,546,546
BEGIN DESCRIPTION:
RED OAK CR TRIB 7 8 0
END DESCRIPTION:
XS GIS Cut Line= 3
       3542592.1     10415691.62      3542392.11     10414991.64
      3542092.09     10414641.62
#Sta/Elev= 30
  4238.4  406.32  4446.4  398.29  4580.3  394.23  4754.5  385.65  4789.6  384.32
  4798.7  382.88  4803.9  380.51  4810.4  380.18  4820.8  380.75  4842.9  384.26
    4852  384.45  4876.7  383.49  4969.7  383.33  4973.5  382.96  4980.1  380.31
  4994.4   376.7  4999.9   376.5  5000.2     376  5004.2   376.5  5008.6  377.04
  5016.3  380.33  5022.9  380.41  5030.6  383.38  5037.2  382.98    5080  386.25
  5129.4  388.12  5171.2  391.27  5292.9  402.41  5362.1  407.58  5427.4  411.44
#Mann= 6 ,-1 , 0
  4238.4     .05       0  4754.5     .12       0  4999.9     .07       0
  5004.2     .12       0  5171.2      .1       0  5362.1     .05       0
Bank Sta=4999.9,5004.2
XS Rating Curve= 0 ,0
Exp/Cntr=0.3,0.1

Type RM Length L Ch R = 1 ,1338    ,588,588,588
BEGIN DESCRIPTION:
RED OAK CR TRIB 7 6 0
END DESCRIPTION:
XS GIS Cut Line= 3
      3542777.92     10415312.18      3542831.75     10414721.86
       3542786.6     10414279.12
#Sta/Elev= 30
  4676.8  394.45  4737.6  392.92  4807.9  389.84  4878.2  385.46  4885.6  384.89
  4888.7  383.78  4898.2  381.66  4908.3   380.3  4918.3  381.49  4948.5  379.57
  4998.6  372.99  4998.9  372.49  5002.9  372.49  5003.3  372.99  5028.8  377.27
  5058.9  380.23  5111.2  379.12  5169.4  379.45  5190.3  380.43  5216.5  382.85
  5221.5  382.54  5267.2  387.09  5289.9  388.47  5320.2   391.8  5380.4  396.96
  5430.6  400.39  5509.2  401.96  5514.3  401.51  5551.2  401.99  5714.6  398.34
#Mann= 5 ,-1 , 0
  4676.8     .05       0  4888.7     .12       0  4998.6     .07       0
  5003.3     .12       0  5190.3     .05       0
Bank Sta=4948.5,5058.9
XS Rating Curve= 0 ,0
Exp/Cntr=0.3,0.1

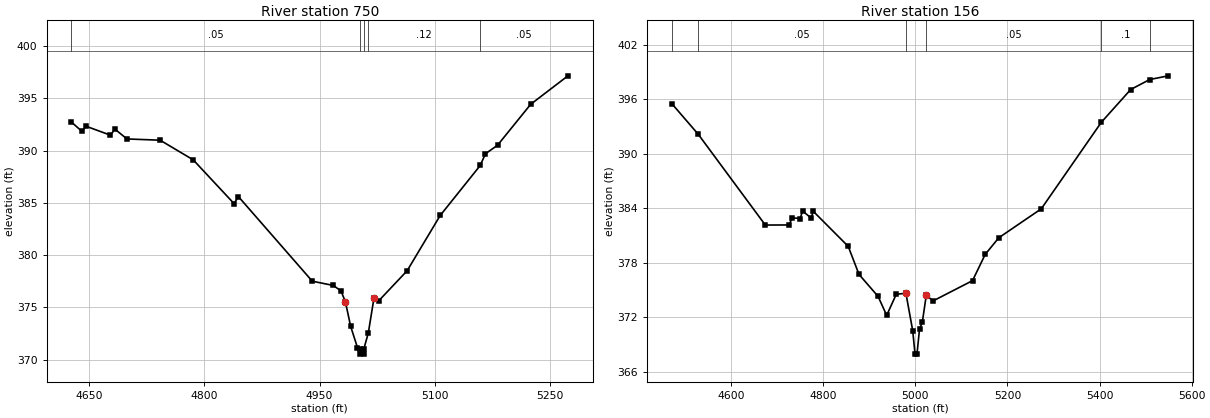
Type RM Length L Ch R = 1 ,750     ,594,594,594
BEGIN DESCRIPTION:
RED OAK CR TRIB 7 2 1 2
END DESCRIPTION:
XS GIS Cut Line= 2
      3543454.67     10415086.79       3543131.9     10414526.28
#Sta/Elev= 30
  4626.8  392.72  4640.2  391.85    4646  392.32  4677.6  391.47  4683.3  392.05
  4699.1  391.11  4742.3  390.99  4785.4  389.11  4838.5  384.93  4844.3  385.59
  4940.5   377.5  4967.9  377.09  4977.9  376.57  4983.7  375.52  4990.5  373.18
  4999.4  371.14  5002.8  371.02  5003.1  370.52  5007.3  370.52  5007.7  371.02
  5013.5  372.54    5021  375.93  5026.8   375.6  5064.1   378.5  5107.2  383.79
  5159.3  388.57  5166.1  389.69  5181.9  390.51  5225.1  394.43  5273.6  397.15
#Mann= 5 ,-1 , 0
  4626.8     .05       0  5002.8     .03       0  5007.7     .05       0
  5013.5     .12       0  5159.3     .05       0
Bank Sta=4983.7,5021
XS Rating Curve= 0 ,0
Exp/Cntr=0.3,0.1

Type RM Length L Ch R = 1 ,156     ,0,0,0
BEGIN DESCRIPTION:
RED OAK CR TRIB 7 1 0
END DESCRIPTION:
XS GIS Cut Line= 3
      3543930.33      10414888.8      3543751.52     10414480.84
      3543385.21     10413965.24
#Sta/Elev= 30
  4471.2  395.54  4528.6  392.16  4674.3  382.15  4726.5  382.16    4732  382.95
  4749.9  382.87  4755.3   383.7  4773.3  382.94  4778.7  383.65  4854.3   379.8
  4877.7  376.71  4919.2  374.28  4937.8  372.19  4958.7  374.53  4979.6  374.62
  4994.3  370.52  4999.4  367.92  5003.6  367.92  5009.1  370.67  5015.2  371.45
  5023.9  374.44  5038.3  373.78  5124.2  376.02  5151.8  378.92  5181.3  380.75
  5273.5  383.94  5403.9  393.48  5467.6  397.09  5508.8  398.19  5549.1   398.6
#Mann= 6 ,-1 , 0
  4471.2     .05       0  4528.6     .05       0  4979.6     .03       0
  5023.9     .05       0  5403.9      .1       0  5508.8     .05       0
Bank Sta=4979.6,5023.9
XS Rating Curve= 0 ,0
Exp/Cntr=0.3,0.1

Chan Stop Cuts=-1
Use User Specified Reach Order=0
Composite Channel Slope=5