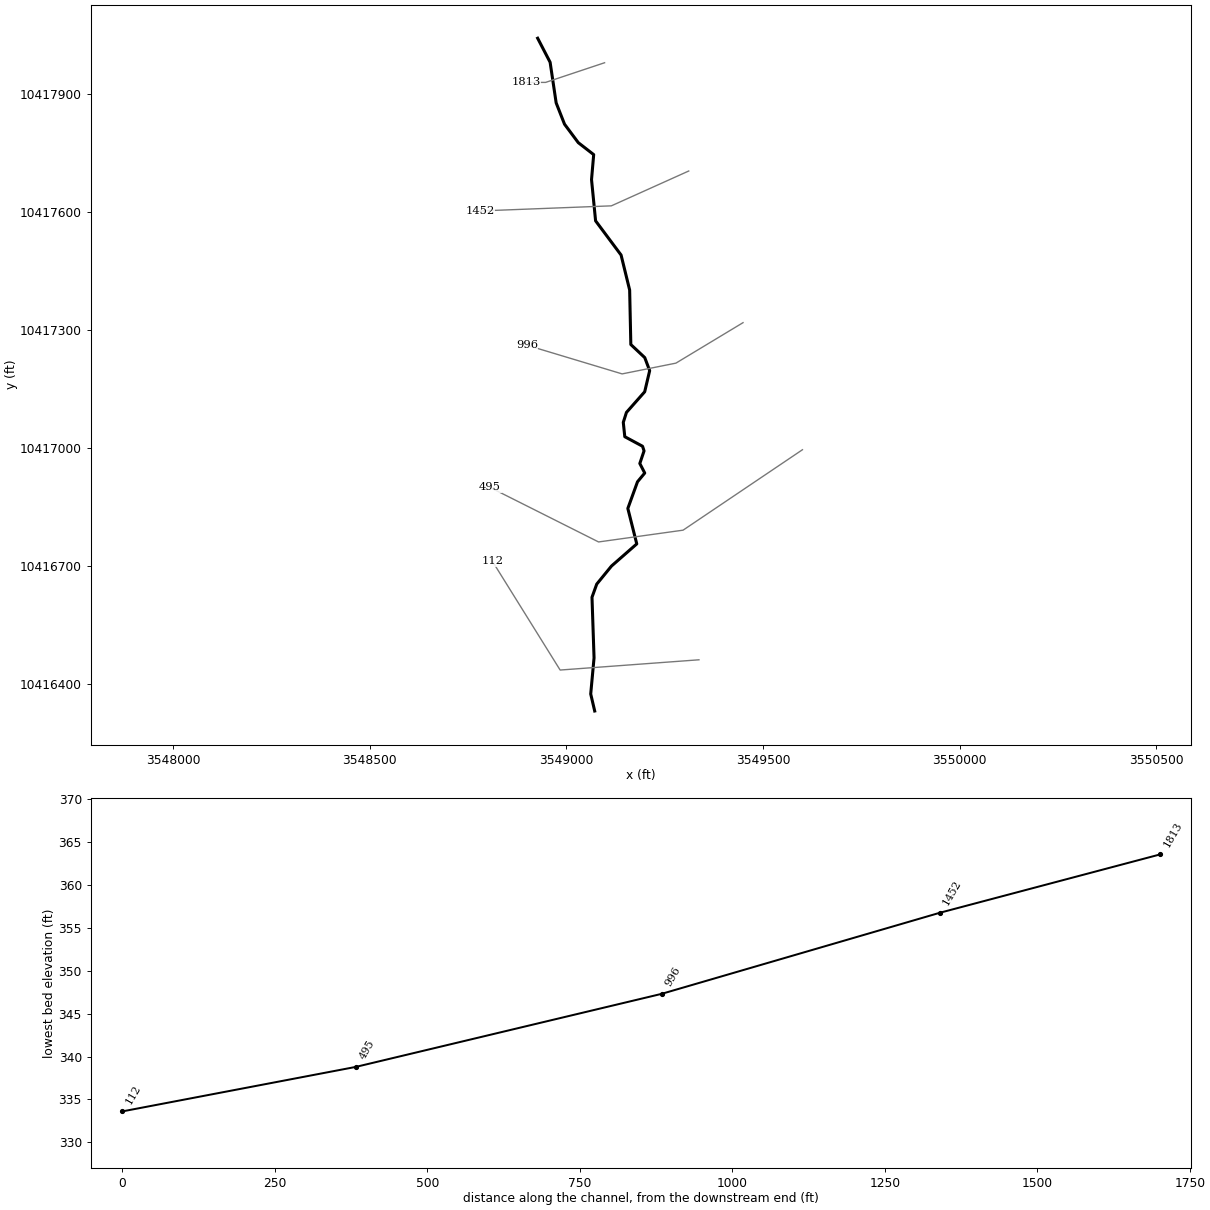
--- RED OAK CREEK TRIB 2.prj (project) ---

Proj Title=RED OAK CREEK TRIB 2 Base Level Engineering
Current Plan=p01
Default Exp/Contr=0.3,0.1
English Units
Geom File=g01
Flow File=f01
Plan File=p01
BEGIN DESCRIPTION:
RED OAK CREEK TRIB 2
END DESCRIPTION:

--- RED OAK CREEK TRIB 2.p01 (plan) ---

Plan Title=Multiple Run
Short Identifier=Multiple
Geom File=g01
Flow File=f01
Subcritical Flow
K Sum by GR= 0
Std Step Tol= 0.01
Critical Tol= 0.01
Num of Std Step Trials= 20
Max Error Tol= 0.3
Flow Tol Ratio= 0.001
Split Flow NTrial= 30
Split Flow Tol= 0.02
Split Flow Ratio= 0.02
Log Output Level= 0
Friction Slope Method= 1
Unsteady Friction Slope Method= 2
Unsteady Bridges Friction Slope Method= 1
Parabolic Critical Depth
Global Vel Dist=  1 , 1 , 1
Global Log Level= 0
CheckData=True
Encroach Param= -1, 0, 0, 0
BEGIN DESCRIPTION:
Multiple Run
END DESCRIPTION:

--- RED OAK CREEK TRIB 2.f01 (steady flow) ---

Flow Title=Multiple
Number of Profiles=7
Profile Names=10-year,25-year,50-year,1pct_min,100-year,1pct_plu,500-year
River Rch & RM= RED OAK CREEK TR,Reach-1,1813
     358     464     546     473     639     865     869
Boundary for River Rch & Prof#=RED OAK CREEK TR,Reach-1,1
Up Type=0
Dn Type=3
Dn Slope=0.005
Boundary for River Rch & Prof#=RED OAK CREEK TR,Reach-1,2
Up Type=0
Dn Type=3
Dn Slope=0.005
Boundary for River Rch & Prof#=RED OAK CREEK TR,Reach-1,3
Up Type=0
Dn Type=3
Dn Slope=0.005
Boundary for River Rch & Prof#=RED OAK CREEK TR,Reach-1,4
Up Type=0
Dn Type=3
Dn Slope=0.005
Boundary for River Rch & Prof#=RED OAK CREEK TR,Reach-1,5
Up Type=0
Dn Type=3
Dn Slope=0.005
Boundary for River Rch & Prof#=RED OAK CREEK TR,Reach-1,6
Up Type=0
Dn Type=3
Dn Slope=0.005
Boundary for River Rch & Prof#=RED OAK CREEK TR,Reach-1,7
Up Type=0
Dn Type=3
Dn Slope=0.005

--- RED OAK CREEK TRIB 2.g01 (geometry) ---

Geom Title=Existing Conditions

River Reach=RED OAK CREEK TR,Reach-1
Reach XY= 30
      3548927.12     10418041.42      3548958.80     10417980.35
      3548974.18     10417877.04      3548995.43     10417822.94
      3549030.37     10417776.04      3549069.55     10417745.63
      3549064.06     10417682.14      3549074.40     10417577.28
      3549139.16     10417490.46      3549160.95     10417401.47
      3549163.95     10417263.02      3549199.33     10417229.76
      3549211.84     10417196.57      3549199.18     10417142.91
      3549152.82     10417090.46      3549144.78     10417065.21
      3549148.60     10417028.75      3549193.74     10417004.45
      3549197.56     10416992.64      3549186.79     10416960.70
      3549199.29     10416936.39      3549180.89     10416914.17
      3549156.32     10416846.41      3549179.04     10416756.30
      3549114.78     10416700.02      3549077.31     10416654.16
      3549065.24     10416620.72      3549070.47     10416466.67
      3549061.99     10416374.95      3549072.11     10416331.64

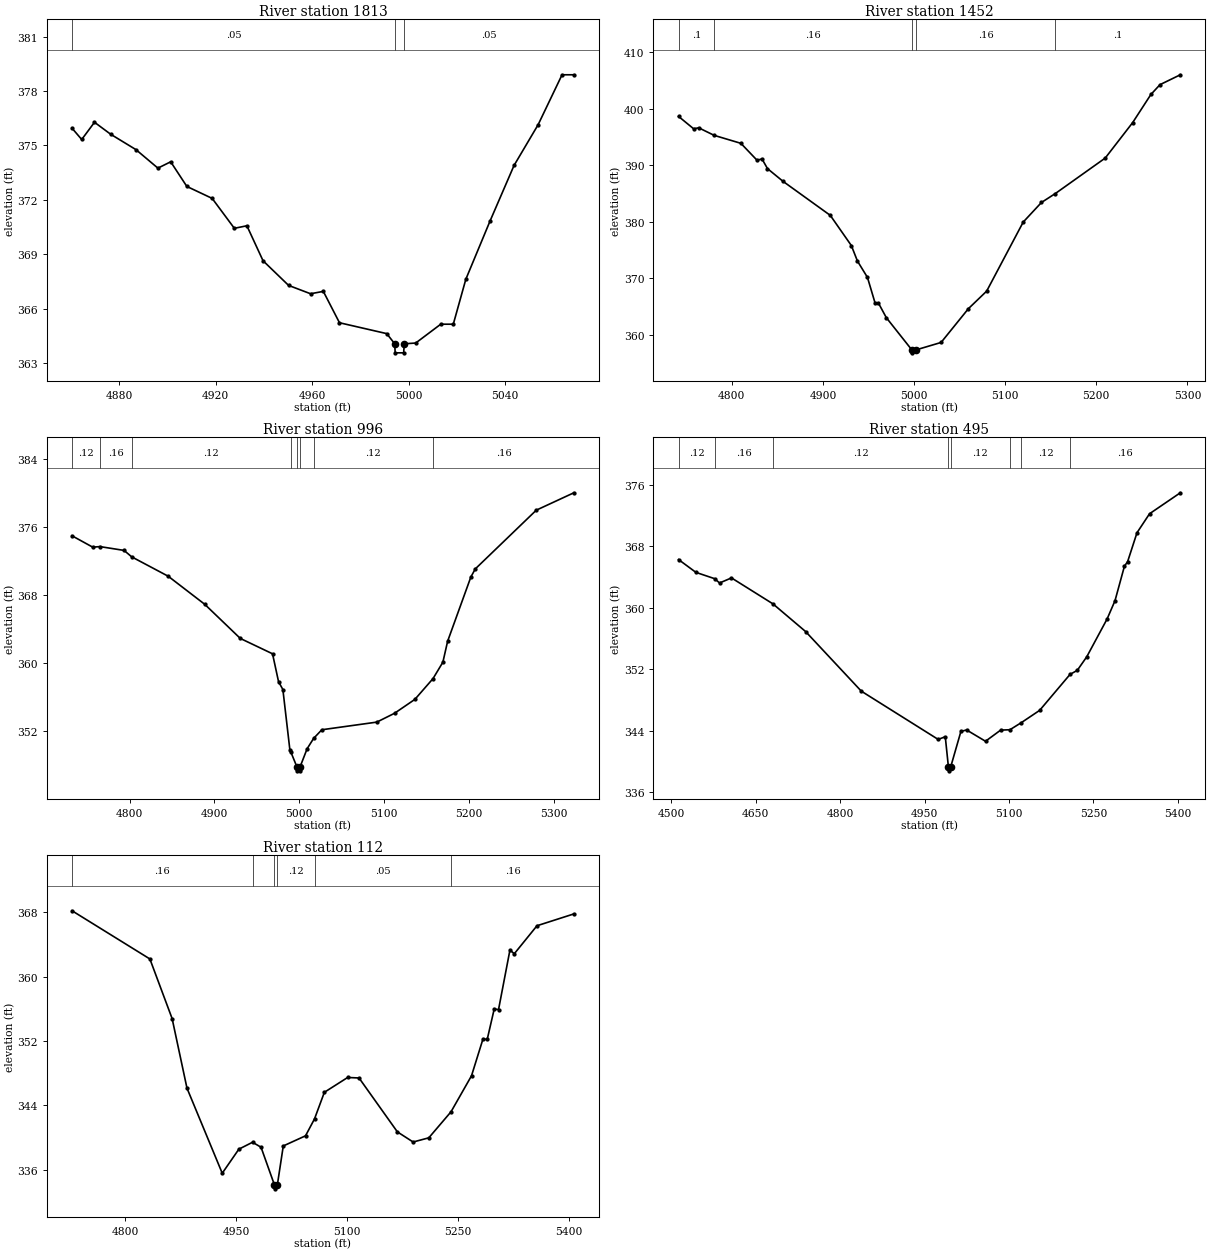
Type RM Length L Ch R = 1,1813,361,361,361
BEGIN DESCRIPTION:
RED OAK CREEK TRIB 2 4 0
END DESCRIPTION:
XS GIS Cut Line= 3
      3549097.27     10417979.13      3548947.31     10417929.14
      3548897.28     10417929.14
#Sta/Elev= 30
  4860.4  375.95  4864.4  375.33  4869.7  376.28  4876.4  375.62  4886.9  374.77
  4896.0  373.75  4901.3  374.10  4908.0  372.74  4918.5  372.08  4927.7  370.43
  4932.9  370.57  4939.6  368.64  4950.2  367.28  4959.3  366.82  4964.6  366.95
  4971.3  365.22  4990.9  364.62  4994.2  364.06  4994.4  363.56  4997.9  363.56
  4998.2  364.06  5002.9  364.10  5013.3  365.14  5018.5  365.14  5023.7  367.62
  5033.7  370.82  5043.7  373.90  5053.7  376.15  5063.6  378.90  5068.5  378.90
#Mann=3,-1,0
  4860.4    0.05       0  4994.2    0.03       0  4998.2    0.05       0
Bank Sta=4994.2,4998.2
Exp/Cntr=0.3,0.1

Type RM Length L Ch R = 1,1452,456,456,456
BEGIN DESCRIPTION:
RED OAK CREEK TRIB 2 2 0
END DESCRIPTION:
XS GIS Cut Line= 3
      3549311.13     10417703.99      3549114.48     10417615.44
      3548779.80     10417602.42
#Sta/Elev= 30
  4741.6  398.64  4758.2  396.44  4763.7  396.62  4780.7  395.28  4810.0  393.87
  4827.7  390.88  4833.2  391.10  4839.2  389.39  4856.3  387.13  4908.1  381.11
  4931.2  375.77  4937.9  373.02  4948.9  370.12  4957.3  365.56  4961.0  365.56
  4969.6  362.99  4997.7  357.26  4997.9  356.76  5001.7  357.26  5029.7  358.60
  5059.7  364.59  5079.7  367.69  5119.8  379.92  5139.8  383.39  5155.1  384.98
  5209.8  391.26  5239.9  397.54  5259.9  402.52  5269.9  404.26  5292.2  406.01
#Mann=5,-1,0
  4741.6     0.1       0  4780.7    0.16       0  4997.7    0.07       0
  5001.7    0.16       0  5155.1     0.1       0
Bank Sta=4997.7,5001.7
Exp/Cntr=0.3,0.1

Type RM Length L Ch R = 1,996,501,501,501
BEGIN DESCRIPTION:
RED OAK CREEK TRIB 2 3 0
END DESCRIPTION:
XS GIS Cut Line= 4
      3549449.10     10417318.55      3549278.54     10417215.70
      3549141.82     10417188.35      3548899.66     10417261.26
#Sta/Elev= 30
  4732.2  375.00  4756.6  373.66  4765.0  373.73  4793.5  373.28  4802.5  372.52
  4845.5  370.24  4888.6  366.93  4930.5  362.91  4968.5  361.10  4975.6  357.81
  4980.7  356.89  4988.9  349.82  4990.0  349.55  4997.1  347.81  4997.4  347.31
  5000.9  347.31  5001.1  347.81  5009.3  349.92  5017.0  351.14  5026.6  352.15
  5091.4  353.05  5112.3  354.09  5136.3  355.73  5157.7  358.18  5169.3  360.11
  5174.9  362.58  5202.3  370.15  5207.5  371.10  5279.4  378.02  5323.7  380.07
#Mann=8,-1,0
  4732.2    0.12       0  4765.0    0.16       0  4802.5    0.12       0
  4990.0    0.16       0  4997.1    0.07       0  5001.1    0.16       0
  5017.0    0.12       0  5157.7    0.16       0
Bank Sta=4997.1,5001.1
Exp/Cntr=0.3,0.1

Type RM Length L Ch R = 1,495,383,383,383
BEGIN DESCRIPTION:
Mapping XS 9105ce10
END DESCRIPTION:
XS GIS Cut Line= 4
      3549600.13     10416995.63      3549296.77     10416791.22
      3549081.93     10416761.27      3548805.83     10416899.97
#Sta/Elev= 30
  4512.7  366.30  4543.6  364.63  4576.9  363.81  4585.6  363.25  4606.8  363.91
  4680.5  360.53  4738.5  356.93  4837.5  349.17  4974.1  342.89  4986.7  343.24
  4992.3  339.30  4992.5  338.80  4996.3  339.30  5014.5  343.93  5024.6  344.12
  5058.2  342.65  5085.1  344.10  5101.6  344.15  5122.0  345.08  5154.4  346.67
  5208.4  351.35  5221.3  351.88  5238.1  353.64  5274.3  358.57  5288.3  360.94
  5305.1  365.44  5310.7  366.02  5327.4  369.79  5349.7  372.26  5404.4  374.99
#Mann=8,-1,0
  4512.7    0.12       0  4576.9    0.16       0  4680.5    0.12       0
  4992.3    0.07       0  4996.3    0.12       0  5101.6    0.05       0
  5122.0    0.12       0  5208.4    0.16       0
Bank Sta=4992.3,4996.3
Exp/Cntr=0.3,0.1

Type RM Length L Ch R = 1,112,0,0,0
BEGIN DESCRIPTION:
RED OAK CREEK TRIB 2 1 0
END DESCRIPTION:
XS GIS Cut Line= 3
      3549337.16     10416461.79      3548984.27     10416435.75
      3548812.41     10416711.77
#Sta/Elev= 30
  4727.8  368.17  4833.1  362.18  4863.2  354.77  4883.3  346.12  4931.0  335.55
  4953.5  338.54  4972.0  339.40  4983.5  338.78  5001.6  334.11  5001.9  333.61
  5005.6  334.11  5013.6  338.94  5043.7  340.20  5055.9  342.31  5069.2  345.61
  5100.7  347.45  5116.1  347.39  5168.0  340.69  5189.3  339.43  5210.5  339.95
  5240.6  343.19  5268.3  347.66  5283.7  352.20  5289.6  352.20  5299.0  355.95
  5304.9  355.90  5320.3  363.29  5326.2  362.83  5356.9  366.31  5406.8  367.78
#Mann=6,-1,0
  4727.8    0.16       0  4972.0    0.12       0  5001.6    0.07       0
  5005.6    0.12       0  5055.9    0.05       0  5240.6    0.16       0
Bank Sta=5001.6,5005.6
Exp/Cntr=0.3,0.1

Chan Stop Cuts=-1