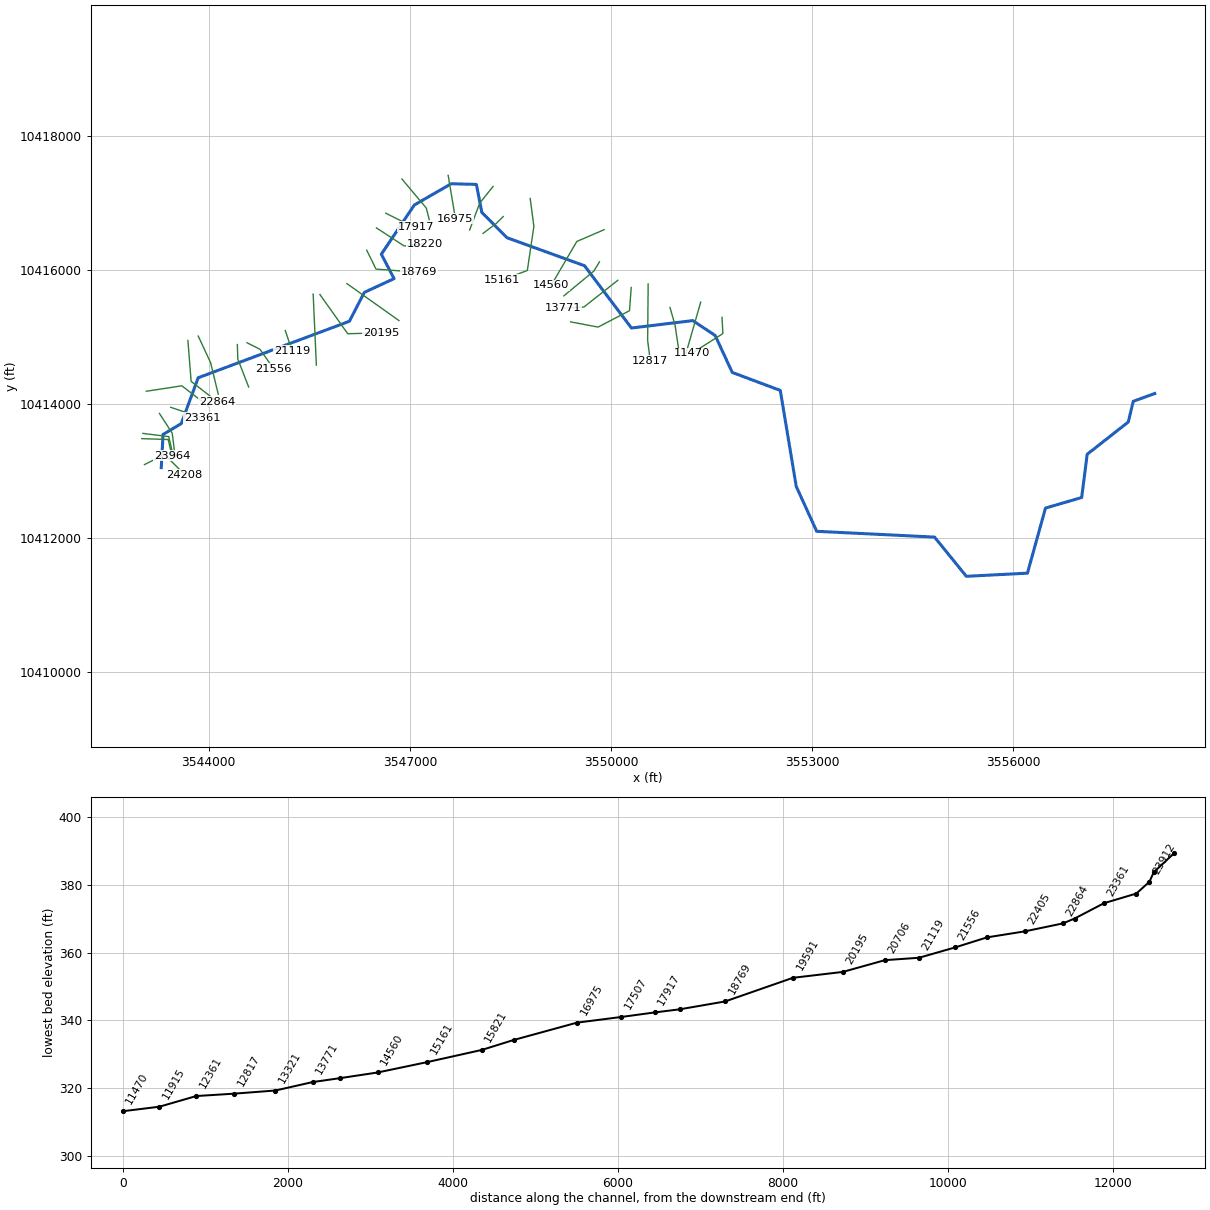
--- RED OAK CREEK.prj (project) ---

Proj Title=RED OAK CREEK Base Level Engineering
Current Plan=p01
Default Exp/Contr=0.3,0.1
English Units
Geom File=g01
Flow File=f01
Plan File=p01
Y Axis Title=Elevation
X Axis Title(PF)=Main Channel Distance
X Axis Title(XS)=Station
BEGIN DESCRIPTION:
RED OAK CREEK
END DESCRIPTION:
DSS Export Rating Curves= 0
DSS Export Rating Curve Sorted= 0
DSS Export Volume Flow Curves= 0
DXF OffsetX= 0
DXF OffsetY= 0
DXF ScaleX= 1
DXF ScaleY= 10

--- RED OAK CREEK.p01 (plan) ---

Plan Title=Multiple Run
Short Identifier=Multiple
Geom File=g01
Flow File=f01
Subcritical Flow
K Sum by GR= 0
Std Step Tol= 0.01
Critical Tol= 0.01
Num of Std Step Trials= 20
Max Error Tol= 0.3
Flow Tol Ratio= 0.001
Split Flow NTrial= 30
Split Flow Tol= 0.02
Split Flow Ratio= 0.02
Log Output Level= 0
Friction Slope Method= 1
Unsteady Friction Slope Method= 2
Unsteady Bridges Friction Slope Method= 1
Parabolic Critical Depth
Global Vel Dist=  1 , 1 , 1
Global Log Level= 0
CheckData=True
Encroach Param= -1, 0, 0, 0
BEGIN DESCRIPTION:
Multiple Run
END DESCRIPTION:

--- RED OAK CREEK.f01 (steady flow) ---

Flow Title=Multiple
Program Version=4.10
Number of Profiles= 7
Profile Names=10-year,25-year,50-year,1pct_min,100-year,1pct_plu,500-year
River Rch & RM=RED OAK CREEK,Reach-1         ,24208
     294     375     438     375     507     685     675
River Rch & RM=RED OAK CREEK,Reach-1         ,22864
    1569    2222    2777    2530    3421    4626    5180
River Rch & RM=RED OAK CREEK,Reach-1         ,22405
    1569    2222    2777    2530    3421    4626    5180
River Rch & RM=RED OAK CREEK,Reach-1         ,20195
    1895    2712    3413    3129    4231    5722    6491
River Rch & RM=RED OAK CREEK,Reach-1         ,18769
    2316    3345    4235    3903    5278    7138    8185
River Rch & RM=RED OAK CREEK,Reach-1         ,16210
    2669    3876    4925    4554    6158    8328    9611
River Rch & RM=RED OAK CREEK,Reach-1         ,14560
    2880    4186    5320    4918    6652    8995   10379
River Rch & RM=RED OAK CREEK,Reach-1         ,9234
    3199    4657    5925    5480    7411   10023   11576
Boundary for River Rch & Prof#=RED OAK CREEK,Reach-1         , 1
Up Type= 0
Dn Type= 3
Dn Slope=0.005
Boundary for River Rch & Prof#=RED OAK CREEK,Reach-1         , 2
Up Type= 0
Dn Type= 3
Dn Slope=0.005
Boundary for River Rch & Prof#=RED OAK CREEK,Reach-1         , 3
Up Type= 0
Dn Type= 3
Dn Slope=0.005
Boundary for River Rch & Prof#=RED OAK CREEK,Reach-1         , 4
Up Type= 0
Dn Type= 3
Dn Slope=0.005
Boundary for River Rch & Prof#=RED OAK CREEK,Reach-1         , 5
Up Type= 0
Dn Type= 3
Dn Slope=0.005
Boundary for River Rch & Prof#=RED OAK CREEK,Reach-1         , 6
Up Type= 0
Dn Type= 3
Dn Slope=0.005
Boundary for River Rch & Prof#=RED OAK CREEK,Reach-1         , 7
Up Type= 0
Dn Type= 3
Dn Slope=0.005
DSS Import GetInterval= 0
DSS Import GetPeak= 0
DSS Import FillOption= 0

--- RED OAK CREEK.g01 (geometry) ---

Geom Title=Existing Conditions
Program Version=4.10

River Reach=RED OAK CREEK   ,Reach-1
Reach XY= 30
      3543292.11     10413046.19      3543318.69     10413541.23
      3543589.98     10413702.46      3543842.73      10414386.7
       3546098.2      10415229.5      3546321.33     10415660.82
      3546764.59     10415865.65      3546574.92     10416230.42
       3547067.1     10416964.48       3547617.5     10417281.26
      3547992.11     10417271.64      3548074.47     10416852.49
      3548449.28     10416476.27      3549605.61     10416058.17
      3550305.67     10415129.02      3551220.92     10415239.59
      3551554.52     10415018.02      3551809.39     10414466.31
       3552525.7     10414198.19      3552763.65     10412767.17
      3553069.14     10412096.06      3554826.96     10412009.78
      3555301.19     10411424.83      3556212.65     10411471.71
      3556482.14     10412442.72      3557021.73     10412600.17
      3557103.85     10413245.25      3557716.95     10413726.88
       3557791.1     10414035.43      3558112.11     10414151.64

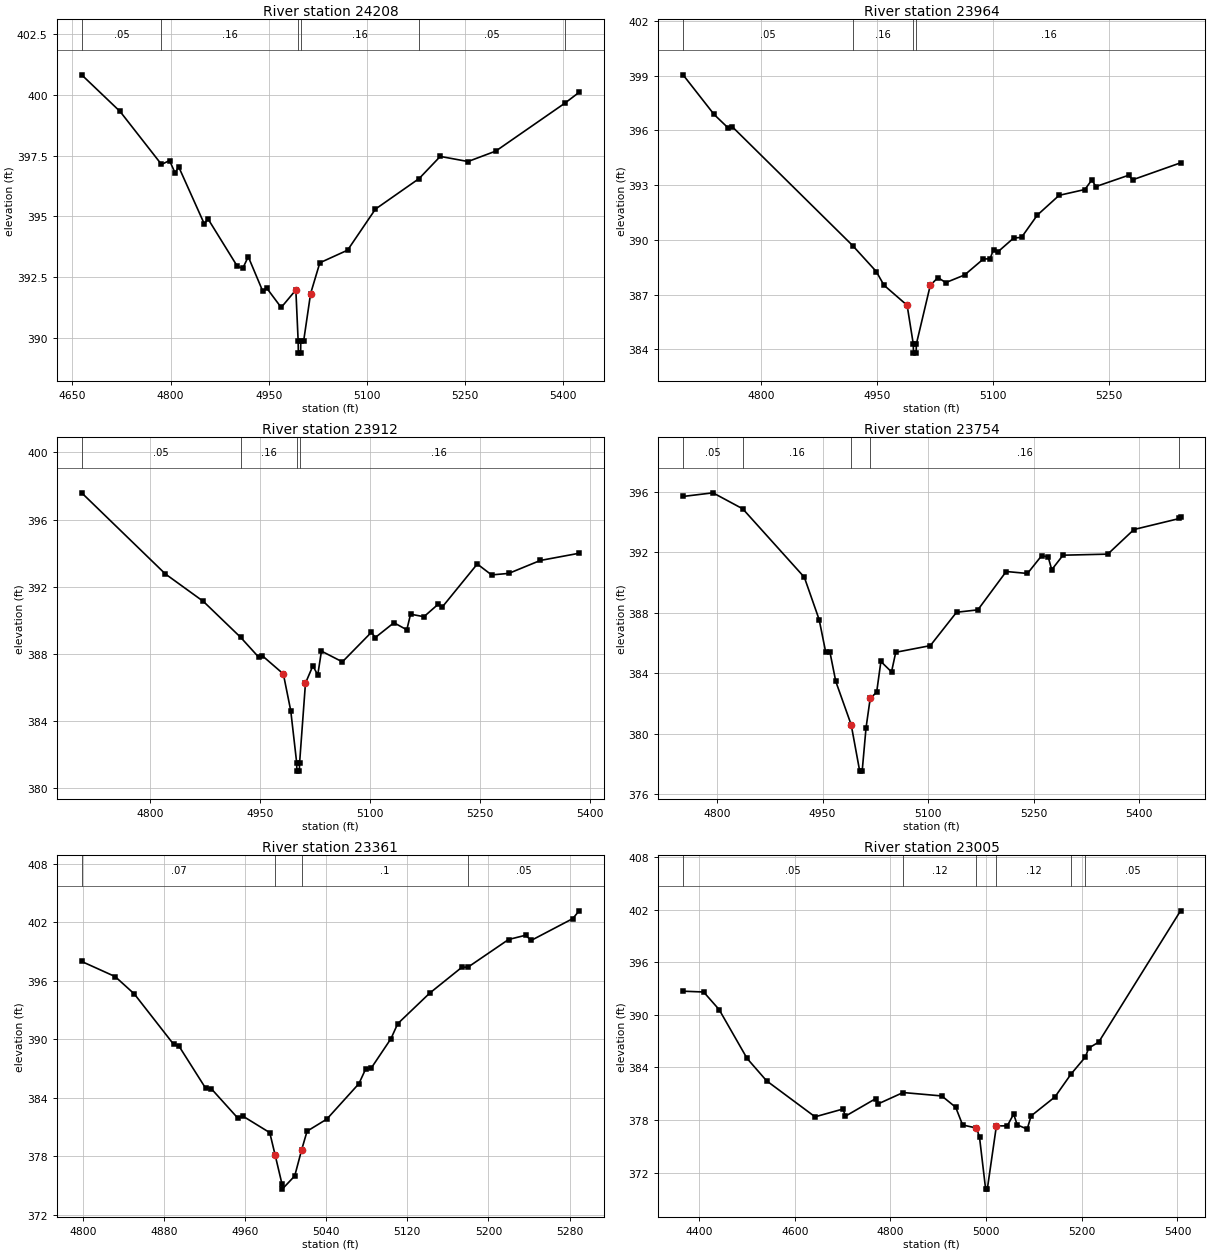
Type RM Length L Ch R = 1 ,24208   ,244,244,244
BEGIN DESCRIPTION:
RED OAK CREEK 6 0
END DESCRIPTION:
XS GIS Cut Line= 3
      3543042.08     10413091.63      3543342.11     10413241.64
       3543642.1     10412941.64
#Sta/Elev= 30
  4664.3  400.83    4723  399.32  4786.2  397.14  4798.5   397.3  4806.9  396.79
  4812.5  397.04  4851.6  394.69  4857.2   394.9  4901.9  392.95  4910.3  392.86
  4918.7  393.34    4941  391.91  4946.6  392.06    4969  391.25  4991.4  391.97
  4994.9  389.87  4995.2  389.37  4998.7  389.37  4998.9  389.87  5003.3  389.87
  5013.9  391.82    5028  393.09  5070.4  393.61  5112.9   395.3  5179.7  396.56
  5211.9  397.47  5254.3  397.26  5296.7  397.69  5402.6  399.67    5424  400.11
#Mann= 6 ,-1 , 0
  4664.3     .05       0  4786.2     .16       0  4994.9     .07       0
  4998.9     .16       0  5179.7     .05       0  5402.6      .1       0
Bank Sta=4991.4,5013.9
XS Rating Curve= 0 ,0
Exp/Cntr=0.3,0.1

Type RM Length L Ch R = 1 ,23964   ,52,52,52
BEGIN DESCRIPTION:
Mapping XS 2f37f848
END DESCRIPTION:
XS GIS Cut Line= 3
      3543001.89      10413478.7      3543395.12     10413465.68
       3543452.4     10413220.93
#Sta/Elev= 30
  4698.5  399.04  4738.7  396.87  4757.2  396.12  4762.2   396.2  4918.3  389.69
  4948.9  388.27  4958.9  387.52  4988.9  386.42  4996.9   384.3  4997.1   383.8
  5000.6   383.8  5000.9   384.3  5018.9  387.51  5028.9  387.94  5038.9  387.66
  5063.4  388.08  5087.9  388.96  5096.3  388.96  5100.9  389.47  5106.4  389.34
  5126.9   390.1  5137.2  390.14  5157.7  391.36  5185.9  392.44  5219.3  392.76
  5228.4  393.29  5233.5  392.92    5276  393.54  5281.1  393.29  5343.3  394.22
#Mann= 4 ,-1 , 0
  4698.5     .05       0  4918.3     .16       0  4996.9     .07       0
  5000.9     .16       0
Bank Sta=4988.9,5018.9
XS Rating Curve= 0 ,0
Exp/Cntr=0.3,0.1

Type RM Length L Ch R = 1 ,23912   ,158,158,158
BEGIN DESCRIPTION:
Mapping XS bd8dc973
END DESCRIPTION:
XS GIS Cut Line= 3
      3543018.82     10413556.83      3543404.23     10413508.65
      3543468.98     10413225.06
#Sta/Elev= 30
  4706.4  397.59  4820.6  392.76  4872.6  391.12  4923.5  388.98  4948.1   387.8
  4953.2  387.88  4981.8   386.8  4991.9  384.61    5000  381.51  5000.2  381.01
  5003.7  381.01    5004  381.51    5012  386.25  5022.1  387.28  5028.8  386.74
  5033.8  388.16  5062.4  387.52    5102  389.28  5107.4  388.97  5132.8  389.85
  5150.4  389.43  5155.5  390.36  5173.8  390.21  5193.4  390.96  5198.5  390.77
  5246.6  393.35  5266.1   392.7  5289.6  392.79  5332.6  393.56  5385.7  393.99
#Mann= 4 ,-1 , 0
  4706.4     .05       0  4923.5     .16       0    5000     .07       0
    5004     .16       0
Bank Sta=4981.8,5012
XS Rating Curve= 0 ,0
Exp/Cntr=0.3,0.1

Type RM Length L Ch R = 1 ,23754   ,393,393,393
BEGIN DESCRIPTION:
RED OAK CREEK 5 0
END DESCRIPTION:
XS GIS Cut Line= 3
      3543264.92     10413853.68      3543455.01     10413560.73
       3543500.5     10413205.96
#Sta/Elev= 30
  4751.8   395.7  4794.3  395.94  4836.6  394.88  4924.1  390.35  4945.2  387.54
  4954.4  385.41  4960.4  385.41  4968.8  383.45  4990.7  380.58  5002.8  377.51
  5006.3  377.51  5011.8  380.38  5017.7  382.32  5026.9  382.74  5032.9  384.77
    5048  384.08    5054  385.38  5103.1  385.82  5140.4  388.03  5170.7  388.19
    5211  390.73  5241.2   390.6  5261.4  391.78  5270.6  391.69  5275.7  390.85
  5291.7  391.81  5355.3  391.88  5392.5  393.51  5457.1  394.24  5458.7  394.33
#Mann= 5 ,-1 , 0
  4751.8     .05       0  4836.6     .16       0  4990.7     .07       0
  5017.7     .16       0  5457.1     .05       0
Bank Sta=4990.7,5017.7
XS Rating Curve= 0 ,0
Exp/Cntr=0.3,0.1

Type RM Length L Ch R = 1 ,23361   ,356,356,356
BEGIN DESCRIPTION:
RED OAK CREEK 43 0
END DESCRIPTION:
XS GIS Cut Line= 2
      3543432.89     10413946.14      3543898.05     10413790.22
#Sta/Elev= 30
  4798.8  397.99  4831.8  396.44  4850.7  394.66  4889.6  389.48  4894.9  389.29
  4921.2  384.97  4926.5  384.96  4952.7  381.94    4958  382.12  4984.3  380.44
  4989.6  378.14  4996.4  375.15  4996.6  374.65  5008.9     376  5015.8   378.7
  5021.1  380.59  5040.6  381.83  5072.2  385.46  5078.9  386.97  5084.2  387.03
  5103.8  390.07  5110.5  391.61    5142  394.74  5173.6  397.38    5180  397.42
  5219.8  400.24  5236.7  400.68    5242  400.14  5283.1  402.38  5289.4  403.18
#Mann= 4 ,-1 , 0
  4798.8     .07       0  4989.6     .05       0  5015.8      .1       0
    5180     .05       0
Bank Sta=4989.6,5015.8
XS Rating Curve= 0 ,0
Exp/Cntr=0.3,0.1

Type RM Length L Ch R = 1 ,23005   ,141,141,141
BEGIN DESCRIPTION:
RED OAK CREEK 42 0
END DESCRIPTION:
XS GIS Cut Line= 3
      3543069.57     10414185.73      3543599.34     10414266.64
      3543998.19     10413958.71
#Sta/Elev= 30
  4366.6   392.7  4409.6  392.61    4442   390.6  4500.4  385.03  4541.1  382.48
  4642.5  378.37  4700.9  379.26  4705.9  378.44  4769.4  380.45  4774.5  379.85
  4826.5  381.14  4907.4  380.75  4936.4  379.46  4950.9  377.44  4979.9  377.09
  4986.2  376.05    4999  370.12  5002.5  370.12  5021.5  377.33  5044.2  377.34
  5057.6  378.68    5065  377.45  5085.9  376.97    5094  378.47  5143.9  380.64
  5177.7  383.26  5207.4  385.19  5214.5  386.21  5235.3  386.89  5406.4  401.87
#Mann= 6 ,-1 , 0
  4366.6     .05       0  4826.5     .12       0  4979.9     .07       0
  5021.5     .12       0  5177.7     .16       0  5207.4     .05       0
Bank Sta=4979.9,5021.5
XS Rating Curve= 0 ,0
Exp/Cntr=0.3,0.1

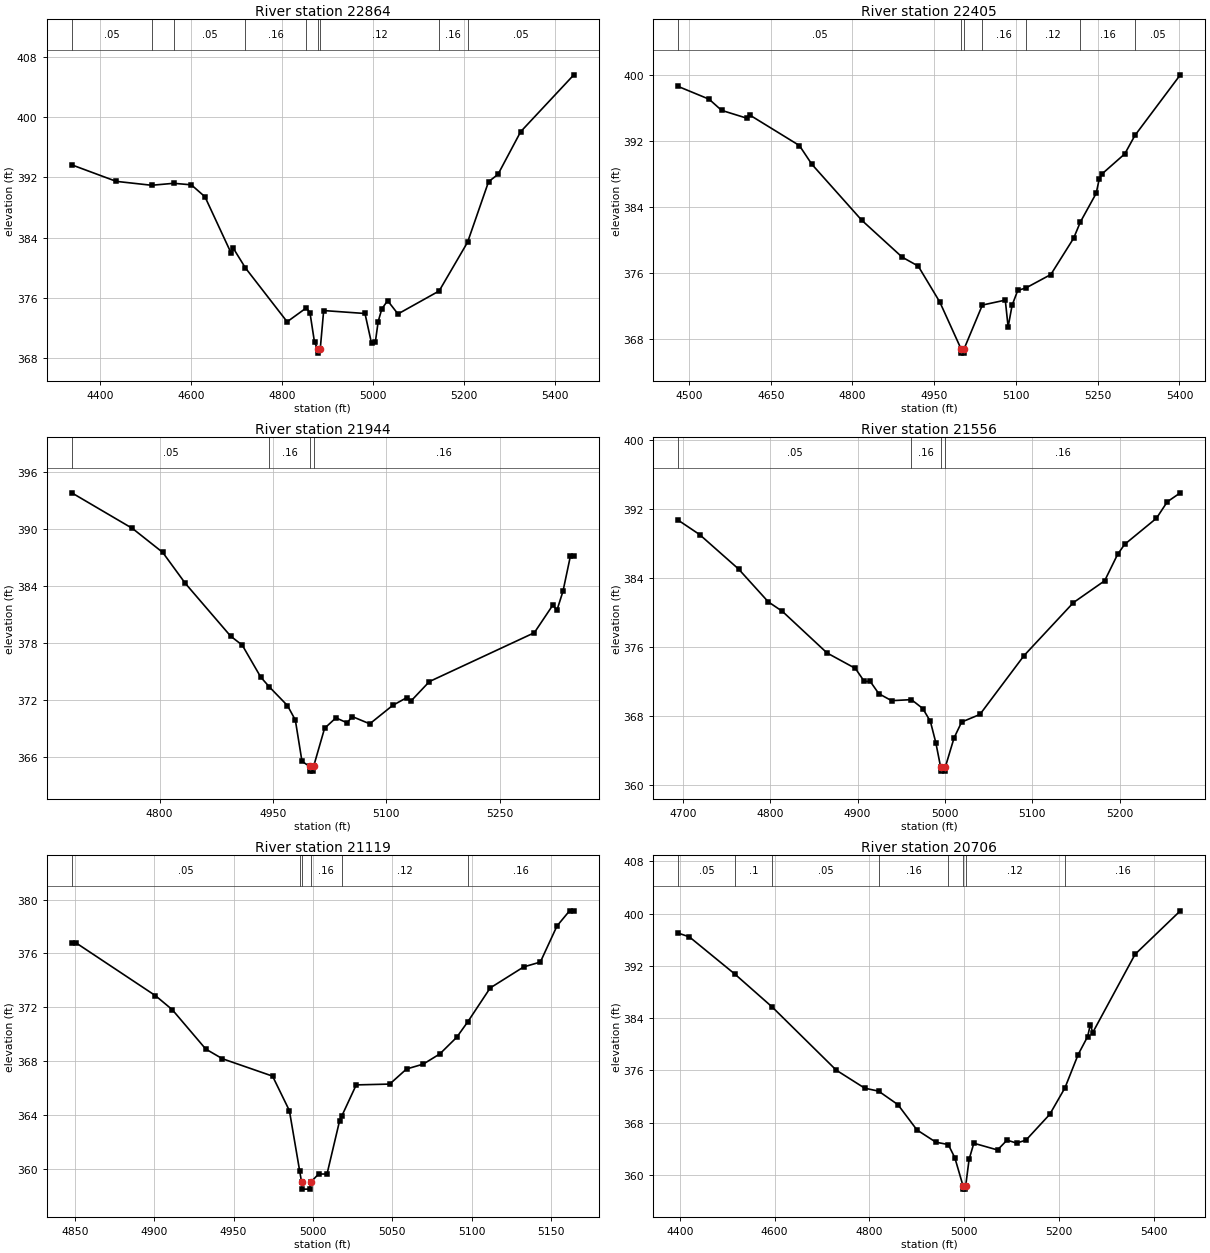
Type RM Length L Ch R = 1 ,22864   ,459,459,459
BEGIN DESCRIPTION:
Mapping XS 6337b6d4
END DESCRIPTION:
XS GIS Cut Line= 3
      3543689.38     10414943.58      3543737.56     10414332.87
      3544125.62     10414032.06
#Sta/Elev= 30
  4338.5  393.67  4436.2  391.48    4514  390.96  4562.4  391.22  4601.3  391.02
  4631.3  389.43  4688.8  381.95  4693.8  382.58  4720.2  379.99  4811.9  372.84
  4854.2  374.69  4862.1  374.04  4872.1   370.1  4879.6  369.18    4880  368.68
  4884.6  369.18  4892.2  374.33    4983  373.94  4997.5  369.96  5005.7  370.12
    5012  372.87  5020.1  374.56  5032.8  375.64  5055.5  373.88    5146  376.93
  5208.5   383.4  5254.6  391.43  5275.4  392.41  5325.2  398.07  5442.1  405.62
#Mann= 9 ,-1 , 0
  4338.5     .05       0    4514     .16       0  4562.4     .05       0
  4720.2     .16       0  4854.2     .12       0  4879.6     .07       0
  4884.6     .12       0    5146     .16       0  5208.5     .05       0
Bank Sta=4879.6,4884.6
XS Rating Curve= 0 ,0
Exp/Cntr=0.3,0.1

Type RM Length L Ch R = 1 ,22405   ,461,461,461
BEGIN DESCRIPTION:
RED OAK CREEK 40 0
END DESCRIPTION:
XS GIS Cut Line= 3
      3543843.54      10415008.6      3544028.13     10414611.51
      3544142.11     10414141.63
#Sta/Elev= 30
  4480.2  398.63  4536.8  397.09  4559.7  395.74  4605.5   394.8    4611  395.19
  4702.5  391.48  4725.4  389.21    4817  382.43  4891.2  377.96  4920.6  376.88
  4960.2  372.53  4999.3  366.84  4999.8  366.34  5004.3  366.34  5004.7  366.84
  5038.3  372.16  5080.4  372.76  5085.6  369.51  5092.9  372.13  5103.2  373.93
  5118.2  374.23    5164  375.86  5205.8  380.25  5218.2  382.22  5247.2  385.69
  5252.8  387.42  5257.9  388.04  5299.7  390.47  5318.3   392.7  5401.6  400.04
#Mann= 7 ,-1 , 0
  4480.2     .05       0  4999.3     .03       0  5004.7     .05       0
  5038.3     .16       0  5118.2     .12       0  5218.2     .16       0
  5318.3     .05       0
Bank Sta=4999.3,5004.7
XS Rating Curve= 0 ,0
Exp/Cntr=0.3,0.1

Type RM Length L Ch R = 1 ,21944   ,388,388,388
BEGIN DESCRIPTION:
RED OAK CREEK 4 0
END DESCRIPTION:
XS GIS Cut Line= 3
      3544426.91     10414881.87      3544433.42     10414667.01
      3544596.18     10414248.18
#Sta/Elev= 30
  4683.9  393.85  4764.2   390.1  4804.2  387.58  4834.2  384.31    4894  378.77
  4909.5  377.81    4934  374.44  4945.5   373.4  4969.3  371.45  4979.7  369.93
  4988.5  365.58  4998.5  365.05  4998.9  364.55  5003.5  364.55  5003.9  365.05
  5018.4  369.06  5033.4  370.16  5048.3  369.63  5054.8   370.3  5078.2  369.53
  5108.5  371.47  5127.2  372.29  5132.6  371.92  5157.1  373.98  5295.9  379.12
  5320.4  382.03  5325.8  381.48  5333.8  383.48  5343.7  387.21  5348.2  387.21
#Mann= 4 ,-1 , 0
  4683.9     .05       0  4945.5     .16       0  4998.5     .07       0
  5003.9     .16       0
Bank Sta=4998.5,5003.9
XS Rating Curve= 0 ,0
Exp/Cntr=0.3,0.1

Type RM Length L Ch R = 1 ,21556   ,437,437,437
BEGIN DESCRIPTION:
RED OAK CREEK 39 0
END DESCRIPTION:
XS GIS Cut Line= 3
      3544570.11     10414910.09      3544763.28     10414812.41
      3544969.44     10414519.45
#Sta/Elev= 30
  4694.8   390.7  4719.2  389.04  4763.8  385.04  4797.9  381.22    4814  380.12
  4865.1  375.29  4897.5   373.5  4907.8  371.98  4914.6  371.98  4924.4  370.56
    4939  369.75  4961.7  369.87  4974.7  368.84  4983.4  367.35  4989.6  364.89
  4995.1  362.07  4995.5  361.57  5000.1  361.57  5000.6  362.07  5010.5  365.42
  5019.2  367.27  5040.1  368.15  5090.6  374.98  5147.2  381.14  5182.9  383.67
  5197.7  386.73  5205.7  387.89  5242.2  390.93  5254.6  392.84  5269.5  393.88
#Mann= 4 ,-1 , 0
  4694.8     .05       0  4961.7     .16       0  4995.1     .07       0
  5000.6     .16       0
Bank Sta=4995.1,5000.6
XS Rating Curve= 0 ,0
Exp/Cntr=0.3,0.1

Type RM Length L Ch R = 1 ,21119   ,413,413,413
BEGIN DESCRIPTION:
RED OAK CREEK 38 0
END DESCRIPTION:
XS GIS Cut Line= 3
      3545142.09     10415091.69      3545192.11     10414941.64
      3545242.11     10414791.62
#Sta/Elev= 30
  4848.1  376.78  4850.8  376.78  4900.8  372.87  4911.4  371.83  4932.5  368.91
    4943  368.19  4974.6   366.9  4985.2  364.34  4991.7  359.85  4992.9  359.02
  4993.4  358.52  4998.1  358.52  4998.5  359.02  5003.6  359.64  5008.9  359.64
  5016.8  363.58  5018.2  363.94  5027.3  366.25  5048.4  366.31    5059  367.43
  5069.5  367.79    5080  368.55  5090.6  369.78  5097.7  370.95  5111.7  373.44
  5132.8     375  5143.3  375.36  5153.8  378.04  5161.7  379.16  5164.4  379.16
#Mann= 6 ,-1 , 0
  4848.1     .05       0  4991.7     .16       0  4992.9     .07       0
  4998.5     .16       0  5018.2     .12       0  5097.7     .16       0
Bank Sta=4992.9,4998.5
XS Rating Curve= 0 ,0
Exp/Cntr=0.3,0.1

Type RM Length L Ch R = 1 ,20706   ,511,511,511
BEGIN DESCRIPTION:
RED OAK CREEK 37 0
END DESCRIPTION:
XS GIS Cut Line= 2
       3545557.9      10415634.9      3545605.62     10414576.27
#Sta/Elev= 30
  4396.5  397.02  4419.8  396.46    4516  390.75  4594.9   385.7  4730.1  376.03
  4790.2  373.27  4819.4  372.82  4860.2  370.75  4900.3  366.88  4940.3     365
  4966.4  364.64  4980.3  362.62  4997.6  358.31    4998  357.81  5002.7  357.81
  5003.2  358.31  5010.4  362.37  5020.4  364.84  5070.4  363.81  5090.5  365.32
  5110.5  364.86  5130.5  365.32  5180.6  369.26  5212.7  373.32  5240.6  378.43
  5260.6  381.18  5266.3  383.02  5271.4   381.8  5360.7  393.78  5456.2  400.44
#Mann= 8 ,-1 , 0
  4396.5     .05       0    4516      .1       0  4594.9     .05       0
  4819.4     .16       0  4966.4     .12       0  4997.6     .07       0
  5003.2     .12       0  5212.7     .16       0
Bank Sta=4997.6,5003.2
XS Rating Curve= 0 ,0
Exp/Cntr=0.3,0.1

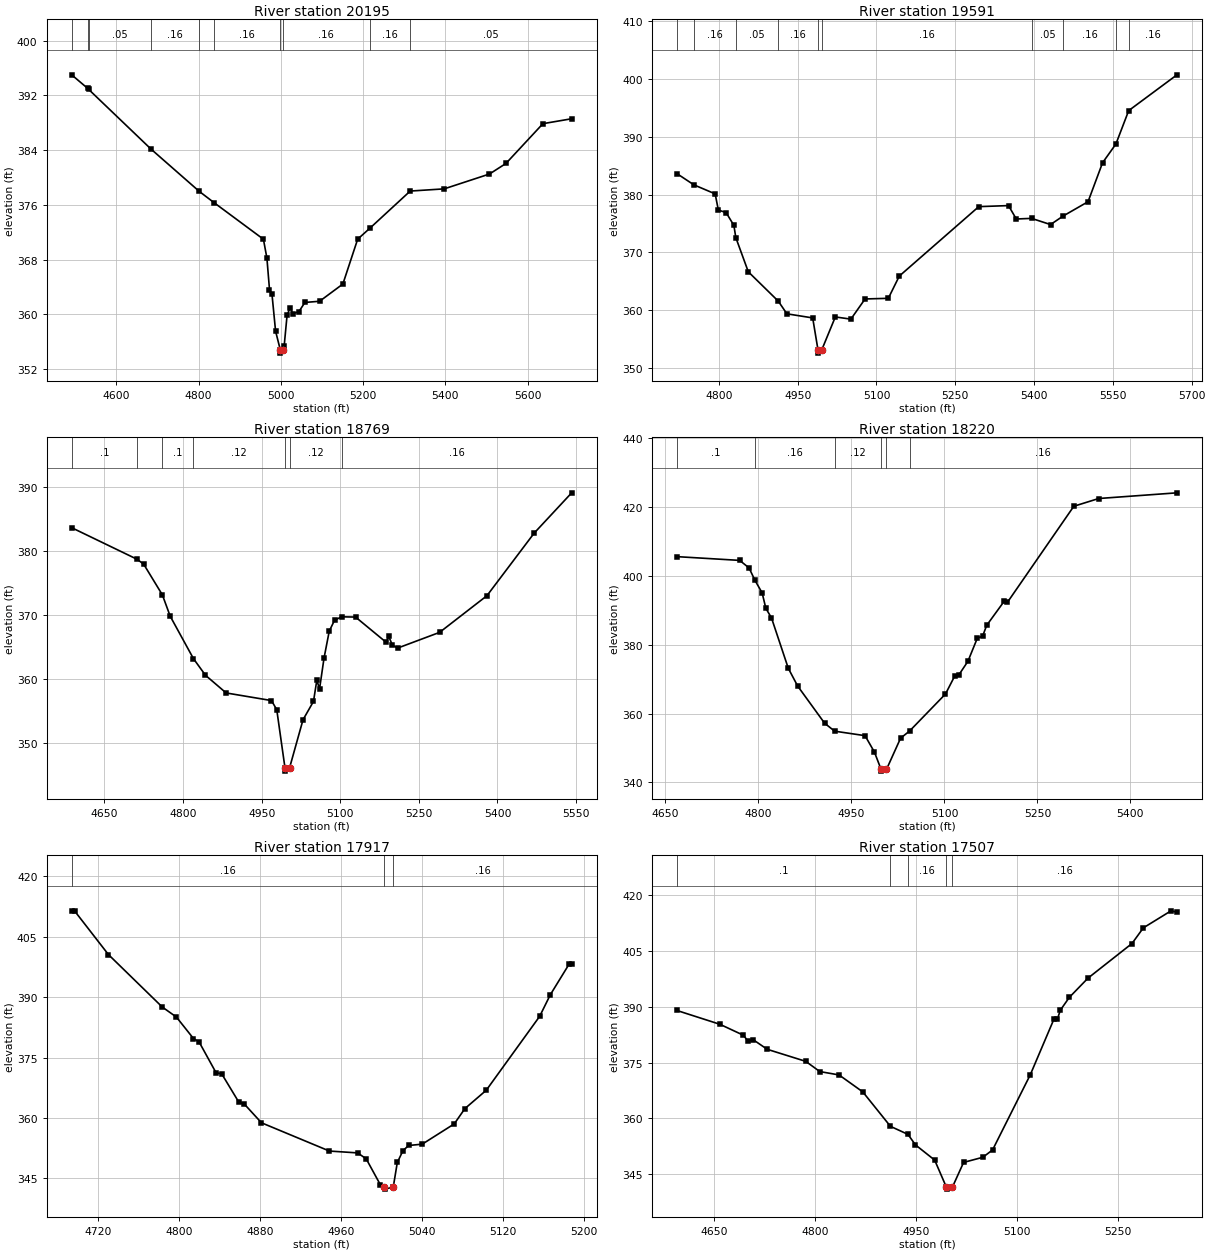
Type RM Length L Ch R = 1 ,20195   ,604,604,604
BEGIN DESCRIPTION:
RED OAK CREEK 36 0
END DESCRIPTION:
XS GIS Cut Line= 3
      3545658.76     10415628.87      3546073.68     10415043.82
      3546571.99     10415055.98
#Sta/Elev= 30
  4491.5  395.01  4530.4  393.03    4533  392.87  4684.5  384.15    4802  377.96
  4837.6  376.33  4957.7  370.98  4966.2  368.23  4972.5  363.63  4978.6   362.9
  4987.3  357.54  4998.7  354.83  4999.2  354.33  5005.4  354.83  5008.2  355.39
  5015.3   359.9    5023  360.98  5029.1  360.08  5043.9  360.39  5058.6  361.74
  5094.3  361.91  5150.9  364.43  5186.9  370.99  5215.9  372.55  5314.6  378.02
  5397.2  378.34  5507.3  380.51  5547.3  382.05  5637.3  387.87  5707.2  388.59
#Mann= 10 ,-1 , 0
  4491.5     .05       0  4530.4      .1       0    4533     .05       0
  4684.5     .16       0    4802     .05       0  4837.6     .16       0
  4998.7     .07       0  5005.4     .16       0  5215.9     .16       0
  5314.6     .05       0
Bank Sta=4998.7,5005.4
XS Rating Curve= 0 ,0
Exp/Cntr=0.3,0.1

Type RM Length L Ch R = 1 ,19591   ,822,822,822
BEGIN DESCRIPTION:
RED OAK CREEK 35 0
END DESCRIPTION:
XS GIS Cut Line= 2
      3546061.33     10415791.21      3546837.68      10415240.4
#Sta/Elev= 30
  4720.2  383.64  4752.4   381.7  4792.9  380.14    4799  377.34  4813.8   376.9
  4828.6  374.68  4832.2  372.59    4856  366.66  4913.1  361.58  4929.5  359.39
  4978.6  358.68  4988.8  353.09  4989.3  352.59  4995.6  353.09  5021.7  358.85
  5051.3  358.47  5078.3  361.96  5122.6  362.07  5143.5  365.92  5294.8  377.93
  5351.4  378.11  5366.2  375.79  5395.2   375.9  5431.4  374.83  5455.5  376.31
  5502.8  378.78  5530.4  385.51  5555.9  388.77  5580.2  394.54  5672.1  400.73
#Mann= 10 ,-1 , 0
  4720.2     .05       0  4752.4     .16       0  4832.2     .05       0
  4913.1     .16       0  4988.8     .07       0  4995.6     .16       0
  5395.2     .05       0  5455.5     .16       0  5555.9     .05       0
  5580.2     .16       0
Bank Sta=4988.8,4995.6
XS Rating Curve= 0 ,0
Exp/Cntr=0.3,0.1

Type RM Length L Ch R = 1 ,18769   ,549,549,549
BEGIN DESCRIPTION:
RED OAK CREEK 34 0
END DESCRIPTION:
XS GIS Cut Line= 3
      3546356.52      10416290.3       3546495.4      10416008.2
      3547133.38     10415960.46
#Sta/Elev= 30
  4587.4  383.65  4712.6   378.7  4724.9  377.94  4760.5  373.15  4775.4  369.82
  4819.9  363.17  4842.8  360.58  4882.2  357.82  4968.7  356.63  4978.8   355.2
  4994.5   346.1    4995   345.6  5003.2   346.1  5028.9  353.63  5048.9   356.5
  5055.3  359.84  5060.4  358.41    5069  363.27    5079  367.49  5089.1  369.19
  5102.5  369.72  5129.2  369.68  5187.5  365.74  5192.5  366.66  5199.4   365.3
  5209.4  364.83  5289.6  367.29  5379.9  373.02  5470.1  382.81  5541.6   389.1
#Mann= 7 ,-1 , 0
  4587.4      .1       0  4712.6     .16       0  4760.5      .1       0
  4819.9     .12       0  4994.5     .07       0  5003.2     .12       0
  5102.5     .16       0
Bank Sta=4994.5,5003.2
XS Rating Curve= 0 ,0
Exp/Cntr=0.3,0.1

Type RM Length L Ch R = 1 ,18220   ,303,303,303
BEGIN DESCRIPTION:
RED OAK CREEK 33 0
END DESCRIPTION:
XS GIS Cut Line= 3
      3546502.49     10416621.96       3546915.7     10416352.85
      3547227.63     10416384.04
#Sta/Elev= 30
  4668.5  405.56  4769.7  404.47  4784.8  402.28  4794.2  398.73  4805.9  395.03
  4811.9  390.55    4821  387.77  4848.1  373.14  4863.2  367.99  4906.7  357.19
  4922.9  354.88  4971.9  353.58    4987  348.83  4997.8  343.78  4998.3  343.28
  5006.5  343.78  5029.2  352.83    5044  354.97  5101.7  365.68  5116.8  370.97
  5122.8  371.11  5137.9  375.18    5153  381.87  5161.6  382.47  5168.1   385.6
  5196.4  392.61  5201.5  392.27  5308.7  420.19  5348.9  422.44  5475.1  424.09
#Mann= 6 ,-1 , 0
  4668.5      .1       0  4794.2     .16       0  4922.9     .12       0
  4997.8     .07       0  5006.5     .12       0    5044     .16       0
Bank Sta=4997.8,5006.5
XS Rating Curve= 0 ,0
Exp/Cntr=0.3,0.1

Type RM Length L Ch R = 1 ,17917   ,410,410,410
BEGIN DESCRIPTION:
RED OAK CREEK 32 0
END DESCRIPTION:
XS GIS Cut Line= 3
      3546642.11     10416841.64      3546942.11     10416691.64
      3547092.08     10416641.65
#Sta/Elev= 30
  4694.3  411.43  4697.1  411.43  4730.6  400.57  4783.7  387.56  4797.7  385.06
  4814.5  379.74  4820.1  378.88  4836.8  371.25  4842.4  370.97  4859.2  363.98
  4864.8  363.45  4881.6  358.83  4948.7  351.81  4976.6  351.35    4985  349.88
    4999  343.44    5003  342.86  5003.5  342.36  5011.7  342.86  5015.7  348.97
  5021.3  351.91  5026.9  353.19  5040.3  353.52  5071.9  358.55  5082.4  362.34
  5103.5   366.9  5156.2  385.24  5166.7  390.59  5185.2  398.17  5187.8  398.17
#Mann= 3 ,-1 , 0
  4694.3     .16       0    5003     .07       0  5011.7     .16       0
Bank Sta=5003,5011.7
XS Rating Curve= 0 ,0
Exp/Cntr=0.3,0.1

Type RM Length L Ch R = 1 ,17507   ,532,532,532
BEGIN DESCRIPTION:
RED OAK CREEK 30 0
END DESCRIPTION:
XS GIS Cut Line= 3
      3546882.69     10417351.13      3547245.56     10416918.82
      3547288.96     10416746.93
#Sta/Elev= 30
  4595.4     389    4659   385.3  4694.1  382.34  4700.6  380.79  4708.4  381.16
  4729.3  378.57  4786.5  375.33  4807.3  372.59  4835.9  371.68  4871.1  367.12
  4912.1  357.87  4938.1  355.71  4949.1   352.9  4977.7   348.8  4995.1   341.5
  4995.6     341  5003.9   341.5  5020.6  348.18  5049.2  349.56  5063.6  351.54
  5119.5  371.72  5154.7  386.72  5159.8  386.72  5164.1  389.08  5177.5  392.54
  5205.1  397.69  5270.4     407  5287.2   411.2  5328.3  415.78  5337.1  415.42
#Mann= 5 ,-1 , 0
  4595.4      .1       0  4912.1     .12       0  4938.1     .16       0
  4995.1     .07       0  5003.9     .16       0
Bank Sta=4995.1,5003.9
XS Rating Curve= 0 ,0
Exp/Cntr=0.3,0.1

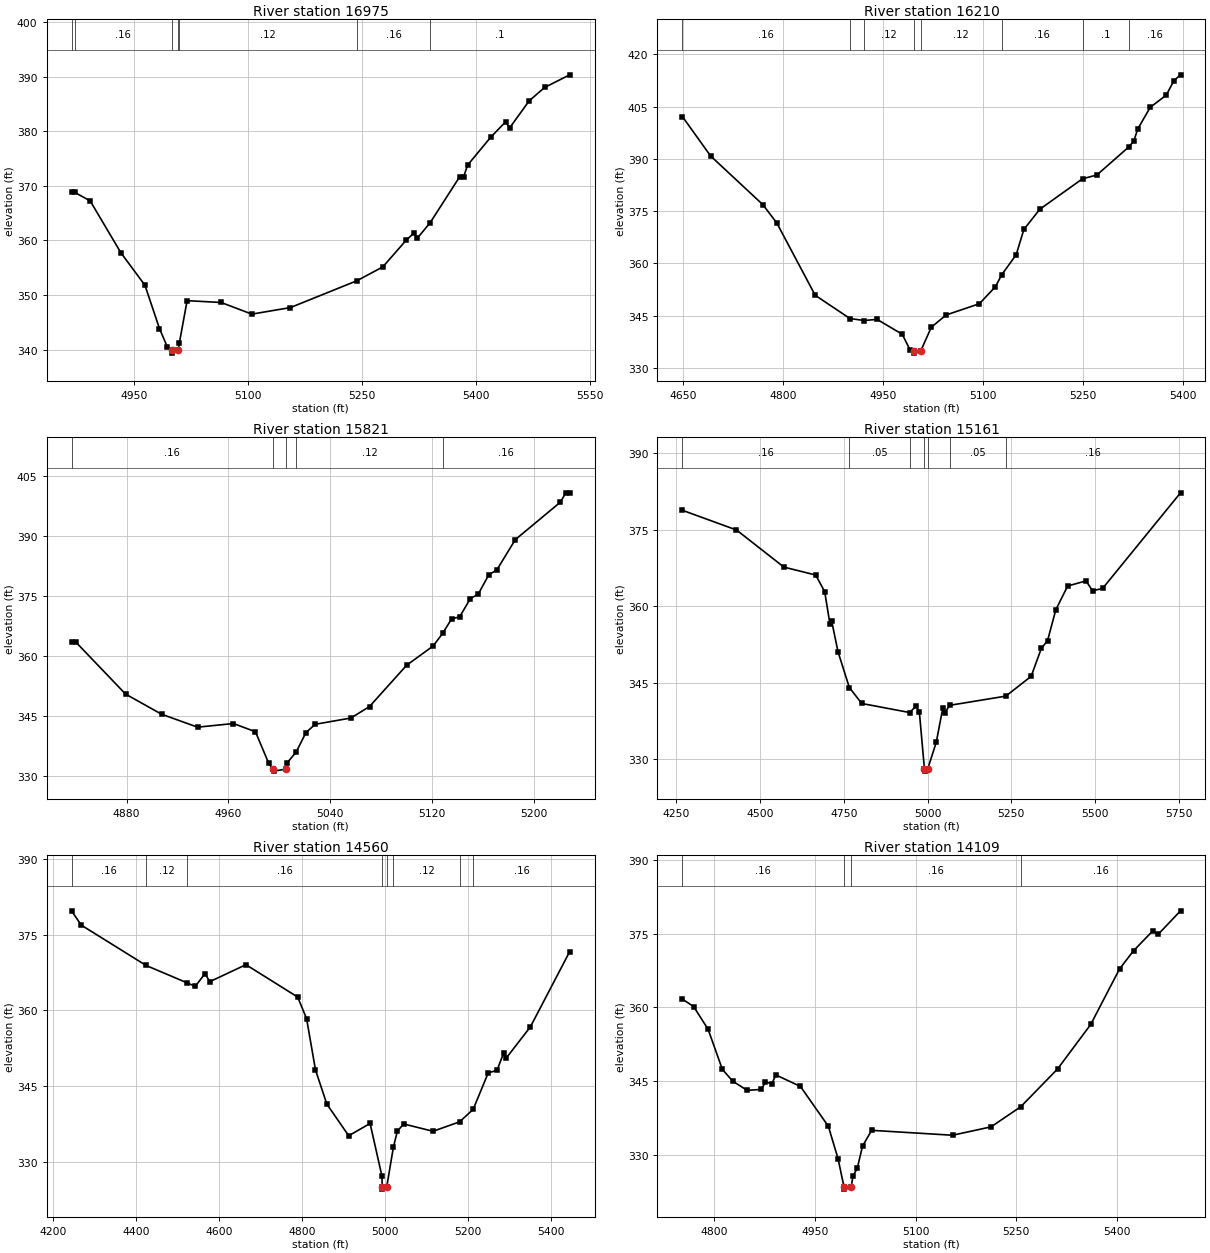
Type RM Length L Ch R = 1 ,16975   ,765,765,765
BEGIN DESCRIPTION:
RED OAK CREEK 3 0
END DESCRIPTION:
XS GIS Cut Line= 2
      3547571.78     10417405.79       3547680.3     10416759.03
#Sta/Elev= 30
  4868.1   368.8  4872.3   368.8  4892.6  367.24  4933.1  357.72  4964.7  351.78
  4983.8  343.85    4994  340.52  4999.7  339.84  5000.2  339.34  5008.5  339.84
    5010   341.2  5020.2  348.96    5065  348.62  5105.5  346.49  5156.2  347.69
  5243.8  352.61  5277.9  355.15  5308.3  359.99  5318.3  361.28  5323.4  360.42
  5340.2  363.25    5379  371.65  5384.1  371.59  5389.4  373.79  5419.9  378.91
  5439.6  381.75  5444.7   380.6  5470.6  385.59  5490.8  388.03  5523.9  390.35
#Mann= 7 ,-1 , 0
  4868.1     .05       0  4872.3     .16       0  4999.7     .07       0
  5008.5     .16       0    5010     .12       0  5243.8     .16       0
  5340.2      .1       0
Bank Sta=4999.7,5008.5
XS Rating Curve= 0 ,0
Exp/Cntr=0.3,0.1

Type RM Length L Ch R = 1 ,16210   ,389,389,389
BEGIN DESCRIPTION:
RED OAK CREEK 29 0
END DESCRIPTION:
XS GIS Cut Line= 3
      3548242.11     10417241.65      3548042.11     10416991.64
      3547892.09     10416591.61
#Sta/Elev= 30
  4648.6  402.12    4691   390.8  4769.5  376.81  4790.3  371.56  4847.9  350.83
    4900  344.16  4921.2  343.59  4940.7  343.92  4978.5  339.64  4990.1  335.19
  4995.7  334.73  4996.2  334.23  5005.9  334.73  5022.2  341.69  5044.4  345.18
  5094.3  348.41  5118.3   353.3    5128  356.79  5149.4  362.45    5161  369.73
    5185  375.53    5249  384.27  5270.5  385.34  5318.1  393.35  5325.7  394.99
  5331.9  398.56  5350.6  404.77  5374.6  408.26  5386.2  412.43    5396  414.09
#Mann= 8 ,-1 , 0
  4648.6     .16       0    4900      .1       0  4921.2     .12       0
  4995.7     .07       0  5005.9     .12       0    5128     .16       0
    5249      .1       0  5318.1     .16       0
Bank Sta=4995.7,5005.9
XS Rating Curve= 0 ,0
Exp/Cntr=0.3,0.1

Type RM Length L Ch R = 1 ,15821   ,660,660,660
BEGIN DESCRIPTION:
RED OAK CREEK 28 0
END DESCRIPTION:
XS GIS Cut Line= 3
      3548392.08     10416791.62      3548292.11     10416691.64
       3548092.1     10416541.64
#Sta/Elev= 30
  4836.7  363.48  4840.2  363.48  4879.1  350.54  4907.4   345.5  4935.7  342.26
  4963.9  343.17  4981.2  341.11  4991.6  333.22  4994.9  331.77  4995.4  331.27
  5005.1  331.77  5006.2   333.4  5013.2  336.05  5020.8  340.88  5028.1  342.98
  5056.2  344.55  5070.8  347.42    5100  357.75  5120.8  362.55  5128.2  365.69
  5135.4  369.38  5141.6  369.82    5150   374.4  5156.2  375.51  5164.5  380.34
  5170.8  381.56  5185.4  389.16  5220.8  398.52    5225  400.85  5228.1  400.85
#Mann= 5 ,-1 , 0
  4836.7     .16       0  4994.9     .07       0  5005.1     .16       0
  5013.2     .12       0  5128.2     .16       0
Bank Sta=4994.9,5005.1
XS Rating Curve= 0 ,0
Exp/Cntr=0.3,0.1

Type RM Length L Ch R = 1 ,15161   ,601,601,601
BEGIN DESCRIPTION:
RED OAK CREEK 27 0
END DESCRIPTION:
XS GIS Cut Line= 4
      3548795.47     10417062.07      3548850.16     10416645.39
       3548752.5     10415987.83      3548377.55     10415844.62
#Sta/Elev= 30
  4268.3  378.77  4429.8  374.91  4571.3  367.64  4666.1  366.09    4693  362.83
  4708.4  356.58  4713.5  357.16  4732.8  351.04  4766.6  344.04  4803.6  340.93
  4946.3  339.16  4965.3   340.4  4975.4  339.29  4990.5  328.18    4991  327.68
  5000.8  328.18    5026  333.37  5045.4  340.03  5050.5  339.05    5066  340.57
  5233.4  342.37    5309  346.25  5339.4  351.71  5357.9  353.23  5382.6  359.28
    5418  363.94  5472.8  364.94  5492.2  363.01  5522.2  363.46  5754.7  382.19
#Mann= 7 ,-1 , 0
  4268.3     .16       0  4766.6     .05       0  4946.3     .12       0
  4990.5     .07       0  5000.8     .12       0    5066     .05       0
  5233.4     .16       0
Bank Sta=4990.5,5000.8
XS Rating Curve= 0 ,0
Exp/Cntr=0.3,0.1

Type RM Length L Ch R = 1 ,14560   ,451,451,451
BEGIN DESCRIPTION:
RED OAK CREEK 26 0
END DESCRIPTION:
XS GIS Cut Line= 3
      3549898.33      10416595.9      3549490.78     10416420.13
       3549108.4     10415765.92
#Sta/Elev= 30
  4243.9   379.7  4267.1  376.88  4423.8  368.88  4521.6  365.48  4542.2  364.74
  4565.7  367.26  4577.4  365.68  4664.5  369.04  4789.3  362.63  4810.8  358.36
  4832.3   348.2  4859.7  341.43  4912.4  335.18    4964  337.61  4992.6  327.17
  4993.2  325.11  4993.7  324.61  5004.2  325.11  5020.3  332.95  5029.8  336.09
    5045  337.51  5115.8  336.06  5179.9  337.93  5212.7  340.41  5248.8  347.59
  5270.3  348.16    5286  351.53  5291.8  350.49  5350.5  356.71  5445.5  371.62
#Mann= 8 ,-1 , 0
  4243.9     .16       0  4423.8     .12       0  4521.6     .16       0
  4993.2     .07       0  5004.2     .16       0  5020.3     .12       0
  5179.9      .1       0  5212.7     .16       0
Bank Sta=4993.2,5004.2
XS Rating Curve= 0 ,0
Exp/Cntr=0.3,0.1

Type RM Length L Ch R = 1 ,14109   ,338,338,338
BEGIN DESCRIPTION:
RED OAK CREEK 25 0
END DESCRIPTION:
XS GIS Cut Line= 3
      3549828.55     10416116.62      3549745.21     10415978.59
      3549297.28     10415608.78
#Sta/Elev= 30
  4752.7  361.68  4769.6  360.13    4791  355.53  4812.3  347.34  4827.8  344.94
  4849.2  343.08  4870.5  343.27  4876.4   344.8    4886   344.4  4891.9  346.23
  4928.6  343.87  4970.2  335.75  4984.6  329.16  4993.4  323.45  4993.9  322.95
  5004.4  323.45  5006.7  325.59  5013.2  327.18  5021.1  331.73  5034.7  334.93
  5155.2  333.93  5212.6  335.64  5256.9  339.75  5311.6  347.43  5361.1  356.52
  5404.1  367.85  5424.9  371.53  5453.6  375.59  5461.4  374.85  5494.8  379.66
#Mann= 4 ,-1 , 0
  4752.7     .16       0  4993.4     .07       0  5004.4     .16       0
  5256.9     .16       0
Bank Sta=4993.4,5004.4
XS Rating Curve= 0 ,0
Exp/Cntr=0.3,0.1

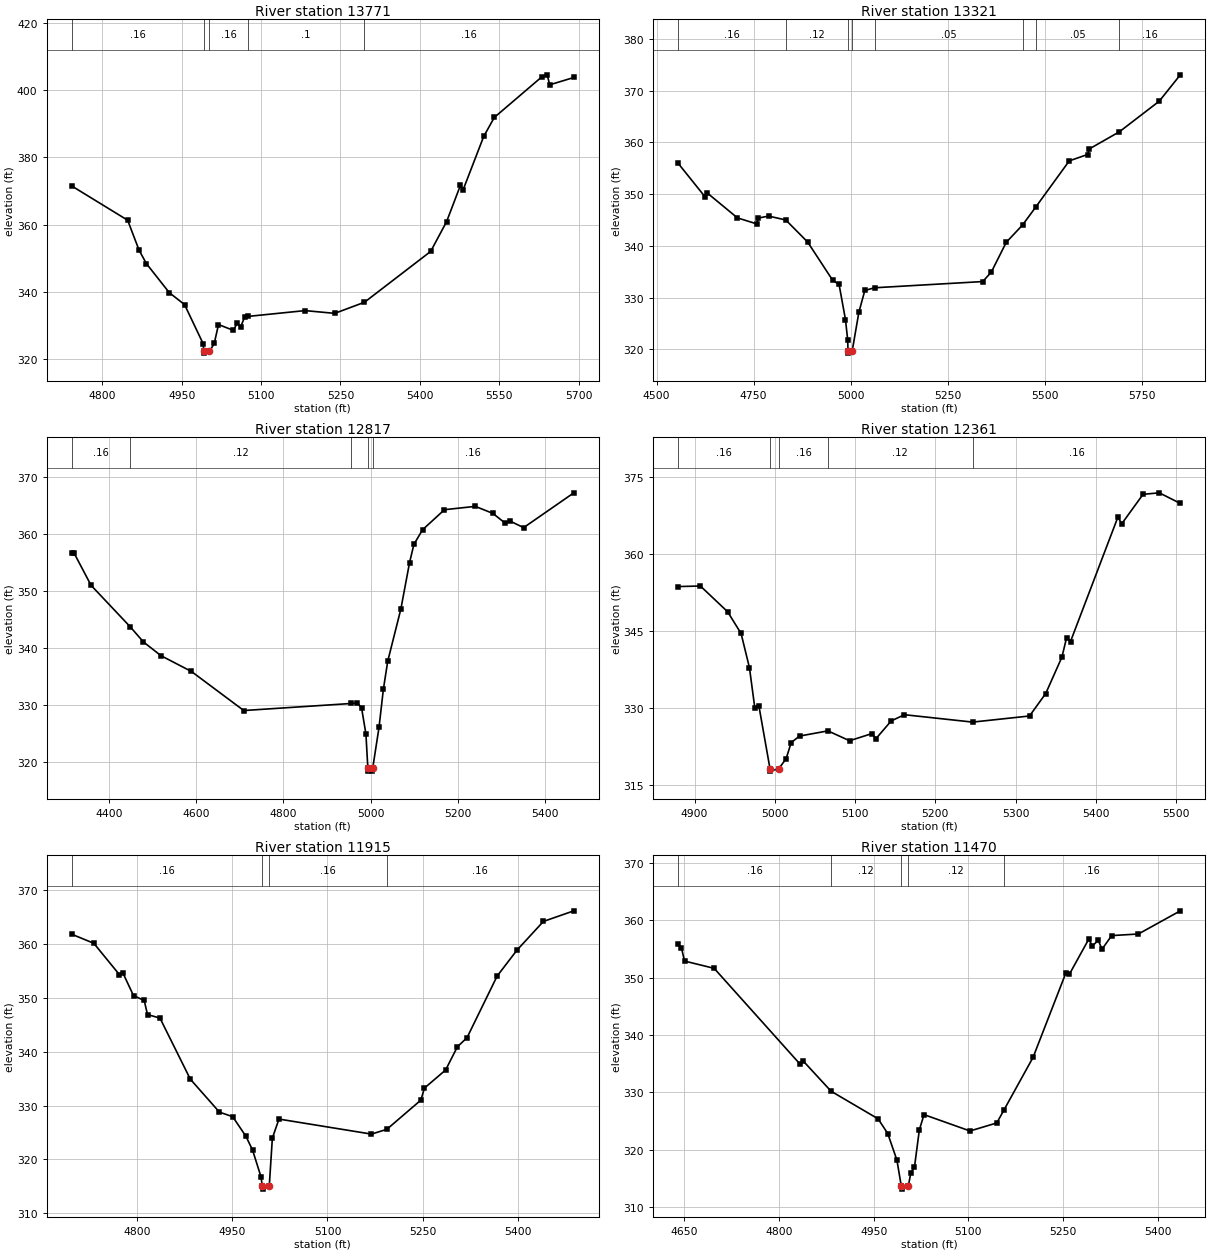
Type RM Length L Ch R = 1 ,13771   ,450,450,450
BEGIN DESCRIPTION:
RED OAK CREEK 24 0
END DESCRIPTION:
XS GIS Cut Line= 3
      3550101.96     10415840.56      3549596.77     10415442.13
      3549292.11      10415423.9
#Sta/Elev= 30
  4742.3  371.45  4847.9  361.27  4869.5  352.35  4883.2   348.4  4926.5  339.75
  4955.4  336.19  4990.7  324.51  4991.5  322.27    4992  321.77  5002.5  322.27
  5011.5  324.65  5019.5  330.27  5047.8  328.52  5054.8  330.75  5061.2  329.47
  5069.2  332.62    5075  332.68  5183.1  334.41  5239.1  333.59  5295.3  336.89
  5420.4     352  5450.5  360.86  5476.6  371.63  5481.6  370.28  5520.6  386.17
  5540.6  391.82  5630.8  403.94  5640.4  404.49  5645.4  401.53  5690.9   403.7
#Mann= 5 ,-1 , 0
  4742.3     .16       0  4991.5     .07       0  5002.5     .16       0
    5075      .1       0  5295.3     .16       0
Bank Sta=4991.5,5002.5
XS Rating Curve= 0 ,0
Exp/Cntr=0.3,0.1

Type RM Length L Ch R = 1 ,13321   ,504,504,504
BEGIN DESCRIPTION:
RED OAK CREEK 23 0
END DESCRIPTION:
XS GIS Cut Line= 4
       3550302.5     10415733.75      3550276.46     10415387.44
      3549807.71     10415142.65      3549398.81     10415220.78
#Sta/Elev= 30
  4555.8  355.94  4625.4  349.43  4630.4  350.23  4708.3  345.41  4757.3  344.27
  4762.3  345.39  4788.6  345.76  4832.6  345.01  4888.8  340.76  4953.4  333.35
  4969.8  332.56  4986.3  325.75  4991.9  321.89  4992.8  319.78  4993.3  319.28
  5003.8  319.78  5020.8  327.19  5036.1  331.39  5061.1  331.91  5339.6  333.11
  5361.7  334.94  5400.2   340.7    5442  344.03  5476.1  347.51  5562.3  356.43
  5609.3  357.66  5614.4  358.76  5691.3  362.05  5793.9  367.96  5848.2  373.06
#Mann= 8 ,-1 , 0
  4555.8     .16       0  4832.6     .12       0  4992.8     .07       0
  5003.8     .12       0  5061.1     .05       0    5442     .16       0
  5476.1     .05       0  5691.3     .16       0
Bank Sta=4992.8,5003.8
XS Rating Curve= 0 ,0
Exp/Cntr=0.3,0.1

Type RM Length L Ch R = 1 ,12817   ,456,456,456
BEGIN DESCRIPTION:
RED OAK CREEK 22 0
END DESCRIPTION:
XS GIS Cut Line= 3
      3550555.11     10415785.88      3550547.29     10414947.34
      3550586.35     10414637.47
#Sta/Elev= 30
  4314.7  356.73  4319.3  356.73  4358.9  350.97  4448.5   343.7  4478.9  341.03
    4519  338.62    4589  335.84    4709  328.98  4955.6  330.22    4969  330.34
    4979  329.45    4989  324.85  4993.4  318.84  4993.9  318.34    5004  318.34
  5004.5  318.84    5019  326.02    5029  332.73    5039  337.65    5069  346.78
    5089  354.96    5099  358.17    5119  360.74  5169.1  364.25  5239.7  364.83
    5280   363.6  5308.4  361.87  5320.3  362.21  5350.5   361.1  5465.6  367.21
#Mann= 5 ,-1 , 0
  4314.7     .16       0  4448.5     .12       0  4955.6     .16       0
  4993.4     .07       0  5004.5     .16       0
Bank Sta=4993.4,5004.5
XS Rating Curve= 0 ,0
Exp/Cntr=0.3,0.1

Type RM Length L Ch R = 1 ,12361   ,446,446,446
BEGIN DESCRIPTION:
RED OAK CREEK 20 0
END DESCRIPTION:
XS GIS Cut Line= 3
      3550880.61     10415436.97      3550956.15      10415171.3
       3551008.1     10414825.78
#Sta/Elev= 30
  4879.6  353.59  4907.2   353.7  4941.1  348.69  4957.9  344.45  4968.3  337.81
    4975  329.98  4980.2  330.26  4993.9  318.14  4994.4  317.64    5005  318.14
  5014.1  320.08  5020.3  323.19  5030.7  324.47  5066.1  325.48  5093.1  323.56
  5120.9  324.95  5126.1  323.99    5145  327.42  5161.4  328.63  5246.4  327.19
  5317.3  328.38  5337.5  332.76  5357.7  339.86  5363.4  343.57  5368.4  342.89
  5427.3  367.07  5432.4  365.86  5458.8  371.56    5479  371.85  5505.2  369.79
#Mann= 5 ,-1 , 0
  4879.6     .16       0  4993.9     .07       0    5005     .16       0
  5066.1     .12       0  5246.4     .16       0
Bank Sta=4993.9,5005
XS Rating Curve= 0 ,0
Exp/Cntr=0.3,0.1

Type RM Length L Ch R = 1 ,11915   ,445,445,445
BEGIN DESCRIPTION:
RED OAK CREEK 2 0
END DESCRIPTION:
XS GIS Cut Line= 2
      3551338.95     10415515.02      3551120.49     10414755.62
#Sta/Elev= 30
  4697.6  361.83  4732.3  360.15  4772.7  354.31  4777.9  354.68  4794.8  350.43
  4811.6  349.53  4816.8  346.91  4836.4  346.26  4884.2  334.91    4930  328.79
  4950.9  327.94  4971.7   324.3  4982.1  321.76  4995.7  316.67  4997.3  314.99
  4997.8  314.49  5008.4  314.99  5013.3  323.96  5023.7   327.5  5169.3  324.71
  5193.5   325.6  5247.1  331.03  5252.6  333.25    5286  336.62  5304.6  340.94
  5319.7  342.62  5367.1  354.07  5398.3  358.88  5439.9  364.21  5487.8  366.18
#Mann= 4 ,-1 , 0
  4697.6     .16       0  4997.3     .07       0  5008.4     .16       0
  5193.5     .16       0
Bank Sta=4997.3,5008.4
XS Rating Curve= 0 ,0
Exp/Cntr=0.3,0.1

Type RM Length L Ch R = 1 ,11470   ,397,397,397
BEGIN DESCRIPTION:
RED OAK CREEK 19 0
END DESCRIPTION:
XS GIS Cut Line= 3
      3551656.67     10415288.49      3551669.69      10415046.3
      3551203.54     10414749.42
#Sta/Elev= 30
  4640.5  355.84  4645.5  355.25  4650.5  352.92  4697.4  351.65  4833.8   334.9
  4838.8  335.45  4882.6  330.22    4957  325.41  4972.3  322.85  4986.9  318.19
  4993.8  313.65  4994.3  313.15  5004.9  313.65  5008.7  315.91  5014.6  316.95
  5022.4   323.5  5029.8  326.14  5102.6  323.29    5145  324.69  5156.3  326.93
  5202.5  336.13  5254.2  350.78  5260.1  350.64  5290.6  356.72  5296.5  355.59
  5305.8  356.52  5311.7  354.99    5327  357.36  5369.3  357.64  5435.7  361.68
#Mann= 5 ,-1 , 0
  4640.5     .16       0  4882.6     .12       0  4993.8     .07       0
  5004.9     .12       0  5156.3     .16       0
Bank Sta=4993.8,5004.9
XS Rating Curve= 0 ,0
Exp/Cntr=0.3,0.1