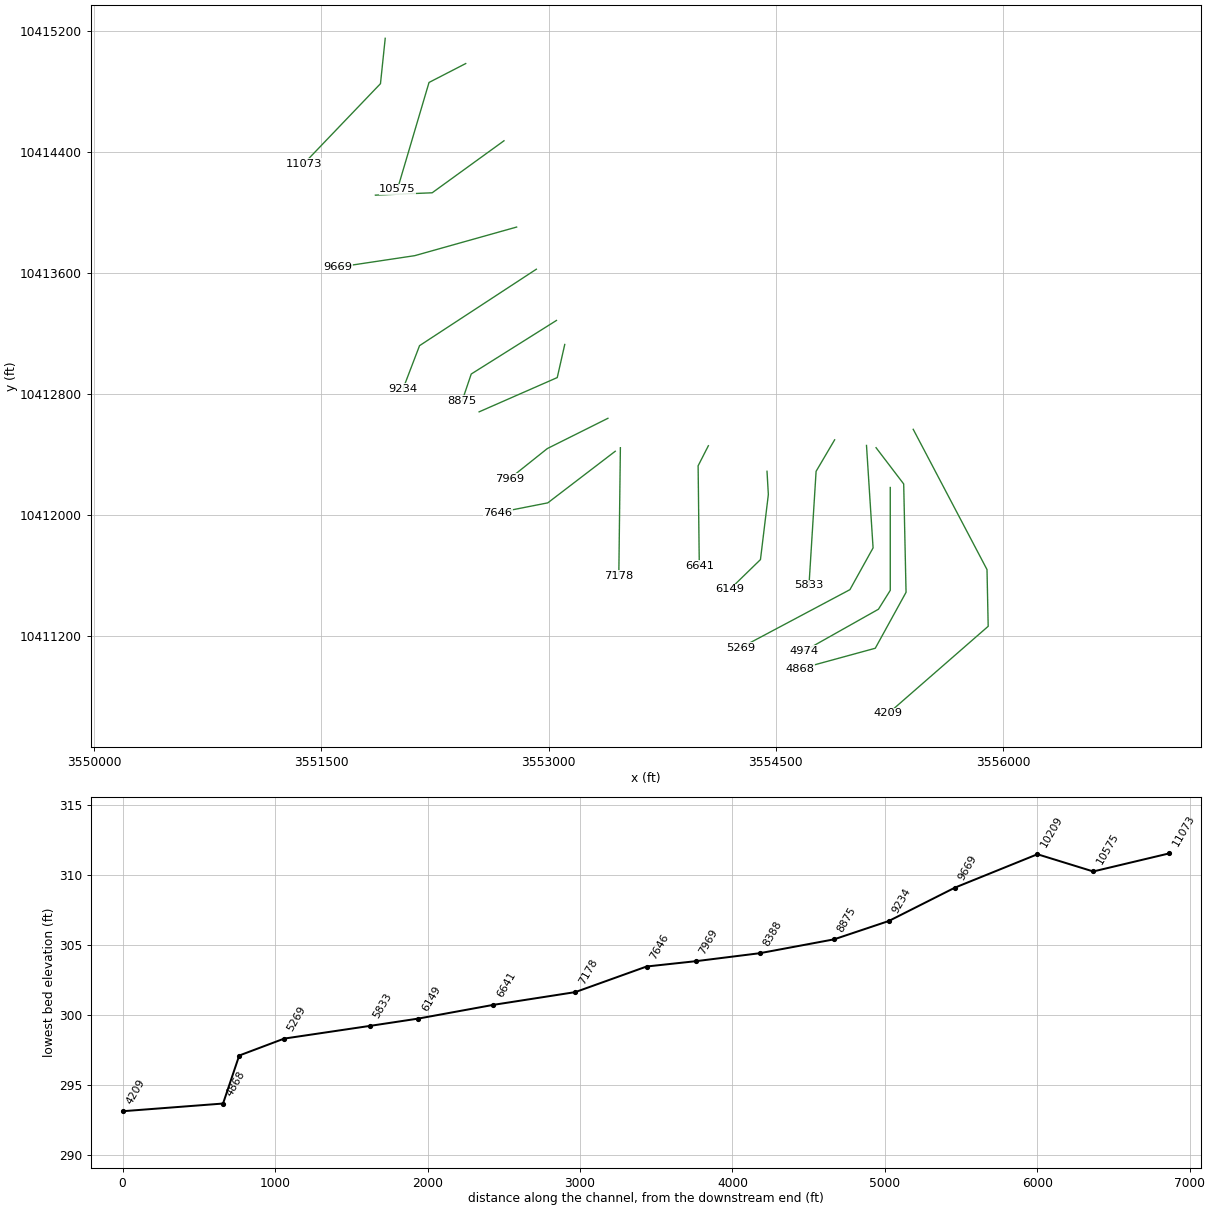
HEC-RAS study RED OAK CREEK.prj: RED OAK CREEK Base Level Engineering

--- RED OAK CREEK.g01 (geometry) --- (continued)

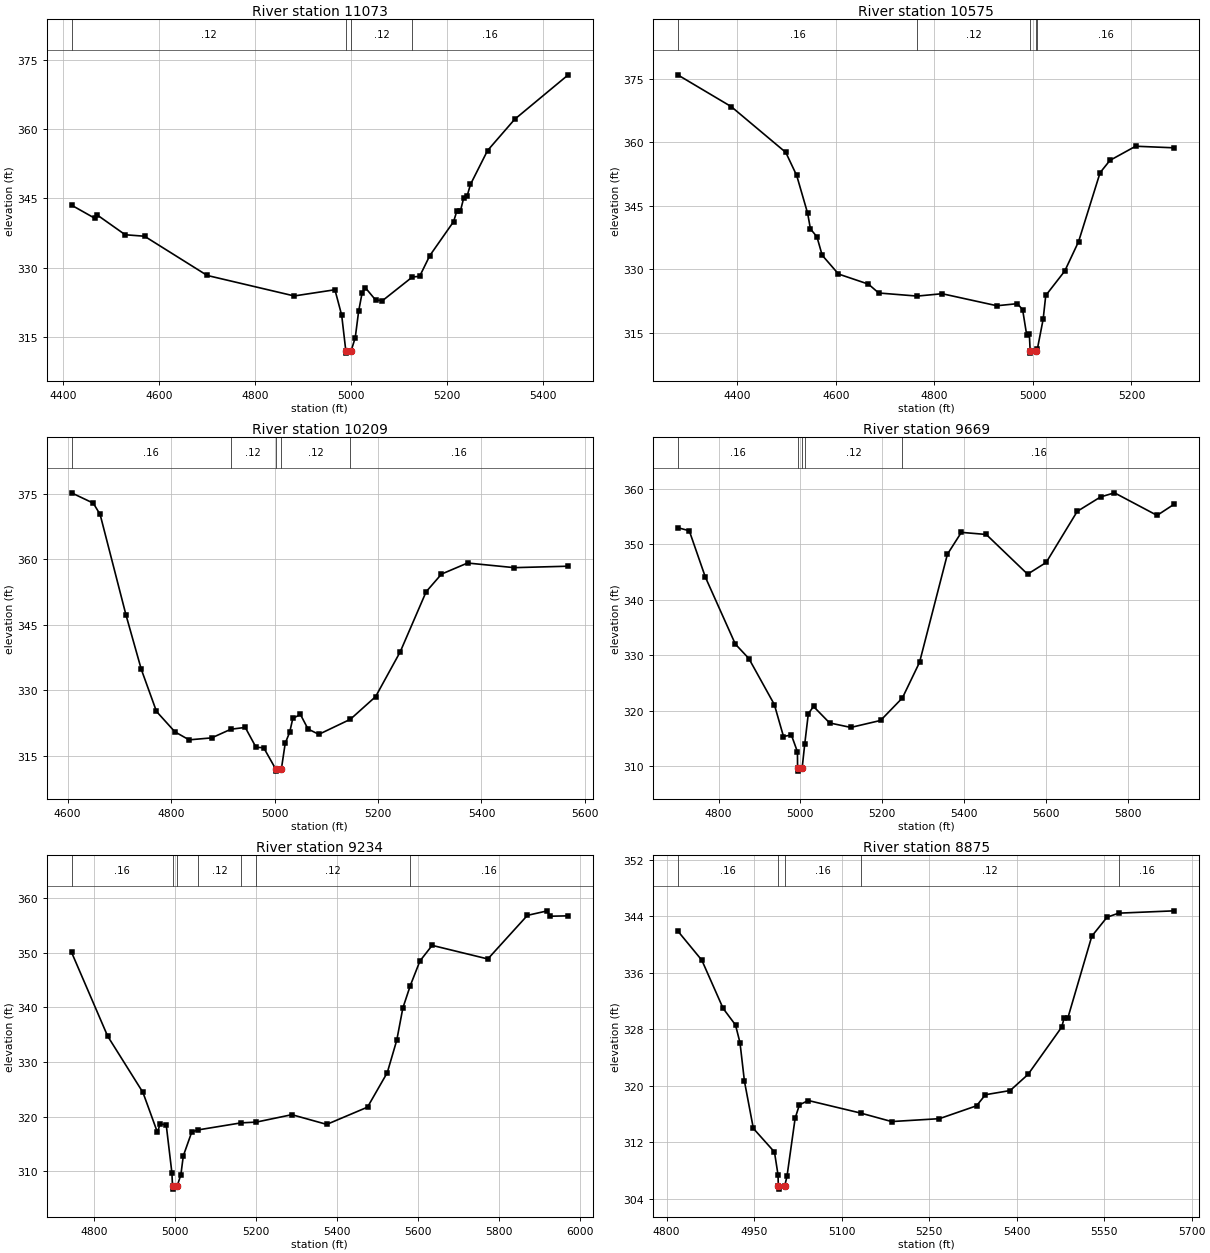
Type RM Length L Ch R = 1 ,11073   ,498,498,498
BEGIN DESCRIPTION:
RED OAK CREEK 18 0
END DESCRIPTION:
XS GIS Cut Line= 3
      3551922.29     10415153.09      3551891.04     10414853.59
      3551383.26     10414322.37
#Sta/Elev= 30
  4416.9  343.52  4465.2   340.7  4470.3  341.41  4528.9  337.12  4569.2   336.8
  4699.9  328.32  4881.4  323.89  4966.3  325.23  4980.4  319.72    4989  312.03
  4989.5  311.53  5000.1  312.03  5008.7  314.89  5015.7  320.55  5022.9  324.51
  5029.8  325.66  5051.2  323.01  5065.3  322.86  5127.8  327.99    5143  328.13
  5164.1   332.6  5213.8  339.96  5220.7   342.3  5227.9  342.22  5234.9  345.08
  5242.1  345.54    5249     348  5284.6  355.32  5341.2  362.08  5452.9  371.69
#Mann= 4 ,-1 , 0
  4416.9     .12       0    4989     .07       0  5000.1     .12       0
  5127.8     .16       0
Bank Sta=4989,5000.1
XS Rating Curve= 0 ,0
Exp/Cntr=0.3,0.1

Type RM Length L Ch R = 1 ,10575   ,366,366,366
BEGIN DESCRIPTION:
RED OAK CREEK 17 0
END DESCRIPTION:
XS GIS Cut Line= 3
      3552453.51     10414986.39      3552211.36      10414861.4
      3552003.18      10414156.2
#Sta/Elev= 30
  4279.4  375.96  4387.9  368.46  4498.7  357.64  4520.8   352.2    4543  343.28
  4548.7  339.58  4561.9  337.71  4572.5  333.36  4605.6  328.92  4666.4  326.53
  4687.2  324.44  4765.4  323.71  4815.9  324.27    4927  321.43  4968.7  321.92
  4979.2  320.49  4987.6  314.42  4992.8   314.8  4994.5  310.74    4995  310.24
  5005.6  310.74  5009.3  311.32  5020.9  318.27  5026.1  323.85  5064.6  329.61
  5092.7  336.57  5136.4  352.86  5156.4  355.76  5208.5   359.1  5287.2  358.72
#Mann= 5 ,-1 , 0
  4279.4     .16       0  4765.4     .12       0  4994.5     .07       0
  5005.6     .12       0  5009.3     .16       0
Bank Sta=4994.5,5005.6
XS Rating Curve= 0 ,0
Exp/Cntr=0.3,0.1

Type RM Length L Ch R = 1 ,10209   ,540,540,540
BEGIN DESCRIPTION:
RED OAK CREEK 16 0
END DESCRIPTION:
XS GIS Cut Line= 3
      3552706.14     10414475.98      3552232.19     10414132.23
       3551857.6     10414116.63
#Sta/Elev= 30
  4607.4  375.26  4649.4   372.9  4662.7  370.31  4712.9  347.19  4742.3  334.81
  4771.7  325.15  4807.3  320.48  4834.7  318.64  4878.4  319.09  4915.5  321.07
  4943.3  321.49  4964.2  316.92  4978.9  316.85  5002.1  311.97  5002.6  311.47
  5013.2  311.97  5020.6  317.87  5029.2  320.37  5035.3  323.56    5050  324.45
  5064.7  321.12  5085.6   319.9  5146.5  323.35  5195.4  328.55    5243  338.83
  5293.1  352.59  5322.7  356.63  5373.1  359.17  5463.2  358.11  5567.8  358.44
#Mann= 5 ,-1 , 0
  4607.4     .16       0  4915.5     .12       0  5002.1     .07       0
  5013.2     .12       0  5146.5     .16       0
Bank Sta=5002.1,5013.2
XS Rating Curve= 0 ,0
Exp/Cntr=0.3,0.1

Type RM Length L Ch R = 1 ,9669    ,435,435,435
BEGIN DESCRIPTION:
RED OAK CREEK 15 0
END DESCRIPTION:
XS GIS Cut Line= 3
      3552789.52     10413905.68      3552117.11     10413716.64
      3551607.21     10413640.05
#Sta/Elev= 30
  4700.1     353  4728.4  352.44  4767.7  344.08    4841     332    4874   329.4
  4936.3   321.1  4958.7  315.33  4977.9  315.62  4992.8  312.57  4993.1  309.59
  4993.6  309.09  5004.2  309.59  5010.6  313.97  5019.4  319.46  5032.1  320.75
  5071.4  317.78  5123.3  316.97    5196  318.23  5249.3  322.29  5291.2  328.71
  5359.3   348.2  5393.4  352.15  5454.2  351.77  5555.3  344.61  5600.7  346.72
  5676.7  355.94  5733.7  358.54  5767.7  359.28  5871.8  355.21  5914.2  357.26
#Mann= 5 ,-1 , 0
  4700.1     .16       0  4993.1     .07       0  5004.2     .16       0
  5010.6     .12       0  5249.3     .16       0
Bank Sta=4993.1,5004.2
XS Rating Curve= 0 ,0
Exp/Cntr=0.3,0.1

Type RM Length L Ch R = 1 ,9234    ,359,359,359
BEGIN DESCRIPTION:
RED OAK CREEK 14 0
END DESCRIPTION:
XS GIS Cut Line= 3
      3552919.73     10413627.05      3552148.86     10413121.82
      3552039.74     10412836.03
#Sta/Elev= 30
  4743.6  350.11    4833  334.72  4920.1  324.42    4956   317.1  4962.6  318.66
  4977.7  318.45  4991.8  309.63  4993.2   307.2  4993.7   306.7  5004.4   307.2
  5013.9  309.34  5019.9  312.79  5040.9  317.19  5057.2  317.56  5162.6  318.84
  5200.2  318.98  5288.2  320.34  5374.4  318.56  5475.1  321.72  5523.9  328.03
  5547.4  333.98  5562.5  339.89  5580.9     344  5604.7   348.5  5634.9  351.36
  5772.5  348.87  5870.3  356.86  5919.8  357.69  5925.1   356.7  5971.2  356.77
#Mann= 7 ,-1 , 0
  4743.6     .16       0  4993.2     .07       0  5004.4     .16       0
  5057.2     .12       0  5162.6     .16       0  5200.2     .12       0
  5580.9     .16       0
Bank Sta=4993.2,5004.4
XS Rating Curve= 0 ,0
Exp/Cntr=0.3,0.1

Type RM Length L Ch R = 1 ,8875    ,487,487,487
BEGIN DESCRIPTION:
RED OAK CREEK 13 0
END DESCRIPTION:
XS GIS Cut Line= 3
      3553052.49     10413288.48        3552490.     10412934.32
      3552430.12     10412757.27
#Sta/Elev= 30
  4818.9  341.93  4860.3  337.78  4896.8  330.96    4918  328.62  4925.7  326.11
  4933.3  320.67  4948.6  313.98  4984.8  310.64    4991  307.36  4991.3  305.89
  4991.8  305.39  5002.5  305.89  5006.3  307.21  5020.2   315.4  5027.5  317.31
  5042.8  317.93  5132.7  316.15  5185.7  314.95  5267.6  315.36  5331.2  317.18
  5346.5  318.75  5388.9  319.34  5419.5  321.62  5477.2  328.31  5481.4  329.59
  5487.7  329.59  5528.9  341.19    5555  343.87    5575  344.44  5670.5  344.77
#Mann= 5 ,-1 , 0
  4818.9     .16       0  4991.3     .07       0  5002.5     .16       0
  5132.7     .12       0    5575     .16       0
Bank Sta=4991.3,5002.5
XS Rating Curve= 0 ,0
Exp/Cntr=0.3,0.1

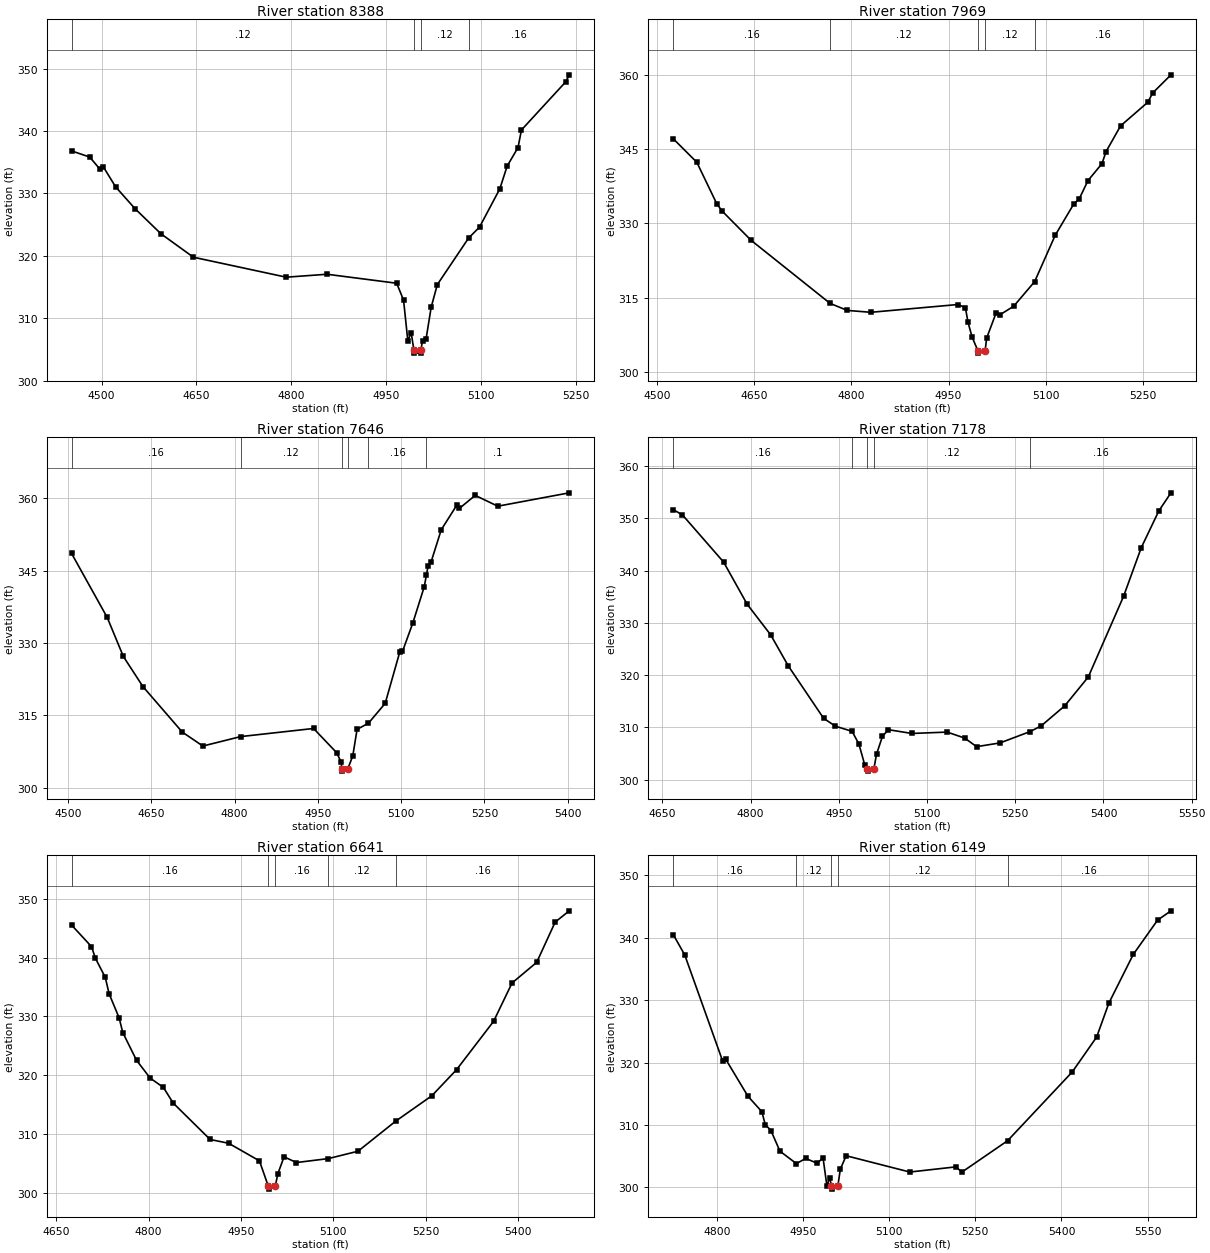
Type RM Length L Ch R = 1 ,8388    ,419,419,419
BEGIN DESCRIPTION:
RED OAK CREEK 12 0
END DESCRIPTION:
XS GIS Cut Line= 3
       3553107.2     10413129.66      3553057.71     10412910.88
       3552542.1     10412684.32
#Sta/Elev= 30
  4452.5  336.81  4481.2  335.82  4497.4  333.88  4502.5   334.3  4522.2  331.05
    4553  327.54    4594  323.52  4645.3  319.77  4792.2  316.57  4856.8  317.04
  4966.9   315.6  4977.8   312.9  4984.5  306.41  4989.9  307.65  4994.1   304.9
  4994.6   304.4  5004.8   304.4  5005.3   304.9  5007.8  306.42  5013.3   306.6
  5021.5  311.76  5031.2  315.38  5080.7  322.84    5098   324.6  5130.1  330.73
  5141.7  334.37  5158.9  337.35  5164.3  340.16  5234.4  347.88    5240     349
#Mann= 4 ,-1 , 0
  4452.5     .12       0  4994.1     .07       0  5005.3     .12       0
  5080.7     .16       0
Bank Sta=4994.1,5005.3
XS Rating Curve= 0 ,0
Exp/Cntr=0.3,0.1

Type RM Length L Ch R = 1 ,7969    ,323,323,323
BEGIN DESCRIPTION:
RED OAK CREEK 11 0
END DESCRIPTION:
XS GIS Cut Line= 3
      3553392.08     10412641.63      3552992.11     10412441.64
      3552742.14     10412241.67
#Sta/Elev= 30
  4525.5   347.1  4561.8  342.36  4592.6  333.98  4600.9   332.5  4645.7  326.58
  4767.3  313.87  4793.8  312.45  4830.1  312.07  4964.3  313.64  4975.9  313.02
  4979.9  310.06  4986.3  307.05  4995.1  304.33  4995.6  303.83  5006.3  304.33
  5008.7  306.87  5023.1  311.91  5029.5   311.6  5050.3  313.29  5082.6  318.25
  5114.4  327.63  5143.2  333.98  5151.2  334.92  5164.8  338.64  5186.4  342.07
  5192.8  344.52  5215.2  349.71  5256.8  354.43  5264.8  356.36  5292.8     360
#Mann= 5 ,-1 , 0
  4525.5     .16       0  4767.3     .12       0  4995.1     .07       0
  5006.3     .12       0  5082.6     .16       0
Bank Sta=4995.1,5006.3
XS Rating Curve= 0 ,0
Exp/Cntr=0.3,0.1

Type RM Length L Ch R = 1 ,7646    ,468,468,468
BEGIN DESCRIPTION:
RED OAK CREEK 10 0
END DESCRIPTION:
XS GIS Cut Line= 3
      3553440.49     10412423.87      3552995.21     10412082.76
      3552665.75      10412017.9
#Sta/Elev= 30
  4506.1  348.57  4570.3  335.31  4599.4  327.22  4634.7  320.97  4705.6  311.54
  4742.7  308.65  4810.9  310.61  4942.1  312.29  4983.7  307.27    4992  305.27
  4992.7  303.95  4993.2  303.45  5003.9  303.95  5012.8  306.63  5020.5  312.11
    5041  313.38  5071.2  317.51  5097.2  328.06  5102.3  328.25  5121.1  334.21
  5141.5  341.66  5145.4  344.09  5148.5  346.02  5153.6  346.72  5172.1  353.47
  5199.9  358.53    5205  357.92  5233.3   360.6    5274  358.36  5402.8  361.13
#Mann= 6 ,-1 , 0
  4506.1     .16       0  4810.9     .12       0  4992.7     .07       0
  5003.9     .12       0    5041     .16       0  5145.4      .1       0
Bank Sta=4992.7,5003.9
XS Rating Curve= 0 ,0
Exp/Cntr=0.3,0.1

Type RM Length L Ch R = 1 ,7178    ,537,537,537
BEGIN DESCRIPTION:
RED OAK CREEK 9 0
END DESCRIPTION:
XS GIS Cut Line= 2
      3553474.38     10412447.37      3553463.96     10411601.03
#Sta/Elev= 30
  4668.4  351.66  4684.1  350.65  4754.1  341.62  4794.1  333.56  4834.1   327.7
  4864.1  321.75  4924.1  311.73  4944.1  310.22  4972.5  309.24  4984.1  306.81
  4994.1  302.81  4998.5  302.12    4999  301.62  5009.7  302.12  5014.1  304.86
  5024.2  308.28  5034.2  309.55  5074.2  308.83  5134.2  309.09  5164.2  307.94
  5184.2   306.3  5224.2  307.02  5275.5   309.2  5294.2  310.29  5334.2  314.12
  5374.2  319.64  5434.2  335.07  5464.2  344.36  5494.2  351.43  5514.8  354.88
#Mann= 5 ,-1 , 0
  4668.4     .16       0  4972.5     .12       0  4998.5     .07       0
  5009.7     .12       0  5275.5     .16       0
Bank Sta=4998.5,5009.7
XS Rating Curve= 0 ,0
Exp/Cntr=0.3,0.1

Type RM Length L Ch R = 1 ,6641    ,492,492,492
BEGIN DESCRIPTION:
RED OAK CREEK 8 0
END DESCRIPTION:
XS GIS Cut Line= 3
      3554055.12     10412460.39       3553987.4     10412327.55
      3553995.21      10411668.7
#Sta/Elev= 30
    4675  345.51  4707.3  341.86  4713.8  339.86  4729.7  336.64    4736  333.84
  4752.2  329.77  4758.2  327.26  4780.5  322.56  4802.7  319.54  4824.1  317.96
    4840  315.31    4900  309.13    4930  308.49    4980  305.51  4994.4  301.21
  4994.9  300.71  5005.7  301.21    5010  303.35    5020  306.19    5040  305.22
  5091.9  305.89    5140  307.14  5201.2  312.24    5260  316.56    5300  320.97
  5360.1  329.17  5390.1  335.68  5430.1  339.18  5460.1  346.01    5483  347.92
#Mann= 5 ,-1 , 0
    4675     .16       0  4994.4     .07       0  5005.7     .16       0
  5091.9     .12       0  5201.2     .16       0
Bank Sta=4994.4,5005.7
XS Rating Curve= 0 ,0
Exp/Cntr=0.3,0.1

Type RM Length L Ch R = 1 ,6149    ,316,316,316
BEGIN DESCRIPTION:
RED OAK CREEK 7 0
END DESCRIPTION:
XS GIS Cut Line= 4
      3554442.11     10412291.61      3554450.94     10412137.44
      3554398.86     10411707.76      3554198.31     10411512.42
#Sta/Elev= 30
  4723.6  340.53  4743.6  337.27  4809.9   320.2  4814.9  320.57  4853.8  314.61
    4878  312.14  4883.9  310.08  4893.9  309.11  4909.5  305.81  4938.2  303.82
  4954.4  304.65  4974.5  303.87  4984.6  304.75  4991.3  300.27  4996.3  301.58
  4999.1  300.23  4999.6  299.73  5010.4  300.23  5014.8  302.95  5024.9  305.08
  5135.7  302.47  5216.3   303.3  5226.4  302.45  5306.2  307.49  5418.9  318.52
  5461.3   324.1  5482.6  329.54  5525.1  337.34  5567.5  342.84  5590.8  344.33
#Mann= 5 ,-1 , 0
  4723.6     .16       0  4938.2     .12       0  4999.1     .07       0
  5010.4     .12       0  5306.2     .16       0
Bank Sta=4999.1,5010.4
XS Rating Curve= 0 ,0
Exp/Cntr=0.3,0.1

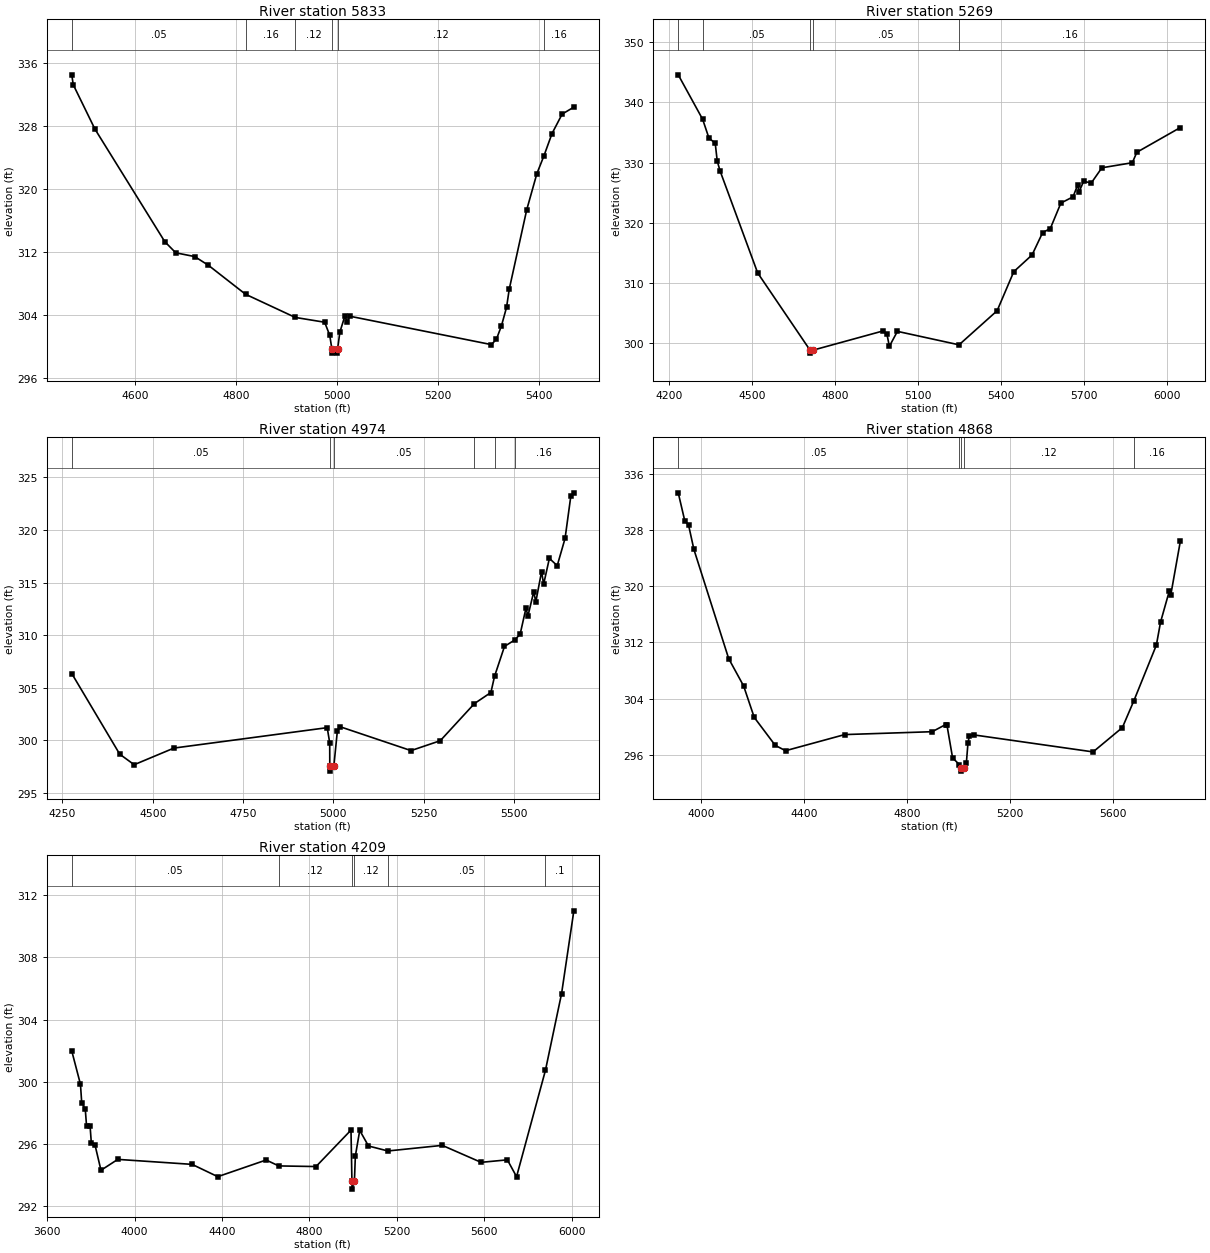
Type RM Length L Ch R = 1 ,5833    ,564,564,564
BEGIN DESCRIPTION:
RED OAK CREEK 41 0
END DESCRIPTION:
XS GIS Cut Line= 3
      3554888.42     10412499.39      3554766.04     10412291.09
      3554719.16     10411538.44
#Sta/Elev= 30
  4473.9  334.52  4476.8  333.27  4519.7  327.65  4658.4  313.35  4680.1  311.94
  4717.7  311.46    4745  310.35  4818.5  306.68  4917.1  303.74  4975.4  303.13
  4985.5  301.47  4989.8  299.71  4990.3  299.21  5000.6  299.21  5001.1  299.71
  5005.5  301.86  5015.3  303.87  5020.3   303.2  5025.5  303.89  5306.1  300.29
  5316.1  300.98  5326.1  302.69  5336.1  305.01  5341.5  307.33  5376.2  317.41
  5396.3  321.99  5410.1  324.21  5426.3  327.07  5446.4  329.54  5469.6  330.42
#Mann= 6 ,-1 , 0
  4473.9     .05       0  4818.5     .16       0  4917.1     .12       0
  4989.8     .07       0  5001.1     .12       0  5410.1     .16       0
Bank Sta=4989.8,5001.1
XS Rating Curve= 0 ,0
Exp/Cntr=0.3,0.1

Type RM Length L Ch R = 1 ,5269    ,295,295,295
BEGIN DESCRIPTION:
RED OAK CREEK 3 1
END DESCRIPTION:
XS GIS Cut Line= 4
       3555098.7      10412462.2      3555142.11     10411785.11
      3554989.32     10411509.07       3554266.2      10411124.1
#Sta/Elev= 30
  4234.4  344.59  4322.6  337.19  4345.2  334.08    4368   333.2  4375.2  330.26
  4385.3  328.63  4521.3  311.64  4710.3   298.8  4710.8   298.3  4721.6   298.8
    4974  301.99  4988.1  301.45  4996.9  299.43  5025.9  301.92  5248.5  299.68
    5386  305.35  5446.2  311.85  5512.2  314.63  5550.4  318.35  5578.1  319.02
  5616.3  323.26  5660.3   324.3  5676.6  326.25  5682.2  325.17  5698.5  326.87
  5726.2  326.61  5764.4  329.13  5874.3  329.97  5890.6  331.71  6047.6  335.82
#Mann= 5 ,-1 , 0
  4234.4     .16       0  4322.6     .05       0  4710.3     .03       0
  4721.6     .05       0  5248.5     .16       0
Bank Sta=4710.3,4721.6
XS Rating Curve= 0 ,0
Exp/Cntr=0.3,0.1

Type RM Length L Ch R = 1 ,4974    ,106,106,106
BEGIN DESCRIPTION:
RED OAK CREEK 31 0
END DESCRIPTION:
XS GIS Cut Line= 4
      3555255.63     10412184.35      3555255.63     10411504.63
       3555177.5     10411379.63      3554687.89     10411103.57
#Sta/Elev= 30
  4276.1  306.36  4408.8   298.7  4448.8   297.7  4558.8  299.28  4982.9  301.22
  4989.8  299.78    4990  297.59  4990.5  297.09  5001.3  297.59    5011  300.92
  5018.3  301.31  5214.8  299.04  5295.7  299.98  5390.3  303.51  5435.8  304.56
  5445.8  306.09  5473.4  308.94  5501.3  309.54  5516.7   310.1  5532.7  312.55
  5538.4  311.85  5554.3  314.13  5560.1  313.17    5576  316.05  5581.7  314.85
  5597.6   317.3  5619.3  316.61    5641   319.2  5656.9  323.21  5665.3  323.53
#Mann= 6 ,-1 , 0
  4276.1     .05       0    4990     .04       0  5001.3     .05       0
  5390.3     .16       0  5445.8     .05       0  5501.3     .16       0
Bank Sta=4990,5001.3
XS Rating Curve= 0 ,0
Exp/Cntr=0.3,0.1

Type RM Length L Ch R = 1 ,4868    ,659,659,659
BEGIN DESCRIPTION:
RED OAK CREEK 2 1
END DESCRIPTION:
XS GIS Cut Line= 5
      3555161.89     10412447.32      3555344.17     10412207.76
      3555359.79     10411491.61      3555156.67     10411121.82
       3554662.3     10410986.52
#Sta/Elev= 30
  3910.9  333.33  3936.5  329.31    3951  328.74  3971.8  325.26    4107   309.7
  4165.1   305.8  4206.3  301.32  4288.1  297.33  4328.1  296.57  4558.1  298.87
  4898.2  299.28    4950  300.29  4955.7  300.18  4977.5  295.54    5004  294.59
  5009.7  294.16  5010.2  293.66    5021  294.16  5030.9  294.77  5037.1  297.63
  5042.8  298.72  5058.9  298.83  5523.6   296.4  5637.5  299.87  5681.9  303.67
  5769.6  311.62  5785.8  314.89  5820.3  319.38  5825.5  318.75  5862.7  326.41
#Mann= 5 ,-1 , 0
  3910.9     .05       0    5004     .12       0  5009.7     .03       0
    5021     .12       0  5681.9     .16       0
Bank Sta=5009.7,5021
XS Rating Curve= 0 ,0
Exp/Cntr=0.3,0.1

Type RM Length L Ch R = 1 ,4209    ,0,0,0
BEGIN DESCRIPTION:
RED OAK CREEK 1 0
END DESCRIPTION:
XS GIS Cut Line= 4
      3555407.06     10412568.94      3555894.04     10411641.87
      3555901.85     10411266.87      3555242.99     10410691.34
#Sta/Elev= 30
  3712.7  301.98  3752.5  299.84  3758.1  298.67  3774.5  298.24  3780.2  297.19
  3796.6  297.14  3802.2  296.07  3818.6  295.97  3846.3  294.32  3923.2  295.02
  4263.1   294.7  4380.6  293.91    4602  294.98  4659.7   294.6  4830.1  294.56
  4990.2   296.9  4994.5  293.61    4995  293.11  5005.8  293.61  5010.2  295.24
  5030.2  296.88  5070.2  295.88  5159.1  295.56  5407.9  295.92  5585.4  294.83
  5705.6  294.99  5747.7  293.91  5879.7  300.73  5953.7  305.67  6009.8  310.98
#Mann= 6 ,-1 , 0
  3712.7     .05       0  4659.7     .12       0  4994.5     .07       0
  5005.8     .12       0  5159.1     .05       0  5879.7      .1       0
Bank Sta=4994.5,5005.8
XS Rating Curve= 0 ,0
Exp/Cntr=0.3,0.1

Chan Stop Cuts=-1
Use User Specified Reach Order=0
Composite Channel Slope=5