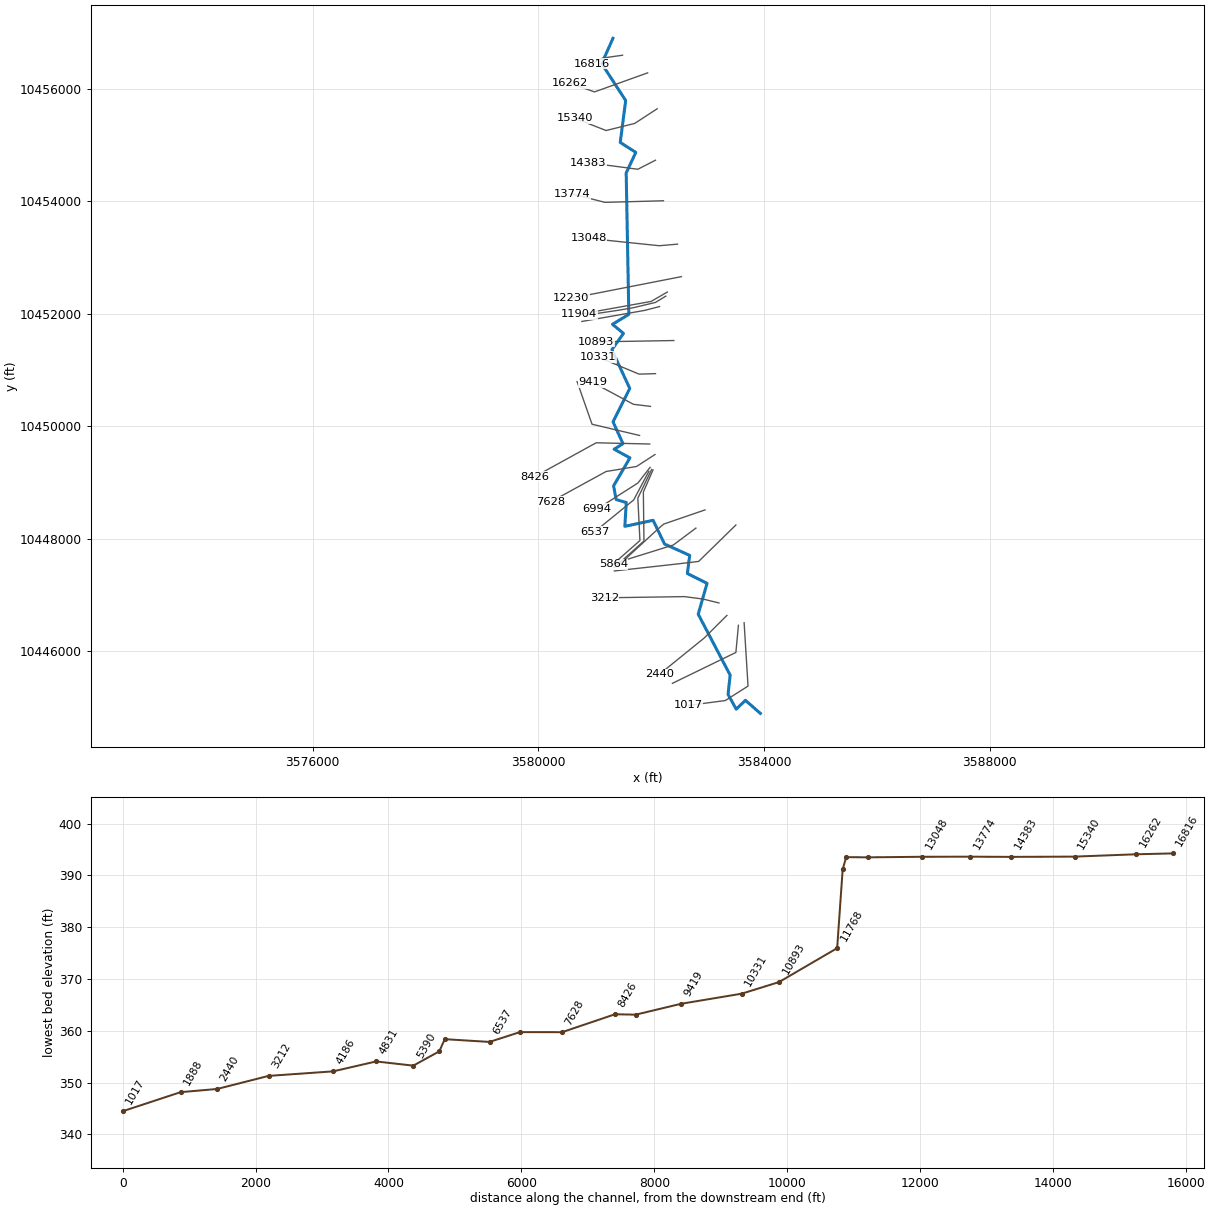
--- SHAW BRANCH.prj (project) ---

Proj Title=SHAW BRANCH Base Level Engineering
Current Plan=p01
Default Exp/Contr=0.3,0.1
English Units
Geom File=g01
Flow File=f01
Plan File=p01
Y Axis Title=Elevation
X Axis Title(PF)=Main Channel Distance
X Axis Title(XS)=Station
BEGIN DESCRIPTION:
SHAW BRANCH
END DESCRIPTION:
DSS Export Rating Curves= 0
DSS Export Rating Curve Sorted= 0
DSS Export Volume Flow Curves= 0
DXF OffsetX= 0
DXF OffsetY= 0
DXF ScaleX= 1
DXF ScaleY= 10

--- SHAW BRANCH.p01 (plan) ---

Plan Title=Multiple Run
Short Identifier=Multiple
Geom File=g01
Flow File=f01
Subcritical Flow
K Sum by GR= 0
Std Step Tol= 0.01
Critical Tol= 0.01
Num of Std Step Trials= 20
Max Error Tol= 0.3
Flow Tol Ratio= 0.001
Split Flow NTrial= 30
Split Flow Tol= 0.02
Split Flow Ratio= 0.02
Log Output Level= 0
Friction Slope Method= 1
Unsteady Friction Slope Method= 2
Unsteady Bridges Friction Slope Method= 1
Parabolic Critical Depth
Global Vel Dist=  1 , 1 , 1
Global Log Level= 0
CheckData=True
Encroach Param= -1, 0, 0, 0
BEGIN DESCRIPTION:
Multiple Run
END DESCRIPTION:

--- SHAW BRANCH.f01 (steady flow) ---

Flow Title=Multiple
Program Version=4.10
Number of Profiles= 7
Profile Names=10-year,25-year,50-year,1pct_min,100-year,1pct_plu,500-year
River Rch & RM=SHAW BRANCH,Reach-1         ,16816
    1425    1988    2458    2213    2993    4047    4428
River Rch & RM=SHAW BRANCH,Reach-1         ,11768
    1633    2299    2861    2592    3506    4741    5253
River Rch & RM=SHAW BRANCH,Reach-1         ,8426
    2269    3235    4058    3702    5007    6771    7608
River Rch & RM=SHAW BRANCH,Reach-1         ,6994
    2269    3235    4058    3702    5007    6771    7608
Boundary for River Rch & Prof#=SHAW BRANCH,Reach-1         , 1
Up Type= 0
Dn Type= 3
Dn Slope=0.005
Boundary for River Rch & Prof#=SHAW BRANCH,Reach-1         , 2
Up Type= 0
Dn Type= 3
Dn Slope=0.005
Boundary for River Rch & Prof#=SHAW BRANCH,Reach-1         , 3
Up Type= 0
Dn Type= 3
Dn Slope=0.005
Boundary for River Rch & Prof#=SHAW BRANCH,Reach-1         , 4
Up Type= 0
Dn Type= 3
Dn Slope=0.005
Boundary for River Rch & Prof#=SHAW BRANCH,Reach-1         , 5
Up Type= 0
Dn Type= 3
Dn Slope=0.005
Boundary for River Rch & Prof#=SHAW BRANCH,Reach-1         , 6
Up Type= 0
Dn Type= 3
Dn Slope=0.005
Boundary for River Rch & Prof#=SHAW BRANCH,Reach-1         , 7
Up Type= 0
Dn Type= 3
Dn Slope=0.005
DSS Import GetInterval= 0
DSS Import GetPeak= 0
DSS Import FillOption= 0

--- SHAW BRANCH.g01 (geometry) ---

Geom Title=Existing Conditions

River Reach=SHAW BRANCH,Reach-1
Reach XY= 30
      3581322.11     10456891.64      3581123.00     10456441.53
      3581547.68     10455787.29      3581451.33     10455042.50
      3581727.37     10454865.42      3581556.80     10454500.83
      3581603.59     10451988.16      3581313.65     10451811.94
      3581508.91     10451650.25      3581303.18     10451360.77
      3581620.11     10450672.03      3581323.92     10450078.88
      3581500.26     10449691.30      3581343.16     10449592.51
      3581622.86     10449439.18      3581333.82     10448942.42
      3581378.91     10448698.57      3581557.73     10448646.49
      3581533.08     10448223.05      3582033.86     10448330.34
      3582235.94     10447909.25      3582682.11     10447706.64
      3582640.85     10447385.12      3582989.32     10447210.51
      3582833.10     10446662.47      3583398.89     10445580.52
      3583362.05     10445236.55      3583506.58     10444975.26
      3583669.34     10445132.38      3583933.93     10444900.61

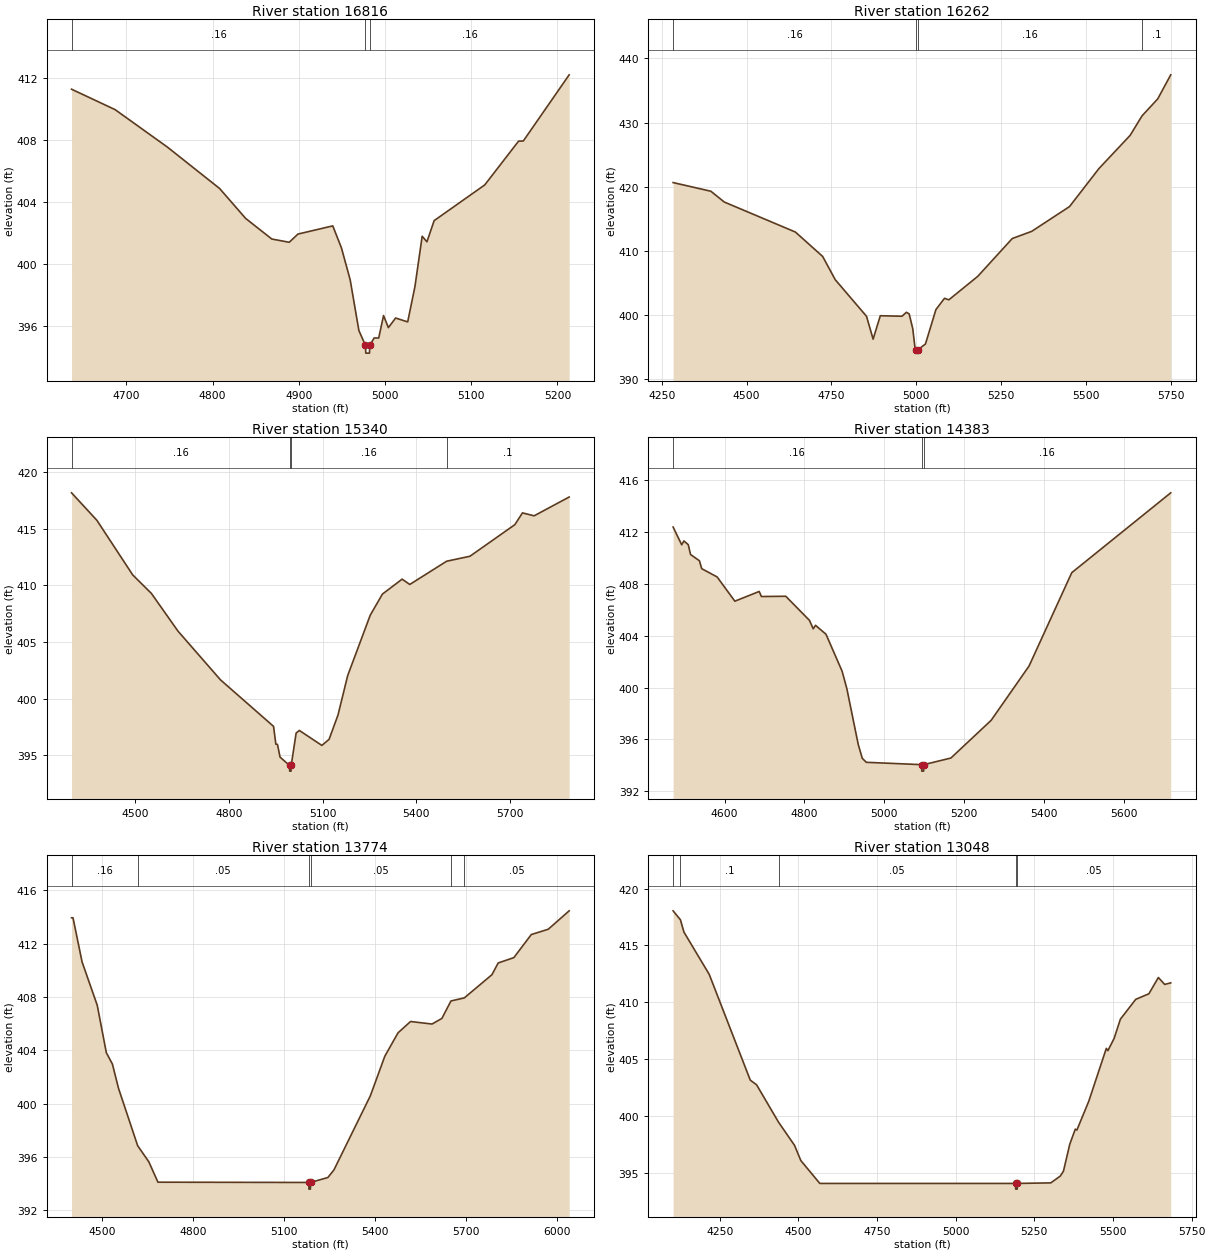
Type RM Length L Ch R = 1,16816,554,554,554
BEGIN DESCRIPTION:
SHAW BRANCH 8 0
END DESCRIPTION:
XS GIS Cut Line= 3
      3581492.10     10456591.64      3581142.11     10456541.64
      3580942.06     10456441.62
#Sta/Elev= 30
  4636.4  411.30  4686.9  409.98  4747.5  407.56  4808.1  404.88  4838.4  402.94
  4868.7  401.61  4888.9  401.40  4899.0  401.93  4939.4  402.46  4949.5  401.03
  4959.6  398.97  4969.7  395.69  4977.3  394.73  4977.7  394.23  4982.0  394.23
  4982.3  394.73  4987.4  395.21  4992.7  395.21  4998.3  396.66  5003.9  395.88
  5012.3  396.50  5026.3  396.25  5034.7  398.53  5043.1  401.79  5048.6  401.43
  5057.0  402.80  5115.7  405.11  5154.9  407.94  5160.4  407.95  5213.6  412.23
#Mann=3,-1,0
  4636.4    0.16       0  4977.3    0.07       0  4982.3    0.16       0
Bank Sta=4977.3,4982.3
Exp/Cntr=0.3,0.1

Type RM Length L Ch R = 1,16262,922,922,922
BEGIN DESCRIPTION:
SHAW BRANCH 7 0
END DESCRIPTION:
XS GIS Cut Line= 3
      3581936.85     10456278.34      3580995.04     10455939.81
      3580556.88     10456098.15
#Sta/Elev= 30
  4283.7  420.65  4395.0  419.30  4434.4  417.62  4644.1  412.94  4724.4  409.14
  4761.7  405.50  4853.8  399.80  4873.2  396.24  4894.4  399.89  4958.2  399.81
  4971.4  400.43  4979.5  400.17  4990.1  397.85  4996.8  394.82  4999.6  394.56
  5000.0  394.06  5004.7  394.56  5027.5  395.49  5058.3  400.85  5083.7  402.61
  5096.4  402.37  5181.4  406.02  5283.4  411.93  5340.8  413.05  5452.1  416.91
  5538.7  422.83  5630.7  428.01  5665.8  431.05  5712.1  433.70  5750.4  437.45
#Mann=4,-1,0
  4283.7    0.16       0  4999.6    0.07       0  5004.7    0.16       0
  5665.8     0.1       0
Bank Sta=4999.6,5004.7
Exp/Cntr=0.3,0.1

Type RM Length L Ch R = 1,15340,957,957,957
BEGIN DESCRIPTION:
SHAW BRANCH 6 0
END DESCRIPTION:
XS GIS Cut Line= 4
      3582106.12     10455640.31      3581706.85     10455379.91
      3581201.20     10455254.04      3580647.79     10455471.07
#Sta/Elev= 30
  4296.7  418.18  4377.9  415.75  4492.5  410.93  4552.2  409.30  4637.3  405.97
  4773.2  401.67  4943.1  397.56  4950.4  395.99  4955.6  395.97  4963.8  394.85
  4994.2  394.11  4994.7  393.61  4999.1  393.61  4999.5  394.11  5015.3  396.97
  5025.6  397.20  5097.7  395.88  5120.8  396.42  5149.3  398.57  5180.2  402.04
  5252.3  407.37  5291.4  409.24  5354.5  410.56  5378.9  410.09  5496.8  412.14
  5571.4  412.58  5715.1  415.37  5739.5  416.41  5776.8  416.15  5888.9  417.81
#Mann=4,-1,0
  4296.7    0.16       0  4994.2    0.07       0  4999.5    0.16       0
  5496.8     0.1       0
Bank Sta=4994.2,4999.5
Exp/Cntr=0.3,0.1

Type RM Length L Ch R = 1,14383,609,609,609
BEGIN DESCRIPTION:
SHAW BRANCH 5 0
END DESCRIPTION:
XS GIS Cut Line= 3
      3582075.77     10454726.70      3581763.27     10454566.11
      3580876.42     10454683.20
#Sta/Elev= 30
  4471.1  412.39  4492.6  411.02  4498.2  411.32  4509.0  411.03  4514.8  410.27
  4537.0  409.79  4542.7  409.18  4581.3  408.54  4625.7  406.67  4686.6  407.42
  4692.2  407.03  4753.2  407.05  4812.5  405.19  4821.9  404.54  4827.6  404.81
  4853.9  404.12  4894.2  401.27  4906.1  399.92  4934.6  395.62  4944.7  394.55
  4954.8  394.24  5093.2  394.06  5093.7  393.56  5098.3  393.56  5098.7  394.06
  5166.6  394.57  5267.4  397.48  5362.3  401.67  5469.2  408.87  5717.0  415.03
#Mann=3,-1,0
  4471.1    0.16       0  5093.2    0.07       0  5098.7    0.16       0
Bank Sta=5093.2,5098.7
Exp/Cntr=0.3,0.1

Type RM Length L Ch R = 1,13774,726,726,726
BEGIN DESCRIPTION:
SHAW BRANCH 4 0
END DESCRIPTION:
XS GIS Cut Line= 3
      3582216.79     10454006.21      3581181.67     10453978.00
      3580595.38     10454127.28
#Sta/Elev= 30
  4399.3  413.95  4404.1  413.95  4434.0  410.64  4484.0  407.39  4514.0  403.83
  4534.0  402.98  4554.0  401.17  4617.2  396.86  4654.1  395.65  4684.1  394.12
  5181.4  394.10  5181.9  393.60  5186.7  393.60  5187.1  394.10  5244.3  394.47
  5264.3  395.04  5384.4  400.60  5432.1  403.57  5475.6  405.32  5516.9  406.17
  5587.7  405.98  5620.1  406.40  5650.1  407.71  5694.1  407.94  5785.2  409.68
  5805.8  410.56  5857.4  410.96  5914.9  412.69  5970.9  413.09  6039.8  414.47
#Mann=6,-1,0
  4399.3    0.16       0  4617.2    0.05       0  5181.4   0.033       0
  5187.1    0.05       0  5650.1    0.16       0  5694.1    0.05       0
Bank Sta=5181.4,5187.1
Exp/Cntr=0.3,0.1

Type RM Length L Ch R = 1,13048,818,818,818
BEGIN DESCRIPTION:
SHAW BRANCH 3 9
END DESCRIPTION:
XS GIS Cut Line= 3
      3582466.36     10453235.81      3582143.04     10453207.60
      3580893.05     10453337.81
#Sta/Elev= 30
  4102.2  418.04  4125.5  417.25  4136.6  416.17  4216.9  412.46  4347.4  403.16
  4367.5  402.75  4437.1  399.47  4488.0  397.43  4508.1  396.09  4568.4  394.08
  5190.3  394.08  5190.8  393.58  5195.7  393.58  5196.1  394.08  5302.4  394.13
  5332.6  394.73  5342.6  395.16  5362.7  397.53  5380.2  398.85  5385.3  398.77
  5423.0  401.30  5478.8  405.95  5483.8  405.75  5503.5  406.82  5523.6  408.52
  5572.3  410.26  5614.1  410.75  5644.2  412.18  5664.3  411.57  5683.5  411.71
#Mann=5,-1,0
  4102.2    0.16       0  4125.5     0.1       0  4437.1    0.05       0
  5190.3   0.033       0  5196.1    0.05       0
Bank Sta=5190.3,5196.1
Exp/Cntr=0.3,0.1

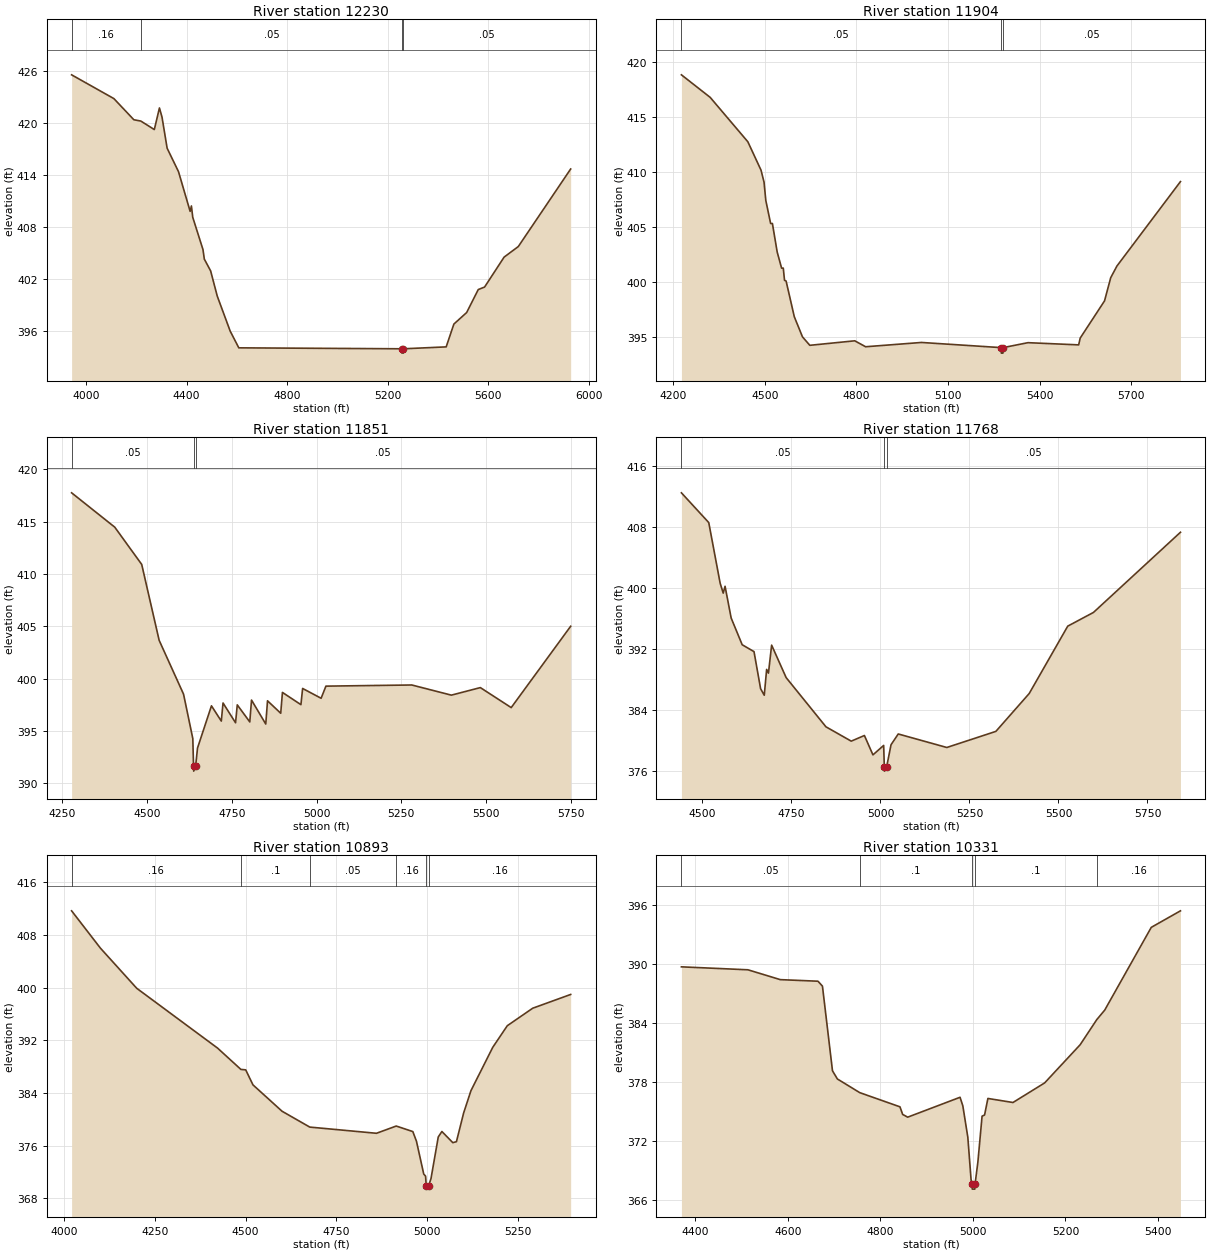
Type RM Length L Ch R = 1,12230,326,326,326
BEGIN DESCRIPTION:
SHAW BRANCH 3 8
END DESCRIPTION:
XS GIS Cut Line= 2
      3582535.19     10452658.45      3580585.88     10452275.88
#Sta/Elev= 30
  3942.4  425.56  4110.6  422.82  4190.1  420.38  4217.8  420.23  4271.6  419.25
  4292.0  421.74  4302.2  420.69  4322.6  417.10  4367.8  414.40  4414.2  409.82
  4419.3  410.44  4424.5  409.14  4465.3  405.41  4470.7  404.31  4495.8  402.95
  4522.1  400.05  4573.6  396.01  4607.9  394.08  5257.1  393.97  5257.6  393.47
  5262.8  393.47  5263.3  393.97  5433.4  394.19  5464.0  396.82  5514.9  398.15
  5561.1  400.80  5586.3  401.09  5664.0  404.54  5720.5  405.76  5928.9  414.70
#Mann=4,-1,0
  3942.4    0.16       0  4217.8    0.05       0  5257.1   0.033       0
  5263.3    0.05       0
Bank Sta=5257.1,5263.3
Exp/Cntr=0.3,0.1

Type RM Length L Ch R = 1,11904,53,53,53
BEGIN DESCRIPTION:
Mapping XS f8f2c8ae
END DESCRIPTION:
XS GIS Cut Line= 3
      3582286.31     10452385.14      3581997.64     10452218.02
      3580717.30     10451987.99
#Sta/Elev= 30
  4227.1  418.82  4321.3  416.77  4444.7  412.73  4487.8  410.15  4497.7  409.06
  4503.5  407.39  4519.3  405.30  4525.1  405.30  4540.8  402.70  4555.2  401.24
  4560.7  401.24  4564.8  400.13  4569.9  400.07  4596.8  396.82  4623.6  394.99
  4647.6  394.22  4794.8  394.63  4830.4  394.09  5013.3  394.48  5274.4  394.01
  5274.9  393.51  5280.1  393.51  5280.6  394.01  5362.0  394.46  5528.1  394.26
  5533.2  394.88  5612.8  398.26  5633.1  400.37  5653.4  401.43  5861.5  409.11
#Mann=3,-1,0
  4227.1    0.05       0  5274.4   0.033       0  5280.6    0.05       0
Bank Sta=5274.4,5280.6
Exp/Cntr=0.3,0.1

Type RM Length L Ch R = 1,11851,83,83,83
BEGIN DESCRIPTION:
SHAW BRANCH 3 7
END DESCRIPTION:
XS GIS Cut Line= 5
      3582258.04     10452311.32      3582075.77     10452200.66
      3581696.00     10452109.51      3581422.56     10452061.77
      3580838.74     10451974.96
#Sta/Elev= 30
  4277.7  417.74  4404.9  414.46  4484.4  410.90  4535.8  403.65  4607.8  398.50
  4635.1  394.26  4637.2  391.65  4637.7  391.15  4643.4  391.65  4649.0  393.36
  4690.1  397.39  4719.1  395.93  4724.2  397.66  4761.1  395.77  4766.2  397.48
  4803.1  395.85  4808.2  397.94  4850.2  395.65  4855.4  397.87  4894.3  396.68
  4899.4  398.67  4953.9  397.50  4958.9  399.05  5013.4  398.11  5027.6  399.27
  5280.8  399.38  5397.5  398.41  5483.0  399.13  5574.0  397.22  5749.3  404.99
#Mann=3,-1,0
  4277.7    0.05       0  4637.2   0.033       0  4643.4    0.05       0
Bank Sta=4637.2,4643.4
Exp/Cntr=0.3,0.1

Type RM Length L Ch R = 1,11768,875,875,875
BEGIN DESCRIPTION:
Mapping XS 45a9c0f1
END DESCRIPTION:
XS GIS Cut Line= 3
      3582147.41     10452126.88      3581886.97     10452059.60
      3580771.51     10451862.12
#Sta/Elev= 30
  4440.8  412.43  4517.6  408.53  4549.6  400.58  4558.2  399.28  4563.4  400.18
  4580.5  396.02  4611.5  392.51  4644.7  391.61  4663.2  386.75  4673.5  385.89
  4680.2  389.28  4685.3  388.79  4694.2  392.46  4735.0  388.20  4846.8  381.75
  4917.8  379.87  4954.8  380.61  4978.8  378.07  5008.9  379.31  5010.8  376.44
  5011.3  375.94  5017.0  376.44  5029.6  379.40  5049.9  380.81  5186.3  379.04
  5324.1  381.15  5417.8  386.12  5526.0  394.95  5598.3  396.75  5842.6  407.26
#Mann=3,-1,0
  4440.8    0.05       0  5010.8   0.035       0  5017.0    0.05       0
Bank Sta=5010.8,5017
Exp/Cntr=0.3,0.1

Type RM Length L Ch R = 1,10893,562,562,562
BEGIN DESCRIPTION:
SHAW BRANCH 3 6
END DESCRIPTION:
XS GIS Cut Line= 2
      3582401.32     10451523.58      3581027.63     10451499.70
#Sta/Elev= 30
  4021.2  411.65  4100.4  405.99  4200.4  399.89  4422.9  390.81  4487.2  387.57
  4500.5  387.50  4520.5  385.22  4600.5  381.22  4676.9  378.81  4860.5  377.87
  4914.9  378.97  4960.6  378.13  4970.6  376.66  4990.6  371.68  4995.7  371.36
  4997.5  369.89  4998.0  369.39  5003.4  369.39  5003.9  369.89  5010.6  370.99
  5030.6  377.31  5040.6  378.14  5070.6  376.45  5080.6  376.59  5100.6  380.98
  5120.6  384.34  5180.6  390.92  5220.6  394.20  5290.6  396.86  5395.1  398.95
#Mann=6,-1,0
  4021.2    0.16       0  4487.2     0.1       0  4676.9    0.05       0
  4914.9    0.16       0  4997.5    0.07       0  5003.9    0.16       0
Bank Sta=4997.5,5003.9
Exp/Cntr=0.3,0.1

Type RM Length L Ch R = 1,10331,912,912,912
BEGIN DESCRIPTION:
SHAW BRANCH 3 5
END DESCRIPTION:
XS GIS Cut Line= 3
      3582075.81     10450935.47      3581784.97     10450926.79
      3581057.97     10451230.61
#Sta/Elev= 30
  4369.7  389.73  4513.5  389.43  4583.5  388.43  4664.9  388.27  4674.6  387.77
  4696.3  379.17  4706.9  378.34  4755.3  376.95  4842.2  375.51  4848.0  374.74
  4858.9  374.46  4972.1  376.48  4978.1  375.61  4988.9  372.42  4995.9  368.12
  4998.1  367.65  4998.6  367.15  5004.0  367.15  5004.5  367.65  5010.6  369.88
  5019.7  374.56  5025.1  374.68  5032.3  376.36  5086.5  375.95  5155.0  377.94
  5231.8  381.82  5267.7  384.37  5284.8  385.33  5385.5  393.74  5448.6  395.42
#Mann=5,-1,0
  4369.7    0.05       0  4755.3     0.1       0  4998.1    0.03       0
  5004.5     0.1       0  5267.7    0.16       0
Bank Sta=4998.1,5004.5
Exp/Cntr=0.3,0.1

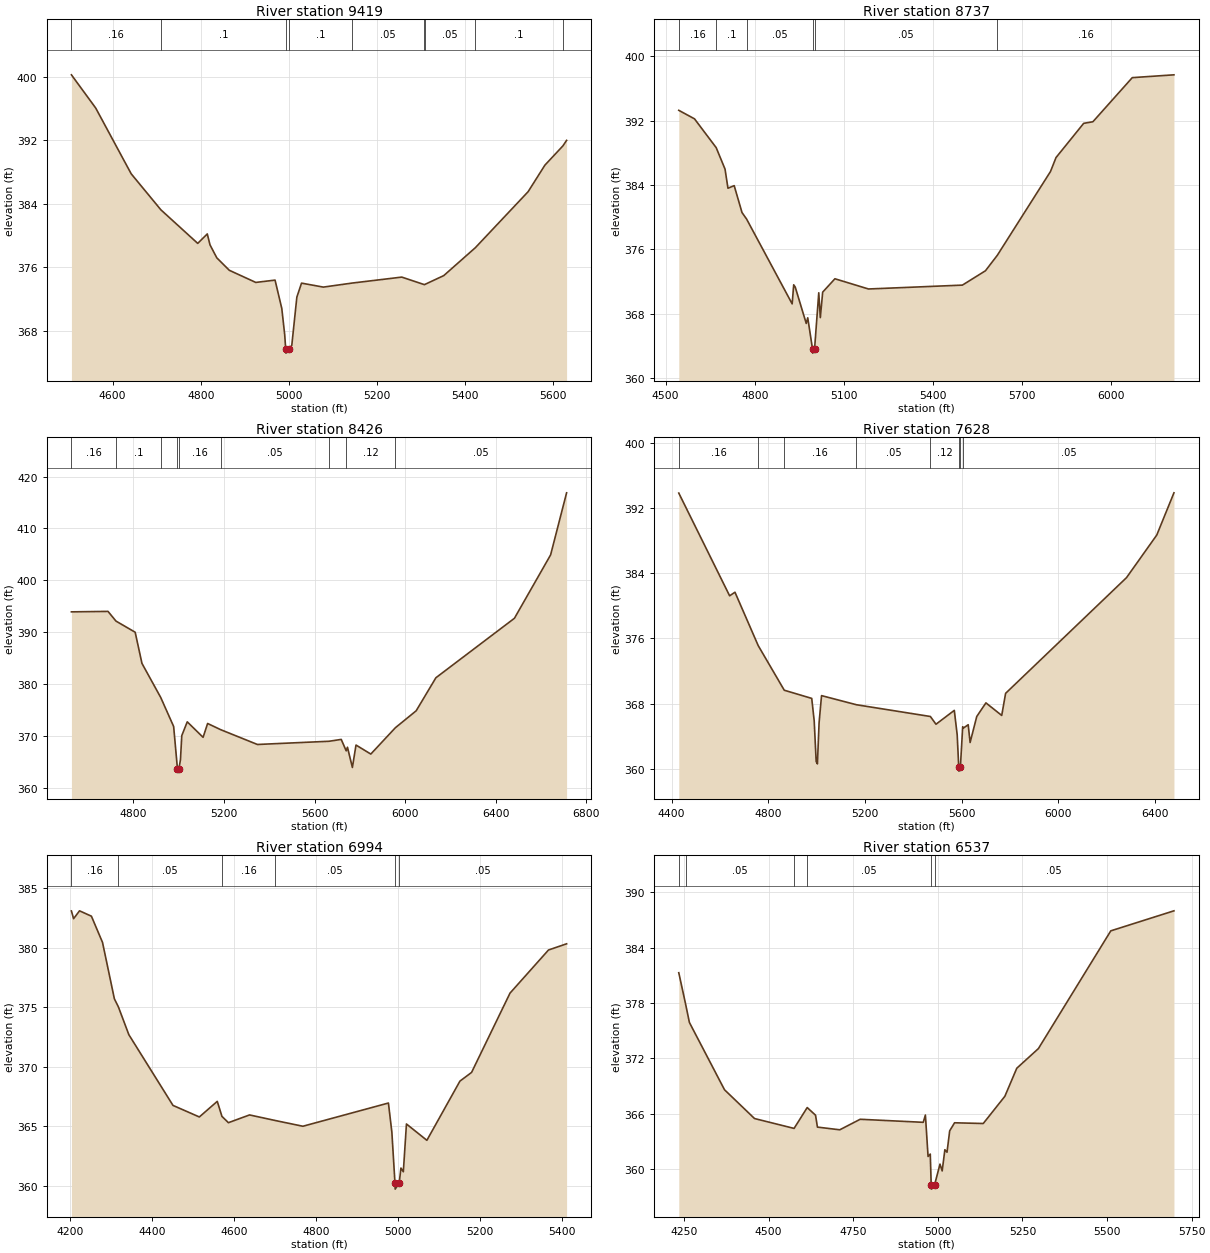
Type RM Length L Ch R = 1,9419,682,682,682
BEGIN DESCRIPTION:
SHAW BRANCH 3 4
END DESCRIPTION:
XS GIS Cut Line= 3
      3581986.81     10450353.87      3581685.14     10450390.76
      3580962.45     10450779.24
#Sta/Elev= 30
  4506.4  400.27  4561.5  396.09  4642.1  387.80  4709.7  383.25  4793.2  379.03
  4814.9  380.22  4821.1  378.84  4836.5  377.21  4864.9  375.64  4925.0  374.11
  4968.8  374.40  4984.1  370.83  4990.7  367.53  4993.0  365.70  4993.5  365.20
  4999.7  365.70  5006.8  366.18  5018.3  372.26  5028.9  374.02  5078.4  373.52
  5144.0  374.03  5256.5  374.78  5307.9  373.83  5308.7  373.85  5351.9  374.97
  5423.7  378.49  5543.4  385.54  5581.6  388.89  5622.5  391.32  5630.8  392.01
#Mann=9,-1,0
  4506.4    0.16       0  4709.7     0.1       0  4993.0    0.07       0
  4999.7     0.1       0  5144.0    0.05       0  5307.9     0.1       0
  5308.7    0.05       0  5423.7     0.1       0  5622.5    0.16       0
Bank Sta=4993,4999.7
Exp/Cntr=0.3,0.1

Type RM Length L Ch R = 1,8737,311,311,311
BEGIN DESCRIPTION:
Mapping XS d1d5ceef
END DESCRIPTION:
XS GIS Cut Line= 3
      3581793.68     10449837.37      3580951.64     10450037.03
      3580686.98     10450794.12
#Sta/Elev= 30
  4544.1  393.27  4597.1  392.21  4670.1  388.63  4699.9  385.96  4709.7  383.59
  4730.7  383.91  4757.0  380.57  4772.6  379.75  4925.9  369.22  4931.1  371.59
  4936.3  371.30  4973.3  366.79  4978.4  367.49  4994.5  363.60  4995.0  363.10
  5001.3  363.60  5015.5  370.60  5020.7  367.51  5028.7  370.68  5069.9  372.34
  5182.9  371.07  5499.1  371.55  5576.7  373.33  5616.8  375.26  5795.7  385.66
  5814.4  387.40  5907.5  391.65  5938.6  391.85  6071.2  397.33  6211.5  397.68
#Mann=6,-1,0
  4544.1    0.16       0  4670.1     0.1       0  4772.6    0.05       0
  4994.5    0.03       0  5001.3    0.05       0  5616.8    0.16       0
Bank Sta=4994.5,5001.3
Exp/Cntr=0.3,0.1

Type RM Length L Ch R = 1,8426,798,798,798
BEGIN DESCRIPTION:
SHAW BRANCH 3 3
END DESCRIPTION:
XS GIS Cut Line= 3
      3581973.74     10449685.47      3581025.42     10449707.17
      3579940.33     10449108.20
#Sta/Elev= 30
  4525.9  393.90  4687.6  393.99  4722.8  392.12  4807.6  389.97  4837.6  383.96
  4920.7  377.37  4977.6  371.79  4994.3  363.68  4994.8  363.18  5001.1  363.68
  5007.7  365.38  5013.5  370.02  5037.7  372.69  5107.7  369.70  5127.7  372.37
  5184.7  371.19  5347.7  368.32  5664.4  368.94  5718.1  369.30  5740.1  367.09
  5745.6  367.79  5767.4  363.89  5783.4  368.21  5848.8  366.47  5957.1  371.54
  6049.3  374.82  6136.4  381.19  6483.4  392.66  6643.3  404.89  6713.9  416.86
#Mann=9,-1,0
  4525.9    0.16       0  4722.8     0.1       0  4920.7    0.16       0
  4994.3    0.07       0  5001.1    0.16       0  5184.7    0.05       0
  5664.4     0.1       0  5740.1    0.12       0  5957.1    0.05       0
Bank Sta=4994.3,5001.1
Exp/Cntr=0.3,0.1

Type RM Length L Ch R = 1,7628,634,634,634
BEGIN DESCRIPTION:
SHAW BRANCH 3 2
END DESCRIPTION:
XS GIS Cut Line= 4
      3582067.13     10449498.86      3581739.40     10449286.16
      3581201.20     10449197.19      3580225.87     10448661.84
#Sta/Elev= 30
  4429.5  393.82  4639.9  381.22  4662.0  381.66  4758.2  375.11  4866.0  369.64
  4979.6  368.64  4989.8  365.89  4998.0  360.90  5003.1  360.61  5010.0  365.64
  5020.2  368.98  5164.6  367.86  5470.5  366.42  5493.7  365.47  5569.5  367.17
  5581.4  364.19  5587.9  360.22  5588.4  359.72  5594.7  360.22  5604.2  365.16
  5606.7  364.99  5627.0  365.41  5634.9  363.23  5662.4  366.42  5700.3  368.09
  5765.7  366.55  5781.8  369.26  6282.1  383.45  6407.2  388.67  6478.3  393.85
#Mann=8,-1,0
  4429.5    0.16       0  4758.2     0.1       0  4866.0    0.16       0
  5164.6    0.05       0  5470.5    0.12       0  5587.9    0.07       0
  5594.7    0.12       0  5606.7    0.05       0
Bank Sta=5587.9,5594.7
Exp/Cntr=0.3,0.1

Type RM Length L Ch R = 1,6994,457,457,457
BEGIN DESCRIPTION:
SHAW BRANCH 3 1
END DESCRIPTION:
XS GIS Cut Line= 3
      3581980.26     10449270.94      3581765.44     10448993.19
      3581042.76     10448530.94
#Sta/Elev= 30
  4203.1  383.09  4208.4  382.44  4222.9  383.10  4251.9  382.65  4279.0  380.45
  4308.0  375.71  4317.7  375.04  4343.3  372.70  4451.1  366.76  4515.4  365.79
  4559.2  367.10  4570.6  365.84  4586.4  365.31  4638.0  365.96  4701.1  365.49
  4768.2  365.01  4977.1  366.96  4985.5  364.51  4993.1  360.23  4993.6  359.73
  5003.4  360.23  5007.6  361.50  5013.5  361.19  5021.1  365.20  5071.0  363.83
  5151.7  368.80  5180.1  369.53  5274.0  376.19  5367.9  379.81  5412.1  380.33
#Mann=6,-1,0
  4203.1    0.16       0  4317.7    0.05       0  4570.6    0.16       0
  4701.1    0.05       0  4993.1    0.03       0  5003.4    0.05       0
Bank Sta=4993.1,5003.4
Exp/Cntr=0.3,0.1

Type RM Length L Ch R = 1,6537,673,673,673
BEGIN DESCRIPTION:
SHAW BRANCH 11 0
END DESCRIPTION:
XS GIS Cut Line= 3
      3581958.59     10449199.37      3581689.49     10448691.54
      3581001.53     10448129.46
#Sta/Elev= 30
  4234.6  381.29  4254.5  377.94  4266.0  375.90  4369.7  368.61  4458.4  365.49
  4575.3  364.42  4614.1  366.68  4638.7  365.85  4644.3  364.56  4710.3  364.27
  4770.6  365.41  4956.9  365.08  4963.3  365.87  4971.2  361.38  4977.7  361.64
  4980.4  358.34  4980.9  357.84  4990.7  358.34  5006.4  360.55  5012.9  359.81
  5020.8  362.11  5027.2  361.84  5035.1  364.16  5049.5  365.03  5134.2  364.95
  5198.1  367.90  5233.3  370.94  5297.2  373.07  5511.1  385.83  5697.7  388.00
#Mann=6,-1,0
  4234.6    0.16       0  4254.5    0.05       0  4575.3    0.16       0
  4614.1    0.05       0  4980.4    0.03       0  4990.7    0.05       0
Bank Sta=4980.4,4990.7
Exp/Cntr=0.3,0.1

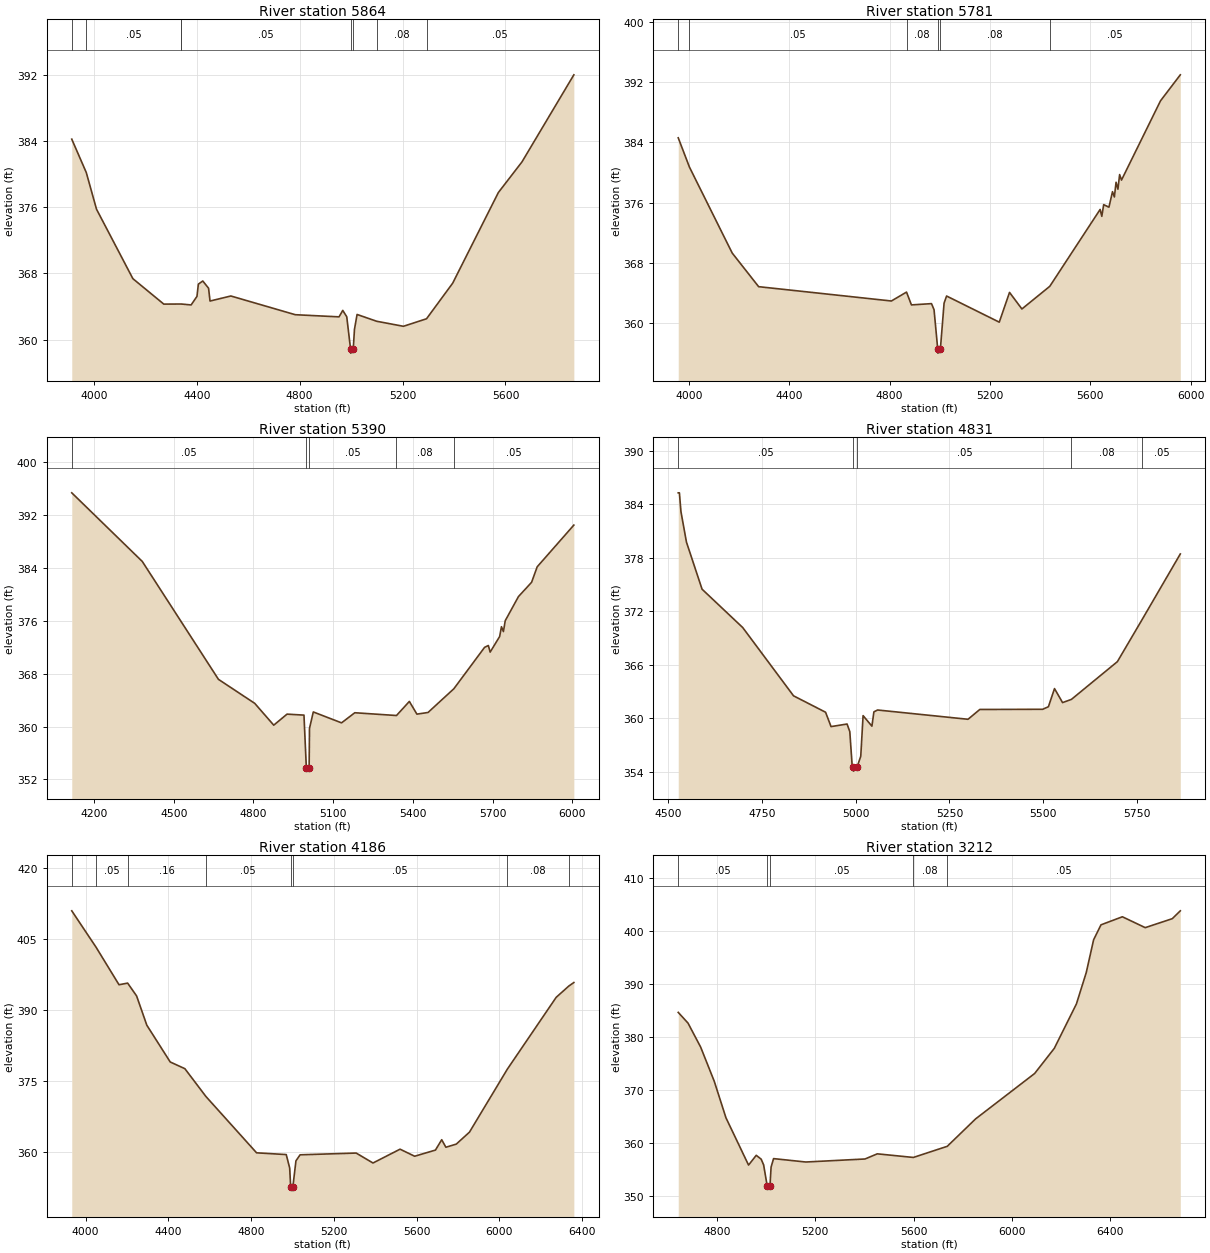
Type RM Length L Ch R = 1,5864,83,83,83
BEGIN DESCRIPTION:
SHAW BRANCH 12 0
END DESCRIPTION:
XS GIS Cut Line= 4
      3582008.48     10449234.05      3581763.27     10448724.10
      3581800.16     10447971.06      3581327.10     10447552.25
#Sta/Elev= 30
  3914.2  384.21  3970.6  380.18  4010.4  375.75  4151.8  367.36  4271.9  364.29
  4338.4  364.30  4340.1  364.30  4378.1  364.19  4400.8  365.22  4406.3  366.70
  4423.4  367.08  4446.0  366.21  4451.6  364.66  4532.6  365.27  4782.9  363.01
  4953.1  362.75  4967.6  363.53  4983.1  362.76  4997.9  358.87  4998.4  358.37
  5008.3  358.87  5013.1  361.24  5023.2  363.04  5099.2  362.22  5203.4  361.61
  5293.2  362.52  5394.9  366.82  5572.3  377.76  5664.3  381.47  5865.8  391.98
#Mann=8,-1,0
  3914.2    0.16       0  3970.6    0.05       0  4338.4    0.16       0
  4340.1    0.05       0  4997.9    0.03       0  5008.3    0.05       0
  5099.2    0.08       0  5293.2    0.05       0
Bank Sta=4997.9,5008.3
Exp/Cntr=0.3,0.1

Type RM Length L Ch R = 1,5781,391,391,391
BEGIN DESCRIPTION:
SHAW BRANCH 11 1
END DESCRIPTION:
XS GIS Cut Line= 4
      3582032.35     10449225.37      3581860.93     10448832.60
      3581871.78     10447962.38      3581348.74     10447493.60
#Sta/Elev= 30
  3957.5  384.60  4002.2  380.71  4172.5  369.31  4278.0  364.84  4807.0  362.94
  4867.4  364.12  4887.0  362.42  4967.0  362.59  4977.1  361.79  4991.9  356.52
  4992.4  356.02  5002.3  356.52  5017.1  362.65  5027.1  363.60  5237.1  360.13
  5278.0  364.08  5327.3  361.88  5438.5  364.89  5639.1  375.09  5645.8  374.18
  5653.3  375.73  5674.2  375.39  5688.4  377.45  5695.9  376.75  5702.6  378.70
  5710.1  377.78  5716.8  379.72  5724.3  378.99  5879.8  389.51  5958.7  392.96
#Mann=6,-1,0
  3957.5    0.16       0  4002.2    0.05       0  4867.4    0.08       0
  4991.9    0.07       0  5002.3    0.08       0  5438.5    0.05       0
Bank Sta=4991.9,5002.3
Exp/Cntr=0.3,0.1

Type RM Length L Ch R = 1,5390,559,559,559
BEGIN DESCRIPTION:
SHAW BRANCH 11 2
END DESCRIPTION:
XS GIS Cut Line= 4
      3582952.94     10448514.81      3582221.56     10448263.06
      3582106.54     10448163.23      3581399.07     10447510.02
#Sta/Elev= 30
  4116.5  395.35  4381.8  384.97  4668.3  367.14  4804.8  363.51  4876.3  360.21
  4926.3  361.88  4990.0  361.73  4998.9  353.76  4999.4  353.26  5009.4  353.76
  5010.8  359.73  5025.1  362.21  5131.3  360.56  5181.2  362.09  5338.0  361.67
  5386.4  363.80  5414.8  361.88  5456.7  362.13  5553.7  365.71  5669.4  371.98
  5683.6  372.26  5690.4  371.26  5726.1  373.62  5732.9  375.10  5740.3  374.37
  5747.1  376.01  5796.9  379.66  5846.3  381.82  5867.3  384.16  6005.2  390.47
#Mann=5,-1,0
  4116.5    0.05       0  4998.9    0.03       0  5009.4    0.05       0
  5338.0    0.08       0  5553.7    0.05       0
Bank Sta=4998.9,5009.4
Exp/Cntr=0.3,0.1

Type RM Length L Ch R = 1,4831,645,645,645
BEGIN DESCRIPTION:
SHAW BRANCH 28 0
END DESCRIPTION:
XS GIS Cut Line= 3
      3582792.11     10448191.64      3582392.11     10447891.64
      3581592.06     10447641.63
#Sta/Elev= 30
  4527.1  385.26  4530.2  385.26  4534.4  383.14  4549.0  379.74  4590.6  374.46
  4699.0  370.16  4834.4  362.51  4919.8  360.67  4934.4  359.06  4977.1  359.35
  4984.4  358.49  4990.6  354.73  4993.7  354.57  4994.2  354.07  5004.2  354.57
  5013.6  355.74  5019.8  360.29  5043.3  359.11  5048.6  360.71  5058.5  360.92
  5299.5  359.88  5330.9  360.98  5498.6  361.00  5513.8  361.29  5530.0  363.32
  5551.5  361.75  5575.1  362.11  5697.6  366.34  5764.4  371.12  5865.3  378.41
#Mann=5,-1,0
  4527.1    0.05       0  4993.7    0.03       0  5004.2    0.05       0
  5575.1    0.08       0  5764.4    0.05       0
Bank Sta=4993.7,5004.2
Exp/Cntr=0.3,0.1

Type RM Length L Ch R = 1,4186,974,974,974
BEGIN DESCRIPTION:
SHAW BRANCH 18 0
END DESCRIPTION:
XS GIS Cut Line= 4
      3583500.24     10448246.50      3582840.49     10447599.77
      3582475.91     10447556.37      3581347.43     10447430.50
#Sta/Elev= 30
  3933.2  410.96  4050.8  403.26  4161.6  395.34  4203.2  395.69  4246.5  392.98
  4295.9  386.80  4409.1  379.02  4479.8  377.61  4581.6  371.73  4826.4  359.83
  4969.7  359.46  4986.4  356.62  4991.1  352.66  4991.6  352.16  5001.8  352.66
  5016.6  358.13  5036.7  359.41  5307.7  359.78  5389.0  357.68  5519.8  360.60
  5590.3  359.11  5690.9  360.41  5721.1  362.60  5741.2  361.01  5791.5  361.67
  5855.1  364.19  6038.5  377.52  6274.5  392.69  6335.5  395.07  6359.7  395.81
#Mann=8,-1,0
  3933.2    0.16       0  4050.8    0.05       0  4203.2    0.16       0
  4581.6    0.05       0  4991.1    0.03       0  5001.8    0.05       0
  6038.5    0.08       0  6335.5    0.05       0
Bank Sta=4991.1,5001.8
Exp/Cntr=0.3,0.1

Type RM Length L Ch R = 1,3212,772,772,772
BEGIN DESCRIPTION:
SHAW BRANCH 7 1
END DESCRIPTION:
XS GIS Cut Line= 4
      3583200.71     10446861.93      3582918.62     10446931.37
      3582588.76     10446974.77      3581169.44     10446953.07
#Sta/Elev= 30
  4642.7  384.59  4682.5  382.57  4733.9  378.05  4789.3  371.60  4836.9  364.72
  4928.8  355.81  4960.0  357.65  4980.1  356.93  4990.2  355.84  5005.0  351.78
  5005.5  351.28  5015.8  351.78  5020.5  355.45  5030.6  357.03  5161.7  356.39
  5402.6  356.96  5452.6  357.93  5599.2  357.25  5737.3  359.35  5852.6  364.52
  6092.7  373.07  6172.7  377.81  6262.7  386.18  6302.7  392.09  6332.7  398.28
  6362.7  401.09  6449.7  402.61  6542.7  400.56  6652.7  402.25  6685.4  403.73
#Mann=5,-1,0
  4642.7    0.05       0  5005.0    0.03       0  5015.8    0.05       0
  5599.2    0.08       0  5737.3    0.05       0
Bank Sta=5005,5015.8
Exp/Cntr=0.3,0.1

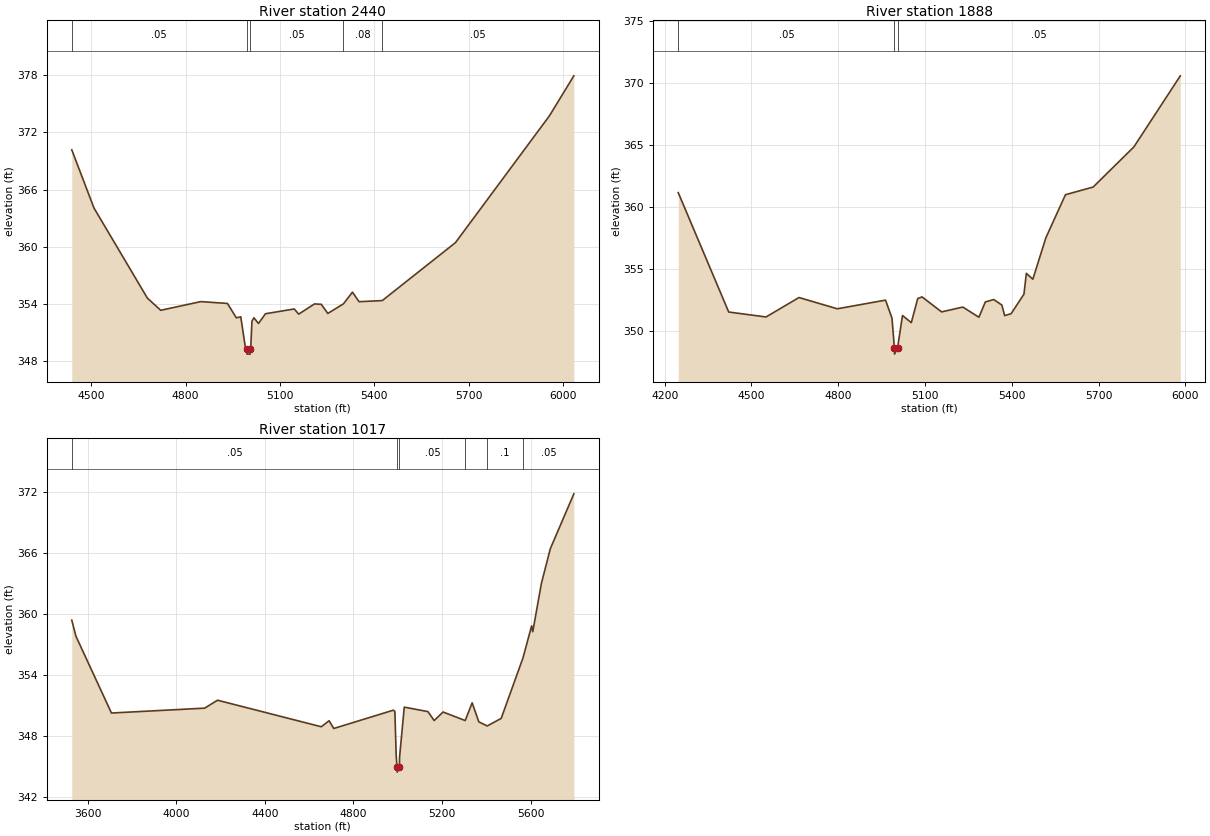
Type RM Length L Ch R = 1,2440,552,552,552
BEGIN DESCRIPTION:
SHAW BRANCH 5 1
END DESCRIPTION:
XS GIS Cut Line= 3
      3583342.12     10446641.65      3582942.11     10446241.64
      3582142.09     10445591.63
#Sta/Elev= 30
  4438.0  370.16  4508.7  364.06  4678.4  354.63  4720.9  353.35  4848.1  354.26
  4933.0  354.07  4961.3  352.56  4975.4  352.67  4989.6  349.56  4994.7  349.26
  4995.2  348.76  5005.1  348.76  5005.6  349.26  5006.9  349.26  5010.9  352.20
  5017.3  352.57  5031.7  351.97  5054.0  352.99  5145.4  353.49  5159.6  352.95
  5209.9  354.02  5231.4  353.98  5252.2  353.02  5302.0  354.03  5330.5  355.25
  5351.6  354.25  5425.4  354.37  5658.1  360.44  5956.9  373.72  6034.5  377.91
#Mann=5,-1,0
  4438.0    0.05       0  4994.7    0.03       0  5005.6    0.05       0
  5302.0    0.08       0  5425.4    0.05       0
Bank Sta=4994.7,5005.6
Exp/Cntr=0.3,0.1

Type RM Length L Ch R = 1,1888,871,871,871
BEGIN DESCRIPTION:
Mapping XS d7f1c838
END DESCRIPTION:
XS GIS Cut Line= 3
      3583545.68     10446465.41      3583500.54     10445982.78
      3582376.33     10445434.55
#Sta/Elev= 30
  4246.8  361.18  4421.3  351.54  4550.3  351.14  4664.2  352.71  4796.6  351.80
  4963.4  352.50  4985.7  351.04  4994.0  348.64  4994.5  348.14  5004.9  348.64
  5022.0  351.26  5052.4  350.68  5074.7  352.63  5089.6  352.76  5157.2  351.55
  5230.5  351.94  5286.1  351.12  5308.3  352.35  5337.4  352.55  5365.5  352.10
  5375.1  351.25  5397.3  351.40  5441.8  352.98  5450.1  354.66  5472.6  354.19
  5517.7  357.54  5585.3  361.01  5681.0  361.63  5821.8  364.87  5982.3  370.61
#Mann=3,-1,0
  4246.8    0.05       0  4994.0    0.03       0  5004.9    0.05       0
Bank Sta=4994,5004.9
Exp/Cntr=0.3,0.1

Type RM Length L Ch R = 1,1017,0,0,0
BEGIN DESCRIPTION:
SHAW BRANCH 1 0
END DESCRIPTION:
XS GIS Cut Line= 4
      3583646.37     10446510.53      3583715.82     10445385.56
      3583313.04     10445128.61      3582656.92     10445041.82
#Sta/Elev= 30
  3528.5  359.40  3547.4  357.82  3707.7  350.27  4128.5  350.75  4186.6  351.53
  4655.1  348.92  4690.2  349.51  4711.4  348.75  4980.3  350.55  4987.2  350.43
  4993.2  346.06  4997.0  344.96  4997.5  344.46  5007.9  344.96  5008.4  345.93
  5029.6  350.85  5136.4  350.41  5164.6  349.53  5204.9  350.37  5304.7  349.53
  5336.1  351.27  5366.3  349.40  5403.9  349.00  5467.2  349.74  5565.6  355.69
  5604.6  358.84  5609.7  358.26  5648.8  363.02  5689.1  366.43  5795.2  371.82
#Mann=6,-1,0
  3528.5    0.05       0  4997.0    0.03       0  5007.9    0.05       0
  5304.7    0.08       0  5403.9     0.1       0  5565.6    0.05       0
Bank Sta=4997,5007.9
Exp/Cntr=0.3,0.1

Chan Stop Cuts=-1