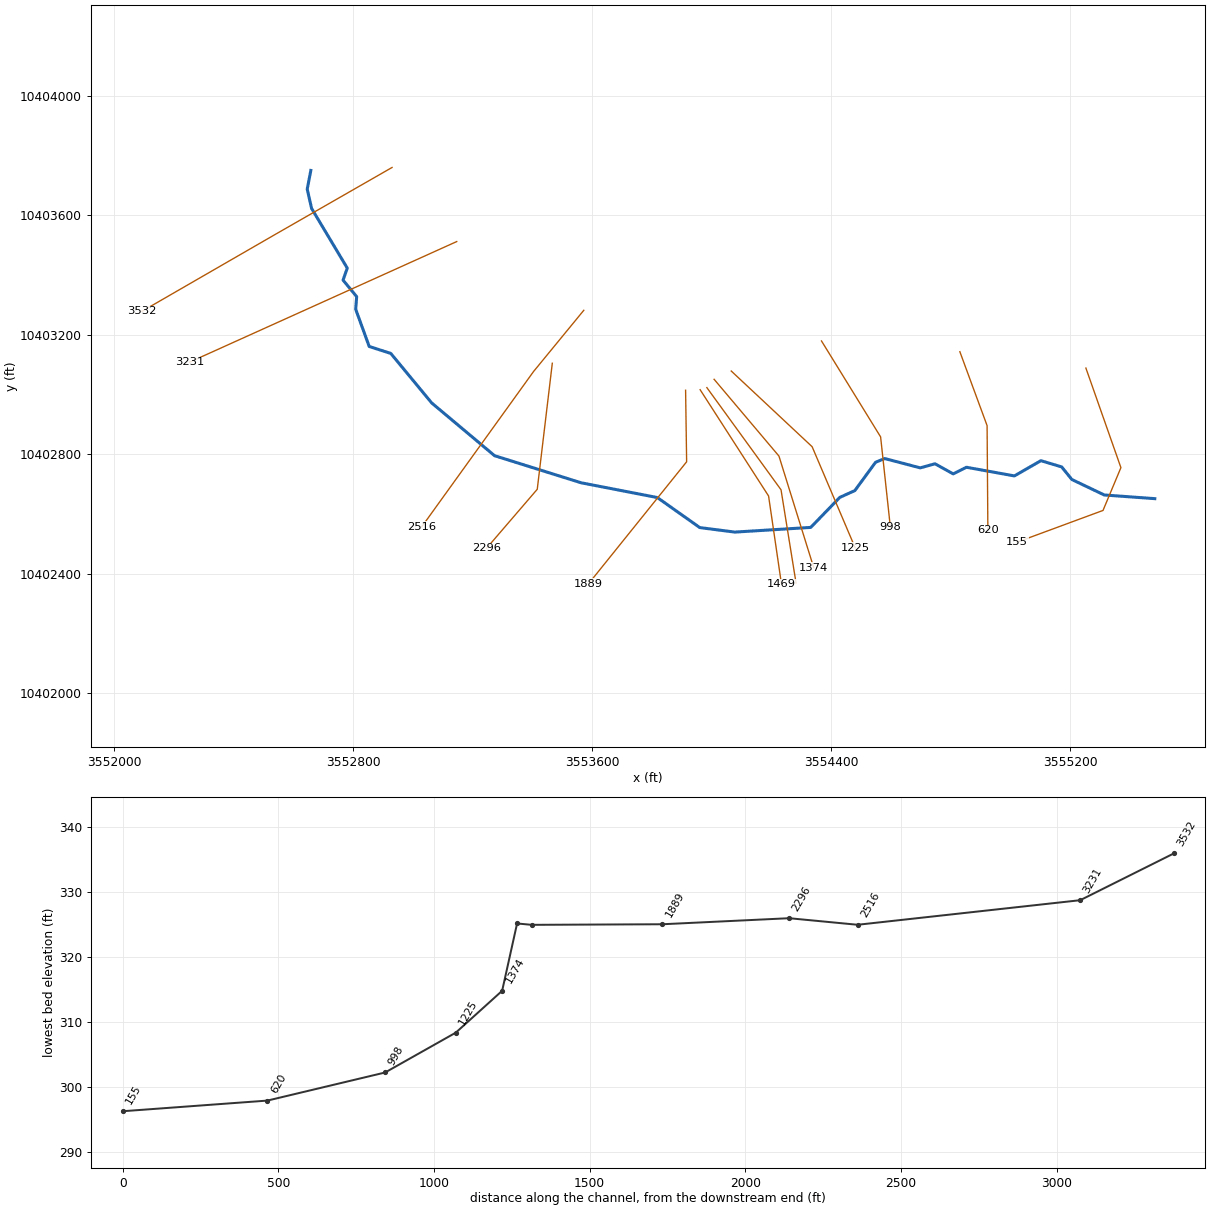
--- SHESKY BRANCH TRIB 1.prj (project) ---

Proj Title=SHESKY BRANCH TRIB 1 Base Level Engineering
Current Plan=p01
Default Exp/Contr=0.3,0.1
English Units
Geom File=g01
Flow File=f01
Plan File=p01
Y Axis Title=Elevation
X Axis Title(PF)=Main Channel Distance
X Axis Title(XS)=Station
BEGIN DESCRIPTION:
SHESKY BRANCH TRIB 1
END DESCRIPTION:
DSS Export Rating Curves= 0
DSS Export Rating Curve Sorted= 0
DSS Export Volume Flow Curves= 0
DXF OffsetX= 0
DXF OffsetY= 0
DXF ScaleX= 1
DXF ScaleY= 10

--- SHESKY BRANCH TRIB 1.p01 (plan) ---

Plan Title=Multiple Run
Short Identifier=Multiple
Geom File=g01
Flow File=f01
Subcritical Flow
K Sum by GR= 0
Std Step Tol= 0.01
Critical Tol= 0.01
Num of Std Step Trials= 20
Max Error Tol= 0.3
Flow Tol Ratio= 0.001
Split Flow NTrial= 30
Split Flow Tol= 0.02
Split Flow Ratio= 0.02
Log Output Level= 0
Friction Slope Method= 1
Unsteady Friction Slope Method= 2
Unsteady Bridges Friction Slope Method= 1
Parabolic Critical Depth
Global Vel Dist=  1 , 1 , 1
Global Log Level= 0
CheckData=True
Encroach Param= -1, 0, 0, 0
BEGIN DESCRIPTION:
Multiple Run
END DESCRIPTION:

--- SHESKY BRANCH TRIB 1.f01 (steady flow) ---

Flow Title=Multiple
Program Version=4.10
Number of Profiles= 7
Profile Names=10-year,25-year,50-year,1pct_min,100-year,1pct_plu,500-year
River Rch & RM=SHESKY BRANCH TR,Reach-1         ,3532
     410     534     632     547     740    1001    1011
Boundary for River Rch & Prof#=SHESKY BRANCH TR,Reach-1         , 1
Up Type= 0
Dn Type= 3
Dn Slope=0.005
Boundary for River Rch & Prof#=SHESKY BRANCH TR,Reach-1         , 2
Up Type= 0
Dn Type= 3
Dn Slope=0.005
Boundary for River Rch & Prof#=SHESKY BRANCH TR,Reach-1         , 3
Up Type= 0
Dn Type= 3
Dn Slope=0.005
Boundary for River Rch & Prof#=SHESKY BRANCH TR,Reach-1         , 4
Up Type= 0
Dn Type= 3
Dn Slope=0.005
Boundary for River Rch & Prof#=SHESKY BRANCH TR,Reach-1         , 5
Up Type= 0
Dn Type= 3
Dn Slope=0.005
Boundary for River Rch & Prof#=SHESKY BRANCH TR,Reach-1         , 6
Up Type= 0
Dn Type= 3
Dn Slope=0.005
Boundary for River Rch & Prof#=SHESKY BRANCH TR,Reach-1         , 7
Up Type= 0
Dn Type= 3
Dn Slope=0.005
DSS Import GetInterval= 0
DSS Import GetPeak= 0
DSS Import FillOption= 0

--- SHESKY BRANCH TRIB 1.g01 (geometry) ---

Geom Title=Existing Conditions
Program Version=4.10

River Reach=SHESKY BRANCH TR,Reach-1
Reach XY= 30
      3552657.22     10403750.19      3552645.07     10403687.69
      3552659.83     10403622.95      3552779.19      10403423.3
      3552765.08     10403383.15      3552810.65     10403327.82
       3552807.4      10403285.5      3552852.59     10403161.05
      3552924.81     10403137.79      3553061.79     10402971.99
      3553272.21     10402795.42      3553561.79      10402704.8
        3553817.     10402655.32      3553959.19      10402554.8
      3554076.37      10402539.7      3554330.58     10402555.37
      3554427.84     10402655.86      3554478.18     10402678.62
      3554547.65     10402773.49      3554578.14     10402785.93
      3554697.02     10402754.68      3554746.38     10402768.33
      3554807.49     10402734.54      3554851.68     10402756.72
      3555012.22     10402727.75      3555100.96     10402778.74
      3555170.44     10402757.89      3555204.59     10402715.72
      3555313.05     10402663.94      3555482.11     10402651.64

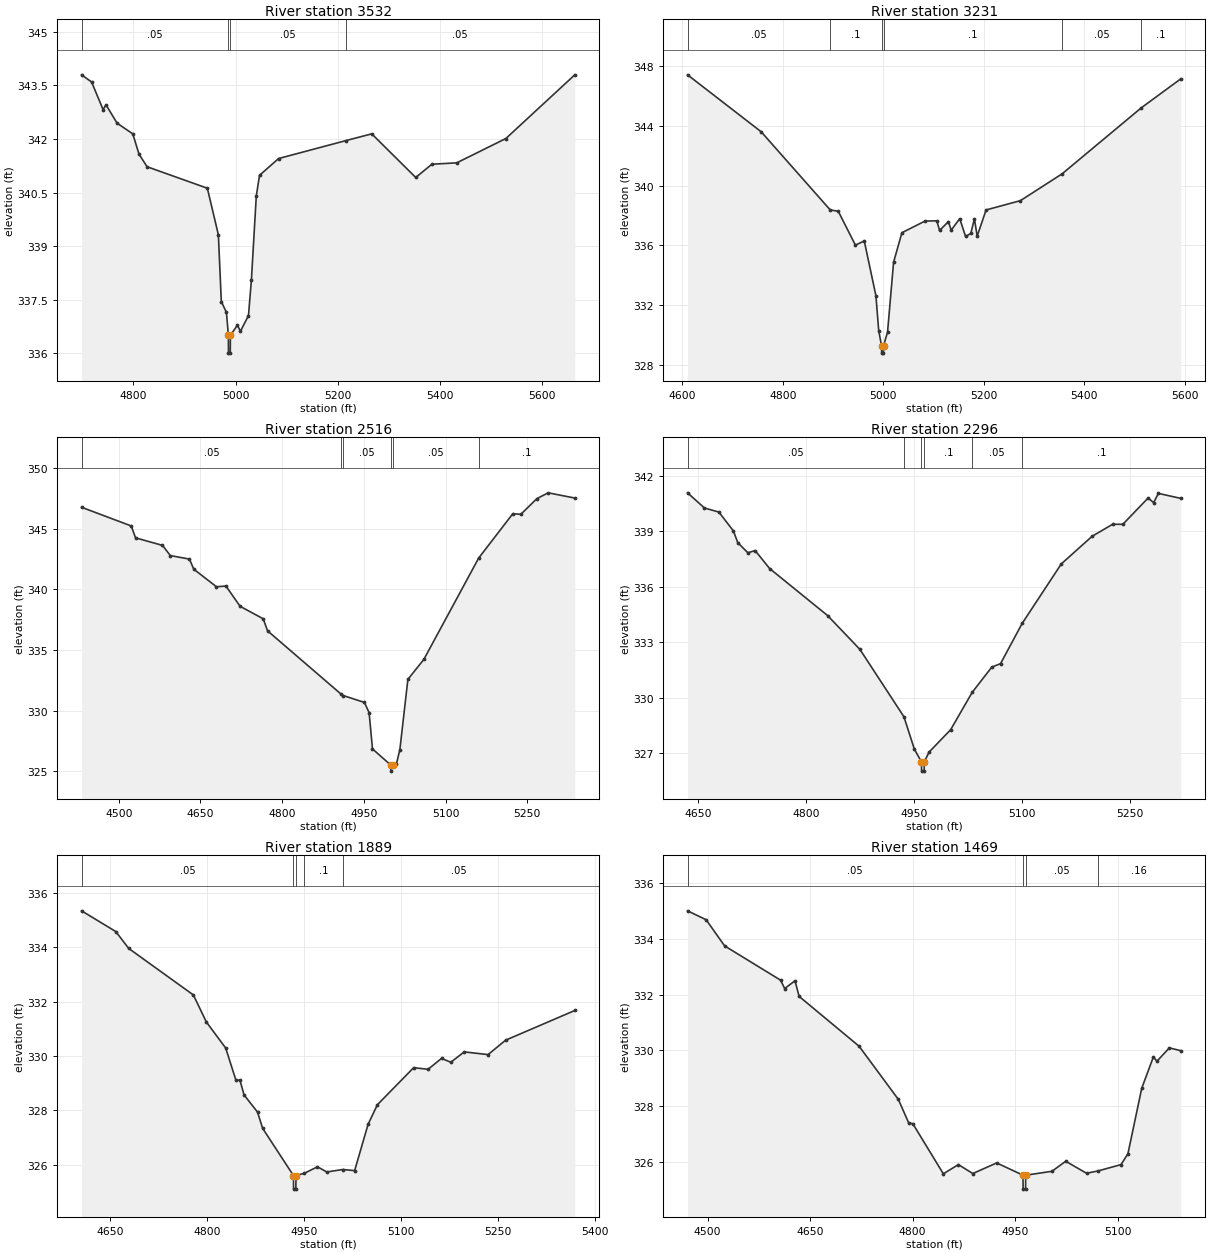
Type RM Length L Ch R = 1 ,3532    ,301,301,301
BEGIN DESCRIPTION:
SOUTH MINERAL CR TRIB 1 8 1
END DESCRIPTION:
XS GIS Cut Line= 3
       3552929.1     10403760.19      3552542.85     10403538.85
      3552091.46     10403278.43
#Sta/Elev= 30
  4698.4  343.79    4718  343.59  4740.5  342.82  4746.3  342.95  4767.9  342.44
  4798.7  342.14    4811  341.57  4826.8  341.22  4944.8  340.62  4966.4  339.32
  4972.2  337.45  4982.2  337.15    4986  336.51  4986.2  336.01  4989.7  336.01
    4990  336.51  5003.8  336.79  5009.6  336.62  5025.4  337.06  5031.1  338.05
  5040.7   340.4    5047  340.98  5084.4  341.45    5216  341.95  5266.9  342.14
  5353.1  340.92  5384.6  341.29  5433.5  341.33  5529.7  342.01  5664.7  343.79
#Mann= 4 ,-1 , 0
  4698.4     .05       0    4986     .07       0    4990     .05       0
    5216     .05       0
Bank Sta=4986,4990
XS Rating Curve= 0 ,0
Exp/Cntr=0.3,0.1

Type RM Length L Ch R = 1 ,3231    ,715,715,715
BEGIN DESCRIPTION:
SOUTH MINERAL CR TRIB 1 8 1
END DESCRIPTION:
XS GIS Cut Line= 2
      3553145.56     10403512.17      3552251.46     10403108.52
#Sta/Elev= 30
  4610.7  347.39  4757.1  343.59  4894.5  338.37  4910.5  338.28  4944.6  336.02
  4962.2   336.3  4985.4  332.64  4990.9  330.32  4996.5  329.31  4996.8  328.81
  5000.3  328.81  5000.5  329.31  5008.5  330.21  5020.5  334.88  5037.1  336.85
  5083.3  337.63  5106.5  337.64    5112     337  5129.6  337.59  5135.1  337.02
  5152.1  337.79  5163.7   336.6  5174.1   336.8  5181.3  337.78  5186.8  336.62
  5204.5  338.37  5272.8  338.99  5355.7  340.78  5513.3  345.19  5591.7  347.12
#Mann= 6 ,-1 , 0
  4610.7     .05       0  4894.5      .1       0  4996.5     .07       0
  5000.5      .1       0  5355.7     .05       0  5513.3      .1       0
Bank Sta=4996.5,5000.5
XS Rating Curve= 0 ,0
Exp/Cntr=0.3,0.1

Type RM Length L Ch R = 1 ,2516    ,220,220,220
BEGIN DESCRIPTION:
SOUTH MINERAL CR TRIB 1 7 1
END DESCRIPTION:
XS GIS Cut Line= 3
      3553570.91     10403282.13      3553402.71     10403077.18
      3553028.41     10402557.34
#Sta/Elev= 30
  4431.7  346.77  4522.9  345.23  4530.8  344.25  4580.3  343.63  4594.7  342.79
  4629.8   342.5  4637.7  341.67  4679.4  340.22  4696.8  340.28  4722.8  338.61
  4765.3  337.58  4773.2  336.59  4908.6  331.36    4912  331.26  4951.1  330.69
  4959.7  329.85  4965.9  326.86  4999.5  325.53  4999.7  325.03  5003.5  325.53
    5010  325.65  5016.2   326.8  5030.9  332.59  5060.3  334.24    5161  342.59
  5223.6  346.24  5238.3  346.19  5267.8  347.48  5288.6  347.96  5337.4  347.53
#Mann= 6 ,-1 , 0
  4431.7     .05       0  4908.6      .1       0    4912     .05       0
  4999.5     .03       0  5003.5     .05       0    5161      .1       0
Bank Sta=4999.5,5003.5
XS Rating Curve= 0 ,0
Exp/Cntr=0.3,0.1

Type RM Length L Ch R = 1 ,2296    ,407,407,407
BEGIN DESCRIPTION:
Mapping XS 7935ed52
END DESCRIPTION:
XS GIS Cut Line= 3
      3553465.49     10403104.95      3553415.13     10402683.03
        3553245.     10402485.12
#Sta/Elev= 30
  4635.3  341.08  4658.8  340.26  4678.9  340.04  4699.1  339.02  4705.1  338.39
  4719.2  337.84  4729.3  337.96  4749.4  336.99    4830  334.45    4875  332.62
  4936.2  328.98  4950.8  327.22  4960.6  326.54  4960.8  326.04  4964.3  326.04
  4964.6  326.54    4971  327.06  5001.2  328.28  5031.2   330.3  5058.4  331.66
  5070.6  331.85  5100.6  334.02  5155.1  337.24  5197.9  338.73  5226.4  339.38
  5240.7  339.38  5275.8   340.8  5283.5  340.55  5290.1  341.05  5321.2  340.78
#Mann= 6 ,-1 , 0
  4635.3     .05       0  4936.2      .1       0  4960.6     .07       0
  4964.6      .1       0  5031.2     .05       0  5100.6      .1       0
Bank Sta=4960.6,4964.6
XS Rating Curve= 0 ,0
Exp/Cntr=0.3,0.1

Type RM Length L Ch R = 1 ,1889    ,420,420,420
BEGIN DESCRIPTION:
Mapping XS 5a5541af
END DESCRIPTION:
XS GIS Cut Line= 3
      3553911.66     10403014.58      3553915.13     10402775.04
      3553587.03     10402367.08
#Sta/Elev= 30
  4605.7  335.33  4658.6  334.57  4678.6  333.95  4778.7  332.24  4798.7  331.25
  4828.7  330.29  4844.5  329.11  4850.7  329.11  4857.1  328.57  4877.9  327.94
  4885.9  327.34  4933.5  325.61  4933.7  325.11  4937.2  325.11  4937.5  325.61
  4950.2  325.69  4970.7  325.93  4985.1  325.74  5009.8  325.83  5028.2  325.79
    5049  327.49  5063.4  328.21  5119.5  329.57  5141.8  329.51  5162.6  329.91
    5177  329.77  5197.8  330.15  5234.6  330.05  5261.8  330.58  5368.8  331.67
#Mann= 5 ,-1 , 0
  4605.7     .05       0  4933.5     .07       0  4937.5     .05       0
  4950.2      .1       0  5009.8     .05       0
Bank Sta=4933.5,4937.5
XS Rating Curve= 0 ,0
Exp/Cntr=0.3,0.1

Type RM Length L Ch R = 1 ,1469    ,47,47,47
BEGIN DESCRIPTION:
SHESKY BRANCH TRIB 1 6 0
END DESCRIPTION:
XS GIS Cut Line= 3
       3553960.3     10403016.32      3554189.44     10402660.46
      3554232.61     10402365.15
#Sta/Elev= 30
  4470.6  335.01  4497.8  334.69  4524.9  333.75  4606.8  332.52  4612.7  332.22
  4627.9   332.5  4633.8  331.94  4721.6  330.15  4779.1  328.24  4794.3  327.39
  4800.2  327.37  4844.9  325.57  4866.9   325.9    4888  325.58    4923  325.96
  4961.4  325.52  4961.7  325.02  4965.2  325.02  4965.4  325.52  5003.8  325.66
    5024  326.02  5054.4  325.59  5070.7  325.67  5104.9   325.9    5115  326.29
  5135.2  328.64  5152.3  329.77  5157.4  329.61  5175.6  330.09  5192.3  329.99
#Mann= 4 ,-1 , 0
  4470.6     .05       0  4961.4    .033       0  4965.4     .05       0
  5070.7     .16       0
Bank Sta=4961.4,4965.4
XS Rating Curve= 0 ,0
Exp/Cntr=0.3,0.1

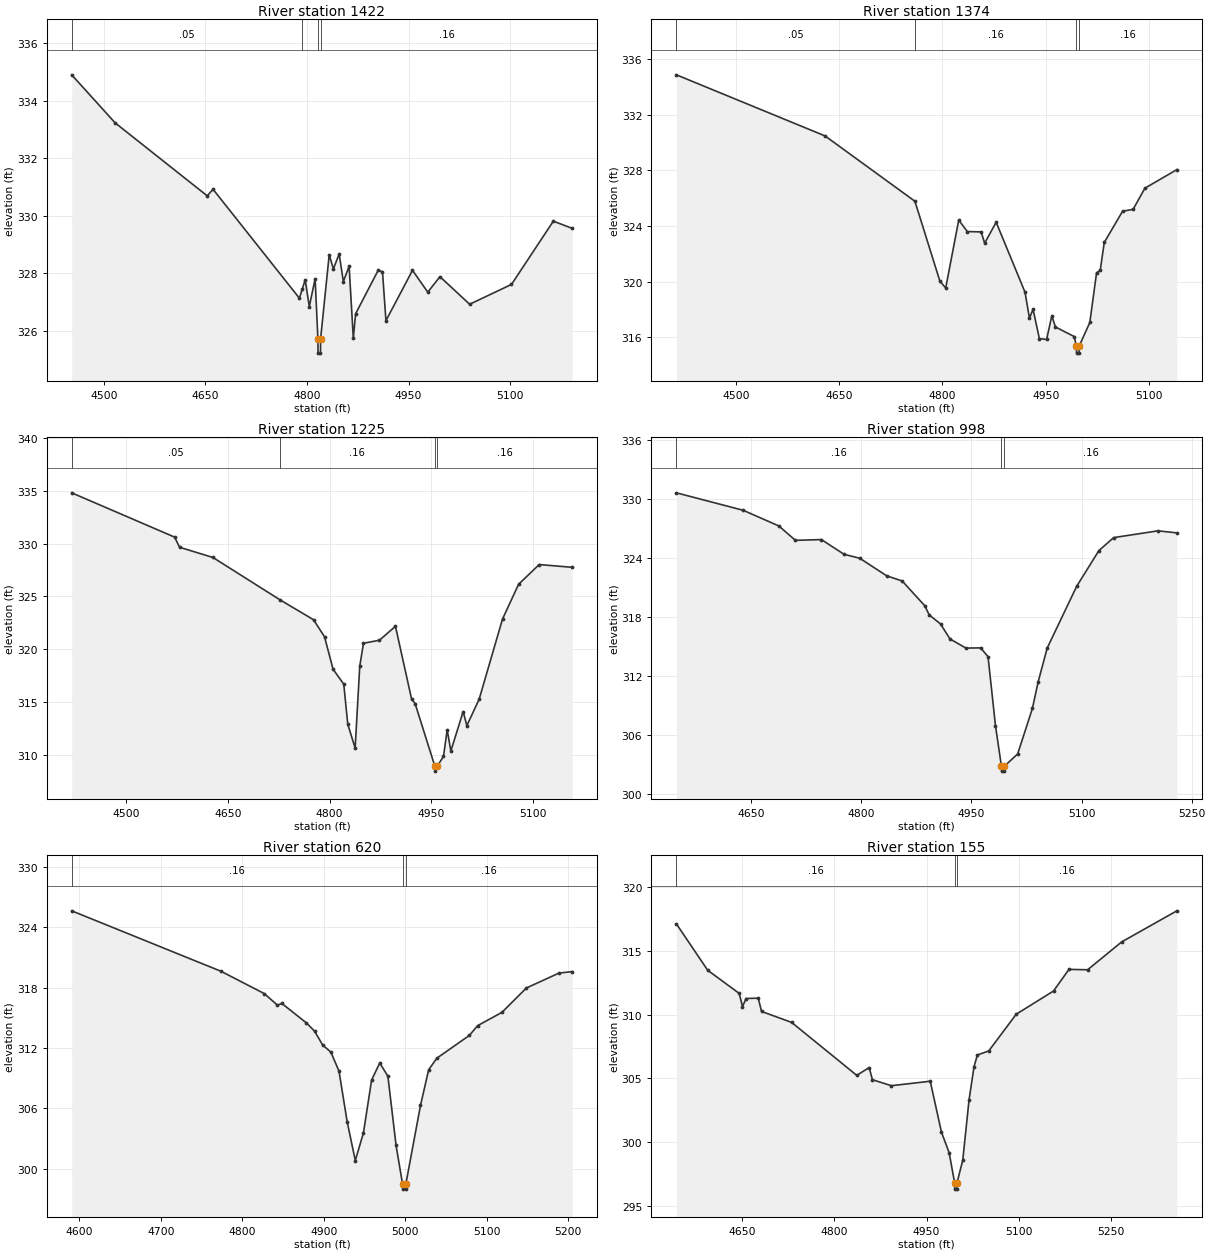
Type RM Length L Ch R = 1 ,1422    ,48,48,48
BEGIN DESCRIPTION:
SHESKY BRANCH TRIB 1 5 0
END DESCRIPTION:
XS GIS Cut Line= 3
      3553982.86     10403023.28      3554231.11     10402681.29
      3554281.45     10402368.81
#Sta/Elev= 30
  4452.5  334.91  4516.6  333.24  4652.7   330.7  4661.2  330.93  4788.8  327.14
  4793.1  327.46  4797.3  327.78  4803.4  326.85    4812  327.82  4816.1  325.73
  4816.4  325.23  4819.9  325.23  4820.1  325.73  4832.8  328.65    4839  328.16
  4847.5  328.68  4853.7  327.72  4862.2  328.25  4868.4  325.75  4871.8   326.6
  4905.1  328.11  4911.5  328.06  4916.6  326.36  4955.8  328.11  4978.4  327.35
  4996.3  327.89  5040.2  326.93    5102  327.62  5163.8  329.82  5191.6  329.57
#Mann= 4 ,-1 , 0
  4452.5     .05       0  4793.1     .16       0  4816.1     .07       0
  4820.1     .16       0
Bank Sta=4816.1,4820.1
XS Rating Curve= 0 ,0
Exp/Cntr=0.3,0.1

Type RM Length L Ch R = 1 ,1374    ,149,149,149
BEGIN DESCRIPTION:
Mapping XS 1cf50086
END DESCRIPTION:
XS GIS Cut Line= 3
      3554007.12     10403051.11      3554224.16     10402794.14
      3554340.47     10402420.91
#Sta/Elev= 30
  4413.4  334.86  4629.5  330.47    4760  325.78  4796.4  320.03  4804.8  319.55
  4823.7  324.43  4836.2   323.6  4856.2  323.58  4861.4  322.77  4878.1  324.27
    4920  319.25  4926.5  317.38  4931.7  318.02  4940.9  315.91  4951.4  315.85
    4959  317.55  4964.2  316.75  4991.5  316.06  4994.7  315.37    4995  314.87
  4998.5  314.87  4998.7  315.37  5014.2  317.07    5024  320.64  5029.3  320.81
  5035.2  322.82  5061.8  325.06  5077.1   325.2  5094.3  326.72  5140.7  328.05
#Mann= 4 ,-1 , 0
  4413.4     .05       0    4760     .16       0  4994.7     .07       0
  4998.7     .16       0
Bank Sta=4994.7,4998.7
XS Rating Curve= 0 ,0
Exp/Cntr=0.3,0.1

Type RM Length L Ch R = 1 ,1225    ,227,227,227
BEGIN DESCRIPTION:
SHESKY BRANCH TRIB 1 4 0
END DESCRIPTION:
XS GIS Cut Line= 3
      3554064.43     10403078.87      3554335.27     10402825.39
      3554479.37     10402486.83
#Sta/Elev= 30
  4419.1  334.81  4571.1  330.61  4578.4  329.65  4627.7  328.68  4726.3  324.68
  4776.2  322.78  4792.4  321.16    4805  318.09  4820.8  316.67  4826.7  312.88
  4837.6  310.61  4844.4  318.38  4849.9  320.55  4873.5  320.84  4897.1  322.16
  4920.8   315.3  4926.2  314.82  4955.1  308.93  4955.4  308.43  4959.1  308.93
    4968  309.82  4973.5  312.34  4978.9  310.34  4997.1  314.08  5002.5  312.74
  5020.7  315.25  5055.2  322.85  5078.9  326.14  5109.3  328.01    5158  327.75
#Mann= 4 ,-1 , 0
  4419.1     .05       0  4726.3     .16       0  4955.1     .07       0
  4959.1     .16       0
Bank Sta=4955.1,4959.1
XS Rating Curve= 0 ,0
Exp/Cntr=0.3,0.1

Type RM Length L Ch R = 1 ,998     ,378,378,378
BEGIN DESCRIPTION:
Mapping XS 3eb1a6dc
END DESCRIPTION:
XS GIS Cut Line= 3
      3554366.53     10403179.54      3554564.44     10402858.37
      3554597.06     10402556.17
#Sta/Elev= 30
  4548.6  330.64  4639.6  328.86    4688  327.27  4710.6   325.8    4746  325.88
  4776.8  324.38  4798.1  323.98  4834.8  322.19    4856  321.66  4886.8  319.13
  4892.7  318.21  4908.1  317.29    4921  315.76  4942.7  314.83  4962.8  314.85
  4972.8  313.95  4982.9  306.93    4991   302.8  4991.2   302.3  4994.7   302.3
    4995   302.8  5013.1  304.05  5033.2  308.69    5041  311.39  5053.3  314.83
  5093.5  321.13  5123.7  324.76  5143.8  326.08  5204.2  326.77  5229.8  326.56
#Mann= 3 ,-1 , 0
  4548.6     .16       0    4991     .07       0    4995     .16       0
Bank Sta=4991,4995
XS Rating Curve= 0 ,0
Exp/Cntr=0.3,0.1

Type RM Length L Ch R = 1 ,620     ,465,465,465
BEGIN DESCRIPTION:
Mapping XS 9b21fb44
END DESCRIPTION:
XS GIS Cut Line= 3
      3554829.73     10403143.42      3554920.86     10402896.05
      3554923.46     10402545.58
#Sta/Elev= 30
  4590.6  325.62  4773.7  319.62  4826.9   317.4  4843.1  316.25  4848.5  316.42
  4878.6  314.49  4888.6  313.67  4898.6  312.29  4908.6  311.59  4918.6   309.7
  4928.6  304.68  4938.6  300.82  4948.6  303.57  4958.6  308.81  4968.6  310.51
  4978.6  309.19  4988.6  302.33  4996.6  298.48  4996.9  297.98  5000.4  297.98
  5000.6  298.48  5018.6  306.29  5028.6  309.83  5038.6  310.98  5078.6  313.25
  5088.6  314.21  5118.6  315.54  5148.6  317.96  5188.6  319.44  5204.7  319.58
#Mann= 3 ,-1 , 0
  4590.6     .16       0  4996.6     .07       0  5000.6     .16       0
Bank Sta=4996.6,5000.6
XS Rating Curve= 0 ,0
Exp/Cntr=0.3,0.1

Type RM Length L Ch R = 1 ,155     ,0,0,0
BEGIN DESCRIPTION:
SHESKY BRANCH TRIB 1 1 0
END DESCRIPTION:
XS GIS Cut Line= 4
       3555251.6     10403088.73      3555368.78     10402755.42
      3555308.88     10402612.19      3555021.52     10402506.05
#Sta/Elev= 30
  4542.6  317.09  4593.6  313.46  4644.9  311.65  4650.2  310.62  4656.1  311.25
  4675.9  311.28  4681.2  310.24  4730.3  309.38  4836.3  305.24  4856.5  305.85
  4861.8   304.9  4892.7  304.43  4955.9  304.78  4974.2   300.8  4986.7  299.19
  4995.6  296.84  4995.8  296.34  4999.3  296.34  4999.6  296.84  5008.9  298.61
  5019.2  303.35  5027.3  305.93  5032.7  306.83  5051.2  307.15  5095.9  310.02
  5156.7  311.84  5181.8  313.53  5212.2   313.5  5267.7  315.68  5357.5  318.11
#Mann= 3 ,-1 , 0
  4542.6     .16       0  4995.6     .07       0  4999.6     .16       0
Bank Sta=4995.6,4999.6
XS Rating Curve= 0 ,0
Exp/Cntr=0.3,0.1

Chan Stop Cuts=-1
Use User Specified Reach Order=0
Composite Channel Slope=5