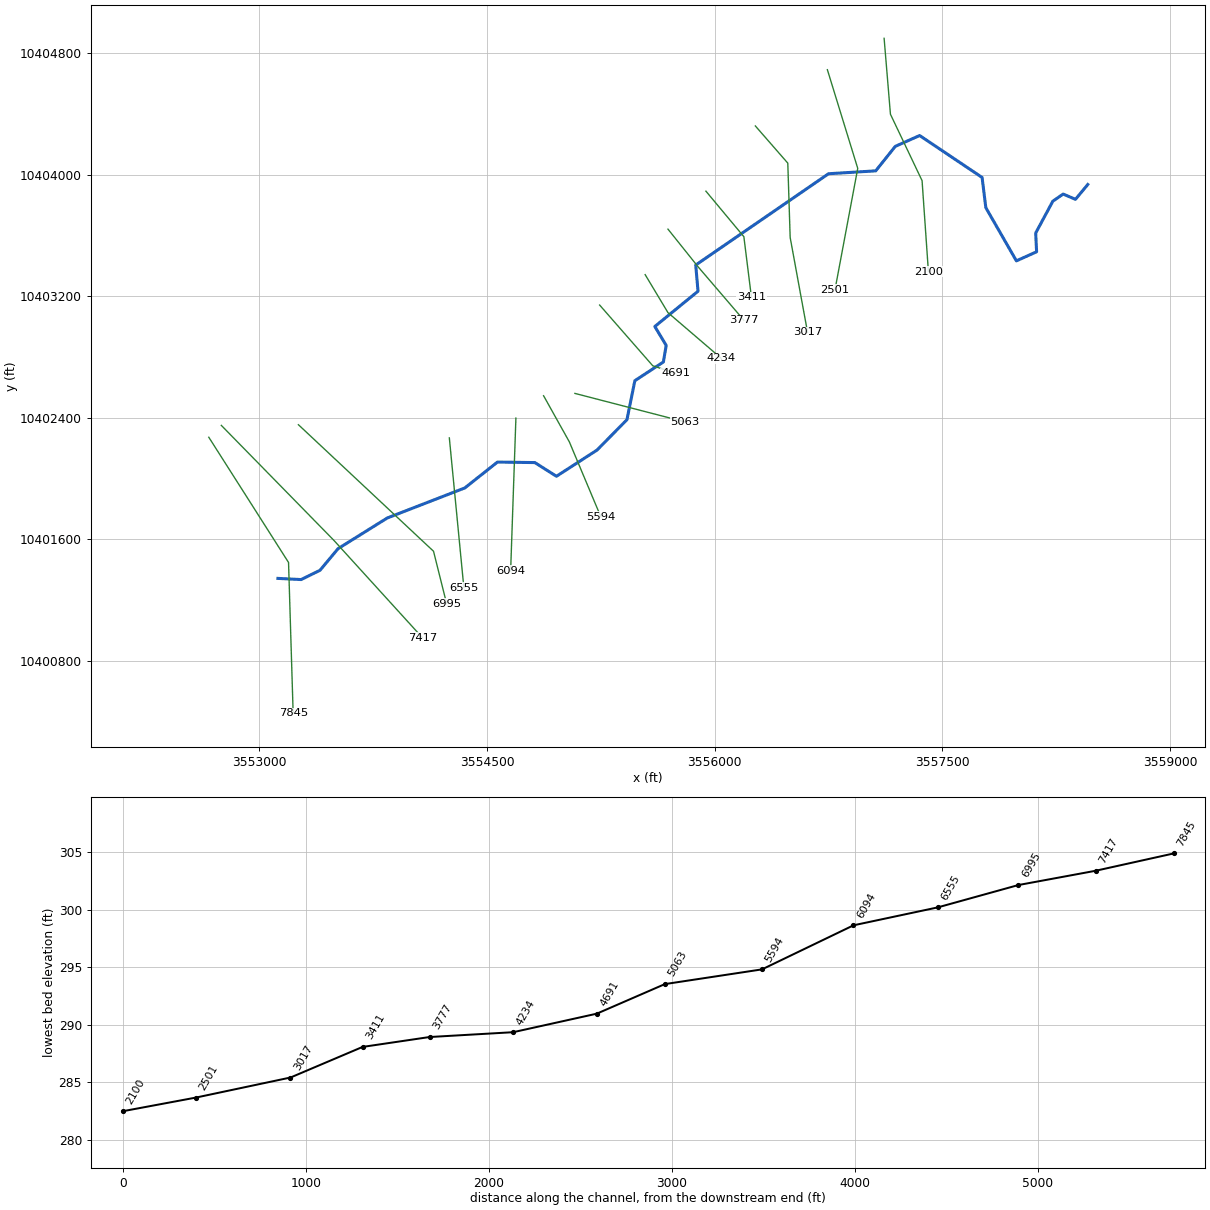
--- SHESKY BRANCH.prj (project) ---

Proj Title=SHESKY BRANCH Base Level Engineering
Current Plan=p01
Default Exp/Contr=0.3,0.1
English Units
Geom File=g01
Flow File=f01
Plan File=p01
BEGIN DESCRIPTION:
SHESKY BRANCH
END DESCRIPTION:

--- SHESKY BRANCH.p01 (plan) ---

Plan Title=Multiple Run
Short Identifier=Multiple
Geom File=g01
Flow File=f01
Subcritical Flow
K Sum by GR= 0
Std Step Tol= 0.01
Critical Tol= 0.01
Num of Std Step Trials= 20
Max Error Tol= 0.3
Flow Tol Ratio= 0.001
Split Flow NTrial= 30
Split Flow Tol= 0.02
Split Flow Ratio= 0.02
Log Output Level= 0
Friction Slope Method= 1
Unsteady Friction Slope Method= 2
Unsteady Bridges Friction Slope Method= 1
Parabolic Critical Depth
Global Vel Dist=  1 , 1 , 1
Global Log Level= 0
CheckData=True
Encroach Param= -1, 0, 0, 0
BEGIN DESCRIPTION:
Multiple Run
END DESCRIPTION:

--- SHESKY BRANCH.f01 (steady flow) ---

Flow Title=Multiple
Number of Profiles=7
Profile Names=10-year,25-year,50-year,1pct_min,100-year,1pct_plu,500-year
River Rch & RM= SHESKY BRANCH,Reach-1,7845
     911    1251    1532    1370    1852    2505    2700
River Rch & RM= SHESKY BRANCH,Reach-1,4691
    1378    1933    2400    2173    2938    3973    4393
Boundary for River Rch & Prof#=SHESKY BRANCH,Reach-1,1
Up Type=0
Dn Type=3
Dn Slope=0.005
Boundary for River Rch & Prof#=SHESKY BRANCH,Reach-1,2
Up Type=0
Dn Type=3
Dn Slope=0.005
Boundary for River Rch & Prof#=SHESKY BRANCH,Reach-1,3
Up Type=0
Dn Type=3
Dn Slope=0.005
Boundary for River Rch & Prof#=SHESKY BRANCH,Reach-1,4
Up Type=0
Dn Type=3
Dn Slope=0.005
Boundary for River Rch & Prof#=SHESKY BRANCH,Reach-1,5
Up Type=0
Dn Type=3
Dn Slope=0.005
Boundary for River Rch & Prof#=SHESKY BRANCH,Reach-1,6
Up Type=0
Dn Type=3
Dn Slope=0.005
Boundary for River Rch & Prof#=SHESKY BRANCH,Reach-1,7
Up Type=0
Dn Type=3
Dn Slope=0.005

--- SHESKY BRANCH.g01 (geometry) ---

Geom Title=Existing Conditions

River Reach=SHESKY BRANCH,Reach-1
Reach XY= 30
      3553123.60     10401341.27      3553276.52     10401333.57
      3553400.85     10401394.89      3553519.29     10401536.89
      3553843.28     10401739.00      3554354.56     10401937.09
      3554569.22     10402107.42      3554815.52     10402104.01
      3554957.65     10402013.83      3555225.00     10402186.38
      3555422.08     10402386.55      3555474.19     10402643.28
      3555662.05     10402766.57      3555680.65     10402875.95
      3555605.69     10403000.25      3555890.10     10403232.59
      3555875.11     10403405.12      3556749.62     10404006.28
      3557060.49     10404025.35      3557189.43     10404186.74
      3557349.74     10404258.01      3557761.07     10403981.98
      3557785.62     10403783.10      3557986.97     10403432.67
      3558120.07     10403492.35      3558114.06     10403615.78
      3558227.12     10403825.63      3558295.17     10403872.51
      3558376.08     10403837.78      3558457.18     10403935.57

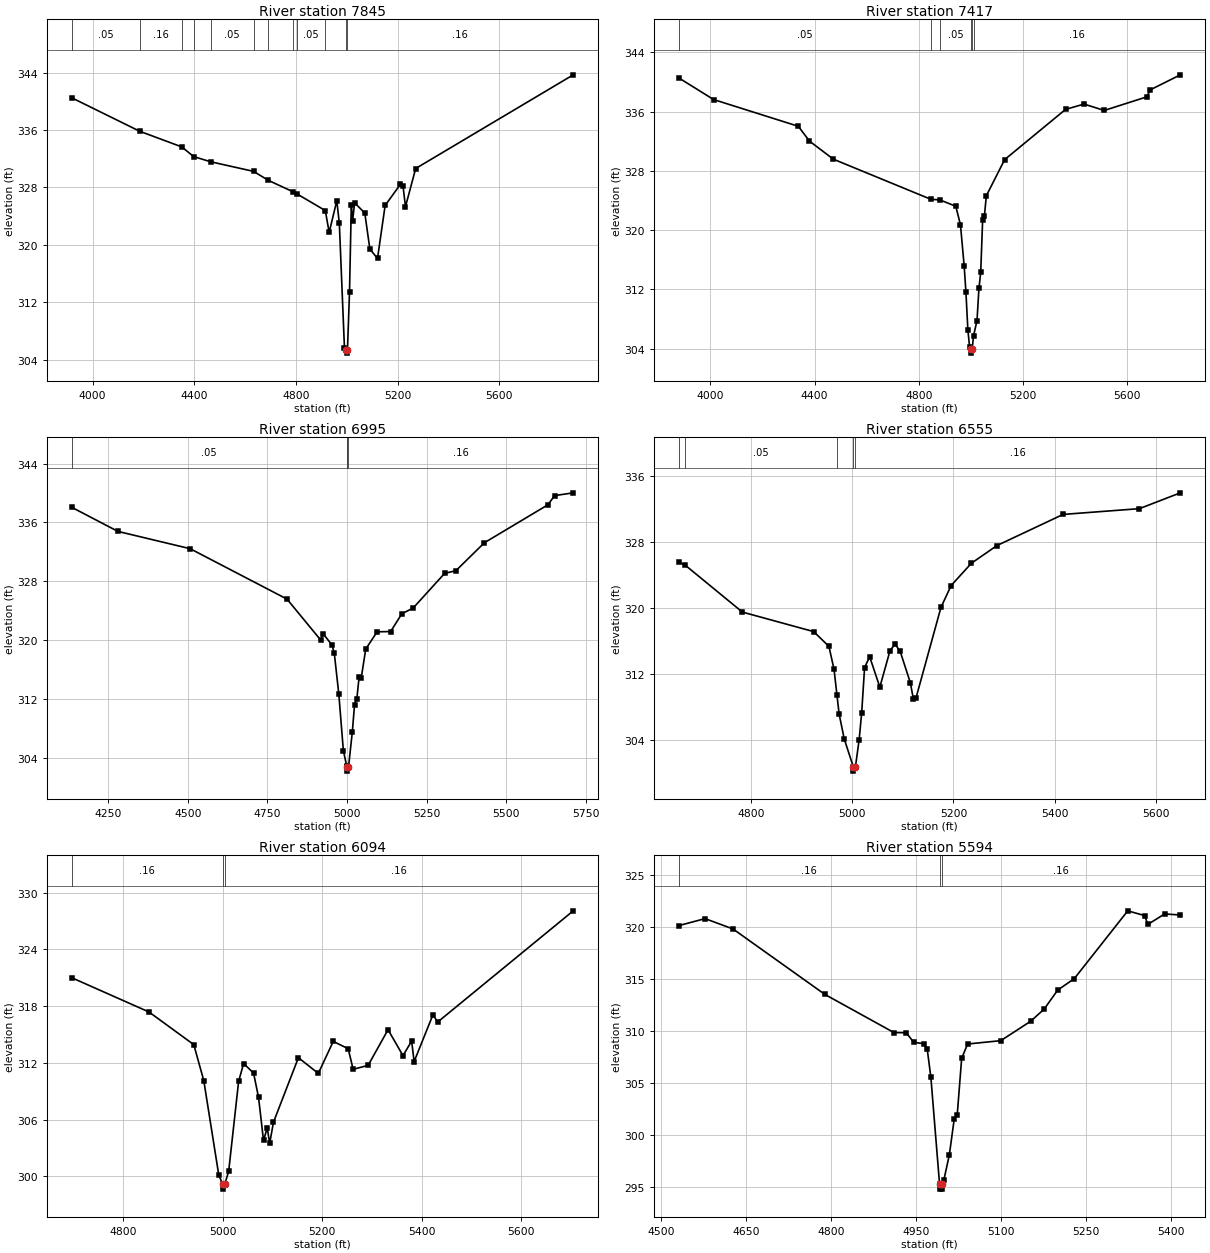
Type RM Length L Ch R = 1,7845,428,428,428
BEGIN DESCRIPTION:
SHESKY BRANCH 4 0
END DESCRIPTION:
XS GIS Cut Line= 3
      3552668.13     10402270.89      3553193.32     10401446.21
      3553223.71     10400452.28
#Sta/Elev= 30
  3918.2  340.48  4185.4  335.82  4350.7  333.64  4397.8  332.29  4464.2  331.57
  4633.2  330.23  4691.3  328.98  4790.1  327.36  4804.8  327.07  4915.3  324.77
  4930.5  321.73  4960.5  326.14  4970.5  322.98  4990.5  305.69  4998.5  305.41
  4998.8  304.91  5002.5  305.41  5010.5  313.44  5017.6  325.58  5022.6  323.33
  5030.5  325.86  5070.6  324.42  5090.6  319.39  5120.6  318.11  5150.6  325.49
  5210.6  328.42  5220.6  328.26  5230.6  325.32  5270.7  330.63  5890.3  343.68
#Mann=12,-1,0
  3918.2    0.05       0  4185.4    0.16       0  4350.7    0.05       0
  4397.8    0.16       0  4464.2    0.05       0  4633.2     0.1       0
  4691.3    0.05       0  4790.1     0.1       0  4804.8    0.05       0
  4915.3    0.16       0  4998.5    0.07       0  5002.5    0.16       0
Bank Sta=4998.5,5002.5
Exp/Cntr=0.3,0.1

Type RM Length L Ch R = 1,7417,422,422,422
BEGIN DESCRIPTION:
SHESKY BRANCH 3 0
END DESCRIPTION:
XS GIS Cut Line= 3
      3552750.61     10402348.99      3553492.11     10401591.64
      3554074.38     10400951.43
#Sta/Elev= 30
  3878.5  340.56  4012.1  337.64  4337.3  334.03  4379.7  332.04  4471.7  329.59
  4846.9  324.16  4880.1  324.10  4941.8  323.23  4959.7  320.72  4973.9  315.18
  4980.6  311.67  4988.1  306.56  4994.8  304.20  5000.3  303.90  5000.5  303.40
  5004.3  303.90  5010.0  305.75  5023.2  307.80  5030.6  312.13  5037.4  314.29
  5044.8  321.34  5051.6  321.92  5059.0  324.65  5129.3  329.53  5363.1  336.31
  5434.0  337.03  5511.7  336.17  5674.6  338.00  5688.8  338.96  5803.8  340.98
#Mann=6,-1,0
  3878.5    0.05       0  4846.9     0.1       0  4880.1    0.05       0
  5000.3   0.035       0  5004.3    0.05       0  5010.0    0.16       0
Bank Sta=5000.3,5004.3
Exp/Cntr=0.3,0.1

Type RM Length L Ch R = 1,6995,440,440,440
BEGIN DESCRIPTION:
SHESKY BRANCH 15 0
END DESCRIPTION:
XS GIS Cut Line= 3
      3553258.41     10402353.34      3554148.18     10401519.99
      3554234.51     10401174.70
#Sta/Elev= 30
  4135.6  338.05  4280.8  334.77  4507.4  332.42  4811.7  325.56  4917.7  319.98
  4924.6  320.88  4952.9  319.32  4960.2  318.18  4974.4  312.62  4988.6  304.96
  4999.4  302.80  5000.7  302.66  5001.0  302.16  5004.7  302.66  5016.9  307.55
  5023.8  311.22  5031.1  312.03  5037.9  314.93  5044.9  314.88  5058.9  318.76
  5094.6  321.11  5137.1  321.15  5172.3  323.57  5207.9  324.35  5306.6  329.06
  5342.2  329.43  5431.5  333.23  5631.3  338.40  5651.9  339.64  5710.6  340.02
#Mann=4,-1,0
  4135.6    0.05       0  4999.4    0.16       0  5000.7    0.07       0
  5004.7    0.16       0
Bank Sta=5000.7,5004.7
Exp/Cntr=0.3,0.1

Type RM Length L Ch R = 1,6555,461,461,461
BEGIN DESCRIPTION:
SHESKY BRANCH 14 0
END DESCRIPTION:
XS GIS Cut Line= 2
      3554252.35     10402266.49      3554347.84     10401281.30
#Sta/Elev= 30
  4658.1  325.57  4670.7  325.21  4783.5  319.52  4924.2  317.15  4954.3  315.36
  4964.4  312.58  4970.1  309.50  4974.4  307.17  4984.5  304.13  5002.6  300.72
  5002.8  300.22  5006.6  300.72  5014.0  304.05  5019.0  307.32  5024.7  312.78
  5034.7  314.11  5054.8  310.41  5074.9  314.84  5084.9  315.64  5095.0  314.74
  5115.1  310.93  5121.1  308.93  5126.1  309.08  5175.4  320.08  5195.4  322.73
  5235.6  325.45  5285.9  327.59  5416.5  331.37  5567.2  332.07  5647.9  333.99
#Mann=5,-1,0
  4658.1    0.16       0  4670.7    0.05       0  4970.1    0.16       0
  5002.6    0.07       0  5006.6    0.16       0
Bank Sta=5002.6,5006.6
Exp/Cntr=0.3,0.1

Type RM Length L Ch R = 1,6094,500,500,500
BEGIN DESCRIPTION:
SHESKY BRANCH 13 0
END DESCRIPTION:
XS GIS Cut Line= 2
      3554690.72     10402396.75      3554656.00     10401389.74
#Sta/Elev= 30
  4696.8  321.00  4852.0  317.38  4942.0  313.93  4962.1  310.13  4992.1  300.18
  5000.1  299.16  5000.3  298.66  5004.1  299.16  5012.1  300.54  5032.1  310.05
  5042.1  311.93  5062.1  310.93  5072.1  308.36  5082.1  303.80  5089.5  305.13
  5094.5  303.50  5102.1  305.73  5152.2  312.55  5192.2  310.89  5222.2  314.27
  5252.2  313.50  5262.2  311.32  5292.3  311.74  5332.3  315.51  5362.3  312.77
  5379.7  314.30  5384.7  312.14  5422.3  317.06  5432.3  316.33  5704.4  328.07
#Mann=3,-1,0
  4696.8    0.16       0  5000.1    0.07       0  5004.1    0.16       0
Bank Sta=5000.1,5004.1
Exp/Cntr=0.3,0.1

Type RM Length L Ch R = 1,5594,531,531,531
BEGIN DESCRIPTION:
SHESKY BRANCH 12 0
END DESCRIPTION:
XS GIS Cut Line= 3
      3554873.03     10402544.27      3555042.61     10402240.64
      3555250.40     10401746.21
#Sta/Elev= 30
  4531.8  320.16  4578.0  320.83  4627.2  319.84  4789.4  313.54  4911.0  309.88
  4932.7  309.86  4945.9  308.94  4964.2  308.81  4969.7  308.28  4976.1  305.59
  4991.4  295.33  4991.7  294.83  4995.2  294.83  4995.4  295.33  4998.8  295.66
  5008.7  298.13  5017.2  301.54  5022.6  301.99  5030.4  307.40  5040.9  308.78
  5099.3  309.10  5152.2  310.97  5175.9  312.14  5199.7  313.96  5228.9  315.06
  5323.2  321.58  5353.1  321.12  5358.5  320.27  5388.3  321.28  5415.9  321.18
#Mann=3,-1,0
  4531.8    0.16       0  4991.4    0.07       0  4995.4    0.16       0
Bank Sta=4991.4,4995.4
Exp/Cntr=0.3,0.1

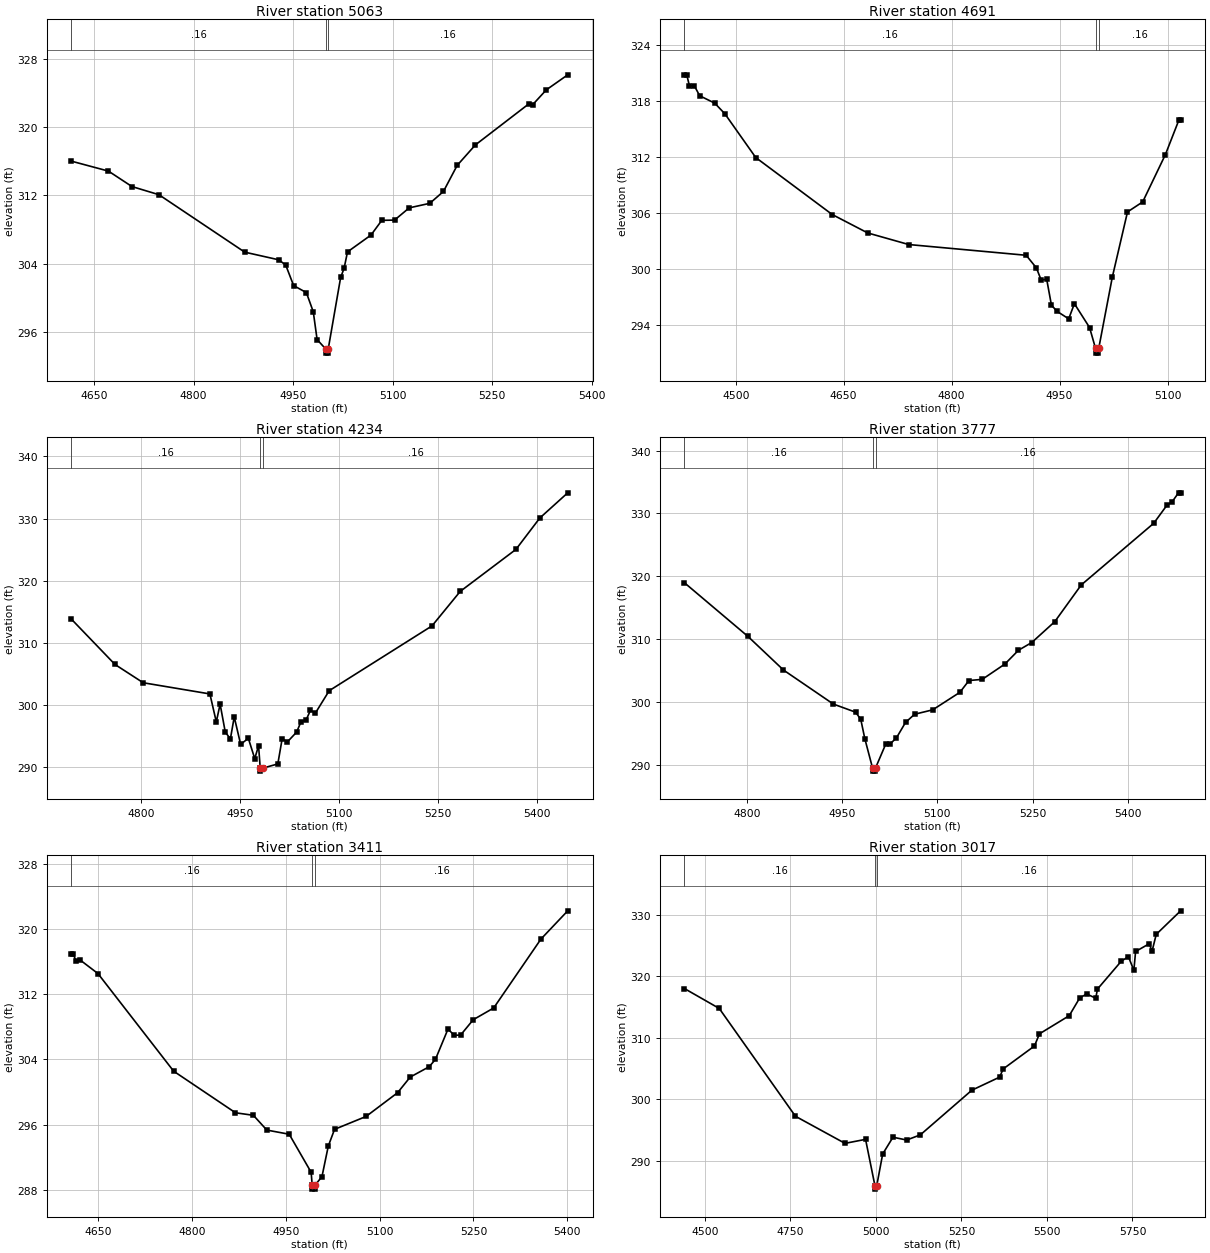
Type RM Length L Ch R = 1,5063,372,372,372
BEGIN DESCRIPTION:
SHESKY BRANCH 39 0
END DESCRIPTION:
XS GIS Cut Line= 2
      3555079.38     10402559.64      3555803.39     10402372.12
#Sta/Elev= 30
  4616.1  316.00  4671.8  314.84  4707.3  313.03  4747.9  312.08  4877.2  305.36
  4928.8  304.46  4939.1  303.83  4950.9  301.45  4970.1  300.63  4980.5  298.39
  4986.3  295.13  4999.1  294.05  4999.4  293.55  5002.9  293.55  5003.1  294.05
  5021.8  302.42  5026.9  303.45  5032.1  305.39  5067.5  307.36  5083.8  309.08
  5103.0  309.11  5125.1  310.54  5156.1  311.07  5176.7  312.46  5197.4  315.51
  5224.8  317.90  5306.0  322.74  5311.1  322.60  5331.7  324.34  5364.0  326.10
#Mann=3,-1,0
  4616.1    0.16       0  4999.1    0.07       0  5003.1    0.16       0
Bank Sta=4999.1,5003.1
Exp/Cntr=0.3,0.1

Type RM Length L Ch R = 1,4691,457,457,457
BEGIN DESCRIPTION:
SHESKY BRANCH 29 0
END DESCRIPTION:
XS GIS Cut Line= 3
      3555242.12     10403141.62      3555592.11     10402741.64
      3555742.11     10402691.64
#Sta/Elev= 30
  4428.6  320.76  4431.9  320.76  4435.7  319.57  4442.3  319.61  4449.9  318.52
  4470.8  317.73  4485.0  316.58  4527.8  311.91  4634.1  305.81  4683.4  303.84
  4740.4  302.60  4903.6  301.45  4917.8  300.10  4924.5  298.79  4932.1  298.89
  4938.7  296.12  4946.3  295.46  4962.7  294.65  4970.6  296.27  4991.7  293.72
  5000.0  291.48  5000.3  290.98  5004.1  290.98  5004.4  291.48  5023.3  299.11
  5044.4  306.09  5065.5  307.16  5097.1  312.23  5115.6  315.88  5118.2  315.88
#Mann=3,-1,0
  4428.6    0.16       0  5000.0    0.07       0  5004.4    0.16       0
Bank Sta=5000,5004.4
Exp/Cntr=0.3,0.1

Type RM Length L Ch R = 1,4234,457,457,457
BEGIN DESCRIPTION:
SHESKY BRANCH 9 0
END DESCRIPTION:
XS GIS Cut Line= 3
      3555542.13     10403341.61      3555692.11     10403091.64
      3556042.12     10402791.63
#Sta/Elev= 30
  4694.2  313.81  4760.2  306.53  4803.0  303.59  4904.1  301.79  4913.8  297.29
  4919.6  300.15  4927.4  295.65  4935.2  294.57  4941.0  298.09  4950.7  293.68
  4962.4  294.65  4972.1  291.38  4977.9  293.46  4980.4  289.87  4980.8  289.37
  4985.1  289.87  5007.1  290.53  5013.7  294.60  5021.4  294.05  5035.6  295.65
  5042.2  297.30  5049.9  297.58  5056.5  299.14  5064.2  298.73  5085.0  302.31
  5240.9  312.74  5283.7  318.29  5368.2  325.05  5404.4  330.10  5446.7  334.15
#Mann=3,-1,0
  4694.2    0.16       0  4980.4    0.07       0  4985.1    0.16       0
Bank Sta=4980.4,4985.1
Exp/Cntr=0.3,0.1

Type RM Length L Ch R = 1,3777,366,366,366
BEGIN DESCRIPTION:
SHESKY BRANCH 8 0
END DESCRIPTION:
XS GIS Cut Line= 3
      3555692.13     10403641.61      3555892.11     10403391.64
      3556192.11     10403041.64
#Sta/Elev= 30
  4701.8  318.96  4801.8  310.41  4857.8  305.05  4936.3  299.63  4971.5  298.33
  4979.5  297.18  4985.9  294.10  4998.0  289.45  4998.3  288.95  5002.4  288.95
  5002.7  289.45  5018.7  293.24  5025.2  293.24  5035.6  294.24  5049.9  296.70
  5064.2  298.01  5092.7  298.71  5135.5  301.50  5149.8  303.38  5170.6  303.56
  5206.3  306.00  5227.7  308.20  5248.6  309.43  5284.8  312.75  5326.5  318.60
  5440.6  328.42  5461.5  331.31  5469.2  331.79  5479.6  333.27  5482.9  333.27
#Mann=3,-1,0
  4701.8    0.16       0  4998.0    0.07       0  5002.7    0.16       0
Bank Sta=4998,5002.7
Exp/Cntr=0.3,0.1

Type RM Length L Ch R = 1,3411,394,394,394
BEGIN DESCRIPTION:
SHESKY BRANCH 7 0
END DESCRIPTION:
XS GIS Cut Line= 3
      3555942.11     10403891.64      3556192.11     10403591.64
      3556242.10     10403191.66
#Sta/Elev= 30
  4607.2  316.86  4610.4  316.86  4614.4  316.04  4620.9  316.19  4649.5  314.52
  4770.6  302.55  4869.5  297.45  4898.1  297.14  4919.6  295.33  4955.4  294.82
  4990.5  290.15  4992.1  288.59  4992.4  288.09  4996.5  288.09  4996.9  288.59
  5007.8  289.63  5017.9  293.37  5027.9  295.42  5078.3  297.00  5128.7  299.91
  5148.9  301.83  5179.1  303.09  5189.2  303.99  5209.3  307.71  5219.4  306.95
  5229.5  306.98  5249.7  308.86  5282.4  310.30  5358.0  318.75  5400.8  322.21
#Mann=3,-1,0
  4607.2    0.16       0  4992.1    0.07       0  4996.9    0.16       0
Bank Sta=4992.1,4996.9
Exp/Cntr=0.3,0.1

Type RM Length L Ch R = 1,3017,516,516,516
BEGIN DESCRIPTION:
SHESKY BRANCH 6 0
END DESCRIPTION:
XS GIS Cut Line= 4
      3556267.85     10404320.99      3556481.42     10404076.17
      3556497.04     10403586.59      3556611.62     10402961.62
#Sta/Elev= 30
  4440.5  318.00  4542.5  314.76  4765.1  297.26  4910.0  292.86  4970.0  293.51
  4997.6  285.93  4998.0  285.43  5002.5  285.93  5020.0  291.13  5050.1  293.86
  5090.1  293.40  5130.1  294.24  5280.6  301.49  5361.7  303.61  5372.1  304.94
  5463.6  308.67  5478.1  310.64  5565.2  313.59  5595.7  316.46  5616.1  317.11
  5642.6  316.43  5647.7  317.91  5717.7  322.46  5738.1  323.16  5754.0  320.95
  5759.1  324.01  5799.1  325.27  5807.1  324.04  5819.4  326.79  5890.6  330.61
#Mann=3,-1,0
  4440.5    0.16       0  4997.6    0.07       0  5002.5    0.16       0
Bank Sta=4997.6,5002.5
Exp/Cntr=0.3,0.1

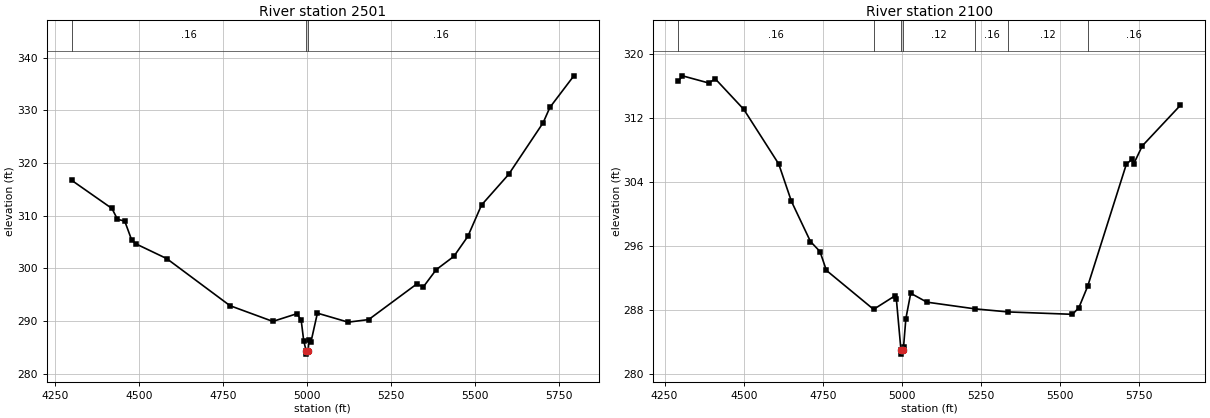
Type RM Length L Ch R = 1,2501,401,401,401
BEGIN DESCRIPTION:
SHESKY BRANCH 5 0
END DESCRIPTION:
XS GIS Cut Line= 3
      3556742.11     10404691.62      3556942.11     10404041.64
      3556792.10     10403241.63
#Sta/Elev= 30
  4299.0  316.68  4418.6  311.34  4435.0  309.29  4456.6  308.95  4476.8  305.43
  4489.3  304.64  4581.5  301.83  4769.8  292.89  4897.3  289.90  4968.6  291.36
  4981.6  290.17  4989.2  286.22  4996.9  284.19  4997.2  283.69  5001.9  284.19
  5005.3  286.45  5010.4  285.91  5029.9  291.47  5121.5  289.76  5182.5  290.25
  5325.0  296.98  5345.3  296.47  5383.5  299.73  5436.0  302.25  5477.6  306.05
  5518.3  312.00  5598.8  317.80  5701.4  327.60  5721.8  330.54  5793.0  336.53
#Mann=3,-1,0
  4299.0    0.16       0  4996.9    0.07       0  5001.9    0.16       0
Bank Sta=4996.9,5001.9
Exp/Cntr=0.3,0.1

Type RM Length L Ch R = 1,2100,0,0,0
BEGIN DESCRIPTION:
SHESKY BRANCH 1 0
END DESCRIPTION:
XS GIS Cut Line= 4
      3557115.85     10404898.14      3557157.51     10404398.18
      3557365.84     10403960.68      3557407.51     10403361.69
#Sta/Elev= 30
  4293.1  316.57  4306.4  317.25  4389.9  316.35  4410.0  316.88  4500.3  313.06
  4610.7  306.24  4650.8  301.58  4711.0  296.56  4741.1  295.31  4761.2  292.96
  4910.5  288.09  4976.8  289.75  4982.4  289.39  4997.0  283.00  4997.4  282.50
  5002.1  283.00  5005.1  283.39  5012.5  286.94  5027.8  290.10  5078.9  288.99
  5231.4  288.15  5335.6  287.77  5539.0  287.47  5559.1  288.29  5587.2  290.99
  5709.4  306.23  5727.2  306.83  5732.2  306.23  5759.6  308.50  5879.8  313.56
#Mann=7,-1,0
  4293.1    0.16       0  4910.5    0.12       0  4997.0    0.07       0
  5002.1    0.12       0  5231.4    0.16       0  5335.6    0.12       0
  5587.2    0.16       0
Bank Sta=4997,5002.1
Exp/Cntr=0.3,0.1

Chan Stop Cuts=-1