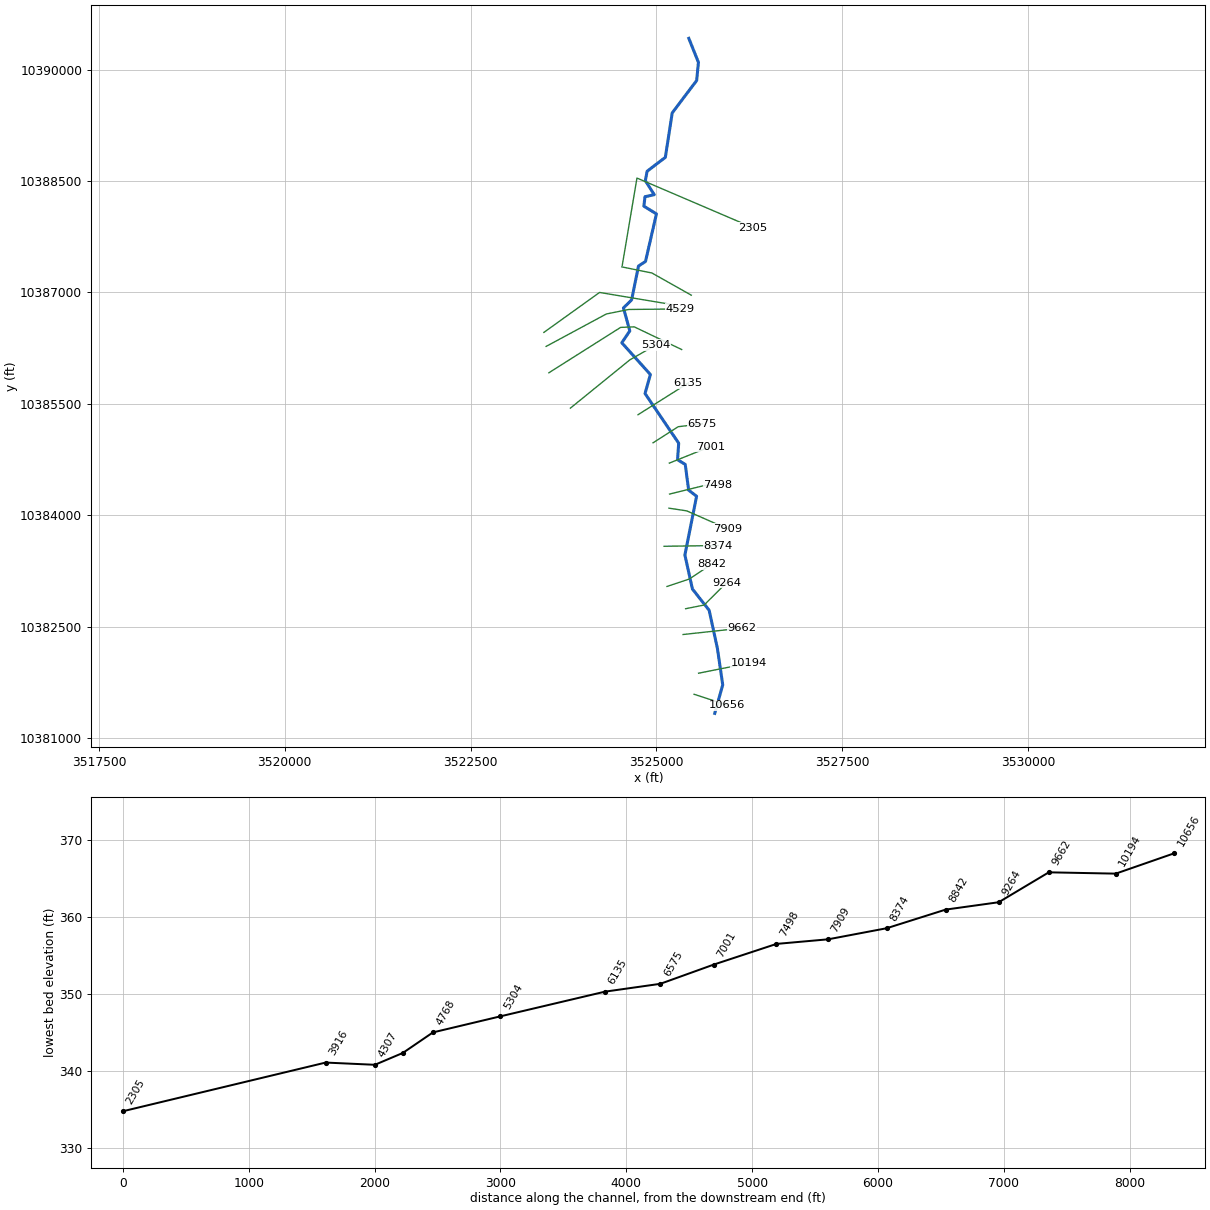
--- SOUTH MINERAL CR TRIB 1.prj (project) ---

Proj Title=SOUTH MINERAL CR TRIB 1 Base Level Engineering
Current Plan=p01
Default Exp/Contr=0.3,0.1
English Units
Geom File=g01
Flow File=f01
Plan File=p01
Y Axis Title=Elevation
X Axis Title(PF)=Main Channel Distance
X Axis Title(XS)=Station
BEGIN DESCRIPTION:
SOUTH MINERAL CR TRIB 1
END DESCRIPTION:
DSS Export Rating Curves= 0
DSS Export Rating Curve Sorted= 0
DSS Export Volume Flow Curves= 0
DXF OffsetX= 0
DXF OffsetY= 0
DXF ScaleX= 1
DXF ScaleY= 10

--- SOUTH MINERAL CR TRIB 1.p01 (plan) ---

Plan Title=Multiple Run
Short Identifier=Multiple
Geom File=g01
Flow File=f01
Subcritical Flow
K Sum by GR= 0
Std Step Tol= 0.01
Critical Tol= 0.01
Num of Std Step Trials= 20
Max Error Tol= 0.3
Flow Tol Ratio= 0.001
Split Flow NTrial= 30
Split Flow Tol= 0.02
Split Flow Ratio= 0.02
Log Output Level= 0
Friction Slope Method= 1
Unsteady Friction Slope Method= 2
Unsteady Bridges Friction Slope Method= 1
Parabolic Critical Depth
Global Vel Dist=  1 , 1 , 1
Global Log Level= 0
CheckData=True
Encroach Param= -1, 0, 0, 0
BEGIN DESCRIPTION:
Multiple Run
END DESCRIPTION:

--- SOUTH MINERAL CR TRIB 1.f01 (steady flow) ---

Flow Title=Multiple
Number of Profiles=7
Profile Names=10-year,25-year,50-year,1pct_min,100-year,1pct_plu,500-year
River Rch & RM= SOUTH MINERAL CR,Reach-1,10656
    1428    1998    2474    2231    3018    4081    4482
River Rch & RM= SOUTH MINERAL CR,Reach-1,4529
    1484    2077    2573    2320    3138    4244    4660
Boundary for River Rch & Prof#=SOUTH MINERAL CR,Reach-1,1
Up Type=0
Dn Type=3
Dn Slope=0.005
Boundary for River Rch & Prof#=SOUTH MINERAL CR,Reach-1,2
Up Type=0
Dn Type=3
Dn Slope=0.005
Boundary for River Rch & Prof#=SOUTH MINERAL CR,Reach-1,3
Up Type=0
Dn Type=3
Dn Slope=0.005
Boundary for River Rch & Prof#=SOUTH MINERAL CR,Reach-1,4
Up Type=0
Dn Type=3
Dn Slope=0.005
Boundary for River Rch & Prof#=SOUTH MINERAL CR,Reach-1,5
Up Type=0
Dn Type=3
Dn Slope=0.005
Boundary for River Rch & Prof#=SOUTH MINERAL CR,Reach-1,6
Up Type=0
Dn Type=3
Dn Slope=0.005
Boundary for River Rch & Prof#=SOUTH MINERAL CR,Reach-1,7
Up Type=0
Dn Type=3
Dn Slope=0.005

--- SOUTH MINERAL CR TRIB 1.g01 (geometry) ---

Geom Title=Existing Conditions
Program Version=4.10

River Reach=SOUTH MINERAL CR,Reach-1
Reach XY= 30
      3525783.88     10381333.01      3525891.41     10381716.89
       3525820.1     10382205.81      3525708.95     10382720.28
      3525483.65     10383007.28      3525382.54     10383465.33
      3525539.87     10384255.96      3525433.13      10384337.2
      3525387.06     10384684.27      3525283.95       10384747.
      3525298.93     10384970.31      3524846.44     10385638.77
      3524918.24     10385894.55      3524533.96     10386321.59
      3524641.58     10386481.94      3524556.07     10386790.75
      3524666.01     10386898.64      3524758.31     10387354.38
      3524852.35     10387416.05      3524999.72     10388056.35
      3524830.45     10388160.51      3524845.56     10388287.25
      3524969.86     10388315.03      3524850.42     10388503.92
      3524874.72       10388631.      3525119.43      10388817.4
      3525212.02     10389415.53       3525540.8     10389852.17
      3525564.54     10390096.57      3525434.95     10390419.62

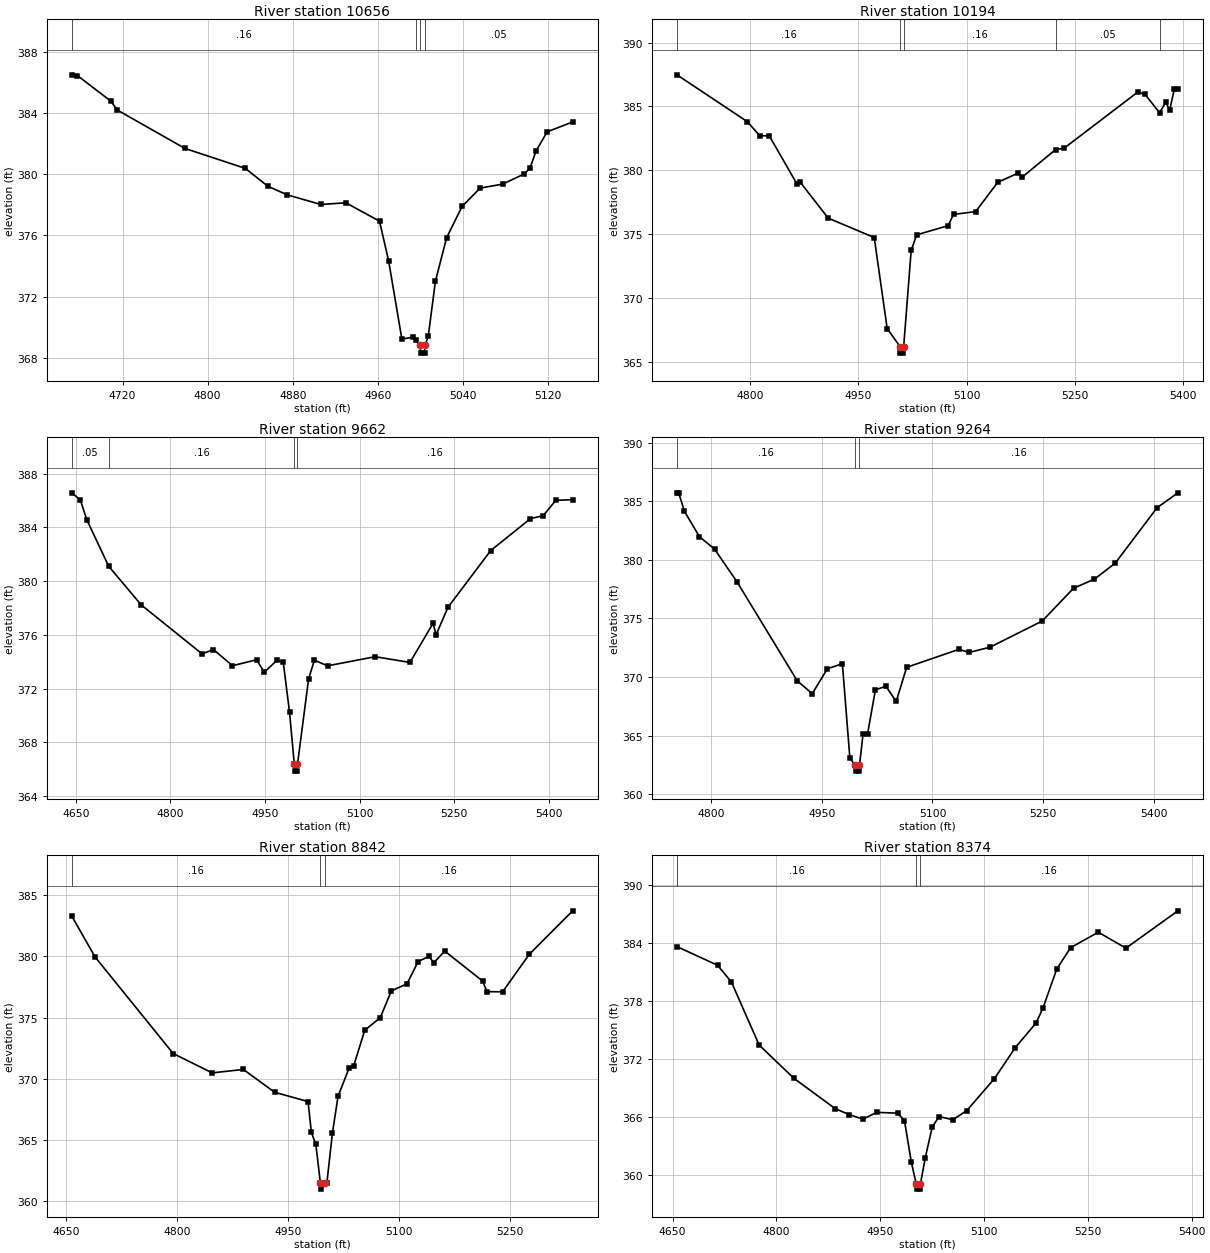
Type RM Length L Ch R = 1 ,10656   ,462,462,462
BEGIN DESCRIPTION:
SOUTH MINERAL CR TRIB 1 3 0
END DESCRIPTION:
XS GIS Cut Line= 2
      3525506.95     10381589.95      3525954.82     10381444.13
#Sta/Elev= 30
  4672.2  386.49  4677.6  386.44  4709.2  384.76  4714.8   384.2  4778.7  381.68
  4835.4  380.38  4856.4  379.22  4874.4  378.66  4906.4  378.02    4930  378.13
  4961.6  376.93  4970.2  374.33  4982.6  369.23  4993.1  369.35  4995.6  369.15
  4999.9  368.81  5000.2  368.31    5004  368.31  5004.3  368.81  5007.4   369.4
  5014.2  373.02  5024.7  375.85  5039.3   377.9  5056.2  379.09  5077.3  379.35
  5097.9  380.02  5103.2  380.42  5108.8  381.52  5119.3  382.77  5143.2  383.41
#Mann= 4 ,-1 , 0
  4672.2     .16       0  4995.6     .05       0  4999.9     .04       0
  5004.3     .05       0
Bank Sta=4999.9,5004.3
XS Rating Curve= 0 ,0
Exp/Cntr=0.3,0.1

Type RM Length L Ch R = 1 ,10194   ,532,532,532
BEGIN DESCRIPTION:
SOUTH MINERAL CR TRIB 1 2 0
END DESCRIPTION:
XS GIS Cut Line= 2
      3525566.81     10381873.81      3526246.55     10382009.24
#Sta/Elev= 30
  4699.3  387.47  4796.5  383.81    4814   382.7  4827.1  382.69    4865  378.96
  4870.1  379.05  4908.6  376.25  4972.3  374.73  4990.2   367.6  5008.2  366.18
  5008.5  365.68  5012.6  365.68    5013  366.18  5023.4  373.72    5031  374.94
  5074.5  375.66    5082  376.54  5112.6  376.76  5143.1  379.05  5171.5  379.78
  5176.6  379.44  5223.1  381.61  5234.9  381.72  5336.9  386.12  5347.1  385.93
  5367.1   384.5  5375.8  385.34  5380.9  384.68  5387.6  386.36  5392.4  386.36
#Mann= 5 ,-1 , 0
  4699.3     .16       0  5008.2     .07       0    5013     .16       0
  5223.1     .05       0  5367.1     .08       0
Bank Sta=5008.2,5013
XS Rating Curve= 0 ,0
Exp/Cntr=0.3,0.1

Type RM Length L Ch R = 1 ,9662    ,398,398,398
BEGIN DESCRIPTION:
SOUTH MINERAL CR TRIB 1 14 0
END DESCRIPTION:
XS GIS Cut Line= 2
      3525358.49     10382394.65      3526148.65     10382480.42
#Sta/Elev= 30
  4643.3  386.57  4656.9  386.05  4667.1  384.58    4702   381.1  4753.5  378.23
  4850.1  374.58  4868.2   374.9  4898.4   373.7  4936.7  374.14  4948.7  373.21
  4968.8  374.09  4978.9  373.97  4988.9  370.24  4996.5  366.35  4996.9  365.85
  5001.1  365.85  5001.5  366.35  5019.1   372.7  5028.3  374.11  5049.3  373.69
  5124.9  374.37    5180  373.94  5216.5  376.85  5221.5  376.01  5240.4  378.06
  5308.1  382.27  5371.2  384.65  5391.3  384.87  5411.4  386.01  5438.1  386.06
#Mann= 4 ,-1 , 0
  4643.3     .05       0    4702     .16       0  4996.5     .07       0
  5001.5     .16       0
Bank Sta=4996.5,5001.5
XS Rating Curve= 0 ,0
Exp/Cntr=0.3,0.1

Type RM Length L Ch R = 1 ,9264    ,422,422,422
BEGIN DESCRIPTION:
SOUTH MINERAL CR TRIB 1 13 0
END DESCRIPTION:
XS GIS Cut Line= 3
      3525392.14     10382741.65      3525642.11     10382791.64
      3525942.12     10383091.66
#Sta/Elev= 30
  4753.5  385.68    4756  385.68  4763.7  384.13  4784.1  381.96  4804.5  380.91
  4835.1   378.1  4916.6  369.67    4937  368.57  4957.4  370.69  4977.8  371.13
    4988  363.05  4995.4  362.46  4995.9  361.96  5000.6  361.96    5001  362.46
  5005.9  365.15    5012  365.15  5022.6  368.89  5036.7  369.21  5050.8  367.91
    5065  370.82  5135.7  372.35  5149.8  372.09  5178.1  372.54  5248.8  374.77
  5291.3  377.57  5319.5  378.34  5347.8  379.71  5404.4  384.43  5432.7  385.71
#Mann= 3 ,-1 , 0
  4753.5     .16       0  4995.4     .07       0    5001     .16       0
Bank Sta=4995.4,5001
XS Rating Curve= 0 ,0
Exp/Cntr=0.3,0.1

Type RM Length L Ch R = 1 ,8842    ,468,468,468
BEGIN DESCRIPTION:
SOUTH MINERAL CR TRIB 1 12 0
END DESCRIPTION:
XS GIS Cut Line= 3
      3525142.08     10383041.63      3525442.11     10383141.64
       3525742.1     10383341.64
#Sta/Elev= 30
  4657.6   383.3  4689.2  379.95  4794.7  372.07  4847.4  370.49  4889.5  370.77
  4931.7  368.91  4976.9  368.15  4981.4  365.63  4987.4  364.66  4993.6   361.5
    4994     361  4999.2   361.5  5002.4  361.54  5009.9   365.6  5017.4  368.57
  5032.4  370.89  5038.5  371.05  5053.5  373.97  5074.5     375  5089.5  377.19
  5110.6  377.76  5125.6  379.58  5140.6  380.01  5146.6  379.47  5161.6  380.43
  5212.7  377.99  5218.7  377.12  5239.8  377.11  5275.8  380.17  5334.4  383.72
#Mann= 3 ,-1 , 0
  4657.6     .16       0  4993.6     .07       0  4999.2     .16       0
Bank Sta=4993.6,4999.2
XS Rating Curve= 0 ,0
Exp/Cntr=0.3,0.1

Type RM Length L Ch R = 1 ,8374    ,465,465,465
BEGIN DESCRIPTION:
SOUTH MINERAL CR TRIB 1 18 0
END DESCRIPTION:
XS GIS Cut Line= 2
       3525103.3     10383582.15      3525827.12     10383592.56
#Sta/Elev= 30
  4656.2  383.61    4715  381.68    4735  379.95    4775  373.45    4825  370.03
    4885  366.88    4905  366.28    4925   365.8    4945   366.5    4975  366.42
    4985  365.65    4995  361.34  5002.1  359.08  5002.6  358.58  5007.5  358.58
    5008  359.08    5015  361.79    5025  364.96    5035  366.07    5055  365.74
    5075  366.68  5115.1  369.99  5145.1  373.18  5175.1  375.72  5185.1  377.26
  5205.1  381.29  5225.1   383.5  5265.1  385.09  5305.1  383.45  5380.1   387.3
#Mann= 3 ,-1 , 0
  4656.2     .16       0  5002.1     .07       0    5008     .16       0
Bank Sta=5002.1,5008
XS Rating Curve= 0 ,0
Exp/Cntr=0.3,0.1

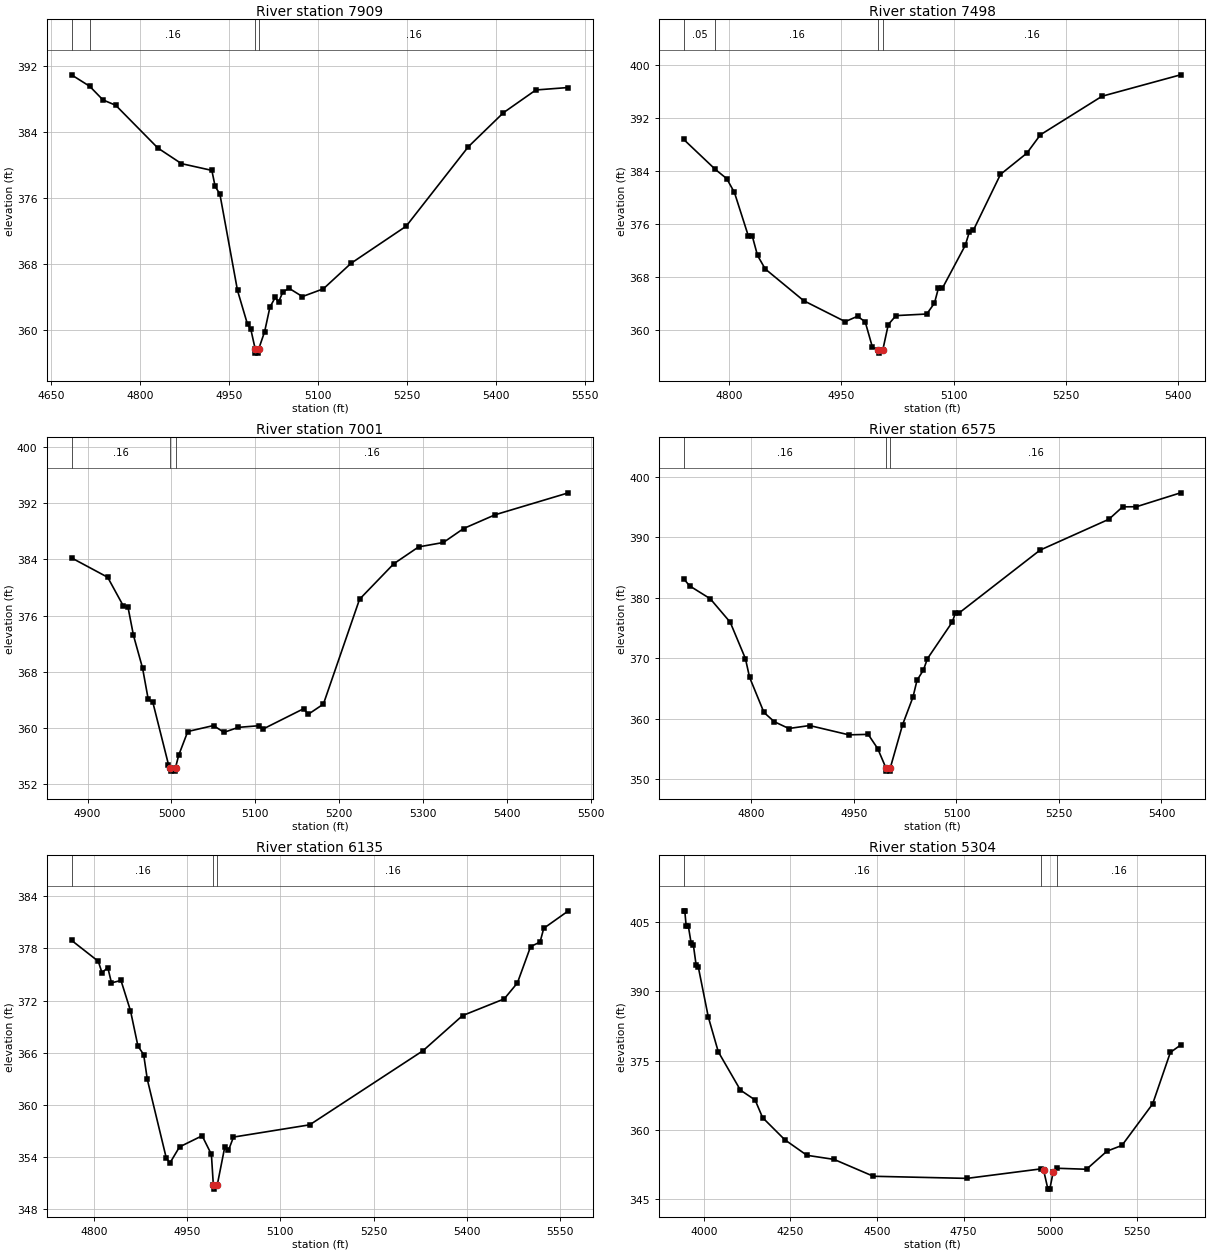
Type RM Length L Ch R = 1 ,7909    ,411,411,411
BEGIN DESCRIPTION:
SOUTH MINERAL CR TRIB 1 28 0
END DESCRIPTION:
XS GIS Cut Line= 3
      3525168.41     10384095.16      3525407.96     10384058.71
      3525952.25     10383819.12
#Sta/Elev= 30
  4684.4  390.95    4715  389.56  4737.4   387.9  4758.9  387.25  4829.8  382.06
  4869.6  380.16  4920.8  379.34  4926.3   377.4  4934.3  376.47    4964  364.75
  4980.9  360.63  4986.4  360.05  4993.8  357.64  4994.3  357.14  4999.3  357.14
  4999.7  357.64  5009.7  359.75  5018.6  362.72  5027.6  363.91  5033.1  363.33
  5040.5  364.59    5051  365.01  5073.3  364.01  5108.6  364.95  5155.2  368.05
  5248.1  372.56  5352.8  382.21    5412  386.35  5466.6  389.11  5521.4  389.41
#Mann= 4 ,-1 , 0
  4684.4     .05       0    4715     .16       0  4993.8     .07       0
  4999.7     .16       0
Bank Sta=4993.8,4999.7
XS Rating Curve= 0 ,0
Exp/Cntr=0.3,0.1

Type RM Length L Ch R = 1 ,7498    ,497,497,497
BEGIN DESCRIPTION:
SOUTH MINERAL CR TRIB 1 9 0
END DESCRIPTION:
XS GIS Cut Line= 3
      3525176.19     10384285.27      3525642.34     10384399.86
      3525827.19     10384402.46
#Sta/Elev= 30
  4738.9  388.78  4781.3  384.25  4796.5  382.86  4806.8  380.78  4825.3  374.26
  4830.5  374.28  4837.7  371.28    4848  369.24  4899.5  364.45  4955.1  361.29
  4971.5   362.1  4981.8  361.26  4991.5  357.42  4999.4  357.04  4999.9  356.54
  5005.4  357.04  5012.7  360.85    5023   362.2  5064.2  362.44  5074.5  364.09
  5079.7  366.31  5084.9  366.29  5115.7   372.8  5121.3  374.87  5126.4  375.04
  5162.8   383.5  5198.1   386.7  5216.2  389.47  5298.7  395.29  5403.8  398.52
#Mann= 4 ,-1 , 0
  4738.9     .05       0  4781.3     .16       0  4999.4     .07       0
  5005.4     .16       0
Bank Sta=4999.4,5005.4
XS Rating Curve= 0 ,0
Exp/Cntr=0.3,0.1

Type RM Length L Ch R = 1 ,7001    ,426,426,426
BEGIN DESCRIPTION:
SOUTH MINERAL CR TRIB 1 8 0
END DESCRIPTION:
XS GIS Cut Line= 2
      3525173.58     10384701.93      3525723.07     10384923.29
#Sta/Elev= 30
  4880.8  384.22  4923.9  381.46  4942.7  377.35  4948.1  377.23  4954.7  373.17
  4965.5  368.53  4972.3  364.06  4977.7  363.68  4996.4  354.79  4998.8  354.36
  4999.3  353.86  5004.3  353.86  5004.8  354.36  5008.6  356.13  5019.4   359.5
  5050.1  360.35  5062.5  359.38  5079.7  360.09  5103.9  360.32  5109.3  359.86
  5157.6  362.75    5163  361.95  5181.1   363.4  5224.2  378.33    5265  383.38
  5294.6  385.78  5324.1  386.41  5348.3   388.4  5385.9  390.36  5473.2  393.48
#Mann= 3 ,-1 , 0
  4880.8     .16       0  4998.8     .07       0  5004.8     .16       0
Bank Sta=4998.8,5004.8
XS Rating Curve= 0 ,0
Exp/Cntr=0.3,0.1

Type RM Length L Ch R = 1 ,6575    ,440,440,440
BEGIN DESCRIPTION:
SOUTH MINERAL CR TRIB 1 7 0
END DESCRIPTION:
XS GIS Cut Line= 3
      3524954.81     10384975.36      3525292.11     10385191.64
      3525616.29     10385230.58
#Sta/Elev= 30
  4700.8  383.17  4709.5  381.99  4739.7  379.86  4768.9  375.98  4791.2  369.95
  4797.2  366.88  4818.3  361.05  4833.5  359.52  4854.7   358.4  4885.1  358.89
  4942.6  357.35  4970.8  357.43  4984.8  355.07  4996.9  351.85  4997.4  351.35
  5002.6  351.35  5003.1  351.85  5021.2  359.04  5036.4   363.6  5042.3  366.38
  5051.6  368.05  5057.5  369.94  5093.9  376.01  5098.5  377.52    5104  377.52
  5222.3   387.9  5323.1  393.01  5343.2  395.06  5363.3  395.08    5428  397.38
#Mann= 3 ,-1 , 0
  4700.8     .16       0  4996.9     .07       0  5003.1     .16       0
Bank Sta=4996.9,5003.1
XS Rating Curve= 0 ,0
Exp/Cntr=0.3,0.1

Type RM Length L Ch R = 1 ,6135    ,831,831,831
BEGIN DESCRIPTION:
SOUTH MINERAL CR TRIB 1 6 0
END DESCRIPTION:
XS GIS Cut Line= 2
      3524751.69     10385352.96      3525427.99     10385779.55
#Sta/Elev= 30
  4763.9  378.92    4807  376.51  4812.9   375.2  4822.3  375.79  4828.2  374.03
  4843.5  374.31  4858.8  370.83  4870.8  366.77    4880  365.79  4885.9  362.93
  4916.5  353.87  4922.4  353.35  4937.7  355.18  4974.1  356.46    4989  354.32
  4992.1  350.83  4992.6  350.33  4998.5  350.83  5010.6   355.2  5016.5  354.79
  5024.5  356.31  5147.2  357.72  5329.6  366.24  5393.1  370.27  5460.2  372.19
  5481.4  374.02  5502.6  378.19  5517.9  378.73  5523.8   380.3  5563.5  382.31
#Mann= 3 ,-1 , 0
  4763.9     .16       0  4992.1     .07       0  4998.5     .16       0
Bank Sta=4992.1,4998.5
XS Rating Curve= 0 ,0
Exp/Cntr=0.3,0.1

Type RM Length L Ch R = 1 ,5304    ,536,536,536
BEGIN DESCRIPTION:
SOUTH MINERAL CR TRIB 1 5 0
END DESCRIPTION:
XS GIS Cut Line= 3
      3523842.09     10385441.63      3524642.11     10386091.64
       3524992.1     10386291.64
#Sta/Elev= 30
  3942.2   407.5  3945.4   407.5  3949.4  404.23  3955.8  404.12  3963.8  400.47
  3970.2  400.09  3978.1  395.75  3984.6  395.25  4013.3  384.46  4042.1  376.91
    4106   368.6  4148.4  366.46  4169.9  362.64  4233.9  357.84  4297.8  354.46
  4376.1  353.57  4489.6  349.91  4759.6  349.45    4973  351.51  4980.9  351.22
  4993.3  347.12  4998.7  347.12  5008.3  350.76  5018.3  351.65  5104.7  351.43
  5163.7  355.36  5206.9   356.6  5295.5   365.6  5346.6  376.78  5376.1  378.37
#Mann= 3 ,-1 , 0
  3942.2     .16       0    4973     .12       0  5018.3     .16       0
Bank Sta=4980.9,5008.3
XS Rating Curve= 0 ,0
Exp/Cntr=0.3,0.1

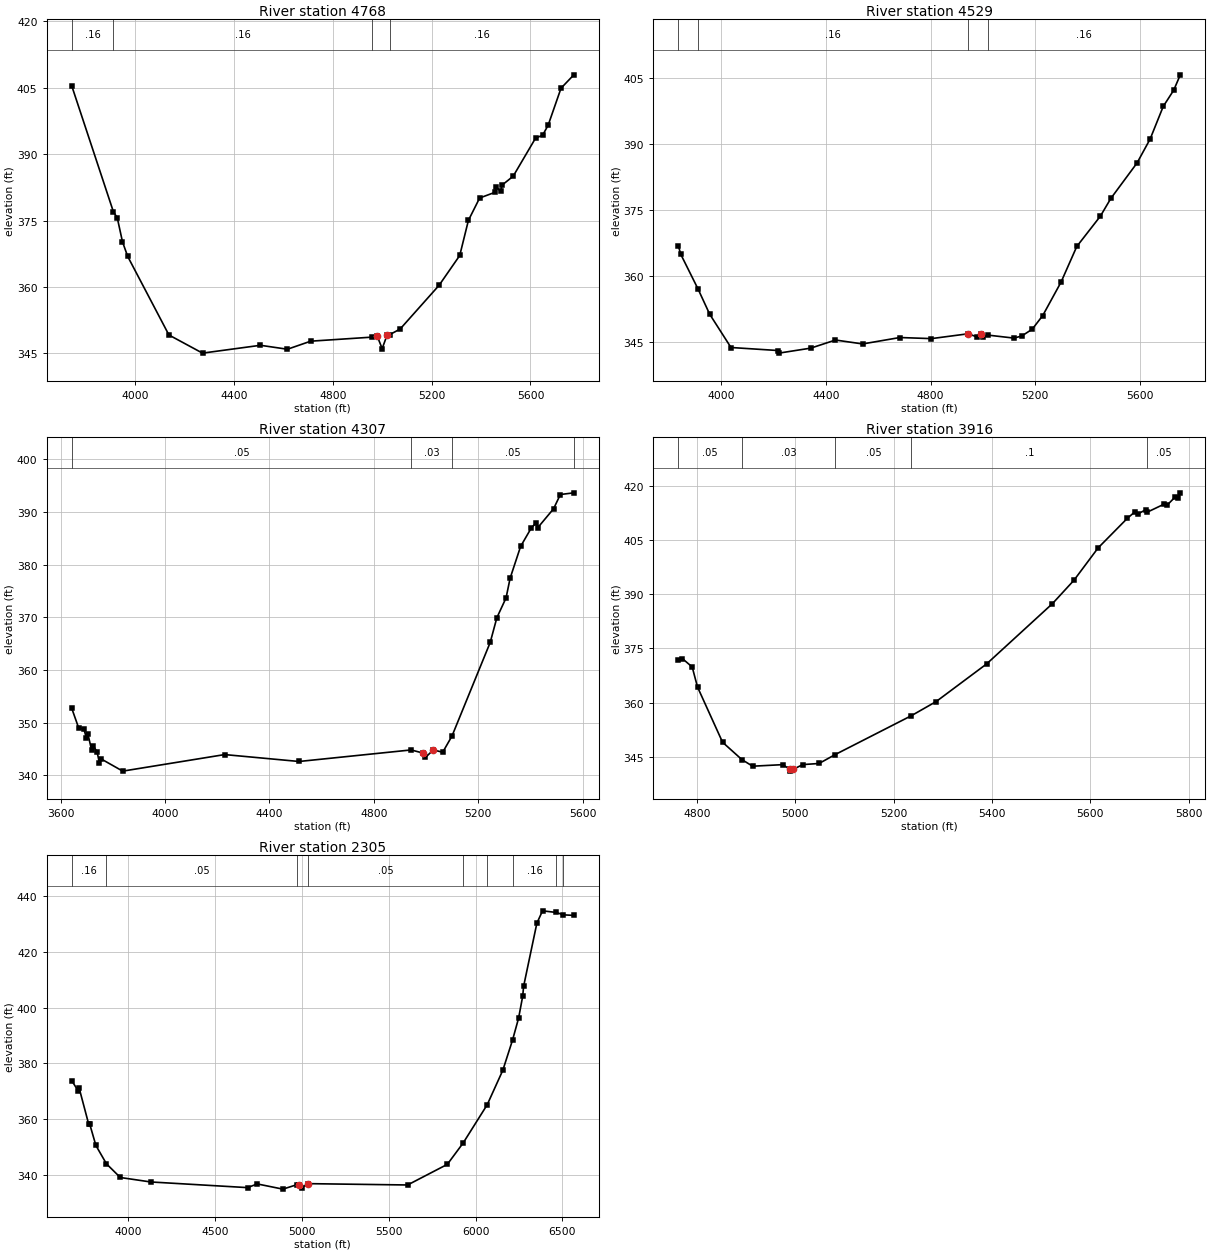
Type RM Length L Ch R = 1 ,4768    ,239,239,239
BEGIN DESCRIPTION:
SOUTH MINERAL CR TRIB 1 31 0
END DESCRIPTION:
XS GIS Cut Line= 4
      3523552.54     10385917.55      3524517.79     10386528.64
      3524701.82     10386535.59      3525338.91     10386230.89
#Sta/Elev= 30
  3742.9  405.43  3911.7  376.94    3927  375.65  3948.2   370.2  3969.4  366.88
  4136.3  349.13  4272.3  345.03  4506.7   346.8  4616.1  345.91  4710.2  347.73
  4959.7  348.65  4979.7  348.84  4999.7  346.06  5019.7  349.13  5029.8   349.2
  5072.4  350.48  5229.9  360.35  5313.7   367.1  5348.8  375.04  5394.2  380.09
  5456.6  381.39  5462.2  382.51  5479.3  381.58  5484.9     383  5530.2  385.03
  5620.9  393.65  5649.1  394.27  5671.8  396.57  5723.8  404.92  5775.7  407.94
#Mann= 4 ,-1 , 0
  3742.9     .16       0  3911.7     .16       0  4959.7     .12       0
  5029.8     .16       0
Bank Sta=4979.7,5019.7
XS Rating Curve= 0 ,0
Exp/Cntr=0.3,0.1

Type RM Length L Ch R = 1 ,4529    ,222,222,222
BEGIN DESCRIPTION:
Mapping XS 59b34019
END DESCRIPTION:
XS GIS Cut Line= 4
      3523516.37     10386272.99      3524325.85      10386709.2
       3524627.5     10386769.96      3525317.34     10386776.47
#Sta/Elev= 30
  3836.4  366.83  3846.3  364.81    3912  356.95  3956.5  351.21  4037.8  343.64
  4217.8  342.95  4220.7  342.36  4342.7   343.5  4436.8  345.34  4540.6  344.45
  4682.6  345.91  4803.1  345.66  4943.2  346.76  4976.5  346.06    4994  346.75
  4999.1  346.03  5017.3  346.47  5118.2  345.78  5148.2  346.26  5188.2  347.81
  5228.2  350.91  5298.2  358.53  5358.3  366.63  5448.3  373.52  5488.3  377.56
  5588.3  385.62  5638.3  391.07  5688.3  398.48  5728.3  402.18  5753.5  405.67
#Mann= 4 ,-1 , 0
  3836.4     .16       0    3912     .16       0  4943.2     .12       0
  5017.3     .16       0
Bank Sta=4943.2,4994
XS Rating Curve= 0 ,0
Exp/Cntr=0.3,0.1

Type RM Length L Ch R = 1 ,4307    ,391,391,391
BEGIN DESCRIPTION:
SOUTH MINERAL CR TRIB 1 4 0
END DESCRIPTION:
XS GIS Cut Line= 3
      3523486.12     10386461.37      3524234.81     10386999.13
      3525223.06     10386833.77
#Sta/Elev= 30
  3642.8  352.73  3668.8  349.07  3689.7  348.74  3698.3  347.18  3704.4   347.9
  3719.2  344.74  3725.3  345.65    3740  344.43  3748.6   342.4  3754.8  343.15
    3838  340.82  4228.7  343.96  4513.6  342.65  4943.1  344.84  4987.7  344.26
  4997.8  343.41  5028.3  344.85  5064.1   344.4  5099.8  347.49  5246.2  365.25
  5271.6  369.92  5306.9  373.69  5322.3   377.4  5362.6  383.45  5403.4  386.94
  5423.3  387.99  5428.4  387.01  5489.1  390.61  5514.9   393.3  5566.6  393.62
#Mann= 4 ,-1 , 0
  3642.8     .05       0  4943.1     .03       0  5099.8     .05       0
  5566.6     .16       0
Bank Sta=4987.7,5028.3
XS Rating Curve= 0 ,0
Exp/Cntr=0.3,0.1

Type RM Length L Ch R = 1 ,3916    ,1611,1611,1611
BEGIN DESCRIPTION:
SOUTH MINERAL CR TRIB 1 24 0
END DESCRIPTION:
XS GIS Cut Line= 3
      3524533.73      10387343.2      3524939.28      10387260.7
      3525468.78      10386962.2
#Sta/Elev= 30
  4761.6  371.93  4770.1  372.19    4790  369.88  4800.8  364.35  4851.8  349.09
  4891.2  344.29    4913  342.47  4974.2   342.9  4989.1  341.61  4989.6  341.11
  4995.6  341.61  5015.1  342.92  5048.1  343.22  5081.1  345.69  5236.1  356.43
  5286.6  360.34  5389.2  370.73  5523.1  387.38  5566.9  393.84    5616  402.77
  5675.3  410.92  5691.2  412.78  5696.9  412.14  5712.8  413.32  5716.5  412.68
  5750.4  414.87  5756.2  414.55  5772.1  416.74  5777.8  416.44  5783.3  417.99
#Mann= 5 ,-1 , 0
  4761.6     .05       0  4891.2     .03       0  5081.1     .05       0
  5236.1      .1       0  5716.5     .05       0
Bank Sta=4989.1,4995.6
XS Rating Curve= 0 ,0
Exp/Cntr=0.3,0.1

Type RM Length L Ch R = 1 ,2305    ,0,0,0
BEGIN DESCRIPTION:
SOUTH MINERAL CR TRIB 1 10 0
END DESCRIPTION:
XS GIS Cut Line= 3
       3524540.2     10387364.89      3524737.69     10388538.96
      3526297.53     10387870.77
#Sta/Elev= 30
    3678  373.75  3714.9  370.07    3720   371.2  3775.5  358.09  3780.5  358.31
  3816.7  350.47  3877.5  343.87  3957.2  338.96    4131  337.36    4689  335.32
  4744.5  336.65    4892  334.78  4970.9  336.34  4982.2  336.29    5000  335.31
  5036.6  336.75  5609.3  336.27  5837.8  343.68  5928.6  351.33  6067.1  365.09
  6157.1   377.5  6213.1  388.38  6247.7  396.21  6271.3  404.09  6276.7  407.69
  6352.9  430.35  6385.5  434.78  6465.1  434.19  6504.5  433.34  6565.5  433.14
#Mann= 9 ,-1 , 0
    3678     .16       0  3877.5     .05       0  4970.9     .03       0
  5036.6     .05       0  5928.6     .05       0  6067.1      .1       0
  6213.1     .16       0  6465.1     .05       0  6504.5      .1       0
Bank Sta=4982.2,5036.6
XS Rating Curve= 0 ,0
Exp/Cntr=0.3,0.1

Chan Stop Cuts=-1
Use User Specified Reach Order=0
Composite Channel Slope=5