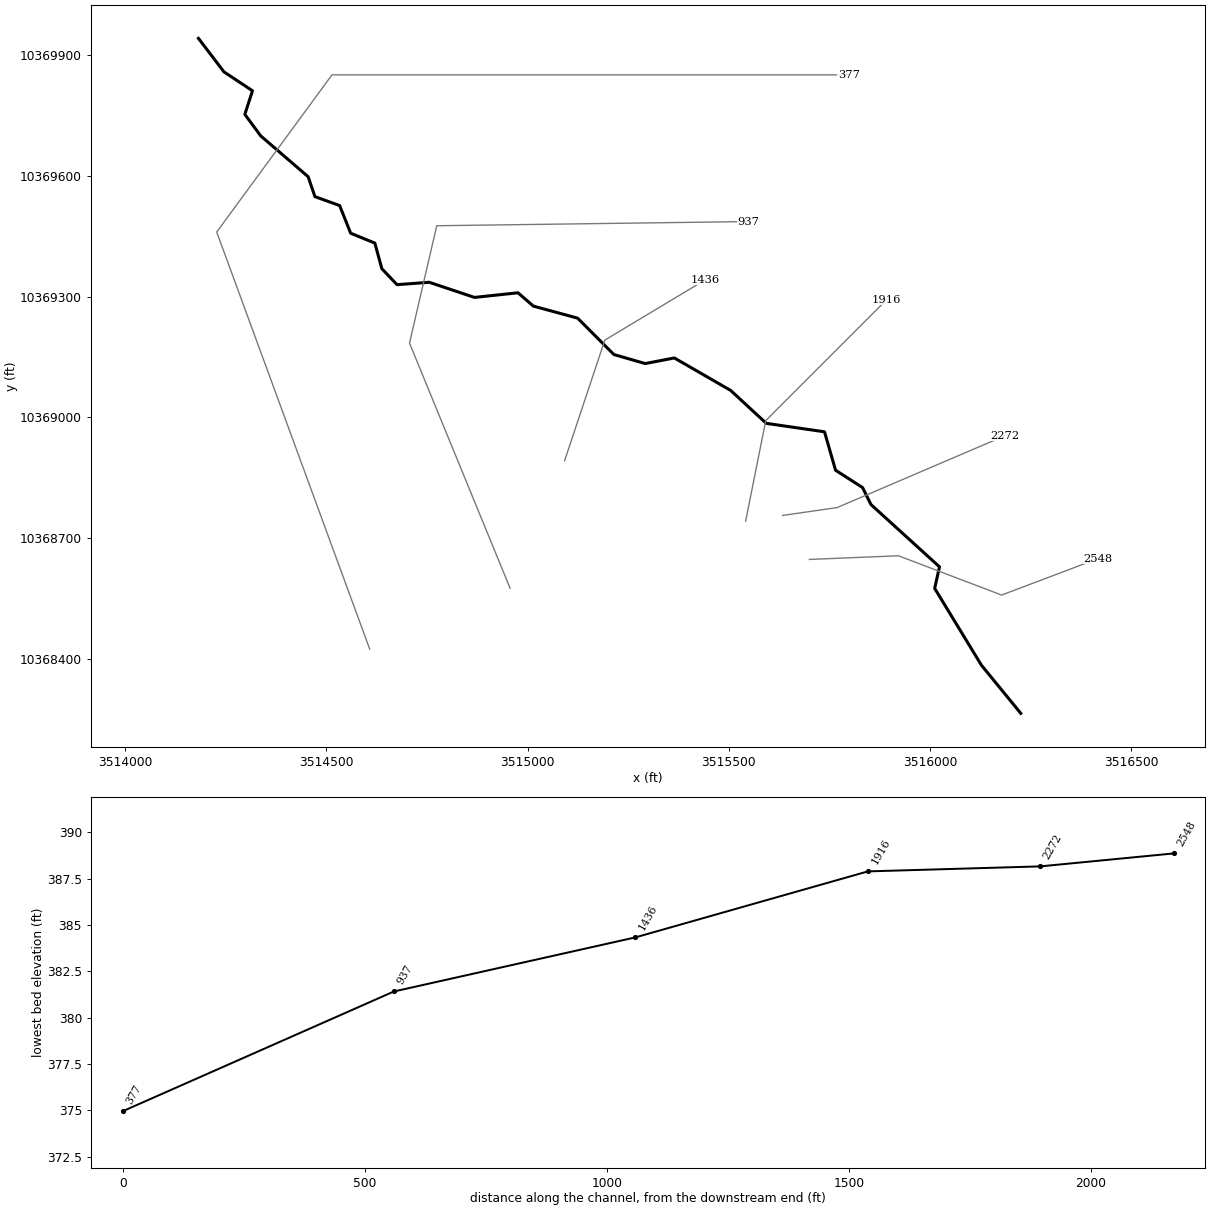
--- SOUTH MINERAL CR TRIB 10.prj (project) ---

Proj Title=SOUTH MINERAL CR TRIB 10 Base Level Engineering
Current Plan=p01
Default Exp/Contr=0.3,0.1
English Units
Geom File=g01
Flow File=f01
Plan File=p01
BEGIN DESCRIPTION:
SOUTH MINERAL CR TRIB 10
END DESCRIPTION:

--- SOUTH MINERAL CR TRIB 10.p01 (plan) ---

Plan Title=Multiple Run
Short Identifier=Multiple
Geom File=g01
Flow File=f01
Subcritical Flow
K Sum by GR= 0
Std Step Tol= 0.01
Critical Tol= 0.01
Num of Std Step Trials= 20
Max Error Tol= 0.3
Flow Tol Ratio= 0.001
Split Flow NTrial= 30
Split Flow Tol= 0.02
Split Flow Ratio= 0.02
Log Output Level= 0
Friction Slope Method= 1
Unsteady Friction Slope Method= 2
Unsteady Bridges Friction Slope Method= 1
Parabolic Critical Depth
Global Vel Dist=  1 , 1 , 1
Global Log Level= 0
CheckData=True
Encroach Param= -1, 0, 0, 0
BEGIN DESCRIPTION:
Multiple Run
END DESCRIPTION:

--- SOUTH MINERAL CR TRIB 10.f01 (steady flow) ---

Flow Title=Multiple
Number of Profiles=7
Profile Names=10-year,25-year,50-year,1pct_min,100-year,1pct_plu,500-year
River Rch & RM= SOUTH MINERAL CR,Reach-1,2548
     581     778     936     823    1113    1505    1569
Boundary for River Rch & Prof#=SOUTH MINERAL CR,Reach-1,1
Up Type=0
Dn Type=3
Dn Slope=0.005
Boundary for River Rch & Prof#=SOUTH MINERAL CR,Reach-1,2
Up Type=0
Dn Type=3
Dn Slope=0.005
Boundary for River Rch & Prof#=SOUTH MINERAL CR,Reach-1,3
Up Type=0
Dn Type=3
Dn Slope=0.005
Boundary for River Rch & Prof#=SOUTH MINERAL CR,Reach-1,4
Up Type=0
Dn Type=3
Dn Slope=0.005
Boundary for River Rch & Prof#=SOUTH MINERAL CR,Reach-1,5
Up Type=0
Dn Type=3
Dn Slope=0.005
Boundary for River Rch & Prof#=SOUTH MINERAL CR,Reach-1,6
Up Type=0
Dn Type=3
Dn Slope=0.005
Boundary for River Rch & Prof#=SOUTH MINERAL CR,Reach-1,7
Up Type=0
Dn Type=3
Dn Slope=0.005

--- SOUTH MINERAL CR TRIB 10.g01 (geometry) ---

Geom Title=Existing Conditions

River Reach=SOUTH MINERAL CR,Reach-1
Reach XY= 30
      3516225.98     10368263.96      3516128.14     10368383.63
      3516011.92     10368574.59      3516023.84     10368628.19
      3515853.56     10368782.97      3515832.73     10368825.13
      3515765.60     10368868.23      3515738.13     10368963.74
      3515593.40     10368984.76      3515504.91     10369066.60
      3515364.87     10369147.29      3515292.43     10369133.33
      3515214.66     10369155.80      3515124.59     10369246.20
      3515014.57     10369276.14      3514976.32     10369309.28
      3514868.25     10369297.74      3514755.84     10369335.35
      3514675.70     10369329.41      3514637.96     10369369.11
      3514620.60     10369432.73      3514560.47     10369457.33
      3514533.12     10369526.00      3514471.66     10369548.24
      3514454.77     10369597.74      3514336.94     10369699.17
      3514297.42     10369752.72      3514316.50     10369811.33
      3514245.55     10369858.32      3514182.11     10369941.64

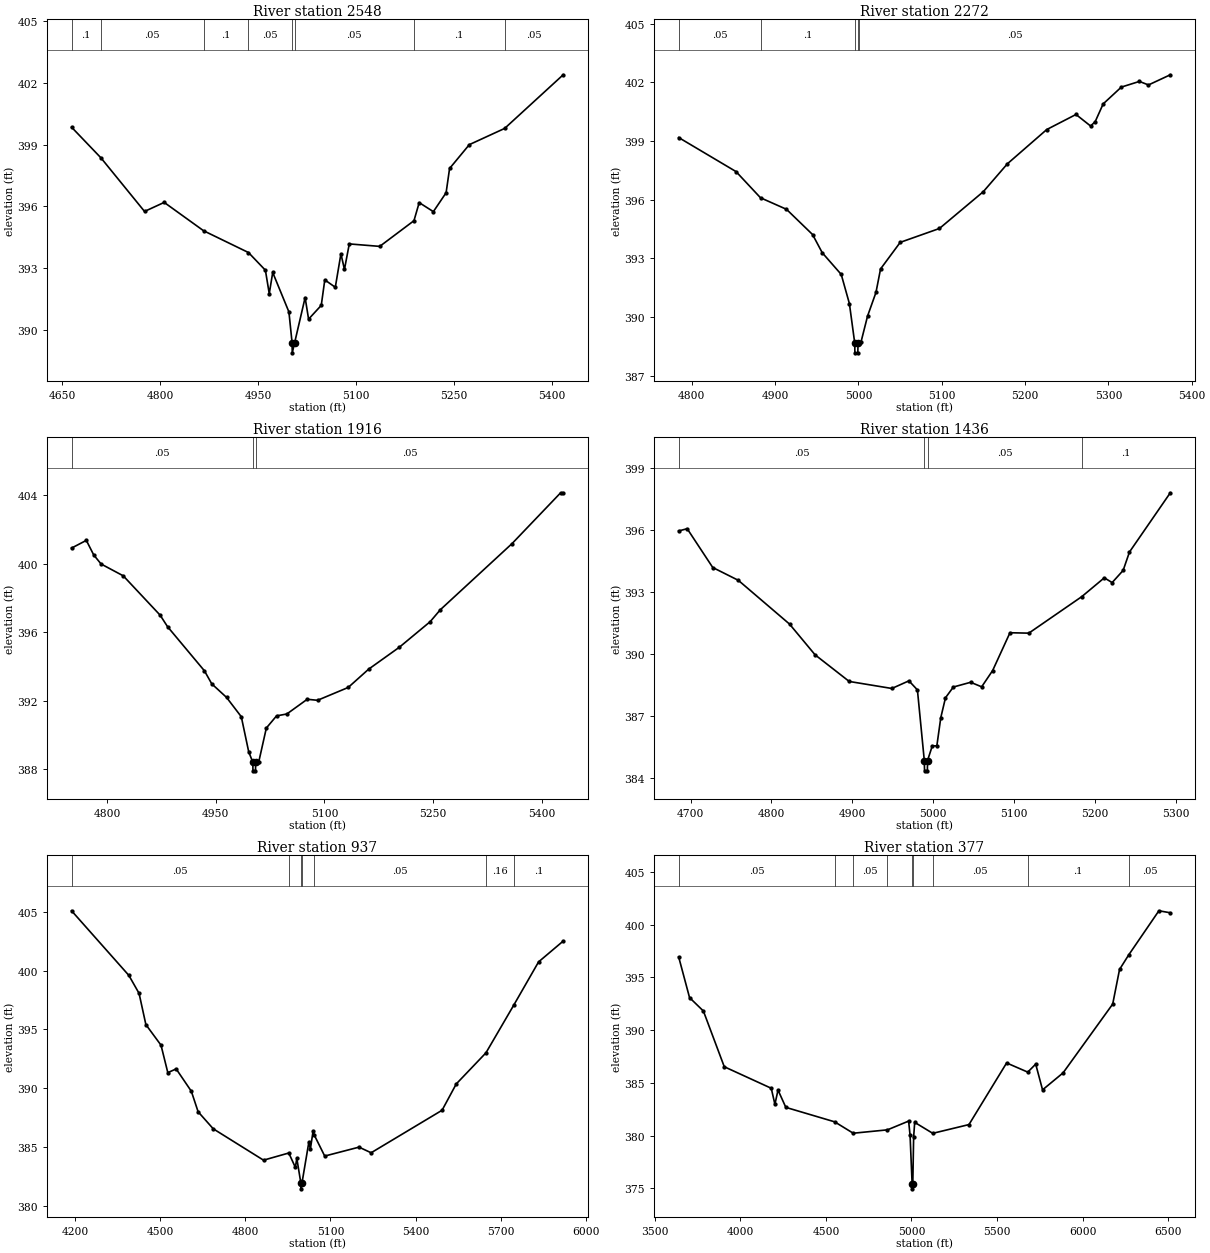
Type RM Length L Ch R = 1,2548,276,276,276
BEGIN DESCRIPTION:
SOUTH MINERAL CR TRIB 10 15 0
END DESCRIPTION:
XS GIS Cut Line= 4
      3515700.47     10368646.54      3515921.86     10368655.65
      3516178.37     10368558.00      3516418.22     10368648.75
#Sta/Elev= 30
  4664.2  399.85  4709.1  398.36  4775.9  395.75  4806.0  396.19  4866.3  394.81
  4935.0  393.75  4960.9  392.89  4966.8  391.75  4972.1  392.78  4996.9  390.86
  5001.7  389.37  5002.0  388.87  5005.7  389.37  5021.7  391.56  5027.0  390.51
  5046.4  391.18  5051.8  392.42  5067.9  392.06  5076.5  393.69  5081.9  392.93
  5089.3  394.17  5135.9  394.05  5188.3  395.30  5196.3  396.18  5218.0  395.74
  5237.5  396.66  5242.8  397.84  5273.0  399.00  5327.1  399.79  5416.7  402.40
#Mann=8,-1,0
  4664.2     0.1       0  4709.1    0.05       0  4866.3     0.1       0
  4935.0    0.05       0  5001.7    0.04       0  5005.7    0.05       0
  5188.3     0.1       0  5327.1    0.05       0
Bank Sta=5001.7,5005.7
Exp/Cntr=0.3,0.1

Type RM Length L Ch R = 1,2272,356,356,356
BEGIN DESCRIPTION:
SOUTH MINERAL CR TRIB 10 25 0
END DESCRIPTION:
XS GIS Cut Line= 3
      3515634.06     10368755.91      3515769.51     10368775.44
      3516186.17     10368953.83
#Sta/Elev= 30
  4784.2  399.18  4853.0  397.44  4882.4  396.10  4913.6  395.51  4944.9  394.22
  4956.5  393.29  4979.3  392.18  4989.1  390.69  4995.5  388.67  4995.7  388.17
  4999.2  388.17  4999.5  388.67  5000.1  388.68  5002.9  388.70  5010.9  390.05
  5021.0  391.26  5026.5  392.46  5050.1  393.82  5097.2  394.53  5149.8  396.41
  5178.8  397.84  5226.0  399.59  5261.1  400.36  5278.6  399.77  5284.1  399.99
  5293.7  400.90  5315.5  401.76  5337.2  402.05  5348.1  401.87  5374.3  402.39
#Mann=5,-1,0
  4784.2    0.05       0  4882.4     0.1       0  4995.5    0.07       0
  4999.5     0.1       0  5000.1    0.05       0
Bank Sta=4995.5,4999.5
Exp/Cntr=0.3,0.1

Type RM Length L Ch R = 1,1916,480,480,480
BEGIN DESCRIPTION:
SOUTH MINERAL CR TRIB 10 5 0
END DESCRIPTION:
XS GIS Cut Line= 3
      3515542.11     10368741.66      3515592.11     10368991.64
      3515892.11     10369291.64
#Sta/Elev= 30
  4750.7  400.91  4771.1  401.36  4781.3  400.51  4791.5  399.98  4822.1  399.29
  4873.1  396.99  4883.3  396.32  4934.3  393.74  4944.4  392.98  4964.8  392.19
  4985.2  391.06  4995.4  389.02  5001.1  388.40  5001.3  387.90  5004.8  387.90
  5005.1  388.40  5009.2  388.40  5019.8  390.40  5033.9  391.11  5048.1  391.22
  5076.3  392.08  5090.5  392.02  5132.9  392.77  5161.2  393.84  5203.6  395.12
  5246.1  396.61  5260.2  397.31  5359.2  401.17  5426.4  404.14  5429.9  404.14
#Mann=3,-1,0
  4750.7    0.05       0  5001.1    0.03       0  5005.1    0.05       0
Bank Sta=5001.1,5005.1
Exp/Cntr=0.3,0.1

Type RM Length L Ch R = 1,1436,499,499,499
BEGIN DESCRIPTION:
SOUTH MINERAL CR TRIB 10 4 0
END DESCRIPTION:
XS GIS Cut Line= 3
      3515092.12     10368891.68      3515192.11     10369191.64
      3515442.08     10369341.63
#Sta/Elev= 30
  4685.3  395.96  4695.8  396.07  4727.4  394.19  4759.0  393.57  4822.3  391.45
  4853.9  389.96  4896.1  388.67  4948.8  388.33  4969.9  388.70  4980.4  388.26
  4988.9  384.84  4989.2  384.34  4992.7  384.34  4992.9  384.84  4998.8  385.55
  5004.4  385.55  5009.3  386.92  5015.1  387.88  5024.8  388.40  5046.2  388.63
  5059.8  388.41  5073.4  389.20  5094.8  391.03  5118.1  391.01  5183.6  392.78
  5211.4  393.69  5221.1  393.46  5234.7  394.05  5242.5  394.94  5293.0  397.81
#Mann=4,-1,0
  4685.3    0.05       0  4988.9    0.03       0  4992.9    0.05       0
  5183.6     0.1       0
Bank Sta=4988.9,4992.9
Exp/Cntr=0.3,0.1

Type RM Length L Ch R = 1,937,560,560,560
BEGIN DESCRIPTION:
SOUTH MINERAL CR TRIB 10 6 0
END DESCRIPTION:
XS GIS Cut Line= 4
      3514956.72     10368574.88      3514706.73     10369184.21
      3514774.44     10369475.88      3515548.83     10369486.27
#Sta/Elev= 30
  4187.6  405.09  4389.5  399.59  4425.5  398.06  4449.5  395.40  4502.8  393.65
  4526.8  391.31  4556.2  391.63  4609.6  389.73  4633.6  387.98  4686.9  386.53
  4864.1  383.86  4953.1  384.47  4976.2  383.25  4981.4  384.01  4995.6  381.92
  4995.8  381.42  4999.6  381.92  5024.0  385.42  5029.1  384.79  5038.6  386.31
  5042.5  386.02  5079.7  384.21  5200.6  384.97  5243.3  384.49  5493.3  388.11
  5543.3  390.35  5648.0  393.00  5746.7  397.09  5833.4  400.74  5920.1  402.51
#Mann=7,-1,0
  4187.6    0.05       0  4953.1     0.1       0  4995.6    0.07       0
  4999.6     0.1       0  5042.5    0.05       0  5648.0    0.16       0
  5746.7     0.1       0
Bank Sta=4995.6,4999.6
Exp/Cntr=0.3,0.1

Type RM Length L Ch R = 1,377,0,0,0
BEGIN DESCRIPTION:
SOUTH MINERAL CR TRIB 10 1 0
END DESCRIPTION:
XS GIS Cut Line= 4
      3514607.79     10368423.74      3514227.57     10369460.25
      3514514.03     10369850.88      3515798.78     10369850.88
#Sta/Elev= 30
  3639.6  396.93  3703.1  393.08  3784.0  391.81  3906.0  386.53  4180.6  384.49
  4201.9  382.97  4220.1  384.32  4265.8  382.68  4551.1  381.31  4659.7  380.23
  4859.6  380.55  4983.4  381.38  4991.8  380.05  5003.8  375.46  5004.0  374.96
  5007.8  375.46  5012.7  379.87  5018.9  381.26  5124.5  380.22  5336.1  381.05
  5556.1  386.89  5679.7  386.02  5726.1  386.78  5766.1  384.34  5886.1  385.95
  6176.1  392.47  6216.1  395.75  6268.9  397.11  6446.1  401.31  6512.8  401.12
#Mann=9,-1,0
  3639.6    0.05       0  4551.1     0.1       0  4659.7    0.05       0
  4859.6     0.1       0  5003.8    0.07       0  5007.8     0.1       0
  5124.5    0.05       0  5679.7     0.1       0  6268.9    0.05       0
Bank Sta=5003.8,5007.8
Exp/Cntr=0.3,0.1

Chan Stop Cuts=-1