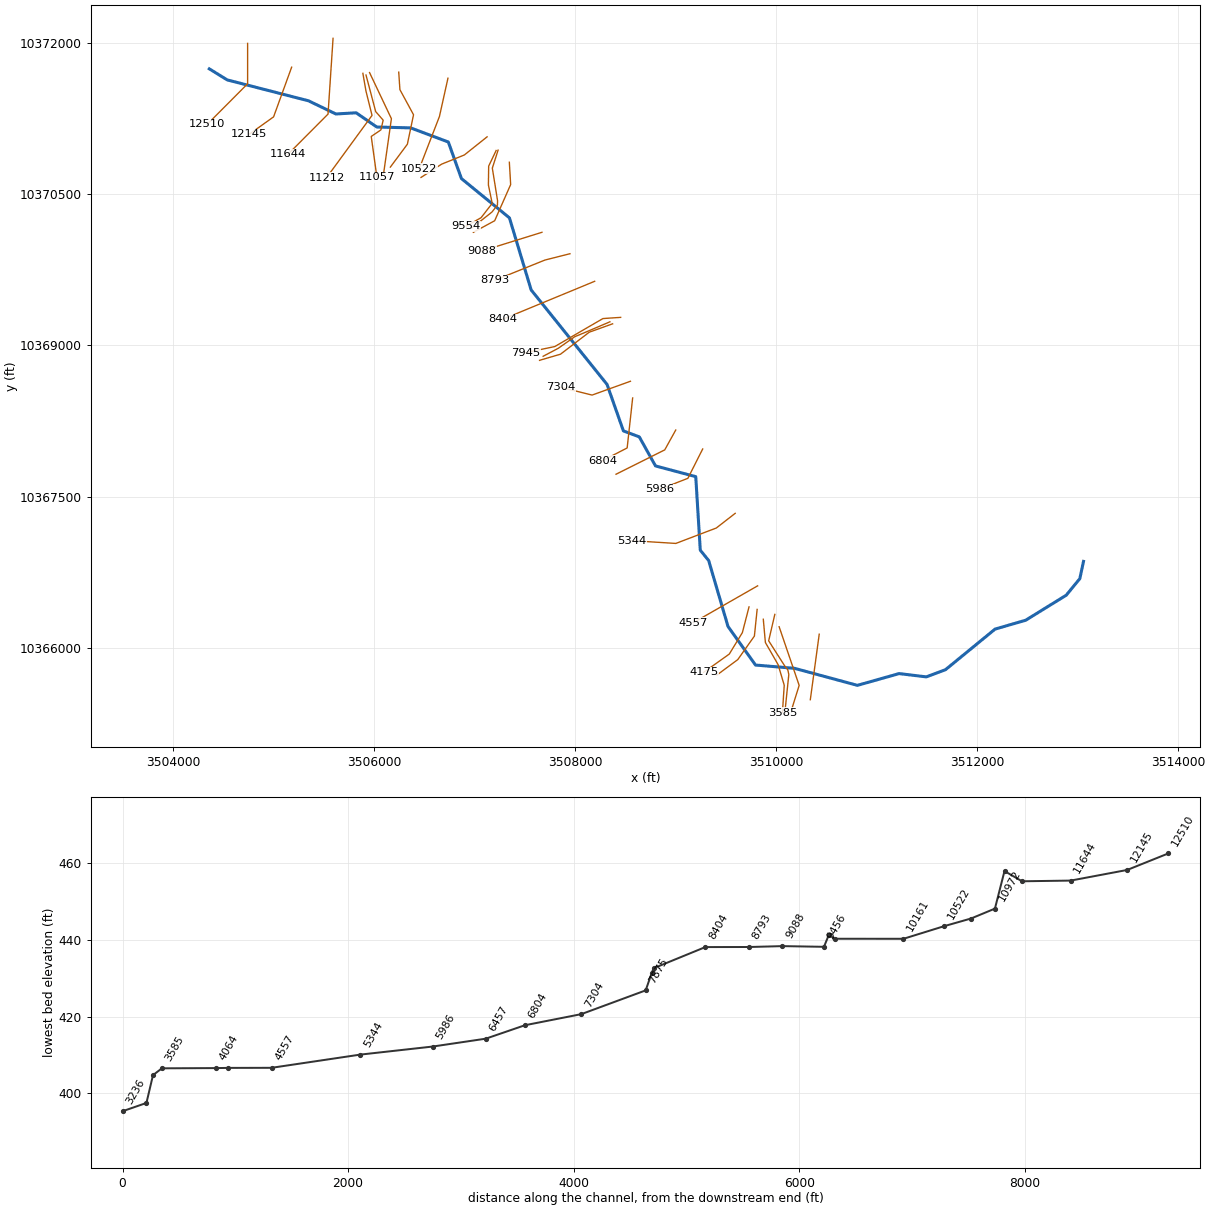
--- SOUTH MINERAL CR TRIB 11.prj (project) ---

Proj Title=SOUTH MINERAL CR TRIB 11 Base Level Engineering
Current Plan=p01
Default Exp/Contr=0.3,0.1
English Units
Geom File=g01
Flow File=f01
Plan File=p01
BEGIN DESCRIPTION:
SOUTH MINERAL CR TRIB 11
END DESCRIPTION:

--- SOUTH MINERAL CR TRIB 11.p01 (plan) ---

Plan Title=Multiple Run
Short Identifier=Multiple
Geom File=g01
Flow File=f01
Subcritical Flow
K Sum by GR= 0
Std Step Tol= 0.01
Critical Tol= 0.01
Num of Std Step Trials= 20
Max Error Tol= 0.3
Flow Tol Ratio= 0.001
Split Flow NTrial= 30
Split Flow Tol= 0.02
Split Flow Ratio= 0.02
Log Output Level= 0
Friction Slope Method= 1
Unsteady Friction Slope Method= 2
Unsteady Bridges Friction Slope Method= 1
Parabolic Critical Depth
Global Vel Dist=  1 , 1 , 1
Global Log Level= 0
CheckData=True
Encroach Param= -1, 0, 0, 0
BEGIN DESCRIPTION:
Multiple Run
END DESCRIPTION:

--- SOUTH MINERAL CR TRIB 11.f01 (steady flow) ---

Flow Title=Multiple
Number of Profiles=7
Profile Names=10-year,25-year,50-year,1pct_min,100-year,1pct_plu,500-year
River Rch & RM= SOUTH MINERAL CR,Reach-1,12510
    1578    2249    2822    2580    3489    4718    5326
River Rch & RM= SOUTH MINERAL CR,Reach-1,4175
    1751    2505    3151    2886    3903    5279    5983
Boundary for River Rch & Prof#=SOUTH MINERAL CR,Reach-1,1
Up Type=0
Dn Type=3
Dn Slope=0.005
Boundary for River Rch & Prof#=SOUTH MINERAL CR,Reach-1,2
Up Type=0
Dn Type=3
Dn Slope=0.005
Boundary for River Rch & Prof#=SOUTH MINERAL CR,Reach-1,3
Up Type=0
Dn Type=3
Dn Slope=0.005
Boundary for River Rch & Prof#=SOUTH MINERAL CR,Reach-1,4
Up Type=0
Dn Type=3
Dn Slope=0.005
Boundary for River Rch & Prof#=SOUTH MINERAL CR,Reach-1,5
Up Type=0
Dn Type=3
Dn Slope=0.005
Boundary for River Rch & Prof#=SOUTH MINERAL CR,Reach-1,6
Up Type=0
Dn Type=3
Dn Slope=0.005
Boundary for River Rch & Prof#=SOUTH MINERAL CR,Reach-1,7
Up Type=0
Dn Type=3
Dn Slope=0.005

--- SOUTH MINERAL CR TRIB 11.g01 (geometry) ---

Geom Title=Existing Conditions

River Reach=SOUTH MINERAL CR,Reach-1
Reach XY= 30
      3504361.23     10371739.56      3504538.77     10371630.17
      3505347.65     10371423.09      3505620.22     10371292.53
      3505821.61     10371304.34      3506027.17     10371163.37
      3506363.44     10371154.92      3506738.58     10371014.94
      3506868.89     10370653.15      3507346.50     10370263.92
      3507562.64     10369550.02      3508317.39     10368614.40
      3508480.06     10368154.02      3508638.27     10368094.75
      3508799.61     10367807.09      3509199.89     10367700.91
      3509244.84     10366972.88      3509328.42     10366870.03
      3509520.54     10366217.64      3509794.37     10365835.25
      3510182.43     10365802.71      3510807.72     10365634.11
      3511222.63     10365750.65      3511493.19     10365718.08
      3511684.16     10365789.26      3512177.22     10366191.17
      3512482.34     10366279.27      3512884.78     10366526.69
      3513020.10     10366690.73      3513056.83     10366861.76

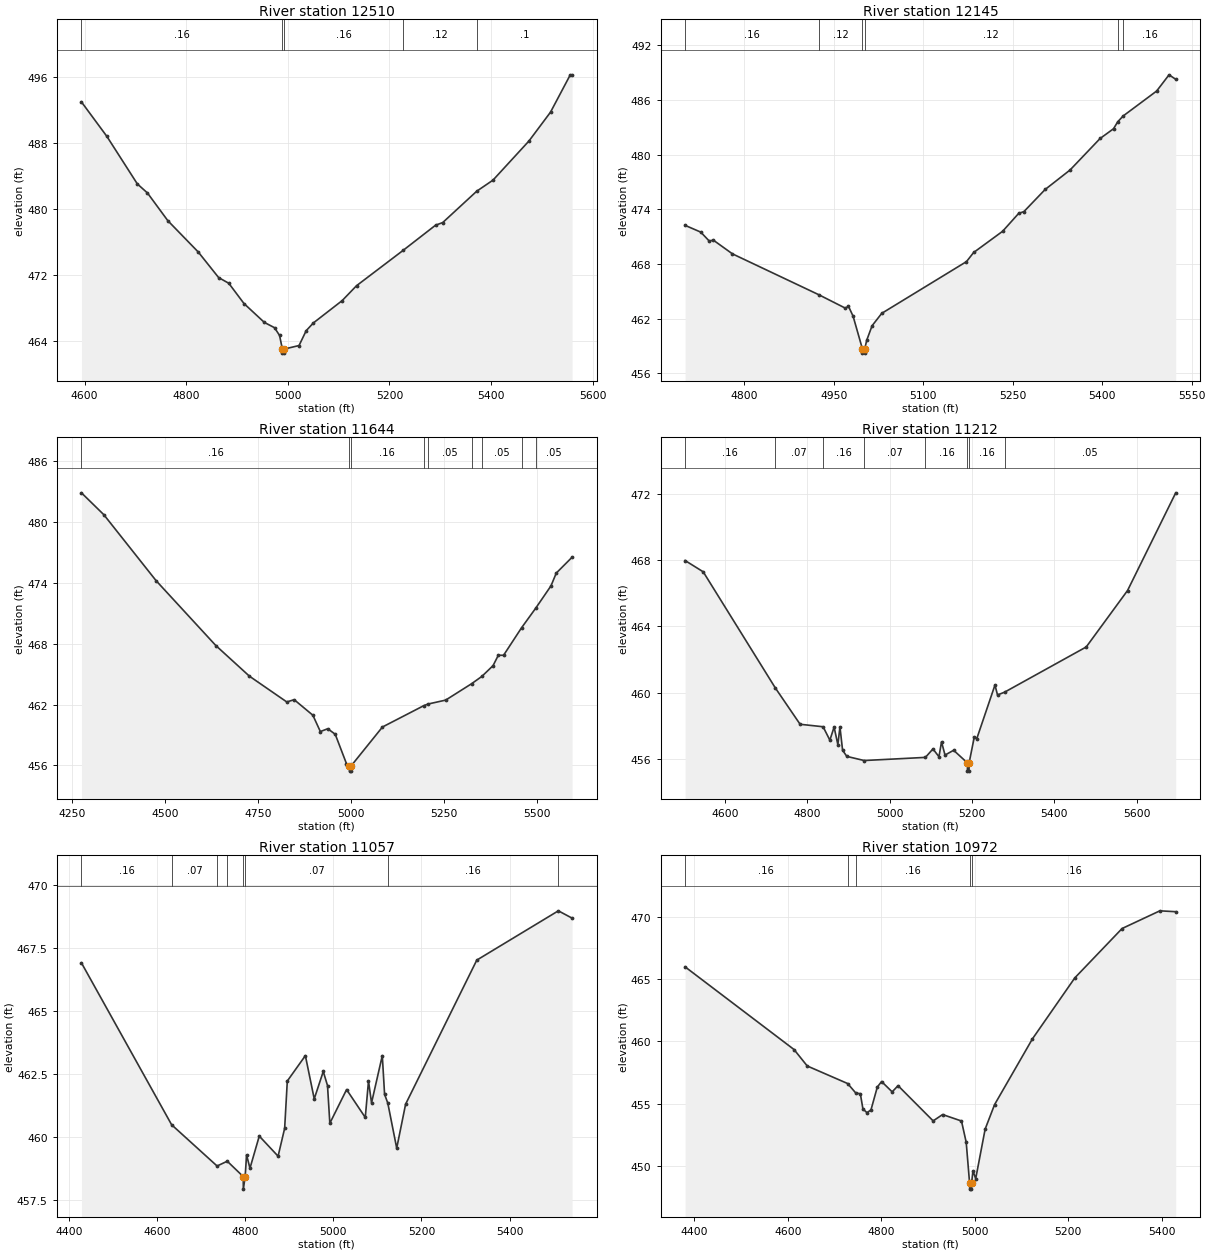
Type RM Length L Ch R = 1,12510,365,365,365
BEGIN DESCRIPTION:
SOUTH MINERAL CR TRIB 11 4 0
END DESCRIPTION:
XS GIS Cut Line= 3
      3504742.11     10371991.66      3504742.11     10371591.64
      3504342.11     10371191.65
#Sta/Elev= 30
  4593.8  492.94  4643.8  488.77  4703.8  483.01  4723.8  481.91  4763.8  478.56
  4823.8  474.76  4863.8  471.67  4883.8  470.98  4913.8  468.52  4953.8  466.24
  4973.8  465.60  4983.8  464.66  4989.2  463.02  4989.5  462.52  4993.1  462.52
  4993.4  463.02  5022.1  463.44  5036.2  465.24  5050.4  466.18  5107.0  468.88
  5135.2  470.68  5226.7  474.95  5290.8  478.01  5304.9  478.33  5371.9  482.13
  5403.9  483.47  5474.7  488.21  5517.1  491.70  5556.0  496.22  5559.5  496.22
#Mann=5,-1,0
  4593.8    0.16       0  4989.2    0.07       0  4993.4    0.16       0
  5226.7    0.12       0  5371.9     0.1       0
Bank Sta=4989.2,4993.4
Exp/Cntr=0.3,0.1

Type RM Length L Ch R = 1,12145,501,501,501
BEGIN DESCRIPTION:
SOUTH MINERAL CR TRIB 11 3 0
END DESCRIPTION:
XS GIS Cut Line= 3
      3505180.29     10371756.24      3505000.60     10371264.04
      3504757.08     10371090.84
#Sta/Elev= 30
  4700.5  472.24  4726.7  471.50  4740.8  470.53  4748.0  470.61  4779.9  469.11
  4924.8  464.62  4969.2  463.15  4974.5  463.35  4982.2  462.27  4997.7  458.71
  4997.9  458.21  5001.6  458.21  5001.9  458.71  5005.1  459.63  5014.1  461.22
  5030.3  462.58  5172.4  468.26  5184.4  469.26  5233.0  471.59  5260.0  473.56
  5268.7  473.75  5304.3  476.18  5346.1  478.32  5396.5  481.78  5419.0  482.85
  5426.0  483.61  5435.1  484.25  5491.3  486.99  5512.1  488.77  5523.3  488.28
#Mann=6,-1,0
  4700.5    0.16       0  4924.8    0.12       0  4997.7    0.07       0
  5001.9    0.12       0  5426.0    0.05       0  5435.1    0.16       0
Bank Sta=4997.7,5001.9
Exp/Cntr=0.3,0.1

Type RM Length L Ch R = 1,11644,432,432,432
BEGIN DESCRIPTION:
SOUTH MINERAL CR TRIB 11 25 0
END DESCRIPTION:
XS GIS Cut Line= 3
      3505592.11     10372041.68      3505542.11     10371291.64
      3505142.10     10370891.63
#Sta/Elev= 30
  4276.3  482.87  4336.5  480.71  4476.8  474.21  4637.1  467.82  4727.3  464.80
  4827.6  462.26  4847.6  462.48  4897.7  460.95  4917.8  459.34  4937.8  459.62
  4957.8  459.07  4987.9  456.18  4995.8  455.94  4996.1  455.44  4999.8  455.44
  5000.1  455.94  5084.6  459.79  5194.9  461.88  5206.7  462.05  5254.3  462.44
  5323.7  464.05  5351.3  464.77  5381.6  465.84  5395.7  466.86  5409.8  466.86
  5458.1  469.57  5495.9  471.49  5537.1  473.70  5551.3  474.96  5593.7  476.52
#Mann=9,-1,0
  4276.3    0.16       0  4995.8    0.07       0  5000.1    0.16       0
  5194.9    0.12       0  5206.7    0.05       0  5323.7    0.16       0
  5351.3    0.05       0  5458.1    0.16       0  5495.9    0.05       0
Bank Sta=4995.8,5000.1
Exp/Cntr=0.3,0.1

Type RM Length L Ch R = 1,11212,155,155,155
BEGIN DESCRIPTION:
SOUTH MINERAL CR TRIB 11 23 0
END DESCRIPTION:
XS GIS Cut Line= 4
      3505888.62     10371695.08      3505919.87     10371517.95
      3505979.77     10371278.36      3505527.93     10370662.46
#Sta/Elev= 30
  4503.9  467.98  4547.8  467.30  4722.7  460.29  4783.0  458.09  4838.8  457.94
  4855.2  457.13  4865.5  457.92  4874.6  456.86  4879.7  457.93  4886.1  456.52
  4896.4  456.15  4938.5  455.90  5087.1  456.09  5105.4  456.60  5120.0  456.13
  5126.2  457.03  5134.7  456.23  5155.6  456.52  5188.9  455.76  5189.2  455.26
  5192.9  455.26  5193.2  455.76  5205.7  457.32  5211.9  457.23  5255.9  460.46
  5262.1  459.86  5279.3  460.03  5477.4  462.76  5577.7  466.17  5694.6  472.07
#Mann=8,-1,0
  4503.9    0.16       0  4722.7    0.07       0  4838.8    0.16       0
  4938.5    0.07       0  5087.1    0.16       0  5188.9    0.07       0
  5193.2    0.16       0  5279.3    0.05       0
Bank Sta=5188.9,5193.2
Exp/Cntr=0.3,0.1

Type RM Length L Ch R = 1,11057,85,85,85
BEGIN DESCRIPTION:
SOUTH MINERAL CR TRIB 11 24 0
END DESCRIPTION:
XS GIS Cut Line= 6
      3505919.86     10371678.14      3506016.23     10371316.13
      3506090.45     10371231.49      3506068.31     10371135.14
      3505971.96     10371070.03      3506027.95     10370667.64
#Sta/Elev= 30
  4428.8  466.92  4633.4  460.48  4736.5  458.84  4759.6  459.03  4795.8  458.42
  4796.1  457.92  4800.2  458.42  4803.4  459.28  4811.1  458.75  4832.2  460.03
  4874.9  459.23  4889.8  460.34  4895.8  462.22  4936.8  463.23  4956.9  461.51
  4977.4  462.60  4987.0  462.04  4992.3  460.54  5030.3  461.88  5072.7  460.77
  5080.0  462.22  5086.9  461.35  5111.3  463.23  5116.5  461.69  5123.8  461.34
  5144.0  459.55  5164.2  461.30  5325.7  467.03  5510.7  468.99  5541.8  468.70
#Mann=8,-1,0
  4428.8    0.16       0  4633.4    0.07       0  4736.5    0.16       0
  4759.6    0.07       0  4795.8    0.07       0  4800.2    0.07       0
  5123.8    0.16       0  5510.7     0.1       0
Bank Sta=4795.8,4800.2
Exp/Cntr=0.3,0.1

Type RM Length L Ch R = 1,10972,212,212,212
BEGIN DESCRIPTION:
Mapping XS 6c91f36f
END DESCRIPTION:
XS GIS Cut Line= 3
      3505955.03     10371702.84      3506172.48     10371245.81
      3506095.66     10370708.09
#Sta/Elev= 30
  4380.5  465.99  4613.5  459.35  4641.7  458.03  4728.1  456.62  4745.5  455.86
  4755.3  455.80  4760.8  454.58  4769.4  454.28  4778.0  454.50  4791.6  456.34
  4800.7  456.78  4823.4  455.95  4835.9  456.45  4911.0  453.62  4931.2  454.13
  4971.6  453.61  4981.7  451.90  4988.9  448.64  4989.2  448.14  4993.0  448.14
  4993.3  448.64  4996.1  449.61  5002.0  448.98  5022.2  452.96  5042.4  454.93
  5123.2  460.20  5214.1  465.11  5315.1  469.07  5395.9  470.49  5429.8  470.42
#Mann=5,-1,0
  4380.5    0.16       0  4728.1    0.07       0  4745.5    0.16       0
  4988.9    0.07       0  4993.3    0.16       0
Bank Sta=4988.9,4993.3
Exp/Cntr=0.3,0.1

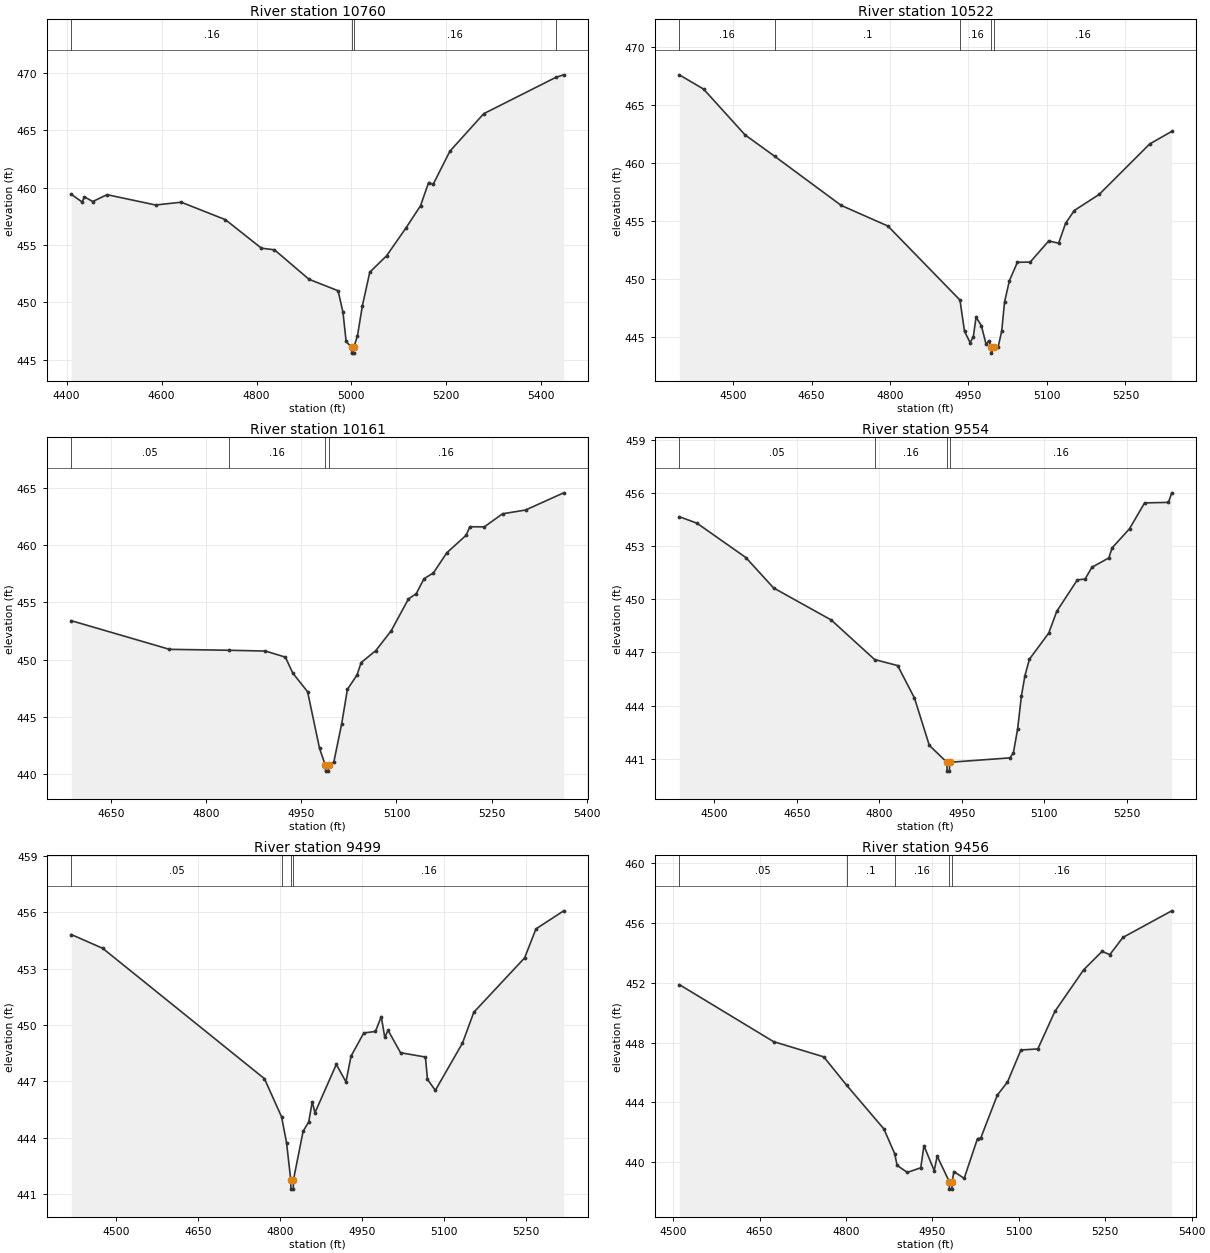
Type RM Length L Ch R = 1,10760,238,238,238
BEGIN DESCRIPTION:
SOUTH MINERAL CR TRIB 11 22 1
END DESCRIPTION:
XS GIS Cut Line= 5
      3506245.39     10371706.76      3506257.11     10371533.57
      3506392.53     10371284.88      3506331.33     10370993.21
      3506162.06     10370766.64
#Sta/Elev= 30
  4409.7  459.41  4432.5  458.74  4437.5  459.19  4454.9  458.78  4485.0  459.38
  4587.2  458.48  4641.4  458.72  4734.4  457.20  4810.4  454.71  4837.9  454.57
  4910.6  452.00  4971.9  451.00  4982.2  449.13  4988.8  446.60  5000.2  446.06
  5000.5  445.56  5004.6  445.56  5005.0  446.06  5012.8  447.08  5023.0  449.67
  5038.7  452.62  5074.1  454.05  5115.0  456.48  5145.6  458.41  5162.7  460.44
  5172.1  460.27  5207.5  463.17  5278.8  466.44  5430.8  469.61  5447.3  469.83
#Mann=4,-1,0
  4409.7    0.16       0  5000.2    0.07       0  5005.0    0.16       0
  5430.8     0.1       0
Bank Sta=5000.2,5005
Exp/Cntr=0.3,0.1

Type RM Length L Ch R = 1,10522,361,361,361
BEGIN DESCRIPTION:
Mapping XS 3a380639
END DESCRIPTION:
XS GIS Cut Line= 3
      3506734.99     10371646.89      3506650.34     10371267.95
      3506449.83     10370752.35
#Sta/Elev= 30
  4397.1  467.59  4443.5  466.36  4522.7  462.41  4579.7  460.55  4706.6  456.32
  4795.9  454.54  4933.7  448.15  4942.4  445.45  4953.1  444.48  4959.2  444.98
  4964.5  446.67  4974.6  445.95  4983.7  444.32  4989.0  444.65  4993.6  444.07
  4993.9  443.57  4998.5  444.07  5006.7  444.10  5013.6  445.50  5018.9  447.97
  5028.2  449.82  5043.5  451.41  5068.0  451.43  5103.3  453.25  5122.4  453.06
  5135.5  454.76  5152.3  455.88  5199.9  457.27  5296.4  461.62  5338.6  462.71
#Mann=5,-1,0
  4397.1    0.16       0  4579.7     0.1       0  4933.7    0.16       0
  4993.6    0.07       0  4998.5    0.16       0
Bank Sta=4993.6,4998.5
Exp/Cntr=0.3,0.1

Type RM Length L Ch R = 1,10161,607,607,607
BEGIN DESCRIPTION:
SOUTH MINERAL CR TRIB 11 22 0
END DESCRIPTION:
XS GIS Cut Line= 4
      3507124.27     10371066.10      3506897.74     10370886.44
      3506671.18     10370795.29      3506466.93     10370663.90
#Sta/Elev= 30
  4587.4  453.41  4742.2  450.91  4835.5  450.83  4893.4  450.76  4924.9  450.23
  4936.5  448.84  4959.9  447.21  4978.7  442.28  4987.9  440.78  4988.3  440.28
  4992.5  440.28  4992.9  440.78  5001.2  441.06  5013.6  444.40  5022.7  447.42
  5037.8  448.67  5044.3  449.75  5067.4  450.80  5091.6  452.52  5118.9  455.31
  5131.2  455.77  5143.4  457.07  5158.2  457.58  5179.4  459.34  5209.7  460.86
  5215.7  461.61  5238.5  461.60  5267.2  462.74  5303.5  463.07  5363.6  464.57
#Mann=4,-1,0
  4587.4    0.05       0  4835.5    0.16       0  4987.9    0.07       0
  4992.9    0.16       0
Bank Sta=4987.9,4992.9
Exp/Cntr=0.3,0.1

Type RM Length L Ch R = 1,9554,55,55,55
BEGIN DESCRIPTION:
SOUTH MINERAL CR TRIB 11 2 0
END DESCRIPTION:
XS GIS Cut Line= 6
      3507214.13     10370930.67      3507139.93     10370775.76
      3507137.32     10370589.56      3507175.08     10370407.27
      3507064.41     10370265.34      3506915.91     10370181.41
#Sta/Elev= 30
  4436.7  454.68  4468.9  454.31  4557.6  452.37  4608.0  450.65  4712.6  448.84
  4791.6  446.60  4833.4  446.26  4864.0  444.42  4890.9  441.75  4922.8  440.79
  4923.2  440.29  4927.5  440.29  4927.8  440.79  5037.5  441.04  5043.8  441.34
  5051.4  442.68  5058.3  444.54  5064.6  445.68  5072.8  446.62  5108.0  448.10
  5122.5  449.33  5160.0  451.11  5173.9  451.15  5186.4  451.82  5217.2  452.35
  5222.9  452.91  5254.7  454.00  5282.1  455.46  5325.4  455.49  5331.4  456.03
#Mann=4,-1,0
  4436.7    0.05       0  4791.6    0.16       0  4922.8    0.07       0
  4927.8    0.16       0
Bank Sta=4922.8,4927.8
Exp/Cntr=0.3,0.1

Type RM Length L Ch R = 1,9499,43,43,43
BEGIN DESCRIPTION:
SOUTH MINERAL CR TRIB 11 20 0
END DESCRIPTION:
XS GIS Cut Line= 6
      3507233.66     10370934.57      3507176.39     10370756.23
      3507228.47     10370433.31      3507227.17     10370390.34
      3507172.48     10370321.33      3506970.64     10370162.47
#Sta/Elev= 30
  4417.5  454.81  4475.0  454.08  4771.5  447.15  4802.9  445.12  4812.0  443.75
  4819.7  441.78  4820.0  441.28  4824.3  441.28  4824.7  441.78  4842.4  444.36
  4852.6  444.85  4859.1  445.92  4864.1  445.34  4903.2  447.91  4920.9  446.98
  4930.2  448.35  4953.6  449.58  4974.9  449.66  4985.6  450.45  4992.0  449.35
  4998.1  449.72  5020.9  448.53  5066.5  448.30  5070.3  447.11  5084.7  446.53
  5134.4  449.04  5155.2  450.68  5248.3  453.57  5269.1  455.11  5319.9  456.07
#Mann=4,-1,0
  4417.5    0.05       0  4802.9    0.16       0  4819.7    0.07       0
  4824.7    0.16       0
Bank Sta=4819.7,4824.7
Exp/Cntr=0.3,0.1

Type RM Length L Ch R = 1,9456,368,368,368
BEGIN DESCRIPTION:
SOUTH MINERAL CR TRIB 11 19 1
END DESCRIPTION:
XS GIS Cut Line= 4
      3507345.65     10370814.87      3507358.68     10370593.47
      3507199.82     10370235.40      3506987.59     10370120.82
#Sta/Elev= 30
  4510.7  451.89  4674.2  448.07  4761.4  447.05  4800.9  445.16  4865.8  442.22
  4884.6  440.56  4888.7  439.78  4906.5  439.31  4929.8  439.62  4935.3  441.10
  4953.1  439.43  4958.3  440.40  4979.3  438.69  4979.6  438.19  4983.9  438.19
  4984.3  438.69  4987.3  439.37  5005.1  438.91  5028.3  441.58  5033.8  441.60
  5062.7  444.49  5080.3  445.36  5103.6  447.51  5133.0  447.58  5162.5  450.09
  5212.5  452.88  5244.4  454.11  5258.0  453.90  5280.7  455.05  5365.4  456.83
#Mann=5,-1,0
  4510.7    0.05       0  4800.9     0.1       0  4884.6    0.16       0
  4979.3    0.07       0  4984.3    0.16       0
Bank Sta=4979.3,4984.3
Exp/Cntr=0.3,0.1

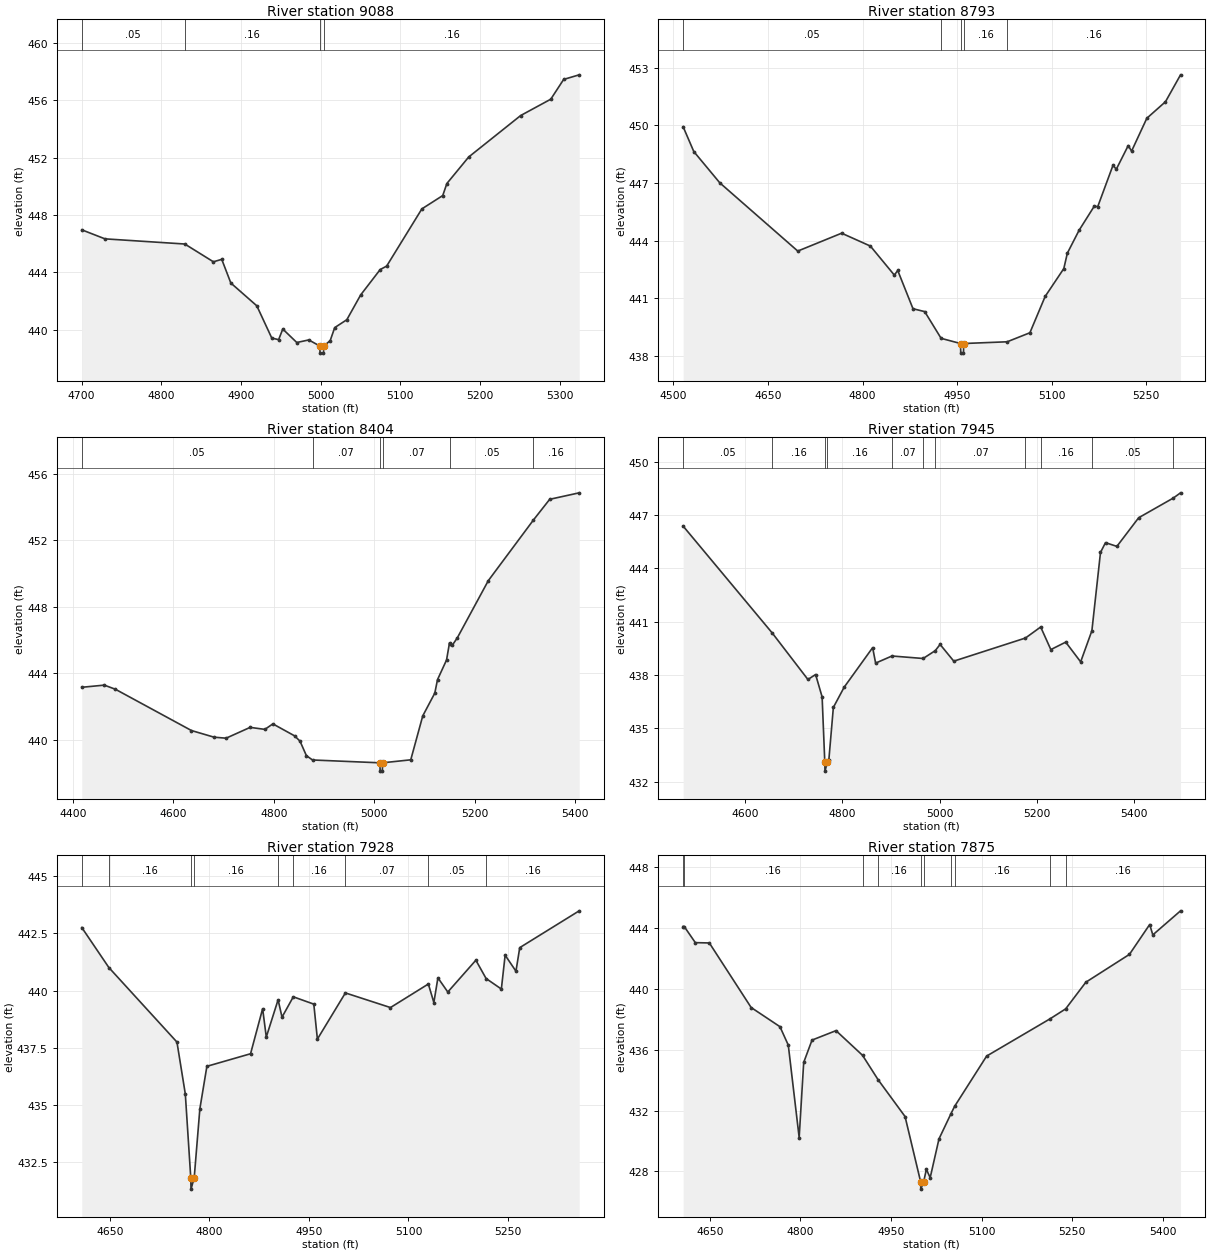
Type RM Length L Ch R = 1,9088,295,295,295
BEGIN DESCRIPTION:
Mapping XS 8b1d1a33
END DESCRIPTION:
XS GIS Cut Line= 2
      3507669.88     10370120.82      3507073.49     10369935.91
#Sta/Elev= 30
  4700.3  446.97  4729.4  446.34  4829.6  445.98  4865.5  444.74  4876.0  444.91
  4887.4  443.26  4920.0  441.67  4938.8  439.42  4947.4  439.31  4952.6  440.05
  4970.2  439.11  4985.2  439.29  4999.0  438.87  4999.4  438.37  5003.7  438.37
  5004.1  438.87  5012.1  439.24  5017.8  440.15  5033.0  440.70  5050.4  442.43
  5074.9  444.20  5083.0  444.44  5127.2  448.43  5153.4  449.36  5158.6  450.20
  5186.0  452.05  5251.2  454.94  5289.0  456.08  5305.2  457.46  5324.7  457.78
#Mann=4,-1,0
  4700.3    0.05       0  4829.6    0.16       0  4999.0    0.07       0
  5004.1    0.16       0
Bank Sta=4999,5004.1
Exp/Cntr=0.3,0.1

Type RM Length L Ch R = 1,8793,389,389,389
BEGIN DESCRIPTION:
SOUTH MINERAL CR TRIB 11 19 2
END DESCRIPTION:
XS GIS Cut Line= 3
      3507948.53     10369908.58      3507699.82     10369846.07
      3507205.44     10369647.54
#Sta/Elev= 30
  4515.3  449.92  4532.2  448.63  4573.5  447.00  4697.2  443.45  4766.8  444.38
  4812.4  443.71  4850.4  442.20  4855.8  442.44  4880.0  440.45  4898.6  440.30
  4924.6  438.91  4955.4  438.64  4955.8  438.14  4960.1  438.14  4960.5  438.64
  5029.4  438.73  5065.5  439.20  5089.7  441.09  5119.3  442.54  5124.9  443.34
  5143.5  444.53  5167.7  445.79  5173.1  445.76  5197.3  447.91  5202.6  447.71
  5221.5  448.94  5226.8  448.65  5251.0  450.36  5280.6  451.22  5304.5  452.62
#Mann=5,-1,0
  4515.3    0.05       0  4924.6    0.16       0  4955.4    0.07       0
  4960.5    0.16       0  5029.4    0.16       0
Bank Sta=4955.4,4960.5
Exp/Cntr=0.3,0.1

Type RM Length L Ch R = 1,8404,459,459,459
BEGIN DESCRIPTION:
Mapping XS 539edc73
END DESCRIPTION:
XS GIS Cut Line= 2
      3508194.20     10369635.51      3507277.69     10369258.56
#Sta/Elev= 30
  4417.4  443.16  4462.3  443.29  4484.5  443.04  4635.9  440.56  4681.0  440.16
  4704.9  440.10  4752.8  440.75  4782.2  440.63  4798.1  440.96  4841.4  440.24
  4852.2  439.92  4864.9  439.05  4877.1  438.79  5011.4  438.62  5011.8  438.12
  5016.2  438.12  5016.6  438.62  5072.8  438.80  5096.7  441.44  5120.7  442.81
  5126.1  443.62  5144.1  444.80  5150.0  445.83  5151.4  445.79  5155.4  445.68
  5165.7  446.14  5227.3  449.57  5317.3  453.22  5349.6  454.46  5408.4  454.85
#Mann=6,-1,0
  4417.4    0.05       0  4877.1    0.07       0  5011.4    0.07       0
  5016.6    0.07       0  5151.4    0.05       0  5317.3    0.16       0
Bank Sta=5011.4,5016.6
Exp/Cntr=0.3,0.1

Type RM Length L Ch R = 1,7945,17,17,17
BEGIN DESCRIPTION:
SOUTH MINERAL CR TRIB 11 18 0
END DESCRIPTION:
XS GIS Cut Line= 4
      3508452.77     10369278.36      3508276.65     10369266.65
      3507797.48     10368989.30      3507511.03     10368929.41
#Sta/Elev= 30
  4472.4  446.37  4656.0  440.35  4729.0  437.75  4744.8  438.03  4758.2  436.77
  4763.7  433.10  4764.1  432.60  4768.9  433.10  4772.1  433.25  4781.3  436.18
  4803.6  437.32  4862.1  439.54  4868.2  438.67  4901.8  439.07  4965.9  438.93
  4990.8  439.37  5000.8  439.72  5028.9  438.78  5176.3  440.08  5207.6  440.70
  5228.5  439.43  5259.1  439.85  5289.8  438.74  5312.9  440.49  5330.6  444.89
  5340.9  445.44  5364.3  445.23  5409.1  446.84  5480.5  447.95  5495.2  448.24
#Mann=11,-1,0
  4472.4    0.05       0  4656.0    0.16       0  4763.7    0.07       0
  4768.9    0.16       0  4901.8    0.07       0  4965.9    0.16       0
  4990.8    0.07       0  5176.3    0.05       0  5207.6    0.16       0
  5312.9    0.05       0  5480.5    0.16       0
Bank Sta=4763.7,4768.9
Exp/Cntr=0.3,0.1

Type RM Length L Ch R = 1,7928,53,53,53
BEGIN DESCRIPTION:
SOUTH MINERAL CR TRIB 11 17 0
END DESCRIPTION:
XS GIS Cut Line= 5
      3508345.67     10369234.10      3508078.73     10369120.81
      3507996.70     10369086.96      3507832.64     10368972.38
      3507681.59     10368892.94
#Sta/Elev= 30
  4607.8  442.76  4648.6  441.01  4751.2  437.75  4763.8  435.48  4772.0  431.82
  4772.4  431.32  4777.2  431.82  4785.7  434.83  4796.3  436.69  4862.1  437.24
  4880.3  439.21  4885.8  437.97  4903.6  439.60  4909.5  438.84  4926.5  439.73
  4957.4  439.41  4962.8  437.88  5005.0  439.90  5072.9  439.26  5130.0  440.29
  5138.3  439.48  5144.4  440.56  5159.3  439.94  5201.6  441.33  5217.0  440.53
  5240.0  440.07  5245.7  441.55  5262.0  440.85  5267.7  441.88  5357.3  443.49
#Mann=9,-1,0
  4607.8    0.05       0  4648.6    0.16       0  4772.0    0.07       0
  4777.2    0.16       0  4903.6    0.07       0  4926.5    0.16       0
  5005.0    0.07       0  5130.0    0.05       0  5217.0    0.16       0
Bank Sta=4772,4777.2
Exp/Cntr=0.3,0.1

Type RM Length L Ch R = 1,7875,571,571,571
BEGIN DESCRIPTION:
SOUTH MINERAL CR TRIB 11 16 0
END DESCRIPTION:
XS GIS Cut Line= 4
      3508373.00     10369214.56      3508139.93     10369131.23
      3507854.77     10368913.78      3507646.11     10368852.87
#Sta/Elev= 30
  4606.0  444.09  4607.8  444.09  4626.2  443.03  4649.4  443.01  4718.6  438.77
  4766.3  437.51  4780.1  436.30  4798.1  430.23  4805.6  435.16  4819.4  436.63
  4859.1  437.25  4903.0  435.63  4928.9  434.02  4973.4  431.61  4999.1  427.34
  4999.5  426.84  5004.3  427.34  5008.7  428.14  5015.0  427.59  5029.6  430.14
  5049.5  431.80  5055.5  432.28  5108.5  435.58  5213.2  438.02  5239.3  438.68
  5272.7  440.43  5344.9  442.26  5378.4  444.22  5383.6  443.54  5429.5  445.12
#Mann=10,-1,0
  4606.0    0.05       0  4607.8    0.16       0  4903.0    0.12       0
  4928.9    0.16       0  4999.1    0.07       0  5004.3    0.16       0
  5049.5    0.07       0  5055.5    0.16       0  5213.2    0.05       0
  5239.3    0.16       0
Bank Sta=4999.1,5004.3
Exp/Cntr=0.3,0.1

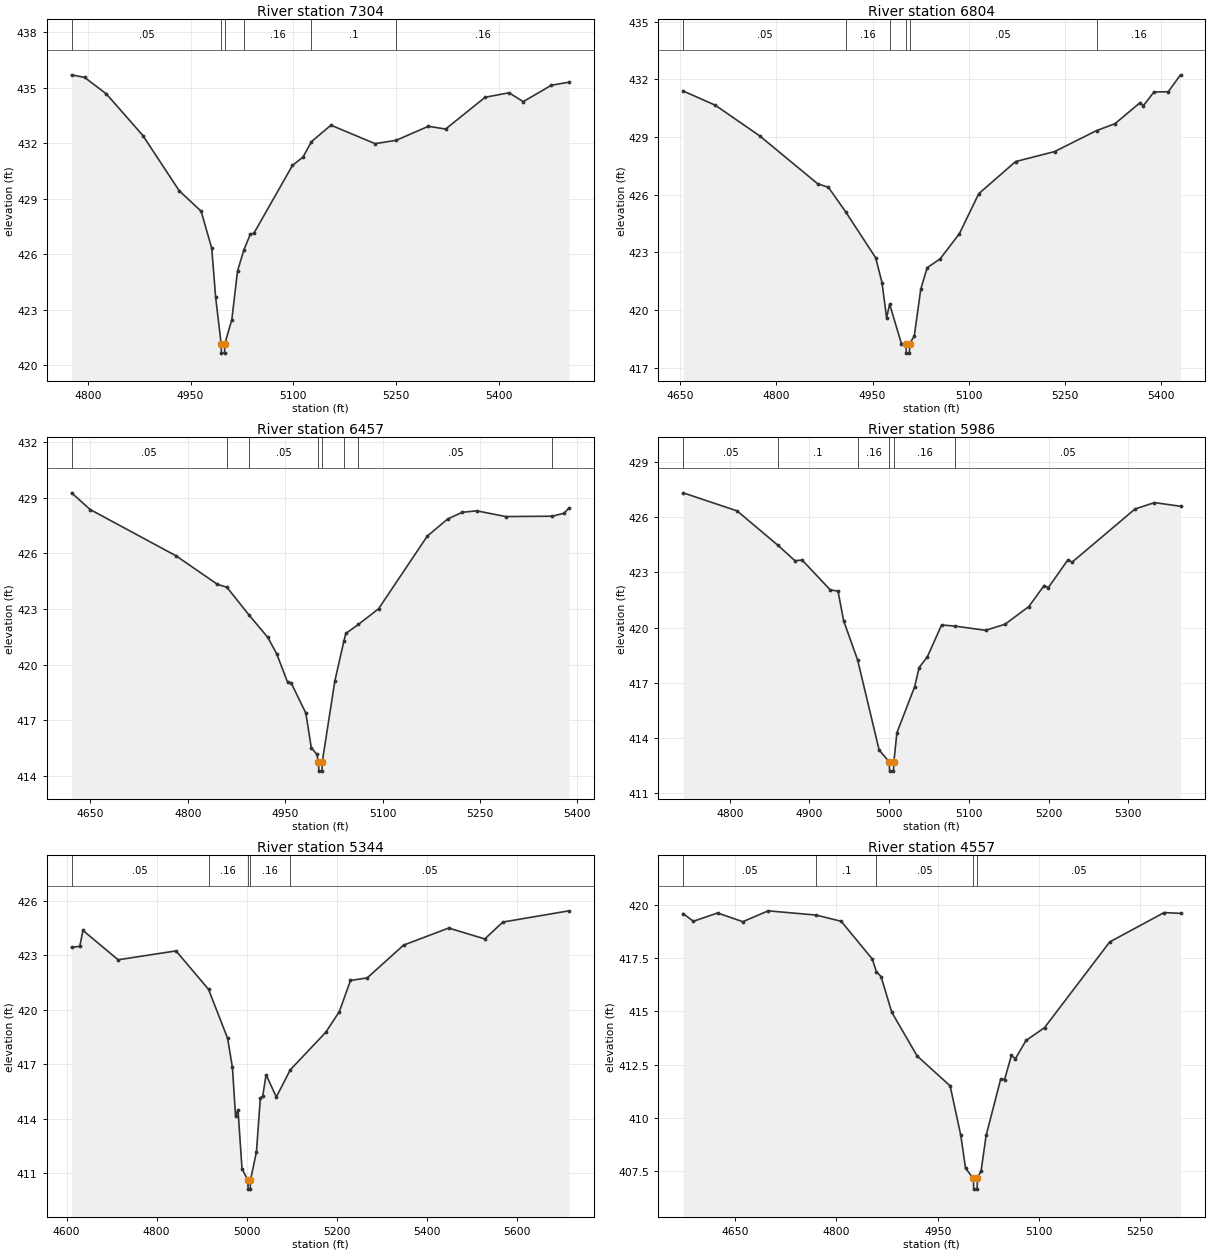
Type RM Length L Ch R = 1,7304,500,500,500
BEGIN DESCRIPTION:
SOUTH MINERAL CR TRIB 11 15 0
END DESCRIPTION:
XS GIS Cut Line= 3
      3508550.07     10368645.55      3508168.57     10368508.83
      3507857.37     10368585.66
#Sta/Elev= 30
  4776.4  435.69  4795.5  435.55  4827.2  434.66  4880.5  432.41  4933.6  429.42
  4965.5  428.32  4981.0  426.31  4986.7  423.66  4994.7  421.15  4995.1  420.65
  4999.6  420.65  5000.0  421.15  5010.3  422.46  5018.6  425.09  5028.0  426.24
  5037.2  427.07  5042.5  427.13  5098.7  430.79  5114.2  431.25  5126.5  432.08
  5154.9  432.97  5219.3  431.97  5250.0  432.15  5297.1  432.91  5322.2  432.76
  5380.0  434.48  5414.9  434.72  5435.5  434.24  5476.7  435.13  5502.2  435.29
#Mann=6,-1,0
  4776.4    0.05       0  4994.7    0.03       0  5000.0    0.05       0
  5028.0    0.16       0  5126.5     0.1       0  5250.0    0.16       0
Bank Sta=4994.7,5000
Exp/Cntr=0.3,0.1

Type RM Length L Ch R = 1,6804,347,347,347
BEGIN DESCRIPTION:
SOUTH MINERAL CR TRIB 11 14 0
END DESCRIPTION:
XS GIS Cut Line= 3
      3508572.22     10368480.18      3508517.53     10367985.40
      3508270.10     10367857.77
#Sta/Elev= 30
  4654.3  431.39  4704.5  430.65  4773.6  429.06  4864.1  426.57  4881.0  426.38
  4908.1  425.10  4954.7  422.72  4964.7  421.42  4971.8  419.59  4976.5  420.31
  4994.9  418.26  5002.1  418.26  5002.6  417.76  5007.4  417.76  5007.8  418.26
  5015.0  418.65  5025.1  421.08  5035.1  422.20  5055.3  422.66  5085.4  423.97
  5115.6  426.05  5173.1  427.72  5234.0  428.24  5299.4  429.33  5328.2  429.69
  5366.9  430.77  5372.6  430.63  5389.1  431.34  5411.3  431.35  5430.5  432.23
#Mann=6,-1,0
  4654.3    0.05       0  4908.1    0.16       0  4976.5    0.05       0
  5002.1    0.03       0  5007.8    0.05       0  5299.4    0.16       0
Bank Sta=5002.1,5007.8
Exp/Cntr=0.3,0.1

Type RM Length L Ch R = 1,6457,471,471,471
BEGIN DESCRIPTION:
SOUTH MINERAL CR TRIB 11 13 0
END DESCRIPTION:
XS GIS Cut Line= 3
      3509000.61     10368162.49      3508891.23     10367965.86
      3508406.83     10367724.97
#Sta/Elev= 30
  4621.1  429.26  4649.8  428.36  4782.3  425.86  4845.7  424.33  4860.4  424.17
  4894.3  422.68  4923.3  421.47  4937.1  420.58  4953.9  419.04  4959.5  419.00
  4981.9  417.39  4990.3  415.52  4998.7  415.17  5001.4  414.76  5001.9  414.26
  5006.7  414.26  5007.2  414.76  5026.7  419.14  5040.4  421.25  5043.5  421.68
  5063.0  422.17  5093.9  423.01  5169.0  426.93  5200.3  427.85  5222.7  428.21
  5245.1  428.29  5289.9  427.98  5361.3  428.00  5379.5  428.16  5387.1  428.44
#Mann=8,-1,0
  4621.1    0.05       0  4860.4    0.16       0  4894.3    0.05       0
  5001.4    0.03       0  5007.2    0.05       0  5040.4    0.16       0
  5063.0    0.05       0  5361.3    0.16       0
Bank Sta=5001.4,5007.2
Exp/Cntr=0.3,0.1

Type RM Length L Ch R = 1,5986,642,642,642
BEGIN DESCRIPTION:
SOUTH MINERAL CR TRIB 11 12 0
END DESCRIPTION:
XS GIS Cut Line= 3
      3509268.81     10367974.94      3509121.70     10367684.61
      3508843.54     10367575.94
#Sta/Elev= 30
  4741.5  427.31  4809.2  426.33  4860.3  424.47  4881.7  423.63  4890.9  423.66
  4926.2  422.04  4935.8  421.98  4942.9  420.37  4960.5  418.23  4987.4  413.36
  5000.1  412.71  5000.6  412.21  5005.4  412.21  5005.9  412.71  5009.7  414.29
  5032.0  416.79  5037.6  417.83  5047.9  418.41  5065.8  420.14  5082.5  420.08
  5121.0  419.85  5145.4  420.18  5175.3  421.14  5194.4  422.28  5199.8  422.17
  5224.2  423.67  5229.6  423.55  5308.4  426.43  5332.9  426.78  5365.6  426.58
#Mann=6,-1,0
  4741.5    0.05       0  4860.3     0.1       0  4960.5    0.16       0
  5000.1    0.07       0  5005.9    0.16       0  5082.5    0.05       0
Bank Sta=5000.1,5005.9
Exp/Cntr=0.3,0.1

Type RM Length L Ch R = 1,5344,787,787,787
BEGIN DESCRIPTION:
SOUTH MINERAL CR TRIB 11 19 0
END DESCRIPTION:
XS GIS Cut Line= 4
      3509592.09     10367337.50      3509404.27     10367192.31
      3509001.49     10367039.53      3508565.55     10367067.21
#Sta/Elev= 30
  4610.9  423.45  4629.2  423.50  4636.2  424.38  4714.4  422.76  4843.0  423.25
  4915.2  421.13  4957.6  418.43  4968.3  416.82  4975.3  414.13  4980.7  414.49
  4989.6  411.23  5002.6  410.61  5003.0  410.11  5007.9  410.11  5008.4  410.61
  5021.7  412.17  5030.3  415.13  5035.6  415.24  5043.1  416.42  5065.8  415.19
  5096.8  416.69  5175.6  418.76  5205.8  419.90  5230.6  421.62  5267.7  421.76
  5348.6  423.57  5448.8  424.51  5529.0  423.91  5569.0  424.84  5715.9  425.46
#Mann=5,-1,0
  4610.9    0.05       0  4915.2    0.16       0  5002.6    0.07       0
  5008.4    0.16       0  5096.8    0.05       0
Bank Sta=5002.6,5008.4
Exp/Cntr=0.3,0.1

Type RM Length L Ch R = 1,4557,382,382,382
BEGIN DESCRIPTION:
SOUTH MINERAL CR TRIB 11 9 0
END DESCRIPTION:
XS GIS Cut Line= 2
      3509815.35     10366619.64      3509175.61     10366254.93
#Sta/Elev= 30
  4573.1  419.59  4588.3  419.23  4624.1  419.62  4661.5  419.21  4699.0  419.72
  4770.1  419.52  4807.1  419.23  4853.1  417.46  4859.3  416.86  4866.1  416.64
  4881.9  414.97  4919.4  412.92  4968.4  411.51  4984.2  409.19  4991.2  407.65
  5002.8  407.17  5003.3  406.67  5008.3  406.67  5008.8  407.17  5014.3  407.54
  5021.7  409.19  5043.3  411.84  5049.0  411.81  5059.1  412.94  5064.9  412.78
  5080.7  413.64  5108.1  414.24  5204.6  418.26  5285.3  419.64  5309.5  419.60
#Mann=5,-1,0
  4573.1    0.05       0  4770.1     0.1       0  4859.3    0.05       0
  5002.8   0.035       0  5008.8    0.05       0
Bank Sta=5002.8,5008.8
Exp/Cntr=0.3,0.1

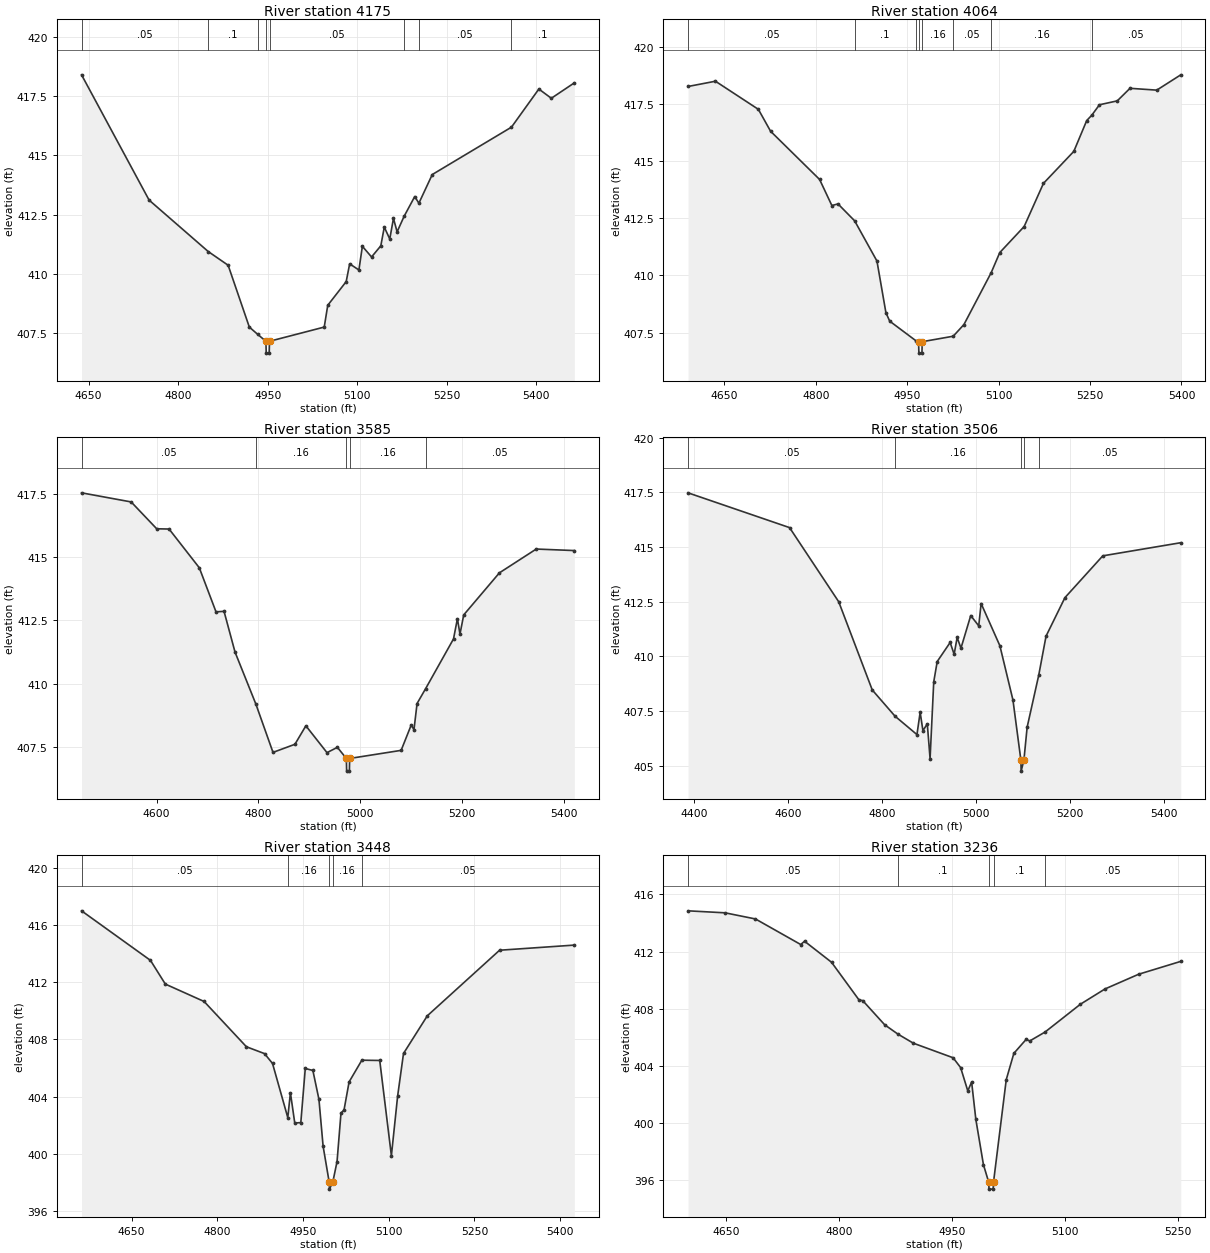
Type RM Length L Ch R = 1,4175,111,111,111
BEGIN DESCRIPTION:
SOUTH MINERAL CR TRIB 11 29 0
END DESCRIPTION:
XS GIS Cut Line= 4
      3509729.78     10366411.20      3509663.36     10366155.97
      3509533.16     10365943.73      3509277.95     10365762.74
#Sta/Elev= 30
  4638.2  418.40  4751.4  413.11  4850.4  410.94  4883.8  410.36  4919.3  407.75
  4933.0  407.45  4947.1  407.15  4947.6  406.65  4952.6  406.65  4953.1  407.15
  5044.8  407.75  5050.7  408.67  5081.6  409.67  5087.4  410.42  5102.9  410.16
  5108.7  411.16  5124.1  410.71  5139.6  411.18  5145.4  411.97  5154.6  411.47
  5160.8  412.34  5166.9  411.77  5178.7  412.43  5196.4  413.26  5203.4  412.98
  5225.8  414.19  5358.5  416.19  5404.4  417.80  5425.3  417.41  5463.8  418.06
#Mann=8,-1,0
  4638.2    0.05       0  4850.4     0.1       0  4933.0    0.05       0
  4947.1    0.04       0  4953.1    0.05       0  5178.7    0.16       0
  5203.4    0.05       0  5358.5     0.1       0
Bank Sta=4947.1,4953.1
Exp/Cntr=0.3,0.1

Type RM Length L Ch R = 1,4064,479,479,479
BEGIN DESCRIPTION:
SOUTH MINERAL CR TRIB 11 8 0
END DESCRIPTION:
XS GIS Cut Line= 4
      3509810.50     10366386.41      3509783.16     10366122.11
      3509617.79     10365889.04      3509410.78     10365736.71
#Sta/Elev= 30
  4590.4  418.27  4635.4  418.50  4705.8  417.27  4725.9  416.31  4806.3  414.20
  4826.4  413.06  4836.5  413.13  4863.8  412.39  4900.4  410.63  4915.1  408.37
  4921.3  408.00  4963.9  407.15  4968.7  407.10  4969.2  406.60  4974.2  406.60
  4974.7  407.10  5025.5  407.34  5043.1  407.85  5087.8  410.12  5101.9  411.00
  5141.9  412.14  5173.6  414.03  5223.4  415.43  5244.6  416.78  5252.8  417.01
  5265.5  417.47  5294.7  417.64  5315.6  418.19  5359.5  418.11  5398.9  418.78
#Mann=8,-1,0
  4590.4    0.05       0  4863.8     0.1       0  4963.9    0.16       0
  4968.7    0.07       0  4974.7    0.16       0  5025.5    0.05       0
  5087.8    0.16       0  5252.8    0.05       0
Bank Sta=4968.7,4974.7
Exp/Cntr=0.3,0.1

Type RM Length L Ch R = 1,3585,79,79,79
BEGIN DESCRIPTION:
Mapping XS c4d75365
END DESCRIPTION:
XS GIS Cut Line= 5
      3509871.70     10366288.76      3509892.53     10366058.31
      3510018.83     10365839.56      3510080.03     10365635.14
      3510061.92     10365364.82
#Sta/Elev= 30
  4452.6  417.53  4550.1  417.17  4600.3  416.11  4624.6  416.10  4684.0  414.57
  4716.8  412.83  4732.6  412.85  4754.2  411.24  4795.1  409.19  4828.8  407.28
  4871.9  407.60  4893.4  408.33  4934.9  407.27  4955.3  407.48  4973.0  407.04
  4973.5  406.54  4978.9  406.54  4979.4  407.04  5080.6  407.36  5100.6  408.37
  5105.8  408.17  5111.9  409.21  5128.8  409.80  5183.5  411.76  5191.2  412.56
  5196.2  411.95  5203.6  412.71  5273.7  414.37  5346.1  415.31  5420.9  415.25
#Mann=5,-1,0
  4452.6    0.05       0  4795.1    0.16       0  4973.0    0.07       0
  4979.4    0.16       0  5128.8    0.05       0
Bank Sta=4973,4979.4
Exp/Cntr=0.3,0.1

Type RM Length L Ch R = 1,3506,58,58,58
BEGIN DESCRIPTION:
SOUTH MINERAL CR TRIB 11 8 1
END DESCRIPTION:
XS GIS Cut Line= 6
      3509986.29     10366336.99      3509925.08     10366075.24
      3510083.94     10365827.84      3510115.23     10365788.36
      3510125.60     10365741.91      3510085.25     10365356.61
#Sta/Elev= 30
  4386.8  417.48  4602.8  415.89  4707.4  412.50  4778.7  408.47  4827.2  407.27
  4873.8  406.43  4880.6  407.45  4886.5  406.61  4895.8  406.92  4901.7  405.33
  4909.5  408.84  4916.9  409.77  4944.4  410.64  4952.9  410.10  4959.3  410.87
  4967.4  410.38  4988.2  411.87  5005.2  411.40  5010.3  412.42  5050.2  410.49
  5078.0  408.01  5094.9  405.26  5095.4  404.76  5101.3  405.26  5108.2  406.77
  5132.8  409.14  5148.4  410.93  5188.6  412.69  5269.1  414.60  5435.0  415.20
#Mann=5,-1,0
  4386.8    0.05       0  4827.2    0.16       0  5094.9    0.07       0
  5101.3    0.16       0  5132.8    0.05       0
Bank Sta=5094.9,5101.3
Exp/Cntr=0.3,0.1

Type RM Length L Ch R = 1,3448,212,212,212
BEGIN DESCRIPTION:
Mapping XS 940b1ca5
END DESCRIPTION:
XS GIS Cut Line= 3
      3510029.26     10366214.55      3510228.47     10365633.83
      3510154.24     10365396.82
#Sta/Elev= 30
  4562.4  417.01  4683.0  413.54  4709.0  411.88  4776.9  410.66  4850.9  407.49
  4882.6  407.01  4896.6  406.32  4923.3  402.53  4927.9  404.27  4935.5  402.15
  4946.1  402.18  4953.9  405.97  4967.2  405.83  4977.8  403.81  4985.1  400.53
  4995.7  398.02  4996.2  397.52  5002.1  398.02  5009.5  399.45  5016.4  402.85
  5021.7  403.06  5030.6  405.03  5052.9  406.55  5084.2  406.53  5104.6  399.86
  5115.5  404.03  5125.8  407.02  5167.5  409.66  5293.9  414.25  5424.7  414.61
#Mann=5,-1,0
  4562.4    0.05       0  4923.3    0.16       0  4995.7    0.07       0
  5002.1    0.16       0  5052.9    0.05       0
Bank Sta=4995.7,5002.1
Exp/Cntr=0.3,0.1

Type RM Length L Ch R = 1,3236,519,519,519
BEGIN DESCRIPTION:
SOUTH MINERAL CR TRIB 11 7 1
END DESCRIPTION:
XS GIS Cut Line= 2
      3510427.98     10366140.46      3510339.43     10365491.98
#Sta/Elev= 30
  4599.0  414.85  4648.3  414.71  4688.6  414.28  4748.7  412.49  4753.8  412.72
  4789.6  411.25  4826.1  408.61  4831.1  408.56  4860.2  406.87  4877.7  406.22
  4898.3  405.58  4951.1  404.56  4961.1  403.87  4970.6  402.24  4975.7  402.86
  4981.3  400.24  4991.4  397.07  4998.3  395.86  4998.8  395.36  5004.3  395.36
  5004.8  395.86  5021.7  403.03  5031.8  404.87  5048.0  405.84  5053.0  405.74
  5073.2  406.36  5120.2  408.31  5152.9  409.38  5197.6  410.41  5253.5  411.31
#Mann=5,-1,0
  4599.0    0.05       0  4877.7     0.1       0  4998.3    0.07       0
  5004.8     0.1       0  5073.2    0.05       0
Bank Sta=4998.3,5004.8
Exp/Cntr=0.3,0.1