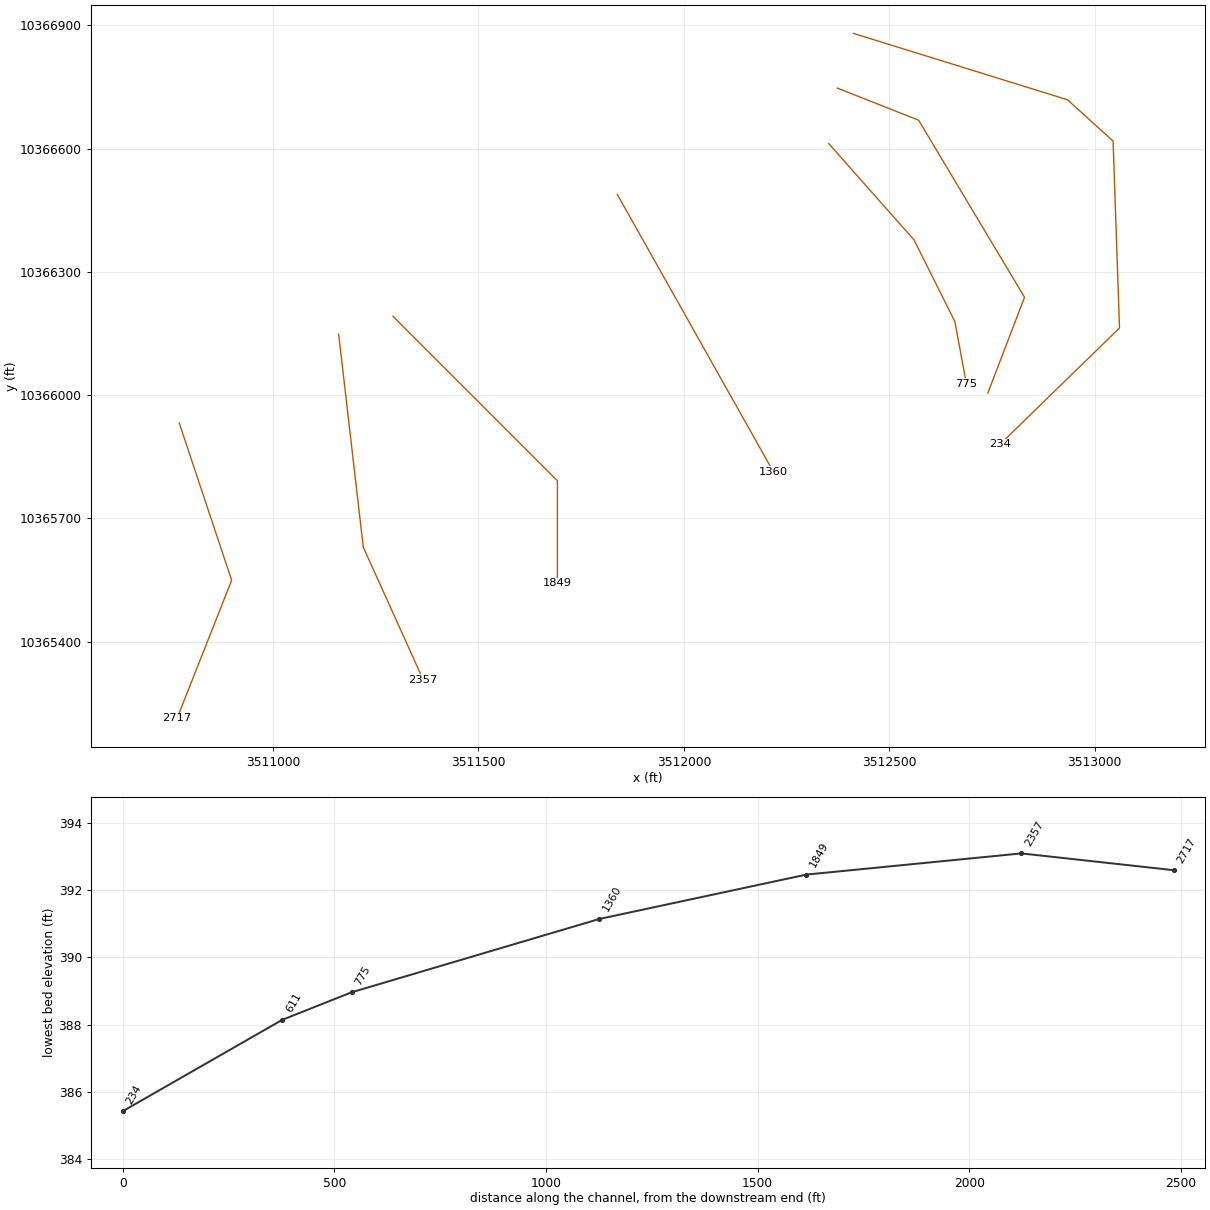
HEC-RAS study SOUTH MINERAL CR TRIB 11.prj: SOUTH MINERAL CR TRIB 11 Base Level Engineering

--- SOUTH MINERAL CR TRIB 11.g01 (geometry) --- (continued)

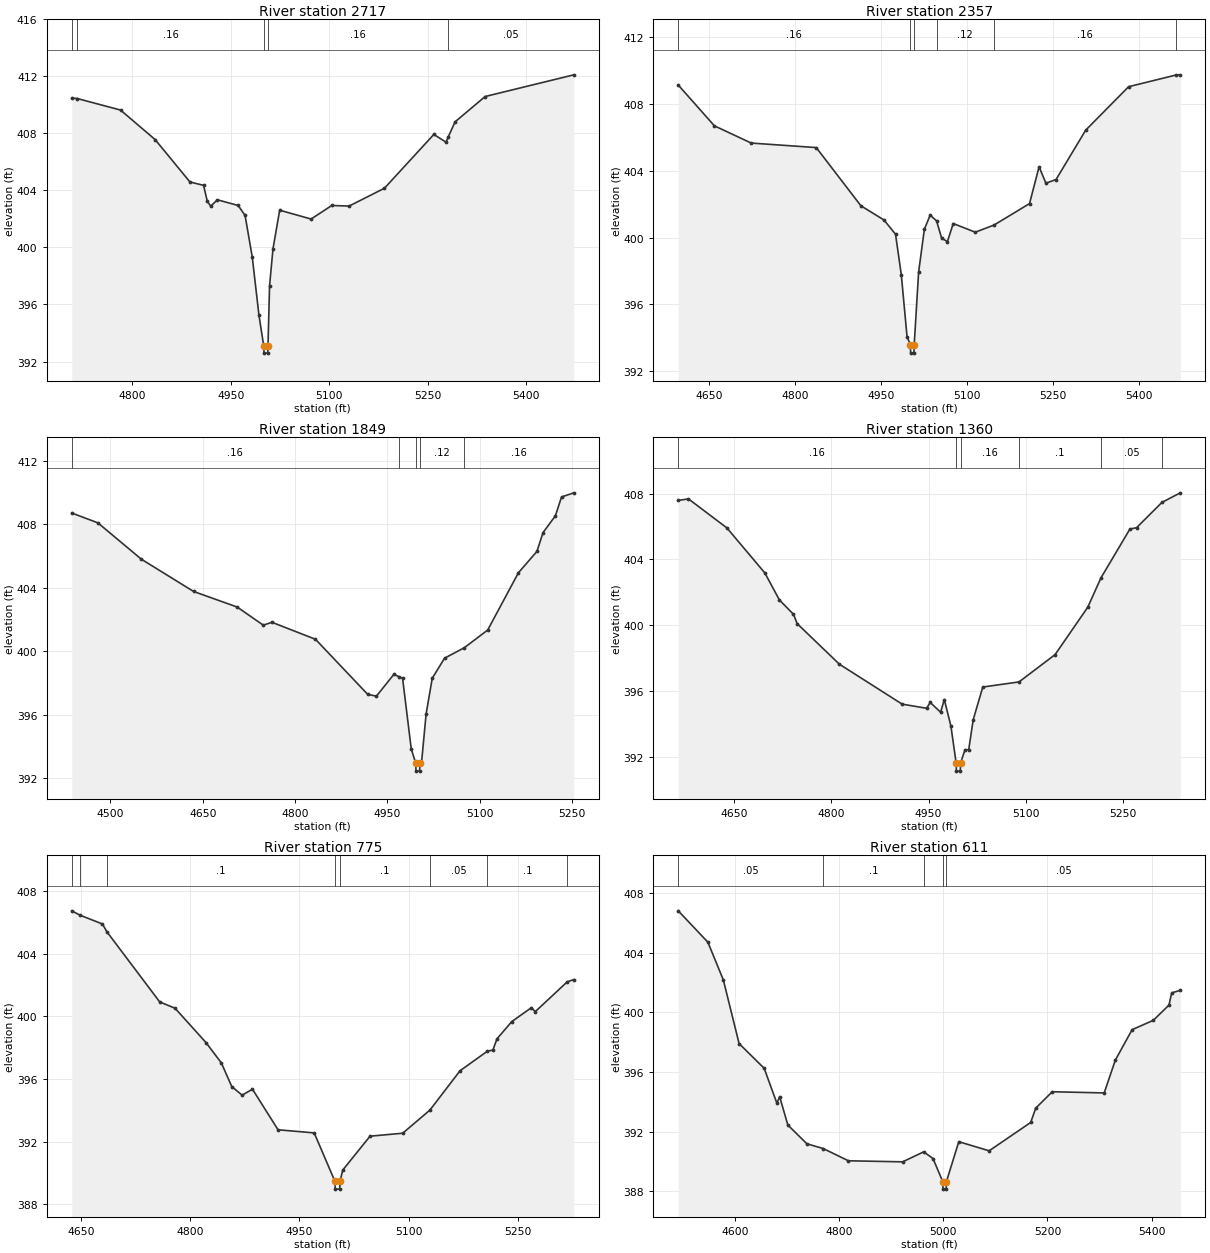
Type RM Length L Ch R = 1,2717,360,360,360
BEGIN DESCRIPTION:
SOUTH MINERAL CR TRIB 11 7 0
END DESCRIPTION:
XS GIS Cut Line= 3
      3510771.72     10365932.10      3510899.33     10365549.27
      3510766.51     10365213.31
#Sta/Elev= 30
  4707.7  410.47  4716.0  410.44  4782.0  409.63  4834.7  407.56  4887.7  404.59
  4908.5  404.35  4914.1  403.24  4919.4  402.89  4929.5  403.34  4961.2  402.94
  4971.7  402.24  4982.6  399.34  4992.8  395.26  5000.1  393.09  5000.6  392.59
  5006.1  392.59  5006.6  393.09  5009.0  397.31  5014.2  399.90  5024.4  402.61
  5072.2  401.99  5103.8  402.94  5130.2  402.90  5184.0  404.15  5259.2  407.92
  5277.9  407.38  5281.3  407.76  5291.5  408.80  5337.4  410.58  5472.5  412.10
#Mann=5,-1,0
  4707.7    0.05       0  4716.0    0.16       0  5000.1    0.07       0
  5006.6    0.16       0  5281.3    0.05       0
Bank Sta=5000.1,5006.6
Exp/Cntr=0.3,0.1

Type RM Length L Ch R = 1,2357,508,508,508
BEGIN DESCRIPTION:
SOUTH MINERAL CR TRIB 11 6 0
END DESCRIPTION:
XS GIS Cut Line= 3
      3511159.75     10366148.24      3511219.64     10365630.00
      3511365.47     10365307.09
#Sta/Elev= 30
  4595.7  409.12  4658.8  406.68  4723.1  405.65  4836.5  405.38  4914.4  401.90
  4954.7  401.05  4974.8  400.20  4984.9  397.78  4994.9  394.08  5000.7  393.59
  5001.2  393.09  5006.9  393.09  5007.4  393.59  5015.1  397.93  5025.1  400.49
  5035.2  401.34  5046.4  401.00  5055.3  399.96  5065.4  399.76  5075.5  400.84
  5114.0  400.32  5146.8  400.75  5208.6  402.03  5225.3  404.23  5237.2  403.25
  5254.9  403.47  5306.6  406.42  5381.5  409.02  5464.3  409.72  5471.7  409.73
#Mann=6,-1,0
  4595.7    0.16       0  5000.7    0.07       0  5007.4    0.16       0
  5046.4    0.12       0  5146.8    0.16       0  5464.3     0.1       0
Bank Sta=5000.7,5007.4
Exp/Cntr=0.3,0.1

Type RM Length L Ch R = 1,1849,489,489,489
BEGIN DESCRIPTION:
SOUTH MINERAL CR TRIB 11 5 0
END DESCRIPTION:
XS GIS Cut Line= 3
      3511292.14     10366191.61      3511692.11     10365791.64
      3511692.11     10365541.68
#Sta/Elev= 30
  4437.2  408.71  4479.6  408.09  4550.3  405.80  4635.1  403.77  4705.9  402.79
  4748.3  401.65  4762.4  401.83  4833.1  400.76  4918.0  397.29  4932.1  397.18
  4960.4  398.55  4968.5  398.41  4974.6  398.30  4988.7  393.85  4995.9  392.96
  4996.4  392.46  5002.2  392.46  5002.7  392.96  5005.3  392.96  5012.8  396.05
  5022.8  398.31  5042.8  399.57  5074.9  400.23  5112.8  401.34  5162.8  404.95
  5192.8  406.29  5202.8  407.48  5222.8  408.53  5232.8  409.72  5252.8  409.98
#Mann=5,-1,0
  4437.2    0.16       0  4968.5    0.12       0  4995.9    0.07       0
  5002.7    0.12       0  5074.9    0.16       0
Bank Sta=4995.9,5002.7
Exp/Cntr=0.3,0.1

Type RM Length L Ch R = 1,1360,585,585,585
BEGIN DESCRIPTION:
SOUTH MINERAL CR TRIB 11 21 0
END DESCRIPTION:
XS GIS Cut Line= 2
      3511838.11     10366488.12      3512217.73     10365813.38
#Sta/Elev= 30
  4564.0  407.59  4579.8  407.68  4639.0  405.92  4697.6  403.18  4720.0  401.54
  4741.7  400.67  4747.4  400.10  4812.4  397.64  4909.3  395.21  4946.9  394.96
  4952.6  395.31  4968.6  394.72  4974.3  395.49  4984.5  393.87  4992.5  391.64
  4993.0  391.14  4998.9  391.14  4999.4  391.64  5006.2  392.44  5011.9  392.44
  5018.9  394.27  5033.6  396.25  5089.5  396.56  5145.1  398.22  5195.5  401.10
  5215.8  402.88  5260.5  405.85  5270.7  405.93  5309.9  407.47  5338.2  408.05
#Mann=6,-1,0
  4564.0    0.16       0  4992.5    0.07       0  4999.4    0.16       0
  5089.5     0.1       0  5215.8    0.05       0  5309.9     0.1       0
Bank Sta=4992.5,4999.4
Exp/Cntr=0.3,0.1

Type RM Length L Ch R = 1,775,164,164,164
BEGIN DESCRIPTION:
SOUTH MINERAL CR TRIB 11 10 0
END DESCRIPTION:
XS GIS Cut Line= 4
      3512352.56     10366612.03      3512560.07     10366377.74
      3512659.55     10366178.78      3512687.35     10366027.94
#Sta/Elev= 30
  4637.7  406.73  4649.1  406.45  4679.8  405.89  4685.6  405.41  4758.4  400.91
  4779.4  400.51  4822.0  398.31  4842.9  397.02  4857.2  395.51  4871.4  394.96
  4885.6  395.34  4920.7  392.75  4970.3  392.55  4998.7  389.46  4999.2  388.96
  5005.2  388.96  5005.7  389.46  5009.5  390.18  5046.9  392.34  5091.7  392.53
  5129.1  394.01  5170.4  396.52  5208.0  397.77  5215.4  397.84  5221.1  398.56
  5241.4  399.66  5268.4  400.55  5273.5  400.29  5317.5  402.20  5326.5  402.34
#Mann=8,-1,0
  4637.7     0.1       0  4649.1    0.05       0  4685.6     0.1       0
  4998.7    0.07       0  5005.7     0.1       0  5129.1    0.05       0
  5208.0     0.1       0  5317.5    0.05       0
Bank Sta=4998.7,5005.7
Exp/Cntr=0.3,0.1

Type RM Length L Ch R = 1,611,377,377,377
BEGIN DESCRIPTION:
SOUTH MINERAL CR TRIB 11 1 3
END DESCRIPTION:
XS GIS Cut Line= 4
      3512373.33     10366747.17      3512571.20     10366669.06
      3512829.02     10366238.07      3512739.73     10366005.15
#Sta/Elev= 30
  4490.9  406.80  4547.8  404.70  4577.5  402.17  4607.8  397.90  4656.0  396.24
  4680.4  393.90  4685.7  394.34  4701.4  392.44  4738.0  391.18  4769.5  390.86
  4817.8  390.04  4922.0  389.97  4962.4  390.64  4980.3  390.19  4999.0  388.64
  4999.5  388.14  5005.5  388.14  5006.0  388.64  5029.8  391.32  5088.1  390.71
  5167.9  392.61  5177.6  393.57  5209.3  394.67  5309.1  394.59  5330.5  396.79
  5362.7  398.83  5403.5  399.46  5433.5  400.48  5438.8  401.30  5455.3  401.47
#Mann=5,-1,0
  4490.9    0.05       0  4769.5     0.1       0  4962.4    0.05       0
  4999.0    0.03       0  5006.0    0.05       0
Bank Sta=4999,5006
Exp/Cntr=0.3,0.1

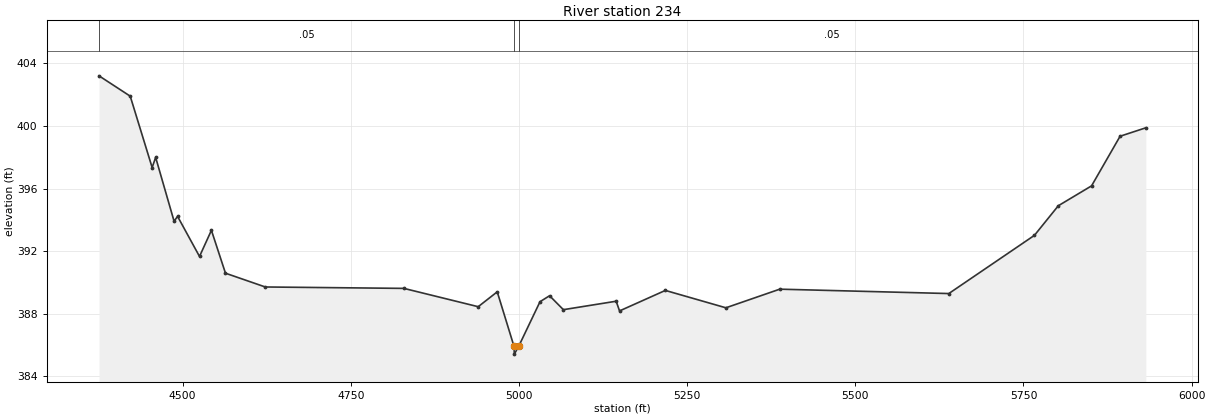
Type RM Length L Ch R = 1,234,0,0,0
BEGIN DESCRIPTION:
SOUTH MINERAL CR TRIB 11 1 0
END DESCRIPTION:
XS GIS Cut Line= 5
      3512412.53     10366880.31      3512933.40     10366718.84
      3513044.51     10366618.15      3513060.14     10366163.29
      3512769.34     10365880.25
#Sta/Elev= 30
  4375.7  403.20  4422.1  401.90  4454.7  397.34  4459.9  397.99  4487.3  393.91
  4492.5  394.22  4525.1  391.66  4542.8  393.33  4563.7  390.59  4622.9  389.71
  4828.9  389.62  4939.4  388.45  4967.7  389.40  4992.6  385.92  4993.1  385.42
  4999.6  385.92  5031.3  388.77  5045.5  389.15  5066.0  388.26  5144.5  388.80
  5149.5  388.18  5217.6  389.49  5307.6  388.38  5387.7  389.57  5639.0  389.29
  5766.3  393.01  5801.8  394.90  5851.2  396.17  5893.6  399.34  5931.9  399.88
#Mann=3,-1,0
  4375.7    0.05       0  4992.6   0.035       0  4999.6    0.05       0
Bank Sta=4992.6,4999.6
Exp/Cntr=0.3,0.1

Chan Stop Cuts=-1