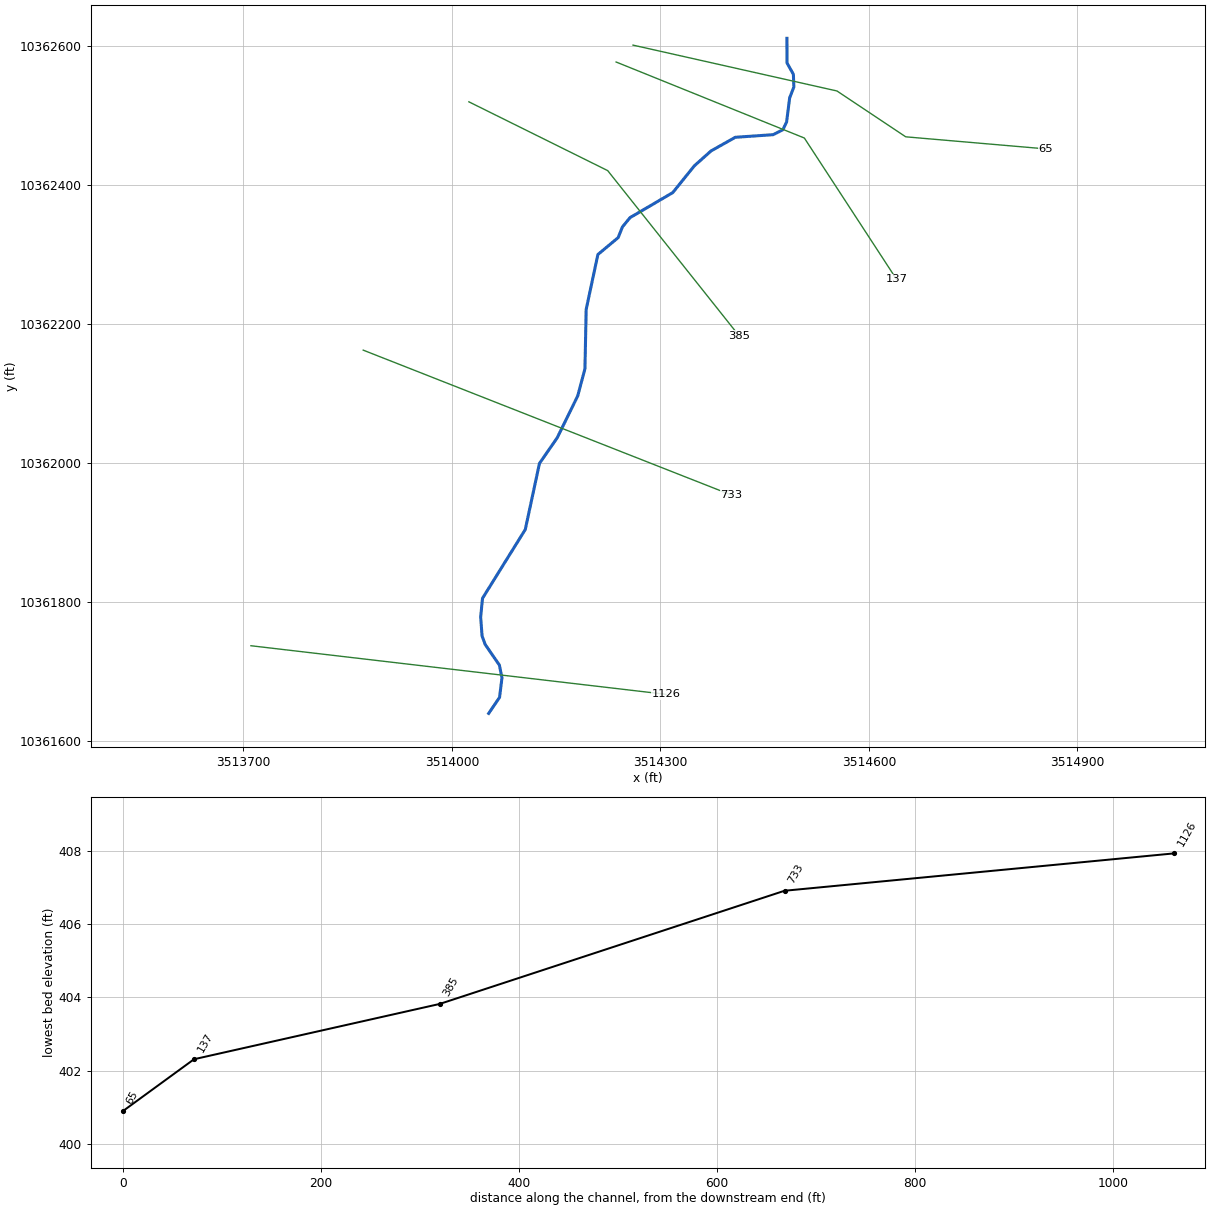
--- SOUTH MINERAL CR TRIB 12 1.prj (project) ---

Proj Title=SOUTH MINERAL CR TRIB 12 1 Base Level Engineering
Current Plan=p01
Default Exp/Contr=0.3,0.1
English Units
Geom File=g01
Flow File=f01
Plan File=p01
Y Axis Title=Elevation
X Axis Title(PF)=Main Channel Distance
X Axis Title(XS)=Station
BEGIN DESCRIPTION:
SOUTH MINERAL CR TRIB 12 1
END DESCRIPTION:
DSS Export Rating Curves= 0
DSS Export Rating Curve Sorted= 0
DSS Export Volume Flow Curves= 0
DXF OffsetX= 0
DXF OffsetY= 0
DXF ScaleX= 1
DXF ScaleY= 10

--- SOUTH MINERAL CR TRIB 12 1.p01 (plan) ---

Plan Title=Multiple Run
Short Identifier=Multiple
Geom File=g01
Flow File=f01
Subcritical Flow
K Sum by GR= 0
Std Step Tol= 0.01
Critical Tol= 0.01
Num of Std Step Trials= 20
Max Error Tol= 0.3
Flow Tol Ratio= 0.001
Split Flow NTrial= 30
Split Flow Tol= 0.02
Split Flow Ratio= 0.02
Log Output Level= 0
Friction Slope Method= 1
Unsteady Friction Slope Method= 2
Unsteady Bridges Friction Slope Method= 1
Parabolic Critical Depth
Global Vel Dist=  1 , 1 , 1
Global Log Level= 0
CheckData=True
Encroach Param= -1, 0, 0, 0
BEGIN DESCRIPTION:
Multiple Run
END DESCRIPTION:

--- SOUTH MINERAL CR TRIB 12 1.f01 (steady flow) ---

Flow Title=Multiple
Number of Profiles=7
Profile Names=10-year,25-year,50-year,1pct_min,100-year,1pct_plu,500-year
River Rch & RM= SOUTH MINERAL CR,Reach-1,1126
     578     774     932     820    1109    1500    1566
Boundary for River Rch & Prof#=SOUTH MINERAL CR,Reach-1,1
Up Type=0
Dn Type=3
Dn Slope=0.005
Boundary for River Rch & Prof#=SOUTH MINERAL CR,Reach-1,2
Up Type=0
Dn Type=3
Dn Slope=0.005
Boundary for River Rch & Prof#=SOUTH MINERAL CR,Reach-1,3
Up Type=0
Dn Type=3
Dn Slope=0.005
Boundary for River Rch & Prof#=SOUTH MINERAL CR,Reach-1,4
Up Type=0
Dn Type=3
Dn Slope=0.005
Boundary for River Rch & Prof#=SOUTH MINERAL CR,Reach-1,5
Up Type=0
Dn Type=3
Dn Slope=0.005
Boundary for River Rch & Prof#=SOUTH MINERAL CR,Reach-1,6
Up Type=0
Dn Type=3
Dn Slope=0.005
Boundary for River Rch & Prof#=SOUTH MINERAL CR,Reach-1,7
Up Type=0
Dn Type=3
Dn Slope=0.005

--- SOUTH MINERAL CR TRIB 12 1.g01 (geometry) ---

Geom Title=Existing Conditions
Program Version=4.10

River Reach=SOUTH MINERAL CR,Reach-1
Reach XY= 30
      3514053.02     10361640.37      3514068.63     10361663.36
      3514072.08     10361691.42       3514068.4     10361709.84
        3514048.     10361739.43      3514043.47     10361751.72
      3514041.46     10361778.98      3514044.11     10361805.95
      3514105.65     10361904.89      3514126.05     10362000.01
      3514151.57     10362036.86      3514181.08     10362097.07
       3514191.5     10362136.24      3514193.27     10362221.62
      3514210.11     10362300.57      3514239.28     10362324.88
      3514245.44     10362340.31      3514256.36     10362353.64
       3514317.8     10362389.64      3514348.99     10362428.27
      3514372.89     10362449.59      3514407.85     10362469.25
      3514462.31     10362473.02      3514476.35     10362480.15
      3514481.66     10362491.36      3514486.06     10362526.15
      3514492.11     10362541.64      3514491.41     10362559.92
      3514482.26     10362576.15      3514482.11     10362611.64

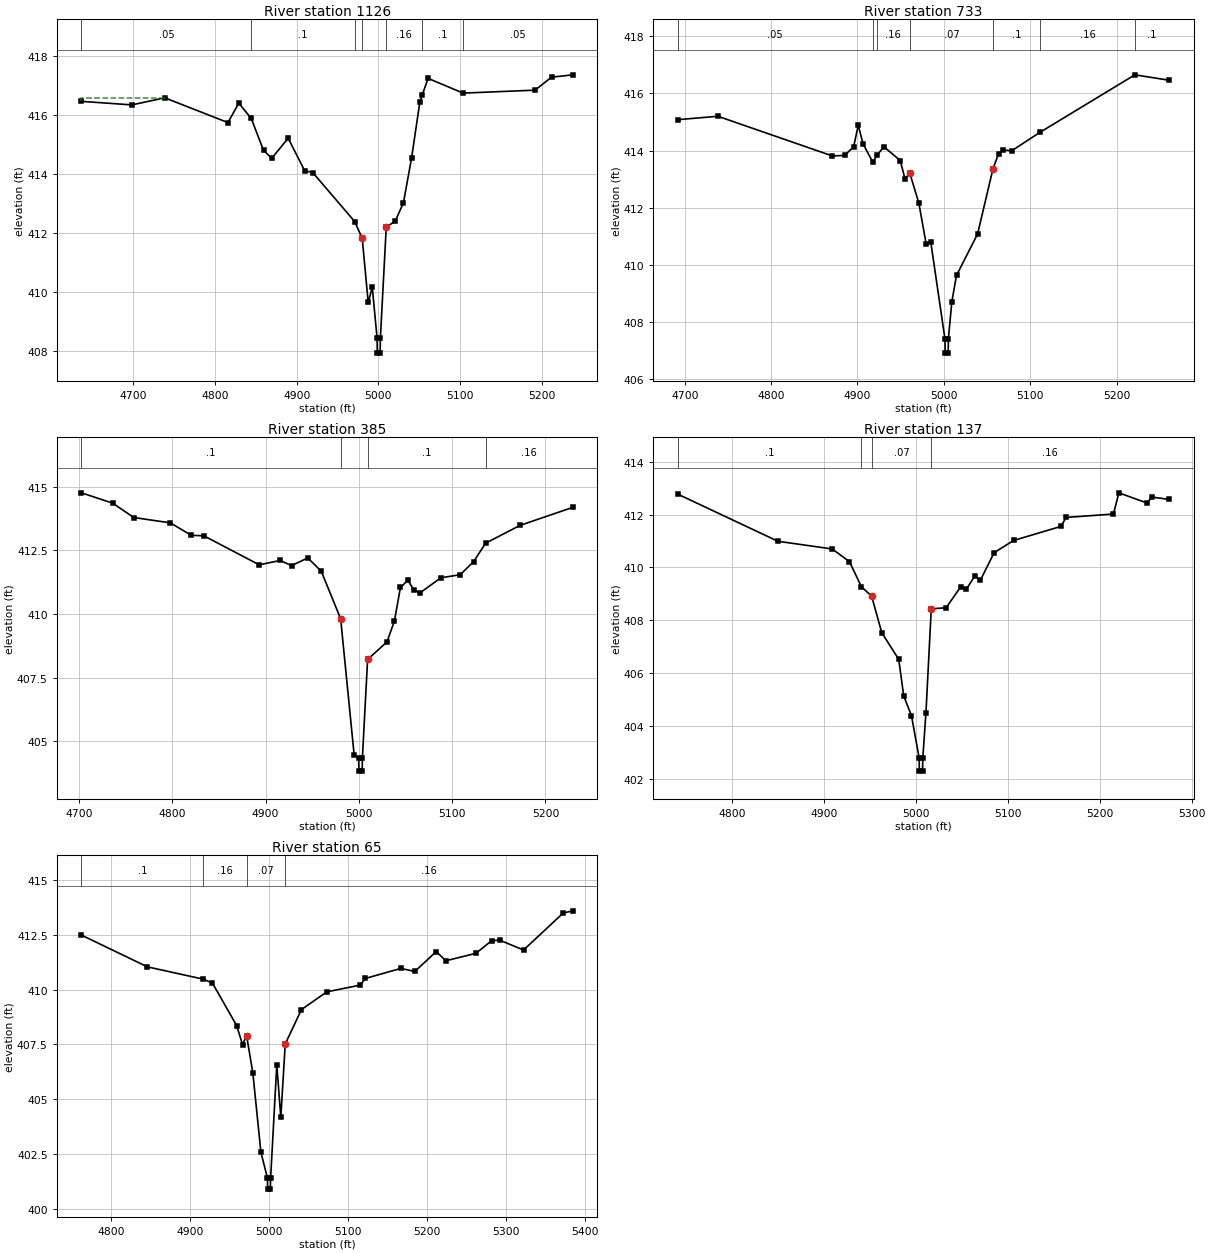
Type RM Length L Ch R = 1 ,1126    ,393,393,393
BEGIN DESCRIPTION:
SOUTH MINERAL CR TRIB 12 1 3 0
END DESCRIPTION:
XS GIS Cut Line= 2
      3513710.91     10361737.69      3514308.13     10361667.77
#Sta/Elev= 30
  4636.7  416.47  4698.3  416.35  4738.6  416.59  4815.9  415.75  4829.2  416.41
  4844.4  415.89  4859.4  414.81  4869.5  414.54  4889.6  415.22  4909.7  414.12
  4919.8  414.05  4971.1  412.39  4980.2  411.82  4987.5  409.65  4992.5  410.16
  4998.4  408.43  4998.6  407.93  5002.1  407.93  5002.4  408.43  5009.6  412.21
  5020.5   412.4  5030.6  413.03  5040.6  414.55  5050.7  416.45  5053.8   416.7
  5060.8  417.25  5103.6  416.75  5191.7  416.85  5211.8  417.29    5238  417.37
#Mann= 7 ,-1 , 0
  4636.7     .05       0  4844.4      .1       0  4971.1     .16       0
  4980.2     .07       0  5009.6     .16       0  5053.8      .1       0
  5103.6     .05       0
#XS Ineff= 2 , 0
         4740.08  416.59
Permanent Ineff=
       F       F
Bank Sta=4980.2,5009.6
XS Rating Curve= 0 ,0
Exp/Cntr=0.3,0.1

Type RM Length L Ch R = 1 ,733     ,348,348,348
BEGIN DESCRIPTION:
SOUTH MINERAL CR TRIB 12 1 2 0
END DESCRIPTION:
XS GIS Cut Line= 2
      3513872.42     10362163.03      3514401.91      10361954.7
#Sta/Elev= 30
    4692  415.08  4738.4   415.2  4871.1  413.81  4885.1  413.83  4895.6  414.13
  4900.9  414.88  4906.6  414.23  4917.8  413.59  4922.6  413.84  4930.7  414.13
  4949.6  413.65  4955.1     413  4960.5  413.22  4971.1  412.16  4979.5  410.74
  4984.9   410.8  5001.3  407.41  5001.6  406.91  5005.1  406.91  5005.3  407.41
  5009.3  408.71  5014.7  409.63  5039.1  411.08    5057  413.37  5063.5  413.89
  5068.8  414.02  5078.5  413.99  5111.5  414.64  5221.2  416.65    5261  416.46
#Mann= 7 ,-1 , 0
    4692     .05       0  4917.8      .1       0  4922.6     .16       0
  4960.5     .07       0    5057      .1       0  5111.5     .16       0
  5221.2      .1       0
Bank Sta=4960.5,5057
XS Rating Curve= 0 ,0
Exp/Cntr=0.3,0.1

Type RM Length L Ch R = 1 ,385     ,248,248,248
BEGIN DESCRIPTION:
Mapping XS ca633b2f
END DESCRIPTION:
XS GIS Cut Line= 3
      3514024.52      10362520.3      3514224.21     10362421.33
      3514413.43     10362183.49
#Sta/Elev= 30
  4702.7  414.76  4736.3  414.35  4758.7  413.79  4797.9  413.58  4820.4  413.09
  4833.9  413.07  4893.2  411.93  4915.6   412.1  4927.9   411.9  4945.3   412.2
  4959.7  411.68  4980.5  409.81    4995  404.45  4999.8  404.32  5000.1  403.82
  5003.6  403.82  5003.8  404.32  5009.4  408.21  5030.2   408.9  5038.2  409.73
  5044.6  411.04  5052.6  411.32    5059  410.94  5065.7  410.83  5087.9  411.42
  5108.7  411.54  5123.1  412.06  5135.9  412.78  5172.8  413.48  5229.5  414.19
#Mann= 4 ,-1 , 0
  4702.7      .1       0  4980.5     .07       0  5009.4      .1       0
  5135.9     .16       0
Bank Sta=4980.5,5009.4
XS Rating Curve= 0 ,0
Exp/Cntr=0.3,0.1

Type RM Length L Ch R = 1 ,137     ,72,72,72
BEGIN DESCRIPTION:
Mapping XS 95b24beb
END DESCRIPTION:
XS GIS Cut Line= 3
      3514236.39     10362577.57      3514507.19      10362468.2
      3514639.79     10362264.99
#Sta/Elev= 30
  4740.9  412.77  4849.9  410.99  4908.9   410.7  4927.7  410.22  4940.7  409.27
  4951.8  408.92  4962.8  407.54  4981.3  406.53  4986.7  405.15  4995.1  404.41
  5003.5  402.81  5003.7  402.31  5007.2  402.31  5007.5  402.81  5010.9  404.52
  5016.7  408.44  5032.9  408.48  5048.9  409.28  5054.9  409.18    5064  409.68
    5070  409.51  5085.1  410.56  5106.2  411.02  5157.6  411.55  5163.5  411.89
  5214.9  412.02  5220.8  412.82  5251.1  412.44    5257  412.66  5275.6  412.57
#Mann= 4 ,-1 , 0
  4740.9      .1       0  4940.7     .16       0  4951.8     .07       0
  5016.7     .16       0
Bank Sta=4951.8,5016.7
XS Rating Curve= 0 ,0
Exp/Cntr=0.3,0.1

Type RM Length L Ch R = 1 ,65      ,0,0,0
BEGIN DESCRIPTION:
SOUTH MINERAL CR TRIB 12 1 1 0
END DESCRIPTION:
XS GIS Cut Line= 4
      3514260.63     10362601.89      3514554.07     10362535.91
      3514653.03     10362469.94      3514854.38     10362452.58
#Sta/Elev= 30
  4762.6  412.49  4846.1  411.04  4916.6  410.48  4928.3   410.3  4958.9  408.36
  4966.4  407.49  4971.5   407.9  4979.4   406.2  4989.6  402.58  4997.9  401.39
  4998.1  400.89  5001.6  400.89  5001.9  401.39  5009.7  406.57  5014.8  404.17
  5020.4  407.52  5040.9  409.09    5073   409.9  5115.6  410.21  5121.6  410.51
  5166.7  410.97  5184.3  410.83  5211.5  411.74  5223.6  411.32  5261.7  411.66
  5281.7  412.24  5291.8  412.26  5321.9  411.81  5372.1   413.5  5384.4   413.6
#Mann= 4 ,-1 , 0
  4762.6      .1       0  4916.6     .16       0  4971.5     .07       0
  5020.4     .16       0
Bank Sta=4971.5,5020.4
XS Rating Curve= 0 ,0
Exp/Cntr=0.3,0.1

Chan Stop Cuts=-1
Use User Specified Reach Order=0
Composite Channel Slope=5