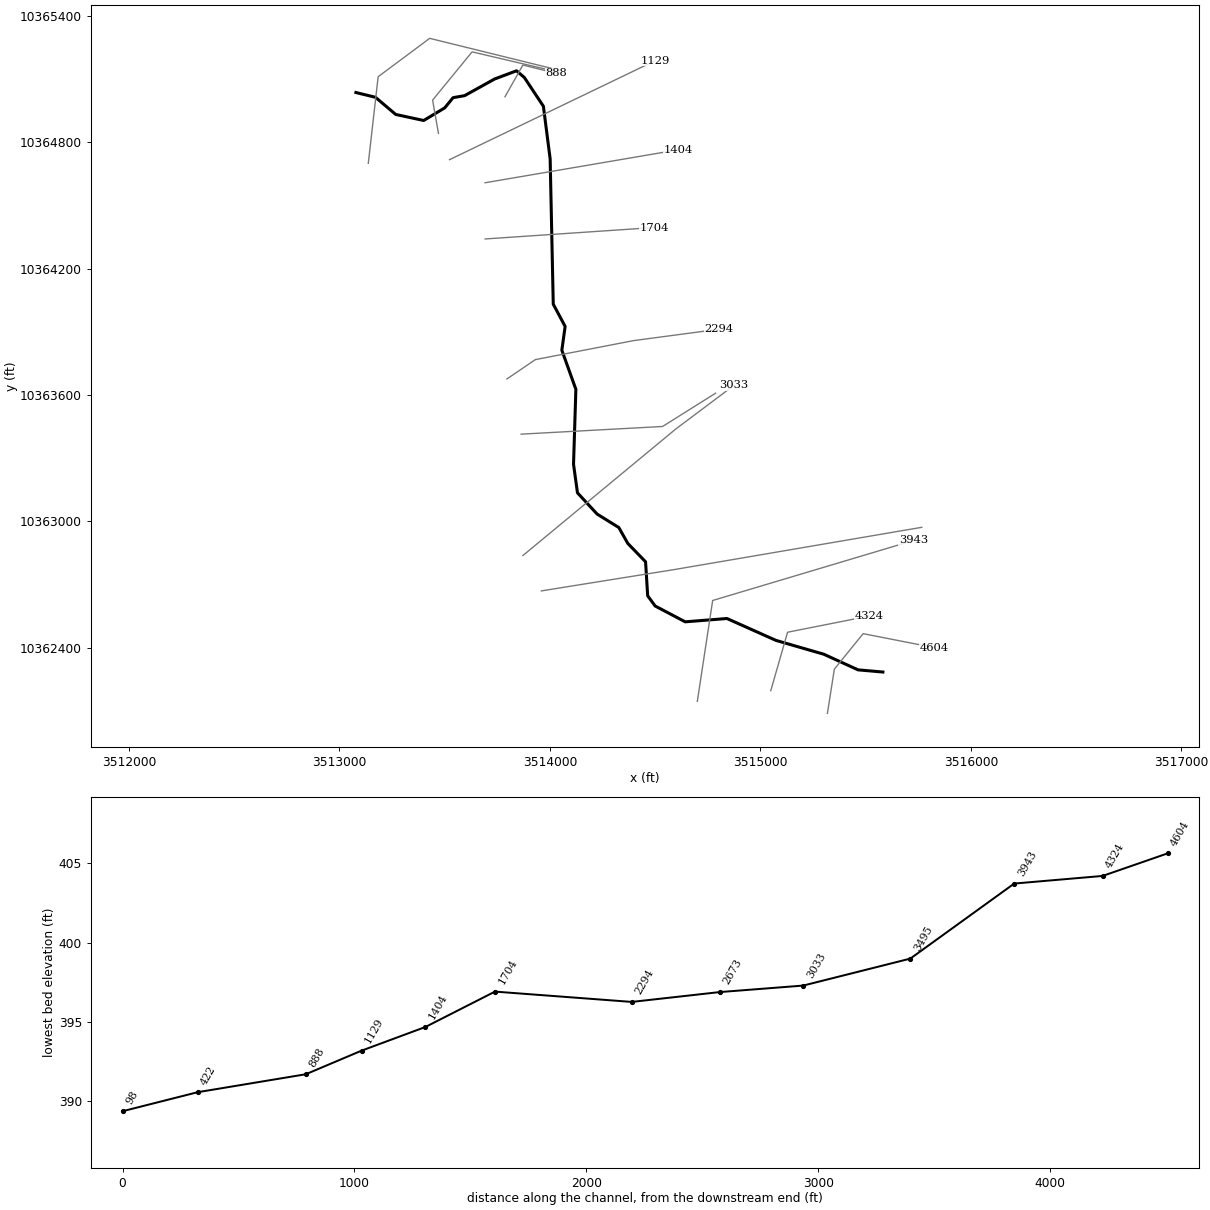
--- SOUTH MINERAL CR TRIB 12.prj (project) ---

Proj Title=SOUTH MINERAL CR TRIB 12 Base Level Engineering
Current Plan=p01
Default Exp/Contr=0.3,0.1
English Units
Geom File=g01
Flow File=f01
Plan File=p01
Y Axis Title=Elevation
X Axis Title(PF)=Main Channel Distance
X Axis Title(XS)=Station
BEGIN DESCRIPTION:
SOUTH MINERAL CR TRIB 12
END DESCRIPTION:
DSS Export Rating Curves= 0
DSS Export Rating Curve Sorted= 0
DSS Export Volume Flow Curves= 0
DXF OffsetX= 0
DXF OffsetY= 0
DXF ScaleX= 1
DXF ScaleY= 10

--- SOUTH MINERAL CR TRIB 12.p01 (plan) ---

Plan Title=Multiple Run
Short Identifier=Multiple
Geom File=g01
Flow File=f01
Subcritical Flow
K Sum by GR= 0
Std Step Tol= 0.01
Critical Tol= 0.01
Num of Std Step Trials= 20
Max Error Tol= 0.3
Flow Tol Ratio= 0.001
Split Flow NTrial= 30
Split Flow Tol= 0.02
Split Flow Ratio= 0.02
Log Output Level= 0
Friction Slope Method= 1
Unsteady Friction Slope Method= 2
Unsteady Bridges Friction Slope Method= 1
Parabolic Critical Depth
Global Vel Dist=  1 , 1 , 1
Global Log Level= 0
CheckData=True
Encroach Param= -1, 0, 0, 0
BEGIN DESCRIPTION:
Multiple Run
END DESCRIPTION:

--- SOUTH MINERAL CR TRIB 12.f01 (steady flow) ---

Flow Title=Multiple
Program Version=4.10
Number of Profiles= 7
Profile Names=10-year,25-year,50-year,1pct_min,100-year,1pct_plu,500-year
River Rch & RM=SOUTH MINERAL CR,Reach-1         ,4604
     666     904    1098     975    1319    1783    1895
River Rch & RM=SOUTH MINERAL CR,Reach-1         ,3495
    1482    2106    2637    2407    3255    4403    4952
Boundary for River Rch & Prof#=SOUTH MINERAL CR,Reach-1         , 1
Up Type= 0
Dn Type= 3
Dn Slope=0.005
Boundary for River Rch & Prof#=SOUTH MINERAL CR,Reach-1         , 2
Up Type= 0
Dn Type= 3
Dn Slope=0.005
Boundary for River Rch & Prof#=SOUTH MINERAL CR,Reach-1         , 3
Up Type= 0
Dn Type= 3
Dn Slope=0.005
Boundary for River Rch & Prof#=SOUTH MINERAL CR,Reach-1         , 4
Up Type= 0
Dn Type= 3
Dn Slope=0.005
Boundary for River Rch & Prof#=SOUTH MINERAL CR,Reach-1         , 5
Up Type= 0
Dn Type= 3
Dn Slope=0.005
Boundary for River Rch & Prof#=SOUTH MINERAL CR,Reach-1         , 6
Up Type= 0
Dn Type= 3
Dn Slope=0.005
Boundary for River Rch & Prof#=SOUTH MINERAL CR,Reach-1         , 7
Up Type= 0
Dn Type= 3
Dn Slope=0.005
DSS Import GetInterval= 0
DSS Import GetPeak= 0
DSS Import FillOption= 0

--- SOUTH MINERAL CR TRIB 12.g01 (geometry) ---

Geom Title=Existing Conditions
Program Version=4.10

River Reach=SOUTH MINERAL CR,Reach-1
Reach XY= 30
      3515581.47     10362284.36      3515463.46     10362294.73
      3515300.96     10362368.87      3515073.37      10362434.7
      3514840.79     10362538.62      3514642.58     10362522.85
      3514499.46     10362598.13      3514464.17     10362646.53
      3514454.13     10362808.09      3514369.88     10362895.11
      3514327.05     10362970.78      3514223.97     10363034.79
      3514130.66     10363135.71      3514111.94     10363271.35
      3514123.06     10363627.24      3514056.44     10363813.22
      3514072.06     10363926.07      3514015.64     10364031.97
      3514000.88     10364722.08      3513968.76     10364972.08
      3513878.49     10365108.36      3513841.16     10365140.48
      3513736.99     10365101.42      3513594.63     10365022.43
      3513539.94     10365012.88      3513500.01     10364964.27
      3513400.19     10364904.37      3513267.38     10364933.02
      3513171.02     10365014.61      3513078.24     10365037.24

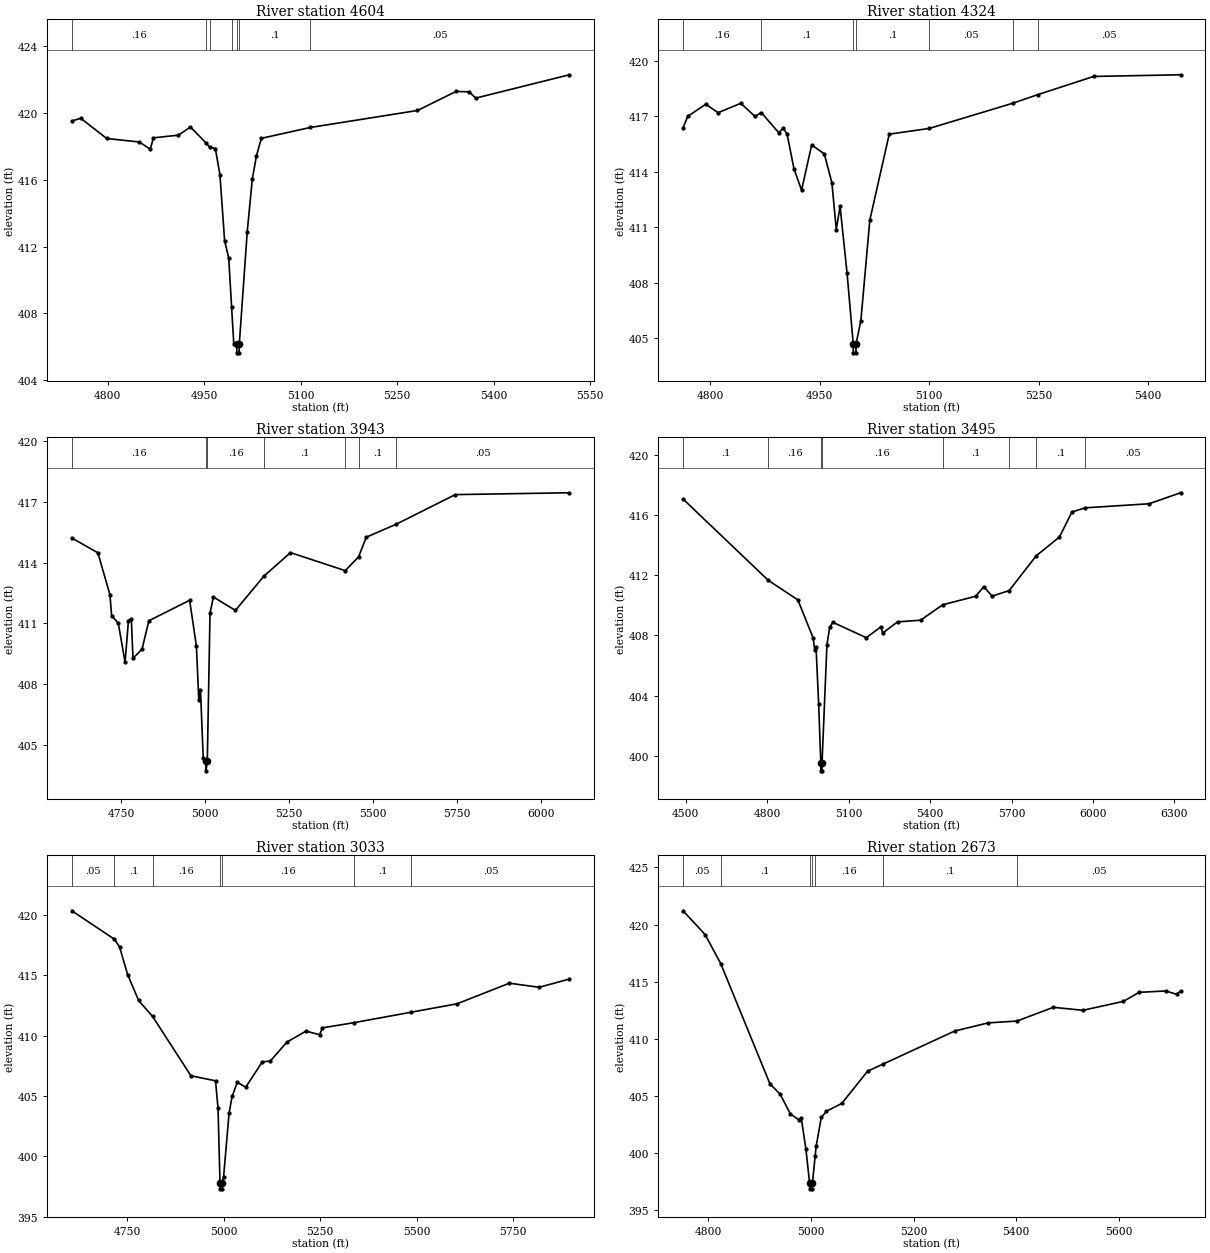
Type RM Length L Ch R = 1 ,4604    ,280,280,280
BEGIN DESCRIPTION:
SOUTH MINERAL CR TRIB 12 28 0
END DESCRIPTION:
XS GIS Cut Line= 4
      3515317.95     10362087.96      3515350.94     10362298.06
      3515487.71     10362466.64      3515824.92     10362400.49
#Sta/Elev= 30
  4744.4  419.53  4758.3  419.69  4798.6  418.48  4849.4  418.27  4866.2  417.84
  4871.3  418.52  4910.1  418.68  4928.8  419.17  4953.3   418.2  4959.1  417.95
  4967.5  417.88  4974.6  416.32  4981.9  412.36  4988.3  411.31  4992.8  408.37
  4996.2  406.15  5000.7  406.13  5000.9  405.63  5004.4  405.63  5004.7  406.13
  5017.1   412.9    5025  416.06  5031.4  417.43    5039  418.49    5115  419.14
  5281.8  420.16  5341.7   421.3  5362.1  421.28  5372.3   420.9  5517.8   422.3
#Mann= 7 ,-1 , 0
  4744.4     .16       0  4953.3      .1       0  4959.1     .16       0
  4992.8      .1       0  5000.7     .07       0  5004.7      .1       0
    5115     .05       0
Bank Sta=5000.7,5004.7
XS Rating Curve= 0 ,0
Exp/Cntr=0.3,0.1

Type RM Length L Ch R = 1 ,4324    ,381,381,381
BEGIN DESCRIPTION:
SOUTH MINERAL CR TRIB 12 18 0
END DESCRIPTION:
XS GIS Cut Line= 3
      3515048.85     10362195.61      3515128.72     10362473.41
      3515514.16     10362549.81
#Sta/Elev= 30
  4762.7  416.38    4769  416.99  4793.8  417.65  4810.6  417.19  4841.8   417.7
  4861.2  416.99  4869.9   417.2  4893.8  416.11  4900.1  416.35  4905.3  416.03
  4914.7  414.15  4925.1  413.01    4939  415.45  4956.3  414.96  4966.7   413.4
  4972.7  410.87  4977.9  412.13  4987.5  408.51  4995.9  404.71  4996.1  404.21
  4999.6  404.21  4999.9  404.71  5006.4  405.95  5018.7  411.39  5045.3  416.03
  5100.2  416.34  5214.5   417.7  5249.3  418.17  5325.5  419.15  5444.7  419.24
#Mann= 7 ,-1 , 0
  4762.7     .16       0  4869.9      .1       0  4995.9     .07       0
  4999.9      .1       0  5100.2     .05       0  5214.5      .1       0
  5249.3     .05       0
Bank Sta=4995.9,4999.9
XS Rating Curve= 0 ,0
Exp/Cntr=0.3,0.1

Type RM Length L Ch R = 1 ,3943    ,448,448,448
BEGIN DESCRIPTION:
SOUTH MINERAL CR TRIB 12 8 0
END DESCRIPTION:
XS GIS Cut Line= 3
      3514699.98     10362145.03      3514772.89     10362624.19
      3515727.23     10362909.32
#Sta/Elev= 30
  4602.9  415.21  4680.4  414.48  4716.3  412.41  4721.3  411.38  4741.1  411.01
  4761.3  409.08  4771.4  411.14  4779.9  411.23  4784.9  409.28  4811.9  409.73
  4832.1  411.13  4953.5  412.14  4973.7  409.87  4980.7  407.24  4985.8  407.72
    4994  404.35  5002.1  404.23  5002.3  403.73  5006.1  404.23  5014.2  411.51
  5024.3   412.3  5089.8  411.64  5174.6  413.33  5253.7  414.49  5416.8   413.6
  5456.4  414.28  5479.3  415.25  5568.4  415.89  5744.3  417.35  6083.6  417.44
#Mann= 7 ,-1 , 0
  4602.9     .16       0  5002.1     .07       0  5006.1     .16       0
  5174.6      .1       0  5416.8     .05       0  5456.4      .1       0
  5568.4     .05       0
Bank Sta=5002.1,5006.1
XS Rating Curve= 0 ,0
Exp/Cntr=0.3,0.1

Type RM Length L Ch R = 1 ,3495    ,462,462,462
BEGIN DESCRIPTION:
SOUTH MINERAL CR TRIB 12 7 2
END DESCRIPTION:
XS GIS Cut Line= 3
      3513959.06     10362669.76       3514591.9     10362771.33
      3515766.37     10362971.85
#Sta/Elev= 30
  4490.1  417.06  4803.9  411.66  4912.8  410.36  4969.2  407.83  4974.8  407.01
  4979.8  407.21  4989.5  403.41  4997.4   399.5  4997.7     399  5001.5     399
  5001.8   399.5  5019.8  407.36    5030  408.54  5041.8  408.87  5164.7  407.85
  5219.8  408.58  5224.8  408.15  5279.9   408.9  5364.6  409.01  5446.8  410.04
  5567.5   410.6  5597.9  411.24  5628.3  410.61  5691.2  410.98  5790.8  413.29
  5876.3  414.54  5922.5   416.2  5970.7  416.48  6206.6  416.75  6322.5  417.48
#Mann= 8 ,-1 , 0
  4490.1      .1       0  4803.9     .16       0  4997.4     .07       0
  5001.8     .16       0  5446.8      .1       0  5691.2     .05       0
  5790.8      .1       0  5970.7     .05       0
Bank Sta=4997.4,5001.8
XS Rating Curve= 0 ,0
Exp/Cntr=0.3,0.1

Type RM Length L Ch R = 1 ,3033    ,360,360,360
BEGIN DESCRIPTION:
SOUTH MINERAL CR TRIB 12 7 1
END DESCRIPTION:
XS GIS Cut Line= 3
      3513871.77     10362837.99      3514597.47     10363438.69
      3514875.02     10363646.85
#Sta/Elev= 30
  4606.6  420.34    4717  417.98  4730.2  417.35    4751  415.06  4779.6  412.91
  4815.7  411.59  4915.1  406.67  4978.9  406.25  4985.4  403.98  4990.5   397.8
    4991   397.3  4995.6   397.3    4996   397.8  4999.8   398.3  5014.1  403.59
  5021.9  404.96  5035.4  406.13  5057.1  405.72  5100.1  407.82  5120.9  407.89
  5163.9  409.46  5213.4  410.37  5248.5  410.07  5256.1  410.64  5337.9  411.07
  5486.7  411.94  5604.5  412.63  5740.5  414.34  5817.6     414  5895.6  414.68
#Mann= 7 ,-1 , 0
  4606.6     .05       0    4717      .1       0  4815.7     .16       0
  4990.5     .07       0    4996     .16       0  5337.9      .1       0
  5486.7     .05       0
Bank Sta=4990.5,4996
XS Rating Curve= 0 ,0
Exp/Cntr=0.3,0.1

Type RM Length L Ch R = 1 ,2673    ,379,379,379
BEGIN DESCRIPTION:
SOUTH MINERAL CR TRIB 12 7 0
END DESCRIPTION:
XS GIS Cut Line= 3
      3513863.07     10363414.38      3514534.97     10363450.84
      3514786.71     10363608.83
#Sta/Elev= 30
  4750.6   421.2  4793.5  419.12  4824.2  416.56  4919.9  406.07  4939.9  405.16
  4959.9  403.43  4975.9  402.94  4980.9  403.11    4990   400.4  4997.3  397.39
  4997.7  396.89  5002.3  396.89  5002.8  397.39  5008.1  399.75    5010   400.6
    5020  403.13    5030  403.67  5060.1  404.36  5110.2  407.17  5139.7  407.78
  5280.4  410.69  5345.7   411.4  5401.7  411.56  5472.6  412.76  5530.4   412.5
  5609.3  413.28  5639.9  414.07  5691.7  414.19    5713   413.9  5720.7  414.18
#Mann= 7 ,-1 , 0
  4750.6     .05       0  4824.2      .1       0  4997.3     .07       0
  5002.8      .1       0  5008.1     .16       0  5139.7      .1       0
  5401.7     .05       0
Bank Sta=4997.3,5002.8
XS Rating Curve= 0 ,0
Exp/Cntr=0.3,0.1

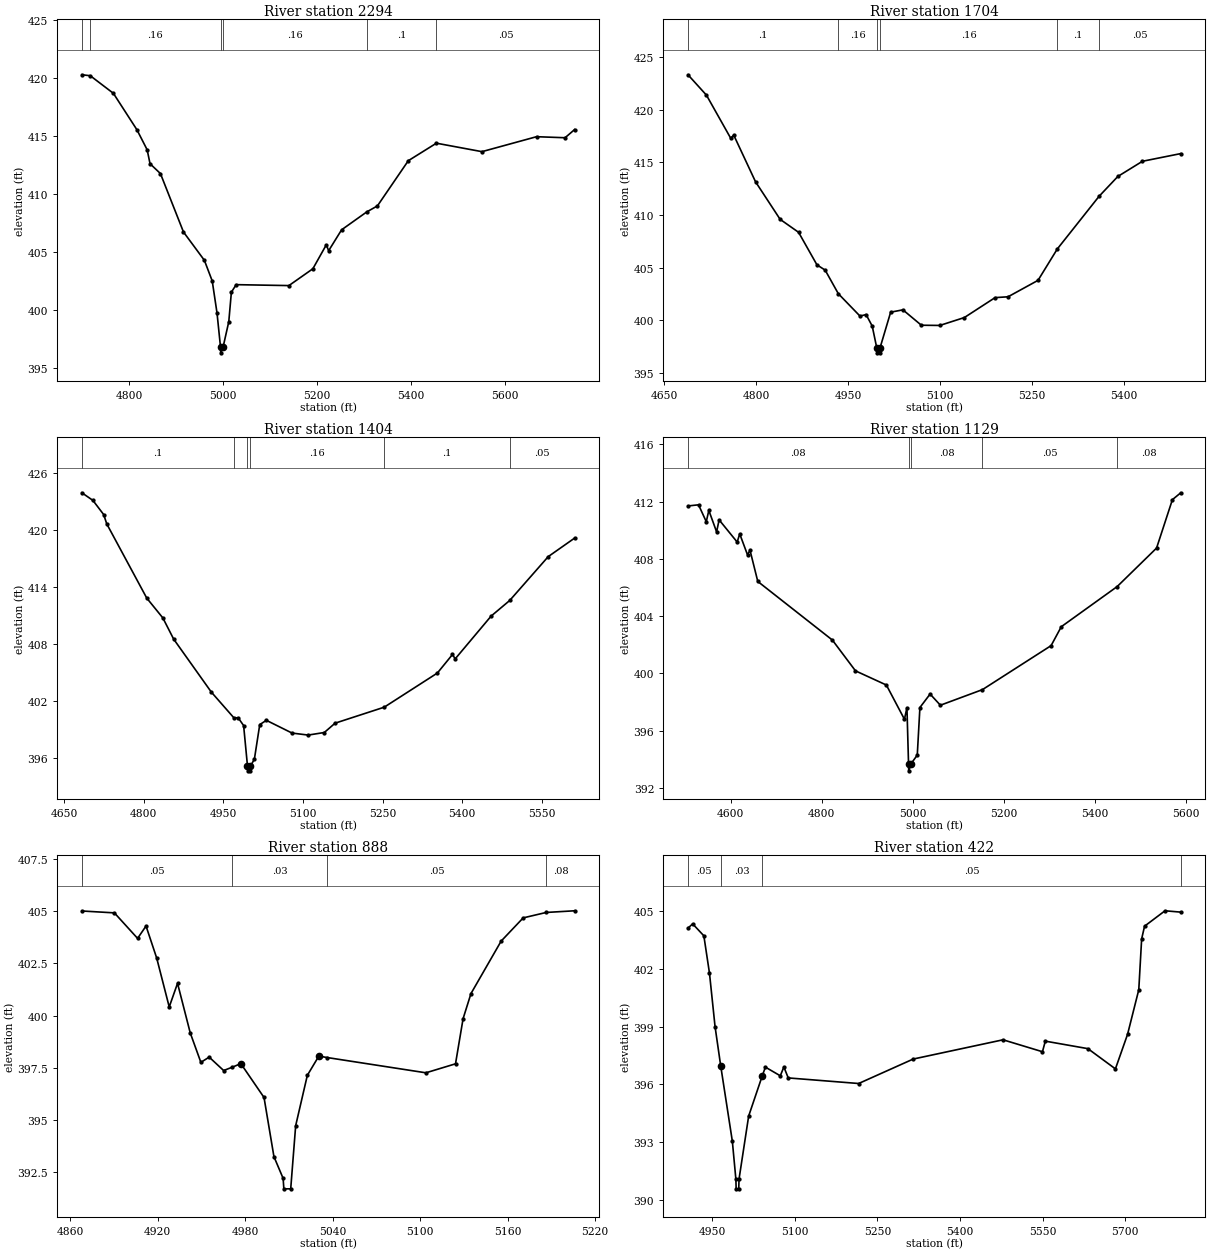
Type RM Length L Ch R = 1 ,2294    ,590,590,590
BEGIN DESCRIPTION:
SOUTH MINERAL CR TRIB 12 6 0
END DESCRIPTION:
XS GIS Cut Line= 4
      3513795.37     10363676.52       3513930.8     10363768.55
      3514397.82     10363858.83      3514802.35     10363912.65
#Sta/Elev= 30
  4699.8  420.25  4717.6  420.17  4766.8  418.65  4816.8  415.51  4838.6  413.78
  4844.7  412.58  4866.8  411.73  4915.8  406.69  4960.2  404.25  4976.9  402.47
  4987.1   399.7  4994.5  396.77    4995  396.27    5000  396.77  5012.1  398.96
  5017.6   401.5  5027.8  402.15  5139.9  402.07  5190.8  403.52  5219.3  405.58
  5224.4  405.08  5251.9  406.88  5305.6  408.43    5328  408.94  5393.7  412.84
  5453.4  414.35  5550.2  413.62  5666.3  414.91  5726.9  414.82  5747.3  415.53
#Mann= 6 ,-1 , 0
  4699.8      .1       0  4717.6     .16       0  4994.5     .07       0
    5000     .16       0  5305.6      .1       0  5453.4     .05       0
Bank Sta=4994.5,5000
XS Rating Curve= 0 ,0
Exp/Cntr=0.3,0.1

Type RM Length L Ch R = 1 ,1704    ,300,300,300
BEGIN DESCRIPTION:
SOUTH MINERAL CR TRIB 12 3 1
END DESCRIPTION:
XS GIS Cut Line= 2
      3513692.06     10364341.64      3514494.53     10364395.94
#Sta/Elev= 30
  4688.9  423.31    4719  421.38  4758.6  417.29  4763.6  417.58  4799.2  413.15
  4839.3  409.59  4869.4  408.36  4899.4  405.27  4912.8  404.77  4934.3  402.53
  4969.6  400.41  4979.6  400.55  4989.6  399.46  4996.9  397.42  4997.3  396.92
    5002  396.92  5002.5  397.42  5019.7  400.78  5039.7     401  5069.8  399.54
  5099.9  399.52    5140  400.27  5190.1  402.16  5211.3  402.24  5260.2   403.8
  5291.7  406.78  5359.9  411.78  5390.5  413.66  5430.6   415.1  5493.2  415.83
#Mann= 6 ,-1 , 0
  4688.9      .1       0  4934.3     .16       0  4996.9     .07       0
  5002.5     .16       0  5291.7      .1       0  5359.9     .05       0
Bank Sta=4996.9,5002.5
XS Rating Curve= 0 ,0
Exp/Cntr=0.3,0.1

Type RM Length L Ch R = 1 ,1404    ,275,275,275
BEGIN DESCRIPTION:
SOUTH MINERAL CR TRIB 12 2 1
END DESCRIPTION:
XS GIS Cut Line= 2
      3513691.58     10364608.62      3514607.25     10364764.84
#Sta/Elev= 30
  4683.2  423.92    4704  423.12  4724.3  421.63  4730.2  420.64  4805.5  412.85
  4835.9  410.76  4856.2  408.54  4927.2  402.97  4969.8  400.26  4977.9  400.26
  4988.1  399.45  4995.4  395.19  4995.9  394.69  5000.6  394.69    5001  395.19
  5008.4  395.92  5018.5  399.55    5031     400  5079.4  398.66  5109.8  398.45
  5140.2  398.72  5160.5   399.7  5253.1  401.38  5353.3  404.97  5381.8  406.92
  5386.9  406.46  5454.7  410.96  5489.7   412.6  5562.3  417.21  5612.1  419.16
#Mann= 6 ,-1 , 0
  4683.2      .1       0  4969.8     .16       0  4995.4     .07       0
    5001     .16       0  5253.1      .1       0  5489.7     .05       0
Bank Sta=4995.4,5001
XS Rating Curve= 0 ,0
Exp/Cntr=0.3,0.1

Type RM Length L Ch R = 1 ,1129    ,241,241,241
BEGIN DESCRIPTION:
SOUTH MINERAL CR TRIB 12 1 0
END DESCRIPTION:
XS GIS Cut Line= 2
      3513522.85     10364718.22      3514498.68     10365187.94
#Sta/Elev= 30
  4505.9  411.69  4529.1  411.77  4546.1  410.59  4551.7  411.38  4568.8  409.88
  4574.3  410.72    4614  409.17  4619.6  409.74  4636.7  408.28  4642.2   408.6
  4659.3  406.42  4823.2  402.33    4874  400.18  4941.9  399.19  4981.6   396.8
  4987.1  397.61  4990.6   393.7    4991   393.2  4996.2   393.7  5009.8   394.3
  5015.6  397.62    5038  398.56  5060.6  397.78  5153.1  398.87  5303.9  401.94
  5326.3  403.26    5449  406.06  5535.7  408.75  5570.5  412.13  5588.9  412.61
#Mann= 5 ,-1 , 0
  4505.9     .08       0  4990.6     .07       0  4996.2     .08       0
  5153.1     .05       0    5449     .08       0
Bank Sta=4990.6,4996.2
XS Rating Curve= 0 ,0
Exp/Cntr=0.3,0.1

Type RM Length L Ch R = 1 ,888     ,466,466,466
BEGIN DESCRIPTION:
SOUTH MINERAL CR TRIB 12 4 0
END DESCRIPTION:
XS GIS Cut Line= 3
      3513786.31     10365016.92      3513871.36     10365167.92
      3514031.04       10365128.
#Sta/Elev= 30
    4868     405  4890.3  404.91  4906.2  403.69    4912  404.28  4919.3  402.75
  4927.9  400.41  4933.6  401.54  4942.3  399.17  4949.6  397.76  4955.3  398.01
  4965.2  397.37  4971.2  397.53    4977   397.7  4992.9  396.08  4999.7  393.25
    5006  392.21  5006.5  391.71  5011.2  391.71  5014.6  394.73  5022.6  397.14
  5030.5  398.06  5036.2  397.99  5103.9  397.26  5124.2  397.69  5129.4  399.85
  5134.8  401.05  5155.5  403.56  5170.6  404.67  5186.4  404.93  5205.9  405.01
#Mann= 4 ,-1 , 0
    4868     .05       0  4971.2     .03       0  5036.2     .05       0
  5186.4     .08       0
Bank Sta=4977,5030.5
XS Rating Curve= 0 ,0
Exp/Cntr=0.3,0.1

Type RM Length L Ch R = 1 ,422     ,324,324,324
BEGIN DESCRIPTION:
SOUTH MINERAL CR TRIB 12 5 0
END DESCRIPTION:
XS GIS Cut Line= 4
      3513470.32     10364843.24      3513442.54     10365001.26
      3513630.04     10365230.42      3514056.11     10365130.37
#Sta/Elev= 30
  4906.4  404.12  4914.9  404.34  4935.2  403.72  4945.4  401.78  4955.5  399.01
  4965.7  396.98  4986.9  393.05  4993.3  391.08  4993.8  390.58  4998.5  390.58
    4999  391.08  5016.5  394.36  5041.2  396.45  5046.9   396.9  5073.9  396.45
  5080.4  396.91  5088.3  396.34  5216.1  396.05  5315.1  397.32  5478.1  398.32
  5549.6   397.7  5554.8  398.25  5632.1  397.86    5682  396.81    5704   398.6
  5724.4  400.92  5729.6  403.56  5734.9  404.22    5772  405.02  5800.6  404.95
#Mann= 4 ,-1 , 0
  4906.4     .05       0  4965.7     .03       0  5041.2     .05       0
  5800.6     .08       0
Bank Sta=4965.7,5041.2
XS Rating Curve= 0 ,0
Exp/Cntr=0.3,0.1

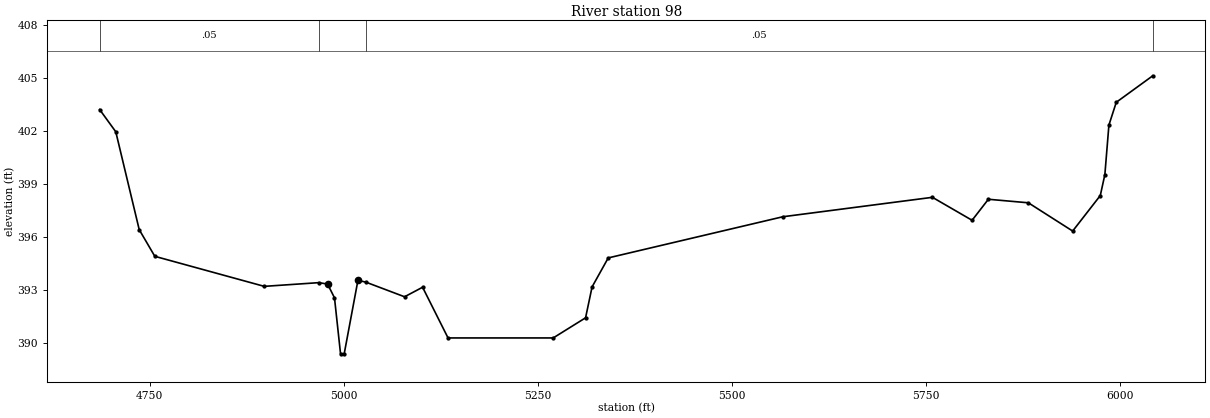
Type RM Length L Ch R = 1 ,98      ,0,0,0
BEGIN DESCRIPTION:
SOUTH MINERAL CR TRIB 12 1 1
END DESCRIPTION:
XS GIS Cut Line= 4
      3513136.99     10364700.95      3513183.86     10365112.37
      3513428.65     10365294.66      3514047.73     10365142.06
#Sta/Elev= 30
  4685.7  403.21  4706.5  401.95  4736.7  396.41  4756.8   394.9  4897.8   393.2
  4968.2  393.41  4979.4  393.33  4988.3  392.55  4996.1  389.38  5000.8  389.38
  5018.5  393.54  5028.6  393.44  5078.6  392.61  5101.8  393.15  5134.6  390.28
  5270.1  390.28  5311.8  391.42  5320.2  393.17    5341  394.81    5566  397.14
  5758.7  398.24  5809.8  396.94  5830.8  398.13  5882.3  397.93  5939.4  396.33
    5975  398.34  5980.9  399.53  5986.1  402.33  5995.6  403.62  6042.6  405.12
#Mann= 4 ,-1 , 0
  4685.7     .05       0  4968.2     .03       0  5028.6     .05       0
  6042.6     .08       0
Bank Sta=4979.4,5018.5
XS Rating Curve= 0 ,0
Exp/Cntr=0.3,0.1

Chan Stop Cuts=-1
Use User Specified Reach Order=0
Composite Channel Slope=5