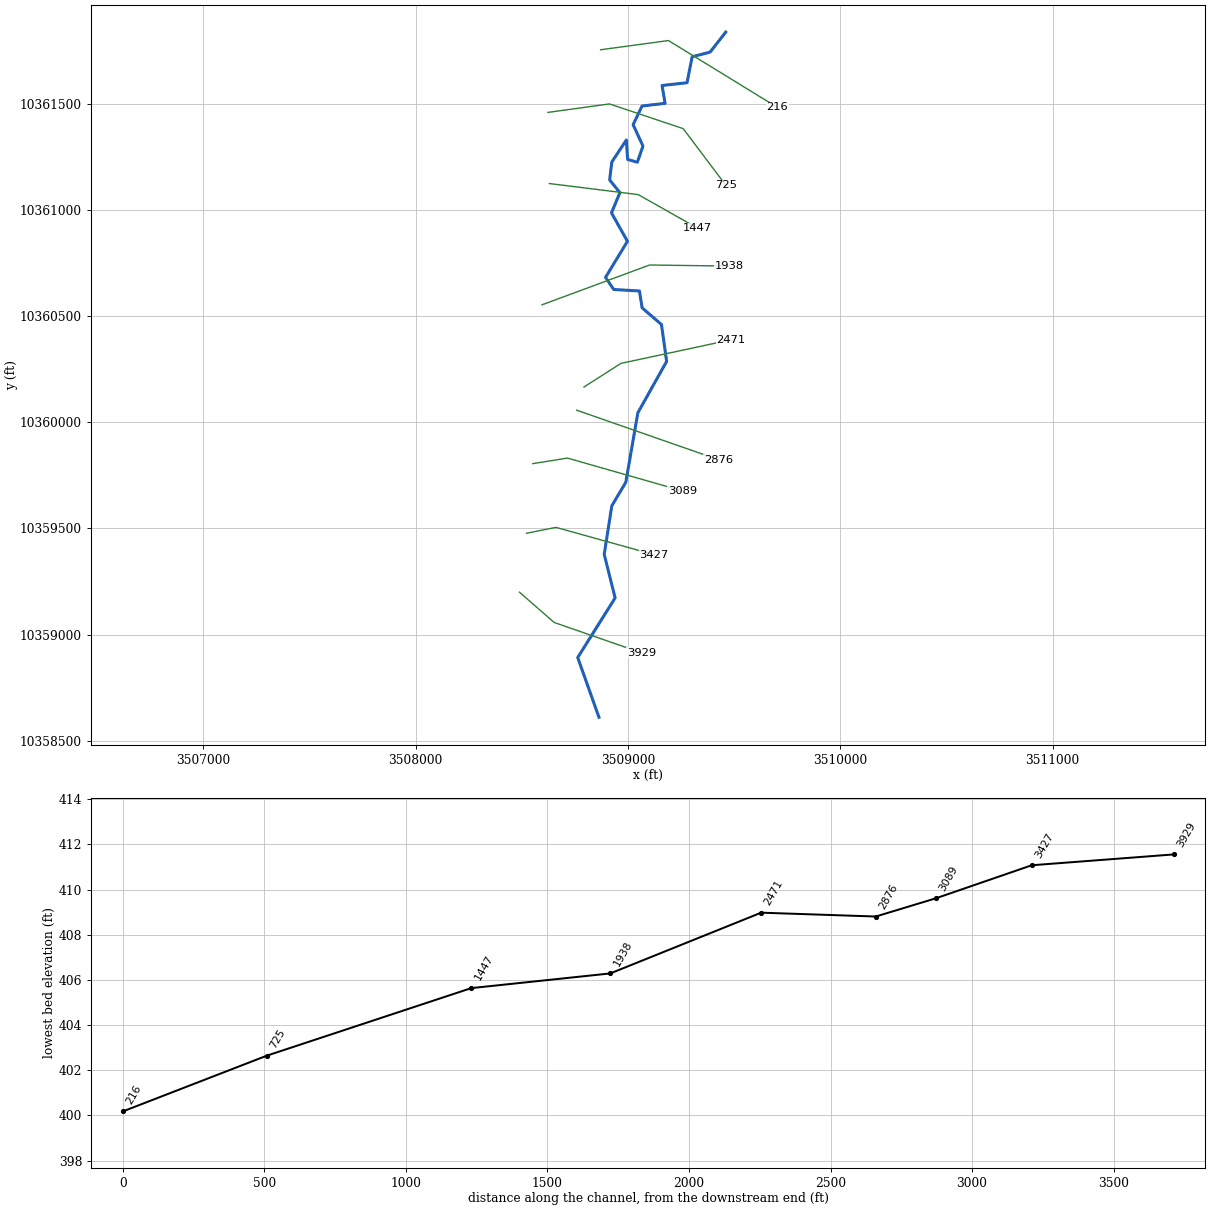
--- SOUTH MINERAL CR TRIB 13.prj (project) ---

Proj Title=SOUTH MINERAL CR TRIB 13 Base Level Engineering
Current Plan=p01
Default Exp/Contr=0.3,0.1
English Units
Geom File=g01
Flow File=f01
Plan File=p01
Y Axis Title=Elevation
X Axis Title(PF)=Main Channel Distance
X Axis Title(XS)=Station
BEGIN DESCRIPTION:
SOUTH MINERAL CR TRIB 13
END DESCRIPTION:
DSS Export Rating Curves= 0
DSS Export Rating Curve Sorted= 0
DSS Export Volume Flow Curves= 0
DXF OffsetX= 0
DXF OffsetY= 0
DXF ScaleX= 1
DXF ScaleY= 10

--- SOUTH MINERAL CR TRIB 13.p01 (plan) ---

Plan Title=Multiple Run
Short Identifier=Multiple
Geom File=g01
Flow File=f01
Subcritical Flow
K Sum by GR= 0
Std Step Tol= 0.01
Critical Tol= 0.01
Num of Std Step Trials= 20
Max Error Tol= 0.3
Flow Tol Ratio= 0.001
Split Flow NTrial= 30
Split Flow Tol= 0.02
Split Flow Ratio= 0.02
Log Output Level= 0
Friction Slope Method= 1
Unsteady Friction Slope Method= 2
Unsteady Bridges Friction Slope Method= 1
Parabolic Critical Depth
Global Vel Dist=  1 , 1 , 1
Global Log Level= 0
CheckData=True
Encroach Param= -1, 0, 0, 0
BEGIN DESCRIPTION:
Multiple Run
END DESCRIPTION:

--- SOUTH MINERAL CR TRIB 13.f01 (steady flow) ---

Flow Title=Multiple
Number of Profiles=7
Profile Names=10-year,25-year,50-year,1pct_min,100-year,1pct_plu,500-year
River Rch & RM= SOUTH MINERAL CR,Reach-1,3929
    1101    1529    1885    1693    2290    3097    3375
Boundary for River Rch & Prof#=SOUTH MINERAL CR,Reach-1,1
Up Type=0
Dn Type=3
Dn Slope=0.005
Boundary for River Rch & Prof#=SOUTH MINERAL CR,Reach-1,2
Up Type=0
Dn Type=3
Dn Slope=0.005
Boundary for River Rch & Prof#=SOUTH MINERAL CR,Reach-1,3
Up Type=0
Dn Type=3
Dn Slope=0.005
Boundary for River Rch & Prof#=SOUTH MINERAL CR,Reach-1,4
Up Type=0
Dn Type=3
Dn Slope=0.005
Boundary for River Rch & Prof#=SOUTH MINERAL CR,Reach-1,5
Up Type=0
Dn Type=3
Dn Slope=0.005
Boundary for River Rch & Prof#=SOUTH MINERAL CR,Reach-1,6
Up Type=0
Dn Type=3
Dn Slope=0.005
Boundary for River Rch & Prof#=SOUTH MINERAL CR,Reach-1,7
Up Type=0
Dn Type=3
Dn Slope=0.005

--- SOUTH MINERAL CR TRIB 13.g01 (geometry) ---

Geom Title=Existing Conditions
Program Version=4.10

River Reach=SOUTH MINERAL CR,Reach-1
Reach XY= 30
      3508863.27     10358610.55      3508763.31     10358891.55
      3508939.53     10359172.77      3508888.14     10359377.69
      3508923.83      10359606.2      3508989.86     10359717.49
      3509046.54     10360044.52      3509182.09     10360286.57
      3509157.96     10360460.25      3509066.77     10360538.93
       3509054.1     10360618.38      3508933.04     10360625.46
      3508894.31     10360682.66      3508997.47     10360852.42
      3508922.29     10360986.65      3508962.14     10361081.79
      3508913.71      10361141.4      3508923.83     10361225.86
      3508992.41     10361329.58      3508998.44     10361238.05
      3509044.18     10361224.92      3509070.66     10361301.06
      3509024.36     10361401.54      3509066.16     10361489.65
       3509174.9     10361502.52      3509160.46     10361586.48
      3509278.18      10361599.5      3509302.46      10361721.8
      3509386.67     10361743.51      3509460.62     10361837.87

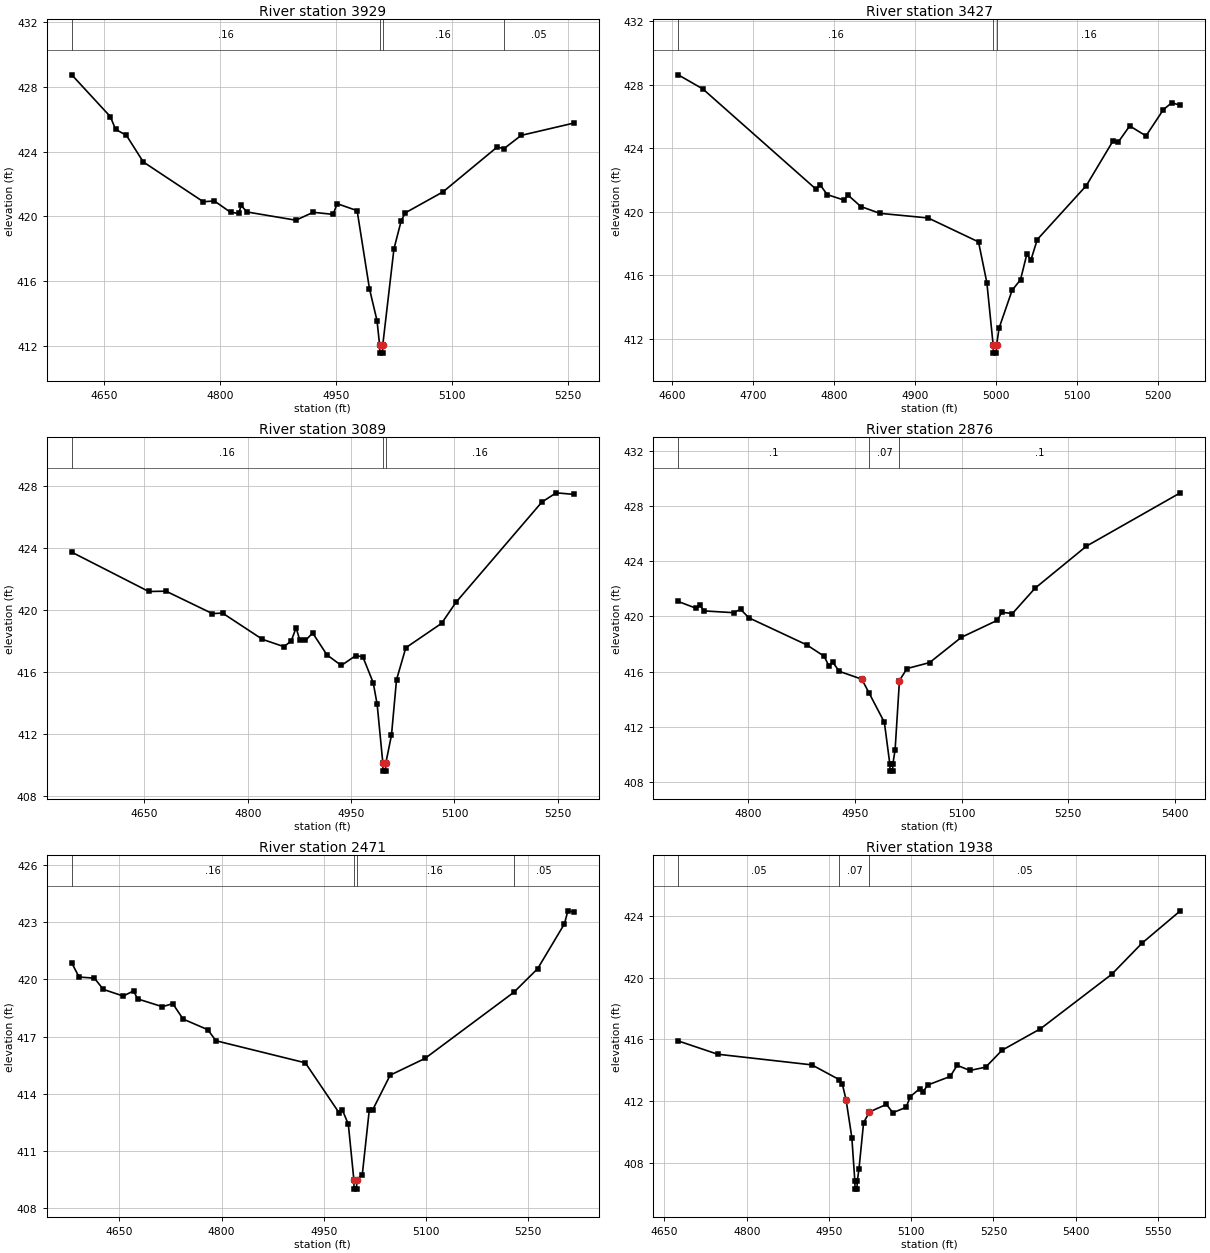
Type RM Length L Ch R = 1 ,3929    ,502,502,502
BEGIN DESCRIPTION:
SOUTH MINERAL CR TRIB 13 8 0
END DESCRIPTION:
XS GIS Cut Line= 3
      3508489.27     10359199.21      3508652.45     10359056.86
      3509062.18      10358914.5
#Sta/Elev= 30
  4607.9  428.75  4657.8  426.17  4664.7  425.38  4678.7  425.01  4700.5  423.37
  4778.3  420.91  4792.6  420.96  4813.5  420.26  4824.4  420.19  4827.2  420.69
  4834.7  420.28  4898.2  419.77  4920.6  420.26  4946.4  420.13  4951.7  420.79
  4977.5  420.36  4993.5  415.53  5003.3  413.56  5006.6  412.06  5006.8  411.56
  5010.4  411.56  5010.7  412.06  5025.2     418  5034.5  419.72  5039.7  420.22
  5088.7  421.52  5158.9  424.29  5167.7  424.19    5190  425.01  5258.2  425.77
#Mann= 4 ,-1 , 0
  4607.9     .16       0  5006.6     .07       0  5010.7     .16       0
  5167.7     .05       0
Bank Sta=5006.6,5010.7
XS Rating Curve= 0 ,0
Exp/Cntr=0.3,0.1

Type RM Length L Ch R = 1 ,3427    ,338,338,338
BEGIN DESCRIPTION:
SOUTH MINERAL CR TRIB 13 7 0
END DESCRIPTION:
XS GIS Cut Line= 3
      3508522.28     10359477.01      3508661.13     10359504.78
      3509122.32     10359376.48
#Sta/Elev= 30
  4607.6  428.62    4638  427.73  4777.9  421.41    4783  421.68  4791.7  421.07
  4812.1  420.73  4817.3  421.04  4833.2  420.32  4856.7  419.89  4916.3   419.6
  4978.6  418.09  4988.9  415.52  4996.7  411.58    4997  411.08  5000.6  411.08
  5000.9  411.58    5004  412.66  5020.1  415.04  5030.5  415.71  5038.2   417.3
  5043.4  416.96  5051.2  418.24  5111.8  421.64  5144.6  424.44  5151.2  424.38
  5165.4   425.4  5185.5  424.77  5206.9  426.42  5217.3  426.86  5227.9   426.7
#Mann= 3 ,-1 , 0
  4607.6     .16       0  4996.7     .07       0  5000.9     .16       0
Bank Sta=4996.7,5000.9
XS Rating Curve= 0 ,0
Exp/Cntr=0.3,0.1

Type RM Length L Ch R = 1 ,3089    ,213,213,213
BEGIN DESCRIPTION:
SOUTH MINERAL CR TRIB 13 6 0
END DESCRIPTION:
XS GIS Cut Line= 3
      3508551.77     10359805.13      3508714.95     10359831.17
       3509256.6     10359676.66
#Sta/Elev= 30
  4544.7  423.71  4656.4  421.18  4681.5   421.2  4748.6  419.76  4763.5  419.79
  4821.4   418.1  4852.6  417.63    4863  417.99  4870.2  418.84  4875.4  418.07
  4883.8  418.03  4894.2  418.51    4915   417.1  4935.8  416.42  4956.6  417.05
    4967  416.98  4982.1  415.31  4987.8  413.92  4996.1  410.12  4996.3  409.62
    5000  409.62  5000.3  410.12  5008.6  411.94  5015.9   415.5  5029.4  417.56
  5081.3  419.13  5102.1  420.48  5226.9  426.94  5247.7  427.53  5273.2  427.43
#Mann= 3 ,-1 , 0
  4544.7     .16       0  4996.1     .07       0  5000.3     .16       0
Bank Sta=4996.1,5000.3
XS Rating Curve= 0 ,0
Exp/Cntr=0.3,0.1

Type RM Length L Ch R = 1 ,2876    ,405,405,405
BEGIN DESCRIPTION:
SOUTH MINERAL CR TRIB 13 5 0
END DESCRIPTION:
XS GIS Cut Line= 2
      3508758.35     10360056.86      3509425.02     10359824.22
#Sta/Elev= 30
  4701.5  421.08  4726.7  420.59  4732.2  420.81  4737.5   420.4  4779.6  420.27
  4789.1  420.52  4800.8   419.9  4882.3  417.94  4906.7  417.12  4913.3  416.43
  4918.6  416.71  4927.9  416.03  4959.7  415.46  4970.1  414.44  4991.4  412.34
  4999.1  409.31  4999.4  408.81  5003.1  408.81  5003.3  409.31  5006.5  410.35
  5012.6  415.36  5023.2  416.23    5055  416.66  5099.7  418.49  5150.3  419.72
  5156.5   420.3  5171.5  420.21  5203.3  422.04  5275.5  425.08  5407.6  428.94
#Mann= 3 ,-1 , 0
  4701.5      .1       0  4970.1     .07       0  5012.6      .1       0
Bank Sta=4959.7,5012.6
XS Rating Curve= 0 ,0
Exp/Cntr=0.3,0.1

Type RM Length L Ch R = 1 ,2471    ,533,533,533
BEGIN DESCRIPTION:
SOUTH MINERAL CR TRIB 13 4 0
END DESCRIPTION:
XS GIS Cut Line= 3
       3508793.1     10360166.26      3508966.68     10360277.35
      3509485.74     10360388.45
#Sta/Elev= 30
    4580  420.87  4590.7  420.13  4613.2  420.07  4626.3  419.48  4655.5  419.13
  4670.7   419.4  4676.6  418.98    4713  418.57  4728.2  418.73  4743.4  417.92
  4779.7  417.36  4791.6  416.78  4922.8  415.62  4972.2     413  4977.3  413.13
  4985.9  412.39    4994  409.48  4994.3  408.98    4998  408.98  4998.3  409.48
  5006.4  409.74  5016.6  413.12  5021.7  413.15  5047.3  414.97  5098.4  415.85
  5228.9  419.33  5263.8  420.57    5303  422.92  5308.2  423.61  5316.9  423.54
#Mann= 4 ,-1 , 0
    4580     .16       0    4994     .07       0  4998.3     .16       0
  5228.9     .05       0
Bank Sta=4994,4998.3
XS Rating Curve= 0 ,0
Exp/Cntr=0.3,0.1

Type RM Length L Ch R = 1 ,1938    ,491,491,491
BEGIN DESCRIPTION:
Mapping XS 636c3335
END DESCRIPTION:
XS GIS Cut Line= 3
      3508595.12     10360553.38       3509102.1     10360740.89
      3509477.12     10360735.68
#Sta/Elev= 30
  4675.1  415.89    4747  415.03  4918.8  414.34  4968.9  413.38  4974.3   413.1
  4981.1  412.09  4991.7  409.63  4997.2  406.79  4997.5  406.29  5001.2  406.29
  5001.5  406.79  5004.7  407.59  5013.1  410.59  5023.7  411.29  5054.8  411.78
  5066.4  411.24  5090.6  411.59  5098.4  412.29  5115.6   412.8    5121  412.58
  5130.4  413.04  5171.1  413.59  5183.7  414.31  5206.9  413.98  5235.7  414.19
  5265.7  415.29  5335.7  416.68  5465.7  420.21    5521  422.23  5590.7  424.32
#Mann= 3 ,-1 , 0
  4675.1     .05       0  4968.9     .07       0  5023.7     .05       0
Bank Sta=4981.1,5023.7
XS Rating Curve= 0 ,0
Exp/Cntr=0.3,0.1

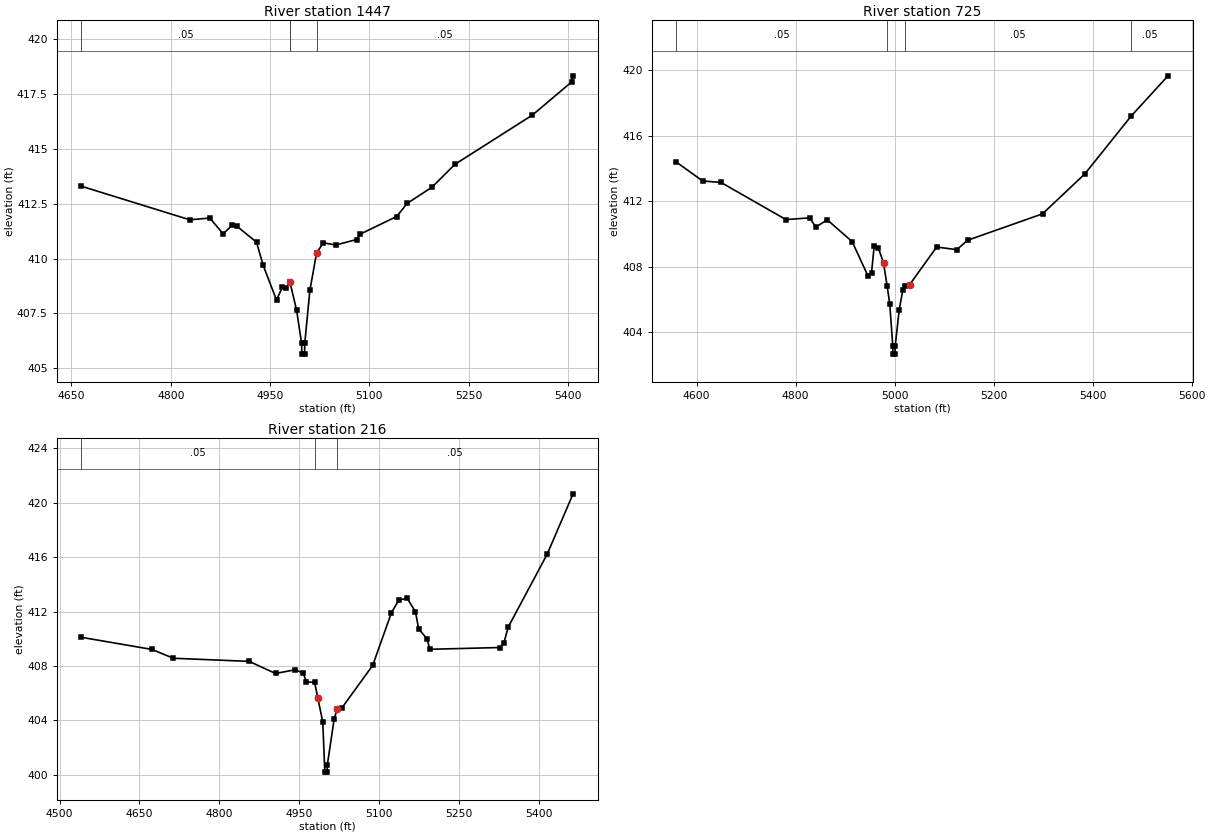
Type RM Length L Ch R = 1 ,1447    ,722,722,722
BEGIN DESCRIPTION:
Mapping XS 2567eaf2
END DESCRIPTION:
XS GIS Cut Line= 3
      3508629.84     10361124.57      3509048.28     10361072.49
      3509327.49     10360914.67
#Sta/Elev= 30
  4665.2   413.3  4828.7  411.77    4859  411.85  4879.1  411.13  4892.8  411.52
  4899.3  411.49  4929.5  410.75  4939.6  409.69  4959.7  408.11  4968.5  408.69
  4973.6  408.65  4979.9  408.94    4990  407.65  4997.6  406.14    4998  405.64
  5002.1  405.64  5002.4  406.14  5010.1  408.55  5020.2  410.25  5030.3  410.72
  5049.3  410.62  5080.7  410.87  5086.3  411.12  5141.2  411.92  5157.1  412.52
  5194.6  413.26  5229.1   414.3  5346.2  416.55  5405.4  418.06  5407.6  418.34
#Mann= 4 ,-1 , 0
  4665.2     .05       0  4979.9     .16       0  4979.9     .03       0
  5020.2     .05       0
Bank Sta=4979.9,5020.2
XS Rating Curve= 0 ,0
Exp/Cntr=0.3,0.1

Type RM Length L Ch R = 1 ,725     ,509,509,509
BEGIN DESCRIPTION:
Mapping XS 2ae182ea
END DESCRIPTION:
XS GIS Cut Line= 4
      3508622.93     10361459.64      3508912.86     10361499.57
      3509260.09     10361383.25      3509461.19     10361116.27
#Sta/Elev= 30
  4559.1  414.39  4612.1  413.24  4649.1  413.15  4780.3  410.88    4828  410.98
  4840.9  410.43  4863.9  410.86  4914.2  409.53  4945.9  407.44  4953.3  407.63
  4958.6  409.27    4967  409.14  4977.5  408.23  4984.9   406.8  4990.1  405.71
  4996.2  403.15  4996.6  402.65  5000.7  402.65  5001.1  403.15  5009.2  405.37
  5016.4  406.55  5021.7  406.79  5030.3   406.9  5084.8   409.2  5125.2  409.04
  5147.9  409.62  5298.7  411.23  5384.1  413.67  5477.8  417.21  5552.2  419.67
#Mann= 4 ,-1 , 0
  4559.1     .05       0  4984.9     .03       0  5021.7     .05       0
  5477.8     .05       0
Bank Sta=4977.5,5030.3
XS Rating Curve= 0 ,0
Exp/Cntr=0.3,0.1

Type RM Length L Ch R = 1 ,216     ,0,0,0
BEGIN DESCRIPTION:
SOUTH MINERAL CR TRIB 13 1 0
END DESCRIPTION:
XS GIS Cut Line= 3
      3508871.16     10361754.77      3509190.64     10361798.18
      3509702.81     10361483.94
#Sta/Elev= 30
  4541.3   410.1  4673.4  409.21  4713.8  408.56  4856.2  408.33  4905.7  407.44
  4942.4  407.71  4957.8  407.48  4963.7   406.8  4979.1   406.8    4985  405.67
  4994.5  403.86  4998.3  400.18  5002.5  400.18  5002.9  400.68  5015.9   404.1
  5021.7  404.83  5029.7  404.87  5088.3  408.04  5123.5  411.92  5137.7  412.86
  5153.2  412.96  5168.6  411.98  5174.5  410.73  5189.9     410  5195.8  409.22
  5327.2  409.35  5334.7  409.69  5342.6  410.84  5416.1  416.23  5464.6  420.66
#Mann= 3 ,-1 , 0
  4541.3     .05       0  4979.1     .03       0  5021.7     .05       0
Bank Sta=4985,5021.7
XS Rating Curve= 0 ,0
Exp/Cntr=0.3,0.1

Chan Stop Cuts=-1
Use User Specified Reach Order=0
Composite Channel Slope=5