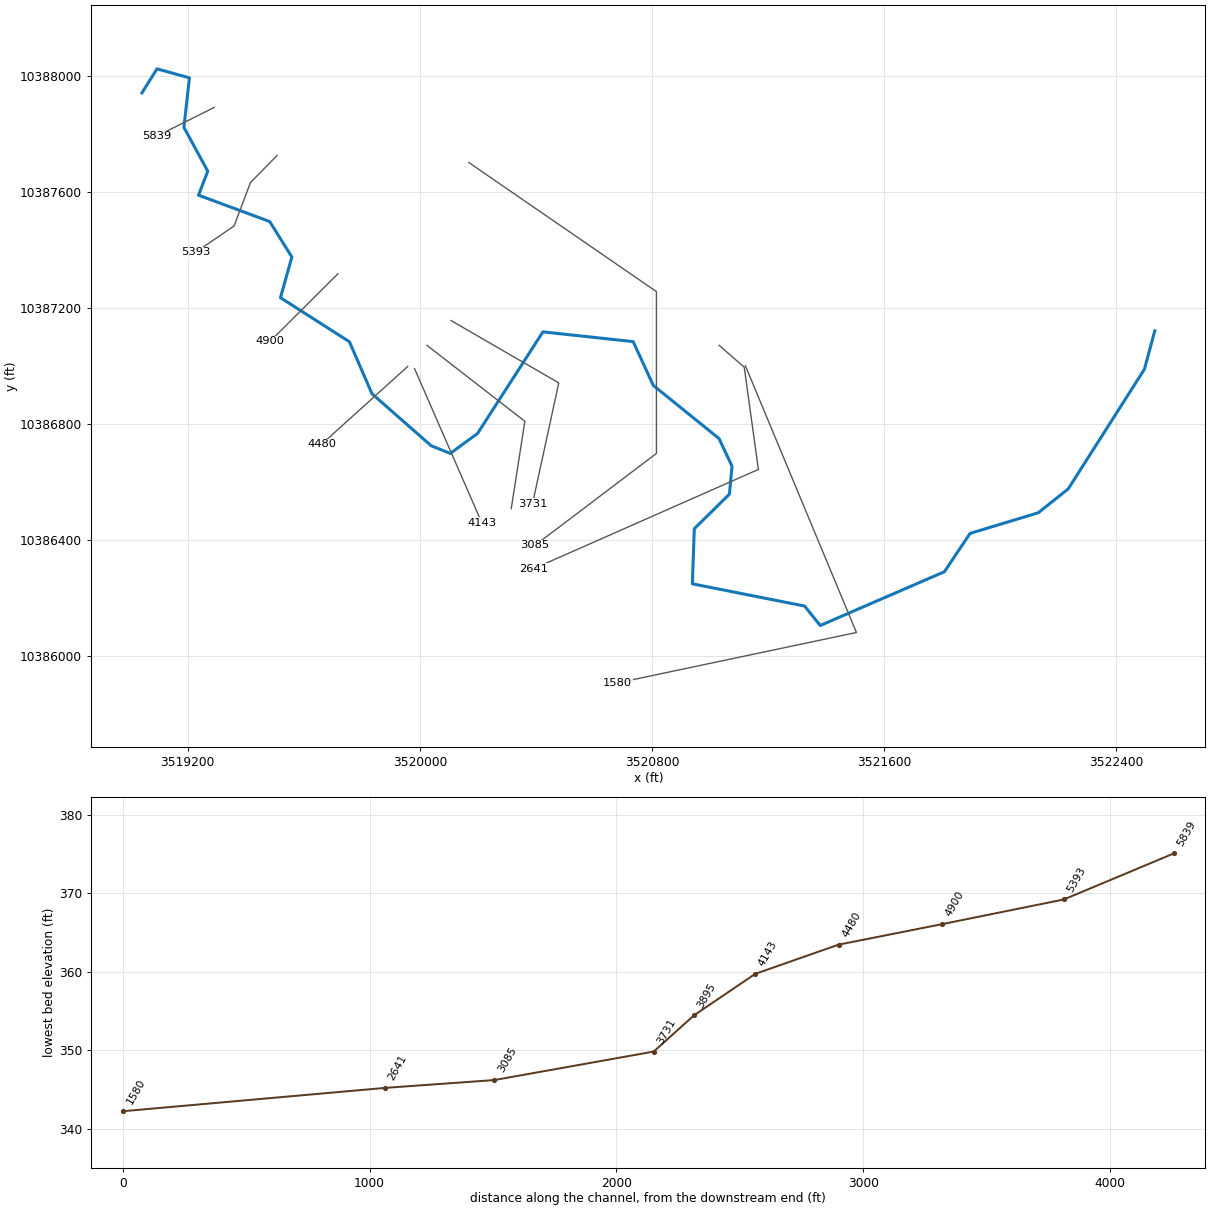
--- SOUTH MINERAL CR TRIB 3.prj (project) ---

Proj Title=SOUTH MINERAL CR TRIB 3 Base Level Engineering
Current Plan=p01
Default Exp/Contr=0.3,0.1
English Units
Geom File=g01
Flow File=f01
Plan File=p01
Y Axis Title=Elevation
X Axis Title(PF)=Main Channel Distance
X Axis Title(XS)=Station
BEGIN DESCRIPTION:
SOUTH MINERAL CR TRIB 3
END DESCRIPTION:
DSS Export Rating Curves= 0
DSS Export Rating Curve Sorted= 0
DSS Export Volume Flow Curves= 0
DXF OffsetX= 0
DXF OffsetY= 0
DXF ScaleX= 1
DXF ScaleY= 10

--- SOUTH MINERAL CR TRIB 3.p01 (plan) ---

Plan Title=Multiple Run
Short Identifier=Multiple
Geom File=g01
Flow File=f01
Subcritical Flow
K Sum by GR= 0
Std Step Tol= 0.01
Critical Tol= 0.01
Num of Std Step Trials= 20
Max Error Tol= 0.3
Flow Tol Ratio= 0.001
Split Flow NTrial= 30
Split Flow Tol= 0.02
Split Flow Ratio= 0.02
Log Output Level= 0
Friction Slope Method= 1
Unsteady Friction Slope Method= 2
Unsteady Bridges Friction Slope Method= 1
Parabolic Critical Depth
Global Vel Dist=  1 , 1 , 1
Global Log Level= 0
CheckData=True
Encroach Param= -1, 0, 0, 0
BEGIN DESCRIPTION:
Multiple Run
END DESCRIPTION:

--- SOUTH MINERAL CR TRIB 3.f01 (steady flow) ---

Flow Title=Multiple
Number of Profiles=7
Profile Names=10-year,25-year,50-year,1pct_min,100-year,1pct_plu,500-year
River Rch & RM= SOUTH MINERAL CR,Reach-1,5839
     866    1196    1470    1320    1785    2414    2624
Boundary for River Rch & Prof#=SOUTH MINERAL CR,Reach-1,1
Up Type=0
Dn Type=3
Dn Slope=0.005
Boundary for River Rch & Prof#=SOUTH MINERAL CR,Reach-1,2
Up Type=0
Dn Type=3
Dn Slope=0.005
Boundary for River Rch & Prof#=SOUTH MINERAL CR,Reach-1,3
Up Type=0
Dn Type=3
Dn Slope=0.005
Boundary for River Rch & Prof#=SOUTH MINERAL CR,Reach-1,4
Up Type=0
Dn Type=3
Dn Slope=0.005
Boundary for River Rch & Prof#=SOUTH MINERAL CR,Reach-1,5
Up Type=0
Dn Type=3
Dn Slope=0.005
Boundary for River Rch & Prof#=SOUTH MINERAL CR,Reach-1,6
Up Type=0
Dn Type=3
Dn Slope=0.005
Boundary for River Rch & Prof#=SOUTH MINERAL CR,Reach-1,7
Up Type=0
Dn Type=3
Dn Slope=0.005

--- SOUTH MINERAL CR TRIB 3.g01 (geometry) ---

Geom Title=Existing Conditions
Program Version=4.10

River Reach=SOUTH MINERAL CR,Reach-1
Reach XY= 30
      3519042.66     10387941.42      3519094.61     10388024.41
      3519206.26     10387993.26      3519187.32     10387822.67
      3519269.45     10387671.63      3519237.56     10387589.05
       3519482.8      10387498.3      3519559.21     10387376.01
      3519519.94     10387235.87      3519757.45     10387084.13
      3519835.27     10386904.91      3520039.27     10386725.78
        3520105.     10386699.34      3520198.84     10386768.08
      3520424.22     10387118.18      3520735.03     10387084.53
      3520804.48     10386933.61      3521030.95     10386750.58
      3521075.64     10386655.34      3521066.66     10386558.99
      3520945.67     10386440.07      3520939.02     10386250.08
      3521325.72     10386173.53      3521379.48     10386106.51
      3521807.29     10386291.73      3521895.71     10386423.78
      3522130.74     10386494.95      3522233.95     10386577.19
      3522496.38     10386989.47      3522532.11     10387121.64

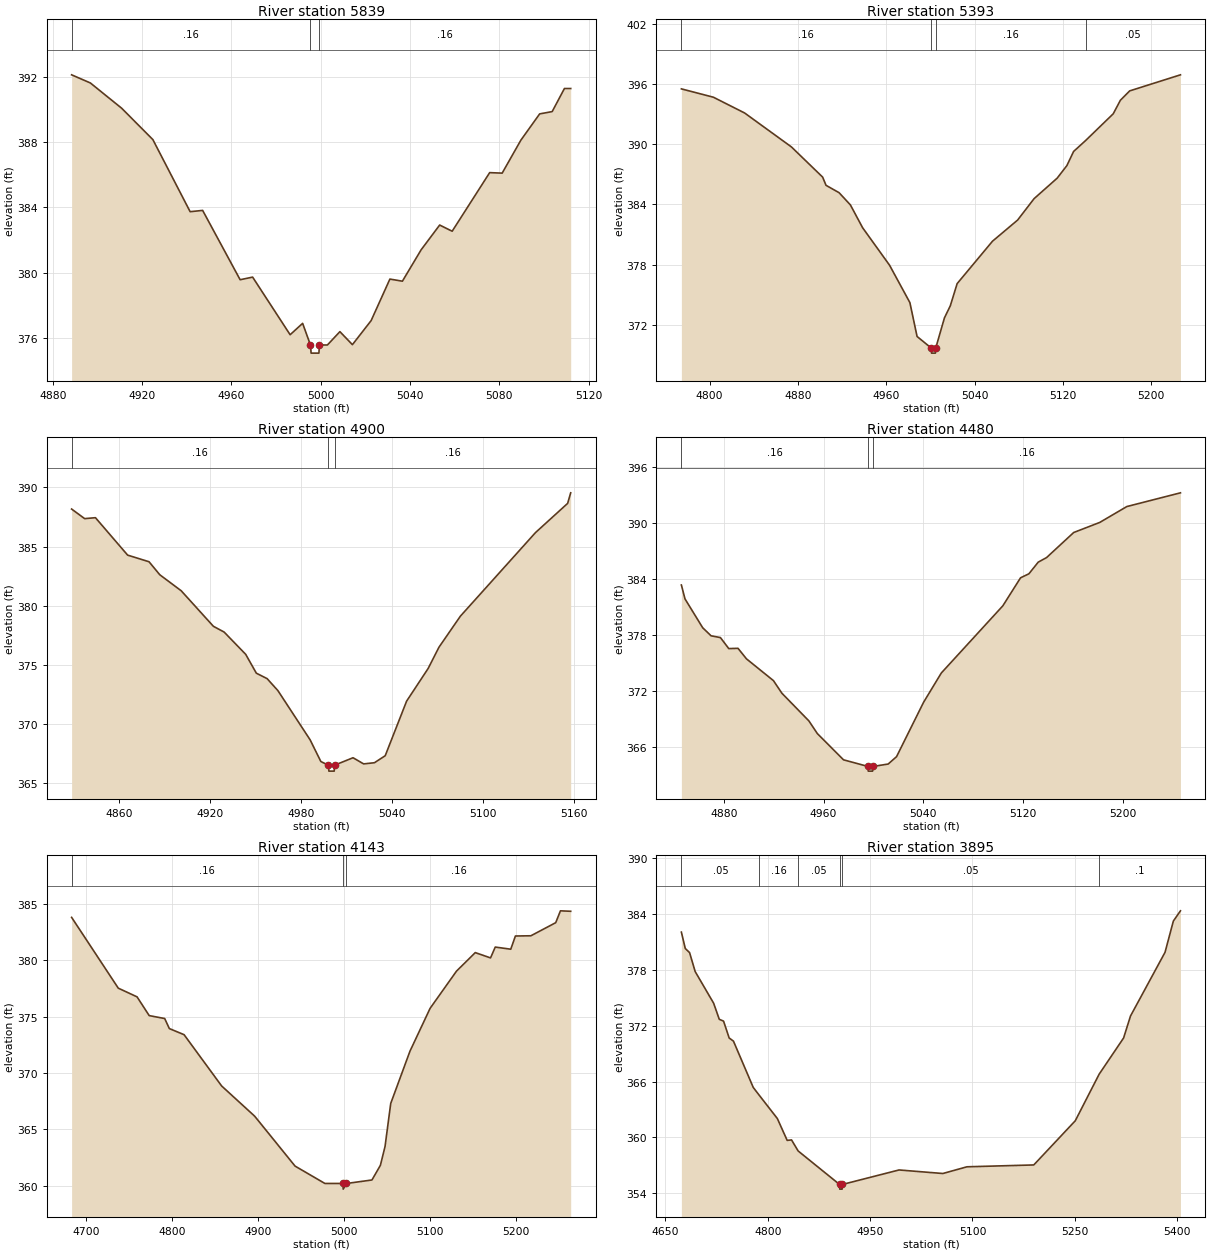
Type RM Length L Ch R = 1 ,5839    ,446,446,446
BEGIN DESCRIPTION:
SOUTH MINERAL CR TRIB 3 28 0
END DESCRIPTION:
XS GIS Cut Line= 3
      3519292.13     10387891.66      3519192.11     10387841.64
      3519092.14     10387791.66
#Sta/Elev= 30
  4888.4  392.15  4896.8  391.65  4910.8   390.1  4924.8  388.17  4941.5  383.74
  4947.1  383.82  4963.9  379.56  4969.5  379.72  4986.3  376.18  4991.9  376.88
  4995.4  375.55  4995.7  375.05  4999.2  375.05  4999.4  375.55    5003  375.55
  5008.6  376.37  5014.2  375.57  5022.6  377.05    5031   379.6  5036.6  379.47
    5045   381.4  5053.3  382.92  5058.9  382.54  5075.7  386.14  5081.3  386.11
  5089.7  388.14  5098.1  389.75  5103.7  389.89  5109.2  391.31    5112  391.31
#Mann= 3 ,-1 , 0
  4888.4     .16       0  4995.4     .07       0  4999.4     .16       0
Bank Sta=4995.4,4999.4
XS Rating Curve= 0 ,0
Exp/Cntr=0.3,0.1

Type RM Length L Ch R = 1 ,5393    ,493,493,493
BEGIN DESCRIPTION:
SOUTH MINERAL CR TRIB 3 18 0
END DESCRIPTION:
XS GIS Cut Line= 4
      3519508.55     10387726.15      3519416.51     10387632.38
      3519360.09     10387483.07      3519227.26     10387391.91
#Sta/Elev= 30
  4774.4  395.49  4803.4  394.66  4831.7  393.09  4874.1  389.71  4902.4   386.7
  4905.4  385.89  4917.3  385.15  4927.5  383.94  4938.6  381.66    4963  377.93
  4981.4  374.21  4987.9  370.84  5000.8  369.68    5001  369.18  5004.5  369.18
  5004.8  369.68  5012.7  372.69    5018  373.89  5024.2   376.1  5056.2  380.32
    5079  382.43  5093.9  384.56  5114.8   386.6  5123.6  387.85  5129.7  389.26
  5140.6  390.35  5165.6  393.01  5172.1  394.36  5180.5  395.29  5226.5  396.89
#Mann= 4 ,-1 , 0
  4774.4     .16       0  5000.8     .07       0  5004.8     .16       0
  5140.6     .05       0
Bank Sta=5000.8,5004.8
XS Rating Curve= 0 ,0
Exp/Cntr=0.3,0.1

Type RM Length L Ch R = 1 ,4900    ,420,420,420
BEGIN DESCRIPTION:
SOUTH MINERAL CR TRIB 3 8 0
END DESCRIPTION:
XS GIS Cut Line= 2
      3519717.75     10387318.17      3519484.82      10387086.1
#Sta/Elev= 30
  4828.9  388.17  4837.5  387.36  4844.6  387.44  4865.8  384.28  4879.9  383.72
    4887  382.62  4901.1  381.27  4922.3  378.27  4929.4  377.78  4943.6   375.9
  4950.6  374.31  4957.7  373.85  4964.8  372.84    4986  368.69  4993.1  366.85
  4998.1  366.54  4998.4  366.04  5001.9  366.04  5002.1  366.54  5014.3  367.17
  5021.3  366.65  5028.4  366.75  5035.5  367.34  5049.6  371.95  5063.8  374.71
  5070.9   376.5    5085  379.12  5134.5  386.18  5155.7  388.65  5157.7  389.54
#Mann= 3 ,-1 , 0
  4828.9     .16       0  4998.1     .07       0  5002.1     .16       0
Bank Sta=4998.1,5002.1
XS Rating Curve= 0 ,0
Exp/Cntr=0.3,0.1

Type RM Length L Ch R = 1 ,4480    ,337,337,337
BEGIN DESCRIPTION:
SOUTH MINERAL CR TRIB 3 7 0
END DESCRIPTION:
XS GIS Cut Line= 2
      3519958.56     10386999.16      3519661.68     10386730.94
#Sta/Elev= 30
    4846  383.35  4848.9  381.86  4863.1  378.77  4869.8  377.91  4877.3  377.72
    4884  376.54  4891.4  376.57  4898.2  375.44  4919.8  373.11  4926.6  371.76
  4948.2   368.8    4955  367.44    4976  364.63  4995.6  363.92  4995.8  363.42
  4999.3  363.42  4999.6  363.92  5011.8  364.18  5018.5  364.97  5040.2   370.8
  5054.4  373.93  5103.7  381.12  5117.9  384.12  5124.6  384.55  5132.1   385.8
  5138.8  386.29  5160.5  388.97  5181.4  390.05  5203.1  391.75  5246.1  393.22
#Mann= 3 ,-1 , 0
    4846     .16       0  4995.6     .07       0  4999.6     .16       0
Bank Sta=4995.6,4999.6
XS Rating Curve= 0 ,0
Exp/Cntr=0.3,0.1

Type RM Length L Ch R = 1 ,4143    ,248,248,248
BEGIN DESCRIPTION:
SOUTH MINERAL CR TRIB 3 6 0
END DESCRIPTION:
XS GIS Cut Line= 2
      3519981.99      10386991.3      3520213.75     10386460.06
#Sta/Elev= 30
  4683.5  383.78  4737.7  377.51  4759.5  376.74  4773.6  375.08  4791.6  374.82
    4797  373.93  4814.1  373.39  4857.7  368.85  4896.1  366.17    4943  361.75
  4977.7  360.21  4998.7  360.21  4998.9  359.71  5002.7  360.21  5032.3  360.52
  5042.1  361.82  5047.5  363.49  5054.1   367.3  5076.4  371.92  5099.8  375.72
  5130.5  379.02  5152.3  380.66    5170  380.19  5175.5  381.15  5193.5  380.96
  5198.9  382.13  5216.9  382.15  5245.7  383.31  5251.2  384.36  5263.1  384.32
#Mann= 3 ,-1 , 0
  4683.5     .16       0  4998.7     .07       0  5002.7     .16       0
Bank Sta=4998.7,5002.7
XS Rating Curve= 0 ,0
Exp/Cntr=0.3,0.1

Type RM Length L Ch R = 1 ,3895    ,164,164,164
BEGIN DESCRIPTION:
Mapping XS 8657471d
END DESCRIPTION:
XS GIS Cut Line= 3
      3520024.72     10387071.77      3520361.92     10386810.08
      3520315.05     10386509.34
#Sta/Elev= 30
  4673.5  382.06  4679.2   380.3  4685.5  379.86  4693.7  377.82  4720.8  374.41
    4729  372.69  4735.3  372.49  4743.5  370.68  4749.8  370.34  4778.8  365.36
  4787.7  364.51  4814.1  362.02  4828.5  359.67  4834.9  359.72  4844.6  358.53
  4905.3  354.93  4905.5  354.43    4909  354.43  4909.3  354.93  4992.4  356.49
  5056.6  356.11  5091.9  356.83  5189.8  357.03  5250.6  361.78  5285.6  366.79
  5321.4  370.68  5331.5  373.04  5382.1  379.89  5394.3  383.25  5404.7  384.35
#Mann= 6 ,-1 , 0
  4673.5     .05       0  4787.7     .16       0  4844.6     .05       0
  4905.3     .03       0  4909.3     .05       0  5285.6      .1       0
Bank Sta=4905.3,4909.3
XS Rating Curve= 0 ,0
Exp/Cntr=0.3,0.1

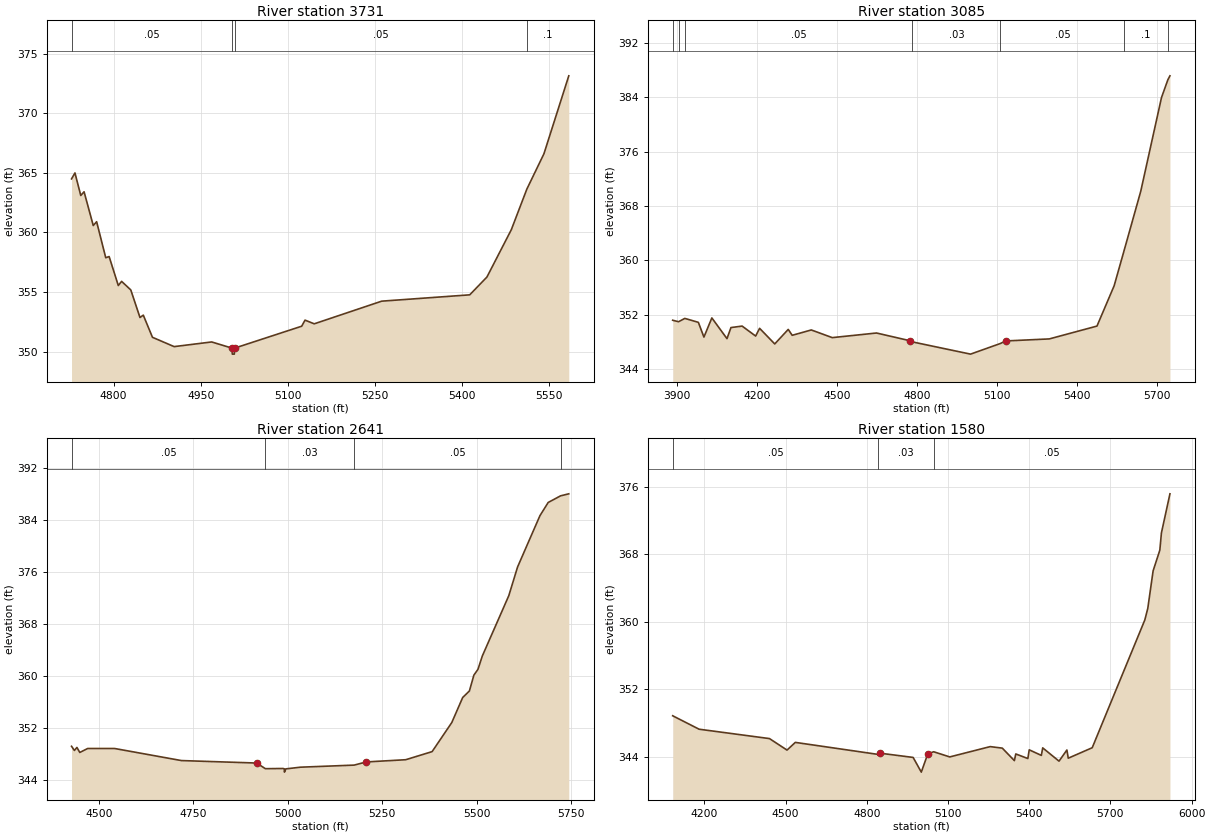
Type RM Length L Ch R = 1 ,3731    ,646,646,646
BEGIN DESCRIPTION:
SOUTH MINERAL CR TRIB 3 5 0
END DESCRIPTION:
XS GIS Cut Line= 3
      3520107.69     10387157.09      3520478.78     10386942.25
      3520387.98     10386525.01
#Sta/Elev= 30
  4727.5  364.49  4733.4  364.99  4743.4   363.1  4749.1  363.41  4764.9  360.58
  4770.7   360.9  4786.4  357.88  4792.2  357.98    4808  355.55  4813.7   355.9
  4829.5  355.18  4845.3  352.87    4851  353.07  4866.8  351.21  4904.1  350.43
  4968.7  350.82    5004   350.3  5004.2   349.8  5007.7   349.8    5008   350.3
  5123.6  352.14  5129.4  352.65  5145.2  352.34  5261.3  354.24  5412.8  354.77
  5442.4  356.26  5484.4  360.23  5511.1  363.63  5540.5  366.59  5583.3  373.13
#Mann= 4 ,-1 , 0
  4727.5     .05       0    5004    .035       0    5008     .05       0
  5511.1      .1       0
Bank Sta=5004,5008
XS Rating Curve= 0 ,0
Exp/Cntr=0.3,0.1

Type RM Length L Ch R = 1 ,3085    ,444,444,444
BEGIN DESCRIPTION:
SOUTH MINERAL CR TRIB 3 4 0
END DESCRIPTION:
XS GIS Cut Line= 4
      3520168.46     10387701.79      3520815.15     10387256.92
      3520815.15     10386699.19      3520396.75     10386382.67
#Sta/Elev= 30
    3883  351.16  3904.9  350.94  3928.6  351.43  3979.4  350.85  4000.3  348.68
  4030.1   351.5  4086.9  348.45  4101.8  350.08  4143.7   350.3  4194.5  348.83
  4209.4  349.97  4266.2  347.67  4316.9  349.81  4331.8  348.94  4403.5  349.73
  4482.2   348.6  4648.4  349.28  4773.2  348.15  4783.2  347.97  5001.5  346.17
  5113.2  347.73  5133.2  348.11  5297.3  348.41  5476.3   350.3  5540.8  356.24
  5579.5  361.61  5640.6  370.14  5718.5  383.94  5742.4  386.56  5750.3  387.15
#Mann= 7 ,-1 , 0
    3883     .16       0  3904.9     .05       0  3928.6     .05       0
  4783.2     .03       0  5113.2     .05       0  5579.5      .1       0
  5742.4     .16       0
Bank Sta=4773.2,5133.2
XS Rating Curve= 0 ,0
Exp/Cntr=0.3,0.1

Type RM Length L Ch R = 1 ,2641    ,1061,1061,1061
BEGIN DESCRIPTION:
SOUTH MINERAL CR TRIB 3 2 1
END DESCRIPTION:
XS GIS Cut Line= 4
       3521031.4     10387071.72       3521117.7     10386996.32
      3521166.48     10386644.21      3520392.22     10386302.22
#Sta/Elev= 30
  4427.5  349.15  4435.1  348.51  4441.8  348.97  4449.4   348.2  4470.3  348.81
  4541.5  348.81  4718.4  346.95  4917.5  346.57  4940.8   345.7  4987.4  345.73
  4990.9  345.67  4991.2  345.17  4994.9  345.67  5033.5  345.93  5175.7  346.25
  5208.1  346.74  5312.3  347.08  5382.2  348.33  5434.3  352.81  5463.1  356.66
  5480.9  357.67  5492.7   360.1  5503.6  361.01  5515.2  363.07  5585.1  372.33
  5608.4  376.76  5667.6  384.66  5689.5   386.7  5722.3  387.72    5744  388.03
#Mann= 4 ,-1 , 0
  4427.5     .05       0  4940.8     .03       0  5175.7     .05       0
  5722.3     .16       0
Bank Sta=4917.5,5208.1
XS Rating Curve= 0 ,0
Exp/Cntr=0.3,0.1

Type RM Length L Ch R = 1 ,1580    ,0,0,0
BEGIN DESCRIPTION:
SOUTH MINERAL CR TRIB 3 2 0
END DESCRIPTION:
XS GIS Cut Line= 3
      3521121.64      10387001.4      3521504.23     10386082.43
      3520681.27     10385908.81
#Sta/Elev= 30
  4083.3  348.87  4180.8  347.28  4440.8  346.17  4505.5  344.81  4536.2  345.72
  4841.3   344.3  4849.4  344.44  4971.3  343.94  5001.5   342.2  5025.4  344.36
  5047.1  344.61  5106.6     344  5255.9  345.22  5300.6  345.04  5345.3  343.56
  5350.4  344.35    5395  343.81  5400.1  344.84  5444.8  344.18  5449.9  345.07
  5510.1   343.5  5539.2  344.82  5544.3  343.85  5632.8  345.09    5827  360.21
  5837.9  361.57  5857.6  366.02  5882.5  368.48  5888.3  370.51  5919.8  375.14
#Mann= 3 ,-1 , 0
  4083.3     .05       0  4841.3     .03       0  5047.1     .05       0
Bank Sta=4849.4,5025.4
XS Rating Curve= 0 ,0
Exp/Cntr=0.3,0.1

Chan Stop Cuts=-1
Use User Specified Reach Order=0
Composite Channel Slope=5