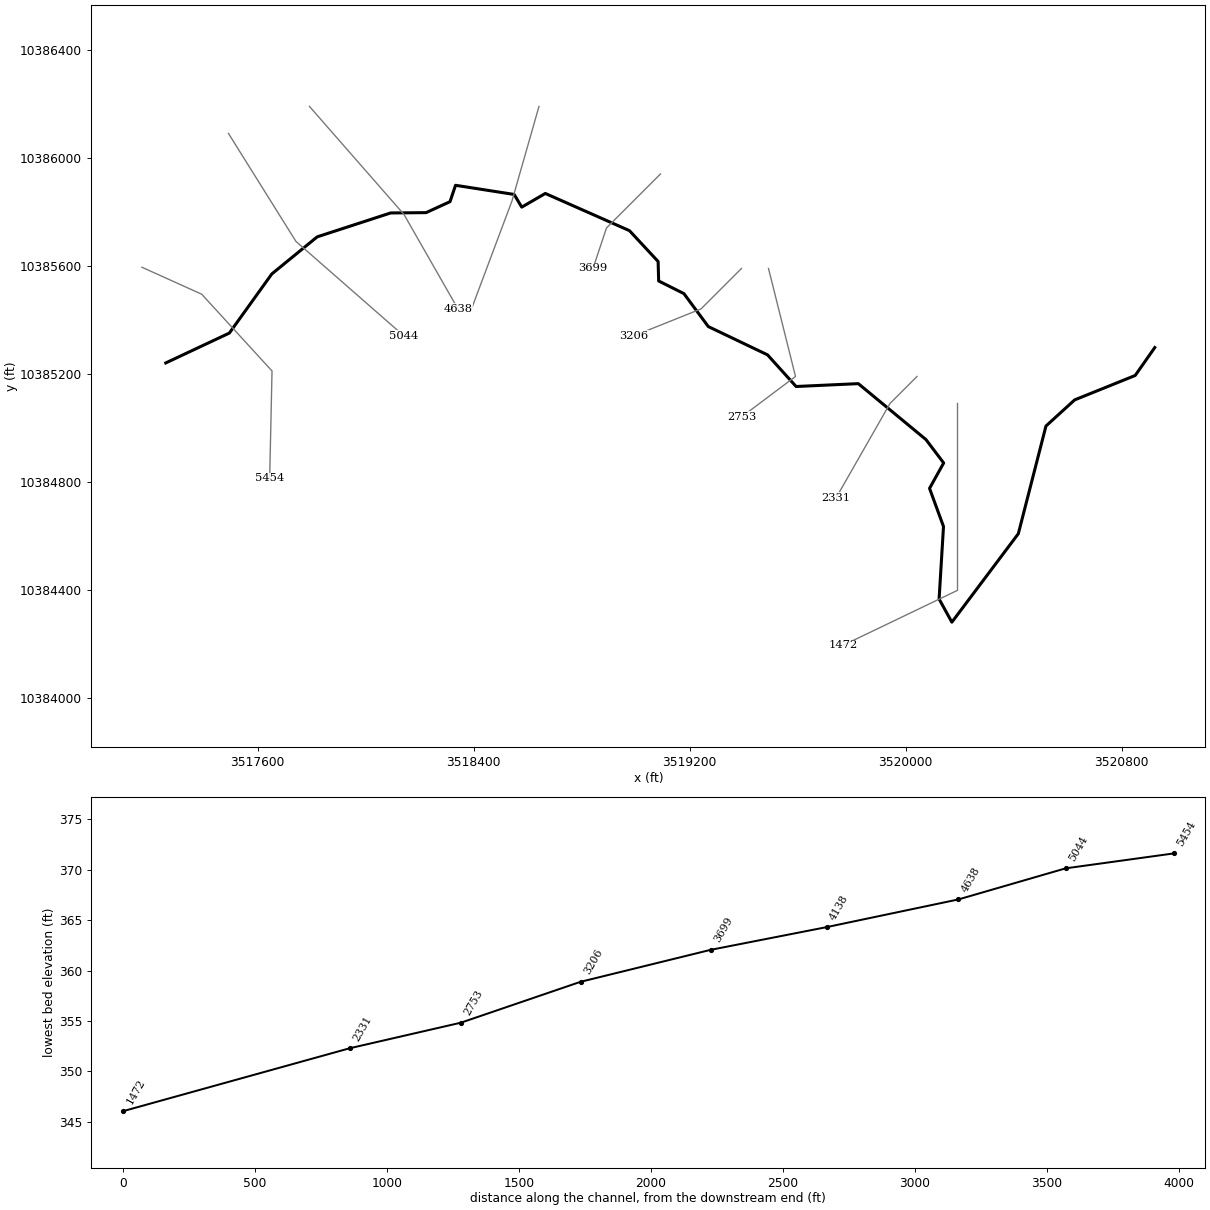
--- SOUTH MINERAL CR TRIB 4 1.prj (project) ---

Proj Title=SOUTH MINERAL CR TRIB 4 1 Base Level Engineering
Current Plan=p01
Default Exp/Contr=0.3,0.1
English Units
Geom File=g01
Flow File=f01
Plan File=p01
BEGIN DESCRIPTION:
SOUTH MINERAL CR TRIB 4 1
END DESCRIPTION:

--- SOUTH MINERAL CR TRIB 4 1.p01 (plan) ---

Plan Title=Multiple Run
Short Identifier=Multiple
Geom File=g01
Flow File=f01
Subcritical Flow
K Sum by GR= 0
Std Step Tol= 0.01
Critical Tol= 0.01
Num of Std Step Trials= 20
Max Error Tol= 0.3
Flow Tol Ratio= 0.001
Split Flow NTrial= 30
Split Flow Tol= 0.02
Split Flow Ratio= 0.02
Log Output Level= 0
Friction Slope Method= 1
Unsteady Friction Slope Method= 2
Unsteady Bridges Friction Slope Method= 1
Parabolic Critical Depth
Global Vel Dist=  1 , 1 , 1
Global Log Level= 0
CheckData=True
Encroach Param= -1, 0, 0, 0
BEGIN DESCRIPTION:
Multiple Run
END DESCRIPTION:

--- SOUTH MINERAL CR TRIB 4 1.f01 (steady flow) ---

Flow Title=Multiple
Number of Profiles=7
Profile Names=10-year,25-year,50-year,1pct_min,100-year,1pct_plu,500-year
River Rch & RM= SOUTH MINERAL CR,Reach-1,5454
    1398    1990    2495    2282    3086    4174    4715
Boundary for River Rch & Prof#=SOUTH MINERAL CR,Reach-1,1
Up Type=0
Dn Type=3
Dn Slope=0.005
Boundary for River Rch & Prof#=SOUTH MINERAL CR,Reach-1,2
Up Type=0
Dn Type=3
Dn Slope=0.005
Boundary for River Rch & Prof#=SOUTH MINERAL CR,Reach-1,3
Up Type=0
Dn Type=3
Dn Slope=0.005
Boundary for River Rch & Prof#=SOUTH MINERAL CR,Reach-1,4
Up Type=0
Dn Type=3
Dn Slope=0.005
Boundary for River Rch & Prof#=SOUTH MINERAL CR,Reach-1,5
Up Type=0
Dn Type=3
Dn Slope=0.005
Boundary for River Rch & Prof#=SOUTH MINERAL CR,Reach-1,6
Up Type=0
Dn Type=3
Dn Slope=0.005
Boundary for River Rch & Prof#=SOUTH MINERAL CR,Reach-1,7
Up Type=0
Dn Type=3
Dn Slope=0.005

--- SOUTH MINERAL CR TRIB 4 1.g01 (geometry) ---

Geom Title=Existing Conditions

River Reach=SOUTH MINERAL CR,Reach-1
Reach XY= 30
      3517259.77     10385241.64      3517495.42     10385352.30
      3517652.72     10385571.34      3517820.80     10385708.69
      3518092.81     10385797.15      3518223.96     10385798.32
      3518312.59     10385838.94      3518333.05     10385899.59
      3518550.16     10385865.68      3518578.26     10385818.70
      3518665.58     10385869.36      3518977.19     10385731.60
      3519083.31     10385617.39      3519085.30     10385545.27
      3519178.81     10385498.45      3519269.23     10385376.33
      3519488.53     10385271.63      3519594.25     10385154.44
      3519824.73     10385165.02      3520075.20     10384957.92
      3520140.85     10384871.24      3520088.53     10384777.10
      3520140.20     10384635.95      3520123.91     10384367.47
      3520171.14     10384281.55      3520417.32     10384609.26
      3520519.68     10385008.04      3520626.00     10385104.86
      3520850.12     10385195.25      3520922.65     10385298.70

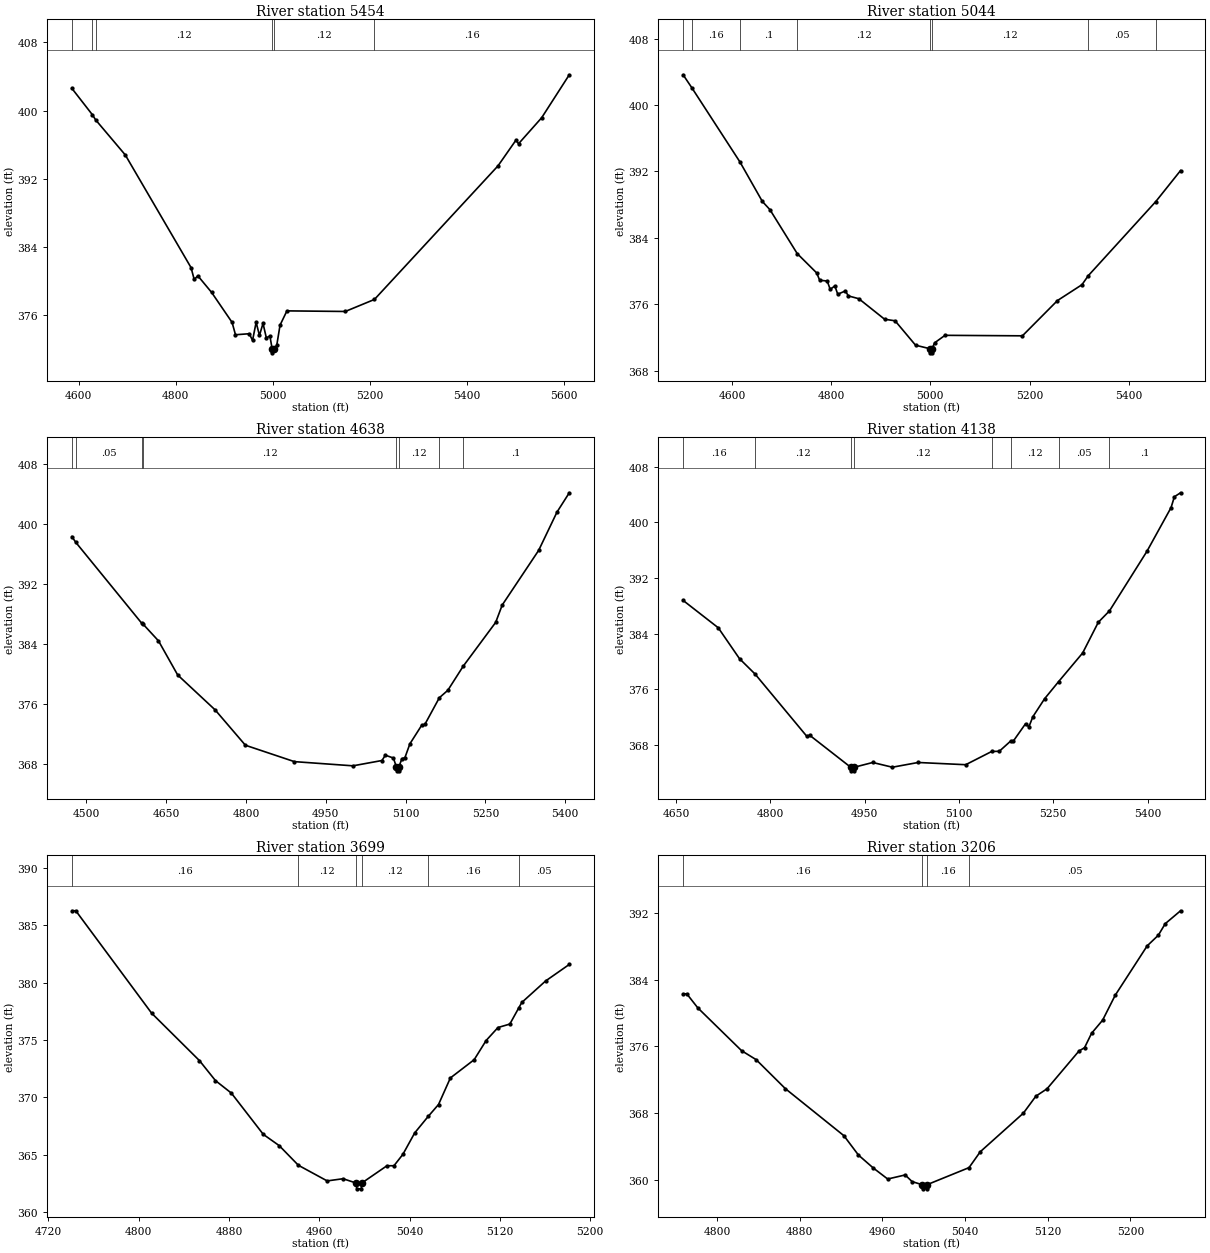
Type RM Length L Ch R = 1,5454,410,410,410
BEGIN DESCRIPTION:
SOUTH MINERAL CR TRIB 4 1 19 0
END DESCRIPTION:
XS GIS Cut Line= 4
      3517171.66     10385596.06      3517392.99     10385496.24
      3517653.41     10385211.95      3517644.77     10384814.68
#Sta/Elev= 30
  4586.0  402.62  4628.4  399.52  4635.1  398.92  4696.2  394.81  4831.8  381.60
  4838.3  380.21  4845.8  380.64  4874.1  378.70  4916.4  375.18  4923.4  373.73
  4951.8  373.85  4958.6  373.07  4966.0  375.19  4972.8  373.65  4980.2  375.06
  4987.0  373.37  4994.4  373.58  4998.9  372.11  4999.2  371.61  5003.3  372.11
  5008.5  372.49  5015.3  374.86  5029.5  376.53  5149.8  376.46  5209.9  377.87
  5464.7  393.53  5501.9  396.56  5507.0  396.12  5554.7  399.17  5611.7  404.21
#Mann=6,-1,0
  4586.0    0.16       0  4628.4     0.1       0  4635.1    0.12       0
  4998.9    0.07       0  5003.3    0.12       0  5209.9    0.16       0
Bank Sta=4998.9,5003.3
Exp/Cntr=0.3,0.1

Type RM Length L Ch R = 1,5044,406,406,406
BEGIN DESCRIPTION:
SOUTH MINERAL CR TRIB 4 1 29 0
END DESCRIPTION:
XS GIS Cut Line= 3
      3517492.09     10386091.66      3517742.11     10385691.64
      3518142.09     10385341.66
#Sta/Elev= 30
  4501.4  403.63  4519.6  402.01  4616.1  393.12  4661.2  388.37  4676.5  387.38
  4731.5  382.09  4770.9  379.75  4776.8  378.88  4792.1  378.78  4798.0  377.78
  4807.4  378.19  4813.3  377.19  4828.7  377.59  4834.6  376.99  4855.8  376.65
  4907.7  374.18  4928.9  373.99  4970.2  371.05  4998.9  370.63  4999.2  370.13
  5003.1  370.13  5003.4  370.63  5008.7  371.34  5029.6  372.24  5185.7  372.18
  5256.4  376.43  5305.8  378.34  5318.6  379.43  5454.6  388.35  5504.6  392.09
#Mann=8,-1,0
  4501.4    0.05       0  4519.6    0.16       0  4616.1     0.1       0
  4731.5    0.12       0  4998.9    0.07       0  5003.4    0.12       0
  5318.6    0.05       0  5454.6     0.1       0
Bank Sta=4998.9,5003.4
Exp/Cntr=0.3,0.1

Type RM Length L Ch R = 1,4638,500,500,500
BEGIN DESCRIPTION:
SOUTH MINERAL CR TRIB 4 1 9 0
END DESCRIPTION:
XS GIS Cut Line= 3
      3517792.08     10386191.67      3518142.11     10385791.64
      3518342.13     10385441.60
#Sta/Elev= 30
  4473.0  398.34  4480.4  397.57  4604.0  386.79  4606.5  386.67  4635.8  384.41
  4671.9  379.85  4742.1  375.20  4799.1  370.47  4891.1  368.28  5001.2  367.72
  5055.7  368.43  5062.1  369.14  5077.2  368.76  5082.9  367.55  5083.2  367.05
  5087.1  367.05  5087.5  367.55  5093.1  368.67  5098.8  368.80  5108.2  370.66
  5130.5  373.15  5136.3  373.25  5163.5  376.81  5179.5  377.81  5208.3  381.02
  5269.4  386.88  5281.7  389.20  5350.1  396.49  5384.6  401.61  5407.7  404.19
#Mann=8,-1,0
  4473.0    0.16       0  4480.4    0.05       0  4604.0    0.16       0
  4606.5    0.12       0  5082.9    0.07       0  5087.5    0.12       0
  5163.5    0.05       0  5208.3     0.1       0
Bank Sta=5082.9,5087.5
Exp/Cntr=0.3,0.1

Type RM Length L Ch R = 1,4138,439,439,439
BEGIN DESCRIPTION:
SOUTH MINERAL CR TRIB 4 1 8 0
END DESCRIPTION:
XS GIS Cut Line= 3
      3518642.11     10386191.66      3518542.11     10385841.64
      3518392.11     10385441.67
#Sta/Elev= 30
  4661.3  388.78  4717.2  384.85  4751.0  380.41  4775.7  378.21  4857.6  369.31
  4862.8  369.40  4928.1  364.80  4928.4  364.30  4932.4  364.30  4932.8  364.80
  4962.9  365.50  4994.1  364.82  5035.1  365.50  5110.8  365.18  5152.1  367.08
  5164.2  367.11  5182.2  368.57  5186.4  368.56  5206.0  371.07  5211.3  370.62
  5217.6  372.07  5236.3  374.66  5258.5  377.11  5296.8  381.23  5321.7  385.64
  5339.5  387.28  5399.1  395.84  5437.4  402.11  5442.7  403.67  5452.5  404.24
#Mann=8,-1,0
  4661.3    0.16       0  4775.7    0.12       0  4928.1    0.07       0
  4932.8    0.12       0  5152.1    0.16       0  5182.2    0.12       0
  5258.5    0.05       0  5339.5     0.1       0
Bank Sta=4928.1,4932.8
Exp/Cntr=0.3,0.1

Type RM Length L Ch R = 1,3699,493,493,493
BEGIN DESCRIPTION:
SOUTH MINERAL CR TRIB 4 1 7 0
END DESCRIPTION:
XS GIS Cut Line= 3
      3519092.09     10385941.63      3518892.11     10385741.64
      3518842.12     10385591.68
#Sta/Elev= 30
  4740.7  386.25  4744.2  386.25  4811.4  377.34  4853.8  373.21  4868.0  371.47
  4882.1  370.38  4910.4  366.79  4924.5  365.81  4941.5  364.10  4967.0  362.74
  4981.1  362.93  4992.8  362.55  4993.2  362.05  4997.3  362.05  4997.6  362.55
  5020.0  364.06  5026.2  364.06  5034.1  365.05  5044.6  366.92  5056.6  368.36
  5065.7  369.39  5076.2  371.70  5097.3  373.29  5107.9  374.96  5118.4  376.09
  5128.9  376.39  5136.6  377.76  5139.5  378.27  5160.6  380.14  5181.6  381.58
#Mann=6,-1,0
  4740.7    0.16       0  4941.5    0.12       0  4992.8    0.07       0
  4997.6    0.12       0  5056.6    0.16       0  5136.6    0.05       0
Bank Sta=4992.8,4997.6
Exp/Cntr=0.3,0.1

Type RM Length L Ch R = 1,3206,453,453,453
BEGIN DESCRIPTION:
SOUTH MINERAL CR TRIB 4 1 6 0
END DESCRIPTION:
XS GIS Cut Line= 3
      3519392.13     10385591.67      3519242.11     10385441.64
      3518992.13     10385341.65
#Sta/Elev= 30
  4767.1  382.32  4770.7  382.32  4781.3  380.64  4823.7  375.49  4837.8  374.41
  4866.1  370.92  4922.7  365.27  4936.8  362.94  4951.0  361.40  4965.1  360.06
  4982.0  360.55  4988.7  359.75  4998.4  359.38  4998.8  358.88  5002.9  358.88
  5003.2  359.38  5043.8  361.43  5054.7  363.34  5096.4  367.98  5108.5  370.02
  5119.3  370.91  5150.2  375.45  5155.6  375.85  5162.4  377.58  5173.1  379.16
  5185.3  382.16  5216.2  388.09  5227.0  389.37  5233.7  390.76  5248.5  392.31
#Mann=4,-1,0
  4767.1    0.16       0  4998.4    0.07       0  5003.2    0.16       0
  5043.8    0.05       0
Bank Sta=4998.4,5003.2
Exp/Cntr=0.3,0.1

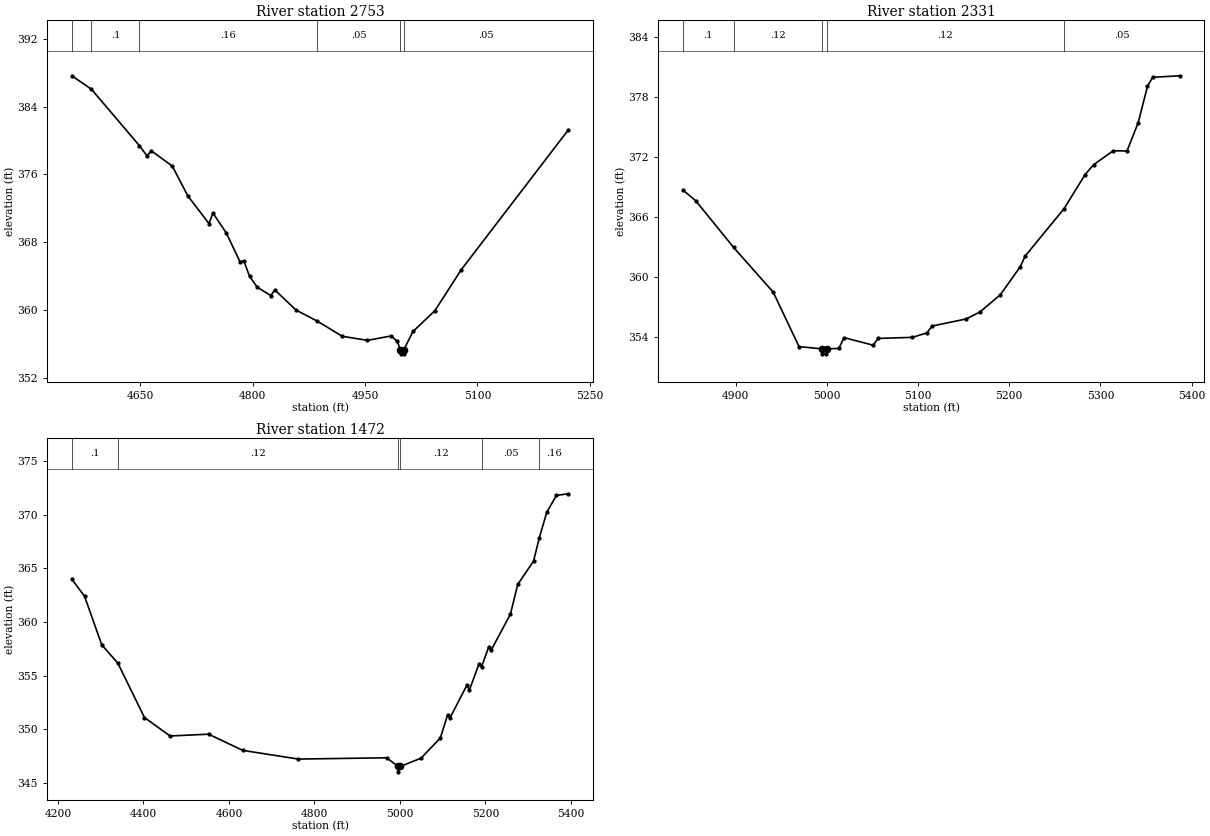
Type RM Length L Ch R = 1,2753,422,422,422
BEGIN DESCRIPTION:
SOUTH MINERAL CR TRIB 4 1 5 0
END DESCRIPTION:
XS GIS Cut Line= 3
      3519492.10     10385591.68      3519592.11     10385191.64
      3519392.07     10385041.61
#Sta/Elev= 30
  4559.0  387.65  4585.2  386.06  4649.0  379.42  4659.5  378.17  4664.7  378.82
  4693.0  376.99  4713.7  373.48  4742.0  370.20  4747.2  371.46  4765.2  369.07
  4783.2  365.72  4788.4  365.81  4796.1  363.97  4806.4  362.69  4824.5  361.70
  4829.6  362.39  4858.0  360.00  4885.8  358.72  4919.8  356.90  4953.3  356.42
  4984.9  356.94  4993.2  356.30  4997.1  355.33  4997.4  354.83  5001.5  354.83
  5001.9  355.33  5014.1  357.47  5043.2  359.92  5078.6  364.78  5221.4  381.28
#Mann=6,-1,0
  4559.0    0.16       0  4585.2     0.1       0  4649.0    0.16       0
  4885.8    0.05       0  4997.1    0.03       0  5001.9    0.05       0
Bank Sta=4997.1,5001.9
Exp/Cntr=0.3,0.1

Type RM Length L Ch R = 1,2331,859,859,859
BEGIN DESCRIPTION:
SOUTH MINERAL CR TRIB 4 1 4 0
END DESCRIPTION:
XS GIS Cut Line= 3
      3520042.11     10385191.64      3519942.11     10385091.64
      3519742.12     10384741.67
#Sta/Elev= 30
  4842.2  368.67  4856.3  367.60  4897.8  362.93  4941.2  358.46  4969.5  353.01
  4994.9  352.79  4995.2  352.29  4999.4  352.29  4999.8  352.79  5013.1  352.83
  5018.9  353.91  5050.6  353.16  5056.3  353.83  5093.8  353.94  5109.6  354.38
  5115.4  355.07  5152.8  355.78  5167.9  356.48  5190.2  358.20  5211.8  360.97
  5217.6  362.09  5260.0  366.80  5283.1  370.21  5292.4  371.20  5314.0  372.60
  5329.1  372.58  5341.4  375.42  5351.5  379.04  5357.2  379.95  5386.7  380.10
#Mann=5,-1,0
  4842.2     0.1       0  4897.8    0.12       0  4994.9    0.07       0
  4999.8    0.12       0  5260.0    0.05       0
Bank Sta=4994.9,4999.8
Exp/Cntr=0.3,0.1

Type RM Length L Ch R = 1,1472,0,0,0
BEGIN DESCRIPTION:
SOUTH MINERAL CR TRIB 4 1 10 0
END DESCRIPTION:
XS GIS Cut Line= 3
      3520192.11     10385091.65      3520192.11     10384399.56
      3519768.45     10384196.03
#Sta/Elev= 30
  4232.4  364.01  4262.4  362.39  4302.4  357.89  4340.2  356.17  4402.4  351.11
  4462.4  349.39  4552.4  349.56  4632.4  348.05  4762.4  347.24  4968.9  347.36
  4996.1  346.55  4996.5  346.05  5001.0  346.55  5049.4  347.32  5094.7  349.20
  5111.8  351.36  5117.3  351.07  5157.0  354.13  5162.6  353.66  5185.2  356.11
  5191.4  355.85  5207.9  357.69  5213.4  357.37  5258.7  360.74  5275.8  363.51
  5312.8  365.68  5326.4  367.87  5343.7  370.23  5366.4  371.81  5394.5  371.96
#Mann=6,-1,0
  4232.4     0.1       0  4340.2    0.12       0  4996.1    0.07       0
  5001.0    0.12       0  5191.4    0.05       0  5326.4    0.16       0
Bank Sta=4996.1,5001
Exp/Cntr=0.3,0.1

Chan Stop Cuts=-1