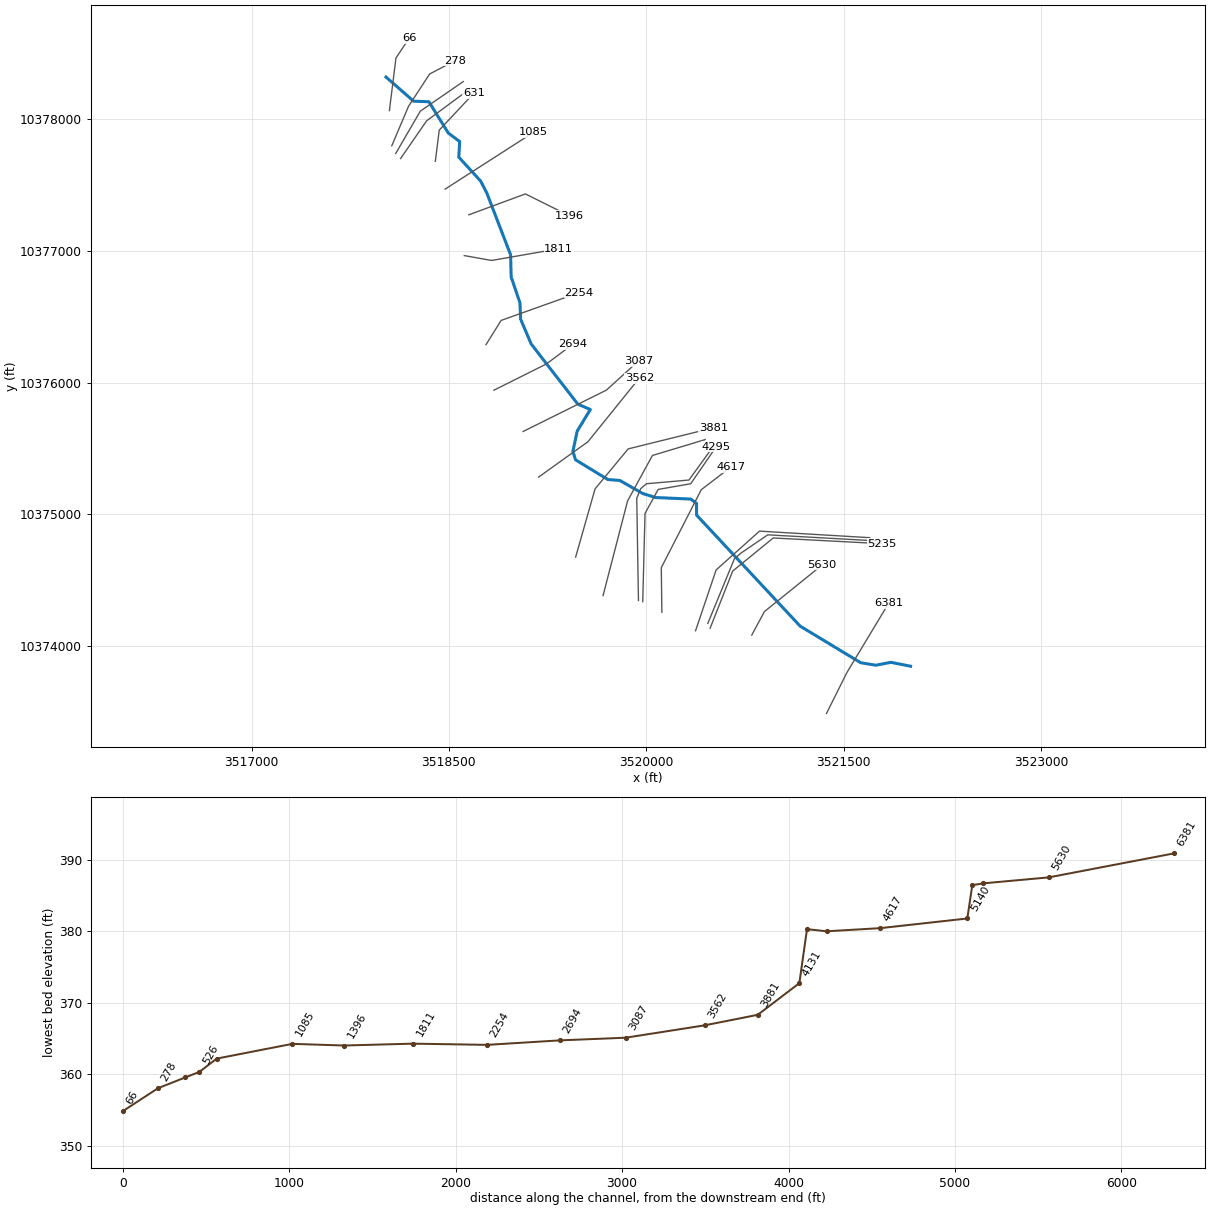
--- SOUTH MINERAL CR TRIB 5.prj (project) ---

Proj Title=SOUTH MINERAL CR TRIB 5 Base Level Engineering
Current Plan=p01
Default Exp/Contr=0.3,0.1
English Units
Geom File=g01
Flow File=f01
Plan File=p01
BEGIN DESCRIPTION:
SOUTH MINERAL CR TRIB 5
END DESCRIPTION:

--- SOUTH MINERAL CR TRIB 5.p01 (plan) ---

Plan Title=Multiple Run
Short Identifier=Multiple
Geom File=g01
Flow File=f01
Subcritical Flow
K Sum by GR= 0
Std Step Tol= 0.01
Critical Tol= 0.01
Num of Std Step Trials= 20
Max Error Tol= 0.3
Flow Tol Ratio= 0.001
Split Flow NTrial= 30
Split Flow Tol= 0.02
Split Flow Ratio= 0.02
Log Output Level= 0
Friction Slope Method= 1
Unsteady Friction Slope Method= 2
Unsteady Bridges Friction Slope Method= 1
Parabolic Critical Depth
Global Vel Dist=  1 , 1 , 1
Global Log Level= 0
CheckData=True
Encroach Param= -1, 0, 0, 0
BEGIN DESCRIPTION:
Multiple Run
END DESCRIPTION:

--- SOUTH MINERAL CR TRIB 5.f01 (steady flow) ---

Flow Title=Multiple
Number of Profiles=7
Profile Names=10-year,25-year,50-year,1pct_min,100-year,1pct_plu,500-year
River Rch & RM= SOUTH MINERAL CR,Reach-1,6381
     971    1348    1661    1495    2022    2734    2987
River Rch & RM= SOUTH MINERAL CR,Reach-1,4295
    1338    1886    2349    2133    2884    3900    4340
Boundary for River Rch & Prof#=SOUTH MINERAL CR,Reach-1,1
Up Type=0
Dn Type=3
Dn Slope=0.005
Boundary for River Rch & Prof#=SOUTH MINERAL CR,Reach-1,2
Up Type=0
Dn Type=3
Dn Slope=0.005
Boundary for River Rch & Prof#=SOUTH MINERAL CR,Reach-1,3
Up Type=0
Dn Type=3
Dn Slope=0.005
Boundary for River Rch & Prof#=SOUTH MINERAL CR,Reach-1,4
Up Type=0
Dn Type=3
Dn Slope=0.005
Boundary for River Rch & Prof#=SOUTH MINERAL CR,Reach-1,5
Up Type=0
Dn Type=3
Dn Slope=0.005
Boundary for River Rch & Prof#=SOUTH MINERAL CR,Reach-1,6
Up Type=0
Dn Type=3
Dn Slope=0.005
Boundary for River Rch & Prof#=SOUTH MINERAL CR,Reach-1,7
Up Type=0
Dn Type=3
Dn Slope=0.005

--- SOUTH MINERAL CR TRIB 5.g01 (geometry) ---

Geom Title=Existing Conditions

River Reach=SOUTH MINERAL CR,Reach-1
Reach XY= 30
      3522009.27     10373843.53      3521859.27     10373873.39
      3521744.30     10373851.11      3521629.72     10373870.56
      3521170.00     10374148.33      3520383.02     10374991.94
      3520382.11     10375081.64      3520338.45     10375114.21
      3520071.72     10375125.89      3519974.33     10375156.10
      3519799.33     10375255.58      3519708.18     10375262.87
      3519462.81     10375412.50      3519442.61     10375476.25
      3519475.17     10375630.40      3519575.07     10375794.71
      3519480.05     10375835.68      3519125.49     10376293.04
      3519044.91     10376482.81      3519040.16     10376606.02
      3518973.33     10376802.15      3518969.24     10376970.46
      3518788.55     10377440.17      3518741.40     10377531.41
      3518575.30     10377713.02      3518582.11     10377831.64
      3518495.34     10377896.75      3518348.12     10378134.25
      3518232.15     10378138.42      3518022.11     10378321.64

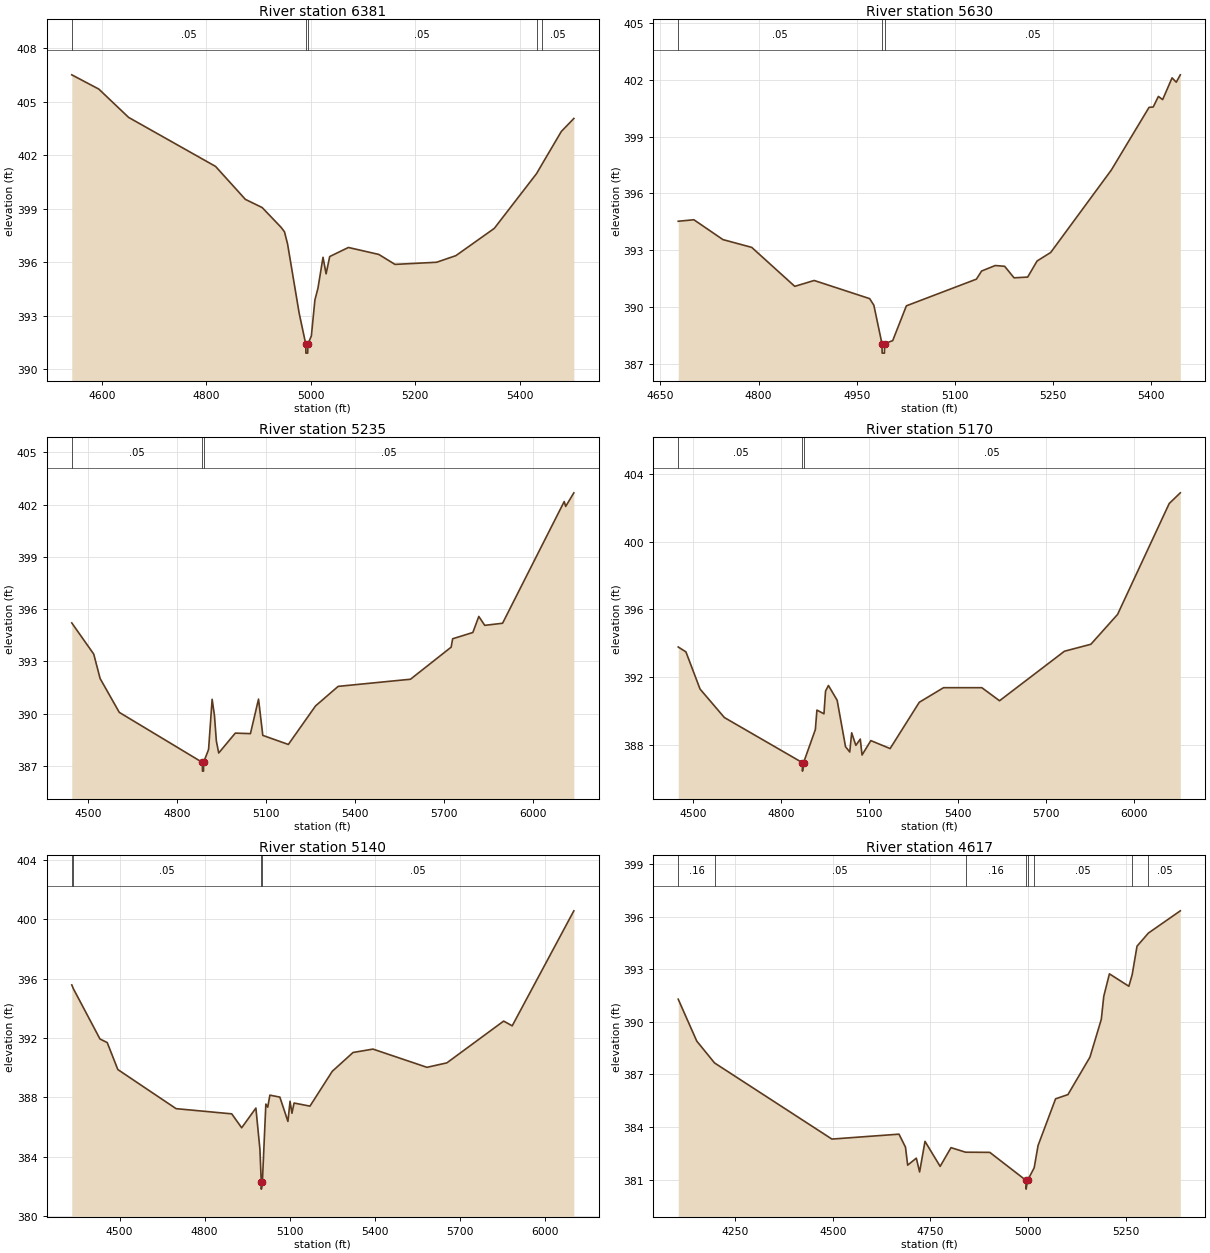
Type RM Length L Ch R = 1,6381,751,751,751
BEGIN DESCRIPTION:
SOUTH MINERAL CR TRIB 5 2 2
END DESCRIPTION:
XS GIS Cut Line= 3
      3521370.34     10373485.32      3521526.61     10373797.85
      3521842.59     10374322.18
#Sta/Elev= 30
  4542.3  406.52  4594.1  405.72  4651.2  404.13  4817.7  401.38  4874.8  399.53
  4907.0  399.07  4942.9  397.97  4949.7  397.71  4955.6  397.03  4977.9  393.13
  4990.5  391.40  4990.7  390.90  4994.2  390.90  4994.5  391.40  5001.2  391.87
  5008.0  393.89  5013.8  394.54  5023.5  396.28  5029.4  395.35  5036.3  396.32
  5072.1  396.83  5130.3  396.44  5161.4  395.88  5241.0  396.00  5277.9  396.37
  5351.5  397.90  5432.6  400.98  5442.3  401.47  5479.9  403.34  5503.9  404.07
#Mann=5,-1,0
  4542.3    0.05       0  4990.5    0.04       0  4994.5    0.05       0
  5432.6    0.08       0  5442.3    0.05       0
Bank Sta=4990.5,4994.5
Exp/Cntr=0.3,0.1

Type RM Length L Ch R = 1,5630,395,395,395
BEGIN DESCRIPTION:
SOUTH MINERAL CR TRIB 5 2 0
END DESCRIPTION:
XS GIS Cut Line= 3
      3520802.45     10374080.62      3520897.94     10374258.58
      3521337.78     10374613.91
#Sta/Elev= 30
  4677.3  394.52  4701.2  394.60  4745.7  393.55  4789.6  393.14  4855.4  391.08
  4885.1  391.39  4969.9  390.43  4976.3  390.08  4988.7  388.05  4989.0  387.55
  4992.5  387.55  4992.7  388.05  5005.1  388.21  5026.0  390.05  5133.0  391.46
  5141.0  391.89  5161.8  392.18  5176.2  392.14  5190.6  391.53  5211.4  391.57
  5225.8  392.42  5246.6  392.87  5339.3  397.23  5396.9  400.54  5403.3  400.56
  5411.2  401.12  5417.7  400.95  5432.1  402.10  5438.5  401.87  5444.7  402.26
#Mann=3,-1,0
  4677.3    0.05       0  4988.7    0.03       0  4992.7    0.05       0
Bank Sta=4988.7,4992.7
Exp/Cntr=0.3,0.1

Type RM Length L Ch R = 1,5235,65,65,65
BEGIN DESCRIPTION:
SOUTH MINERAL CR TRIB 5 22 0
END DESCRIPTION:
XS GIS Cut Line= 4
      3520485.61     10374132.69      3520657.06     10374566.74
      3520965.22     10374818.47      3521792.09     10374775.07
#Sta/Elev= 30
  4444.3  395.21  4518.4  393.42  4539.9  392.02  4604.5  390.08  4884.6  387.21
  4884.9  386.71  4888.4  386.71  4888.6  387.21  4905.5  387.95  4917.5  390.83
  4925.3  389.90  4931.8  388.43  4939.7  387.75  4995.6  388.89  5046.6  388.86
  5073.9  390.84  5088.3  388.76  5174.4  388.24  5266.1  390.45  5342.3  391.57
  5586.2  391.98  5723.3  393.82  5728.3  394.30  5796.4  394.66  5816.5  395.58
  5836.5  395.07  5896.6  395.19  6104.4  402.17  6109.4  401.89  6136.9  402.67
#Mann=3,-1,0
  4444.3    0.05       0  4884.6    0.03       0  4888.6    0.05       0
Bank Sta=4884.6,4888.6
Exp/Cntr=0.3,0.1

Type RM Length L Ch R = 1,5170,30,30,30
BEGIN DESCRIPTION:
Mapping XS 8661b868
END DESCRIPTION:
XS GIS Cut Line= 5
      3520468.26     10374169.62      3520670.08     10374660.05
      3520719.99     10374703.45      3520923.99     10374842.34
      3521785.50     10374794.60
#Sta/Elev= 30
  4450.7  393.78  4476.9  393.49  4524.8  391.30  4607.5  389.62  4872.6  386.96
  4872.9  386.46  4876.6  386.96  4916.6  388.91  4922.0  390.06  4945.9  389.84
  4951.3  391.18  4961.1  391.51  4990.7  390.64  5019.2  387.90  5033.5  387.59
  5040.1  388.72  5054.3  387.98  5069.3  388.35  5075.3  387.41  5105.2  388.26
  5170.7  387.79  5269.8  390.52  5352.2  391.38  5482.4  391.38  5542.5  390.61
  5763.1  393.53  5852.9  393.94  5943.6  395.70  6119.1  402.24  6156.8  402.87
#Mann=3,-1,0
  4450.7    0.05       0  4872.6    0.03       0  4876.6    0.05       0
Bank Sta=4872.6,4876.6
Exp/Cntr=0.3,0.1

Type RM Length L Ch R = 1,5140,523,523,523
BEGIN DESCRIPTION:
SOUTH MINERAL CR TRIB 5 15 0
END DESCRIPTION:
XS GIS Cut Line= 4
      3520374.94     10374113.18      3520531.19     10374575.42
      3520861.05     10374870.56      3521699.02     10374820.75
#Sta/Elev= 30
  4331.5  395.58  4337.0  395.33  4431.0  391.93  4456.5  391.69  4493.9  389.87
  4699.3  387.23  4895.4  386.88  4930.5  385.94  4980.6  387.27  4994.8  384.49
  4999.5  382.30  4999.8  381.80  5003.5  382.30  5015.7  387.54  5022.4  387.33
  5029.9  388.14  5065.1  388.01  5093.5  386.37  5101.0  387.73  5107.7  386.92
  5115.2  387.61  5171.2  387.40  5249.8  389.75  5323.1  391.02  5393.3  391.25
  5583.7  390.02  5653.8  390.32  5854.1  393.14  5884.2  392.82  6101.5  400.58
#Mann=4,-1,0
  4331.5    0.16       0  4337.0    0.05       0  4999.5    0.03       0
  5003.5    0.05       0
Bank Sta=4999.5,5003.5
Exp/Cntr=0.3,0.1

Type RM Length L Ch R = 1,4617,322,322,322
BEGIN DESCRIPTION:
SOUTH MINERAL CR TRIB 5 11 1
END DESCRIPTION:
XS GIS Cut Line= 4
      3520118.86     10374254.22      3520114.52     10374592.78
      3520418.34     10375185.23      3520641.87     10375356.67
#Sta/Elev= 30
  4103.9  391.30  4151.3  388.91  4196.9  387.66  4497.5  383.31  4669.4  383.59
  4686.0  382.85  4691.6  381.82  4713.8  382.22  4722.2  381.43  4736.0  383.18
  4774.8  381.75  4802.6  382.82  4839.9  382.56  4902.0  382.55  4994.8  380.95
  4995.0  380.45  4998.8  380.95  5015.7  381.67  5025.6  382.94  5070.5  385.61
  5102.1  385.85  5158.5  387.99  5187.6  390.15  5193.9  391.46  5208.4  392.75
  5258.2  392.04  5266.7  392.70  5279.1  394.33  5308.3  395.08  5390.0  396.35
#Mann=8,-1,0
  4103.9    0.16       0  4196.9    0.05       0  4839.9    0.16       0
  4994.8    0.07       0  4998.8    0.16       0  5015.7    0.05       0
  5266.7    0.15       0  5308.3    0.05       0
Bank Sta=4994.8,4998.8
Exp/Cntr=0.3,0.1

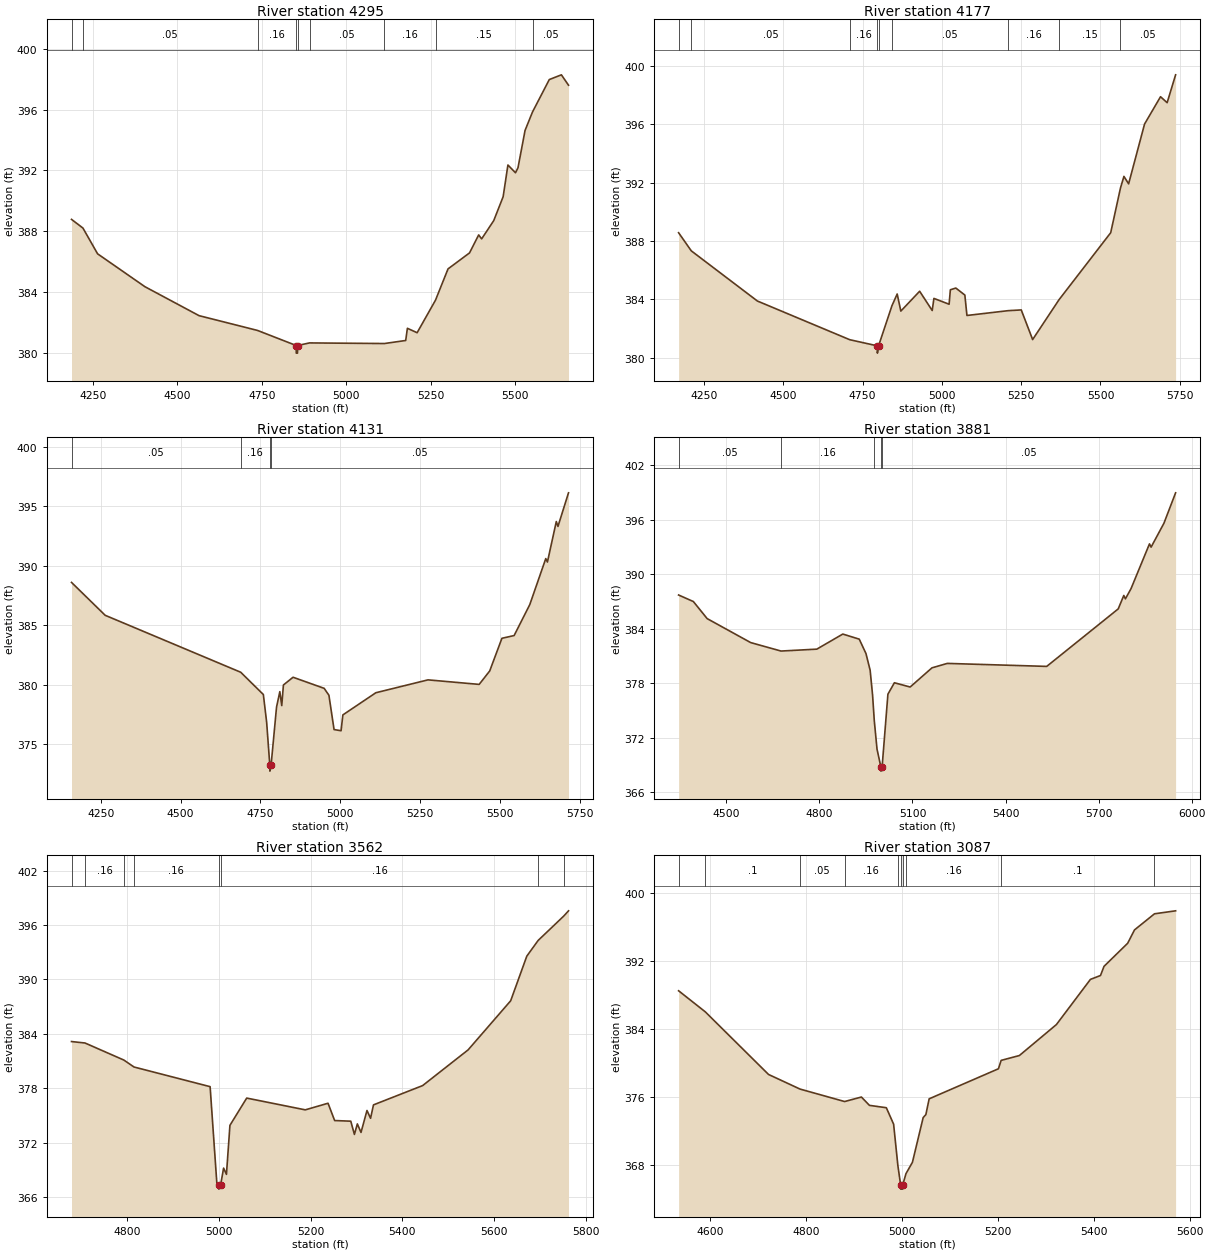
Type RM Length L Ch R = 1,4295,118,118,118
BEGIN DESCRIPTION:
SOUTH MINERAL CR TRIB 5 13 0
END DESCRIPTION:
XS GIS Cut Line= 5
      3519973.46     10374334.54      3519990.83     10375005.10
      3520090.65     10375187.40      3520338.05     10375230.80
      3520531.19     10375510.74
#Sta/Elev= 30
  4187.4  388.79  4221.2  388.22  4264.5  386.53  4404.6  384.37  4564.6  382.47
  4737.5  381.50  4852.0  380.51  4852.2  380.01  4855.7  380.01  4856.0  380.51
  4891.3  380.68  5112.8  380.64  5175.8  380.84  5180.8  381.64  5209.6  381.35
  5264.0  383.49  5301.0  385.54  5364.6  386.59  5391.6  387.77  5400.4  387.51
  5436.2  388.71  5464.0  390.28  5478.1  392.36  5500.5  391.85  5507.9  392.18
  5528.8  394.63  5550.8  395.84  5600.5  397.97  5636.3  398.28  5657.3  397.60
#Mann=9,-1,0
  4187.4    0.16       0  4221.2    0.05       0  4737.5    0.16       0
  4852.0    0.03       0  4856.0    0.16       0  4891.3    0.05       0
  5112.8    0.16       0  5264.0    0.15       0  5550.8    0.05       0
Bank Sta=4852,4856
Exp/Cntr=0.3,0.1

Type RM Length L Ch R = 1,4177,46,46,46
BEGIN DESCRIPTION:
SOUTH MINERAL CR TRIB 5 10 0
END DESCRIPTION:
XS GIS Cut Line= 6
      3519940.91     10374343.25      3519927.89     10375120.12
      3519958.27     10375193.91      3520001.68     10375230.80
      3520325.03     10375259.01      3520515.98     10375523.74
#Sta/Elev= 30
  4170.1  388.56  4210.0  387.32  4418.5  383.88  4709.6  381.23  4796.5  380.81
  4796.8  380.31  4800.5  380.81  4842.7  383.56  4859.2  384.36  4870.7  383.19
  4930.0  384.55  4969.6  383.23  4975.0  384.06  5022.9  383.66  5026.8  384.65
  5044.0  384.77  5072.5  384.29  5079.1  382.89  5209.2  383.22  5250.3  383.27
  5286.2  381.24  5369.4  383.97  5532.3  388.56  5563.1  391.62  5574.0  392.42
  5588.8  391.91  5639.1  396.01  5689.4  397.88  5710.2  397.47  5736.9  399.38
#Mann=9,-1,0
  4170.1    0.16       0  4210.0    0.05       0  4709.6    0.16       0
  4796.5    0.03       0  4800.5    0.16       0  4842.7    0.05       0
  5209.2    0.16       0  5369.4    0.15       0  5563.1    0.05       0
Bank Sta=4796.5,4800.5
Exp/Cntr=0.3,0.1

Type RM Length L Ch R = 1,4131,250,250,250
BEGIN DESCRIPTION:
SOUTH MINERAL CR TRIB 5 12 0
END DESCRIPTION:
XS GIS Cut Line= 4
      3519671.82     10374380.14      3519858.45     10375100.59
      3520047.25     10375445.64      3520448.11     10375566.33
#Sta/Elev= 30
  4158.4  388.60  4263.8  385.84  4688.2  381.06  4759.1  379.19  4769.4  376.87
  4779.3  373.26  4779.5  372.76  4783.3  373.26  4800.4  378.14  4810.7  379.43
  4816.7  378.26  4821.9  379.99  4852.1  380.64  4949.4  379.71  4964.4  379.13
  4980.5  376.25  5002.4  376.15  5008.1  377.48  5111.4  379.34  5274.6  380.42
  5434.9  380.04  5467.9  381.17  5506.1  383.91  5544.3  384.14  5593.4  386.74
  5643.4  390.60  5648.6  390.31  5676.4  393.71  5681.6  393.30  5714.6  396.12
#Mann=4,-1,0
  4158.4    0.05       0  4688.2    0.16       0  4779.3    0.03       0
  4783.3    0.05       0
Bank Sta=4779.3,4783.3
Exp/Cntr=0.3,0.1

Type RM Length L Ch R = 1,3881,319,319,319
BEGIN DESCRIPTION:
SOUTH MINERAL CR TRIB 5 29 0
END DESCRIPTION:
XS GIS Cut Line= 4
      3519463.48     10374673.05      3519611.05     10375191.74
      3519862.79     10375495.56      3520511.68     10375656.15
#Sta/Elev= 30
  4346.0  387.72  4393.6  387.00  4438.1  385.12  4578.5  382.48  4676.2  381.55
  4791.6  381.76  4875.4  383.42  4928.4  382.86  4950.1  381.27  4963.5  379.44
  4971.3  376.73  4976.9  373.87  4985.7  370.75  4997.9  368.83  4998.2  368.33
  5002.2  368.83  5020.8  376.80  5041.7  378.06  5092.5  377.59  5162.8  379.70
  5212.3  380.19  5532.8  379.86  5763.3  386.19  5781.3  387.67  5786.5  387.30
  5804.5  388.41  5864.1  393.35  5869.3  392.99  5910.7  395.62  5948.3  398.97
#Mann=5,-1,0
  4346.0    0.05       0  4676.2    0.16       0  4976.9    0.05       0
  4997.9    0.03       0  5002.2    0.05       0
Bank Sta=4997.9,5002.2
Exp/Cntr=0.3,0.1

Type RM Length L Ch R = 1,3562,475,475,475
BEGIN DESCRIPTION:
SOUTH MINERAL CR TRIB 5 19 0
END DESCRIPTION:
XS GIS Cut Line= 3
      3519181.38     10375280.72      3519556.80     10375549.81
      3519947.28     10376033.58
#Sta/Elev= 30
  4678.7  383.15  4708.1  382.99  4792.7  381.11  4815.0  380.34  4980.9  378.17
  4995.6  367.49  4999.6  367.36  4999.9  366.86  5003.9  367.36  5010.3  369.18
  5016.5  368.49  5024.1  373.90  5060.7  376.91  5188.4  375.61  5238.0  376.34
  5252.4  374.43  5287.6  374.36  5295.5  372.90  5301.9  374.06  5309.9  373.12
  5322.9  375.54  5330.7  374.68  5337.1  376.16  5444.3  378.29  5543.4  382.23
  5636.2  387.65  5671.4  392.58  5696.1  394.31  5752.3  397.02  5762.3  397.58
#Mann=8,-1,0
  4678.7    0.05       0  4708.1    0.16       0  4792.7    0.05       0
  4815.0    0.16       0  4999.6    0.07       0  5003.9    0.16       0
  5696.1     0.1       0  5752.3    0.05       0
Bank Sta=4999.6,5003.9
Exp/Cntr=0.3,0.1

Type RM Length L Ch R = 1,3087,393,393,393
BEGIN DESCRIPTION:
SOUTH MINERAL CR TRIB 5 9 0
END DESCRIPTION:
XS GIS Cut Line= 3
      3519064.20     10375627.95      3519697.86     10375942.60
      3519940.89     10376163.94
#Sta/Elev= 30
  4534.8  388.50  4590.4  386.02  4722.3  378.64  4787.9  376.92  4880.9  375.45
  4915.9  375.98  4932.7  375.00  4967.9  374.72  4983.1  372.78  4991.9  367.94
  4997.7  365.63  4998.0  365.13  5001.8  365.13  5002.1  365.63  5008.9  366.96
  5022.3  368.29  5044.7  373.56  5050.3  373.91  5057.2  375.77  5201.6  379.31
  5207.3  380.30  5245.3  380.87  5322.5  384.52  5393.4  389.84  5414.4  390.30
  5421.8  391.38  5471.1  394.10  5485.3  395.67  5527.0  397.57  5571.0  397.92
#Mann=10,-1,0
  4534.8    0.05       0  4590.4     0.1       0  4787.9    0.05       0
  4880.9    0.16       0  4991.9    0.05       0  4997.7    0.03       0
  5002.1    0.05       0  5008.9    0.16       0  5207.3     0.1       0
  5527.0    0.05       0
Bank Sta=4997.7,5002.1
Exp/Cntr=0.3,0.1

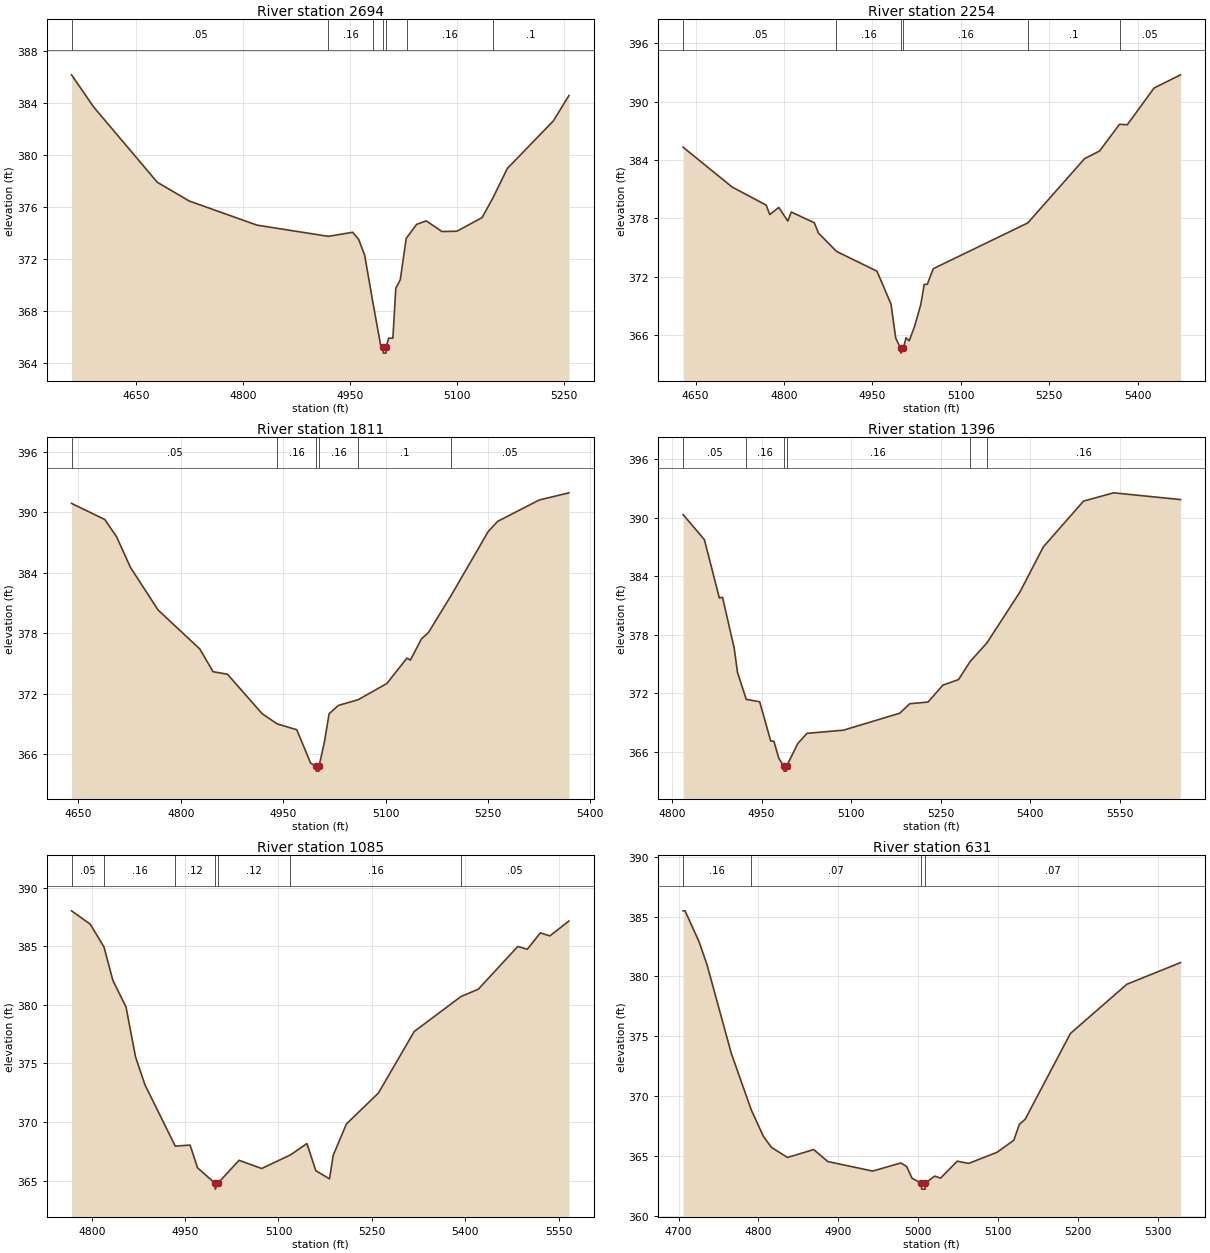
Type RM Length L Ch R = 1,2694,440,440,440
BEGIN DESCRIPTION:
SOUTH MINERAL CR TRIB 5 8 0
END DESCRIPTION:
XS GIS Cut Line= 3
      3518842.08     10375941.63      3519242.11     10376141.64
      3519442.07     10376291.62
#Sta/Elev= 30
  4559.5  386.18  4590.3  383.72  4679.7  377.91  4724.4  376.47  4819.5  374.61
  4919.3  373.75  4953.6  374.06  4962.0  373.51  4970.4  372.29  4981.6  368.75
  4992.8  365.36  4996.2  365.26  4996.5  364.76  5000.3  364.76  5000.6  365.26
  5003.9  365.91  5009.9  365.91  5014.0  369.75  5020.3  370.41  5028.6  373.60
  5029.8  373.68  5043.2  374.67  5056.7  374.94  5078.6  374.12  5099.5  374.14
  5134.9  375.19  5149.8  376.67  5170.3  378.97  5234.9  382.64  5256.7  384.59
#Mann=7,-1,0
  4559.5    0.05       0  4919.3    0.16       0  4981.6    0.05       0
  4996.2    0.03       0  5000.6    0.05       0  5029.8    0.16       0
  5149.8     0.1       0
Bank Sta=4996.2,5000.6
Exp/Cntr=0.3,0.1

Type RM Length L Ch R = 1,2254,443,443,443
BEGIN DESCRIPTION:
SOUTH MINERAL CR TRIB 5 7 0
END DESCRIPTION:
XS GIS Cut Line= 3
      3518782.07     10376287.67      3518897.08     10376472.12
      3519487.20     10376682.57
#Sta/Elev= 30
  4628.8  385.32  4712.0  381.22  4769.8  379.36  4775.7  378.39  4791.1  379.12
  4806.4  377.72  4812.3  378.65  4851.5  377.54  4858.2  376.50  4889.0  374.60
  4957.7  372.56  4981.5  369.18  4989.5  365.67  4997.9  364.63  4998.2  364.13
  5002.4  364.63  5007.0  365.71  5012.3  365.39  5021.4  366.87  5032.0  369.13
  5037.8  371.20  5043.1  371.22  5053.2  372.82  5213.6  377.53  5309.8  384.14
  5335.3  384.93  5369.2  387.68  5382.4  387.63  5427.7  391.41  5472.7  392.77
#Mann=6,-1,0
  4628.8    0.05       0  4889.0    0.16       0  4997.9    0.07       0
  5002.4    0.16       0  5213.6     0.1       0  5369.2    0.05       0
Bank Sta=4997.9,5002.4
Exp/Cntr=0.3,0.1

Type RM Length L Ch R = 1,1811,415,415,415
BEGIN DESCRIPTION:
SOUTH MINERAL CR TRIB 5 6 0
END DESCRIPTION:
XS GIS Cut Line= 3
      3518617.10     10376964.74      3518825.46     10376927.85
      3519334.96     10377016.74
#Sta/Elev= 30
  4639.9  390.88  4688.5  389.29  4705.9  387.57  4726.2  384.53  4766.8  380.29
  4827.8  376.43  4847.3  374.17  4868.4  373.92  4919.2  370.00  4941.2  368.99
  4969.9  368.41  4990.2  365.10  4998.1  364.80  4998.4  364.30  5002.3  364.30
  5002.6  364.80  5010.5  367.23  5017.3  370.00  5030.8  370.82  5060.1  371.40
  5101.9  373.00  5131.3  375.52  5136.4  375.32  5152.6  377.43  5162.8  378.06
  5196.0  381.73  5250.4  388.09  5264.3  389.10  5325.2  391.22  5368.7  391.93
#Mann=6,-1,0
  4639.9    0.05       0  4941.2    0.16       0  4998.1    0.07       0
  5002.6    0.16       0  5060.1     0.1       0  5196.0    0.05       0
Bank Sta=4998.1,5002.6
Exp/Cntr=0.3,0.1

Type RM Length L Ch R = 1,1396,311,311,311
BEGIN DESCRIPTION:
SOUTH MINERAL CR TRIB 5 5 0
END DESCRIPTION:
XS GIS Cut Line= 3
      3518651.82     10377275.06      3519081.54     10377433.49
      3519417.29     10377266.70
#Sta/Elev= 30
  4818.6  390.30  4854.2  387.74  4879.3  381.76  4884.6  381.83  4904.2  376.60
  4909.7  374.14  4924.3  371.39  4946.8  371.14  4965.3  367.12  4970.6  367.10
  4978.8  365.36  4987.1  364.54  4987.5  364.04  4991.4  364.04  4991.7  364.54
  5010.8  366.88  5026.1  367.91  5087.0  368.23  5181.3  369.97  5198.1  370.94
  5228.6  371.11  5253.7  372.85  5279.7  373.41  5299.2  375.26  5327.2  377.16
  5382.6  382.38  5421.8  387.00  5489.0  391.68  5539.4  392.53  5651.5  391.84
#Mann=6,-1,0
  4818.6    0.05       0  4924.3    0.16       0  4987.1    0.07       0
  4991.7    0.16       0  5299.2    0.12       0  5327.2    0.16       0
Bank Sta=4987.1,4991.7
Exp/Cntr=0.3,0.1

Type RM Length L Ch R = 1,1085,454,454,454
BEGIN DESCRIPTION:
SOUTH MINERAL CR TRIB 5 2 1
END DESCRIPTION:
XS GIS Cut Line= 2
      3518471.76     10377470.40      3519144.48     10377902.25
#Sta/Elev= 30
  4767.4  388.02  4797.5  386.88  4819.6  384.93  4833.8  382.09  4855.0  379.81
  4870.2  375.57  4885.4  373.17  4934.1  367.94  4957.9  368.03  4969.9  366.09
  4998.0  364.77  4998.4  364.27  5002.6  364.77  5036.6  366.73  5073.0  366.03
  5119.2  367.19  5145.7  368.16  5160.0  365.84  5182.0  365.15  5187.9  367.15
  5209.1  369.83  5260.6  372.47  5318.1  377.72  5393.4  380.71  5421.1  381.33
  5484.6  384.98  5499.8  384.74  5520.9  386.14  5536.1  385.88  5566.8  387.15
#Mann=7,-1,0
  4767.4    0.05       0  4819.6    0.16       0  4934.1    0.12       0
  4998.0    0.07       0  5002.6    0.12       0  5119.2    0.16       0
  5393.4    0.05       0
Bank Sta=4998,5002.6
Exp/Cntr=0.3,0.1

Type RM Length L Ch R = 1,631,105,105,105
BEGIN DESCRIPTION:
SOUTH MINERAL CR TRIB 5 21 0
END DESCRIPTION:
XS GIS Cut Line= 3
      3518397.13     10377681.83      3518426.70     10377918.39
      3518689.65     10378199.33
#Sta/Elev= 30
  4705.6  385.49  4708.0  385.49  4725.6  382.90  4735.6  380.97  4765.9  373.58
  4790.9  368.85  4806.2  366.62  4816.3  365.70  4836.4  364.86  4869.2  365.52
  4886.8  364.52  4943.1  363.72  4978.3  364.40  4985.6  364.11  4992.4  363.12
  5004.0  362.71  5004.4  362.21  5008.8  362.21  5009.2  362.71  5020.8  363.30
  5028.1  363.13  5049.1  364.55  5063.3  364.36  5098.9  365.29  5119.9  366.30
  5126.8  367.62  5134.1  368.05  5190.8  375.23  5261.6  379.35  5328.8  381.16
#Mann=4,-1,0
  4705.6    0.16       0  4790.9    0.07       0  5004.0    0.07       0
  5009.2    0.07       0
Bank Sta=5004,5009.2
Exp/Cntr=0.3,0.1

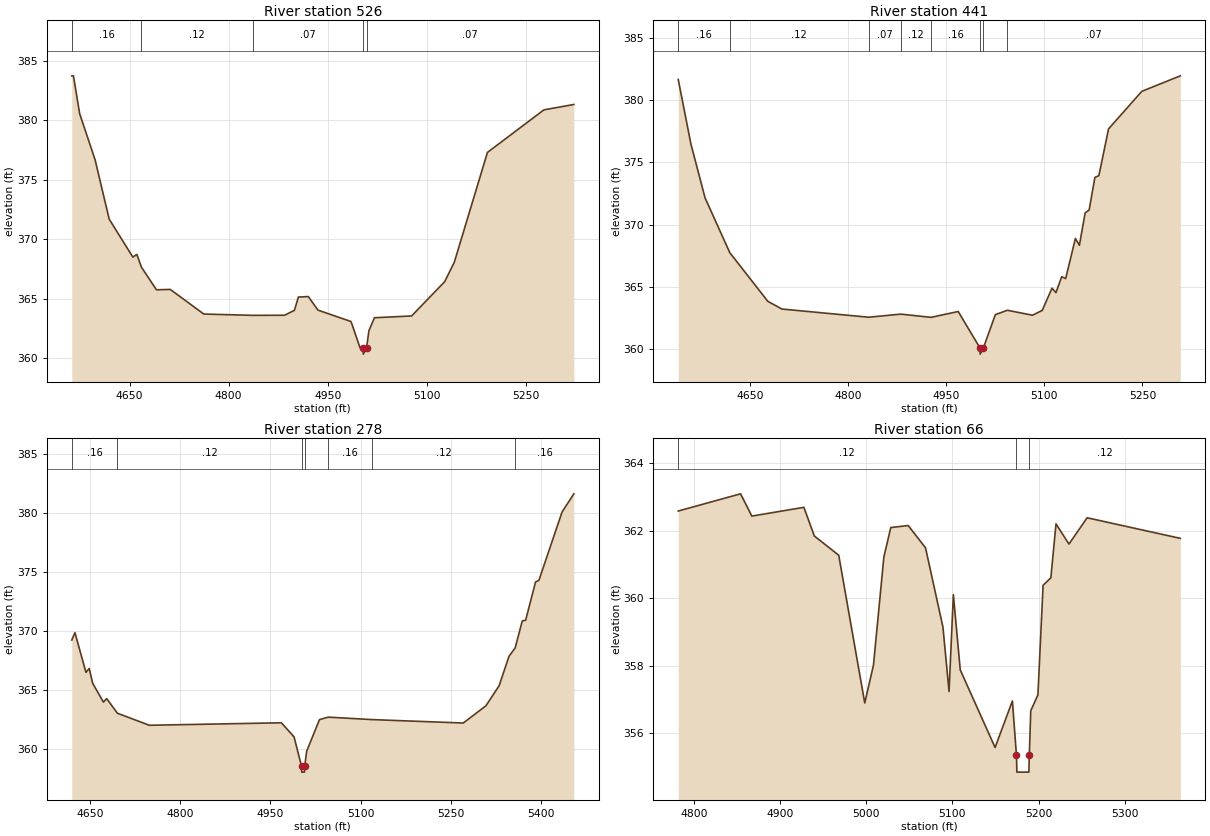
Type RM Length L Ch R = 1,526,85,85,85
BEGIN DESCRIPTION:
SOUTH MINERAL CR TRIB 5 4 0
END DESCRIPTION:
XS GIS Cut Line= 3
      3518133.17     10377702.57      3518330.67     10377989.04
      3518662.68     10378234.25
#Sta/Elev= 30
  4562.3  383.74  4564.8  383.74  4574.3  380.55  4597.6  376.69  4619.0  371.69
  4654.8  368.50  4660.9  368.72  4667.8  367.66  4690.6  365.75  4711.6  365.78
  4762.3  363.71  4837.2  363.60  4884.7  363.61  4899.6  364.02  4905.7  365.14
  4920.7  365.18  4935.3  364.04  4985.4  363.08  4999.1  360.87  5003.6  360.84
  5004.0  360.34  5008.9  360.84  5012.5  362.31  5020.9  363.40  5077.2  363.55
  5127.3  366.43  5141.9  368.07  5192.1  377.30  5277.7  380.88  5323.0  381.33
#Mann=5,-1,0
  4562.3    0.16       0  4667.8    0.12       0  4837.2    0.07       0
  5003.6    0.07       0  5008.9    0.07       0
Bank Sta=5003.6,5008.9
Exp/Cntr=0.3,0.1

Type RM Length L Ch R = 1,441,163,163,163
BEGIN DESCRIPTION:
SOUTH MINERAL CR TRIB 5 3 0
END DESCRIPTION:
XS GIS Cut Line= 3
      3518096.29     10377741.65      3518282.93     10378062.83
      3518609.25     10378287.58
#Sta/Elev= 30
  4540.2  381.68  4559.6  376.48  4581.2  372.15  4619.0  367.74  4677.2  363.82
  4698.7  363.20  4831.3  362.54  4880.7  362.79  4926.7  362.53  4968.3  363.00
  5001.5  360.07  5001.9  359.57  5006.8  360.07  5025.1  362.75  5043.5  363.10
  5081.9  362.70  5096.8  363.09  5111.7  364.88  5117.7  364.52  5126.6  365.80
  5132.6  365.65  5147.5  368.88  5153.6  368.33  5162.4  370.94  5168.5  371.17
  5177.3  373.79  5183.4  373.94  5198.2  377.70  5249.0  380.72  5307.9  381.97
#Mann=8,-1,0
  4540.2    0.16       0  4619.0    0.12       0  4831.3    0.07       0
  4880.7    0.12       0  4926.7    0.16       0  5001.5    0.07       0
  5006.8    0.16       0  5043.5    0.07       0
Bank Sta=5001.5,5006.8
Exp/Cntr=0.3,0.1

Type RM Length L Ch R = 1,278,212,212,212
BEGIN DESCRIPTION:
SOUTH MINERAL CR TRIB 5 11 0
END DESCRIPTION:
XS GIS Cut Line= 4
      3518065.93     10377799.56      3518192.84     10378098.58
      3518353.70     10378345.16      3518545.09     10378445.41
#Sta/Elev= 30
  4619.4  369.26  4624.7  369.89  4643.0  366.52  4648.4  366.85  4654.2  365.60
  4672.1  364.00  4677.5  364.30  4695.3  363.06  4748.5  362.04  4968.1  362.25
  4989.2  361.06  5001.6  358.57  5002.0  358.07  5006.5  358.07  5006.9  358.57
  5010.3  359.85  5031.5  362.52  5046.0  362.73  5119.2  362.52  5270.7  362.23
  5308.4  363.69  5330.4  365.39  5346.8  367.88  5357.1  368.60  5368.9  370.88
  5374.5  370.94  5391.0  374.18  5396.6  374.32  5435.1  380.11  5454.7  381.65
#Mann=7,-1,0
  4619.4    0.16       0  4695.3    0.12       0  5001.6    0.07       0
  5006.9    0.12       0  5046.0    0.16       0  5119.2    0.12       0
  5357.1    0.16       0
Bank Sta=5001.6,5006.9
Exp/Cntr=0.3,0.1

Type RM Length L Ch R = 1,66,0,0,0
BEGIN DESCRIPTION:
SOUTH MINERAL CR TRIB 5 1 0
END DESCRIPTION:
XS GIS Cut Line= 3
      3518047.89     10378066.92      3518097.89     10378466.93
      3518197.39     10378616.18
#Sta/Elev= 30
  4781.9  362.59  4854.2  363.10  4867.3  362.44  4927.7  362.70  4939.8  361.85
  4968.1  361.28  4998.3  356.90  5008.4  358.02  5020.5  361.23  5028.5  362.10
  5048.7  362.16  5068.8  361.50  5089.0  359.15  5096.1  357.24  5101.1  360.11
  5109.1  357.88  5149.5  355.58  5169.6  356.96  5174.3  355.35  5174.8  354.85
  5188.7  354.85  5189.2  355.35  5190.9  356.67  5199.2  357.14  5205.2  360.39
  5214.2  360.61  5220.2  362.21  5235.2  361.61  5256.3  362.39  5364.4  361.78
#Mann=3,-1,0
  4781.9    0.12       0  5174.3    0.07       0  5189.2    0.12       0
Bank Sta=5174.3,5189.2
Exp/Cntr=0.3,0.1

Chan Stop Cuts=-1