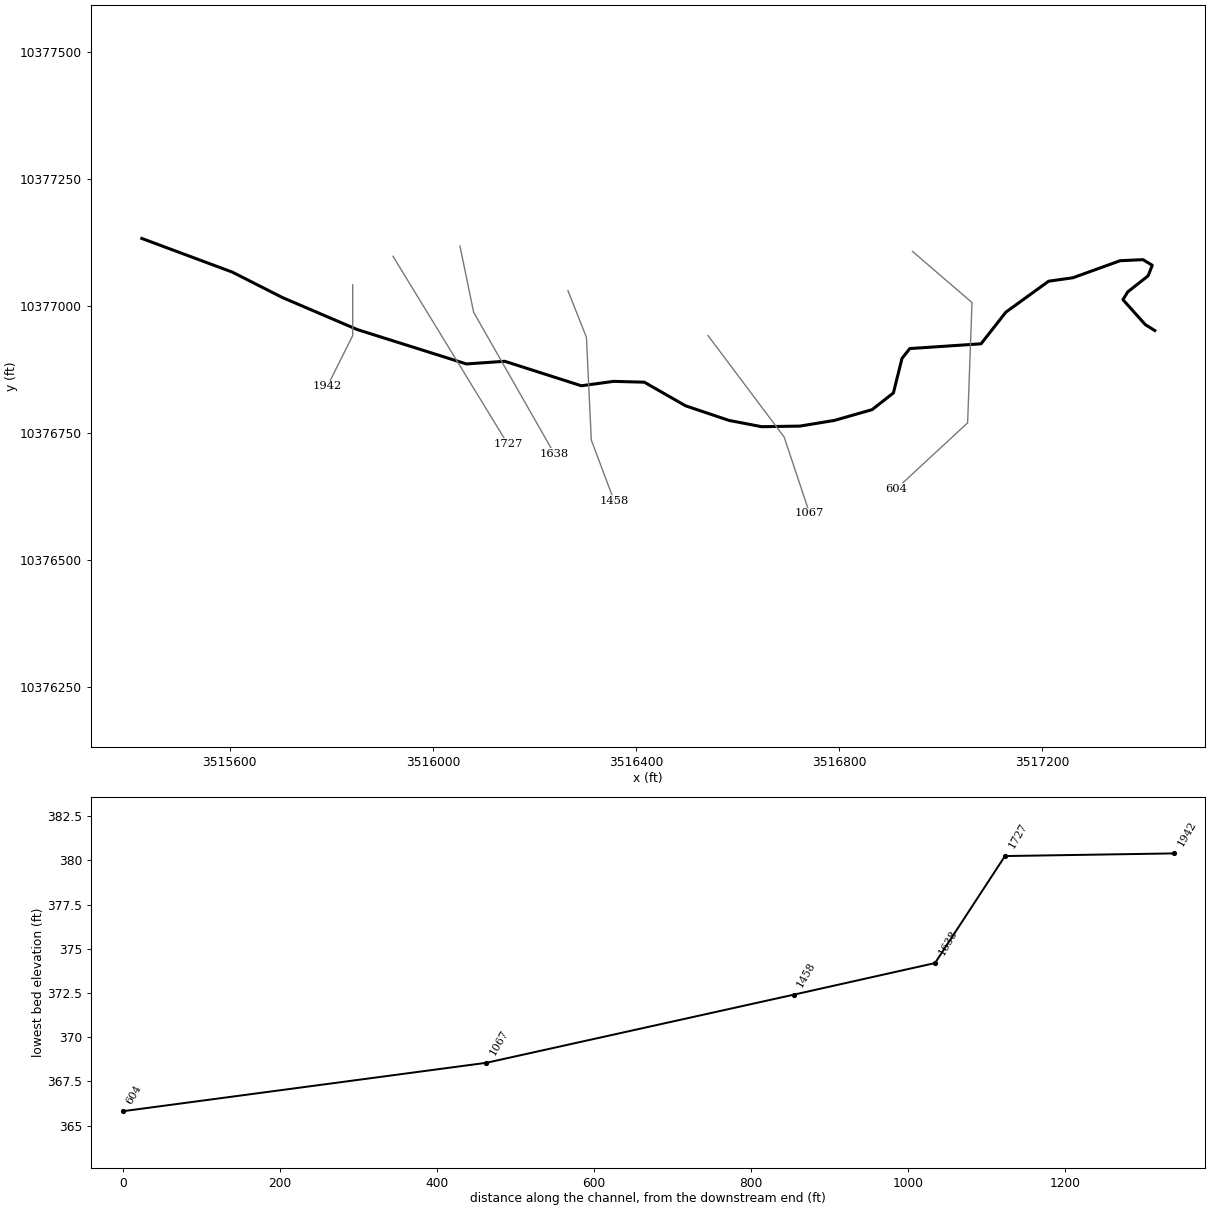
--- SOUTH MINERAL CR TRIB 6.prj (project) ---

Proj Title=SOUTH MINERAL CR TRIB 6 Base Level Engineering
Current Plan=p01
Default Exp/Contr=0.3,0.1
English Units
Geom File=g01
Flow File=f01
Plan File=p01
BEGIN DESCRIPTION:
SOUTH MINERAL CR TRIB 6
END DESCRIPTION:

--- SOUTH MINERAL CR TRIB 6.p01 (plan) ---

Plan Title=Multiple Run
Short Identifier=Multiple
Geom File=g01
Flow File=f01
Subcritical Flow
K Sum by GR= 0
Std Step Tol= 0.01
Critical Tol= 0.01
Num of Std Step Trials= 20
Max Error Tol= 0.3
Flow Tol Ratio= 0.001
Split Flow NTrial= 30
Split Flow Tol= 0.02
Split Flow Ratio= 0.02
Log Output Level= 0
Friction Slope Method= 1
Unsteady Friction Slope Method= 2
Unsteady Bridges Friction Slope Method= 1
Parabolic Critical Depth
Global Vel Dist=  1 , 1 , 1
Global Log Level= 0
CheckData=True
Encroach Param= -1, 0, 0, 0
BEGIN DESCRIPTION:
Multiple Run
END DESCRIPTION:

--- SOUTH MINERAL CR TRIB 6.f01 (steady flow) ---

Flow Title=Multiple
Number of Profiles=7
Profile Names=10-year,25-year,50-year,1pct_min,100-year,1pct_plu,500-year
River Rch & RM= SOUTH MINERAL CR,Reach-1,1942
     816    1129    1390    1251    1692    2289    2500
Boundary for River Rch & Prof#=SOUTH MINERAL CR,Reach-1,1
Up Type=0
Dn Type=3
Dn Slope=0.005
Boundary for River Rch & Prof#=SOUTH MINERAL CR,Reach-1,2
Up Type=0
Dn Type=3
Dn Slope=0.005
Boundary for River Rch & Prof#=SOUTH MINERAL CR,Reach-1,3
Up Type=0
Dn Type=3
Dn Slope=0.005
Boundary for River Rch & Prof#=SOUTH MINERAL CR,Reach-1,4
Up Type=0
Dn Type=3
Dn Slope=0.005
Boundary for River Rch & Prof#=SOUTH MINERAL CR,Reach-1,5
Up Type=0
Dn Type=3
Dn Slope=0.005
Boundary for River Rch & Prof#=SOUTH MINERAL CR,Reach-1,6
Up Type=0
Dn Type=3
Dn Slope=0.005
Boundary for River Rch & Prof#=SOUTH MINERAL CR,Reach-1,7
Up Type=0
Dn Type=3
Dn Slope=0.005

--- SOUTH MINERAL CR TRIB 6.g01 (geometry) ---

Geom Title=Existing Conditions

River Reach=SOUTH MINERAL CR,Reach-1
Reach XY= 30
      3515426.68     10377133.02      3515604.81     10377066.78
      3515704.03     10377016.46      3515851.17     10376953.53
      3516066.01     10376885.82      3516141.66     10376891.07
      3516292.54     10376842.80      3516355.94     10376851.49
      3516416.58     10376849.87      3516497.82     10376803.37
      3516583.33     10376774.59      3516647.78     10376762.18
      3516723.23     10376763.40      3516790.91     10376774.54
      3516865.32     10376795.80      3516907.24     10376828.68
      3516924.20     10376896.78      3516939.58     10376916.11
      3517079.93     10376925.51      3517128.84     10376987.90
      3517213.08     10377048.81      3517260.85     10377055.58
      3517353.80     10377089.13      3517398.83     10377091.26
      3517417.20     10377080.16      3517408.87     10377059.23
      3517368.99     10377027.91      3517359.40     10377012.46
      3517403.45     10376963.29      3517422.11     10376951.64

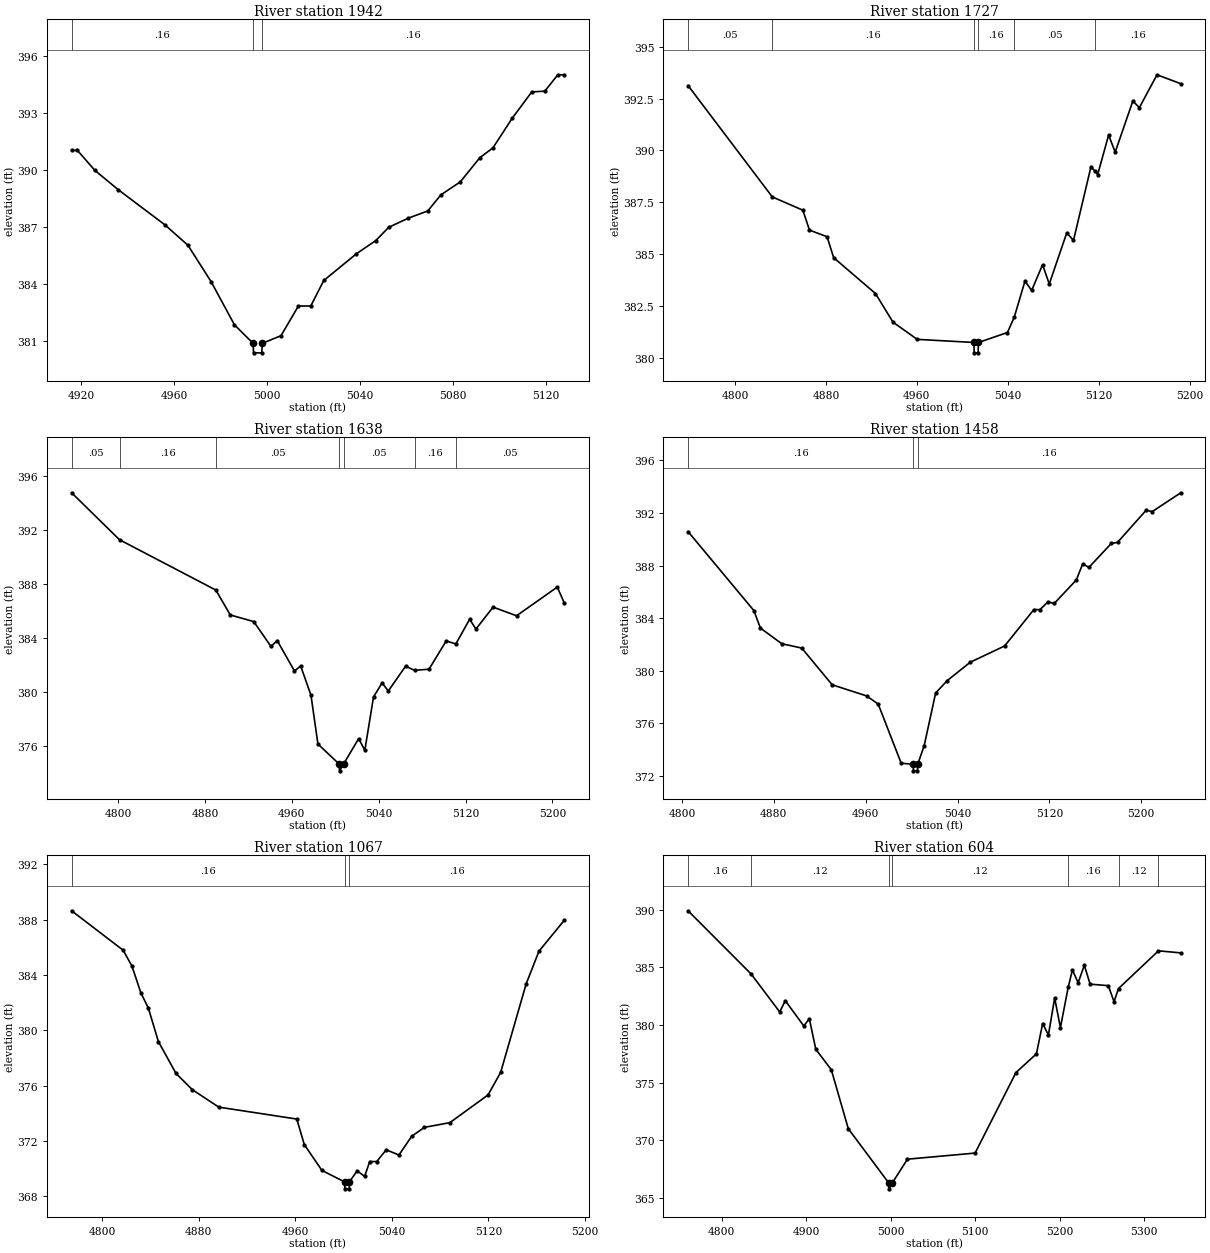
Type RM Length L Ch R = 1,1942,215,215,215
BEGIN DESCRIPTION:
SOUTH MINERAL CR TRIB 6 2 0
END DESCRIPTION:
XS GIS Cut Line= 3
      3515842.11     10377041.64      3515842.11     10376941.64
      3515792.10     10376841.64
#Sta/Elev= 30
  4916.0  391.02  4918.5  391.02  4926.0  389.97  4936.0  388.96  4956.0  387.12
  4966.0  386.04  4976.0  384.12  4986.0  381.86  4994.0  380.89  4994.2  380.39
  4997.7  380.39  4998.0  380.89  5006.0  381.29  5013.5  382.85  5018.8  382.85
  5024.4  384.19  5038.4  385.59  5046.7  386.28  5052.3  386.98  5060.7  387.46
  5069.1  387.84  5074.7  388.68  5083.1  389.37  5091.5  390.64  5097.1  391.15
  5105.4  392.71  5113.8  394.09  5119.4  394.13  5125.0  394.99  5127.8  394.99
#Mann=3,-1,0
  4916.0    0.16       0  4994.0    0.07       0  4998.0    0.16       0
Bank Sta=4994,4998
Exp/Cntr=0.3,0.1

Type RM Length L Ch R = 1,1727,89,89,89
BEGIN DESCRIPTION:
Mapping XS 4eff08fa
END DESCRIPTION:
XS GIS Cut Line= 2
      3515921.47     10377097.90      3516147.55     10376728.02
#Sta/Elev= 30
  4758.7  393.13  4832.8  387.76  4859.7  387.12  4865.5  386.16  4881.0  385.84
  4886.8  384.83  4923.6  383.10  4939.0  381.72  4960.3  380.89  5010.2  380.74
  5010.4  380.24  5013.9  380.24  5014.2  380.74  5039.7  381.22  5045.7  381.96
  5055.1  383.70  5061.0  383.25  5070.6  384.49  5076.5  383.56  5091.9  386.03
  5097.8  385.66  5113.2  389.22  5116.5  389.01  5119.1  388.84  5128.7  390.74
  5134.5  389.92  5150.0  392.38  5155.8  392.07  5171.3  393.65  5192.2  393.22
#Mann=6,-1,0
  4758.7    0.05       0  4832.8    0.16       0  5010.2    0.07       0
  5014.2    0.16       0  5045.7    0.05       0  5116.5    0.16       0
Bank Sta=5010.2,5014.2
Exp/Cntr=0.3,0.1

Type RM Length L Ch R = 1,1638,180,180,180
BEGIN DESCRIPTION:
Mapping XS 1771f49b
END DESCRIPTION:
XS GIS Cut Line= 3
      3516053.43     10377117.85      3516080.34     10376987.64
      3516239.18     10376709.00
#Sta/Elev= 30
  4757.2  394.74  4801.3  391.27  4890.0  387.55  4903.3  385.71  4924.9  385.22
  4940.8  383.38  4946.5  383.82  4962.4  381.57  4968.1  381.94  4977.6  379.78
  4984.0  376.17  5003.6  374.69  5003.9  374.19  5007.6  374.69  5021.5  376.57
  5027.2  375.71  5035.2  379.65  5043.1  380.69  5048.8  380.09  5064.7  381.92
  5073.0  381.62  5086.3  381.70  5102.1  383.79  5111.0  383.57  5123.7  385.39
  5129.5  384.67  5145.3  386.29  5166.9  385.65  5204.4  387.77  5210.9  386.59
#Mann=7,-1,0
  4757.2    0.05       0  4801.3    0.16       0  4890.0    0.05       0
  5003.6    0.04       0  5007.6    0.05       0  5073.0    0.16       0
  5111.0    0.05       0
Bank Sta=5003.6,5007.6
Exp/Cntr=0.3,0.1

Type RM Length L Ch R = 1,1458,391,391,391
BEGIN DESCRIPTION:
SOUTH MINERAL CR TRIB 6 3 0
END DESCRIPTION:
XS GIS Cut Line= 4
      3516266.10     10377030.18      3516302.56     10376938.16
      3516312.11     10376735.90      3516357.02     10376616.42
#Sta/Elev= 30
  4805.3  390.58  4862.6  384.58  4868.3  383.25  4886.9  382.06  4904.3  381.73
  4930.8  378.94  4960.9  378.09  4970.9  377.47  4990.9  372.98  5001.3  372.90
  5001.6  372.40  5005.1  372.40  5005.3  372.90  5010.9  374.30  5020.9  378.31
  5030.9  379.25  5051.0  380.65  5081.0  381.89  5106.4  384.65  5111.7  384.65
  5118.8  385.24  5124.2  385.12  5143.4  386.90  5149.0  388.13  5154.4  387.86
  5173.9  389.68  5179.3  389.76  5204.2  392.20  5209.5  392.10  5234.4  393.53
#Mann=3,-1,0
  4805.3    0.16       0  5001.3    0.07       0  5005.3    0.16       0
Bank Sta=5001.3,5005.3
Exp/Cntr=0.3,0.1

Type RM Length L Ch R = 1,1067,463,463,463
BEGIN DESCRIPTION:
SOUTH MINERAL CR TRIB 6 4 0
END DESCRIPTION:
XS GIS Cut Line= 3
      3516542.09     10376941.66      3516692.11     10376741.64
      3516742.09     10376591.67
#Sta/Elev= 30
  4774.8  388.63  4817.5  385.78  4824.8  384.63  4832.1  382.72  4838.4  381.59
  4846.7  379.18  4861.3  376.88  4874.8  375.71  4896.7  374.45  4961.3  373.59
  4967.5  371.75  4982.1  369.88  5000.9  369.05  5001.2  368.55  5004.7  368.55
  5004.9  369.05  5011.3  369.85  5017.5  369.45  5021.7  370.52  5027.5  370.52
  5035.4  371.37  5045.9  370.99  5056.4  372.34  5067.0  372.99  5088.1  373.33
  5119.7  375.33  5130.2  376.97  5151.3  383.36  5161.9  385.71  5182.9  387.95
#Mann=3,-1,0
  4774.8    0.16       0  5000.9    0.07       0  5004.9    0.16       0
Bank Sta=5000.9,5004.9
Exp/Cntr=0.3,0.1

Type RM Length L Ch R = 1,604,0,0,0
BEGIN DESCRIPTION:
SOUTH MINERAL CR TRIB 6 1 0
END DESCRIPTION:
XS GIS Cut Line= 4
      3516944.90     10377107.45      3517062.11     10377006.73
      3517053.43     10376769.75      3516912.82     10376639.56
#Sta/Elev= 30
  4760.1  389.91  4834.9  384.42  4868.6  381.14  4875.2  382.12  4897.1  379.93
  4903.7  380.55  4911.3  377.91  4929.7  376.13  4949.8  371.02  4997.8  366.31
  4998.0  365.81  5001.8  366.31  5019.8  368.38  5099.9  368.91  5148.3  375.89
  5172.5  377.51  5179.9  380.14  5186.7  379.14  5194.1  382.35  5200.9  379.78
  5210.1  383.27  5215.1  384.78  5221.9  383.67  5229.2  385.19  5236.1  383.55
  5257.6  383.42  5264.4  382.03  5269.7  383.17  5317.0  386.44  5343.4  386.26
#Mann=7,-1,0
  4760.1    0.16       0  4834.9    0.12       0  4997.8    0.07       0
  5001.8    0.12       0  5210.1    0.16       0  5269.7    0.12       0
  5317.0    0.16       0
Bank Sta=4997.8,5001.8
Exp/Cntr=0.3,0.1

Chan Stop Cuts=-1