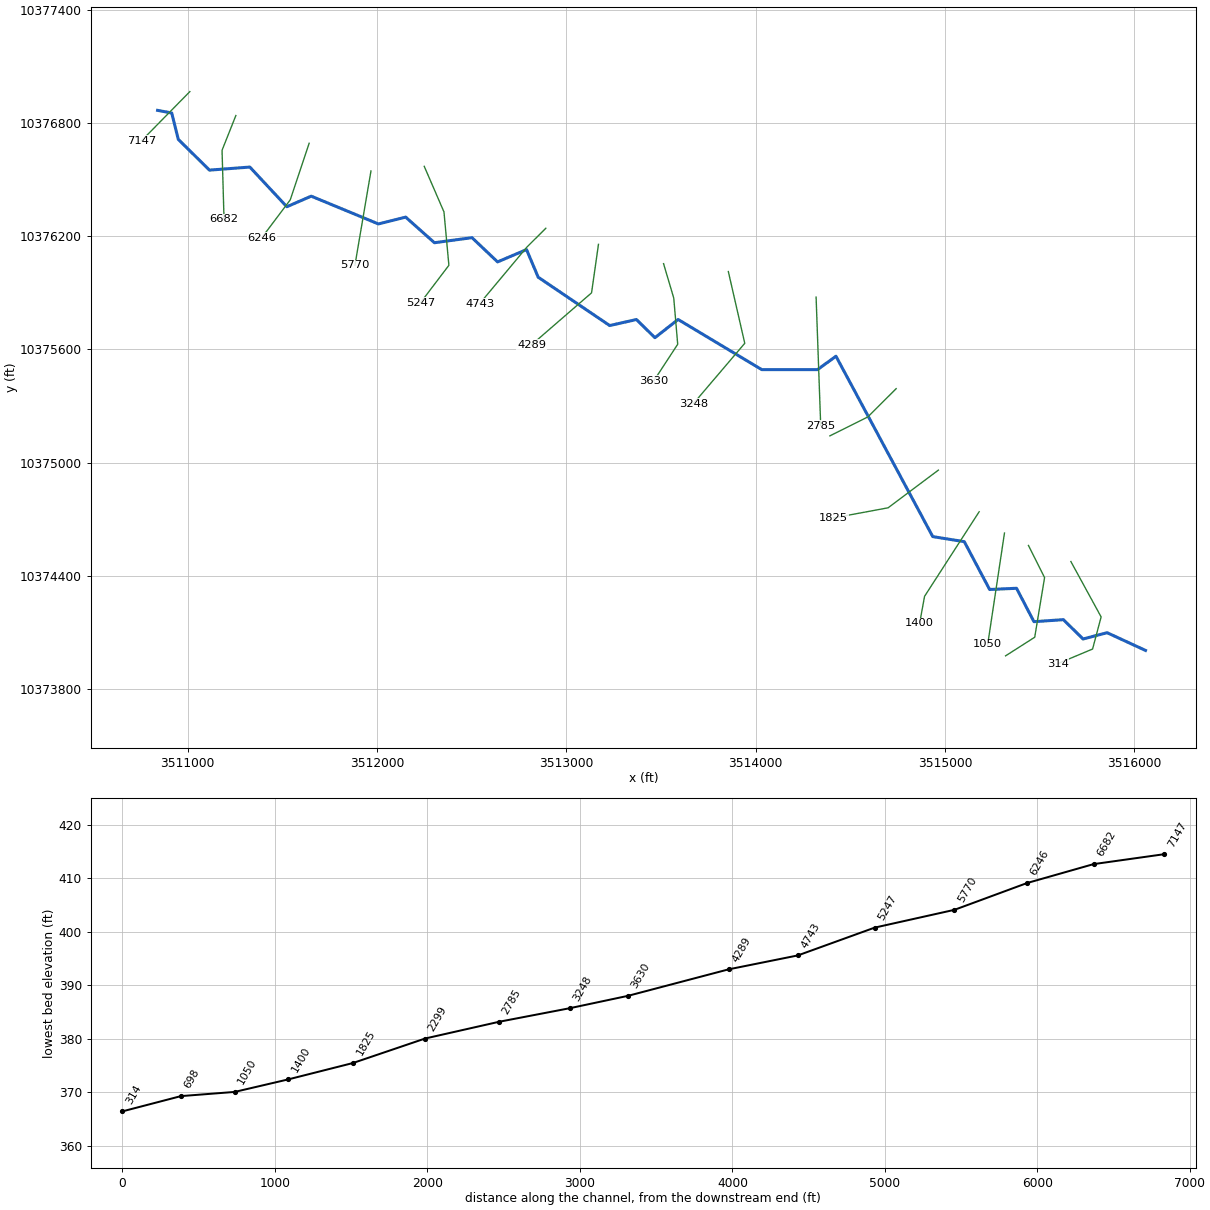
--- SOUTH MINERAL CR TRIB 7.prj (project) ---

Proj Title=SOUTH MINERAL CR TRIB 7 Base Level Engineering
Current Plan=p01
Default Exp/Contr=0.3,0.1
English Units
Geom File=g01
Flow File=f01
Plan File=p01
BEGIN DESCRIPTION:
SOUTH MINERAL CR TRIB 7
END DESCRIPTION:

--- SOUTH MINERAL CR TRIB 7.p01 (plan) ---

Plan Title=Multiple Run
Short Identifier=Multiple
Geom File=g01
Flow File=f01
Subcritical Flow
K Sum by GR= 0
Std Step Tol= 0.01
Critical Tol= 0.01
Num of Std Step Trials= 20
Max Error Tol= 0.3
Flow Tol Ratio= 0.001
Split Flow NTrial= 30
Split Flow Tol= 0.02
Split Flow Ratio= 0.02
Log Output Level= 0
Friction Slope Method= 1
Unsteady Friction Slope Method= 2
Unsteady Bridges Friction Slope Method= 1
Parabolic Critical Depth
Global Vel Dist=  1 , 1 , 1
Global Log Level= 0
CheckData=True
Encroach Param= -1, 0, 0, 0
BEGIN DESCRIPTION:
Multiple Run
END DESCRIPTION:

--- SOUTH MINERAL CR TRIB 7.f01 (steady flow) ---

Flow Title=Multiple
Number of Profiles=7
Profile Names=10-year,25-year,50-year,1pct_min,100-year,1pct_plu,500-year
River Rch & RM= SOUTH MINERAL CR,Reach-1,7147
    1029    1440    1785    1617    2186    2957    3271
Boundary for River Rch & Prof#=SOUTH MINERAL CR,Reach-1,1
Up Type=0
Dn Type=3
Dn Slope=0.005
Boundary for River Rch & Prof#=SOUTH MINERAL CR,Reach-1,2
Up Type=0
Dn Type=3
Dn Slope=0.005
Boundary for River Rch & Prof#=SOUTH MINERAL CR,Reach-1,3
Up Type=0
Dn Type=3
Dn Slope=0.005
Boundary for River Rch & Prof#=SOUTH MINERAL CR,Reach-1,4
Up Type=0
Dn Type=3
Dn Slope=0.005
Boundary for River Rch & Prof#=SOUTH MINERAL CR,Reach-1,5
Up Type=0
Dn Type=3
Dn Slope=0.005
Boundary for River Rch & Prof#=SOUTH MINERAL CR,Reach-1,6
Up Type=0
Dn Type=3
Dn Slope=0.005
Boundary for River Rch & Prof#=SOUTH MINERAL CR,Reach-1,7
Up Type=0
Dn Type=3
Dn Slope=0.005

--- SOUTH MINERAL CR TRIB 7.g01 (geometry) ---

Geom Title=Existing Conditions

River Reach=SOUTH MINERAL CR,Reach-1
Reach XY= 30
      3510841.59     10376866.10      3510916.26     10376852.30
      3510950.95     10376712.39      3511115.78     10376549.49
      3511328.87     10376565.65      3511524.21     10376355.43
      3511653.08     10376411.51      3512007.79     10376264.35
      3512151.88     10376300.54      3512303.64     10376164.86
      3512502.11     10376191.64      3512637.19     10376063.23
      3512790.10     10376128.34      3512851.81     10375982.02
      3513229.31     10375726.02      3513370.46     10375757.95
      3513468.21     10375661.64      3513590.54     10375758.19
      3514032.33     10375492.56      3514326.47     10375492.40
      3514424.28     10375563.44      3514935.38     10374607.84
      3515101.91     10374581.10      3515235.65     10374327.78
      3515377.78     10374334.13      3515469.69     10374157.22
      3515625.14     10374167.84      3515729.07     10374065.50
      3515856.14     10374098.82      3516058.82     10374004.96

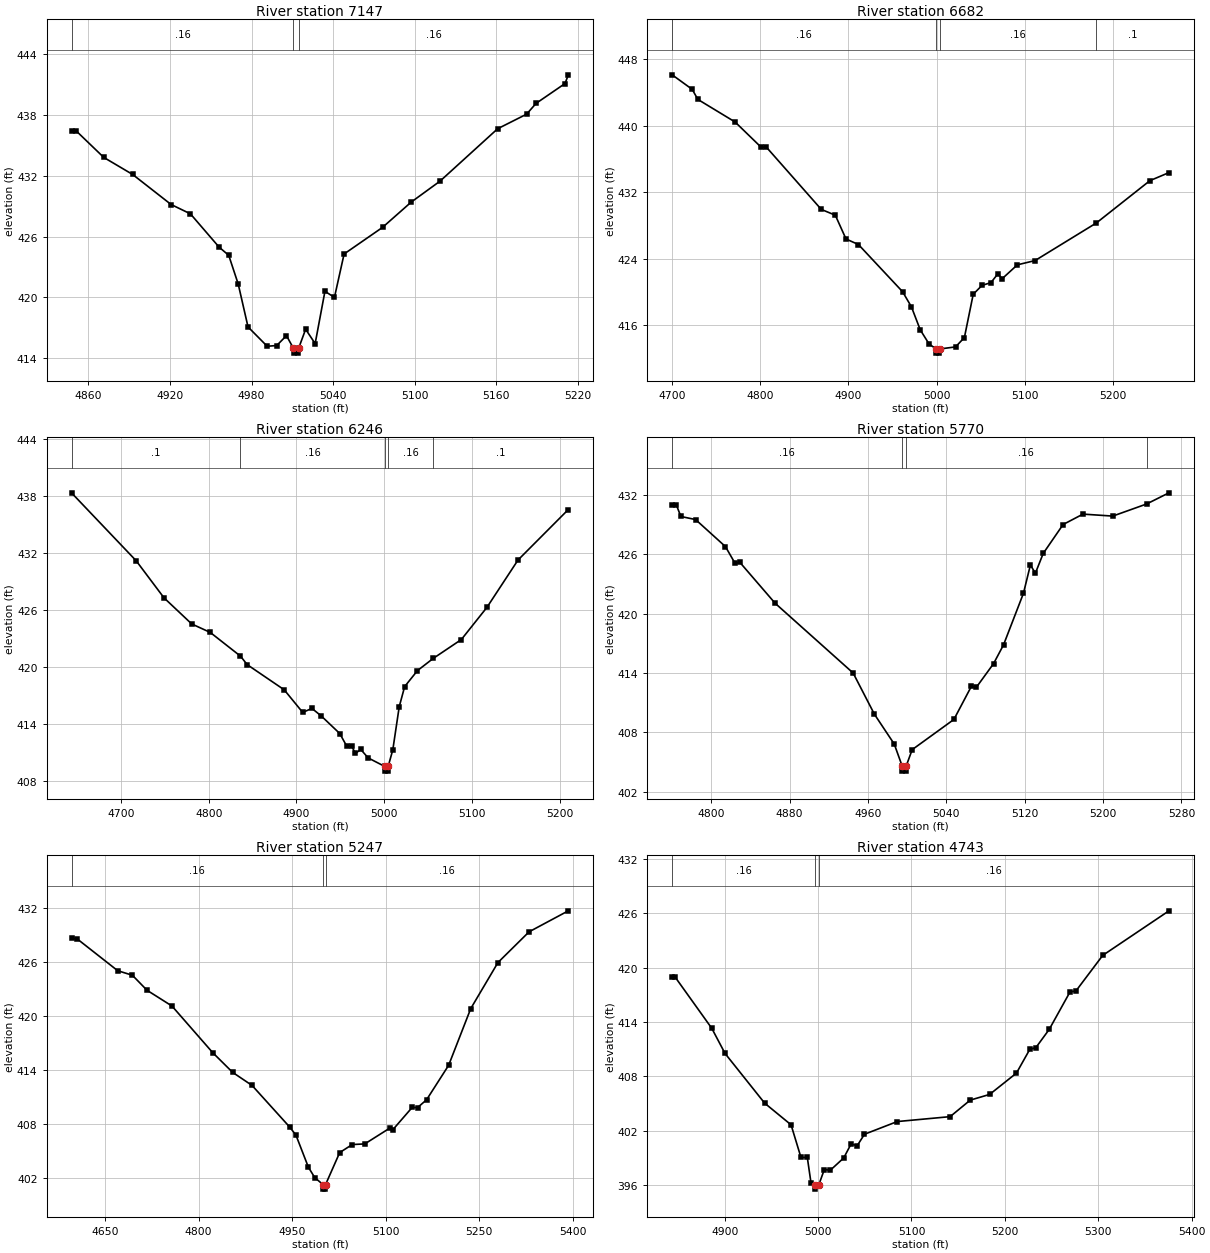
Type RM Length L Ch R = 1,7147,465,465,465
BEGIN DESCRIPTION:
SOUTH MINERAL CR TRIB 7 3 0
END DESCRIPTION:
XS GIS Cut Line= 2
      3511011.99     10376965.36      3510756.08     10376704.26
#Sta/Elev= 30
  4847.5  436.44  4851.0  436.44  4871.2  433.83  4892.5  432.14  4920.8  429.17
  4935.0  428.25  4956.1  424.96  4963.2  424.15  4970.2  421.30  4977.4  417.07
  4991.5  415.16  4998.5  415.23  5005.7  416.21  5010.7  414.98  5010.9  414.48
  5014.4  414.48  5014.7  414.98  5019.8  416.84  5026.8  415.42  5034.0  420.59
  5041.0  419.99  5048.1  424.28  5076.4  426.91  5097.5  429.41  5118.7  431.48
  5161.1  436.66  5182.4  438.10  5189.4  439.17  5210.7  441.13  5213.1  441.99
#Mann=3,-1,0
  4847.5    0.16       0  5010.7    0.07       0  5014.7    0.16       0
Bank Sta=5010.7,5014.7
Exp/Cntr=0.3,0.1

Type RM Length L Ch R = 1,6682,436,436,436
BEGIN DESCRIPTION:
SOUTH MINERAL CR TRIB 7 2 0
END DESCRIPTION:
XS GIS Cut Line= 3
      3511255.08     10376838.68      3511182.15     10376654.61
      3511192.56     10376290.05
#Sta/Elev= 30
  4700.4  446.12  4723.1  444.37  4729.5  443.16  4771.7  440.44  4801.4  437.38
  4806.8  437.45  4869.3  429.92  4885.2  429.22  4897.3  426.36  4911.4  425.69
  4961.4  420.01  4971.4  418.19  4981.4  415.42  4991.4  413.72  4999.4  413.12
  4999.6  412.62  5003.1  412.62  5003.4  413.12  5021.4  413.37  5031.4  414.50
  5041.4  419.71  5051.4  420.78  5061.4  421.10  5069.2  422.15  5074.3  421.59
  5091.4  423.25  5111.4  423.76  5180.9  428.29  5241.5  433.38  5263.1  434.35
#Mann=4,-1,0
  4700.4    0.16       0  4999.4    0.07       0  5003.4    0.16       0
  5180.9     0.1       0
Bank Sta=4999.4,5003.4
Exp/Cntr=0.3,0.1

Type RM Length L Ch R = 1,6246,476,476,476
BEGIN DESCRIPTION:
SOUTH MINERAL CR TRIB 7 15 0
END DESCRIPTION:
XS GIS Cut Line= 3
      3511642.09     10376691.61      3511542.11     10376391.64
      3511392.10     10376191.63
#Sta/Elev= 30
  4643.6  438.38  4717.3  431.23  4749.0  427.33  4780.6  424.58  4801.7  423.69
  4836.2  421.19  4843.8  420.30  4886.0  417.65  4907.1  415.27  4917.6  415.69
  4928.2  414.90  4949.3  413.05  4957.2  411.73  4962.9  411.73  4967.1  410.95
  4973.3  411.37  4981.7  410.48  5000.5  409.59  5000.7  409.09  5004.2  409.09
  5004.5  409.59  5009.8  411.34  5017.1  415.87  5023.3  417.99  5037.9  419.67
  5055.8  420.95  5087.9  422.94  5117.1  426.33  5152.5  431.31  5209.8  436.62
#Mann=5,-1,0
  4643.6     0.1       0  4836.2    0.16       0  5000.5    0.07       0
  5004.5    0.16       0  5055.8     0.1       0
Bank Sta=5000.5,5004.5
Exp/Cntr=0.3,0.1

Type RM Length L Ch R = 1,5770,523,523,523
BEGIN DESCRIPTION:
SOUTH MINERAL CR TRIB 7 14 0
END DESCRIPTION:
XS GIS Cut Line= 2
      3511968.61     10376545.25      3511883.80     10376045.09
#Sta/Elev= 30
  4760.0  430.94  4764.4  430.94  4768.9  429.81  4783.9  429.50  4814.4  426.77
  4824.1  425.10  4829.2  425.17  4865.1  421.05  4944.8  414.00  4966.5  409.84
  4986.8  406.82  4994.9  404.59  4995.2  404.09  4998.7  404.09  4998.9  404.59
  5005.1  406.26  5047.7  409.31  5065.5  412.65  5070.5  412.54  5088.2  414.95
  5098.4  416.85  5118.7  422.05  5125.8  424.91  5130.9  424.08  5138.9  426.08
  5159.2  429.00  5179.5  430.05  5209.9  429.85  5244.4  431.07  5267.3  432.20
#Mann=4,-1,0
  4760.0    0.16       0  4994.9    0.07       0  4998.9    0.16       0
  5244.4    0.05       0
Bank Sta=4994.9,4998.9
Exp/Cntr=0.3,0.1

Type RM Length L Ch R = 1,5247,504,504,504
BEGIN DESCRIPTION:
SOUTH MINERAL CR TRIB 7 13 0
END DESCRIPTION:
XS GIS Cut Line= 4
      3512249.84     10376569.56      3512354.02     10376328.22
      3512380.06     10376045.24      3512229.44     10375846.14
#Sta/Elev= 30
  4596.2  428.61  4604.8  428.58  4670.3  425.02  4693.8  424.52  4717.3  422.85
  4757.3  421.10  4822.7  415.92  4854.5  413.74  4885.8  412.28  4946.0  407.67
  4956.1  406.77  4976.1  403.20  4986.2  402.06  4999.6  401.27  4999.8  400.77
  5003.3  400.77  5003.6  401.27  5026.3  404.83  5046.4  405.72  5066.5  405.79
  5106.3  407.53  5111.3  407.35  5142.5  409.84  5151.1  409.82  5165.6  410.69
  5201.0  414.52  5236.4  420.81  5280.1  425.93  5330.0  429.34  5392.9  431.67
#Mann=3,-1,0
  4596.2    0.16       0  4999.6    0.07       0  5003.6    0.16       0
Bank Sta=4999.6,5003.6
Exp/Cntr=0.3,0.1

Type RM Length L Ch R = 1,4743,454,454,454
BEGIN DESCRIPTION:
SOUTH MINERAL CR TRIB 7 12 0
END DESCRIPTION:
XS GIS Cut Line= 3
      3512892.11     10376241.65      3512792.11     10376141.64
      3512542.13     10375841.67
#Sta/Elev= 30
  4843.8  418.91  4847.3  418.91  4886.2  413.31  4900.4  410.54  4942.8  405.06
  4971.1  402.67  4981.7  399.07  4988.5  399.07  4992.4  396.30  4996.9  396.08
  4997.1  395.58  5000.9  396.08  5006.7  397.74  5013.2  397.67  5027.5  399.02
  5035.3  400.55  5041.9  400.37  5049.7  401.63  5084.8  403.03  5141.4  403.57
  5162.9  405.39  5183.7  406.02  5212.4  408.37  5226.7  410.99  5233.2  411.18
  5247.5  413.19  5269.7  417.31  5276.2  417.44  5304.8  421.35  5375.7  426.26
#Mann=3,-1,0
  4843.8    0.16       0  4996.9    0.07       0  5000.9    0.16       0
Bank Sta=4996.9,5000.9
Exp/Cntr=0.3,0.1

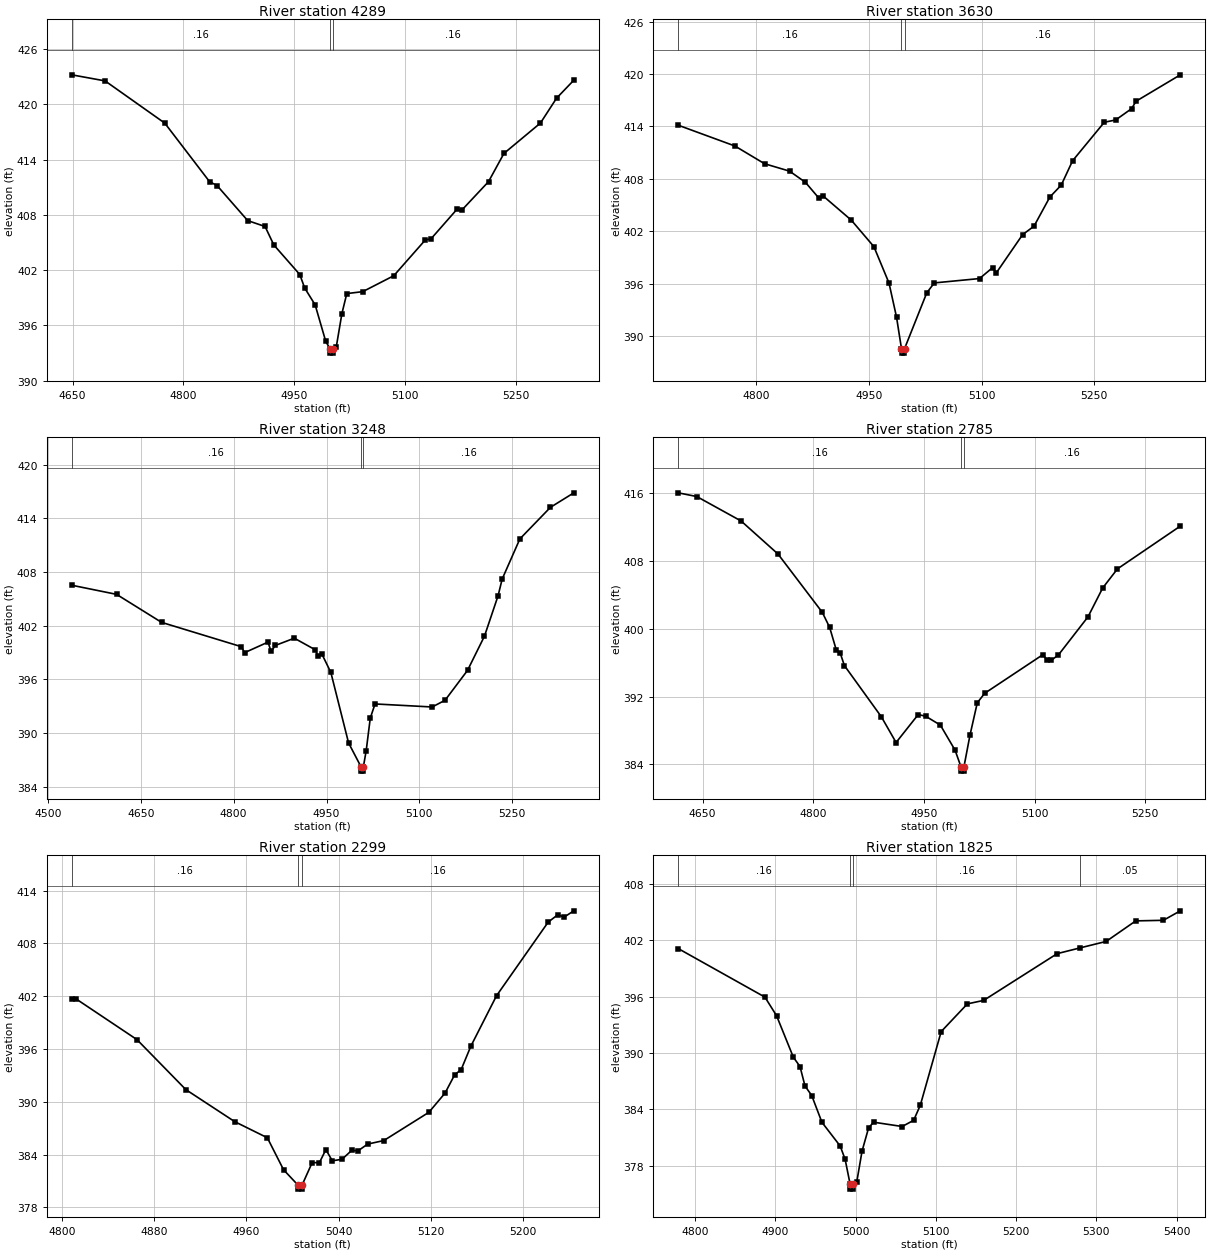
Type RM Length L Ch R = 1,4289,659,659,659
BEGIN DESCRIPTION:
SOUTH MINERAL CR TRIB 7 29 0
END DESCRIPTION:
XS GIS Cut Line= 3
      3513169.99     10376156.30      3513133.53     10375899.40
      3512816.47     10375623.92
#Sta/Elev= 30
  4648.8  423.22  4693.9  422.56  4774.7  417.97  4835.3  411.61  4845.4  411.19
  4886.9  407.38  4910.4  406.74  4922.3  404.73  4957.4  401.52  4964.0  400.06
  4978.2  398.22  4992.5  394.26  4998.1  393.48  4998.4  392.98  5001.9  392.98
  5002.1  393.48  5006.7  393.62  5014.4  397.28  5021.0  399.45  5042.6  399.66
  5084.6  401.39  5127.3  405.28  5135.0  405.40  5170.1  408.61  5176.7  408.52
  5212.8  411.61  5233.7  414.68  5283.1  417.98  5304.9  420.68  5328.3  422.64
#Mann=3,-1,0
  4648.8    0.16       0  4998.1    0.07       0  5002.1    0.16       0
Bank Sta=4998.1,5002.1
Exp/Cntr=0.3,0.1

Type RM Length L Ch R = 1,3630,382,382,382
BEGIN DESCRIPTION:
SOUTH MINERAL CR TRIB 7 19 0
END DESCRIPTION:
XS GIS Cut Line= 4
      3513513.74     10376053.93      3513567.56     10375871.63
      3513588.40     10375626.83      3513461.64     10375432.35
#Sta/Elev= 30
  4696.5  414.14  4771.9  411.76  4811.3  409.73  4844.6  408.88  4865.7  407.60
  4883.2  405.83  4889.1  406.05  4926.7  403.27  4956.8  400.23  4976.9  396.06
  4986.9  392.16  4993.5  388.54  4993.8  388.04  4997.3  388.04  4997.5  388.54
  5027.1  394.94  5037.1  396.08  5097.3  396.58  5114.7  397.83  5119.7  397.24
  5154.6  401.61  5169.8  402.58  5190.9  405.92  5206.0  407.28  5221.1  410.07
  5263.3  414.48  5278.4  414.74  5299.5  416.03  5305.6  416.89  5364.4  419.91
#Mann=3,-1,0
  4696.5    0.16       0  4993.5    0.07       0  4997.5    0.16       0
Bank Sta=4993.5,4997.5
Exp/Cntr=0.3,0.1

Type RM Length L Ch R = 1,3248,463,463,463
BEGIN DESCRIPTION:
SOUTH MINERAL CR TRIB 7 9 0
END DESCRIPTION:
XS GIS Cut Line= 3
      3513855.75     10376012.26      3513942.56     10375632.04
      3513670.02     10375310.90
#Sta/Elev= 30
  4538.4  406.51  4610.8  405.49  4683.5  402.36  4812.4  399.64  4817.6  398.97
  4855.4  400.15  4860.5  399.11  4867.3  399.78  4898.0  400.59  4931.9  399.29
  4936.2  398.58  4942.7  398.79  4957.0  396.76  4985.6  388.89  5005.6  386.23
  5005.8  385.73  5009.3  385.73  5009.6  386.23  5014.1  388.02  5020.7  391.66
  5028.4  393.24  5120.7  392.90  5141.5  393.65  5177.8  396.99  5205.2  400.82
  5227.2  405.34  5233.8  407.20  5262.4  411.69  5311.8  415.22  5349.6  416.84
#Mann=3,-1,0
  4538.4    0.16       0  5005.6    0.07       0  5009.6    0.16       0
Bank Sta=5005.6,5009.6
Exp/Cntr=0.3,0.1

Type RM Length L Ch R = 1,2785,486,486,486
BEGIN DESCRIPTION:
SOUTH MINERAL CR TRIB 7 8 0
END DESCRIPTION:
XS GIS Cut Line= 2
      3514319.30     10375876.84      3514343.60     10375196.48
#Sta/Elev= 30
  4616.9  416.07  4642.1  415.63  4702.2  412.74  4752.2  408.84  4812.2  401.96
  4822.2  400.18  4831.4  397.45  4836.4  397.18  4842.2  395.67  4892.3  389.62
  4912.3  386.58  4942.3  389.88  4952.3  389.69  4972.3  388.64  4992.3  385.67
  5000.3  383.70  5000.6  383.20  5004.1  383.20  5004.3  383.70  5012.4  387.41
  5022.4  391.27  5032.4  392.39  5111.6  396.97  5116.6  396.34  5122.4  396.27
  5132.4  396.92  5172.5  401.42  5192.5  404.84  5212.5  407.09  5297.7  412.14
#Mann=3,-1,0
  4616.9    0.16       0  5000.3    0.07       0  5004.3    0.16       0
Bank Sta=5000.3,5004.3
Exp/Cntr=0.3,0.1

Type RM Length L Ch R = 1,2299,474,474,474
BEGIN DESCRIPTION:
SOUTH MINERAL CR TRIB 7 7 0
END DESCRIPTION:
XS GIS Cut Line= 3
      3514742.10     10375391.63      3514592.11     10375241.64
      3514392.13     10375141.65
#Sta/Elev= 30
  4808.5  401.71  4812.0  401.71  4865.1  397.06  4907.5  391.38  4949.9  387.74
  4978.2  385.91  4992.3  382.27  5004.5  380.57  5004.7  380.07  5008.2  380.07
  5008.5  380.57  5017.1  383.08  5023.4  383.08  5029.0  384.56  5034.6  383.29
  5043.0  383.46  5051.4  384.47  5057.0  384.43  5065.3  385.19  5079.3  385.59
  5118.4  388.80  5132.4  390.98  5140.8  393.07  5146.4  393.65  5154.8  396.31
  5177.1  402.05  5221.9  410.41  5230.2  411.25  5235.8  410.99  5244.2  411.70
#Mann=3,-1,0
  4808.5    0.16       0  5004.5    0.07       0  5008.5    0.16       0
Bank Sta=5004.5,5008.5
Exp/Cntr=0.3,0.1

Type RM Length L Ch R = 1,1825,425,425,425
BEGIN DESCRIPTION:
SOUTH MINERAL CR TRIB 7 6 0
END DESCRIPTION:
XS GIS Cut Line= 3
      3514965.16     10374960.19      3514699.51     10374760.51
      3514411.32     10374706.70
#Sta/Elev= 30
  4779.0  401.11  4887.0  395.94  4901.5  393.96  4922.4  389.54  4930.7  388.55
  4936.9  386.48  4945.3  385.46  4958.0  382.61  4980.7  380.09  4986.9  378.67
  4993.2  375.99  4993.5  375.49  4997.0  375.49  4997.2  375.99  5001.5  376.30
  5008.0  379.54  5016.1  382.00  5022.3  382.62  5058.0  382.16  5072.3  382.82
  5080.6  384.43  5106.6  392.27  5139.2  395.22  5159.5  395.59  5251.1  400.57
  5279.0  401.17  5312.1  401.87  5349.0  404.06  5383.4  404.12  5404.5  405.13
#Mann=4,-1,0
  4779.0    0.16       0  4993.2    0.07       0  4997.2    0.16       0
  5279.0    0.05       0
Bank Sta=4993.2,4997.2
Exp/Cntr=0.3,0.1

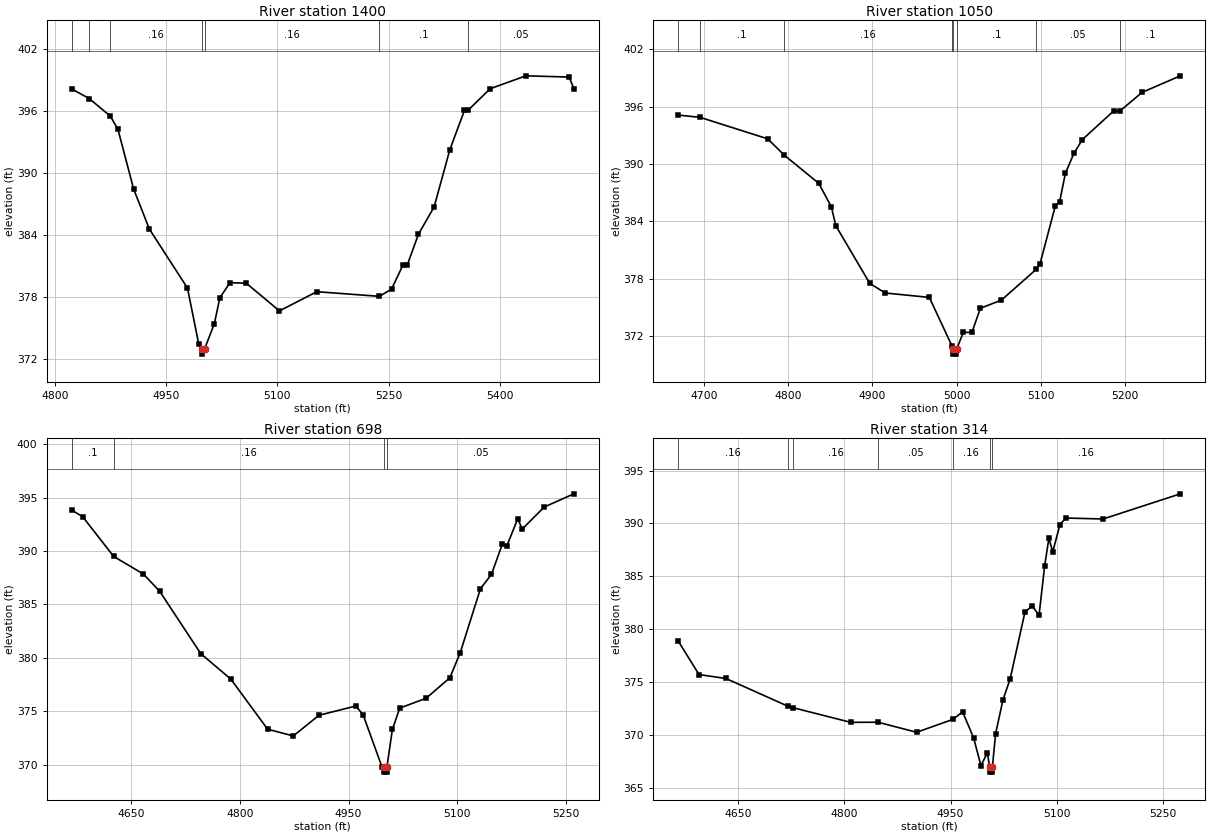
Type RM Length L Ch R = 1,1400,350,350,350
BEGIN DESCRIPTION:
SOUTH MINERAL CR TRIB 7 5 0
END DESCRIPTION:
XS GIS Cut Line= 3
      3515180.42     10374739.70      3514892.11     10374291.64
      3514866.17     10374149.39
#Sta/Elev= 30
  4822.6  398.12  4846.1  397.20  4874.6  395.50  4884.9  394.21  4906.1  388.42
  4927.3  384.55  4978.7  378.83  4993.9  373.41  4997.8  372.93  4998.1  372.43
  5001.8  372.93  5015.0  375.39  5022.4  377.89  5036.1  379.36  5058.1  379.30
  5102.8  376.62  5153.2  378.48  5237.7  378.03  5254.0  378.73  5269.2  381.02
  5275.2  381.06  5290.4  384.06  5311.5  386.70  5332.6  392.22  5352.4  396.05
  5357.1  396.05  5387.1  398.15  5435.3  399.40  5493.7  399.28  5500.0  398.16
#Mann=7,-1,0
  4822.6    0.05       0  4846.1     0.1       0  4874.6    0.16       0
  4997.8    0.07       0  5001.8    0.16       0  5237.7     0.1       0
  5357.1    0.05       0
Bank Sta=4997.8,5001.8
Exp/Cntr=0.3,0.1

Type RM Length L Ch R = 1,1050,352,352,352
BEGIN DESCRIPTION:
SOUTH MINERAL CR TRIB 7 4 0
END DESCRIPTION:
XS GIS Cut Line= 2
      3515314.10     10374626.87      3515225.55     10374036.58
#Sta/Elev= 30
  4669.1  395.13  4695.2  394.89  4775.5  392.64  4795.1  390.94  4836.2  387.98
  4851.2  385.51  4856.4  383.55  4896.8  377.51  4915.2  376.50  4967.6  376.04
  4994.8  370.91  4996.0  370.60  4996.2  370.10  4999.7  370.10  5000.0  370.60
  5008.1  372.39  5018.2  372.37  5028.3  374.90  5053.4  375.76  5094.7  378.98
  5099.1  379.52  5117.5  385.65  5122.5  386.05  5129.4  389.04  5139.5  391.12
  5149.6  392.57  5186.6  395.55  5194.6  395.58  5220.4  397.50  5266.0  399.24
#Mann=8,-1,0
  4669.1    0.05       0  4695.2     0.1       0  4795.1    0.16       0
  4994.8     0.1       0  4996.0    0.07       0  5000.0     0.1       0
  5094.7    0.05       0  5194.6     0.1       0
Bank Sta=4996,5000
Exp/Cntr=0.3,0.1

Type RM Length L Ch R = 1,698,384,384,384
BEGIN DESCRIPTION:
Mapping XS 12cf494b
END DESCRIPTION:
XS GIS Cut Line= 4
      3515440.84     10374560.84      3515525.90     10374390.72
      3515473.81     10374074.75      3515319.98     10373976.23
#Sta/Elev= 30
  4567.9  393.82  4582.8  393.22  4625.8  389.49  4666.7  387.85  4689.1  386.25
  4745.9  380.41  4787.6  378.01  4838.2  373.34  4873.7  372.70  4909.2  374.64
  4959.9  375.50  4970.0  374.70  4996.0  369.83  4999.0  369.82  4999.3  369.32
  5002.8  369.32  5003.0  369.82  5010.5  373.32  5020.7  375.31  5057.1  376.23
  5089.8  378.14  5104.1  380.48  5132.1  386.48  5147.3  387.82  5162.5  390.69
  5168.5  390.48  5183.7  393.04  5189.6  392.05  5220.0  394.11  5261.0  395.35
#Mann=4,-1,0
  4567.9     0.1       0  4625.8    0.16       0  4999.0    0.03       0
  5003.0    0.05       0
Bank Sta=4999,5003
Exp/Cntr=0.3,0.1

Type RM Length L Ch R = 1,314,0,0,0
BEGIN DESCRIPTION:
SOUTH MINERAL CR TRIB 7 1 0
END DESCRIPTION:
XS GIS Cut Line= 4
      3515664.80     10374475.75      3515824.51     10374182.39
      3515779.37     10374012.25      3515595.32     10373934.85
#Sta/Elev= 30
  4565.1  378.87  4594.5  375.70  4632.5  375.33  4720.0  372.71  4727.1  372.57
  4808.9  371.18  4847.5  371.19  4902.1  370.24  4953.3  371.46  4967.1  372.17
  4982.7  369.70  4993.0  367.08  5002.1  368.31  5005.2  366.97  5005.5  366.47
  5009.0  366.47  5009.2  366.97  5013.7  370.10  5024.0  373.28  5034.4  375.32
  5055.1  381.59  5065.4  382.22  5075.1  381.30  5083.0  385.97  5089.0  388.59
  5094.5  387.32  5104.7  389.89  5112.8  390.51  5165.7  390.42  5274.8  392.80
#Mann=7,-1,0
  4565.1    0.16       0  4720.0    0.05       0  4727.1    0.16       0
  4847.5    0.05       0  4953.3    0.16       0  5005.2    0.07       0
  5009.2    0.16       0
Bank Sta=5005.2,5009.2
Exp/Cntr=0.3,0.1

Chan Stop Cuts=-1