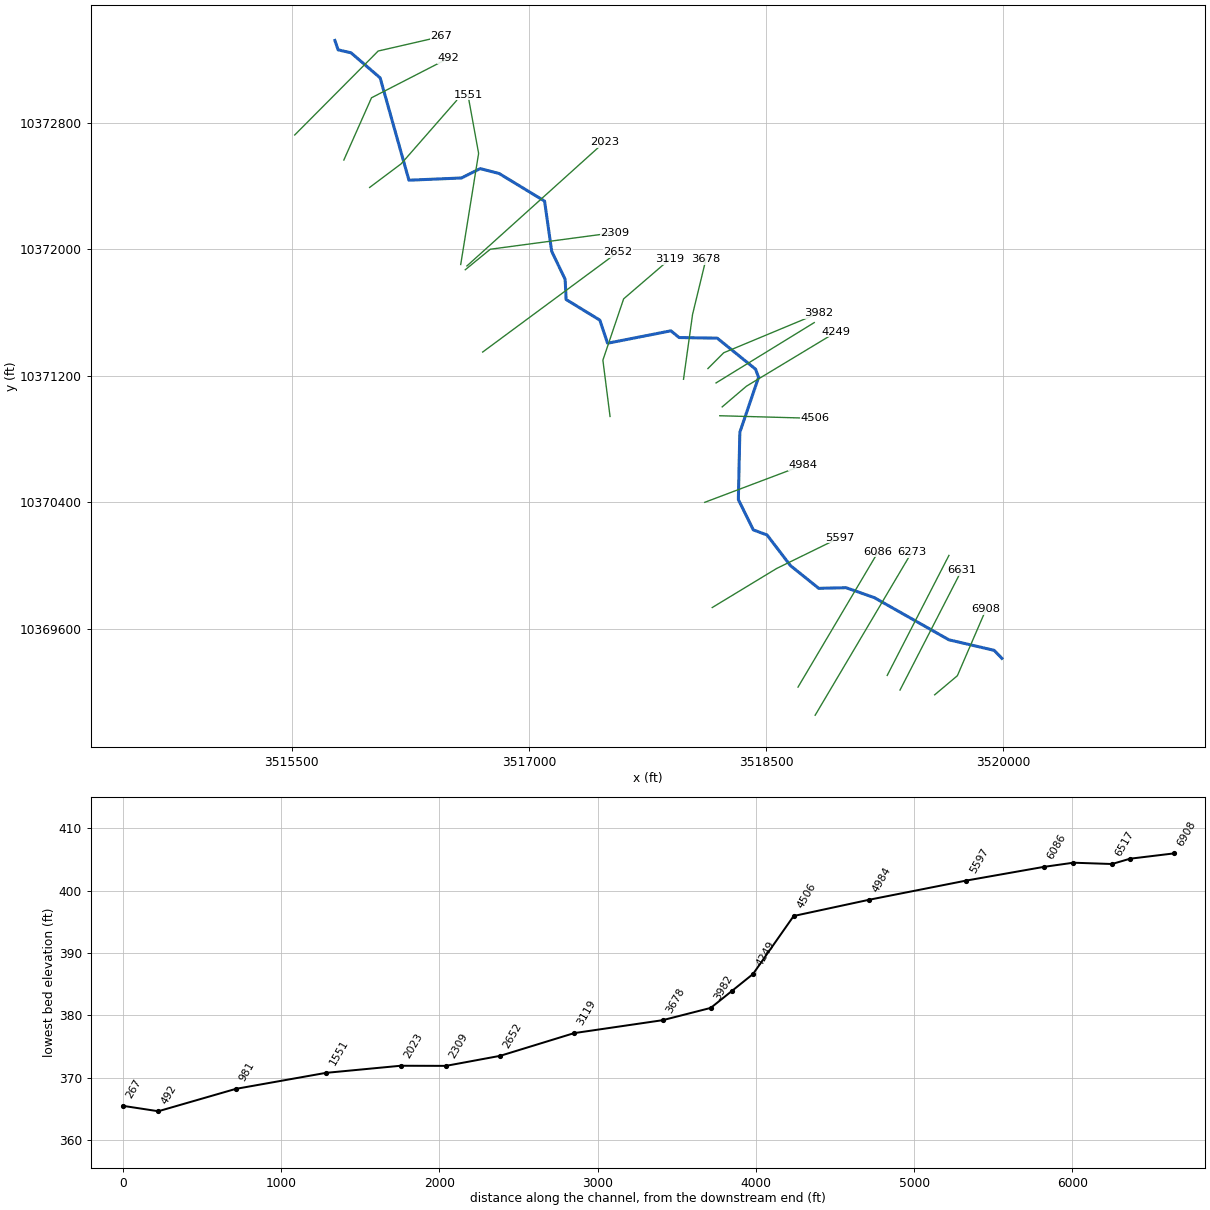
--- SOUTH MINERAL CR TRIB 8.prj (project) ---

Proj Title=SOUTH MINERAL CR TRIB 8 Base Level Engineering
Current Plan=p01
Default Exp/Contr=0.3,0.1
English Units
Geom File=g01
Flow File=f01
Plan File=p01
BEGIN DESCRIPTION:
SOUTH MINERAL CR TRIB 8
END DESCRIPTION:

--- SOUTH MINERAL CR TRIB 8.p01 (plan) ---

Plan Title=Multiple Run
Short Identifier=Multiple
Geom File=g01
Flow File=f01
Subcritical Flow
K Sum by GR= 0
Std Step Tol= 0.01
Critical Tol= 0.01
Num of Std Step Trials= 20
Max Error Tol= 0.3
Flow Tol Ratio= 0.001
Split Flow NTrial= 30
Split Flow Tol= 0.02
Split Flow Ratio= 0.02
Log Output Level= 0
Friction Slope Method= 1
Unsteady Friction Slope Method= 2
Unsteady Bridges Friction Slope Method= 1
Parabolic Critical Depth
Global Vel Dist=  1 , 1 , 1
Global Log Level= 0
CheckData=True
Encroach Param= -1, 0, 0, 0
BEGIN DESCRIPTION:
Multiple Run
END DESCRIPTION:

--- SOUTH MINERAL CR TRIB 8.f01 (steady flow) ---

Flow Title=Multiple
Number of Profiles=7
Profile Names=10-year,25-year,50-year,1pct_min,100-year,1pct_plu,500-year
River Rch & RM= SOUTH MINERAL CR,Reach-1,6908
     922    1272    1562    1399    1892    2559    2772
River Rch & RM= SOUTH MINERAL CR,Reach-1,3119
    1149    1605    1987    1794    2426    3280    3608
Boundary for River Rch & Prof#=SOUTH MINERAL CR,Reach-1,1
Up Type=0
Dn Type=3
Dn Slope=0.005
Boundary for River Rch & Prof#=SOUTH MINERAL CR,Reach-1,2
Up Type=0
Dn Type=3
Dn Slope=0.005
Boundary for River Rch & Prof#=SOUTH MINERAL CR,Reach-1,3
Up Type=0
Dn Type=3
Dn Slope=0.005
Boundary for River Rch & Prof#=SOUTH MINERAL CR,Reach-1,4
Up Type=0
Dn Type=3
Dn Slope=0.005
Boundary for River Rch & Prof#=SOUTH MINERAL CR,Reach-1,5
Up Type=0
Dn Type=3
Dn Slope=0.005
Boundary for River Rch & Prof#=SOUTH MINERAL CR,Reach-1,6
Up Type=0
Dn Type=3
Dn Slope=0.005
Boundary for River Rch & Prof#=SOUTH MINERAL CR,Reach-1,7
Up Type=0
Dn Type=3
Dn Slope=0.005

--- SOUTH MINERAL CR TRIB 8.g01 (geometry) ---

Geom Title=Existing Conditions

River Reach=SOUTH MINERAL CR,Reach-1
Reach XY= 30
      3519992.14     10369412.50      3519942.99     10369463.02
      3519656.92     10369529.62      3519185.39     10369796.28
      3519006.34     10369859.31      3518833.53     10369855.24
      3518654.29     10369999.30      3518506.48     10370192.87
      3518419.59     10370224.89      3518324.83     10370417.03
      3518334.29     10370842.46      3518452.75     10371190.21
      3518434.00     10371241.60      3518191.45     10371438.05
      3517950.13     10371441.96      3517898.05     10371484.50
      3517497.44     10371405.94      3517448.39     10371552.20
      3517235.06     10371682.70      3517229.01     10371810.40
      3517143.96     10371987.41      3517098.85     10372305.20
      3516811.37     10372479.87      3516691.38     10372510.82
      3516573.10     10372451.52      3516240.63     10372437.44
      3516058.50     10373085.01      3515874.18     10373243.61
      3515792.69     10373262.22      3515772.11     10373321.64

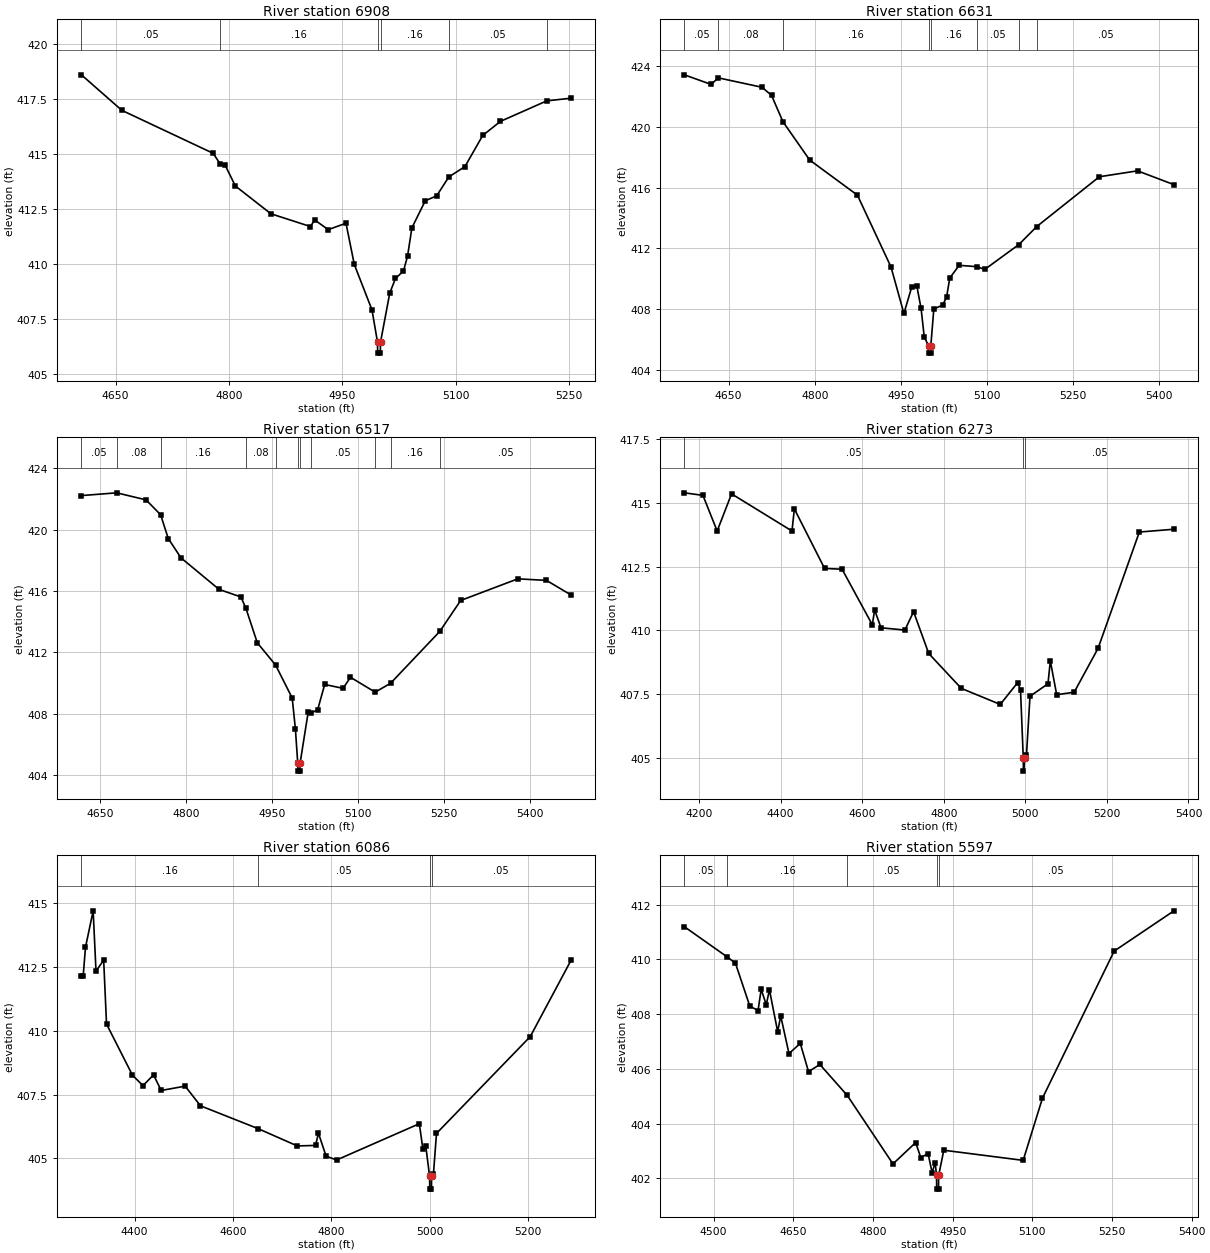
Type RM Length L Ch R = 1,6908,277,277,277
BEGIN DESCRIPTION:
SOUTH MINERAL CR TRIB 8 3 0
END DESCRIPTION:
XS GIS Cut Line= 3
      3519567.04     10369181.52      3519710.44     10369302.27
      3519893.05     10369724.84
#Sta/Elev= 30
  4604.8  418.58  4658.3  416.97  4779.2  415.02  4788.2  414.55  4794.6  414.51
  4808.5  413.54  4855.5  412.28  4907.9  411.70  4913.4  412.00  4931.4  411.56
  4954.9  411.85  4965.9  409.98  4989.3  407.92  4996.6  406.46  4996.8  405.96
  5000.3  405.96  5000.6  406.46  5012.8  408.68  5020.4  409.35  5030.9  409.68
  5036.3  410.35  5042.1  411.64  5059.8  412.87  5074.8  413.09  5091.0  413.95
  5112.3  414.42  5135.8  415.83  5159.3  416.47  5220.6  417.40  5252.6  417.52
#Mann=6,-1,0
  4604.8    0.05       0  4788.2    0.16       0  4996.6    0.07       0
  5000.6    0.16       0  5091.0    0.05       0  5220.6    0.16       0
Bank Sta=4996.6,5000.6
Exp/Cntr=0.3,0.1

Type RM Length L Ch R = 1,6631,114,114,114
BEGIN DESCRIPTION:
SOUTH MINERAL CR TRIB 8 21 0
END DESCRIPTION:
XS GIS Cut Line= 2
      3519347.69     10369211.61      3519737.72     10369969.99
#Sta/Elev= 30
  4572.9  423.43  4619.4  422.80  4632.1  423.23  4708.2  422.61  4724.7  422.08
  4744.5  420.35  4791.2  417.82  4874.3  415.51  4932.8  410.78  4955.3  407.72
  4968.7  409.44  4977.8  409.53  4985.2  408.05  4990.8  406.15  4998.2  405.61
  4998.5  405.11  5002.0  405.11  5002.2  405.61  5007.4  408.02  5022.7  408.27
  5029.6  408.79  5035.2  410.06  5051.7  410.89  5082.6  410.80  5096.1  410.62
  5155.6  412.26  5186.6  413.44  5295.7  416.72  5362.2  417.11  5425.7  416.20
#Mann=8,-1,0
  4572.9    0.05       0  4632.1    0.08       0  4744.5    0.16       0
  4998.2    0.07       0  5002.2    0.16       0  5082.6    0.05       0
  5155.6    0.16       0  5186.6    0.05       0
Bank Sta=4998.2,5002.2
Exp/Cntr=0.3,0.1

Type RM Length L Ch R = 1,6517,244,244,244
BEGIN DESCRIPTION:
SOUTH MINERAL CR TRIB 8 22 0
END DESCRIPTION:
XS GIS Cut Line= 2
      3519266.63     10369304.21      3519657.20     10370063.66
#Sta/Elev= 30
  4617.6  422.23  4679.2  422.41  4730.4  421.95  4755.8  420.98  4769.1  419.43
  4791.3  418.17  4857.8  416.11  4895.8  415.62  4904.6  414.88  4924.4  412.63
  4956.3  411.18  4985.3  409.03  4990.9  407.01  4995.0  404.76  4995.3  404.26
  4998.8  404.26  4999.0  404.76  5013.1  408.09  5017.3  408.04  5029.6  408.25
  5042.0  409.91  5074.0  409.66  5087.0  410.38  5130.0  409.41  5156.9  409.99
  5242.7  413.37  5279.2  415.39  5378.8  416.80  5428.8  416.70  5471.6  415.75
#Mann=11,-1,0
  4617.6    0.05       0  4679.2    0.08       0  4755.8    0.16       0
  4904.6    0.08       0  4956.3    0.16       0  4995.0    0.07       0
  4999.0    0.16       0  5017.3    0.05       0  5130.0    0.08       0
  5156.9    0.16       0  5242.7    0.05       0
Bank Sta=4995,4999
Exp/Cntr=0.3,0.1

Type RM Length L Ch R = 1,6273,187,187,187
BEGIN DESCRIPTION:
SOUTH MINERAL CR TRIB 8 16 0
END DESCRIPTION:
XS GIS Cut Line= 2
      3518810.91     10369052.49      3519422.86     10370085.43
#Sta/Elev= 30
  4163.9  415.40  4209.4  415.30  4244.3  413.90  4279.6  415.36  4427.8  413.90
  4433.6  414.77  4507.7  412.43  4550.6  412.40  4624.7  410.22  4630.5  410.80
  4646.1  410.10  4704.6  410.01  4726.0  410.73  4763.1  409.09  4843.0  407.72
  4938.5  407.09  4981.4  407.95  4988.2  407.65  4995.0  404.97  4995.3  404.47
  4999.0  404.97  5002.8  405.09  5011.4  407.41  5055.5  407.90  5061.3  408.80
  5076.9  407.47  5119.8  407.57  5178.3  409.29  5279.6  413.86  5364.5  413.97
#Mann=3,-1,0
  4163.9    0.05       0  4995.0    0.04       0  4999.0    0.05       0
Bank Sta=4995,4999
Exp/Cntr=0.3,0.1

Type RM Length L Ch R = 1,6086,489,489,489
BEGIN DESCRIPTION:
SOUTH MINERAL CR TRIB 8 17 0
END DESCRIPTION:
XS GIS Cut Line= 3
      3518702.37     10369230.40      3518960.73     10369666.49
      3519209.84     10370086.96
#Sta/Elev= 30
  4291.7  412.13  4295.3  412.13  4300.0  413.26  4315.6  414.69  4321.4  412.33
  4337.0  412.76  4342.8  410.26  4395.5  408.26  4416.9  407.85  4438.4  408.27
  4454.0  407.66  4502.7  407.83  4533.9  407.06  4650.6  406.17  4730.8  405.49
  4767.9  405.51  4773.7  405.99  4789.3  405.09  4810.7  404.94  4978.9  406.36
  4986.2  405.36  4992.0  405.49  4999.8  404.30  5000.1  403.80  5003.6  403.80
  5003.8  404.30  5007.6  404.39  5013.8  405.98  5204.5  409.77  5287.3  412.75
#Mann=4,-1,0
  4291.7    0.16       0  4650.6    0.05       0  4999.8    0.03       0
  5003.8    0.05       0
Bank Sta=4999.8,5003.8
Exp/Cntr=0.3,0.1

Type RM Length L Ch R = 1,5597,613,613,613
BEGIN DESCRIPTION:
SOUTH MINERAL CR TRIB 8 2 0
END DESCRIPTION:
XS GIS Cut Line= 3
      3518159.83     10369733.89      3518567.85     10369981.30
      3518967.17     10370176.62
#Sta/Elev= 30
  4445.0  411.19  4526.1  410.08  4541.1  409.86  4568.2  408.29  4583.7  408.13
  4589.6  408.90  4599.2  408.34  4605.1  408.89  4620.6  407.36  4626.4  407.93
  4641.9  406.56  4663.2  406.93  4678.7  405.90  4700.1  406.16  4751.7  405.03
  4837.7  402.53  4880.4  403.31  4890.1  402.76  4903.8  402.91  4911.4  402.21
  4917.2  402.58  4919.7  402.11  4920.0  401.61  4923.5  401.61  4923.7  402.11
  4933.4  403.03  5082.8  402.66  5119.1  404.93  5254.1  410.30  5366.7  411.77
#Mann=5,-1,0
  4445.0    0.05       0  4526.1    0.16       0  4751.7    0.05       0
  4919.7    0.03       0  4923.7    0.05       0
Bank Sta=4919.7,4923.7
Exp/Cntr=0.3,0.1

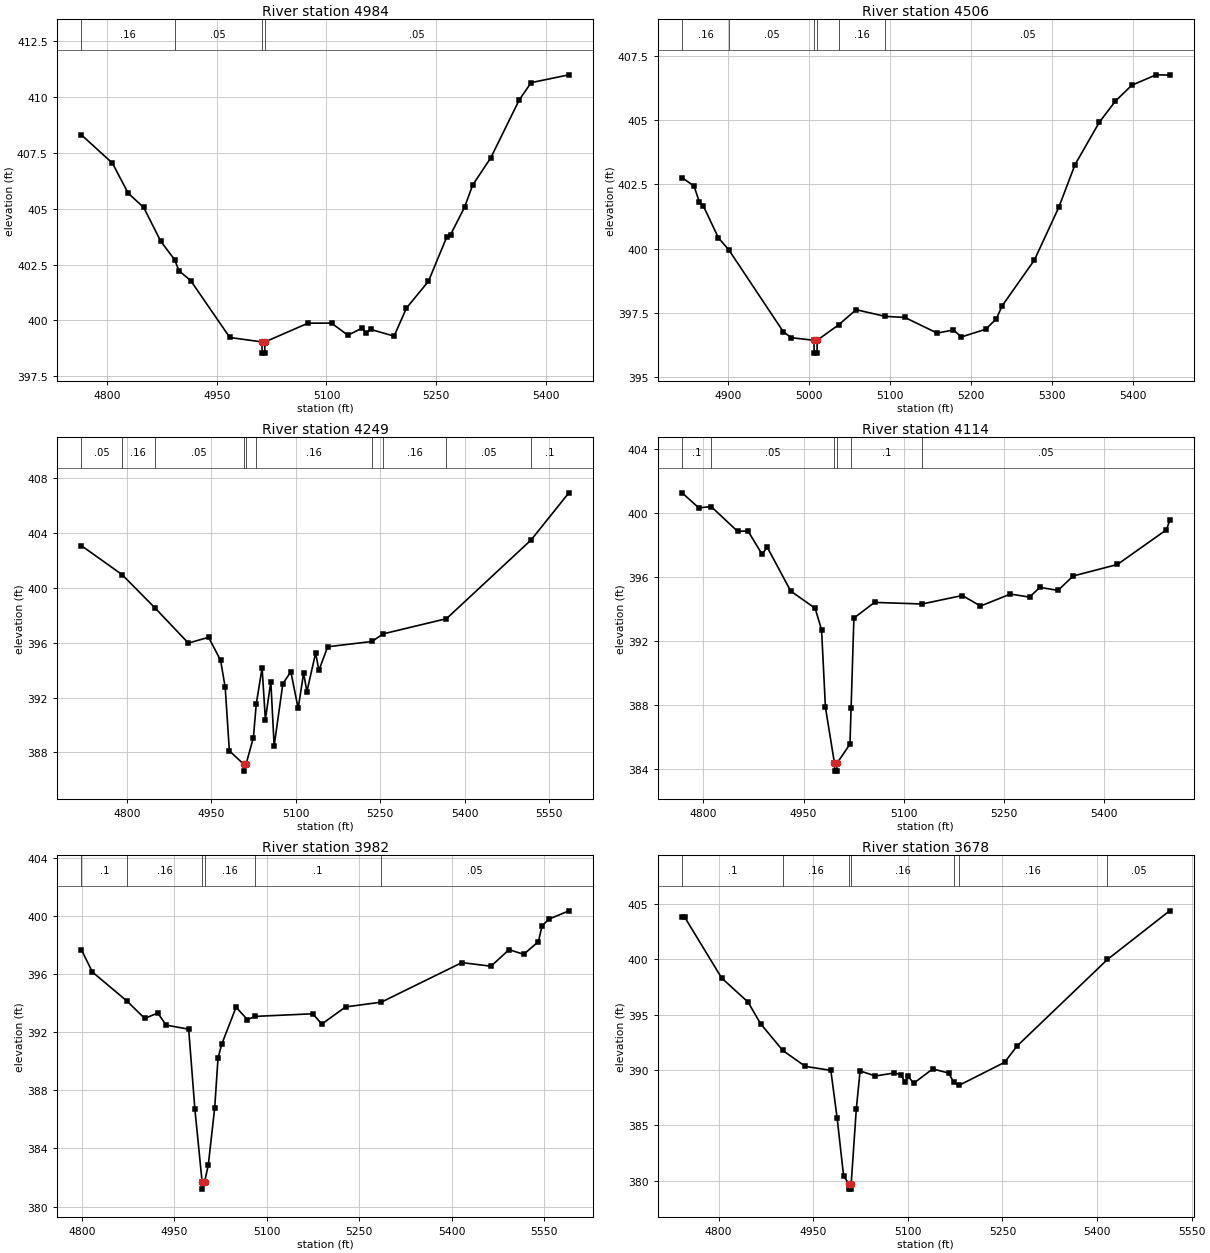
Type RM Length L Ch R = 1,4984,478,478,478
BEGIN DESCRIPTION:
SOUTH MINERAL CR TRIB 8 15 0
END DESCRIPTION:
XS GIS Cut Line= 2
      3518112.27     10370399.45      3518735.49     10370634.85
#Sta/Elev= 30
  4765.0  408.30  4807.6  407.03  4829.0  405.69  4850.3  405.05  4873.7  403.53
  4892.5  402.72  4898.5  402.22  4914.5  401.78  4967.9  399.24  5011.9  399.04
  5012.1  398.54  5015.6  398.54  5015.9  399.04  5074.8  399.88  5106.9  399.88
  5129.3  399.34  5148.8  399.66  5154.1  399.44  5160.3  399.60  5192.4  399.30
  5209.2  400.55  5239.3  401.75  5264.2  403.72  5269.5  403.83  5288.6  405.06
  5299.7  406.05  5324.5  407.27  5363.4  409.86  5379.6  410.63  5431.2  410.98
#Mann=4,-1,0
  4765.0    0.16       0  4892.5    0.05       0  5011.9    0.03       0
  5015.9    0.05       0
Bank Sta=5011.9,5015.9
Exp/Cntr=0.3,0.1

Type RM Length L Ch R = 1,4506,257,257,257
BEGIN DESCRIPTION:
SOUTH MINERAL CR TRIB 8 12 0
END DESCRIPTION:
XS GIS Cut Line= 2
      3518207.32     10370947.26      3518808.99     10370930.71
#Sta/Elev= 30
  4843.6  402.76  4858.4  402.43  4864.7  401.83  4869.7  401.67  4888.4  400.42
  4901.5  399.94  4968.4  396.77  4978.4  396.53  5006.4  396.43  5006.7  395.93
  5010.2  395.93  5010.4  396.43  5036.8  397.03  5058.5  397.62  5094.3  397.36
  5118.5  397.32  5158.5  396.71  5178.5  396.83  5188.5  396.56  5218.5  396.86
  5231.7  397.27  5238.5  397.76  5278.5  399.55  5308.6  401.60  5328.6  403.26
  5358.6  404.91  5378.6  405.74  5398.6  406.35  5428.6  406.76  5445.5  406.75
#Mann=6,-1,0
  4843.6    0.16       0  4901.5    0.05       0  5006.4    0.03       0
  5010.4    0.05       0  5036.8    0.16       0  5094.3    0.05       0
Bank Sta=5006.4,5010.4
Exp/Cntr=0.3,0.1

Type RM Length L Ch R = 1,4249,135,135,135
BEGIN DESCRIPTION:
SOUTH MINERAL CR TRIB 8 11 0
END DESCRIPTION:
XS GIS Cut Line= 3
      3518222.41     10371003.11      3518376.33     10371134.40
      3518945.25     10371477.55
#Sta/Elev= 30
  4718.8  403.08  4791.1  400.97  4849.2  398.56  4909.1  395.97  4945.1  396.39
  4966.4  394.71  4974.6  392.74  4982.0  388.11  5007.6  387.13  5007.8  386.63
  5011.6  387.13  5024.7  389.07  5029.9  391.56  5040.2  394.16  5046.0  390.39
  5055.7  393.16  5061.6  388.47  5077.1  393.01  5091.3  393.88  5104.3  391.20
  5114.0  393.79  5119.8  392.42  5135.3  395.24  5141.2  393.98  5156.7  395.70
  5235.8  396.09  5255.2  396.64  5367.9  397.75  5518.3  403.49  5585.5  406.93
#Mann=10,-1,0
  4718.8    0.05       0  4791.1    0.16       0  4849.2    0.05       0
  5007.6    0.03       0  5011.6    0.05       0  5029.9    0.16       0
  5235.8    0.05       0  5255.2    0.16       0  5367.9    0.05       0
  5518.3     0.1       0
Bank Sta=5007.6,5011.6
Exp/Cntr=0.3,0.1

Type RM Length L Ch R = 1,4114,132,132,132
BEGIN DESCRIPTION:
SOUTH MINERAL CR TRIB 8 29 1
END DESCRIPTION:
XS GIS Cut Line= 2
      3518183.63     10371154.74      3518805.16     10371536.68
#Sta/Elev= 30
  4768.2  401.28  4793.3  400.34  4811.8  400.42  4851.3  398.87  4866.8  398.90
  4888.0  397.43  4895.5  397.89  4930.7  395.14  4967.3  394.06  4976.9  392.72
  4982.7  387.87  4996.2  384.38  4996.4  383.88  4999.9  383.88  5000.2  384.38
  5019.4  385.57  5021.1  387.84  5025.3  393.45  5056.2  394.43  5127.3  394.33
  5187.6  394.86  5214.7  394.20  5259.4  394.95  5288.1  394.76  5303.5  395.37
  5330.7  395.18  5353.3  396.08  5419.5  396.80  5492.9  398.97  5497.7  399.55
#Mann=6,-1,0
  4768.2     0.1       0  4811.8    0.05       0  4996.2    0.04       0
  5000.2    0.05       0  5021.1     0.1       0  5127.3    0.05       0
Bank Sta=4996.2,5000.2
Exp/Cntr=0.3,0.1

Type RM Length L Ch R = 1,3982,304,304,304
BEGIN DESCRIPTION:
SOUTH MINERAL CR TRIB 8 19 1
END DESCRIPTION:
XS GIS Cut Line= 3
      3518132.41     10371245.83      3518232.38     10371345.81
      3518832.39     10371595.81
#Sta/Elev= 30
  4799.0  397.68  4817.0  396.13  4873.8  394.11  4901.9  392.94  4923.1  393.31
  4936.7  392.48  4973.3  392.20  4983.4  386.68  4995.1  381.70  4995.4  381.20
  4999.1  381.70  5005.1  382.85  5015.5  386.78  5020.9  390.20  5026.8  391.15
  5050.2  393.71  5068.6  392.86  5081.2  393.08  5174.8  393.26  5189.3  392.55
  5227.9  393.73  5286.0  394.06  5416.8  396.78  5464.0  396.53  5493.3  397.67
  5517.1  397.35  5540.9  398.22  5546.8  399.29  5557.6  399.76  5590.4  400.34
#Mann=6,-1,0
  4799.0     0.1       0  4873.8    0.16       0  4995.1    0.07       0
  4999.1    0.16       0  5081.2     0.1       0  5286.0    0.05       0
Bank Sta=4995.1,4999.1
Exp/Cntr=0.3,0.1

Type RM Length L Ch R = 1,3678,559,559,559
BEGIN DESCRIPTION:
SOUTH MINERAL CR TRIB 8 9 1
END DESCRIPTION:
XS GIS Cut Line= 3
      3517977.91     10371178.14      3518035.26     10371588.66
      3518119.70     10371936.97
#Sta/Elev= 30
  4742.2  403.81  4746.5  403.81  4805.0  398.32  4846.7  396.15  4866.9  394.17
  4901.9  391.77  4937.6  390.33  4978.0  389.97  4988.1  385.62  4998.2  380.44
  5006.3  379.73  5006.5  379.23  5010.0  379.23  5010.3  379.73  5018.4  386.48
  5024.4  389.92  5048.6  389.46  5078.9  389.74  5089.0  389.58  5095.9  388.88
  5101.0  389.42  5109.2  388.80  5139.5  390.10  5164.7  389.73  5173.0  388.89
  5181.0  388.61  5253.5  390.70  5273.0  392.16  5416.5  400.00  5515.1  404.40
#Mann=7,-1,0
  4742.2     0.1       0  4901.9    0.16       0  5006.3    0.07       0
  5010.3    0.16       0  5173.0     0.1       0  5181.0    0.16       0
  5416.5    0.05       0
Bank Sta=5006.3,5010.3
Exp/Cntr=0.3,0.1

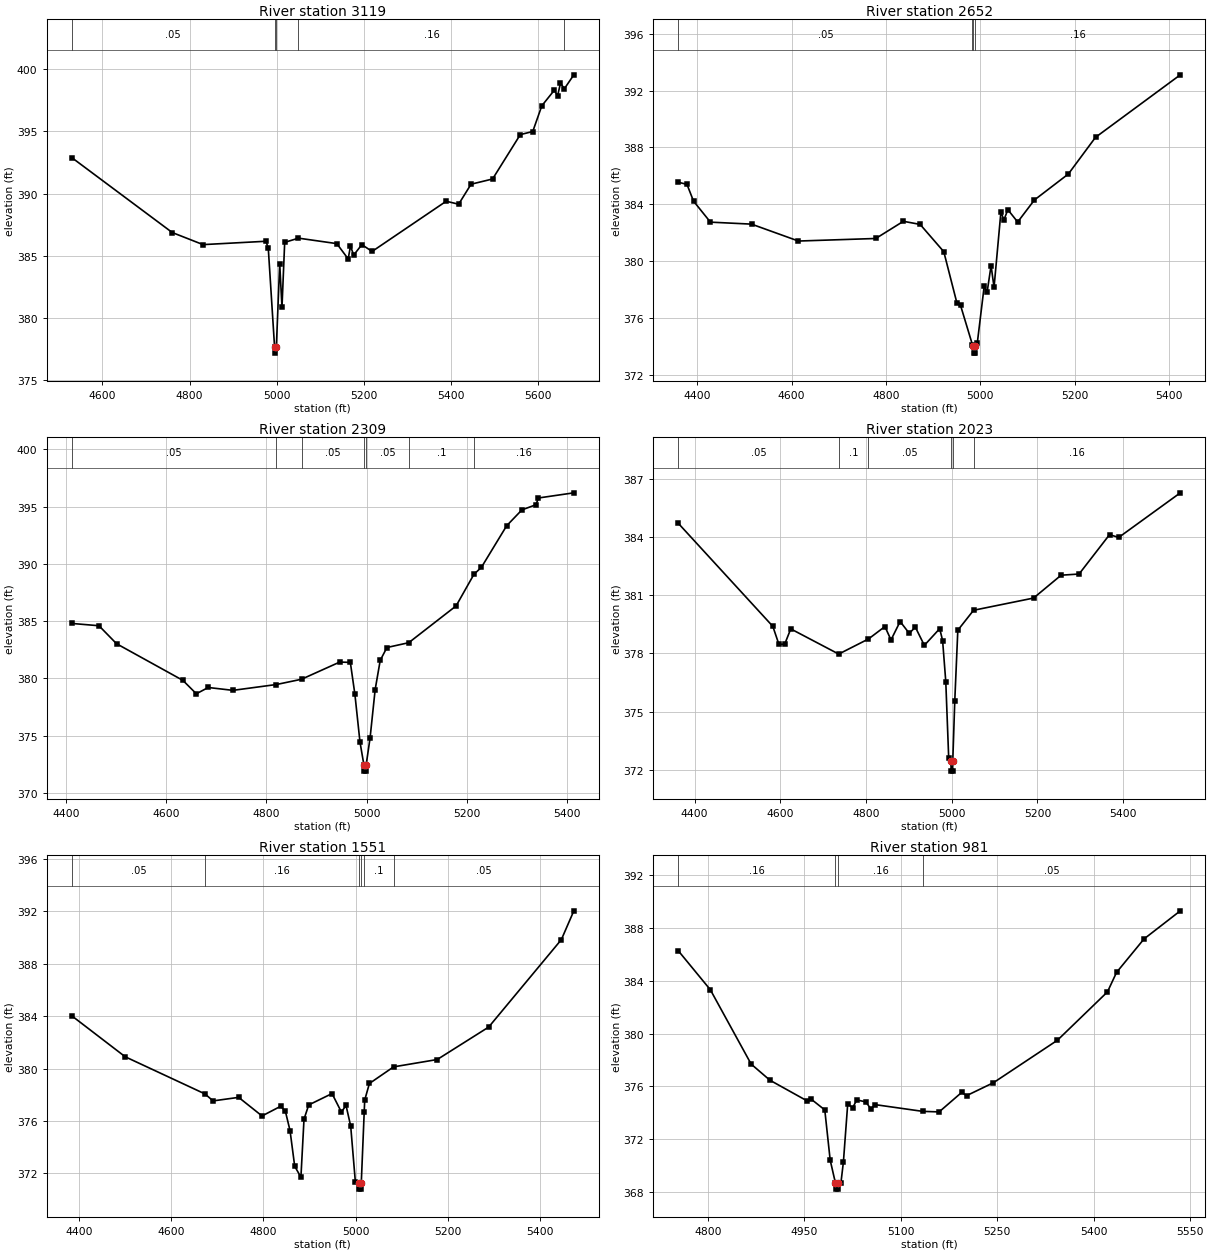
Type RM Length L Ch R = 1,3119,467,467,467
BEGIN DESCRIPTION:
SOUTH MINERAL CR TRIB 8 9 0
END DESCRIPTION:
XS GIS Cut Line= 4
      3517513.09     10370942.74      3517467.81     10371298.90
      3517599.11     10371686.75      3517890.01     10371936.96
#Sta/Elev= 30
  4529.7  392.89  4760.4  386.86  4831.0  385.89  4975.4  386.16  4980.7  385.58
  4995.1  377.66  4995.4  377.16  4999.2  377.66  5006.9  384.36  5012.1  380.84
  5018.3  386.07  5050.0  386.41  5137.9  385.97  5164.0  384.74  5169.3  385.77
  5176.7  385.05  5195.4  385.89  5218.9  385.34  5389.0  389.38  5417.5  389.14
  5446.0  390.75  5495.4  391.17  5559.0  394.74  5587.6  394.99  5608.4  397.06
  5637.0  398.31  5644.6  397.86  5651.2  398.87  5660.3  398.44  5681.9  399.55
#Mann=5,-1,0
  4529.7    0.05       0  4995.1    0.03       0  4999.2    0.05       0
  5050.0    0.16       0  5660.3    0.05       0
Bank Sta=4995.1,4999.2
Exp/Cntr=0.3,0.1

Type RM Length L Ch R = 1,2652,343,343,343
BEGIN DESCRIPTION:
SOUTH MINERAL CR TRIB 8 8 0
END DESCRIPTION:
XS GIS Cut Line= 2
      3516707.23     10371350.23      3517562.85     10371982.52
#Sta/Elev= 30
  4359.7  385.55  4378.2  385.40  4392.1  384.22  4427.9  382.74  4515.0  382.60
  4614.4  381.41  4778.3  381.59  4836.8  382.80  4872.3  382.58  4922.4  380.66
  4950.2  377.05  4957.9  376.88  4983.1  374.11  4985.1  374.02  4985.4  373.52
  4989.0  373.52  4989.2  374.02  4993.4  374.23  5008.0  378.22  5014.2  377.81
  5022.6  379.68  5028.9  378.15  5043.5  383.48  5049.7  382.88  5058.1  383.62
  5079.0  382.75  5114.4  384.30  5186.4  386.13  5243.9  388.71  5423.6  393.11
#Mann=4,-1,0
  4359.7    0.05       0  4983.1    0.16       0  4985.1    0.07       0
  4989.2    0.16       0
Bank Sta=4985.1,4989.2
Exp/Cntr=0.3,0.1

Type RM Length L Ch R = 1,2309,286,286,286
BEGIN DESCRIPTION:
SOUTH MINERAL CR TRIB 8 7 0
END DESCRIPTION:
XS GIS Cut Line= 3
      3516597.01     10371870.86      3516755.49     10372000.66
      3517544.80     10372106.30
#Sta/Elev= 30
  4411.7  384.80  4465.9  384.60  4501.0  383.03  4633.3  379.83  4660.1  378.66
  4683.8  379.21  4733.1  378.96  4819.9  379.47  4869.9  379.93  4946.1  381.43
  4967.2  381.40  4976.3  378.61  4986.4  374.46  4994.4  372.41  4994.7  371.91
  4998.3  371.91  4998.6  372.41  5006.6  374.82  5016.7  379.03  5026.8  381.58
  5040.2  382.70  5083.7  383.12  5178.1  386.33  5213.7  389.09  5228.6  389.70
  5279.0  393.33  5309.3  394.71  5337.3  395.16  5342.3  395.75  5412.9  396.20
#Mann=7,-1,0
  4411.7    0.05       0  4819.9     0.1       0  4869.9    0.05       0
  4994.4    0.03       0  4998.6    0.05       0  5083.7     0.1       0
  5213.7    0.16       0
Bank Sta=4994.4,4998.6
Exp/Cntr=0.3,0.1

Type RM Length L Ch R = 1,2023,472,472,472
BEGIN DESCRIPTION:
SOUTH MINERAL CR TRIB 8 6 0
END DESCRIPTION:
XS GIS Cut Line= 2
      3516607.55     10371894.99      3517477.72     10372679.19
#Sta/Elev= 30
  4362.0  384.72  4582.7  379.40  4596.9  378.47  4610.4  378.48  4624.5  379.27
  4736.4  377.97  4805.9  378.75  4844.2  379.39  4858.4  378.70  4879.7  379.65
  4901.0  379.04  4915.2  379.36  4936.2  378.42  4972.0  379.28  4978.8  378.67
  4986.2  376.55  4993.0  372.62  4998.3  372.43  4998.6  371.93  5002.2  371.93
  5002.5  372.43  5007.2  375.56  5014.3  379.20  5051.0  380.23  5191.0  380.86
  5255.3  382.04  5297.2  382.10  5368.2  384.13  5389.8  383.99  5533.4  386.29
#Mann=6,-1,0
  4362.0    0.05       0  4736.4     0.1       0  4805.9    0.05       0
  4998.3    0.03       0  5002.5    0.05       0  5051.0    0.16       0
Bank Sta=4998.3,5002.5
Exp/Cntr=0.3,0.1

Type RM Length L Ch R = 1,1551,570,570,570
BEGIN DESCRIPTION:
SOUTH MINERAL CR TRIB 8 5 0
END DESCRIPTION:
XS GIS Cut Line= 3
      3516568.35     10371904.10      3516681.54     10372607.34
      3516613.95     10372978.34
#Sta/Elev= 30
  4384.2  384.03  4500.2  380.90  4673.4  378.06  4690.8  377.53  4746.3  377.80
  4797.0  376.38  4837.5  377.12  4847.6  376.75  4857.8  375.26  4867.9  372.54
  4881.4  371.70  4888.1  376.13  4898.3  377.22  4948.9  378.09  4969.2  376.68
  4979.3  377.18  4989.4  375.61  4999.6  371.31  5008.0  371.29  5008.3  370.79
  5012.1  370.79  5012.4  371.29  5018.7  376.65  5019.8  377.59  5030.0  378.86
  5082.5  380.13  5177.1  380.69  5288.8  383.17  5446.5  389.85  5473.6  392.05
#Mann=6,-1,0
  4384.2    0.05       0  4673.4    0.16       0  5008.0    0.07       0
  5012.4    0.16       0  5018.7     0.1       0  5082.5    0.05       0
Bank Sta=5008,5012.4
Exp/Cntr=0.3,0.1

Type RM Length L Ch R = 1,981,489,489,489
BEGIN DESCRIPTION:
SOUTH MINERAL CR TRIB 8 4 0
END DESCRIPTION:
XS GIS Cut Line= 3
      3515992.10     10372391.64      3516192.11     10372541.64
      3516542.10     10372941.63
#Sta/Elev= 30
  4753.5  386.28  4803.5  383.32  4867.0  377.69  4896.2  376.47  4953.5  374.92
  4960.8  375.02  4981.6  374.22  4990.0  370.42  4998.0  368.72  4998.3  368.22
  5002.4  368.22  5002.8  368.72  5006.8  368.72  5010.6  370.28  5017.3  374.68
  5024.9  374.38  5031.5  374.98  5045.7  374.82  5053.3  374.29  5060.0  374.62
  5134.0  374.11  5159.6  374.07  5194.8  375.55  5202.3  375.30  5244.1  376.28
  5343.8  379.50  5421.6  383.16  5435.8  384.64  5478.5  387.17  5535.0  389.30
#Mann=4,-1,0
  4753.5    0.16       0  4998.0    0.07       0  5002.8    0.16       0
  5134.0    0.05       0
Bank Sta=4998,5002.8
Exp/Cntr=0.3,0.1

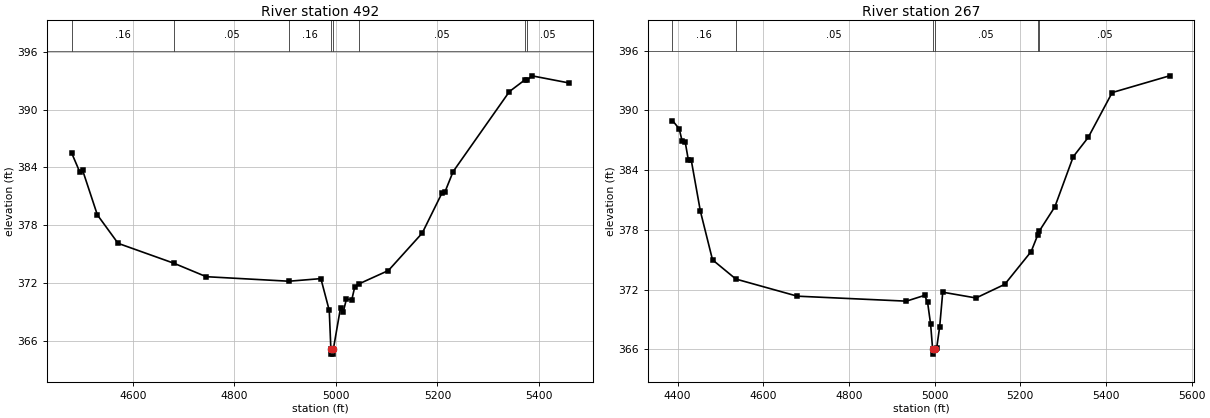
Type RM Length L Ch R = 1,492,225,225,225
BEGIN DESCRIPTION:
Mapping XS f18b1b83
END DESCRIPTION:
XS GIS Cut Line= 3
      3515828.88     10372565.13      3516003.92     10372958.98
      3516491.41     10373209.52
#Sta/Elev= 30
  4479.2  385.53  4495.6  383.51  4501.1  383.70  4530.1  379.08  4570.9  376.13
  4680.6  374.07  4744.6  372.67  4907.5  372.20  4970.4  372.47  4986.9  369.17
  4990.1  365.14  4990.5  364.64  4994.6  364.64  4994.9  365.14  5009.1  369.45
  5014.7  369.06  5020.6  370.33  5031.3  370.29  5036.9  371.56  5045.6  371.93
  5103.4  373.31  5170.0  377.19  5208.7  381.32  5214.4  381.41  5230.9  383.57
  5341.8  391.87  5372.2  393.08  5376.9  393.08  5386.2  393.50  5458.3  392.77
#Mann=8,-1,0
  4479.2    0.16       0  4680.6    0.05       0  4907.5    0.16       0
  4990.1    0.07       0  4994.9    0.16       0  5045.6    0.05       0
  5372.2    0.16       0  5376.9    0.05       0
Bank Sta=4990.1,4994.9
Exp/Cntr=0.3,0.1

Type RM Length L Ch R = 1,267,0,0,0
BEGIN DESCRIPTION:
SOUTH MINERAL CR TRIB 8 1 0
END DESCRIPTION:
XS GIS Cut Line= 3
      3515517.99     10372723.57      3516046.18     10373254.78
      3516446.97     10373346.69
#Sta/Elev= 30
  4388.0  388.97  4403.7  388.14  4410.8  386.87  4417.8  386.80  4424.9  385.05
  4432.0  384.96  4453.2  379.86  4481.5  374.98  4536.0  373.05  4679.5  371.33
  4934.0  370.83  4976.5  371.41  4983.5  370.73  4990.6  368.52  4995.3  366.01
  4995.6  365.51  5000.1  366.01  5004.7  366.11  5011.8  368.26  5018.9  371.73
  5096.6  371.15  5163.7  372.52  5225.3  375.81  5240.6  377.47  5244.3  377.87
  5280.7  380.31  5323.6  385.34  5358.6  387.28  5414.5  391.78  5548.3  393.46
#Mann=6,-1,0
  4388.0    0.16       0  4536.0    0.05       0  4995.3   0.035       0
  5000.1    0.05       0  5240.6    0.16       0  5244.3    0.05       0
Bank Sta=4995.3,5000.1
Exp/Cntr=0.3,0.1

Chan Stop Cuts=-1