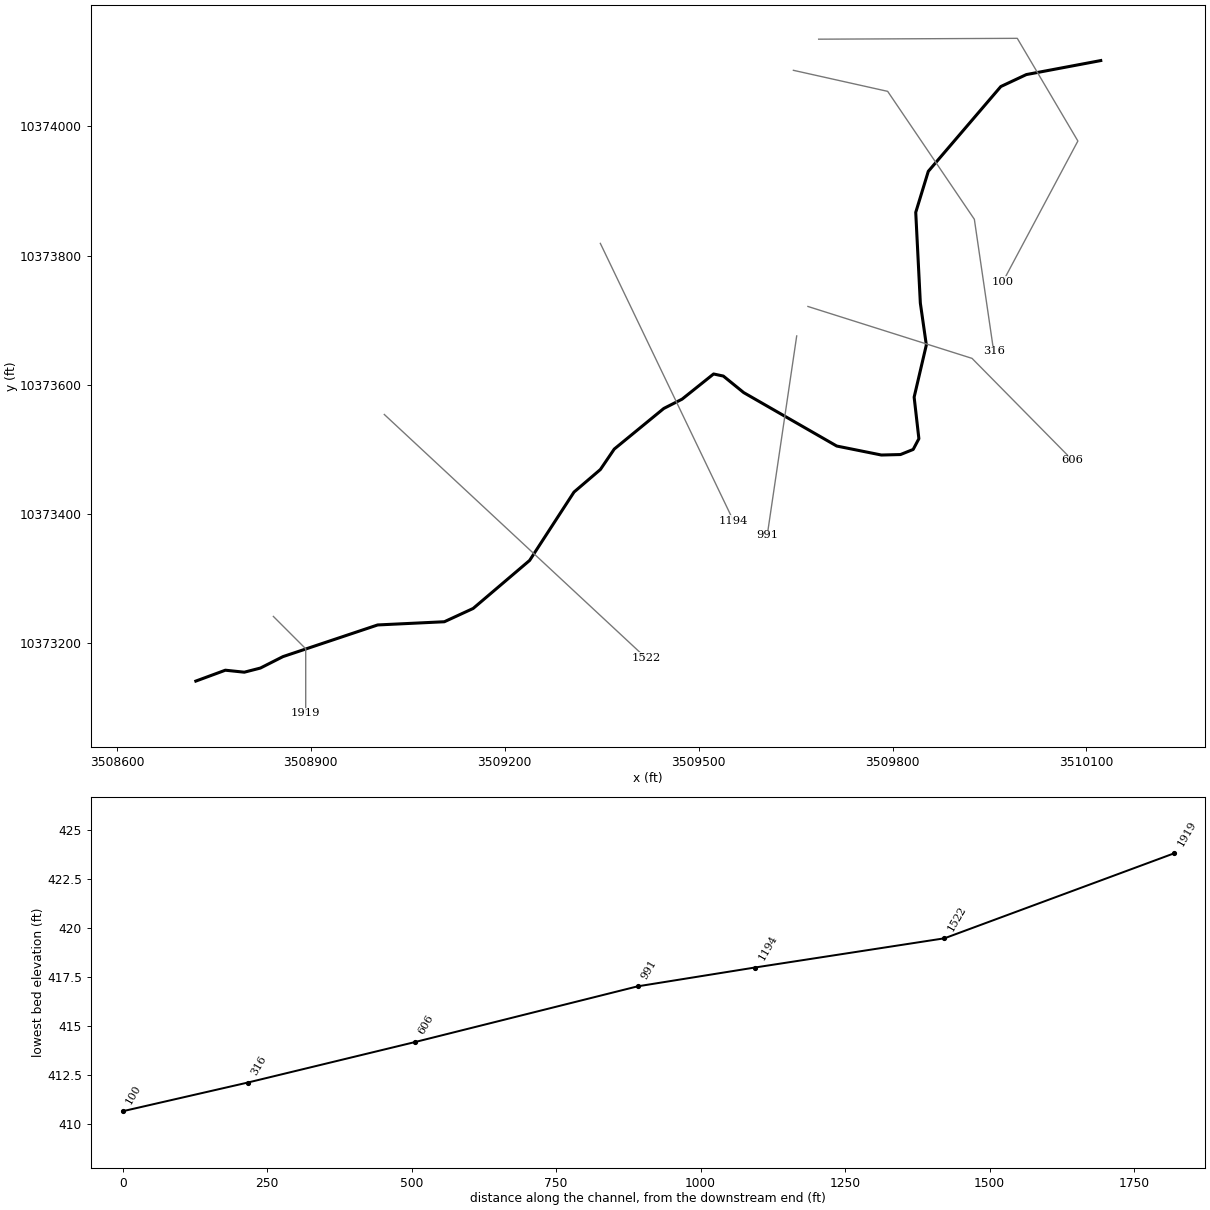
--- SOUTH MINERAL CR TRIB 9 1.prj (project) ---

Proj Title=SOUTH MINERAL CR TRIB 9 1 Base Level Engineering
Current Plan=p01
Default Exp/Contr=0.3,0.1
English Units
Geom File=g01
Flow File=f01
Plan File=p01
BEGIN DESCRIPTION:
SOUTH MINERAL CR TRIB 9 1
END DESCRIPTION:

--- SOUTH MINERAL CR TRIB 9 1.p01 (plan) ---

Plan Title=Multiple Run
Short Identifier=Multiple
Geom File=g01
Flow File=f01
Subcritical Flow
K Sum by GR= 0
Std Step Tol= 0.01
Critical Tol= 0.01
Num of Std Step Trials= 20
Max Error Tol= 0.3
Flow Tol Ratio= 0.001
Split Flow NTrial= 30
Split Flow Tol= 0.02
Split Flow Ratio= 0.02
Log Output Level= 0
Friction Slope Method= 1
Unsteady Friction Slope Method= 2
Unsteady Bridges Friction Slope Method= 1
Parabolic Critical Depth
Global Vel Dist=  1 , 1 , 1
Global Log Level= 0
CheckData=True
Encroach Param= -1, 0, 0, 0
BEGIN DESCRIPTION:
Multiple Run
END DESCRIPTION:

--- SOUTH MINERAL CR TRIB 9 1.f01 (steady flow) ---

Flow Title=Multiple
Number of Profiles=7
Profile Names=10-year,25-year,50-year,1pct_min,100-year,1pct_plu,500-year
River Rch & RM= SOUTH MINERAL CR,Reach-1,1919
     591     801     971     863    1167    1578    1677
Boundary for River Rch & Prof#=SOUTH MINERAL CR,Reach-1,1
Up Type=0
Dn Type=3
Dn Slope=0.005
Boundary for River Rch & Prof#=SOUTH MINERAL CR,Reach-1,2
Up Type=0
Dn Type=3
Dn Slope=0.005
Boundary for River Rch & Prof#=SOUTH MINERAL CR,Reach-1,3
Up Type=0
Dn Type=3
Dn Slope=0.005
Boundary for River Rch & Prof#=SOUTH MINERAL CR,Reach-1,4
Up Type=0
Dn Type=3
Dn Slope=0.005
Boundary for River Rch & Prof#=SOUTH MINERAL CR,Reach-1,5
Up Type=0
Dn Type=3
Dn Slope=0.005
Boundary for River Rch & Prof#=SOUTH MINERAL CR,Reach-1,6
Up Type=0
Dn Type=3
Dn Slope=0.005
Boundary for River Rch & Prof#=SOUTH MINERAL CR,Reach-1,7
Up Type=0
Dn Type=3
Dn Slope=0.005

--- SOUTH MINERAL CR TRIB 9 1.g01 (geometry) ---

Geom Title=Existing Conditions

River Reach=SOUTH MINERAL CR,Reach-1
Reach XY= 30
      3508722.11     10373141.64      3508767.79     10373158.48
      3508797.10     10373155.40      3508821.99     10373161.80
      3508856.92     10373179.50      3509003.41     10373228.49
      3509106.58     10373233.45      3509151.14     10373254.00
      3509238.52     10373328.32      3509307.19     10373434.08
      3509347.96     10373468.94      3509369.46     10373500.61
      3509446.09     10373563.43      3509474.41     10373577.83
      3509523.12     10373616.77      3509538.23     10373613.54
      3509569.74     10373587.95      3509713.66     10373505.28
      3509782.73     10373491.39      3509812.27     10373492.13
      3509831.91     10373500.01      3509840.74     10373516.64
      3509833.40     10373580.95      3509852.26     10373661.65
      3509843.00     10373726.46      3509835.87     10373866.77
      3509855.29     10373930.26      3509967.48     10374061.45
      3510006.99     10374079.98      3510122.11     10374101.64

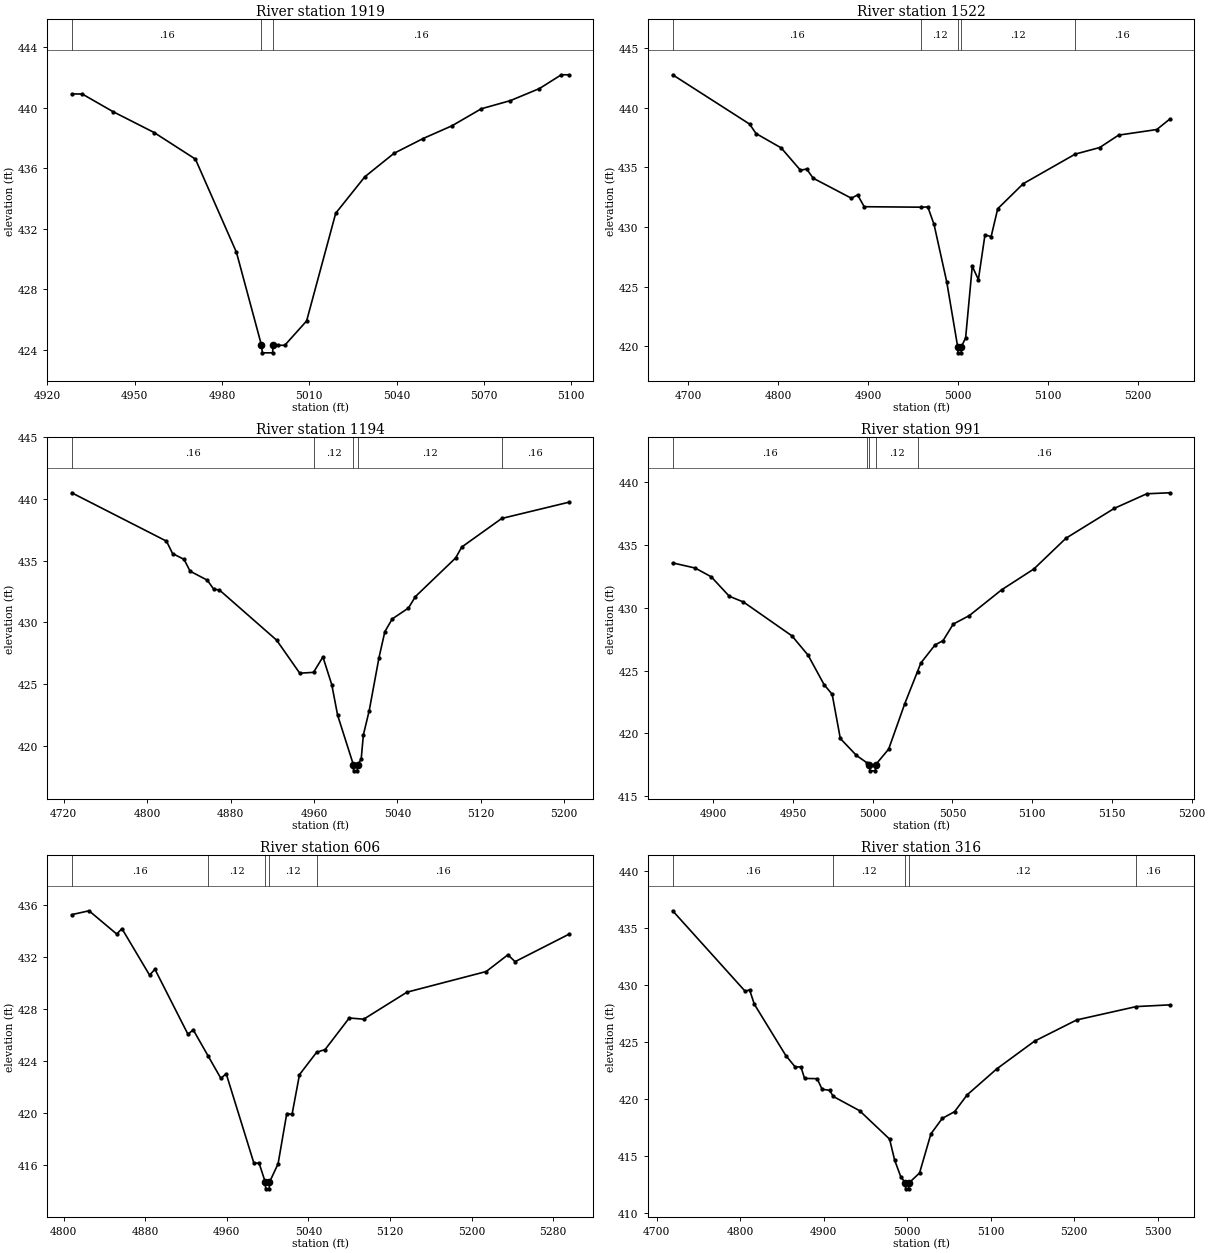
Type RM Length L Ch R = 1,1919,397,397,397
BEGIN DESCRIPTION:
SOUTH MINERAL CR TRIB 9 1 2 1
END DESCRIPTION:
XS GIS Cut Line= 3
      3508842.08     10373241.67      3508892.11     10373191.64
      3508892.11     10373091.69
#Sta/Elev= 23
  4928.4  440.92  4932.0  440.92  4942.6  439.75  4956.7  438.37  4970.9  436.61
  4985.0  430.44  4993.6  424.29  4993.9  423.79  4997.4  423.79  4997.6  424.29
  4999.1  424.29  5001.6  424.29  5009.1  425.90  5019.1  433.03  5029.1  435.44
  5039.1  436.99  5049.1  437.97  5059.1  438.82  5069.1  439.94  5079.1  440.48
  5089.1  441.28  5096.6  442.19  5099.1  442.19
#Mann=3,-1,0
  4928.4    0.16       0  4993.6    0.07       0  4997.6    0.16       0
Bank Sta=4993.6,4997.6
Exp/Cntr=0.3,0.1

Type RM Length L Ch R = 1,1522,328,328,328
BEGIN DESCRIPTION:
SOUTH MINERAL CR TRIB 9 1 2 0
END DESCRIPTION:
XS GIS Cut Line= 2
      3509013.71     10373554.10      3509418.27     10373177.66
#Sta/Elev= 30
  4682.4  442.77  4767.9  438.64  4775.2  437.84  4803.1  436.64  4824.5  434.77
  4831.4  434.87  4838.7  434.10  4881.2  432.42  4888.1  432.70  4895.4  431.71
  4958.9  431.67  4966.2  431.69  4973.1  430.22  4987.2  425.41  4999.4  419.96
  4999.7  419.46  5003.2  419.46  5003.4  419.96  5008.2  420.71  5015.6  426.72
  5022.4  425.60  5029.7  429.34  5036.6  429.21  5043.9  431.54  5072.3  433.64
  5130.1  436.12  5157.3  436.67  5178.3  437.71  5220.8  438.18  5235.0  439.04
#Mann=5,-1,0
  4682.4    0.16       0  4958.9    0.12       0  4999.4    0.07       0
  5003.4    0.12       0  5130.1    0.16       0
Bank Sta=4999.4,5003.4
Exp/Cntr=0.3,0.1

Type RM Length L Ch R = 1,1194,203,203,203
BEGIN DESCRIPTION:
SOUTH MINERAL CR TRIB 9 1 3 0
END DESCRIPTION:
XS GIS Cut Line= 2
      3509347.92     10373818.83      3509554.04     10373389.22
#Sta/Elev= 30
  4727.7  440.50  4818.6  436.58  4824.4  435.58  4835.5  435.10  4841.2  434.15
  4857.7  433.42  4863.9  432.69  4869.4  432.62  4924.2  428.56  4946.4  425.88
  4959.6  425.95  4968.6  427.20  4977.1  424.95  4982.7  422.48  4997.8  418.47
  4998.0  417.97  5001.5  417.97  5001.8  418.47  5005.3  418.91  5007.4  420.88
  5013.0  422.85  5022.4  427.15  5028.0  429.25  5035.1  430.28  5050.6  431.16
  5057.3  432.09  5095.9  435.22  5101.7  436.10  5140.1  438.42  5204.2  439.73
#Mann=5,-1,0
  4727.7    0.16       0  4959.6    0.12       0  4997.8    0.07       0
  5001.8    0.12       0  5140.1    0.16       0
Bank Sta=4997.8,5001.8
Exp/Cntr=0.3,0.1

Type RM Length L Ch R = 1,991,385,385,385
BEGIN DESCRIPTION:
SOUTH MINERAL CR TRIB 9 1 5 0
END DESCRIPTION:
XS GIS Cut Line= 2
      3509651.72     10373675.61      3509606.15     10373367.46
#Sta/Elev= 30
  4874.6  433.59  4888.7  433.18  4898.8  432.48  4910.1  430.93  4919.0  430.47
  4949.4  427.77  4959.5  426.23  4969.5  423.89  4974.6  423.11  4979.7  419.59
  4989.8  418.24  4996.4  417.65  4997.9  417.51  4998.2  417.01  5001.7  417.01
  5001.9  417.51  5010.0  418.74  5020.1  422.36  5028.1  424.93  5030.2  425.61
  5039.1  427.05  5044.1  427.39  5050.5  428.71  5060.6  429.39  5080.8  431.44
  5101.0  433.10  5121.2  435.56  5151.5  437.94  5171.8  439.10  5186.1  439.18
#Mann=5,-1,0
  4874.6    0.16       0  4996.4    0.12       0  4997.9    0.07       0
  5001.9    0.12       0  5028.1    0.16       0
Bank Sta=4997.9,5001.9
Exp/Cntr=0.3,0.1

Type RM Length L Ch R = 1,606,290,290,290
BEGIN DESCRIPTION:
SOUTH MINERAL CR TRIB 9 1 4 0
END DESCRIPTION:
XS GIS Cut Line= 3
      3509669.10     10373721.20      3509922.99     10373640.91
      3510078.19     10373483.56
#Sta/Elev= 30
  4807.9  435.29  4824.9  435.59  4852.0  433.80  4857.2  434.21  4884.3  430.63
  4889.5  431.09  4921.9  426.08  4927.1  426.42  4941.5  424.43  4954.2  422.68
  4959.4  423.04  4986.5  416.17  4991.7  416.14  4997.8  414.67  4998.1  414.17
  5001.6  414.17  5001.8  414.67  5010.3  416.10  5018.8  419.97  5024.0  419.91
  5031.3  422.97  5048.1  424.69  5056.4  424.90  5080.1  427.33  5094.3  427.24
  5136.7  429.32  5214.4  430.91  5235.7  432.20  5242.7  431.67  5295.2  433.77
#Mann=5,-1,0
  4807.9    0.16       0  4941.5    0.12       0  4997.8    0.07       0
  5001.8    0.12       0  5048.1    0.16       0
Bank Sta=4997.8,5001.8
Exp/Cntr=0.3,0.1

Type RM Length L Ch R = 1,316,216,216,216
BEGIN DESCRIPTION:
Mapping XS 4b9bf30c
END DESCRIPTION:
XS GIS Cut Line= 4
      3509646.63     10374086.56      3509792.45     10374054.01
      3509926.56     10373856.09      3509956.51     10373651.66
#Sta/Elev= 30
  4719.3  436.48  4806.2  429.42  4811.4  429.55  4817.1  428.29  4854.8  423.79
  4866.0  422.79  4872.9  422.79  4877.3  421.78  4892.3  421.76  4898.3  420.83
  4907.2  420.74  4911.7  420.20  4943.2  418.95  4979.1  416.46  4985.1  414.63
  4992.4  413.18  4998.1  412.60  4998.3  412.10  5001.8  412.10  5002.1  412.60
  5015.0  413.49  5028.6  416.92  5042.1  418.27  5057.0  418.87  5072.0  420.34
  5107.5  422.62  5152.7  425.05  5203.2  426.91  5274.5  428.08  5314.4  428.23
#Mann=5,-1,0
  4719.3    0.16       0  4911.7    0.12       0  4998.1    0.07       0
  5002.1    0.12       0  5274.5    0.16       0
Bank Sta=4998.1,5002.1
Exp/Cntr=0.3,0.1

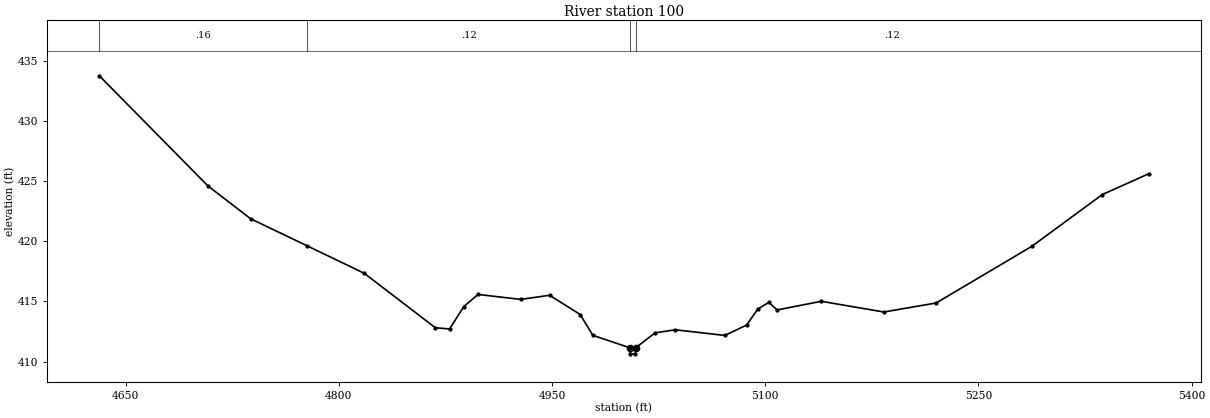
Type RM Length L Ch R = 1,100,0,0,0
BEGIN DESCRIPTION:
SOUTH MINERAL CR TRIB 9 1 1 0
END DESCRIPTION:
XS GIS Cut Line= 4
      3509685.69     10374134.74      3509992.97     10374136.04
      3510086.72     10373977.19      3509970.85     10373759.77
#Sta/Elev= 30
  4631.5  433.77  4707.9  424.61  4737.9  421.88  4777.6  419.63  4817.9  417.34
  4867.9  412.81  4877.9  412.71  4887.9  414.57  4897.9  415.58  4927.9  415.17
  4948.3  415.51  4969.8  413.91  4978.7  412.18  5004.8  411.14  5005.1  410.64
  5008.6  410.64  5008.8  411.14  5022.5  412.39  5036.8  412.64  5071.6  412.17
  5086.8  413.03  5094.8  414.37  5102.5  414.92  5108.3  414.29  5139.4  415.01
  5183.4  414.12  5220.2  414.87  5287.5  419.58  5337.1  423.89  5369.6  425.61
#Mann=4,-1,0
  4631.5    0.16       0  4777.6    0.12       0  5004.8    0.07       0
  5008.8    0.12       0
Bank Sta=5004.8,5008.8
Exp/Cntr=0.3,0.1

Chan Stop Cuts=-1