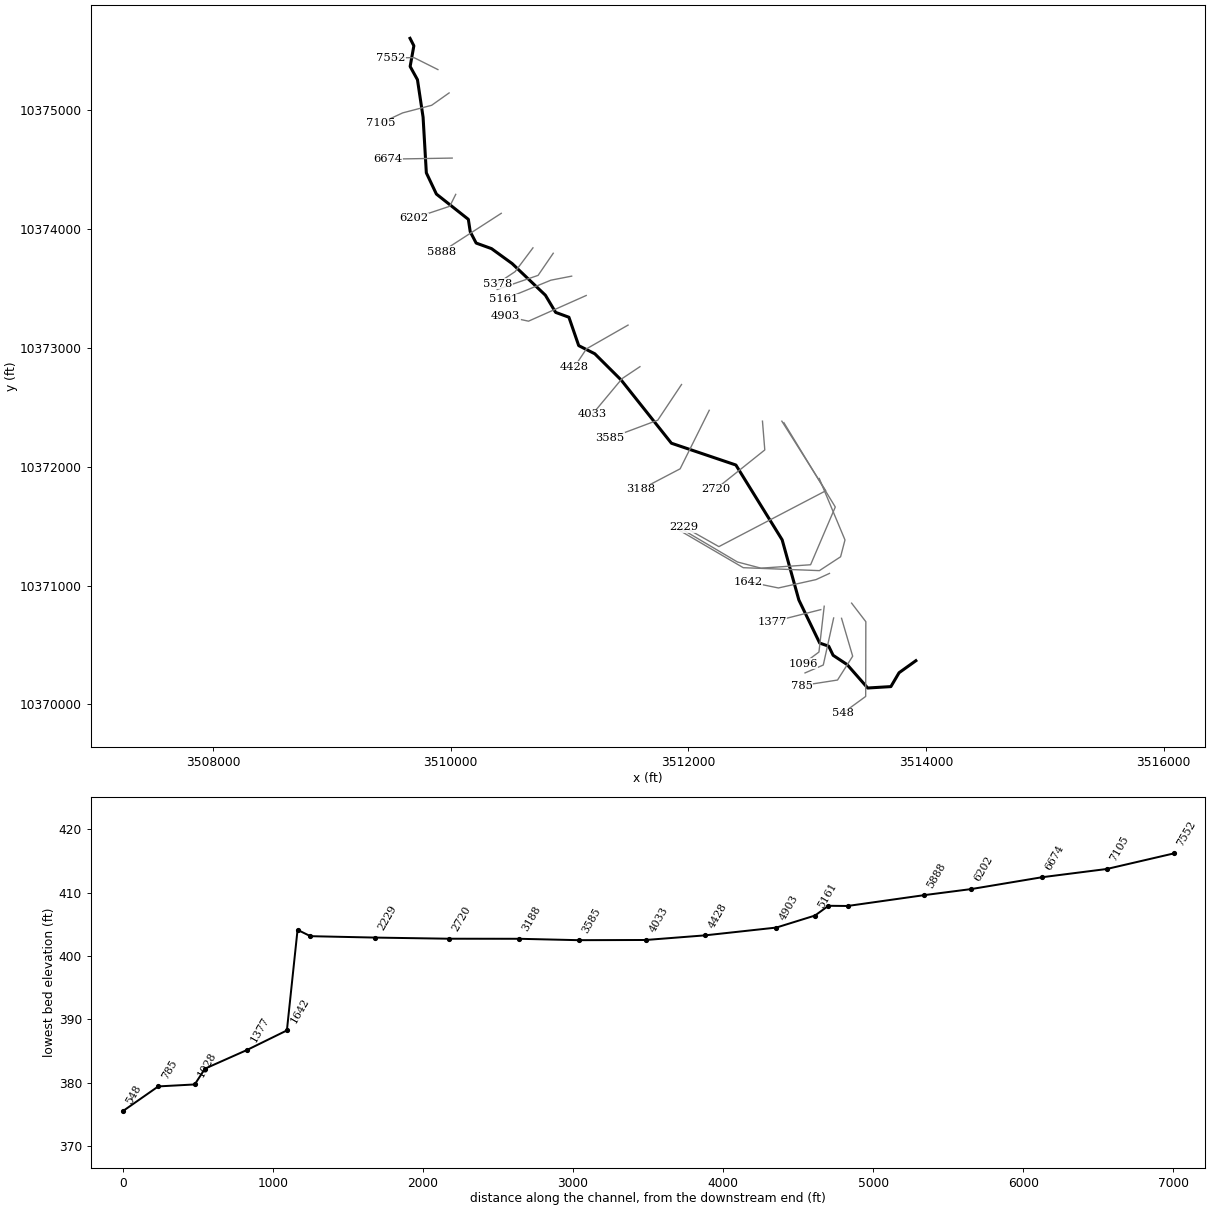
--- SOUTH MINERAL CR TRIB 9.prj (project) ---

Proj Title=SOUTH MINERAL CR TRIB 9 Base Level Engineering
Current Plan=p01
Default Exp/Contr=0.3,0.1
English Units
Geom File=g01
Flow File=f01
Plan File=p01
Y Axis Title=Elevation
X Axis Title(PF)=Main Channel Distance
X Axis Title(XS)=Station
BEGIN DESCRIPTION:
SOUTH MINERAL CR TRIB 9
END DESCRIPTION:
DSS Export Rating Curves= 0
DSS Export Rating Curve Sorted= 0
DSS Export Volume Flow Curves= 0
DXF OffsetX= 0
DXF OffsetY= 0
DXF ScaleX= 1
DXF ScaleY= 10

--- SOUTH MINERAL CR TRIB 9.p01 (plan) ---

Plan Title=Multiple Run
Short Identifier=Multiple
Geom File=g01
Flow File=f01
Subcritical Flow
K Sum by GR= 0
Std Step Tol= 0.01
Critical Tol= 0.01
Num of Std Step Trials= 20
Max Error Tol= 0.3
Flow Tol Ratio= 0.001
Split Flow NTrial= 30
Split Flow Tol= 0.02
Split Flow Ratio= 0.02
Log Output Level= 0
Friction Slope Method= 1
Unsteady Friction Slope Method= 2
Unsteady Bridges Friction Slope Method= 1
Parabolic Critical Depth
Global Vel Dist=  1 , 1 , 1
Global Log Level= 0
CheckData=True
Encroach Param= -1, 0, 0, 0
BEGIN DESCRIPTION:
Multiple Run
END DESCRIPTION:

--- SOUTH MINERAL CR TRIB 9.f01 (steady flow) ---

Flow Title=Multiple
Number of Profiles=7
Profile Names=10-year,25-year,50-year,1pct_min,100-year,1pct_plu,500-year
River Rch & RM= SOUTH MINERAL CR,Reach-1,7552
     811    1118    1373    1233    1667    2255    2450
River Rch & RM= SOUTH MINERAL CR,Reach-1,5888
    1735    2495    3149    2897    3918    5299    6055
Boundary for River Rch & Prof#=SOUTH MINERAL CR,Reach-1,1
Up Type=0
Dn Type=3
Dn Slope=0.005
Boundary for River Rch & Prof#=SOUTH MINERAL CR,Reach-1,2
Up Type=0
Dn Type=3
Dn Slope=0.005
Boundary for River Rch & Prof#=SOUTH MINERAL CR,Reach-1,3
Up Type=0
Dn Type=3
Dn Slope=0.005
Boundary for River Rch & Prof#=SOUTH MINERAL CR,Reach-1,4
Up Type=0
Dn Type=3
Dn Slope=0.005
Boundary for River Rch & Prof#=SOUTH MINERAL CR,Reach-1,5
Up Type=0
Dn Type=3
Dn Slope=0.005
Boundary for River Rch & Prof#=SOUTH MINERAL CR,Reach-1,6
Up Type=0
Dn Type=3
Dn Slope=0.005
Boundary for River Rch & Prof#=SOUTH MINERAL CR,Reach-1,7
Up Type=0
Dn Type=3
Dn Slope=0.005

--- SOUTH MINERAL CR TRIB 9.g01 (geometry) ---

Geom Title=Existing Conditions
Program Version=4.10

River Reach=SOUTH MINERAL CR,Reach-1
Reach XY= 30
      3509657.65     10375604.52      3509689.94     10375541.75
      3509658.63     10375367.86      3509720.18     10375256.41
      3509767.52     10374940.78      3509794.87     10374472.79
       3509879.5     10374294.21      3510148.36     10374081.47
       3510164.2      10373977.5      3510214.19     10373881.77
      3510343.32     10373835.11      3510516.93     10373709.24
      3510796.62     10373443.11      3510882.78     10373298.69
       3510994.6     10373257.76      3511076.99     10373018.96
      3511212.38     10372950.34      3511434.07     10372729.68
      3511856.99     10372197.74      3512399.52     10372014.36
      3512788.85      10371384.8       3512929.4     10370878.44
      3513104.76     10370516.09      3513180.71     10370489.61
      3513217.61     10370413.23       3513336.1     10370334.67
      3513508.65     10370137.99      3513703.75     10370149.89
       3513772.5     10370266.56      3513913.97     10370367.74

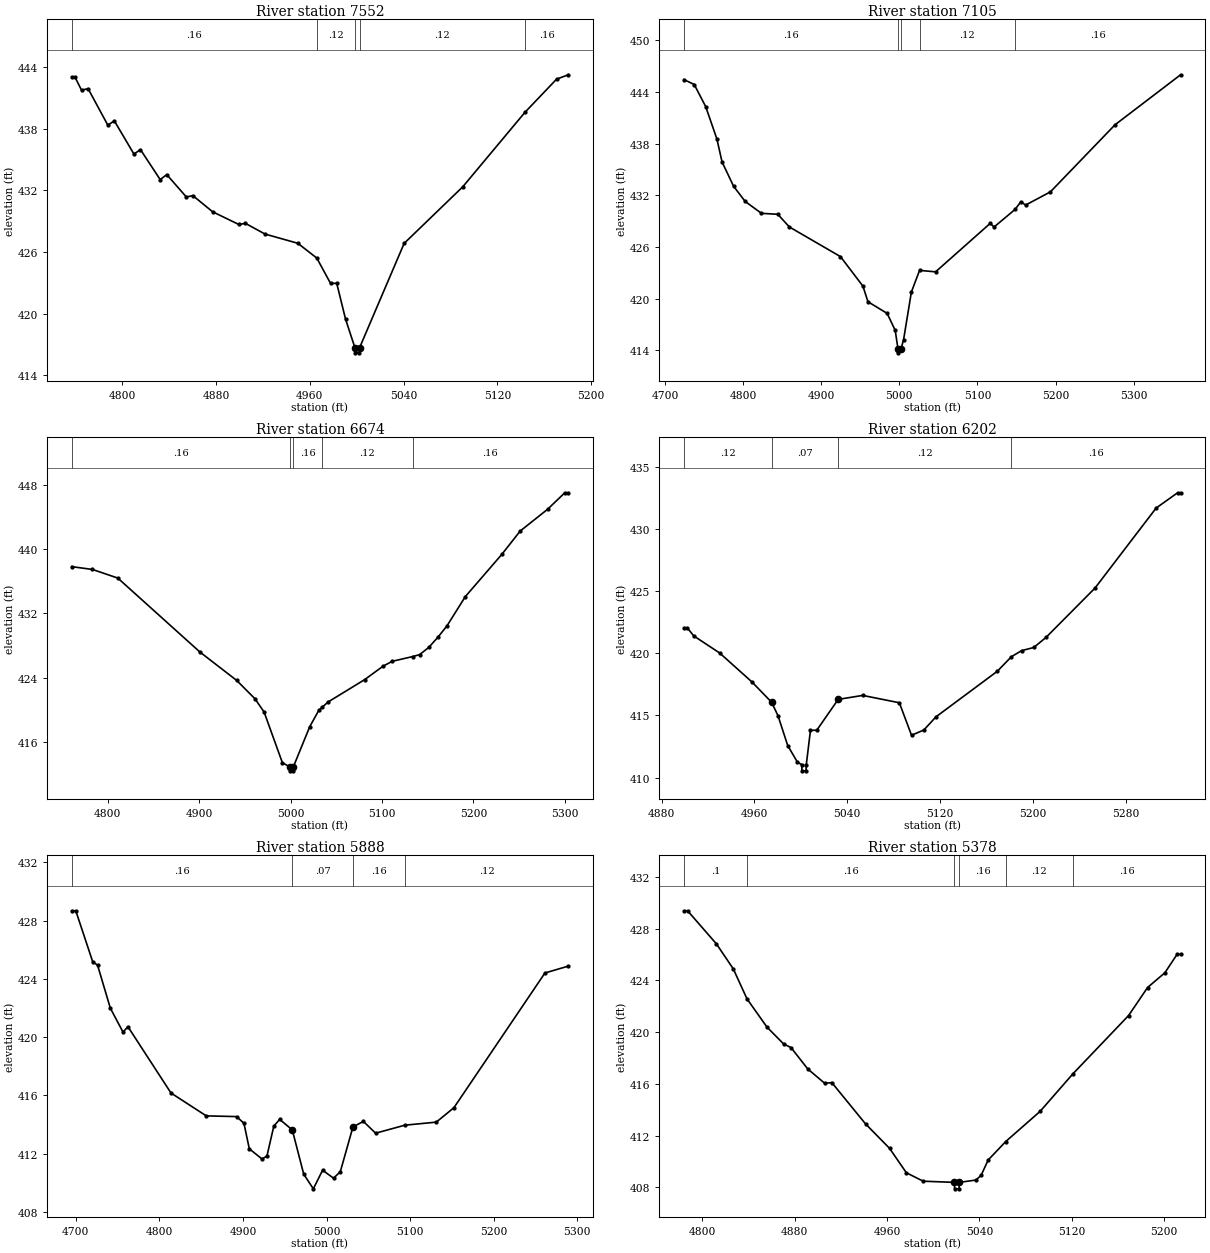
Type RM Length L Ch R = 1 ,7552    ,447,447,447
BEGIN DESCRIPTION:
SOUTH MINERAL CR TRIB 9 3 0
END DESCRIPTION:
XS GIS Cut Line= 3
      3509892.12     10375341.64      3509692.11     10375441.64
      3509492.13     10375441.64
#Sta/Elev= 30
  4756.9  443.04  4759.7  443.04  4765.3  441.76  4770.9  441.91  4787.7  438.36
  4793.3  438.77    4810  435.54  4815.6  435.97  4832.4  433.05    4838  433.54
  4854.7  431.36  4860.3  431.49  4877.1  429.92  4899.5  428.68  4905.1  428.79
  4921.8  427.75  4949.8  426.85    4966  425.41  4977.7  422.95    4983  422.95
  4990.5  419.47  4998.5  416.68  4998.8  416.18  5002.3  416.18  5002.5  416.68
  5040.5  426.84  5090.5  432.35  5143.6  439.61  5170.5  442.83  5180.5  443.26
#Mann= 5 ,-1 , 0
  4756.9     .16       0    4966     .12       0  4998.5     .07       0
  5002.5     .12       0  5143.6     .16       0
Bank Sta=4998.5,5002.5
XS Rating Curve= 0 ,0
Exp/Cntr=0.3,0.1

Type RM Length L Ch R = 1 ,7105    ,431,431,431
BEGIN DESCRIPTION:
SOUTH MINERAL CR TRIB 9 2 0
END DESCRIPTION:
XS GIS Cut Line= 4
      3509986.43     10375145.14      3509839.32     10375040.99
      3509595.84     10374977.19      3509410.98     10374891.27
#Sta/Elev= 30
  4724.3  445.43  4737.4  444.86  4752.1  442.29  4766.4  438.54    4773  435.88
  4787.8  433.05  4802.6  431.29  4823.5  429.91  4844.4   429.8  4859.2  428.33
  4924.6  424.89  4953.4  421.46  4959.8  419.65  4984.4   418.3  4994.7  416.33
  4998.2  414.22  4998.5  413.72  5002.2  414.22  5005.4  415.23  5015.4  420.77
  5025.9  423.29  5046.4  423.12  5116.3  428.74  5121.4  428.33  5148.1  430.36
  5155.6  431.25  5161.7  430.87  5193.4   432.4  5276.2  440.19  5360.1  445.99
#Mann= 5 ,-1 , 0
  4724.3     .16       0  4998.2     .07       0  5002.2     .16       0
  5025.9     .12       0  5148.1     .16       0
Bank Sta=4998.2,5002.2
XS Rating Curve= 0 ,0
Exp/Cntr=0.3,0.1

Type RM Length L Ch R = 1 ,6674    ,472,472,472
BEGIN DESCRIPTION:
SOUTH MINERAL CR TRIB 9 16 0
END DESCRIPTION:
XS GIS Cut Line= 2
      3510012.46     10374596.98      3509469.54     10374587.86
#Sta/Elev= 30
  4760.7   437.8  4783.4  437.45  4811.1  436.38  4901.1  427.17  4941.1  423.66
  4961.1  421.38  4971.1  419.73  4991.1  413.43  4999.1  412.92  4999.3  412.42
  5002.8  412.42  5003.1  412.92  5021.1  417.93  5031.1  419.97  5034.7  420.33
  5041.1  420.98  5081.1  423.76  5101.1  425.42  5111.1  426.03  5133.4  426.62
  5141.1  426.86  5151.1  427.75  5161.1  429.02  5171.1  430.44  5191.1  434.07
  5231.1  439.33  5251.1  442.22  5281.1  444.93  5299.9  446.98  5303.7  446.98
#Mann= 5 ,-1 , 0
  4760.7     .16       0  4999.1     .07       0  5003.1     .16       0
  5034.7     .12       0  5133.4     .16       0
Bank Sta=4999.1,5003.1
XS Rating Curve= 0 ,0
Exp/Cntr=0.3,0.1

Type RM Length L Ch R = 1 ,6202    ,314,314,314
BEGIN DESCRIPTION:
SOUTH MINERAL CR TRIB 9 15 0
END DESCRIPTION:
XS GIS Cut Line= 3
       3510042.1     10374291.63      3509992.11     10374191.64
      3509692.13     10374091.65
#Sta/Elev= 30
  4899.4  422.04  4902.2  422.04  4907.8  421.39  4930.1  420.02  4958.1  417.68
  4974.9  416.06  4980.4  414.98  4988.8  412.58  4997.2  411.24  5000.8  411.05
  5001.1  410.55  5004.6  410.55  5004.8  411.05  5008.4  413.81  5013.8  413.81
  5032.3  416.29  5053.4  416.61    5085  416.02  5095.5  413.41  5106.1  413.83
  5116.6  414.89  5169.3  418.54  5181.6  419.72  5190.4  420.21  5200.9  420.46
  5211.5  421.28  5253.6  425.23  5306.3  431.66  5324.8  432.89  5327.4  432.89
#Mann= 4 ,-1 , 0
  4899.4     .12       0  4974.9     .07       0  5032.3     .12       0
  5181.6     .16       0
Bank Sta=4974.9,5032.3
XS Rating Curve= 0 ,0
Exp/Cntr=0.3,0.1

Type RM Length L Ch R = 1 ,5888    ,510,510,510
BEGIN DESCRIPTION:
SOUTH MINERAL CR TRIB 9 14 0
END DESCRIPTION:
XS GIS Cut Line= 2
      3510425.27     10374132.14       3509926.2     10373809.83
#Sta/Elev= 30
  4695.1  428.68    4700  428.68  4720.2  425.19  4726.1  424.94  4741.3     422
  4756.5  420.35  4762.4  420.72  4813.9  416.17  4856.1   414.6  4892.4  414.55
  4901.2  414.09  4907.6  412.34  4922.8  411.64  4928.7  411.84  4936.9  413.89
  4943.9  414.36    4959  413.64  4972.7   410.6  4984.2  409.59  4995.3  410.87
  5008.4  410.32  5016.5  410.77  5031.6  413.84  5044.1  414.22  5058.7  413.41
  5093.7  413.96  5131.3  414.17  5152.4  415.16  5261.3  424.41  5289.2  424.88
#Mann= 4 ,-1 , 0
  4695.1     .16       0    4959     .07       0  5031.6     .16       0
  5093.7     .12       0
Bank Sta=4959,5031.6
XS Rating Curve= 0 ,0
Exp/Cntr=0.3,0.1

Type RM Length L Ch R = 1 ,5378    ,128,128,128
BEGIN DESCRIPTION:
SOUTH MINERAL CR TRIB 9 11 1
END DESCRIPTION:
XS GIS Cut Line= 3
       3510692.1     10373841.63      3510542.11     10373641.64
      3510392.08     10373541.62
#Sta/Elev= 30
  4784.1  429.37  4787.2  429.37  4812.2  426.81  4826.8  424.88  4838.7  422.56
    4856  420.38  4870.5  419.07  4876.8   418.8  4891.4  417.14    4906  416.04
  4912.2  416.09  4941.4   412.9  4962.2  411.01  4976.8  409.12  4991.4  408.47
  5018.3  408.38  5018.6  407.88  5022.4  407.88  5022.7  408.38  5037.1  408.56
  5041.6  408.93  5047.6   410.1  5062.8  411.53  5092.7  413.87  5120.9  416.75
  5169.3  421.27  5185.8  423.44  5200.8  424.58  5211.4  426.01  5214.4  426.01
#Mann= 6 ,-1 , 0
  4784.1      .1       0  4838.7     .16       0  5018.3     .07       0
  5022.7     .16       0  5062.8     .12       0  5120.9     .16       0
Bank Sta=5018.3,5022.7
XS Rating Curve= 0 ,0
Exp/Cntr=0.3,0.1

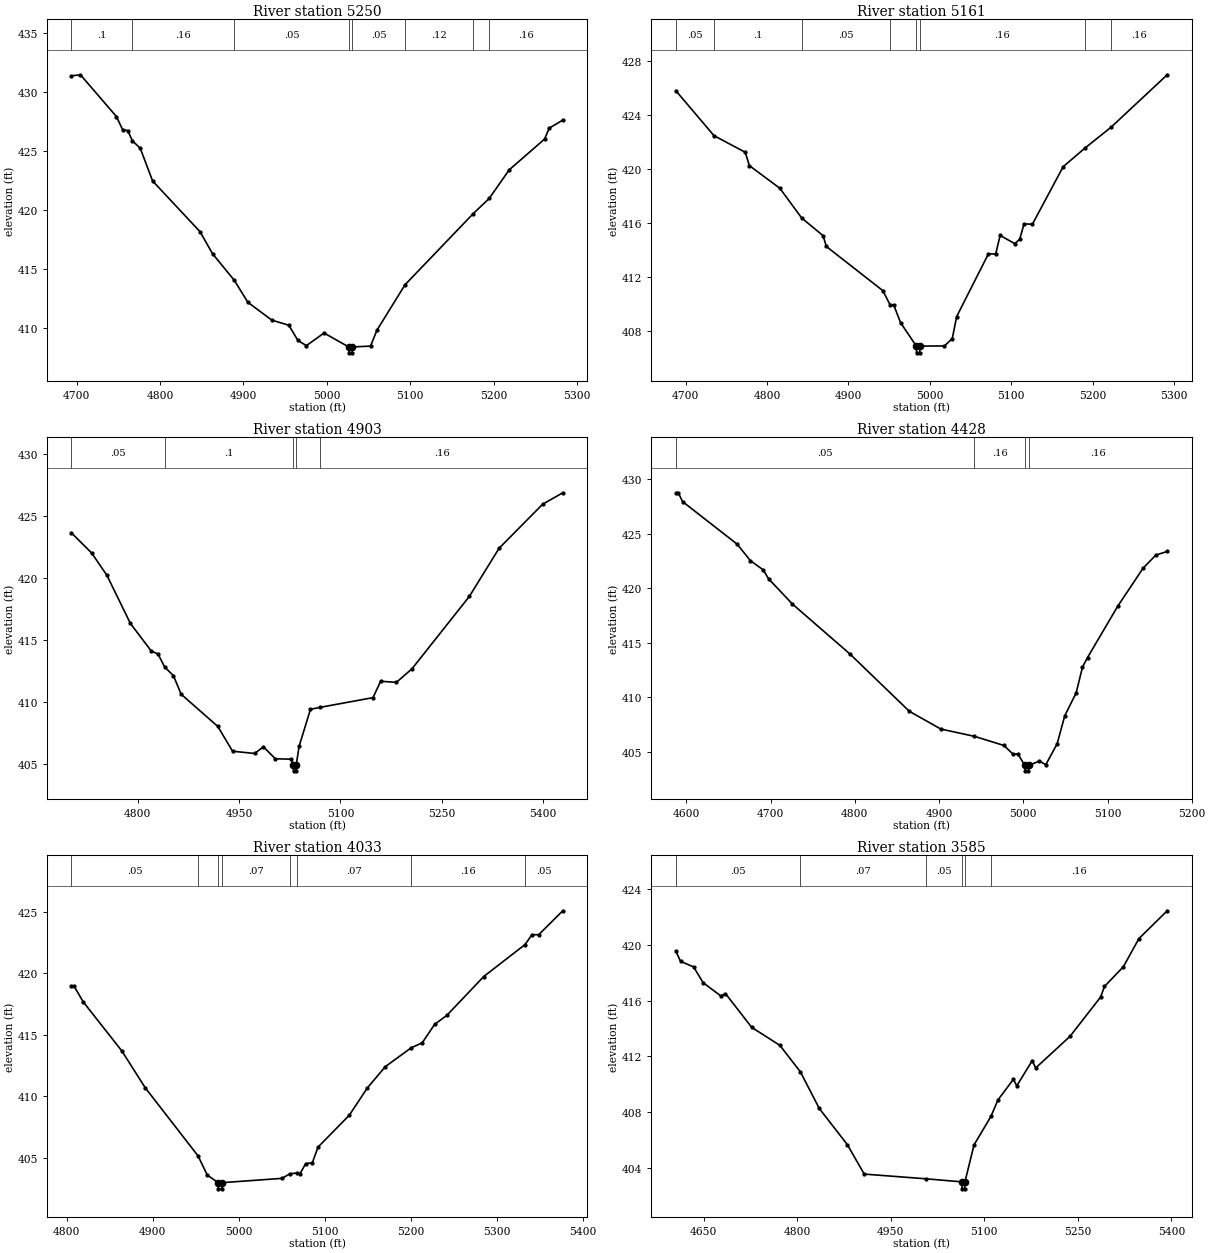
Type RM Length L Ch R = 1 ,5250    ,89,89,89
BEGIN DESCRIPTION:
SOUTH MINERAL CR TRIB 9 13 0
END DESCRIPTION:
XS GIS Cut Line= 3
      3510862.74     10373796.17      3510735.16       10373610.
       3510391.4     10373491.51
#Sta/Elev= 30
  4693.7  431.38  4704.5  431.47  4747.7  427.93  4755.2   426.8  4761.3  426.74
  4766.8  425.88  4776.2  425.25  4791.1  422.47    4848  418.17  4862.9  416.31
  4889.1  414.05  4905.3  412.19  4934.1  410.68  4954.4  410.25  4965.3  408.96
  4975.5  408.52  4996.7  409.59  5026.2  408.41  5026.5  407.91  5030.3  407.91
  5030.6  408.41  5052.4  408.48  5060.1  409.83  5093.8  413.68  5175.5   419.7
  5194.7  420.99  5218.8  423.42  5261.1  426.02  5266.8  426.95    5283  427.63
#Mann= 8 ,-1 , 0
  4693.7      .1       0  4766.8     .16       0  4889.1     .05       0
  5026.2     .04       0  5030.6     .05       0  5093.8     .12       0
  5175.5     .05       0  5194.7     .16       0
Bank Sta=5026.2,5030.6
XS Rating Curve= 0 ,0
Exp/Cntr=0.3,0.1

Type RM Length L Ch R = 1 ,5161    ,258,258,258
BEGIN DESCRIPTION:
SOUTH MINERAL CR TRIB 9 12 0
END DESCRIPTION:
XS GIS Cut Line= 3
      3511017.69     10373603.49      3510843.23     10373569.64
      3510448.71     10373408.18
#Sta/Elev= 30
  4687.8  425.79  4734.7  422.46  4773.1  421.23  4778.2  420.24  4815.7  418.56
  4842.5  416.36  4868.8  415.05  4872.8  414.25  4942.4  410.97  4950.9  409.95
  4955.6  409.92    4964  408.61  4983.4  406.87  4983.7  406.37  4987.5  406.37
  4987.8  406.87    5018  406.88  5027.6  407.43    5033  409.06    5072   413.7
    5081   413.7  5086.4  415.07  5104.4  414.46  5110.4  414.78  5115.8  415.92
  5126.1   415.9  5163.9  420.16  5190.7  421.54  5222.7  423.08  5291.8  426.97
#Mann= 8 ,-1 , 0
  4687.8     .05       0  4734.7      .1       0  4842.5     .05       0
  4950.9     .16       0  4983.4     .07       0  4987.8     .16       0
  5190.7     .05       0  5222.7     .16       0
Bank Sta=4983.4,4987.8
XS Rating Curve= 0 ,0
Exp/Cntr=0.3,0.1

Type RM Length L Ch R = 1 ,4903    ,475,475,475
BEGIN DESCRIPTION:
SOUTH MINERAL CR TRIB 9 11 0
END DESCRIPTION:
XS GIS Cut Line= 3
      3511140.07     10373440.72      3510654.43     10373224.58
      3510462.98     10373266.26
#Sta/Elev= 30
  4701.7  423.65  4731.6  422.03  4754.2  420.23    4789  416.35  4819.9  414.13
    4830  413.88  4839.6  412.85  4852.7  412.14  4864.2  410.64  4918.4  408.05
  4940.3  406.05  4973.1  405.87  4985.9  406.41  5003.7  405.44  5026.9  405.41
  5030.1  404.97  5030.5  404.47  5034.3  404.47  5034.6  404.97  5038.8  406.45
  5055.6  409.43  5070.2  409.59  5148.2  410.37  5159.5  411.69  5182.8   411.6
    5206   412.7  5290.9  418.53  5334.9  422.41  5399.4  425.96  5429.2  426.88
#Mann= 5 ,-1 , 0
  4701.7     .05       0  4839.6      .1       0  5030.1     .07       0
  5034.6      .1       0  5070.2     .16       0
Bank Sta=5030.1,5034.6
XS Rating Curve= 0 ,0
Exp/Cntr=0.3,0.1

Type RM Length L Ch R = 1 ,4428    ,395,395,395
BEGIN DESCRIPTION:
SOUTH MINERAL CR TRIB 9 29 0
END DESCRIPTION:
XS GIS Cut Line= 3
      3511492.15     10373191.67      3511142.11     10372991.64
      3511042.13     10372841.67
#Sta/Elev= 30
  4587.5  428.78  4590.4  428.78  4595.5  427.97  4660.3  424.06  4676.1  422.54
  4691.2   421.7  4697.7  420.87  4725.8  418.57  4794.1  413.98  4864.7  408.71
  4902.1  407.08  4941.9  406.41    4977  405.57  4987.8  404.78  4993.7  404.78
  5001.8  403.74  5002.2  403.24  5006.2  403.24  5006.5  403.74  5019.2  404.14
  5026.7   403.8  5040.2  405.72  5049.2  408.29  5062.8   410.4  5070.3  412.77
  5076.3  413.65  5112.3  418.38  5142.4  421.87  5157.4  423.06  5170.9  423.39
#Mann= 4 ,-1 , 0
  4587.5     .05       0  4941.9     .16       0  5001.8     .07       0
  5006.5     .16       0
Bank Sta=5001.8,5006.5
XS Rating Curve= 0 ,0
Exp/Cntr=0.3,0.1

Type RM Length L Ch R = 1 ,4033    ,448,448,448
BEGIN DESCRIPTION:
SOUTH MINERAL CR TRIB 9 19 0
END DESCRIPTION:
XS GIS Cut Line= 3
      3511592.13     10372841.66      3511442.11     10372741.64
      3511192.12     10372441.65
#Sta/Elev= 30
  4805.5  418.96  4808.5  418.96    4819  417.69  4864.1  413.69  4891.2  410.71
  4952.6  405.18  4963.3  403.63  4975.9  403.01  4976.3  402.51  4980.3  402.51
  4980.6  403.01  5050.2  403.36  5059.2  403.73  5068.1   403.8  5071.1  403.75
  5077.6  404.55  5085.4  404.63  5091.9  405.89  5128.3  408.48  5149.2  410.69
    5170  412.41  5200.2  413.95    5213  414.35  5227.3  415.84  5241.6  416.58
  5284.5  419.73  5332.4  422.32  5340.5  423.12  5348.3  423.12  5376.3  425.06
#Mann= 8 ,-1 , 0
  4805.5     .05       0  4952.6     .07       0  4975.9     .07       0
  4980.6     .07       0  5059.2     .16       0  5068.1     .07       0
  5200.2     .16       0  5332.4     .05       0
Bank Sta=4975.9,4980.6
XS Rating Curve= 0 ,0
Exp/Cntr=0.3,0.1

Type RM Length L Ch R = 1 ,3585    ,397,397,397
BEGIN DESCRIPTION:
SOUTH MINERAL CR TRIB 9 9 0
END DESCRIPTION:
XS GIS Cut Line= 3
      3511942.12     10372691.66      3511742.11     10372391.64
      3511342.08     10372241.63
#Sta/Elev= 30
  4605.6  419.57  4613.1  418.83  4634.2  418.42  4649.2   417.3  4677.7  416.34
  4685.2  416.51  4727.3  414.08  4772.4  412.79  4805.4  410.88  4835.5  408.26
  4880.5  405.66  4907.6  403.54  5007.1   403.2  5064.4  402.98  5064.7  402.48
  5068.7  402.48  5069.1  402.98  5083.7  405.64  5111.1  407.71  5121.9  408.86
  5146.8  410.35  5152.2  409.88  5177.1   411.7  5182.4  411.16  5237.6  413.44
  5286.6  416.26  5292.8  417.02  5323.1  418.44    5348  420.46  5393.4  422.46
#Mann= 6 ,-1 , 0
  4605.6     .05       0  4805.4     .07       0  5007.1     .05       0
  5064.4     .07       0  5069.1     .05       0  5111.1     .16       0
Bank Sta=5064.4,5069.1
XS Rating Curve= 0 ,0
Exp/Cntr=0.3,0.1

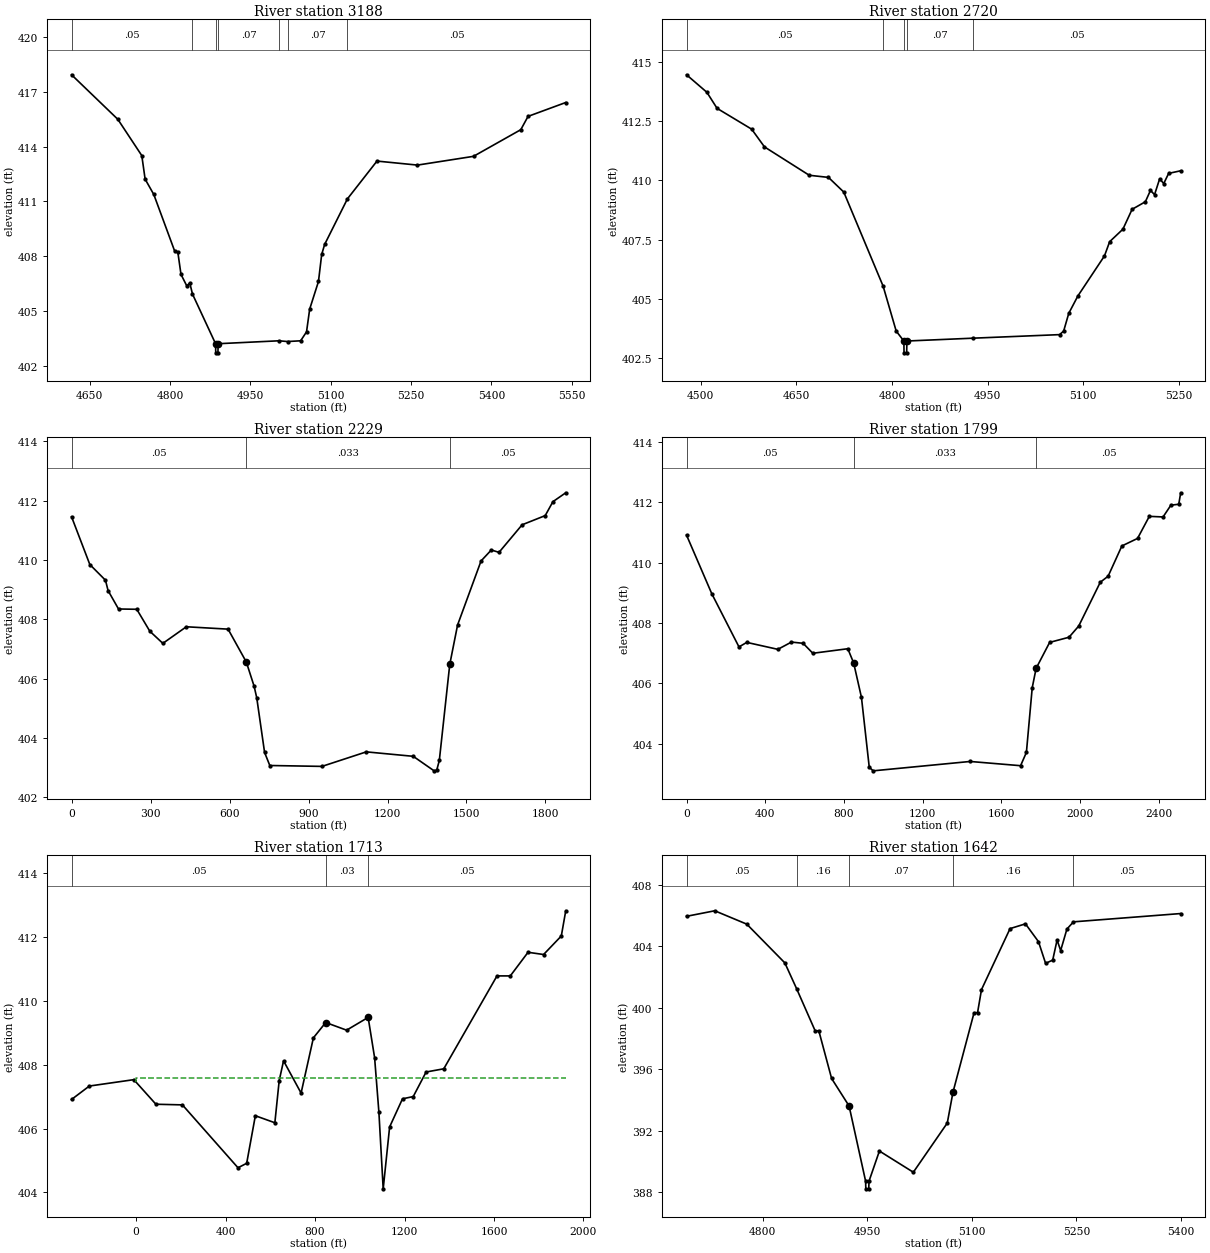
Type RM Length L Ch R = 1 ,3188    ,468,468,468
BEGIN DESCRIPTION:
SOUTH MINERAL CR TRIB 9 8 0
END DESCRIPTION:
XS GIS Cut Line= 3
      3512175.28     10372474.63      3511930.47      10371982.4
      3511599.72     10371809.21
#Sta/Elev= 30
  4615.9  417.94  4702.3   415.5  4747.1  413.51  4753.3  412.22  4769.5  411.38
  4808.7  408.26  4814.3  408.24  4820.3     407  4831.1  406.37  4836.7  406.53
  4841.8  405.92  4884.9   403.2  4885.2   402.7  4889.3   402.7  4889.7   403.2
  5003.1  403.36  5019.3  403.32  5043.8  403.36  5054.8  403.85  5060.7   405.1
  5077.1  406.61  5083.1  408.09  5088.6  408.64  5131.2  411.14  5186.4  413.21
    5262  412.99  5366.7  413.47    5455  414.93  5468.6  415.66    5539  416.42
#Mann= 7 ,-1 , 0
  4615.9     .05       0  4841.8     .07       0  4884.9     .07       0
  4889.7     .07       0  5003.1     .05       0  5019.3     .07       0
  5131.2     .05       0
Bank Sta=4884.9,4889.7
XS Rating Curve= 0 ,0
Exp/Cntr=0.3,0.1

Type RM Length L Ch R = 1 ,2720    ,491,491,491
BEGIN DESCRIPTION:
Mapping XS a7470c96
END DESCRIPTION:
XS GIS Cut Line= 3
      3512623.18      10372383.4      3512642.71     10372141.25
      3512227.35     10371809.22
#Sta/Elev= 30
    4478  414.47  4509.9  413.73  4525.9  413.05  4580.1  412.17  4600.2  411.42
  4670.4  410.22  4700.5  410.13  4724.5  409.51  4786.2  405.53  4806.7  403.63
  4818.7  403.21    4819  402.71  4823.1  402.71  4823.5  403.21  4927.1  403.33
  5062.8  403.48  5069.2  403.63  5077.2  404.38  5091.6  405.12  5133.2  406.81
  5141.3  407.41  5162.1  407.94  5176.5  408.78  5197.3   409.1  5205.3  409.58
  5211.7   409.4  5219.7  410.07  5226.1  409.87  5233.8   410.3  5252.7  410.41
#Mann= 5 ,-1 , 0
    4478     .05       0  4786.2     .07       0  4818.7    .033       0
  4823.5     .07       0  4927.1     .05       0
Bank Sta=4818.7,4823.5
XS Rating Curve= 0 ,0
Exp/Cntr=0.3,0.1

Type RM Length L Ch R = 1 ,2229    ,430,430,430
BEGIN DESCRIPTION:
Mapping XS f121b497
END DESCRIPTION:
XS GIS Cut Line= 4
     3512786.209    10372383.318      3513155.75     10371797.51
      3512256.56     10371327.75     3511962.309    10371493.198
#Sta/Elev= 30
       0  411.46   69.35  409.85  128.79  409.32   138.7  408.97  178.33  408.35
  247.68  408.34  297.21   407.6  346.75  407.19  435.91  407.75  594.43  407.67
  663.78  406.56   693.5  405.74  703.41  405.35  733.12  403.51  752.93  403.07
  951.04  403.04 1119.43  403.53 1297.73  403.38 1376.98  402.89 1386.88  402.91
 1396.79  403.24 1436.41  406.48 1466.13  407.81 1555.28  409.97 1594.27  410.34
 1623.51  410.26 1711.25  411.19 1798.98   411.5 1828.23  411.97 1876.97  412.27
#Mann= 3 , 0 , 0
       0     .05       0  663.78    .033       0 1436.41     .05       0
Bank Sta=663.78,1436.41
XS Rating Curve= 0 ,0
Exp/Cntr=0.3,0.1

Type RM Length L Ch R = 1 ,1799    ,86,86,86
BEGIN DESCRIPTION:
SOUTH MINERAL CR TRIB 9 7 0
END DESCRIPTION:
XS GIS Cut Line= 6
     3512803.454    10372370.482     3513235.889    10371661.058
      3513028.13      10371175.1      3512610.16     10371146.46
      3512412.29     10371198.53     3511949.989    10371471.638
#Sta/Elev= 30
       0  410.91   128.4  408.97  266.68  407.21  306.19  407.36  464.23  407.13
  533.37  407.37  592.63  407.33  642.01     407  819.86  407.15  849.59  406.68
  889.22  405.54  928.85  403.23  948.66  403.11  1441.6  403.42 1698.11  403.28
  1727.7  403.72  1757.3  405.86 1777.03   406.5 1845.88  407.36 1944.24  407.53
 1993.55   407.9 2103.24  409.35 2143.12  409.55 2212.92  410.55 2292.69   410.8
 2352.52  411.53 2422.32  411.51 2462.21   411.9 2502.09  411.93 2512.06  412.31
#Mann= 3 , 0 , 0
       0     .05       0  849.59    .033       0 1777.03     .05       0
Bank Sta=849.59,1777.03
XS Rating Curve= 0 ,0
Exp/Cntr=0.3,0.1

Type RM Length L Ch R = 1 ,1713    ,71,71,71
BEGIN DESCRIPTION:
SOUTH MINERAL CR TRIB 9 6 0
END DESCRIPTION:
XS GIS Cut Line= 6
     3513101.197     10371900.65     3513317.509    10371383.858
     3513280.549    10371242.178      3513102.35     10371125.63
      3512461.69     10371150.37     3511925.349    10371463.938
#Sta/Elev= 30
 -288.22  406.91 -208.71  407.33   -9.94  407.53    88.8  406.76  207.21  406.74
  455.72  404.77  494.49  404.91  533.25   406.4  620.46  406.18  639.84   407.5
  659.33  408.12  737.69  407.11   792.7  408.84  847.81  409.32  941.18  409.08
 1037.42  409.48 1066.29  408.22  1085.5  406.51 1104.69  404.11 1133.46  406.05
    1191  406.93 1238.96     407  1296.5  407.77 1375.48  407.87 1613.38  410.78
 1672.86  410.78 1752.16  411.52 1821.55  411.45 1900.85  412.03 1920.67  412.82
#Mann= 3 , 0 , 0
 -288.22     .05       0  847.81     .03       0 1037.42     .05       0
#XS Ineff= 2 , 0
       0   -49.7  407.58               0
Permanent Ineff=
       F       F
Bank Sta=847.81,1037.42
XS Rating Curve= 0 ,0
Exp/Cntr=0.3,0.1

Type RM Length L Ch R = 1 ,1642    ,265,265,265
BEGIN DESCRIPTION:
SOUTH MINERAL CR TRIB 9 3 1
END DESCRIPTION:
XS GIS Cut Line= 4
      3513186.94     10371102.17       3513073.7      10371050.1
      3512757.29     10370979.79      3512502.12     10371031.87
#Sta/Elev= 30
  4690.5  405.96    4731  406.32    4777  405.45  4831.6  402.93  4848.5  401.25
  4875.2   398.5  4880.3  398.52  4898.7  395.41  4923.8  393.62  4947.5  388.73
  4947.8  388.23    4952  388.23  4952.4  388.73  4967.3  390.69    5016  389.31
  5064.7  392.51  5072.9  394.52  5103.1  399.68  5108.2   399.7  5113.8  401.19
  5154.8  405.16  5176.9  405.47  5195.6  404.31  5205.8   402.9    5216  403.11
  5222.3  404.42  5227.4  403.73  5236.4  405.13  5245.8   405.6  5399.7  406.14
#Mann= 5 ,-1 , 0
  4690.5     .05       0  4848.5     .16       0  4923.8     .07       0
  5072.9     .16       0  5245.8     .05       0
Bank Sta=4923.8,5072.9
XS Rating Curve= 0 ,0
Exp/Cntr=0.3,0.1

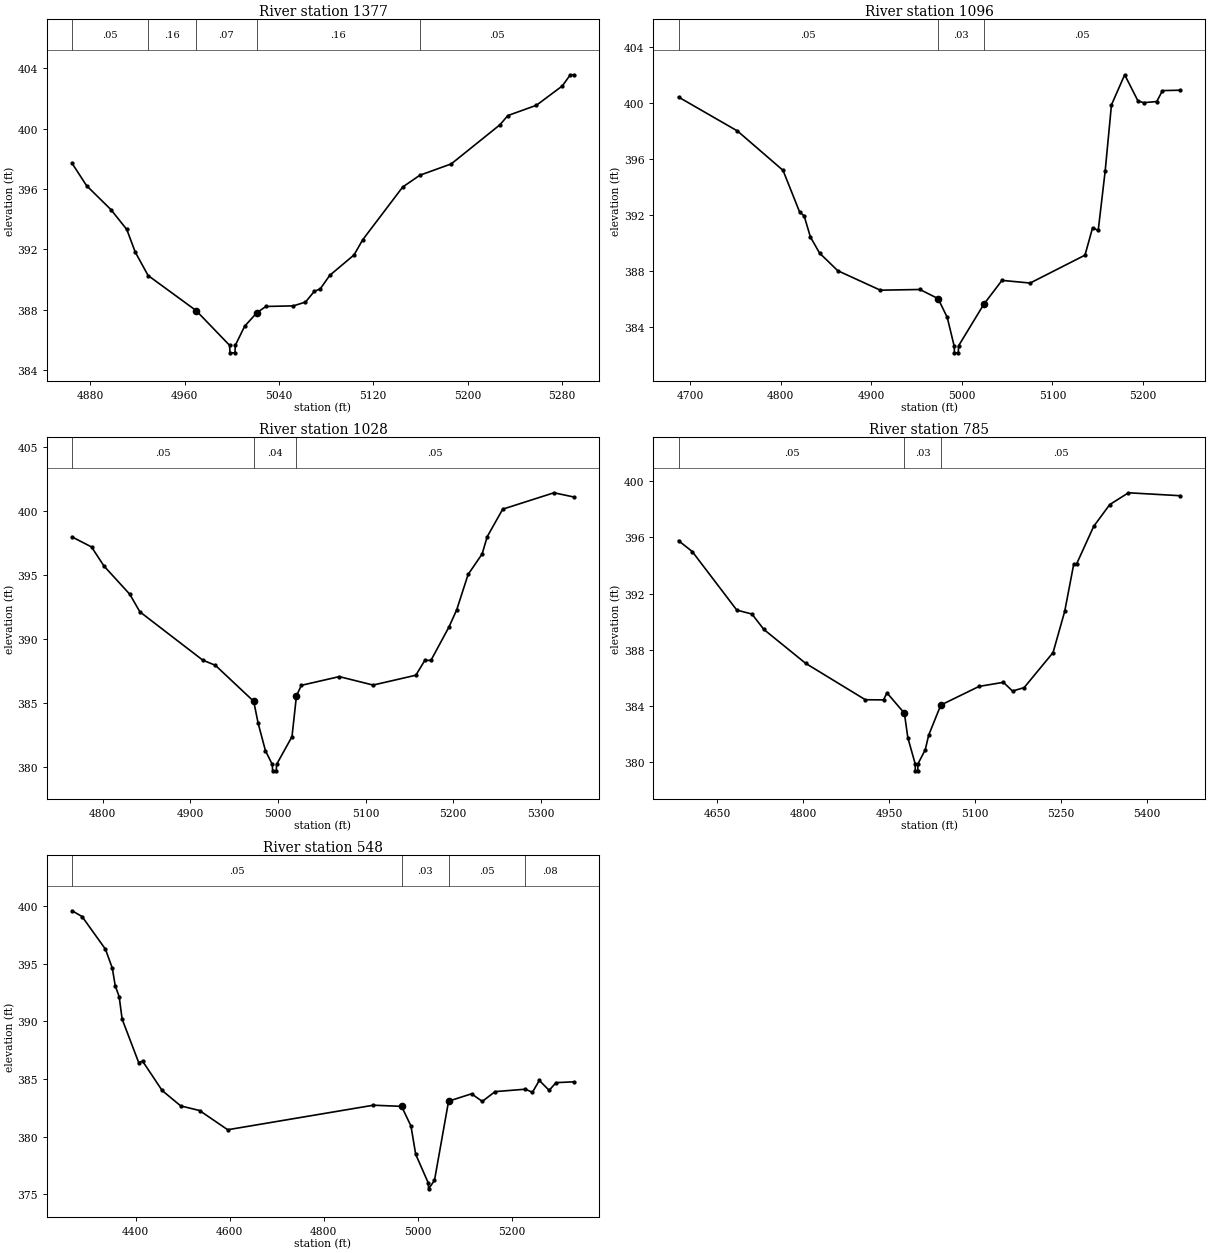
Type RM Length L Ch R = 1 ,1377    ,281,281,281
BEGIN DESCRIPTION:
SOUTH MINERAL CR TRIB 9 5 0
END DESCRIPTION:
XS GIS Cut Line= 2
      3513114.06      10370797.5      3512701.31     10370693.33
#Sta/Elev= 30
  4864.5   397.7  4876.8  396.22  4897.5  394.63  4910.9  393.32  4918.1  391.82
    4929  390.27  4969.7  387.95  4998.1  385.65  4998.5  385.15  5002.7  385.15
    5003  385.65  5010.9  386.91  5021.2   387.8  5028.9  388.22  5052.2  388.26
  5062.5  388.51    5070  389.22  5075.1  389.39  5083.1  390.28  5103.7  391.63
    5111  392.63    5145  396.13  5159.6  396.91  5186.2  397.66  5227.5  400.25
  5234.2  400.86  5258.4  401.54  5280.4  402.82  5287.2  403.56  5290.2  403.56
#Mann= 5 ,-1 , 0
  4864.5     .05       0    4929     .16       0  4969.7     .07       0
  5021.2     .16       0  5159.6     .05       0
Bank Sta=4969.7,5021.2
XS Rating Curve= 0 ,0
Exp/Cntr=0.3,0.1

Type RM Length L Ch R = 1 ,1096    ,68,68,68
BEGIN DESCRIPTION:
SOUTH MINERAL CR TRIB 9 4 0
END DESCRIPTION:
XS GIS Cut Line= 3
      3513142.72     10370826.19      3513098.44     10370440.73
      3512965.73     10370341.52
#Sta/Elev= 30
  4687.4  400.44  4752.4  398.02  4802.7  395.21    4821  392.24    4826  391.96
  4832.9  390.46    4843  389.31  4863.1  388.05  4910.1  386.66  4953.7  386.71
  4973.8  386.06  4983.9  384.72  4991.5  382.69  4991.9  382.19  4996.1  382.19
  4996.4  382.69  5024.2  385.65  5044.3  387.36  5075.4  387.17  5135.9  389.16
  5144.3  391.12  5150.5  390.92  5158.2  395.18  5165.1  399.88  5179.7  402.03
  5194.3  400.17  5200.5  400.04  5215.1  400.12  5221.4   400.9  5241.1  400.93
#Mann= 3 , 0 , 0
  4687.4     .05       0  4973.8     .03       0  5024.2     .05       0
Bank Sta=4973.8,5024.2
XS Rating Curve= 0 ,0
Exp/Cntr=0.3,0.1

Type RM Length L Ch R = 1 ,1028    ,243,243,243
BEGIN DESCRIPTION:
SOUTH MINERAL CR TRIB 9 2 1
END DESCRIPTION:
XS GIS Cut Line= 3
      3513222.14      10370727.2       3513134.9     10370331.35
      3512981.28     10370264.96
#Sta/Elev= 30
  4764.9  397.97  4787.1  397.19  4801.3   395.7  4830.8  393.49  4842.3  392.12
    4914  388.35  4928.5  387.94  4972.2  385.13  4977.3  383.41  4985.6  381.27
  4993.4   380.2  4993.8   379.7    4998   379.7  4998.3   380.2  5015.9  382.37
    5021  385.56  5026.6  386.38  5069.9  387.06  5108.5   386.4  5157.3  387.17
  5167.5  388.33  5174.5  388.33  5195.1  390.94  5203.9  392.28  5216.9  395.04
  5232.9  396.64  5238.7  397.99  5256.4  400.14  5314.9  401.42  5337.6  401.09
#Mann= 3 , 0 , 0
  4764.9     .05       0  4972.2     .04       0    5021     .05       0
Bank Sta=4972.2,5021
XS Rating Curve= 0 ,0
Exp/Cntr=0.3,0.1

Type RM Length L Ch R = 1 ,785     ,237,237,237
BEGIN DESCRIPTION:
SOUTH MINERAL CR TRIB 9 3 2
END DESCRIPTION:
XS GIS Cut Line= 4
      3513288.55     10370724.55      3513382.29     10370405.57
      3513254.69     10370205.05      3512952.65     10370158.18
#Sta/Elev= 30
  4582.5  395.77  4606.4     395  4684.2  390.83  4710.6  390.55  4731.5  389.45
  4804.4  387.04  4908.6  384.45  4940.3  384.44  4946.3  384.94  4976.7  383.49
  4982.7  381.75  4995.5  379.89  4995.8  379.39    5000  379.39  5000.4  379.89
  5013.1  380.89  5019.1  381.93  5040.2  384.07  5107.1   385.4  5149.5  385.69
  5165.4  385.07  5185.6  385.31  5236.2  387.81  5256.5  390.74  5272.2  394.09
  5277.2  394.11  5307.1  396.79  5335.1  398.34  5367.8  399.18  5458.3  398.97
#Mann= 3 , 0 , 0
  4582.5     .05       0  4976.7     .03       0  5040.2     .05       0
Bank Sta=4976.7,5040.2
XS Rating Curve= 0 ,0
Exp/Cntr=0.3,0.1

Type RM Length L Ch R = 1 ,548     ,0,0,0
BEGIN DESCRIPTION:
SOUTH MINERAL CR TRIB 9 1 0
END DESCRIPTION:
XS GIS Cut Line= 4
      3513373.16     10370852.21      3513492.97     10370695.94
      3513491.67     10370067.03      3513296.08     10369924.55
#Sta/Elev= 30
  4264.9  399.61  4286.2  399.11    4336  396.27  4350.5  394.63  4356.8  393.09
  4365.1  392.16  4371.4  390.21  4406.7  386.43  4414.9  386.56  4456.5  384.01
  4496.1  382.67  4536.1  382.27  4596.1   380.6  4906.1  382.73  4966.1  382.63
  4986.1  380.92  4996.1  378.47    5023  375.97  5023.5  375.47  5036.1   376.2
  5066.1  383.08  5114.9  383.72  5137.9  383.06    5165  383.91  5229.4  384.12
  5244.5  383.85  5259.2  384.88  5280.1  384.02  5294.7  384.69  5332.7  384.76
#Mann= 4 ,-1 , 0
  4264.9     .05       0  4966.1     .03       0  5066.1     .05       0
  5229.4     .08       0
Bank Sta=4966.1,5066.1
XS Rating Curve= 0 ,0
Exp/Cntr=0.3,0.1

Chan Stop Cuts=-1
Use User Specified Reach Order=0
Composite Channel Slope=5