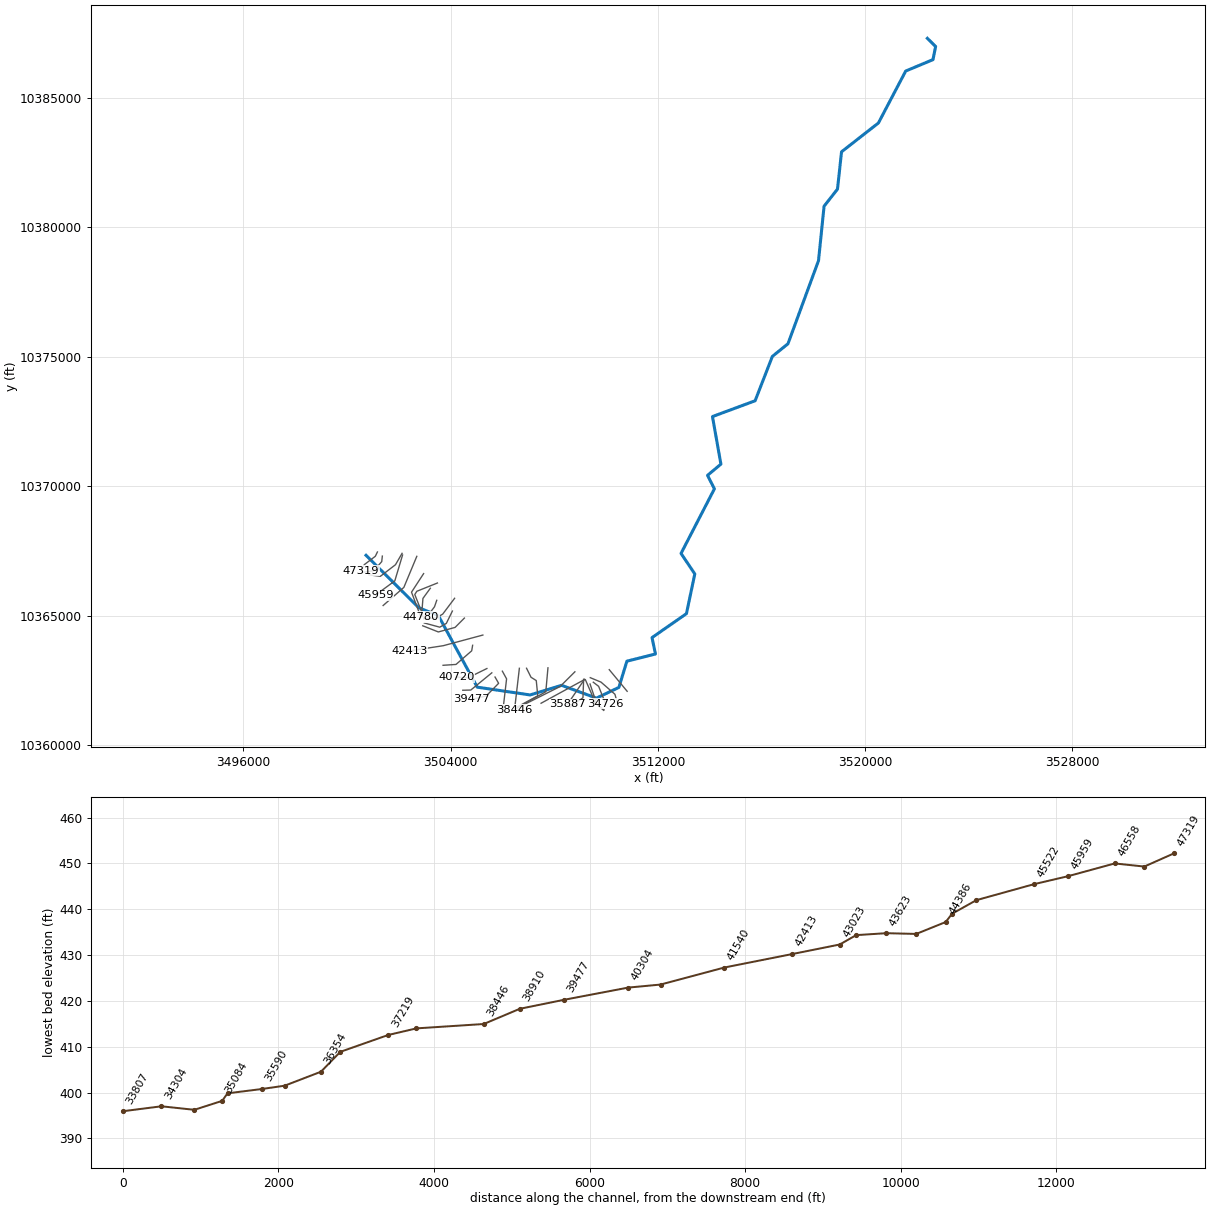
--- SOUTH MINERAL CREEK.prj (project) ---

Proj Title=SOUTH MINERAL CREEK Base Level Engineering
Current Plan=p01
Default Exp/Contr=0.3,0.1
English Units
Geom File=g01
Flow File=f01
Plan File=p01
Y Axis Title=Elevation
X Axis Title(PF)=Main Channel Distance
X Axis Title(XS)=Station
BEGIN DESCRIPTION:
SOUTH MINERAL CREEK
END DESCRIPTION:
DSS Export Rating Curves= 0
DSS Export Rating Curve Sorted= 0
DSS Export Volume Flow Curves= 0
DXF OffsetX= 0
DXF OffsetY= 0
DXF ScaleX= 1
DXF ScaleY= 10

--- SOUTH MINERAL CREEK.p01 (plan) ---

Plan Title=Multiple Run
Short Identifier=Multiple
Geom File=g01
Flow File=f01
Subcritical Flow
K Sum by GR= 0
Std Step Tol= 0.01
Critical Tol= 0.01
Num of Std Step Trials= 20
Max Error Tol= 0.3
Flow Tol Ratio= 0.001
Split Flow NTrial= 30
Split Flow Tol= 0.02
Split Flow Ratio= 0.02
Log Output Level= 0
Friction Slope Method= 1
Unsteady Friction Slope Method= 2
Unsteady Bridges Friction Slope Method= 1
Parabolic Critical Depth
Global Vel Dist=  1 , 1 , 1
Global Log Level= 0
CheckData=True
Encroach Param= -1, 0, 0, 0
BEGIN DESCRIPTION:
Multiple Run
END DESCRIPTION:

--- SOUTH MINERAL CREEK.f01 (steady flow) ---

Flow Title=Multiple
Program Version=4.10
Number of Profiles= 7
Profile Names=10-year,25-year,50-year,1pct_min,100-year,1pct_plu,500-year
River Rch & RM=SOUTH MINERAL CR,Reach-1         ,47319
    1386    1966    2458    2241    3031    4100    4602
River Rch & RM=SOUTH MINERAL CR,Reach-1         ,40720
    1697    2426    3051    2794    3779    5111    5790
River Rch & RM=SOUTH MINERAL CR,Reach-1         ,37582
    2182    3160    4007    3698    5001    6763    7781
River Rch & RM=SOUTH MINERAL CR,Reach-1         ,36603
    2485    3623    4613    4274    5780    7817    9066
River Rch & RM=SOUTH MINERAL CR,Reach-1         ,35153
    3336    4906    6284    5850    7912   10700   12529
River Rch & RM=SOUTH MINERAL CR,Reach-1         ,28744
    4021    5954    7662    7162    9685   13098   15463
River Rch & RM=SOUTH MINERAL CR,Reach-1         ,26730
    4848    7220    9325    8743   11824   15991   18995
River Rch & RM=SOUTH MINERAL CR,Reach-1         ,23107
    5060    7550    9764    9165   12395   16763   19959
River Rch & RM=SOUTH MINERAL CR,Reach-1         ,22237
    5677    8485   10986   10321   13957   18876   22507
River Rch & RM=SOUTH MINERAL CR,Reach-1         ,17700
    6074    9099   11800   11101   15012   20302   24277
River Rch & RM=SOUTH MINERAL CR,Reach-1         ,16733
    6233    9324   12081   11352   15352   20761   24766
River Rch & RM=SOUTH MINERAL CR,Reach-1         ,13512
    6426    9622   12474   11728   15861   21450   25615
River Rch & RM=SOUTH MINERAL CR,Reach-1         ,13035
    6426    9622   12474   11728   15861   21450   25615
River Rch & RM=SOUTH MINERAL CR,Reach-1         ,11711
    6611    9871   12772   11981   16203   21913   26050
River Rch & RM=SOUTH MINERAL CR,Reach-1         ,4141
    7069   10573   13695   12859   17390   23519   28009
River Rch & RM=SOUTH MINERAL CR,Reach-1         ,3262
    7069   10573   13695   12859   17390   23519   28009
River Rch & RM=SOUTH MINERAL CR,Reach-1         ,2150
    7183   10740   13910   13057   17658   23881   28425
River Rch & RM=SOUTH MINERAL CR,Reach-1         ,75
    7183   10740   13910   13057   17658   23881   28425
Boundary for River Rch & Prof#=SOUTH MINERAL CR,Reach-1         , 1
Up Type= 0
Dn Type= 1
Dn Known WS=346.97
Boundary for River Rch & Prof#=SOUTH MINERAL CR,Reach-1         , 2
Up Type= 0
Dn Type= 1
Dn Known WS=348.2
Boundary for River Rch & Prof#=SOUTH MINERAL CR,Reach-1         , 3
Up Type= 0
Dn Type= 1
Dn Known WS=349.13
Boundary for River Rch & Prof#=SOUTH MINERAL CR,Reach-1         , 4
Up Type= 0
Dn Type= 1
Dn Known WS=348.88
Boundary for River Rch & Prof#=SOUTH MINERAL CR,Reach-1         , 5
Up Type= 0
Dn Type= 1
Dn Known WS=350.11
Boundary for River Rch & Prof#=SOUTH MINERAL CR,Reach-1         , 6
Up Type= 0
Dn Type= 1
Dn Known WS=351.58
Boundary for River Rch & Prof#=SOUTH MINERAL CR,Reach-1         , 7
Up Type= 0
Dn Type= 1
Dn Known WS=352.54
DSS Import GetInterval= 0
DSS Import GetPeak= 0
DSS Import FillOption= 0

--- SOUTH MINERAL CREEK.g01 (geometry) ---

Geom Title=Existing Conditions
Program Version=4.10

River Reach=SOUTH MINERAL CR,Reach-1
Reach XY= 30
      3500732.11     10367331.64      3502763.55     10365309.29
      3503527.13       10364997.      3505025.83     10362236.96
      3507067.19     10361936.74      3508279.19     10362308.65
      3509628.15     10361814.43      3510492.73     10362227.62
      3510801.76     10363240.65      3511904.57     10363518.48
      3511772.11     10364151.64      3513100.62     10365076.94
      3513423.58     10366611.33       3512892.3     10367403.94
      3514180.02     10369897.96      3513915.35     10370420.15
      3514431.31     10370852.26      3514105.28     10372690.42
      3515751.61     10373300.54      3516417.76     10375014.21
       3517019.5     10375502.72      3518199.06      10378712.9
      3518413.65       10380816.      3518931.35      10381476.8
      3519088.35      10382918.7      3520511.16     10384030.95
      3521565.27     10386038.48      3522617.36     10386478.53
      3522719.99     10386986.09      3522402.11     10387301.64

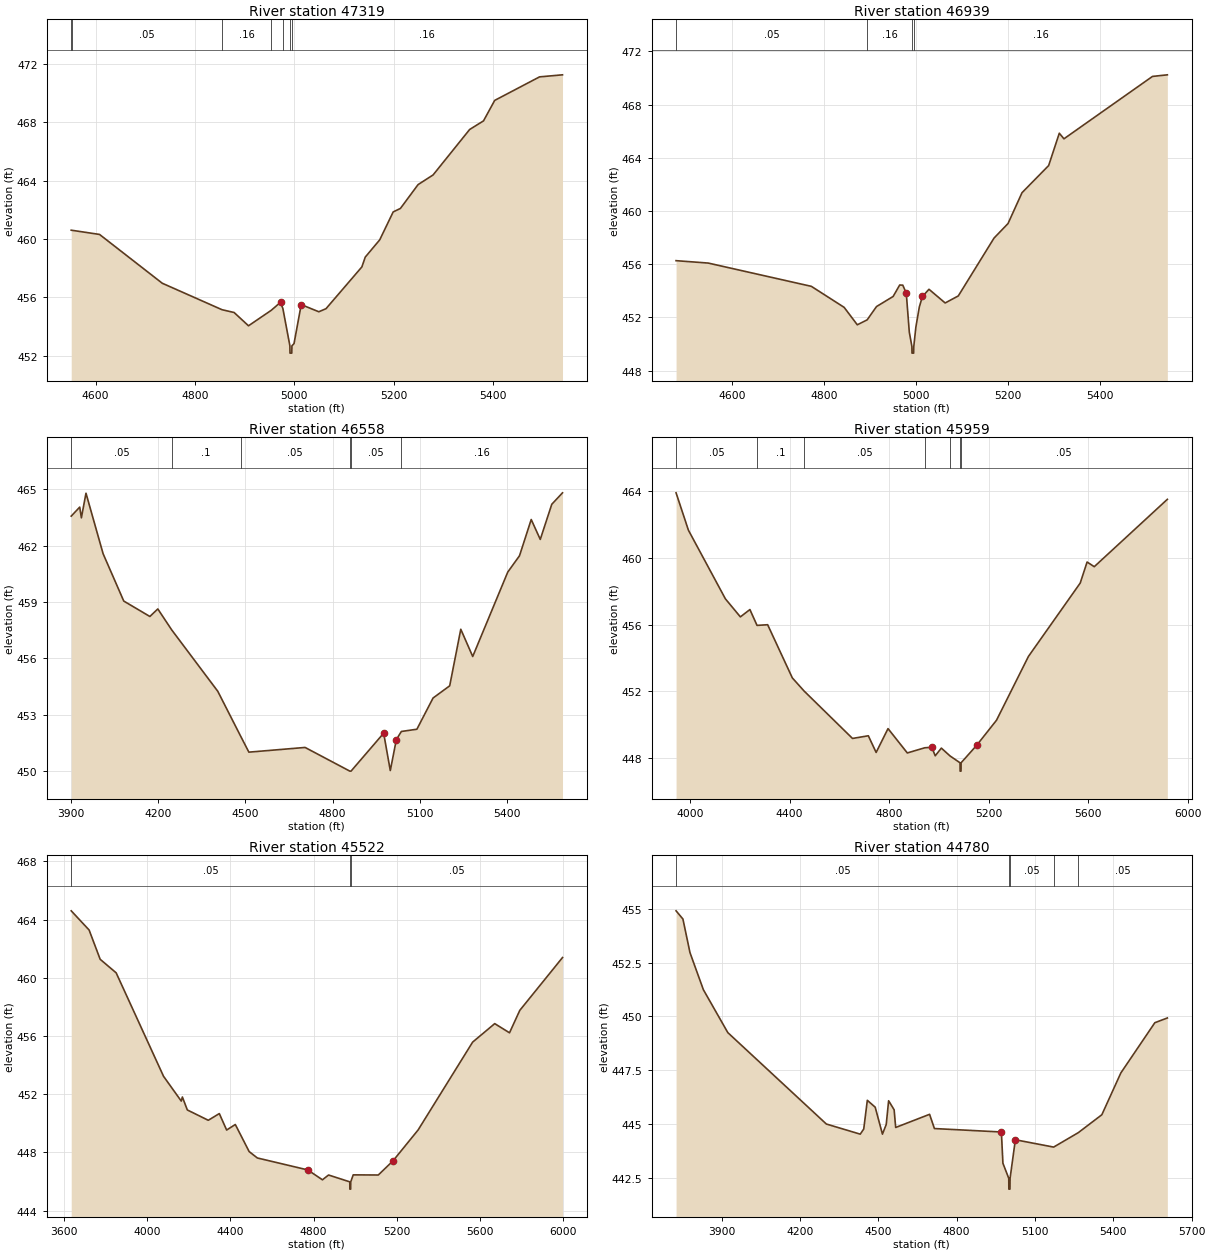
Type RM Length L Ch R = 1 ,47319   ,380,380,380
BEGIN DESCRIPTION:
SOUTH MINERAL CREEK 8 1
END DESCRIPTION:
XS GIS Cut Line= 4
      3501171.02     10367459.85      3501090.29     10367293.18
      3500665.81     10366970.27       3500540.8     10366730.65
#Sta/Elev= 30
    4551   460.6  4553.2  460.59    4608  460.31  4734.3  456.97  4854.5  455.16
  4878.8  454.97  4907.8  454.06  4953.6  455.12  4972.3  455.67    4977  455.24
  4991.1  452.69  4991.3  452.19  4994.9  452.19  4995.2  452.69  4999.4  452.84
  5013.9  455.51  5049.3  455.02  5063.8  455.23    5136  458.09  5142.8  458.76
  5171.9  459.94    5199  461.85  5213.6  462.09  5249.1  463.72  5279.3  464.38
  5352.9  467.49  5380.8  468.08  5403.3  469.48  5493.6  471.09  5539.8  471.23
#Mann= 7 ,-1 , 0
    4551     .16       0  4553.2     .05       0  4854.5     .16       0
  4953.6     .05       0    4977     .16       0  4991.1     .07       0
  4995.2     .16       0
Bank Sta=4972.3,5013.9
XS Rating Curve= 0 ,0
Exp/Cntr=0.3,0.1

Type RM Length L Ch R = 1 ,46939   ,381,381,381
BEGIN DESCRIPTION:
SOUTH MINERAL CREEK 7 0
END DESCRIPTION:
XS GIS Cut Line= 4
      3501361.12     10367300.95      3501337.69     10367087.46
       3501030.4     10366735.89       3500650.2      10366678.6
#Sta/Elev= 30
  4479.3  456.27    4549  456.09  4772.9  454.34  4844.1  452.76  4872.6  451.45
    4894  451.82  4914.3  452.82  4950.4  453.58  4964.6  454.44  4971.3  454.43
  4978.9  453.83  4985.5  450.89  4991.1  449.82  4991.3  449.32  4994.9  449.32
  4995.2  449.82  4999.7  451.27  5007.3   452.8    5014  453.58  5028.2  454.12
  5063.3  453.09  5091.8  453.62  5169.4  457.97  5199.7  459.06  5230.1  461.38
  5287.9  463.42    5311  465.85  5321.1  465.43  5513.2  470.12  5545.5  470.24
#Mann= 4 ,-1 , 0
  4479.3     .05       0    4894     .16       0  4991.1     .07       0
  4995.2     .16       0
Bank Sta=4978.9,5014
XS Rating Curve= 0 ,0
Exp/Cntr=0.3,0.1

Type RM Length L Ch R = 1 ,46558   ,599,599,599
BEGIN DESCRIPTION:
SOUTH MINERAL CREEK 65 0
END DESCRIPTION:
XS GIS Cut Line= 4
      3502124.13     10367407.75      3501868.94     10366967.66
       3501285.6     10366519.75       3500845.5     10366577.04
#Sta/Elev= 30
  3901.7  463.57  3930.9  464.05  3936.6  463.48  3952.4  464.79  4011.2  461.57
  4082.2  459.05  4171.9  458.23  4199.2  458.63  4247.2  457.51  4405.2  454.25
  4483.8  451.86  4512.1  451.01  4705.2  451.26    4859     450  4863.1     450
  4975.2  452.02    4998  450.03  5018.8  451.68    5036  452.11  5089.4  452.23
  5144.9  453.89  5202.1  454.54  5240.2  457.55  5281.2   456.1  5401.5  460.59
  5441.9  461.46  5482.2  463.39  5513.3  462.33  5552.8   464.2  5589.7  464.81
#Mann= 6 ,-1 , 0
  3901.7     .05       0  4247.2      .1       0  4483.8     .05       0
    4859     .03       0  4863.1     .05       0    5036     .16       0
Bank Sta=4975.2,5018.8
XS Rating Curve= 0 ,0
Exp/Cntr=0.3,0.1

Type RM Length L Ch R = 1 ,45959   ,437,437,437
BEGIN DESCRIPTION:
SOUTH MINERAL CREEK 64 0
END DESCRIPTION:
XS GIS Cut Line= 3
       3502142.1     10367341.62      3501842.11     10366341.64
      3501092.07     10365791.62
#Sta/Elev= 30
  3944.2  463.91  3993.8  461.67  4142.5  457.55  4202.6  456.47  4240.9  456.91
  4269.5  455.96  4312.2     456  4411.4  452.81  4458.2  452.03  4653.2  449.18
  4716.8  449.34  4748.1  448.34  4795.9  449.77  4873.4  448.31  4943.5  448.62
  4971.7  448.65  4985.6  448.14  5010.2   448.6  5045.1  448.13  5085.3  447.72
  5085.6  447.22  5089.3  447.22  5089.5  447.72  5152.2  448.77  5231.7  450.27
  5360.2   454.1  5568.2   458.5  5595.8  459.76  5624.6  459.48  5918.3  463.52
#Mann= 7 ,-1 , 0
  3944.2     .05       0  4269.5      .1       0  4458.2     .05       0
  4943.5      .1       0  5045.1     .05       0  5085.3     .07       0
  5089.5     .05       0
Bank Sta=4971.7,5152.2
XS Rating Curve= 0 ,0
Exp/Cntr=0.3,0.1

Type RM Length L Ch R = 1 ,45522   ,742,742,742
BEGIN DESCRIPTION:
SOUTH MINERAL CREEK 63 0
END DESCRIPTION:
XS GIS Cut Line= 3
      3502692.09     10367291.61      3502192.11     10366091.64
      3501392.09     10365391.63
#Sta/Elev= 30
  3634.4   464.6  3720.5  463.28  3773.6  461.27  3850.5  460.34  4078.5  453.23
  4163.6  451.53    4169  451.81  4192.8  450.92  4293.6  450.21  4346.7  450.67
  4381.9  449.54  4423.6  449.92  4490.2  448.06  4529.7  447.62  4771.9   446.8
  4842.8  446.12  4872.1  446.45  4974.3  445.98  4974.6  445.48  4978.5  445.48
  4978.8  445.98  4990.8  446.46  5111.4  446.45  5182.6  447.43  5303.1  449.55
  5565.1  455.58  5671.4  456.85  5742.5  456.22  5791.9  457.76  5997.4  461.39
#Mann= 3 ,-1 , 0
  3634.4     .05       0  4974.3     .03       0  4978.8     .05       0
Bank Sta=4771.9,5182.6
XS Rating Curve= 0 ,0
Exp/Cntr=0.3,0.1

Type RM Length L Ch R = 1 ,44780   ,313,313,313
BEGIN DESCRIPTION:
SOUTH MINERAL CREEK 61 0
END DESCRIPTION:
XS GIS Cut Line= 3
      3502954.51     10366623.84      3502487.52     10365906.86
      3502848.63     10364946.77
#Sta/Elev= 30
  3725.5   454.9  3751.7  454.52  3778.8  452.96  3830.1  451.24  3923.7  449.25
    4301  445.01  4430.8  444.54  4444.2  444.78  4457.9  446.11  4488.1  445.79
  4515.8  444.54  4530.3  444.99  4539.5  446.09  4560.6  445.67  4566.5  444.85
  4696.3  445.46  4714.9   444.8  4971.3  444.64  4977.2  443.19  4999.6  442.49
  4999.9  441.99  5004.2  441.99  5004.6  442.49  5024.8  444.28  5171.5  443.94
  5265.9  444.61    5356  445.44  5428.8  447.38    5559  449.71  5606.9  449.93
#Mann= 5 ,-1 , 0
  3725.5     .05       0  4999.6     .03       0  5004.6     .05       0
  5171.5     .08       0  5265.9     .05       0
Bank Sta=4971.3,5024.8
XS Rating Curve= 0 ,0
Exp/Cntr=0.3,0.1

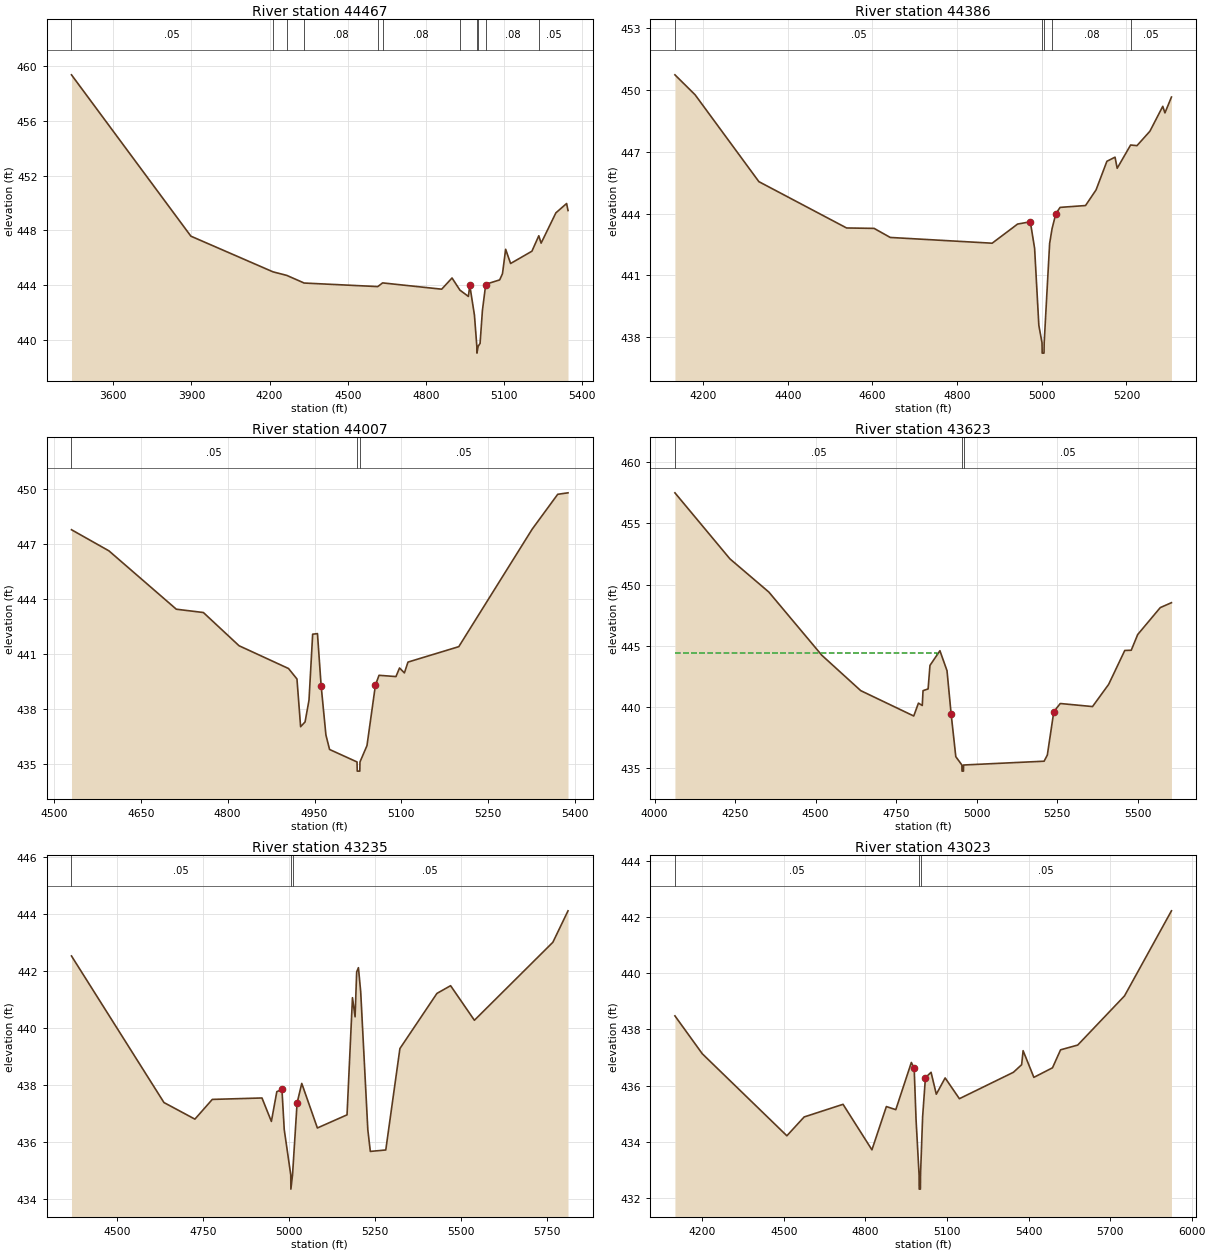
Type RM Length L Ch R = 1 ,44467   ,81,81,81
BEGIN DESCRIPTION:
SOUTH MINERAL CREEK 6 0
END DESCRIPTION:
XS GIS Cut Line= 5
      3503487.52     10366261.03      3502692.38     10365941.58
      3502614.25     10365814.85      3502857.31     10365203.74
      3502909.32     10364966.23
#Sta/Elev= 30
  3439.2  459.39  3897.7  447.58  4212.9  444.97  4265.8  444.71  4332.6  444.15
  4615.3  443.89  4633.8  444.16  4860.7   443.7  4900.4  444.52  4930.8  443.63
  4963.2  443.17  4968.6  443.98  4986.5   441.8  4995.7  439.52  4996.1  439.02
  5000.8  439.52  5008.1  439.73  5017.2  442.16  5029.6  444.02  5031.4  444.07
  5083.4  444.38  5094.2  444.84  5106.3  446.62  5125.3  445.58  5207.2  446.48
  5233.6  447.61  5242.5  447.07  5299.3  449.29  5340.4  449.97  5345.8  449.46
#Mann= 11 ,-1 , 0
  3439.2     .05       0  4212.9     .08       0  4265.8     .05       0
  4332.6     .08       0  4615.3     .05       0  4633.8     .08       0
  4930.8     .05       0  4995.7     .03       0  5000.8     .05       0
  5031.4     .08       0  5233.6     .05       0
Bank Sta=4968.6,5029.6
XS Rating Curve= 0 ,0
Exp/Cntr=0.3,0.1

Type RM Length L Ch R = 1 ,44386   ,379,379,379
BEGIN DESCRIPTION:
SOUTH MINERAL CREEK 60 0
END DESCRIPTION:
XS GIS Cut Line= 4
      3503213.19     10366057.88      3502928.49     10365665.54
      3502888.56     10365156.86      3502919.81     10364981.52
#Sta/Elev= 30
  4133.3  450.74    4181  449.77  4331.7  445.55  4538.9   443.3  4603.9  443.28
    4642  442.84  4882.8  442.56  4942.9  443.49    4973   443.6  4983.1  442.31
  4993.1  438.57  5000.6  437.72    5001  437.22  5005.3  437.22  5005.7  437.72
  5018.6  442.55  5024.3  443.26  5033.2  443.99  5043.3   444.3  5103.4  444.39
  5128.3  445.15  5153.9  446.54  5173.1  446.74  5178.2   446.2  5209.9  447.33
    5225   447.3  5255.5     448  5285.9  449.21    5291  448.89  5306.4  449.66
#Mann= 5 ,-1 , 0
  4133.3     .05       0  5000.6     .03       0  5005.7     .05       0
  5024.3     .08       0  5209.9     .05       0
Bank Sta=4973,5033.2
XS Rating Curve= 0 ,0
Exp/Cntr=0.3,0.1

Type RM Length L Ch R = 1 ,44007   ,384,384,384
BEGIN DESCRIPTION:
SOUTH MINERAL CREEK 67 0
END DESCRIPTION:
XS GIS Cut Line= 4
      3503461.48     10365592.63      3503374.67     10365342.62
      3503162.86     10365059.64      3502951.06     10364948.53
#Sta/Elev= 30
  4530.4  447.77    4595  446.62  4711.4  443.44  4758.1  443.26  4819.7  441.45
  4905.1  440.21  4919.7  439.64    4926  437.04  4933.7   437.3  4940.5  438.49
  4946.8  442.08  4955.1  442.11  4961.4  439.28  4969.7  436.59    4976   435.8
  5023.4  435.12  5023.8  434.62  5028.2  434.62  5028.5  435.12  5040.6  436.01
  5055.2  439.31  5061.4  439.84  5090.6  439.77  5096.8  440.24  5105.2  439.97
  5111.4  440.56  5199.1   441.4  5325.8   447.8  5369.9   449.7  5387.7  449.78
#Mann= 3 ,-1 , 0
  4530.4     .05       0  5023.4     .03       0  5028.5     .05       0
Bank Sta=4961.4,5055.2
XS Rating Curve= 0 ,0
Exp/Cntr=0.3,0.1

Type RM Length L Ch R = 1 ,43623   ,388,388,388
BEGIN DESCRIPTION:
SOUTH MINERAL CREEK 59 1
END DESCRIPTION:
XS GIS Cut Line= 4
      3504151.39     10365670.78      3503691.33     10365058.82
      3503430.91     10364906.91      3502957.46     10364880.19
#Sta/Elev= 30
  4063.3   457.5    4234  452.11  4354.8   449.4  4519.3  444.24  4640.1  441.35
  4804.6  439.28  4819.2  440.33  4831.1  440.14  4833.5  441.35  4849.2  441.49
    4855  443.41  4885.9  444.61  4907.9  442.98  4920.6  439.47  4935.2  435.96
  4954.1  435.28  4954.5  434.78  4958.9  434.78  4959.3  435.28  5209.3  435.59
  5219.3  436.09  5239.4  439.63  5259.4   440.3  5359.6  440.05  5409.6  441.86
  5459.7  444.63  5479.8  444.65  5499.8  445.93  5569.9  448.13  5604.6  448.53
#Mann= 3 ,-1 , 0
  4063.3     .05       0  4954.1     .03       0  4959.3     .05       0
#XS Ineff= 2 , 0
          4876.3  444.44
Permanent Ineff=
       F       F
Bank Sta=4920.6,5239.4
XS Rating Curve= 0 ,0
Exp/Cntr=0.3,0.1

Type RM Length L Ch R = 1 ,43235   ,212,212,212
BEGIN DESCRIPTION:
SOUTH MINERAL CREEK 59 0
END DESCRIPTION:
XS GIS Cut Line= 4
      3504065.64      10365177.7      3503831.27     10364700.26
      3503577.79     10364554.43      3502980.66     10364717.13
#Sta/Elev= 30
  4367.5  442.52  4636.3  437.39  4726.2  436.81  4776.8   437.5  4921.2  437.55
  4948.5  436.73  4964.3  437.77  4979.2  437.85  4985.9  436.44  5004.8  434.86
  5005.2  434.36    5010  434.86  5023.2  437.37  5036.8  438.06  5082.2   436.5
  5168.4  436.96  5184.2  441.06  5191.8  440.39  5196.4  441.96  5201.5  442.11
  5208.1  441.27  5228.8  436.44  5236.1  435.68    5281  435.73  5322.1  439.28
  5429.7  441.21  5469.4  441.48  5538.6  440.27  5766.7     443  5810.7   444.1
#Mann= 3 ,-1 , 0
  4367.5     .05       0  5004.8     .03       0    5010     .05       0
Bank Sta=4979.2,5023.2
XS Rating Curve= 0 ,0
Exp/Cntr=0.3,0.1

Type RM Length L Ch R = 1 ,43023   ,610,610,610
BEGIN DESCRIPTION:
SOUTH MINERAL CREEK 58 1
END DESCRIPTION:
XS GIS Cut Line= 4
      3504529.21     10364906.89      3504169.81     10364545.75
      3503522.24      10364370.4      3502921.51     10364608.26
#Sta/Elev= 30
  4099.2  438.48  4199.9  437.13    4511  434.21  4574.6  434.88  4717.6  435.33
  4823.9  433.71    4877  435.25  4911.7  435.14  4968.9  436.82  4979.3  436.61
  4986.2  434.79  4997.4  432.81  4997.8  432.31  5002.2  432.31  5002.6  432.81
  5010.4  434.89  5020.7  436.28  5041.4  436.47  5060.7  435.69  5093.2  436.27
  5145.6  435.53  5344.3  436.47  5374.6  436.74    5380  437.24  5419.6  436.29
  5488.1  436.63  5517.8  437.27  5580.9  437.44    5753  439.19  5925.7  442.22
#Mann= 3 ,-1 , 0
  4099.2     .05       0  4997.4     .03       0  5002.6     .05       0
#XS Ineff= 2 , 0
                         5379.75          437.21
Permanent Ineff=
       F       F
Bank Sta=4979.3,5020.7
XS Rating Curve= 0 ,0
Exp/Cntr=0.3,0.1

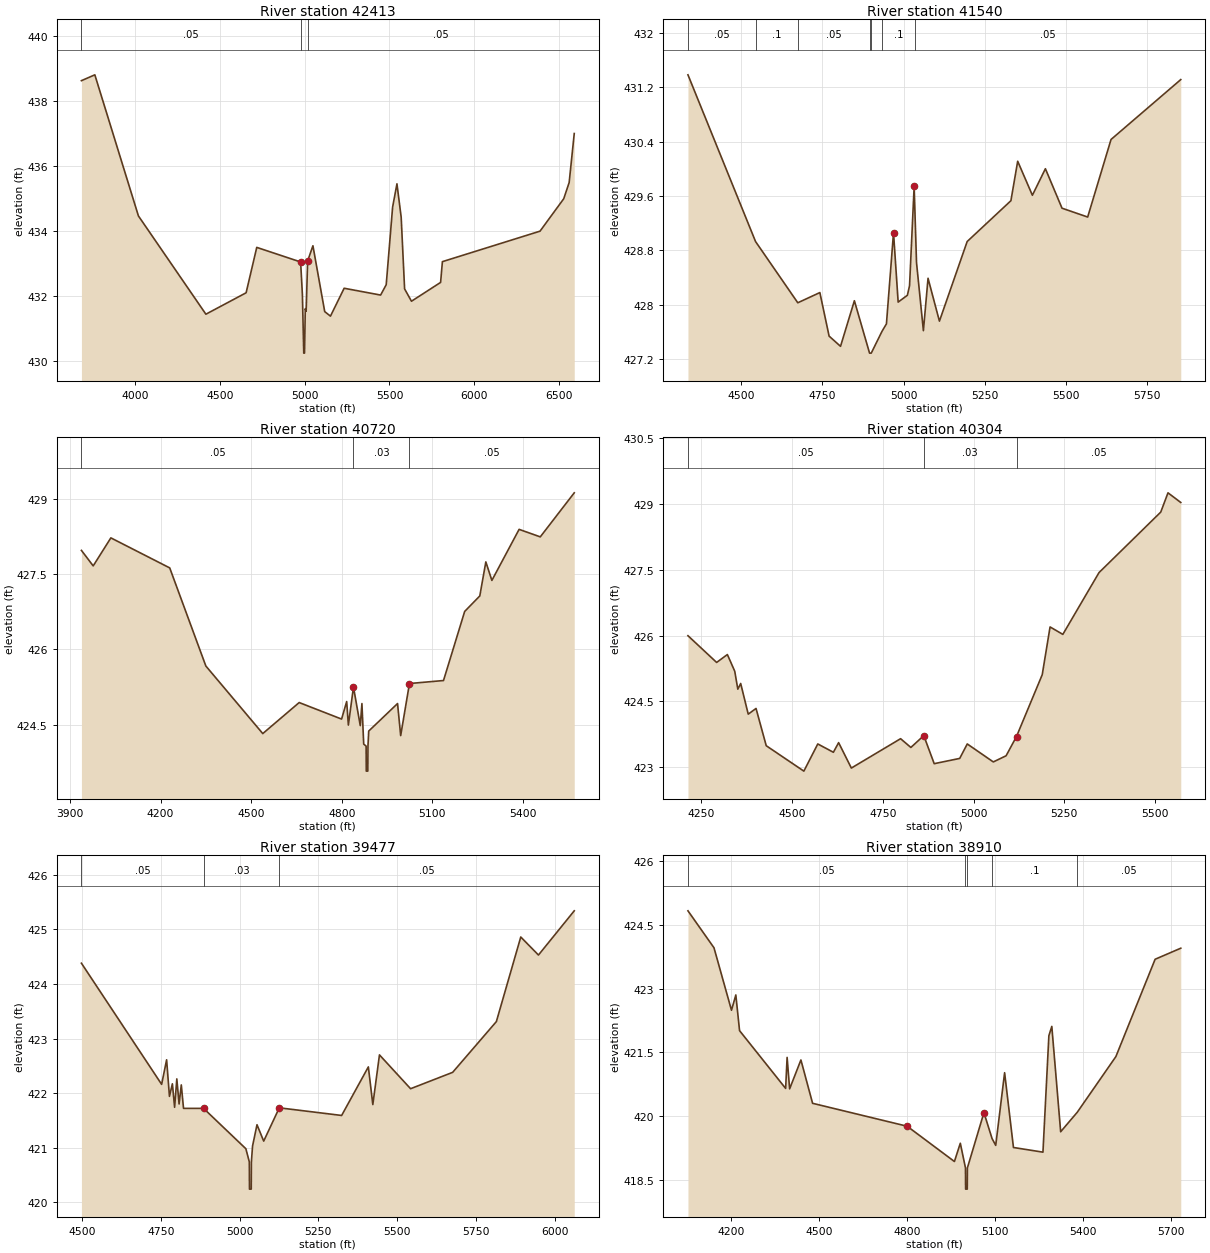
Type RM Length L Ch R = 1 ,42413   ,873,873,873
BEGIN DESCRIPTION:
SOUTH MINERAL CREEK 58 0
END DESCRIPTION:
XS GIS Cut Line= 4
3505241.5029703810364250.2943878      3504648.97     10364090.89
      3503713.21     10363839.15      3502402.42     10363637.76
#Sta/Elev= 30
    3682  438.63 3761.15  438.81 4018.37  434.46  4416.6  431.43    4654  432.09
  4716.9  433.49  4975.8  433.04  4986.2  432.04  4994.3  430.23  4998.7  430.23
  5003.3   431.6  5008.4  431.52  5017.2  433.07  5048.4  433.54    5118  431.51
  5151.9  431.37  5232.7  432.23  5447.9  432.02    5481  432.34  5518.7  434.73
  5544.3  435.45  5569.3  434.42  5589.5  432.21    5630  431.83    5802  432.41
  5812.6  433.05  6388.8  433.99  6528.8  434.99  6560.8  435.49  6590.8     437
#Mann= 3 , 0 , 0
    3682     .05       0  4975.8     .03       0  5017.2     .05       0
Bank Sta=4975.8,5017.2
XS Rating Curve= 0 ,0
Exp/Cntr=0.3,0.1

Type RM Length L Ch R = 1 ,41540   ,820,820,820
BEGIN DESCRIPTION:
SOUTH MINERAL CREEK 55 2
END DESCRIPTION:
XS GIS Cut Line= 4
      3504846.89     10363854.75      3504810.43     10363641.24
      3504204.53     10363115.19      3503705.82     10363082.29
#Sta/Elev= 30
  4335.4  431.38  4543.7  428.93  4673.9  428.03  4741.9  428.18  4770.4  427.54
  4805.6  427.39  4848.3  428.06  4895.1  427.29  4900.3  427.29  4933.4  427.61
  4947.1  427.72  4968.9  429.06  4983.2  428.04  5011.6  428.14  5018.3  428.28
  5032.5  429.74  5036.2  429.17  5039.8  428.62    5061  427.62  5075.3  428.39
  5110.4  427.76  5195.9  428.93  5330.7  429.53  5351.6  430.11  5396.9  429.61
    5437     430  5488.2  429.42  5567.3  429.29  5639.3  430.43  5854.2  431.31
#Mann= 7 ,-1 , 0
  4335.4     .05       0  4543.7      .1       0  4673.9     .05       0
  4895.1     .07       0  4900.3     .05       0  4933.4      .1       0
  5036.2     .05       0
Bank Sta=4968.9,5032.5
XS Rating Curve= 0 ,0
Exp/Cntr=0.3,0.1

Type RM Length L Ch R = 1 ,40720   ,416,416,416
BEGIN DESCRIPTION:
SOUTH MINERAL CREEK 54 2
END DESCRIPTION:
XS GIS Cut Line= 3
      3505397.28     10362957.23      3504669.81     10362599.57
      3504209.79     10362625.61
#Sta/Elev= 30
    3938  427.98 3976.99  427.67 4035.48  428.23 4230.44  427.63  4350.1  425.67
  4538.6  424.32  4659.2  424.94  4799.6  424.61  4816.5  424.96  4822.1  424.49
    4839  425.25  4861.5  424.48    4867  424.92  4872.9  424.11  4880.9  424.07
  4881.4  423.57  4886.5  423.57    4887  424.07  4889.5  424.37    4985  424.92
  4995.4  424.28  5024.4  425.32  5137.2  425.38  5207.3  426.76  5257.4  427.07
  5277.4  427.75  5297.4  427.38  5387.6   428.4  5457.7  428.25  5570.2  429.13
#Mann= 3 , 0 , 0
    3938     .05       0    4839     .03       0  5024.4     .05       0
Bank Sta=4839,5024.4
XS Rating Curve= 0 ,0
Exp/Cntr=0.3,0.1

Type RM Length L Ch R = 1 ,40304   ,827,827,827
BEGIN DESCRIPTION:
SOUTH MINERAL CREEK 53 1
END DESCRIPTION:
XS GIS Cut Line= 4
3505587.2079001910362790.6438158      3505487.51     10362708.94
      3504775.71     10362125.61      3504466.87     10362118.67
#Sta/Elev= 30
    4213     426 4292.01  425.39 4321.63  425.57  4341.9  425.19  4350.4  424.78
  4358.3  424.91  4379.1  424.21  4400.6  424.34  4428.7  423.49  4532.4  422.91
  4570.8  423.53  4613.8  423.34  4628.2  423.56  4663.3  422.98    4799  423.65
  4827.3  423.45  4862.9  423.72  4891.6  423.08  4961.9   423.2  4982.7  423.53
  5054.5  423.12  5089.7  423.26  5118.4   423.7  5189.3  425.11  5210.9   426.2
  5246.1  426.03  5345.8  427.44  5515.9  428.82  5535.9  429.26  5571.1  429.04
#Mann= 3 , 0 , 0
    4213     .05       0  4862.9     .03       0  5118.4     .05       0
Bank Sta=4862.9,5118.4
XS Rating Curve= 0 ,0
Exp/Cntr=0.3,0.1

Type RM Length L Ch R = 1 ,39477   ,567,567,567
BEGIN DESCRIPTION:
SOUTH MINERAL CREEK 52 2
END DESCRIPTION:
XS GIS Cut Line= 4
       3505711.5     10362629.05      3505850.36     10362386.03
      3505367.72     10361894.71       3504786.6     10361761.13
#Sta/Elev= 30
  4497.8  424.38  4752.5  422.16  4768.3  422.61  4777.3  421.94  4786.6  422.17
  4793.7  421.74  4800.7  422.26  4807.9   421.8  4814.9  422.15    4822  421.72
  4885.6  421.72    5020  420.98  5030.9  420.74  5031.4  420.24    5037  420.24
  5037.5  420.74  5041.2  421.03  5055.3  421.42  5076.6  421.12  5126.1  421.73
  5324.1  421.59  5408.9  422.48  5423.1  421.79  5444.2   422.7    5543  422.08
  5676.6  422.38  5815.4  423.31  5892.9  424.86  5949.1  424.53  6062.7  425.34
#Mann= 3 , 0 , 0
  4497.8     .05       0  4885.6     .03       0  5126.1     .05       0
Bank Sta=4885.6,5126.1
XS Rating Curve= 0 ,0
Exp/Cntr=0.3,0.1

Type RM Length L Ch R = 1 ,38910   ,464,464,464
BEGIN DESCRIPTION:
Mapping XS 3c6fbc7c
END DESCRIPTION:
XS GIS Cut Line= 3
      3505994.46     10362854.77      3506157.66      10362557.9
      3506001.63     10361224.77
#Sta/Elev= 30
    4053  424.83  4141.8  423.96  4201.5  422.49  4216.3  422.85    4229  422.01
  4386.2  420.65  4391.2  421.38  4399.8  420.64  4438.3  421.32  4478.1   420.3
  4800.8  419.76  4961.9  418.93    4982  419.36  4999.6  418.78  5000.1  418.28
  5005.7  418.28  5006.2  418.78  5062.6  420.08  5090.3  419.47  5102.8  419.31
  5133.1  421.02  5163.3  419.26  5263.9  419.15  5284.1  421.89  5294.1  422.11
  5324.3  419.63    5381  420.09  5512.7   421.4  5646.5  423.69    5734  423.95
#Mann= 5 ,-1 , 0
    4053     .05       0  4999.6     .03       0  5006.2     .05       0
  5090.3      .1       0    5381     .05       0
Bank Sta=4800.8,5062.6
XS Rating Curve= 0 ,0
Exp/Cntr=0.3,0.1

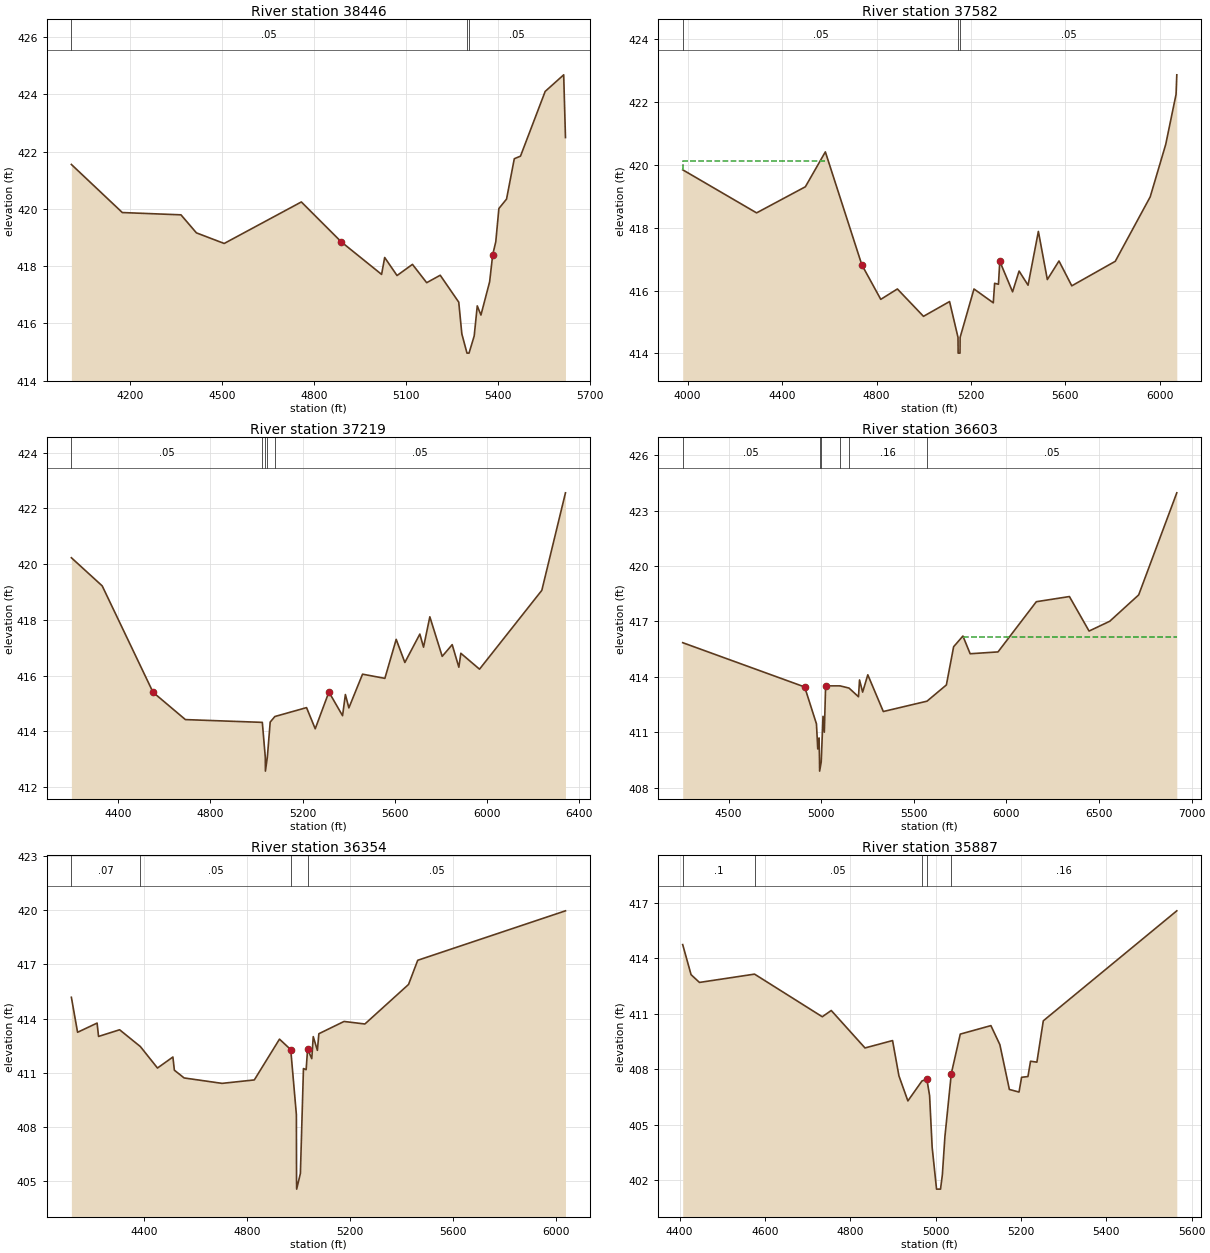
Type RM Length L Ch R = 1 ,38446   ,864,864,864
BEGIN DESCRIPTION:
SOUTH MINERAL CREEK 54 1
END DESCRIPTION:
XS GIS Cut Line= 2
      3506651.39     10362966.76      3506464.84      10361365.9
#Sta/Elev= 30
  4008.1  421.55  4174.3  419.87  4365.6  419.79    4416  419.16  4506.6  418.79
  4758.3  420.24  4889.1  418.84    5020  417.71  5030.1   418.3  5070.4  417.67
  5120.7  418.06  5167.1  417.42  5211.3  417.68  5271.7  416.74  5281.8  415.63
  5298.6  414.96  5305.2  414.96  5322.1  415.56  5332.1  416.61  5344.1  416.29
  5372.4  417.45  5382.5   418.4  5392.5  418.85  5402.6  420.01  5427.6  420.34
  5452.9  421.75  5473.1  421.84  5553.6   424.1    5614  424.68  5619.8  422.49
#Mann= 3 ,-1 , 0
  4008.1     .05       0  5298.6     .03       0  5305.2     .05       0
Bank Sta=4889.1,5382.5
XS Rating Curve= 0 ,0
Exp/Cntr=0.3,0.1

Type RM Length L Ch R = 1 ,37582   ,363,363,363
BEGIN DESCRIPTION:
SOUTH MINERAL CREEK 53 4
END DESCRIPTION:
XS GIS Cut Line= 5
       3506928.5     10362967.61      3507100.36      10362620.4
      3507303.49     10362491.93      3507360.78     10361903.39
       3506593.2     10361485.81
#Sta/Elev= 30
  3978.9  419.84  4291.9  418.47  4498.5   419.3  4583.2  420.41  4737.6  416.82
  4817.9  415.72  4888.3  416.05  4998.8  415.18  5109.3  415.65  5145.1  414.51
  5145.6  414.01  5153.5  414.01    5154  414.51  5212.8  416.05  5294.5  415.61
  5300.2  416.23  5316.4   416.2  5322.1  416.93  5376.2  415.96  5403.8  416.62
  5441.8  416.17  5485.5  417.88  5523.5  416.35  5572.8  416.94    5627  416.15
  5811.2  416.93  5959.2  418.98    6025  420.65  6068.7  422.24  6071.8  422.86
#Mann= 3 ,-1 , 0
  3978.9     .05       0  5145.1     .03       0    5154     .05       0
#XS Ineff= 2 , 0
         4581.33  420.11
Permanent Ineff=
       F       F
Bank Sta=4737.6,5322.1
XS Rating Curve= 0 ,0
Exp/Cntr=0.3,0.1

Type RM Length L Ch R = 1 ,37219   ,616,616,616
BEGIN DESCRIPTION:
SOUTH MINERAL CREEK 57 0
END DESCRIPTION:
XS GIS Cut Line= 3
      3507754.88     10362984.96      3507671.54     10362061.37
      3506607.96     10361466.25
#Sta/Elev= 30
    4196  420.23  4329.9  419.22  4550.8   415.4  4691.3  414.42  5025.4  414.32
  5038.3  413.07  5038.8  412.57  5047.2  413.07  5059.6  414.33  5079.8  414.53
  5217.5  414.85  5255.2  414.09  5314.6  415.41  5373.9  414.56  5386.2  415.32
  5401.3  414.84  5460.7  416.05  5557.7   415.9  5606.9   417.3  5644.5  416.47
  5709.6  417.49  5725.6  417.02    5753  418.11  5806.7  416.69  5850.1  417.11
    5879   416.3  5887.7   416.8  5968.8  416.23  6239.4  419.06  6342.1  422.56
#Mann= 5 ,-1 , 0
    4196     .05       0  5025.4     .16       0  5038.3     .03       0
  5047.2     .16       0  5079.8     .05       0
Bank Sta=4550.8,5314.6
XS Rating Curve= 0 ,0
Exp/Cntr=0.3,0.1

Type RM Length L Ch R = 1 ,36603   ,249,249,249
BEGIN DESCRIPTION:
SOUTH MINERAL CREEK 56 0
END DESCRIPTION:
XS GIS Cut Line= 3
       3508794.8     10362830.46      3508221.89     10362261.03
      3506559.35     10361426.28
#Sta/Elev= 30
  4251.7  415.85  4910.4  413.45    4974  411.45  4981.1  410.09  4988.2  410.69
  4990.6  409.39  4991.1  408.89  4999.8  409.39  5009.4  411.86  5016.5     411
  5023.5  413.51  5101.2  413.51  5149.9  413.39    5201  412.92  5206.6  413.83
  5223.4  413.17  5251.3  414.11    5335  412.12  5570.9  412.68  5675.6  413.56
  5714.7  415.63  5764.9  416.21    5804  415.25  5954.4  415.35  6161.3  418.07
    6340  418.35  6446.1  416.48  6557.7  417.01  6714.1  418.44  6919.8  423.97
#Mann= 6 ,-1 , 0
  4251.7     .05       0  4990.6     .03       0  4999.8     .05       0
  5101.2     .08       0  5149.9     .16       0  5570.9     .05       0
#XS Ineff= 2 , 0
                         5769.46          416.16
Permanent Ineff=
       F       F
Bank Sta=4910.4,5023.5
XS Rating Curve= 0 ,0
Exp/Cntr=0.3,0.1

Type RM Length L Ch R = 1 ,36354   ,467,467,467
BEGIN DESCRIPTION:
SOUTH MINERAL CREEK 62 0
END DESCRIPTION:
XS GIS Cut Line= 3
      3509173.26     10362535.32      3508124.67     10361964.15
      3507488.85     10361615.92
#Sta/Elev= 30
  4117.7  415.18  4141.8  413.24  4217.6  413.75  4223.3  413.01    4305  413.38
  4385.6  412.45  4452.2  411.26    4512  411.87  4517.7  411.14  4555.7  410.71
  4702.9  410.41  4828.2   410.6    4926  412.86  4969.7  412.28  4991.6  408.68
  4992.2  405.05  4992.7  404.55  5007.2  405.42  5019.1  411.23  5029.5  411.17
  5035.2  412.31  5051.4  411.78  5057.1     413  5073.2  412.24  5078.9  413.16
  5176.7  413.84  5257.7   413.7  5427.2  415.89  5462.9  417.23  6036.7  419.97
#Mann= 4 ,-1 , 0
  4117.7     .07       0  4385.6     .05       0  4969.7     .03       0
  5035.2     .05       0
Bank Sta=4969.7,5035.2
XS Rating Curve= 0 ,0
Exp/Cntr=0.3,0.1

Type RM Length L Ch R = 1 ,35887   ,297,297,297
BEGIN DESCRIPTION:
SOUTH MINERAL CREEK 55 0
END DESCRIPTION:
XS GIS Cut Line= 3
  3509162.39409710362535.1139012      3509084.76     10362420.78
      3508511.83     10361577.01
#Sta/Elev= 30
  4407.4  414.75 4427.06  413.12 4446.72   412.7  4575.8  413.15  4734.6  410.84
  4755.6  411.18  4834.7  409.15  4899.3  409.55  4914.2  407.64  4935.2  406.28
  4968.2  407.36  4979.7  407.46  4986.1  406.57  4992.1  403.77  5002.4   401.5
  5011.7   401.5    5016  402.27    5022  404.34    5037  407.76    5058   409.9
  5129.8  410.36  5150.8  409.33  5173.1   406.9  5195.7  406.76  5201.7  407.56
  5216.6   407.6  5222.7  408.43  5237.6  408.38  5252.6  410.62  5565.5  416.58
#Mann= 5 ,-1 , 0
  4407.4      .1       0  4575.8     .05       0  4968.2     .16       0
  4979.7     .07       0    5037     .16       0
Bank Sta=4979.7,5037
XS Rating Curve= 0 ,0
Exp/Cntr=0.3,0.1

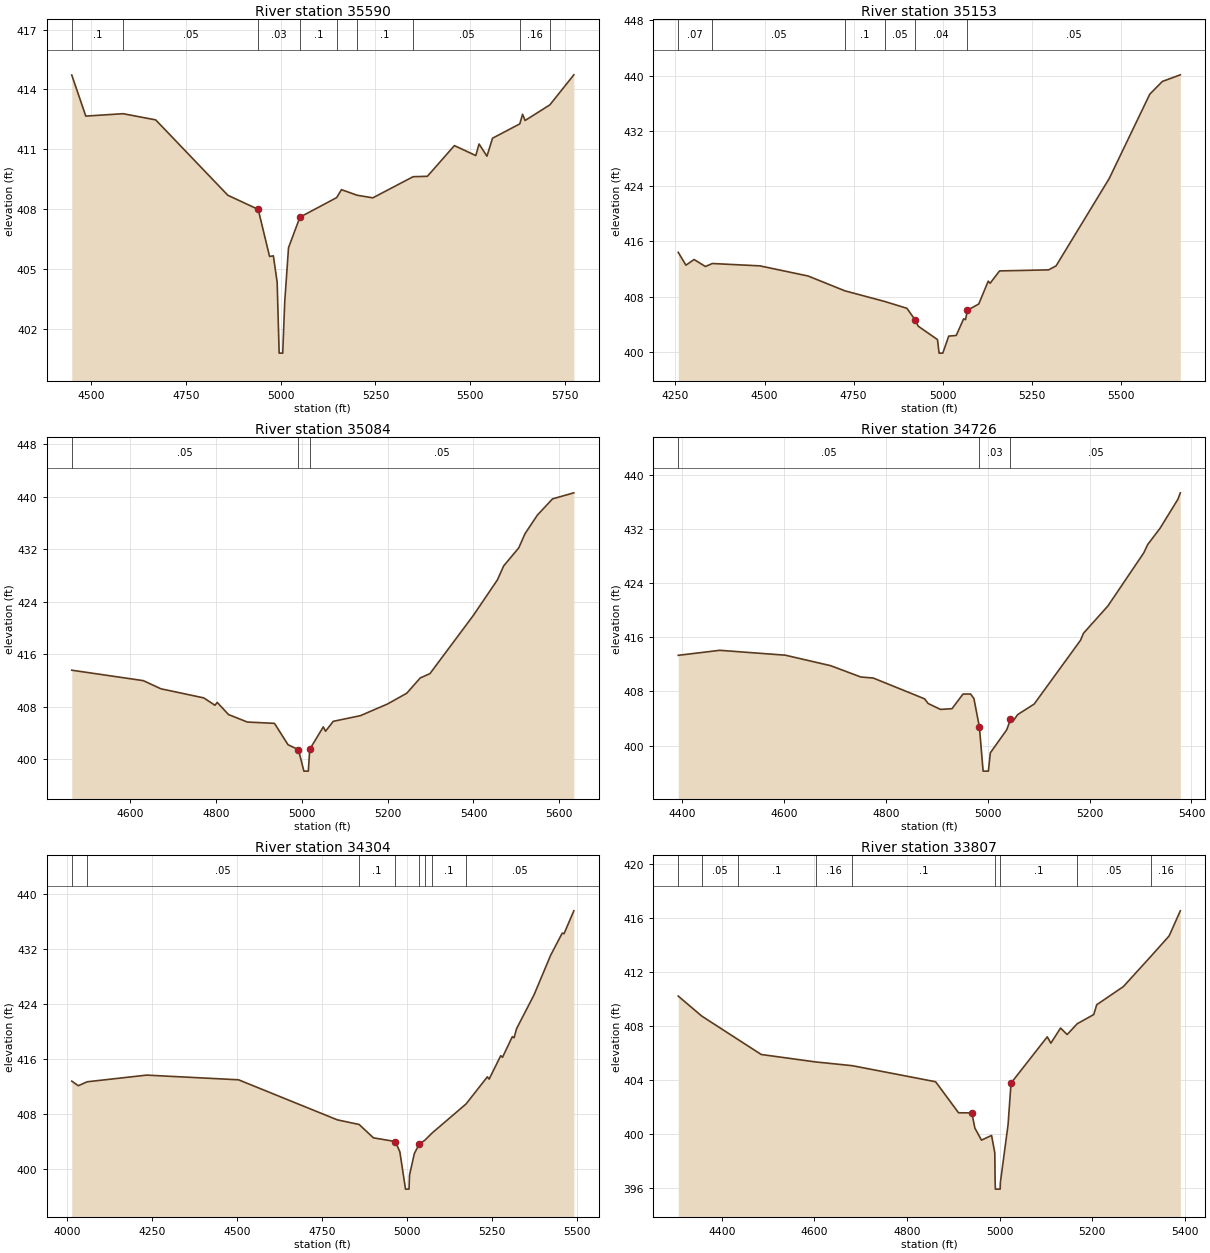
Type RM Length L Ch R = 1 ,35590   ,437,437,437
BEGIN DESCRIPTION:
SOUTH MINERAL CREEK 53 5
END DESCRIPTION:
XS GIS Cut Line= 4
3509131.9048948610362542.7809909      3509128.14     10362440.55
      3509105.57     10361827.69      3508612.48     10361471.77
#Sta/Elev= 30
  4449.3  414.72 4486.29  412.66  4584.7  412.78  4670.6  412.47  4860.7  408.69
  4940.8  407.98  4970.8  405.62  4980.8  405.65  4990.8  404.33  4996.1  400.77
  5005.5  400.77  5010.8  403.36  5020.8  406.06  5050.8  407.59  5147.6  408.57
  5160.4  408.97  5201.6  408.69  5243.1  408.56  5349.3  409.62  5386.9  409.64
  5458.1  411.18  5514.5  410.68  5523.1  411.26  5543.9  410.65  5558.6  411.55
  5630.5  412.27  5637.8  412.75  5644.5  412.44  5709.6  413.22    5773  414.73
#Mann= 9 ,-1 , 0
  4449.3      .1       0  4584.7     .05       0  4940.8     .03       0
  5050.8      .1       0  5147.6     .05       0  5201.6      .1       0
  5349.3     .05       0  5630.5     .16       0  5709.6     .05       0
Bank Sta=4940.8,5050.8
XS Rating Curve= 0 ,0
Exp/Cntr=0.3,0.1

Type RM Length L Ch R = 1 ,35153   ,69,69,69
BEGIN DESCRIPTION:
SOUTH MINERAL CREEK 53 2
END DESCRIPTION:
XS GIS Cut Line= 4
      3509201.07     10362521.42      3509445.85     10361964.15
      3509546.54     10361656.86      3509904.18     10361342.63
#Sta/Elev= 30
    4258  414.43  4279.6  412.57  4302.4  413.39  4334.2  412.38  4353.7  412.81
  4487.1  412.47  4622.4     411  4725.2  408.86  4836.9  407.32  4899.2  406.33
  4921.9   404.7  4931.1  403.74  4985.1   401.8  4989.6  399.84  4999.9  399.84
  5016.6   402.3  5037.7   402.4  5058.4   404.8  5063.7  404.69  5069.2  406.05
  5100.8  406.95  5127.4  410.26  5132.6  409.95  5159.2  411.74  5296.8  411.89
  5317.7  412.47  5466.7  425.11  5580.5  437.32  5615.7  439.16  5666.1  440.12
#Mann= 6 ,-1 , 0
    4258     .07       0  4353.7     .05       0  4725.2      .1       0
  4836.9     .05       0  4921.9     .04       0  5069.2     .05       0
Bank Sta=4921.9,5069.2
XS Rating Curve= 0 ,0
Exp/Cntr=0.3,0.1

Type RM Length L Ch R = 1 ,35084   ,358,358,358
BEGIN DESCRIPTION:
SOUTH MINERAL CREEK 54 0
END DESCRIPTION:
XS GIS Cut Line= 3
      3509379.89     10362359.95      3509640.29     10361582.21
      3509917.09     10361366.66
#Sta/Elev= 30
  4463.1  413.57    4630  411.98  4670.9  410.74  4770.9  409.35  4797.1  408.23
  4802.4  408.66  4828.7  406.81  4872.6  405.67  4935.9  405.47  4967.5  402.21
  4991.8  401.47  5004.5  398.19  5014.8  398.19  5018.1  401.51  5049.7  404.93
    5055  404.27    5073  405.78  5136.2  406.64  5199.5  408.42  5244.4  410.06
  5275.9  412.39  5298.5  413.05  5399.6  421.91  5455.9  427.34  5470.4  429.46
  5505.6  432.21  5520.1  434.36  5549.1  437.21  5584.4  439.68  5634.1   440.6
#Mann= 3 , 0 , 0
  4463.1     .05       0  4991.8     .03       0  5018.1     .05       0
Bank Sta=4991.8,5018.1
XS Rating Curve= 0 ,0
Exp/Cntr=0.3,0.1

Type RM Length L Ch R = 1 ,34726   ,422,422,422
BEGIN DESCRIPTION:
SOUTH MINERAL CREEK 53 3
END DESCRIPTION:
XS GIS Cut Line= 3
      3509504.85     10362428.41      3509711.47     10362268.67
      3509979.92     10361594.95
#Sta/Elev= 30
  4391.7  413.33  4473.4  414.07    4602  413.35  4691.2   411.8  4750.5  410.13
  4774.8  409.98  4875.7  406.91  4882.7  406.22  4906.9  405.35  4929.5  405.45
  4951.1  407.61  4966.2  407.62  4972.6  406.95  4983.4  402.75  4990.7  396.24
    5001  396.24  5004.9  398.95  5037.2  402.35  5044.4  403.86  5049.8  403.66
  5058.7  404.59    5091  406.14    5182  415.55  5187.9  416.59  5235.9  420.62
  5306.3  428.45  5314.1  429.69  5338.4  432.09  5373.4  436.36  5378.1  437.31
#Mann= 3 , 0 , 0
  4391.7     .05       0  4983.4     .03       0  5044.4     .05       0
Bank Sta=4983.4,5044.4
XS Rating Curve= 0 ,0
Exp/Cntr=0.3,0.1

Type RM Length L Ch R = 1 ,34304   ,497,497,497
BEGIN DESCRIPTION:
SOUTH MINERAL CREEK 53 0
END DESCRIPTION:
XS GIS Cut Line= 4
      3509388.53     10362603.75      3509803.49     10362431.86
      3510339.95     10361963.11      3510425.03     10361659.24
#Sta/Elev= 30
  4014.2  412.73  4033.5  412.07  4059.8  412.64  4234.5  413.61  4504.8  412.93
  4795.3   407.1  4859.7  406.42  4901.6  404.48  4966.1  403.94  4979.4  402.45
  4996.1  397.01  5006.4  397.01  5007.9  399.06  5022.1   402.2  5036.4  403.54
  5052.7  404.12  5073.8  405.16  5174.2  409.41  5236.9  413.36  5242.1  413.03
  5276.2  416.44  5281.4   416.2  5310.3  419.21  5315.5  419.05  5322.7  420.36
  5374.6  425.34  5423.1  431.07  5457.2  434.29  5462.4   434.2  5491.3  437.53
#Mann= 8 ,-1 , 0
  4014.2      .1       0  4059.8     .05       0  4859.7      .1       0
  4966.1     .05       0  5036.4      .1       0  5052.7     .16       0
  5073.8      .1       0  5174.2     .05       0
Bank Sta=4966.1,5036.4
XS Rating Curve= 0 ,0
Exp/Cntr=0.3,0.1

Type RM Length L Ch R = 1 ,33807   ,231,231,231
BEGIN DESCRIPTION:
SOUTH MINERAL CREEK 52 1
END DESCRIPTION:
XS GIS Cut Line= 2
      3510121.22     10362912.74      3510812.14     10362077.72
#Sta/Elev= 30
  4306.2  410.24  4356.9  408.76  4435.3  407.02  4485.4  405.91  4602.6  405.36
  4682.1  405.08  4861.8  403.89  4911.3  401.59    4940  401.58  4946.5  400.46
  4960.8  399.56  4982.6  399.91  4989.5  398.63  4990.3  396.43  4990.8  395.93
  5001.1  395.93  5001.6  396.43  5018.2  400.71  5024.6  403.79  5102.8  407.22
  5110.6  406.75  5131.5  407.87  5145.8  407.39  5167.5  408.19  5203.1  408.87
  5209.6   409.6    5267  410.94  5326.6  413.19  5365.9   414.7    5390  416.56
#Mann= 9 ,-1 , 0
  4306.2     .08       0  4356.9     .05       0  4435.3      .1       0
  4602.6     .16       0  4682.1      .1       0  4990.3     .07       0
  5001.6      .1       0  5167.5     .05       0  5326.6     .16       0
Bank Sta=4940,5024.6
XS Rating Curve= 0 ,0
Exp/Cntr=0.3,0.1