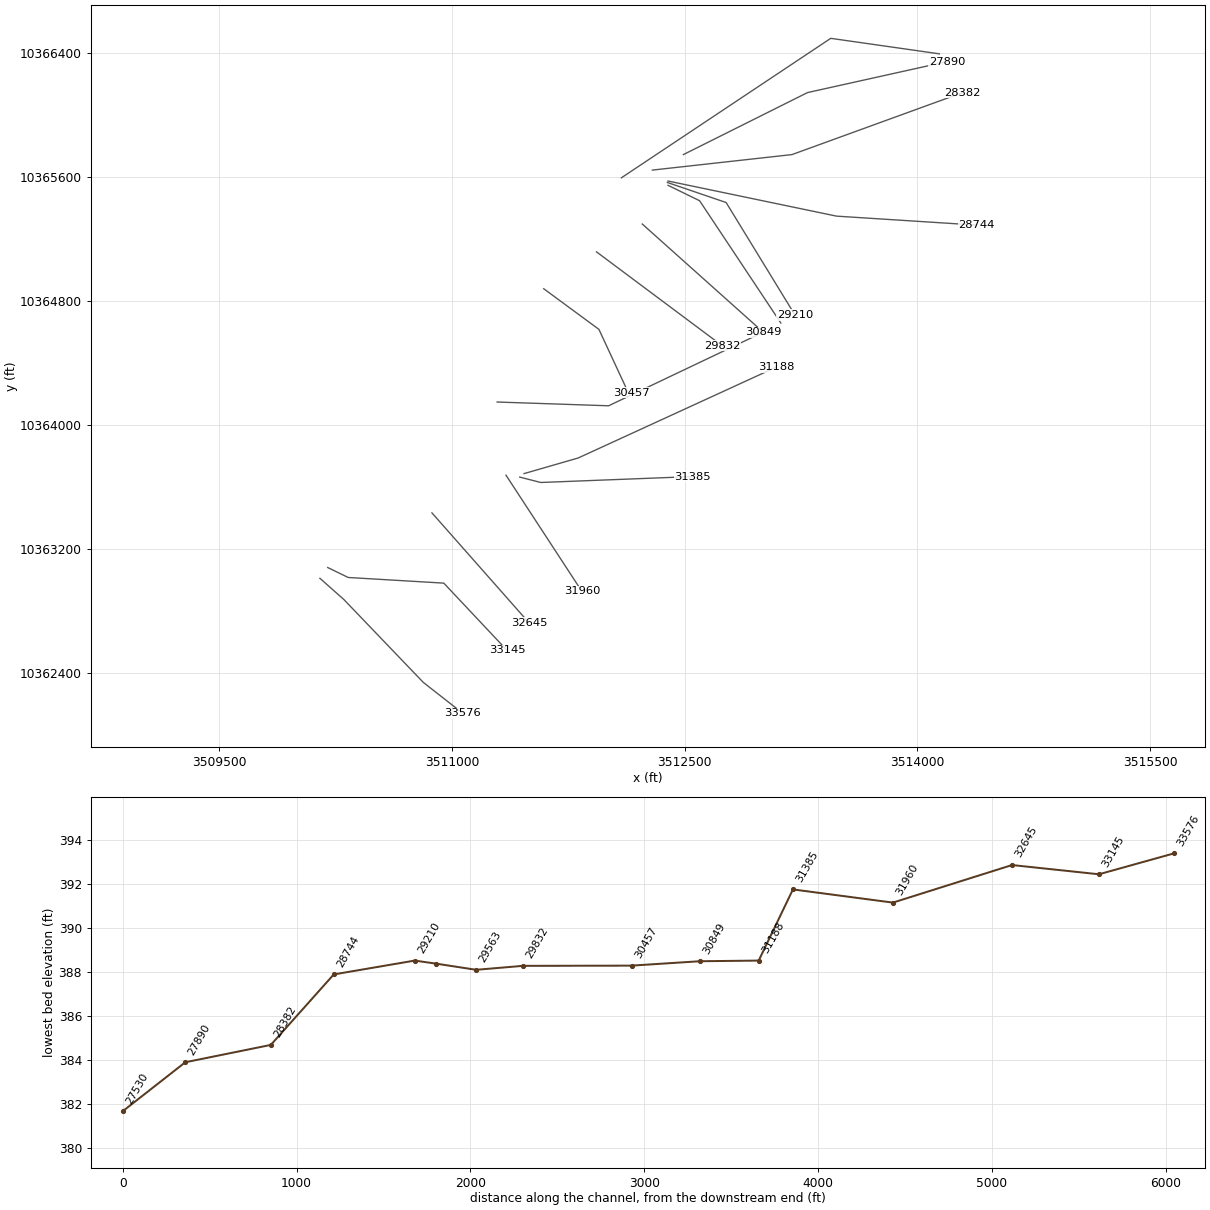
HEC-RAS study SOUTH MINERAL CREEK.prj: SOUTH MINERAL CREEK Base Level Engineering

--- SOUTH MINERAL CREEK.g01 (geometry) --- (continued)

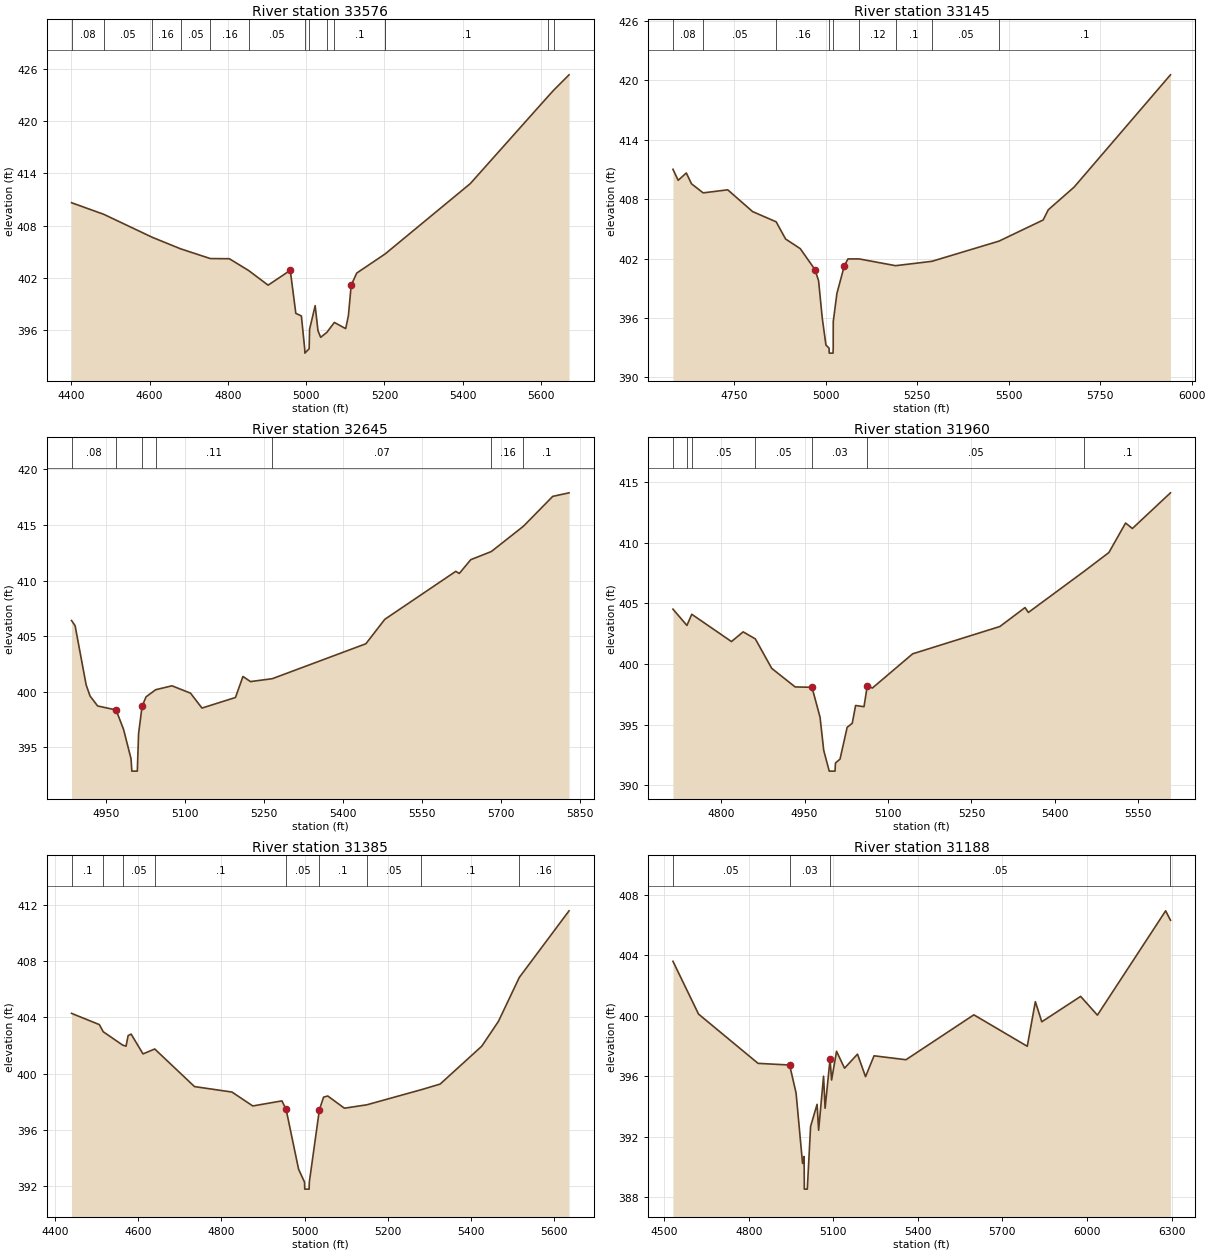
Type RM Length L Ch R = 1 ,33576   ,431,431,431
BEGIN DESCRIPTION:
SOUTH MINERAL CREEK 52 0
END DESCRIPTION:
XS GIS Cut Line= 4
      3510148.99     10363008.23      3510303.49      10362871.1
      3510815.64     10362336.37      3511070.83     10362136.74
#Sta/Elev= 30
  4400.7  410.64  4483.1  409.31  4606.3  406.69  4679.1  405.36  4755.2  404.24
  4803.9  404.22  4853.1  402.87  4902.9  401.19  4959.5  402.89  4973.7  397.96
  4987.9  397.66  4996.4   393.9  4996.9   393.4  5007.7   393.9  5008.9  396.14
  5023.1  398.84  5030.3  395.97  5037.2  395.21  5053.2  395.79  5072.1  396.92
  5101.1  396.21    5108  397.69  5115.2   401.2  5129.4  402.58  5202.2  404.78
  5202.7   404.8  5419.4  412.83  5619.1  422.88  5632.5  423.54  5671.7   425.3
#Mann= 14 ,-1 , 0
  4400.7     .08       0  4483.1     .05       0  4606.3     .16       0
  4679.1     .05       0  4755.2     .16       0  4853.1     .05       0
  4996.4     .04       0  5007.7     .05       0  5053.2     .12       0
  5072.1      .1       0  5202.2     .05       0  5202.7      .1       0
  5619.1     .16       0  5632.5      .1       0
Bank Sta=4959.5,5115.2
XS Rating Curve= 0 ,0
Exp/Cntr=0.3,0.1

Type RM Length L Ch R = 1 ,33145   ,500,500,500
BEGIN DESCRIPTION:
SOUTH MINERAL CREEK 50 0
END DESCRIPTION:
XS GIS Cut Line= 4
      3510199.32     10363077.69      3510331.27     10363013.46
      3510947.59       10362977.      3511355.55     10362542.99
#Sta/Elev= 30
  4582.3  411.01  4596.5   409.9  4618.8  410.64  4632.9  409.55  4664.8  408.63
    4732  408.94    4800  406.74  4864.3  405.71  4890.2  403.97  4930.2     403
  4970.3  400.89  4980.3  399.76  4990.3     396  5000.4  393.27  5008.9  392.95
  5009.4  392.45  5019.8  392.45  5020.3  392.95  5020.4  395.64  5030.4  398.48
  5050.5  401.24  5060.5  401.96  5091.6  401.96  5190.8  401.28    5290  401.72
  5473.5  403.76    5594  405.89  5608.1  406.92  5678.9  409.22  5942.1  420.55
#Mann= 9 ,-1 , 0
  4582.3     .08       0  4664.8     .05       0  4864.3     .16       0
  5008.9     .07       0  5020.3     .16       0  5091.6     .12       0
  5190.8      .1       0    5290     .05       0  5473.5      .1       0
Bank Sta=4970.3,5050.5
XS Rating Curve= 0 ,0
Exp/Cntr=0.3,0.1

Type RM Length L Ch R = 1 ,32645   ,685,685,685
BEGIN DESCRIPTION:
SOUTH MINERAL CREEK 5 0
END DESCRIPTION:
XS GIS Cut Line= 2
       3510871.2     10363430.13      3511496.23     10362721.75
#Sta/Elev= 30
  4884.3  406.41  4891.1  405.94    4912  400.63  4919.5  399.62  4933.8  398.73
  4968.9  398.37  4983.1  396.62  4997.3  393.98  4998.8  392.87  5009.2  392.87
  5011.6  396.23  5018.2  398.69  5025.8  399.55  5044.1  400.19  5075.1  400.54
  5110.2  399.88    5132  398.54  5195.6  399.49  5209.8  401.38  5224.1  400.92
  5265.5  401.18  5443.2  404.32  5479.2  406.52  5613.9  410.83  5620.6  410.64
  5642.4  411.88  5681.4  412.61  5742.5  414.89    5798  417.57    5829  417.89
#Mann= 7 ,-1 , 0
  4884.3     .08       0  4968.9     .03       0  5018.2     .05       0
  5044.1     .11       0  5265.5     .07       0  5681.4     .16       0
  5742.5      .1       0
Bank Sta=4968.9,5018.2
XS Rating Curve= 0 ,0
Exp/Cntr=0.3,0.1

Type RM Length L Ch R = 1 ,31960   ,575,575,575
BEGIN DESCRIPTION:
SOUTH MINERAL CREEK 49 0
END DESCRIPTION:
XS GIS Cut Line= 2
      3511348.63     10363673.17      3511837.64     10362924.05
#Sta/Elev= 30
  4713.4  404.51  4738.5  403.17  4747.2  404.09  4818.6  401.84  4839.6  402.64
  4861.5  402.06    4891  399.63  4933.1   398.1  4963.4  398.07  4977.9   395.6
  4984.5  392.87  4994.4  391.16  5004.8  391.16  5005.6  391.83  5013.8  392.15
  5026.6  394.77  5035.8  395.11  5041.8  396.57  5056.9  396.47  5062.9  398.21
    5072  398.01  5144.4  400.83  5301.2  403.08  5346.5  404.64  5352.5  404.24
  5452.8  407.63  5497.3  409.18  5527.3  411.61  5539.5  411.16    5608   414.1
#Mann= 7 ,-1 , 0
  4713.4     .05       0  4738.5     .08       0  4747.2     .05       0
  4861.5     .05       0  4963.4     .03       0  5062.9     .05       0
  5452.8      .1       0
Bank Sta=4963.4,5062.9
XS Rating Curve= 0 ,0
Exp/Cntr=0.3,0.1

Type RM Length L Ch R = 1 ,31385   ,197,197,197
BEGIN DESCRIPTION:
SOUTH MINERAL CREEK 47 0
END DESCRIPTION:
XS GIS Cut Line= 3
      3511437.13     10363661.04      3511572.59      10363626.3
       3512551.7      10363664.5
#Sta/Elev= 30
    4440  404.29 4506.79  403.49  4516.2  402.98  4562.8  402.03    4571  401.95
  4576.1  402.71  4583.3  402.81  4611.8   401.4    4640  401.75  4735.6  399.07
  4825.7  398.68  4875.7  397.69  4945.8  398.05  4955.8  397.44  4985.8  393.18
  5000.1  392.26  5000.6  391.76  5011.1  391.76  5011.6  392.26  5035.8  397.42
  5045.9  398.32  5055.9   398.4  5095.9  397.53  5149.6  397.77  5280.9  398.85
  5326.1  399.25  5426.1  401.95  5466.2  403.72  5516.3  406.85  5635.9   411.6
#Mann= 9 ,-1 , 0
    4440      .1       0  4516.2     .08       0  4562.8     .05       0
    4640      .1       0  4955.8     .05       0  5035.8      .1       0
  5149.6     .05       0  5280.9      .1       0  5516.3     .16       0
Bank Sta=4955.8,5035.8
XS Rating Curve= 0 ,0
Exp/Cntr=0.3,0.1

Type RM Length L Ch R = 1 ,31188   ,339,339,339
BEGIN DESCRIPTION:
SOUTH MINERAL CREEK 48 0
END DESCRIPTION:
XS GIS Cut Line= 3
      3511464.94     10363683.59      3511813.91     10363784.29
      3513087.66     10364369.11
#Sta/Elev= 30
  4531.3  403.59    4622   400.1  4833.1  396.84  4945.1  396.73    4968  394.88
    4991  390.22  4996.5  390.68  4997.3  388.52  5007.8  388.52  5019.5  392.67
  5042.5  394.13    5048  392.42  5065.5  395.99    5071  393.87  5088.5  397.12
    5094  395.74  5111.5  397.64    5140  396.52  5185.9  397.45  5214.4  395.96
  5244.6  397.34  5357.8  397.08  5598.7  400.05  5788.1  397.97  5816.8  400.92
  5839.6  399.59  5977.5  401.27  6036.9  400.03    6279  406.93  6296.1  406.31
#Mann= 4 ,-1 , 0
  4531.3     .05       0  4945.1     .03       0  5088.5     .05       0
  6296.1     .05       0
Bank Sta=4945.1,5088.5
XS Rating Curve= 0 ,0
Exp/Cntr=0.3,0.1

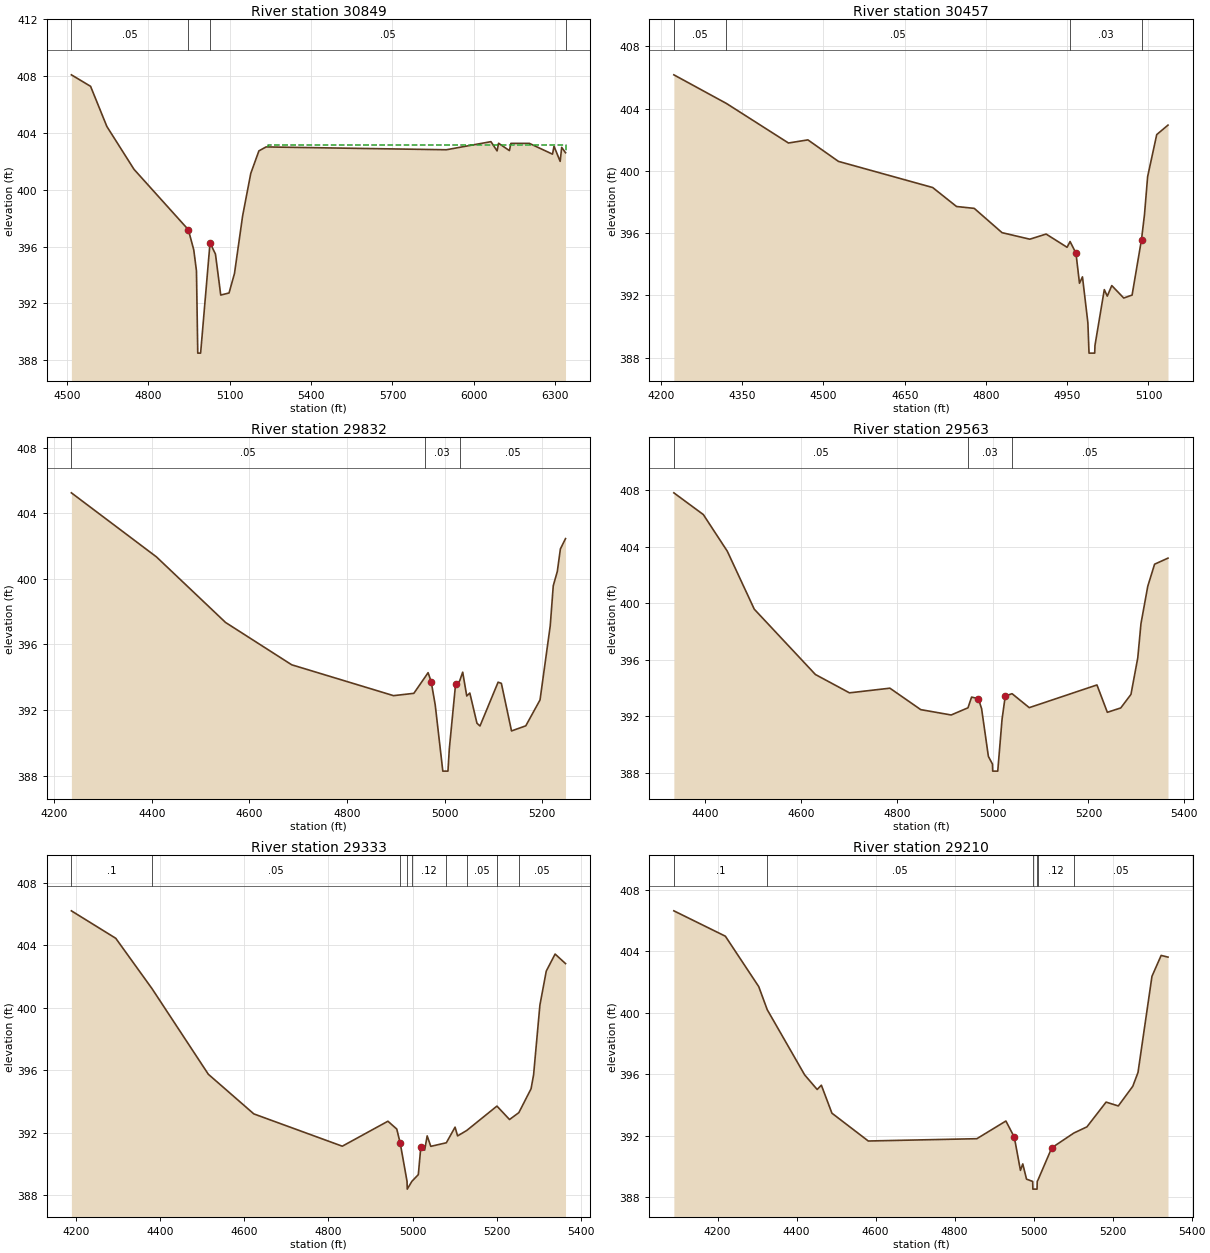
Type RM Length L Ch R = 1 ,30849   ,392,392,392
BEGIN DESCRIPTION:
SOUTH MINERAL CREEK 46 0
END DESCRIPTION:
XS GIS Cut Line= 3
      3511291.37      10364145.4      3512010.09      10364121.1
      3513004.92     10364595.07
#Sta/Elev= 30
  4516.7   408.1  4587.5  407.29  4647.5  404.46  4747.6  401.44  4947.7  397.19
  4967.7  395.77  4977.7  394.29  4982.5  388.49    4993  388.49  5027.7  396.26
  5047.7  395.47  5067.2  392.58  5097.8  392.73  5117.8   394.1  5147.8  398.16
  5177.8  401.15  5207.8  402.74  5234.3  403.02  5898.4  402.82  6062.9  403.39
  6085.6  402.74  6091.1  403.28    6131  402.76  6136.5  403.27  6204.6  403.27
  6289.9  402.51  6295.4  403.07  6318.1     402  6323.7  402.99  6337.8  402.61
#Mann= 4 ,-1 , 0
  4516.7     .05       0  4947.7     .03       0  5027.7     .05       0
  6337.8     .05       0
#XS Ineff= 2 , 0
                         5243.12          403.18
Permanent Ineff=
       F       F
Bank Sta=4947.7,5027.7
XS Rating Curve= 0 ,0
Exp/Cntr=0.3,0.1

Type RM Length L Ch R = 1 ,30457   ,625,625,625
BEGIN DESCRIPTION:
SOUTH MINERAL CREEK 46 1
END DESCRIPTION:
XS GIS Cut Line= 4
      3511591.71     10364876.28      3511947.59     10364614.15
      3512136.82     10364206.17      3512157.39     10364206.17
#Sta/Elev= 30
  4223.8  406.17  4320.9  404.33  4435.4  401.79  4471.3  401.99  4527.6  400.61
  4701.6  398.93  4745.7  397.71  4778.4  397.59  4829.7  396.03    4881  395.61
  4911.1  395.94  4949.8  395.09  4955.3  395.46  4966.2  394.71  4972.7  392.78
  4978.2  393.19  4988.2  390.24  4990.3  388.29  5000.8  388.29  5001.3  388.79
  5018.5  392.37    5024  391.95  5032.3  392.63  5054.4  391.83  5069.8  392.02
  5087.2  395.59  5092.7  397.19  5098.5  399.63  5115.3  402.33  5136.1  402.94
#Mann= 4 ,-1 , 0
  4223.8     .05       0  4320.9     .05       0  4955.3     .03       0
  5087.2     .05       0
Bank Sta=4966.2,5087.2
XS Rating Curve= 0 ,0
Exp/Cntr=0.3,0.1

Type RM Length L Ch R = 1 ,29832   ,269,269,269
BEGIN DESCRIPTION:
SOUTH MINERAL CREEK 55 1
END DESCRIPTION:
XS GIS Cut Line= 2
        3511932.     10365114.12      3512742.72     10364508.25
#Sta/Elev= 30
  4235.5  405.24  4409.6  401.34  4551.3  397.34  4686.8  394.76  4895.3  392.88
  4936.9  393.02  4959.7     394  4966.1  394.28  4972.4  393.74  4980.7  392.32
  4996.3  388.28  5006.8  388.28  5009.6  389.64  5022.4  393.57  5030.7  393.77
    5037  394.31  5045.3  392.86  5051.6  393.04  5066.2   391.2  5072.4  391.03
  5109.5   393.7  5116.2  393.63    5137  390.73  5166.2  391.04  5195.4  392.62
  5216.3  397.14  5222.5  399.58  5230.8  400.45  5237.1  401.82  5247.6  402.45
#Mann= 3 ,-1 , 0
  4235.5     .05       0  4959.7     .03       0  5030.7     .05       0
Bank Sta=4972.4,5022.4
XS Rating Curve= 0 ,0
Exp/Cntr=0.3,0.1

Type RM Length L Ch R = 1 ,29563   ,230,230,230
BEGIN DESCRIPTION:
SOUTH MINERAL CREEK 62 1
END DESCRIPTION:
XS GIS Cut Line= 2
      3512226.95     10365293.79      3512995.61     10364605.92
#Sta/Elev= 30
  4334.6  407.83  4396.1  406.29  4446.2  403.69  4502.5  399.58  4630.1  394.95
  4701.2  393.65  4785.6  393.98    4850  392.46  4913.5  392.08  4948.6  392.59
  4956.1  393.35  4970.3  393.23    4977  392.53  4991.2  389.14  4999.7   388.6
  5000.2   388.1  5010.7   388.1  5019.7  391.78  5026.4  393.42  5040.6  393.59
  5076.5   392.6  5217.8  394.21  5239.5  392.27  5267.5  392.58  5288.8  393.54
    5303  396.13  5309.7  398.56  5323.9  401.21  5338.1  402.77  5366.1   403.2
#Mann= 3 ,-1 , 0
  4334.6     .05       0  4948.6     .03       0  5040.6     .05       0
Bank Sta=4970.3,5026.4
XS Rating Curve= 0 ,0
Exp/Cntr=0.3,0.1

Type RM Length L Ch R = 1 ,29333   ,123,123,123
BEGIN DESCRIPTION:
SOUTH MINERAL CREEK 45 1
END DESCRIPTION:
XS GIS Cut Line= 3
       3512393.3     10365543.32      3512596.66     10365443.95
      3513120.17     10364655.22
#Sta/Elev= 30
  4189.8  406.21  4295.2  404.45  4381.6  401.21  4514.9  395.74  4622.9   393.2
  4832.9  391.13  4941.2  392.73  4962.2  392.23  4970.4  391.33  4986.6  388.88
  4987.1  388.38  4998.1  388.88  5013.4  389.31  5019.4   391.1  5028.4  390.88
  5034.4  391.79    5043  391.12  5079.9  391.35  5100.6  392.35  5106.6  391.79
  5128.4  392.14    5200   393.7  5229.9  392.84    5252  393.28    5281  394.81
    5287   395.7    5302  400.17  5317.1  402.35  5338.1  403.44  5362.8  402.83
#Mann= 9 ,-1 , 0
  4189.8      .1       0  4381.6     .05       0  4970.4     .12       0
  4986.6     .07       0  4998.1     .12       0  5079.9     .16       0
  5128.4     .05       0    5200     .16       0    5252     .05       0
Bank Sta=4970.4,5019.4
XS Rating Curve= 0 ,0
Exp/Cntr=0.3,0.1

Type RM Length L Ch R = 1 ,29210   ,466,466,466
BEGIN DESCRIPTION:
SOUTH MINERAL CREEK 56 1
END DESCRIPTION:
XS GIS Cut Line= 3
      3512388.73     10365561.78      3512767.64      10365432.4
      3513211.27     10364706.87
#Sta/Elev= 30
  4089.3  406.62  4219.7  404.97  4304.2  401.69  4325.7  400.19  4420.4  395.95
  4452.1     395  4462.7  395.28  4489.4  393.46  4581.5  391.65  4856.3   391.8
  4929.8  392.95  4951.1   391.9  4966.6  389.74  4972.5  390.16    4982  389.17
  4997.6  389.02  4998.1  388.52  5008.6  388.52  5009.1  389.02  5011.1  389.12
    5046  391.21  5101.9  392.17  5134.9  392.57  5183.4  394.18  5214.3  393.93
    5251  395.21  5264.2  396.11  5299.5  402.36  5322.8  403.72  5340.1  403.61
#Mann= 6 ,-1 , 0
  4089.3      .1       0  4325.7     .05       0  4997.6     .03       0
  5009.1     .05       0  5011.1     .12       0  5101.9     .05       0
Bank Sta=4951.1,5046
XS Rating Curve= 0 ,0
Exp/Cntr=0.3,0.1

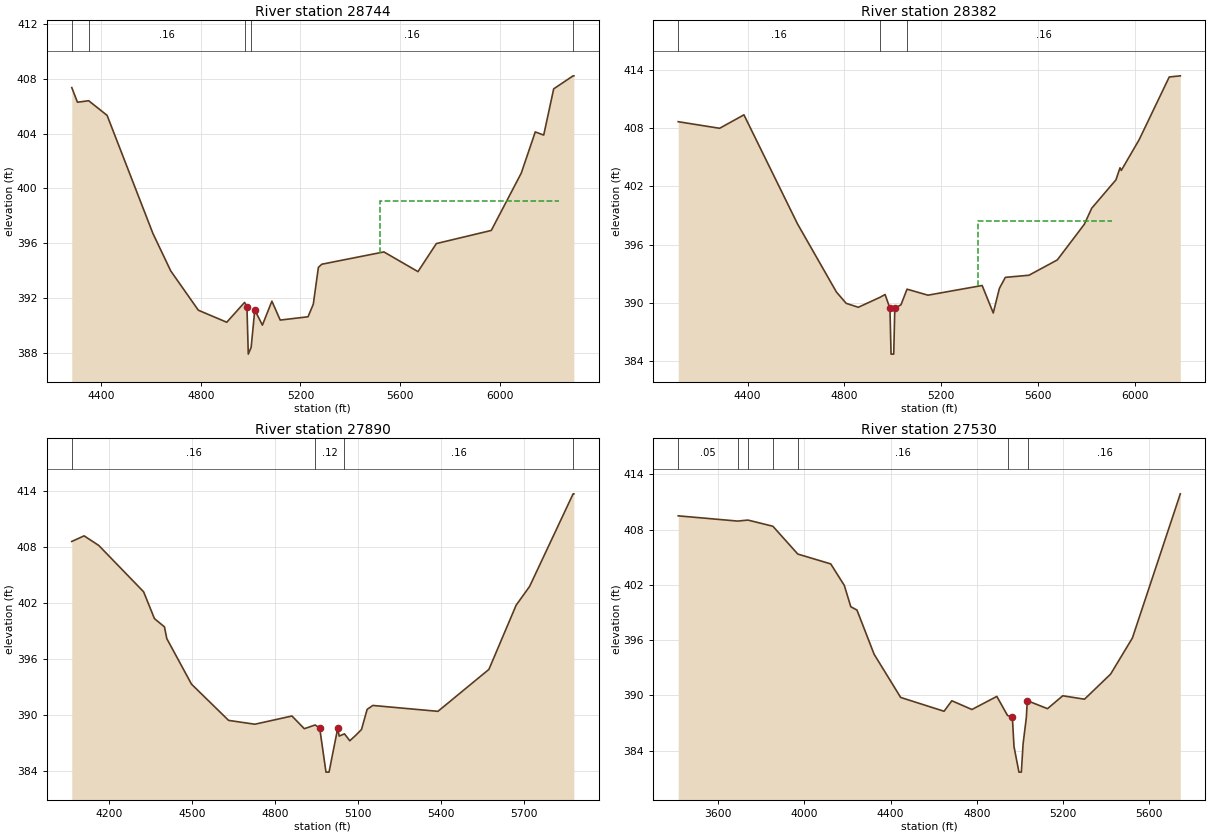
Type RM Length L Ch R = 1 ,28744   ,362,362,362
BEGIN DESCRIPTION:
SOUTH MINERAL CREEK 45 0
END DESCRIPTION:
XS GIS Cut Line= 3
      3512393.31     10365571.03      3513479.28      10365344.6
      3514382.71     10365286.83
#Sta/Elev= 30
  4282.5  407.37  4305.4   406.3  4350.3  406.41  4424.3  405.34  4608.1  396.71
  4679.7  393.97  4790.4   391.1  4904.4  390.22  4975.9  391.67  4985.4  391.34
  4990.8  387.89  5002.3  388.39  5016.8  391.12  5047.4  390.01  5085.5  391.76
  5118.9  390.38  5230.5  390.62  5251.7  391.54  5272.1  394.23  5285.6  394.46
  5534.9  395.36  5671.7  393.92  5745.4  395.97  5965.8  396.93  6086.1  401.12
  6142.3  404.13  6176.2   403.9  6216.3  407.28  6294.3  408.23  6297.1  408.23
#Mann= 5 ,-1 , 0
  4282.5      .1       0  4350.3     .16       0  4975.9     .12       0
  5002.3     .16       0  6294.3     .05       0
#XS Ineff= 1 ,-1
 5518.47 6237.22  399.11
Permanent Ineff=
       T
Bank Sta=4985.4,5016.8
XS Rating Curve= 0 ,0
Exp/Cntr=0.3,0.1

Type RM Length L Ch R = 1 ,28382   ,492,492,492
BEGIN DESCRIPTION:
SOUTH MINERAL CREEK 44 0
END DESCRIPTION:
XS GIS Cut Line= 3
      3512292.07     10365641.64      3513192.11     10365741.64
      3514292.06     10366141.63
#Sta/Elev= 30
    4113  408.69  4284.1  408.01  4384.7   409.4  4606.1  398.14    4767   391.1
  4807.3  389.93  4857.6  389.52  4948.1  390.56  4968.3  390.84  4988.4  389.41
    4993  384.68    5004  384.68  5008.5  389.43  5033.9  389.77  5059.1  391.39
  5145.6  390.77  5369.7  391.77  5415.6  388.93  5440.9  391.47  5465.5  392.61
  5563.2  392.83  5680.3  394.41    5792  398.09  5822.6  399.75    5923  402.69
  5939.7  403.93    5945  403.66  6018.8  406.83  6143.2  413.31    6189  413.43
#Mann= 3 ,-1 , 0
    4113     .16       0  4948.1     .12       0  5059.1     .16       0
#XS Ineff= 1 ,-1
 5353.69 5906.25   398.4
Permanent Ineff=
       T
Bank Sta=4988.4,5008.5
XS Rating Curve= 0 ,0
Exp/Cntr=0.3,0.1

Type RM Length L Ch R = 1 ,27890   ,360,360,360
BEGIN DESCRIPTION:
SOUTH MINERAL CREEK 43 0
END DESCRIPTION:
XS GIS Cut Line= 3
       3512492.1     10365741.64      3513292.11     10366141.64
      3514192.12     10366341.64
#Sta/Elev= 30
  4065.3  408.59    4110  409.19  4163.1  408.16  4325.2   403.2  4364.4  400.33
  4400.7  399.44  4409.1  398.19  4498.5  393.31  4632.7  389.43  4727.7  389.02
  4861.9   389.9  4906.6  388.54  4945.8  388.94  4962.3   388.6    4985  383.89
    4996  383.89  5027.6   388.6  5032.7  387.75  5051.9  387.99  5071.1  387.25
  5092.9  387.84  5113.4  388.45  5133.9  390.61  5154.4  391.03    5390   390.4
  5574.4  394.89    5673  401.77  5721.6  403.77  5879.1  413.69  5881.7  413.69
#Mann= 4 ,-1 , 0
  4065.3     .16       0  4945.8     .12       0  5051.9     .16       0
  5879.1     .05       0
Bank Sta=4962.3,5027.6
XS Rating Curve= 0 ,0
Exp/Cntr=0.3,0.1

Type RM Length L Ch R = 1 ,27530   ,800,800,800
BEGIN DESCRIPTION:
SOUTH MINERAL CREEK 42 0
END DESCRIPTION:
XS GIS Cut Line= 3
       3512092.1     10365591.64      3513442.11     10366491.64
      3514142.09     10366391.64
#Sta/Elev= 30
  3414.5  409.49  3690.2  408.92  3737.9  409.03  3853.6  408.36  3969.3  405.34
  4122.1  404.27  4185.2  401.93  4215.2  399.62  4243.8  399.26  4323.4  394.46
  4446.6  389.77  4647.9  388.27    4684  389.41  4777.1  388.46  4892.8  389.88
  4942.4  387.81  4964.9  387.63  4972.4  384.44  4995.4  381.66  5006.5  381.66
  5014.5  384.71  5029.5  387.54    5034  389.37  5039.5  389.37  5127.9  388.55
  5198.6  389.95  5299.6  389.58  5420.9  392.31  5521.9  396.23  5744.1  411.88
#Mann= 7 ,-1 , 0
  3414.5     .05       0  3690.2      .1       0  3737.9     .05       0
  3853.6     .16       0  3969.3     .16       0  4942.4     .12       0
  5039.5     .16       0
Bank Sta=4964.9,5034
XS Rating Curve= 0 ,0
Exp/Cntr=0.3,0.1