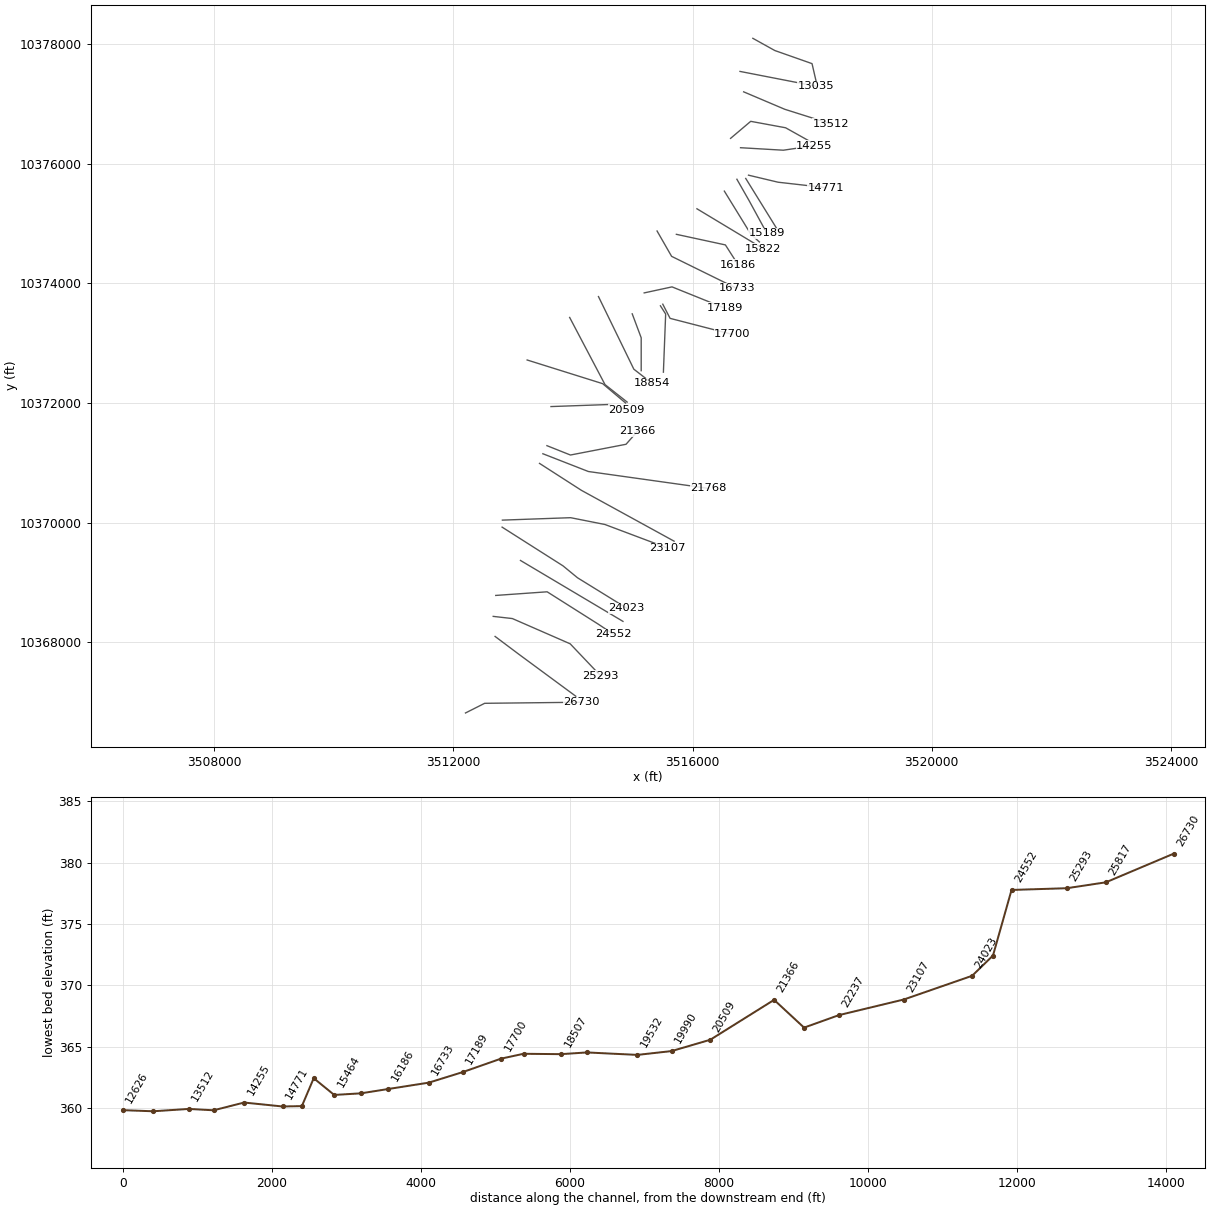
HEC-RAS study SOUTH MINERAL CREEK.prj: SOUTH MINERAL CREEK Base Level Engineering

--- SOUTH MINERAL CREEK.g01 (geometry) --- (continued)

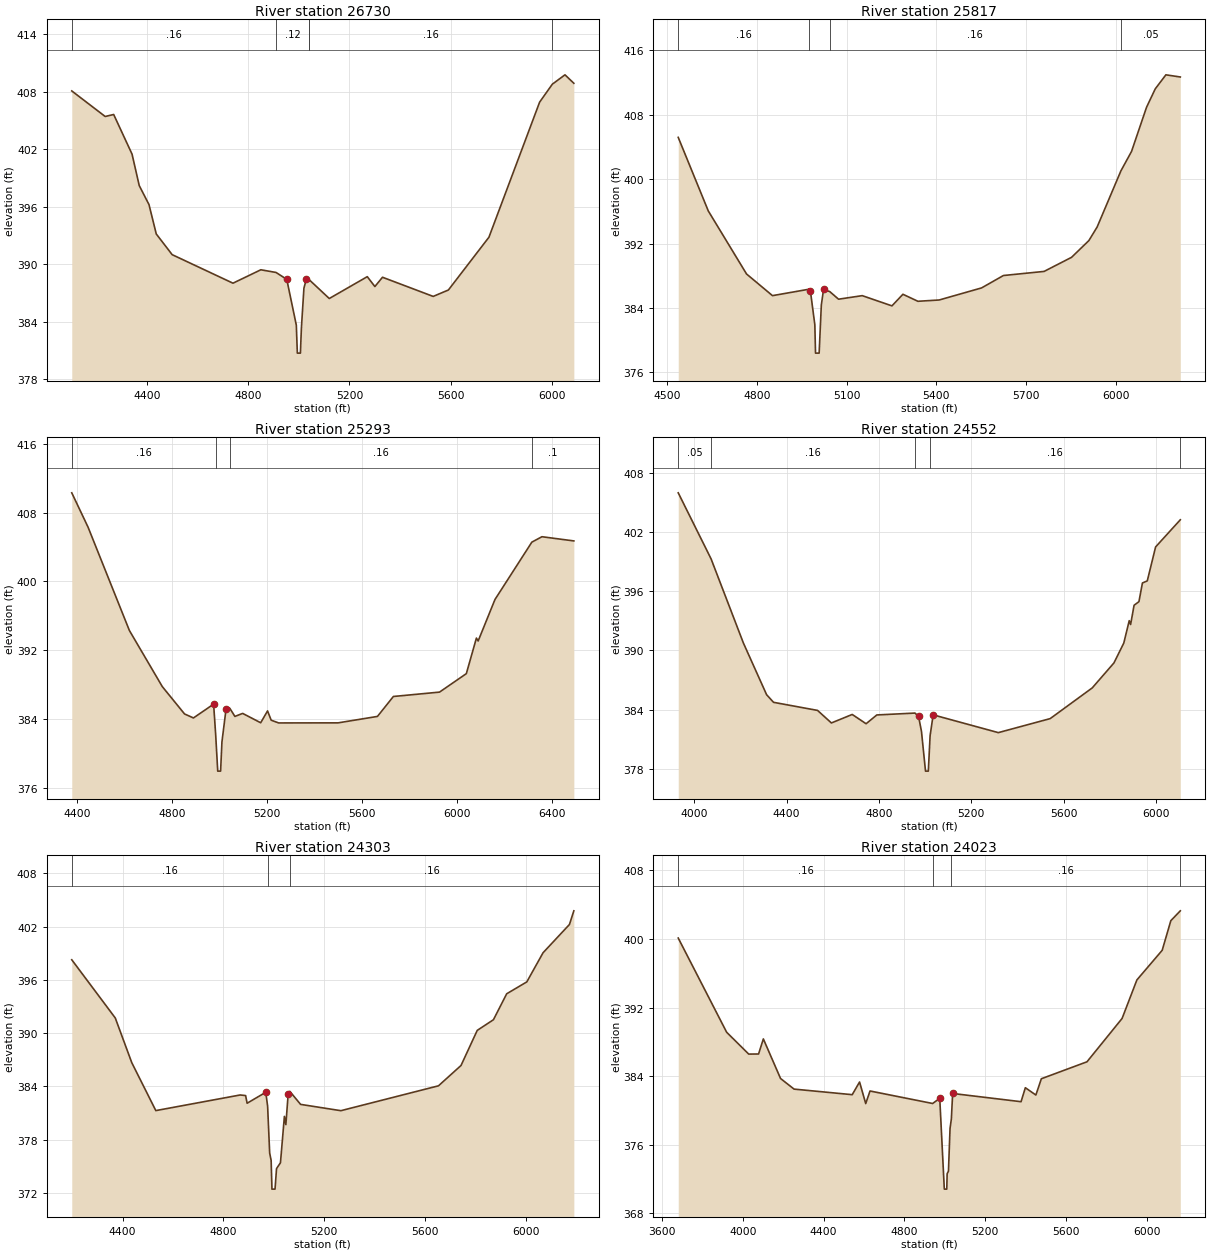
Type RM Length L Ch R = 1 ,26730   ,913,913,913
BEGIN DESCRIPTION:
SOUTH MINERAL CREEK 40 0
END DESCRIPTION:
XS GIS Cut Line= 3
       3512204.4     10366819.71      3512524.72     10366981.17
      3514147.11      10366999.4
#Sta/Elev= 30
  4104.3  408.11  4236.2  405.44  4269.7  405.65  4342.2  401.51  4370.5  398.23
  4409.1  396.24  4437.7  393.18  4500.4  391.02  4740.4  388.04  4850.4  389.44
  4910.4  389.16  4952.7  388.44  4990.4  383.66  4994.4  380.74  5006.5  380.74
  5010.4  383.35  5020.4  387.52  5030.4   388.5  5041.7  388.39  5120.4  386.44
  5270.4  388.72  5300.4  387.69  5330.5  388.66  5530.5  386.66  5590.5  387.33
  5750.5  392.84  5950.5  406.94  6000.5  408.81  6050.5  409.79  6085.5  408.91
#Mann= 5 ,-1 , 0
  4104.3     .16       0  4910.4     .12       0  5041.7     .05       0
  5041.7     .16       0  6000.5     .05       0
Bank Sta=4952.7,5030.4
XS Rating Curve= 0 ,0
Exp/Cntr=0.3,0.1

Type RM Length L Ch R = 1 ,25817   ,524,524,524
BEGIN DESCRIPTION:
SOUTH MINERAL CREEK 4 0
END DESCRIPTION:
XS GIS Cut Line= 3
       3512699.4     10368098.93       3513099.4     10367798.93
      3514048.24     10367099.79
#Sta/Elev= 30
  4537.1   405.2  4637.6  396.06  4765.5  388.23  4852.2  385.54    4973  386.33
  4979.2  386.06  4993.8  381.93  4996.1   378.4  5008.2   378.4  5015.5  384.37
    5023  386.32  5043.8  386.04  5073.1   385.1  5152.3  385.54  5251.6  384.27
  5288.3  385.71  5338.4  384.84  5409.4     385  5551.3   386.5  5624.3  388.04
  5760.3  388.55  5852.1   390.3    5910  392.38  5937.7  394.07  6017.1  401.04
  6052.6  403.45  6102.8  408.94    6132  411.23  6167.5  412.97  6215.7   412.7
#Mann= 4 ,-1 , 0
  4537.1     .16       0    4973     .12       0  5043.8     .16       0
  6017.1     .05       0
Bank Sta=4979.2,5023
XS Rating Curve= 0 ,0
Exp/Cntr=0.3,0.1

Type RM Length L Ch R = 1 ,25293   ,741,741,741
BEGIN DESCRIPTION:
SOUTH MINERAL CREEK 39 0
END DESCRIPTION:
XS GIS Cut Line= 4
      3512667.95      10368434.3      3512988.26     10368397.84
      3513954.41     10367975.96      3514462.21     10367442.12
#Sta/Elev= 30
  4378.2  410.32  4446.8  406.32  4620.8  394.29  4759.3  387.76  4852.8  384.58
  4890.3  384.11  4975.3  385.72  4984.3  382.01  4992.6  377.92  5004.7  377.92
  5010.3  381.32  5027.6  385.14    5043  385.25  5064.9  384.29  5097.6  384.64
  5173.4  383.55  5202.3  384.93  5217.6  383.85  5249.1  383.53  5499.6  383.54
    5665  384.29    5732  386.61  5926.2  387.12  6039.1  389.27  6081.5  393.41
  6088.8  393.07  6159.6   397.9  6314.9  404.58  6357.4  405.21  6491.6  404.72
#Mann= 4 ,-1 , 0
  4378.2     .16       0  4984.3     .12       0    5043     .16       0
  6314.9      .1       0
Bank Sta=4975.3,5027.6
XS Rating Curve= 0 ,0
Exp/Cntr=0.3,0.1

Type RM Length L Ch R = 1 ,24552   ,249,249,249
BEGIN DESCRIPTION:
SOUTH MINERAL CREEK 36 1
END DESCRIPTION:
XS GIS Cut Line= 4
      3512710.21     10368784.42      3513569.62     10368845.19
      3514420.32     10368306.99      3514676.42     10368137.71
#Sta/Elev= 30
  3930.5  405.97  4072.8  399.28  4213.1  390.74  4313.4  385.52  4343.4  384.75
    4534  383.93  4594.1  382.66  4684.3  383.52  4744.4  382.58  4790.8  383.47
  4956.2  383.66  4971.5  383.34  4984.3  381.81  5001.8  377.78    5014  377.78
  5021.7  381.37    5035  383.48  5317.3  381.68    5542   383.1  5724.2  386.21
  5818.2  388.74  5860.8  390.75  5884.4  393.02  5890.4  392.63  5905.4  394.58
  5926.5  394.95  5941.6  396.84  5962.6  397.05  5998.7  400.49  6105.7  403.24
#Mann= 5 ,-1 , 0
  3930.5     .05       0  4072.8     .16       0  4956.2     .12       0
  5021.7     .16       0  6105.7     .05       0
Bank Sta=4971.5,5035
XS Rating Curve= 0 ,0
Exp/Cntr=0.3,0.1

Type RM Length L Ch R = 1 ,24303   ,280,280,280
BEGIN DESCRIPTION:
SOUTH MINERAL CREEK 38 0
END DESCRIPTION:
XS GIS Cut Line= 2
      3513123.68     10369369.19      3514837.18     10368350.99
#Sta/Elev= 30
  4198.3  398.26    4371  391.71  4436.6  386.67    4532  381.28  4867.1  383.04
  4888.5  382.97  4894.4  382.11  4968.4  383.34  4975.8  381.78    4984  376.49
  4989.8  375.68    4993  372.44  5005.2  372.44  5011.2  374.75  5026.8  375.41
  5042.4  380.63  5048.2   379.7  5057.3   383.1  5063.8  383.45  5106.7  381.98
  5266.6  381.27  5654.1  384.07  5743.6  386.36    5808  390.31  5872.3  391.51
  5924.9  394.43  6004.8  395.77  6069.3  399.05    6174  402.23  6191.5  403.77
#Mann= 3 ,-1 , 0
  4198.3     .16       0  4975.8     .12       0  5063.8     .16       0
Bank Sta=4968.4,5057.3
XS Rating Curve= 0 ,0
Exp/Cntr=0.3,0.1

Type RM Length L Ch R = 1 ,24023   ,916,916,916
BEGIN DESCRIPTION:
SOUTH MINERAL CREEK 37 0
END DESCRIPTION:
XS GIS Cut Line= 4
      3512816.44     10369926.25      3513834.38     10369279.21
      3514077.44     10369079.56      3514898.46      10368572.9
#Sta/Elev= 30
  3680.2  400.11  3919.9  389.11  4029.1  386.56  4077.9  386.57  4101.6  388.33
  4186.7  383.71  4253.6  382.47  4541.5  381.82  4577.9   383.3  4608.4  380.78
  4629.6  382.25  4939.7  380.79  4974.8   381.4  4997.4  370.79  5009.6  370.79
  5011.4  372.59  5017.9  372.89  5025.8  377.89  5032.2  378.97  5038.7  381.96
  5377.3     381  5398.6  382.63  5450.7  381.78  5477.8  383.68  5703.7  385.66
  5877.5  390.72  5950.8  395.22    6076  398.68  6118.8  402.14  6165.7  403.29
#Mann= 4 ,-1 , 0
  3680.2     .16       0  4939.7     .12       0  5032.2     .16       0
  6165.7     .05       0
Bank Sta=4974.8,5038.7
XS Rating Curve= 0 ,0
Exp/Cntr=0.3,0.1

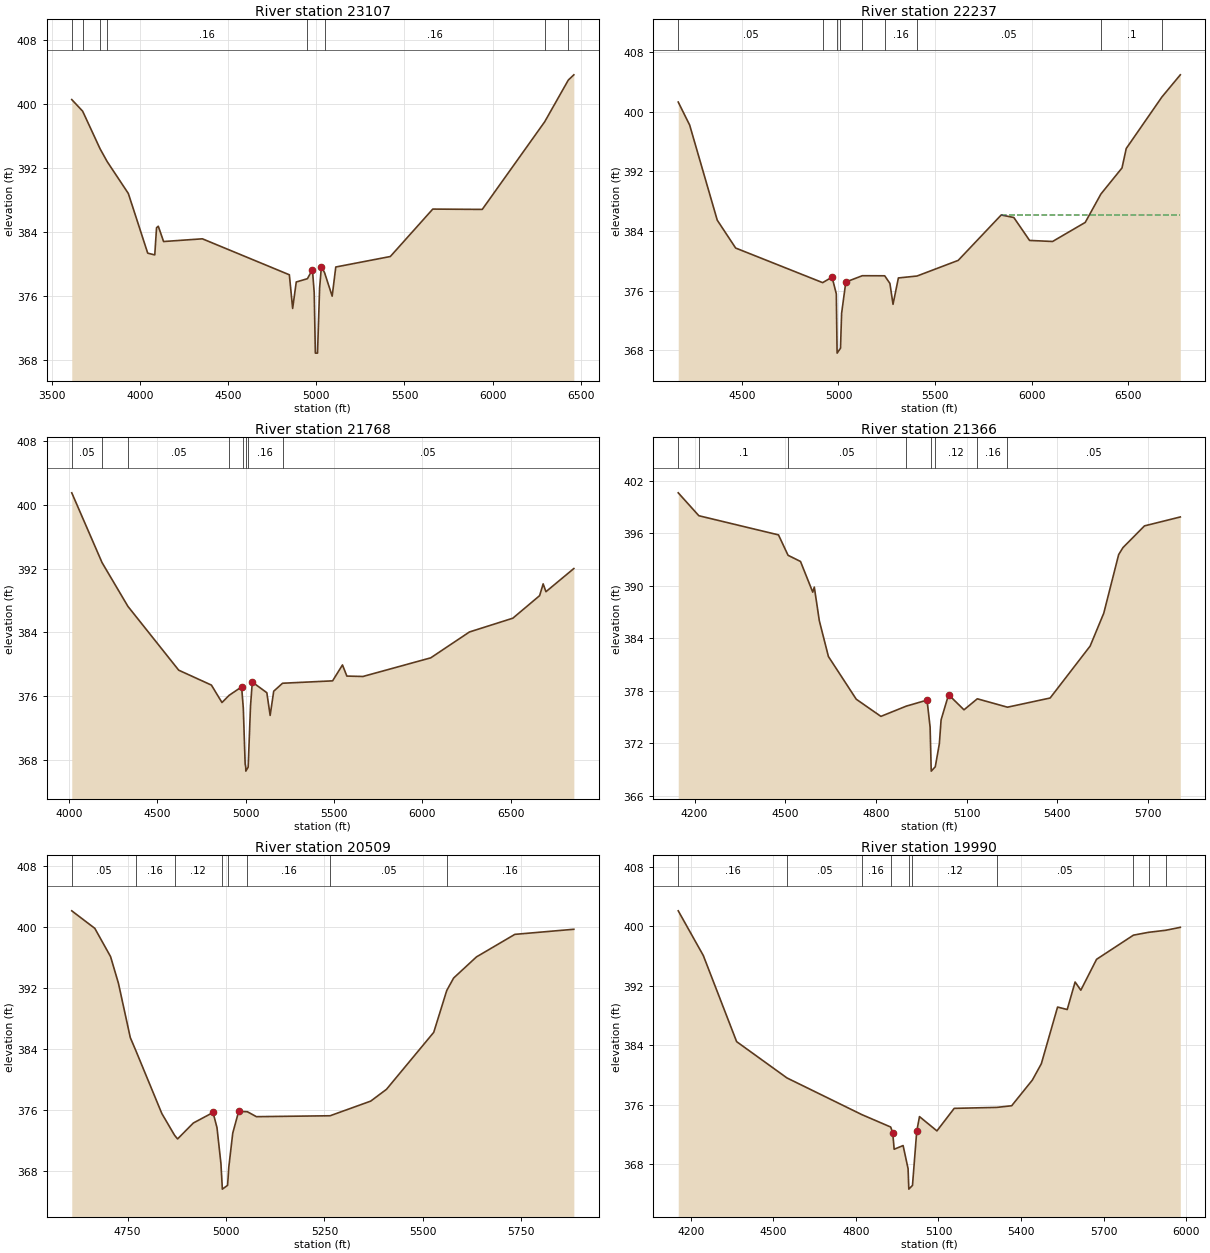
Type RM Length L Ch R = 1 ,23107   ,870,870,870
BEGIN DESCRIPTION:
SOUTH MINERAL CREEK 65 1
END DESCRIPTION:
XS GIS Cut Line= 4
      3512821.35     10370043.58      3513961.87     10370084.15
      3514534.86     10369970.67       3515586.9     10369574.85
#Sta/Elev= 30
  3611.7  400.51  3673.5  399.06  3772.3  394.37  3812.6  392.77  3932.7  388.79
  4042.7  381.34  4082.8  381.12  4092.8  384.51  4102.8   384.7  4132.8  382.79
  4352.9  383.13  4846.5  378.64  4865.3  374.44  4885.7  377.74    4949  378.15
  4977.5  379.28  4987.6  376.42  4994.1  368.86  5006.4  368.86  5018.2  376.96
  5028.4  379.65  5046.3  378.91  5089.6  375.97    5110  379.61  5419.6  380.92
  5660.4  386.84  5941.3   386.8  6295.7  397.74  6429.8  402.95  6461.1   403.6
#Mann= 8 ,-1 , 0
  3611.7     .05       0  3673.5     .16       0  3772.3     .05       0
  3812.6     .16       0    4949     .12       0  5046.3     .16       0
  6295.7      .1       0  6429.8     .05       0
Bank Sta=4977.5,5028.4
XS Rating Curve= 0 ,0
Exp/Cntr=0.3,0.1

Type RM Length L Ch R = 1 ,22237   ,469,469,469
BEGIN DESCRIPTION:
SOUTH MINERAL CREEK 35 1
END DESCRIPTION:
XS GIS Cut Line= 3
      3513442.06     10370991.67      3514142.11     10370541.64
      3515692.12     10369691.63
#Sta/Elev= 30
  4170.3  401.32  4229.5  398.23  4372.4  385.45  4467.6  381.71  4918.2  377.06
  4966.9   377.8    4989  375.54  4992.7  368.09  4993.2  367.59  5006.4  368.09
  5010.6  368.25  5016.3  372.93  5038.1  377.14  5123.4  377.99  5239.6  377.98
  5266.5  376.95  5282.6  374.15  5310.4  377.69  5407.1  377.95  5620.1  380.05
  5842.8  386.15  5908.2  385.81  5989.7  382.73  6108.8  382.59  6277.9  385.15
  6359.2  388.97  6468.4  392.47  6490.2  395.08  6674.9     402  6770.3  404.98
#Mann= 9 ,-1 , 0
  4170.3     .05       0  4918.2     .16       0  4992.7     .07       0
  5006.4     .16       0  5123.4     .05       0  5239.6     .16       0
  5407.1     .05       0  6359.2      .1       0  6674.9     .05       0
#XS Ineff= 2 , 0
                         5843.18          386.15
Permanent Ineff=
       F       F
Bank Sta=4966.9,5038.1
XS Rating Curve= 0 ,0
Exp/Cntr=0.3,0.1

Type RM Length L Ch R = 1 ,21768   ,402,402,402
BEGIN DESCRIPTION:
SOUTH MINERAL CREEK 35 0
END DESCRIPTION:
XS GIS Cut Line= 3
      3513498.38     10371152.97      3514258.82     10370856.08
      3516264.05     10370574.83
#Sta/Elev= 30
  4016.2  401.53  4187.7  392.76  4333.9  387.27  4621.4  379.25  4806.4  377.38
  4866.2  375.19  4906.5  376.09  4977.4  377.15  4986.9  374.49  4997.4  367.46
  5000.7  367.07  5001.2  366.57  5014.4  367.07  5027.7  374.74  5037.8  377.76
  5120.1  376.42  5138.8  373.57    5159  376.61  5208.9  377.61  5492.2  377.91
  5548.1  379.91    5573  378.51  5663.9  378.46  6047.5   380.8  6266.6  384.05
  6512.1  385.78  6663.6  388.61  6683.8  390.09  6699.6  389.11  6857.4  392.02
#Mann= 8 ,-1 , 0
  4016.2     .05       0  4187.7      .1       0  4333.9     .05       0
  4906.5     .12       0  4986.9     .16       0  5000.7     .07       0
  5014.4     .16       0  5208.9     .05       0
Bank Sta=4977.4,5037.8
XS Rating Curve= 0 ,0
Exp/Cntr=0.3,0.1

Type RM Length L Ch R = 1 ,21366   ,857,857,857
BEGIN DESCRIPTION:
SOUTH MINERAL CREEK 34 0
END DESCRIPTION:
XS GIS Cut Line= 4
      3513565.85     10371288.01      3513959.12     10371131.74
       3514888.8     10371311.43      3515081.51     10371530.18
#Sta/Elev= 30
  4145.8  400.65  4214.1  398.03  4477.6  395.84  4509.2  393.51  4550.5   392.8
    4591  389.29  4596.1  389.87  4612.8  386.01  4642.9  381.93    4735  377.05
  4816.5  375.09  4900.4  376.26  4969.2  376.95  4979.4  373.85  4982.7  369.33
  4983.2  368.83  4996.5  369.33    5010  371.97  5015.7  374.69  5040.5  377.57
  5091.5  375.84  5135.6   377.1  5235.4  376.14  5376.6  377.19    5509  383.13
  5554.1  386.89  5603.4  393.59  5617.7  394.39  5688.8  396.87  5807.4  397.89
#Mann= 8 ,-1 , 0
  4145.8     .05       0  4214.1      .1       0  4509.2     .05       0
  4900.4     .12       0  4982.7     .07       0  4996.5     .12       0
  5135.6     .16       0  5235.4     .05       0
Bank Sta=4969.2,5040.5
XS Rating Curve= 0 ,0
Exp/Cntr=0.3,0.1

Type RM Length L Ch R = 1 ,20509   ,519,519,519
BEGIN DESCRIPTION:
SOUTH MINERAL CREEK 33 0
END DESCRIPTION:
XS GIS Cut Line= 3
      3513633.64     10371941.64      3514589.32     10371975.49
      3514896.64     10371892.16
#Sta/Elev= 30
  4608.5  402.11    4667  399.81    4707   396.1    4727   392.6  4757.1  385.47
  4770.7  383.82  4837.1  375.51  4869.4  372.66  4877.1  372.17  4917.2  374.26
  4967.2  375.64  4977.2  373.65  4987.2  368.95  4990.3  366.08  4990.8  365.58
  5004.1  366.08  5007.2  368.47  5017.2  372.93  5032.2  375.78  5054.3  375.74
  5077.3  375.09  5264.3  375.21  5367.4  377.13  5407.5  378.68  5527.5  386.16
  5560.5  391.65    5578  393.29  5635.9  396.06  5733.4  399.02  5883.2  399.69
#Mann= 8 ,-1 , 0
  4608.5     .05       0  4770.7     .16       0  4869.4     .12       0
  4990.3     .07       0  5004.1     .12       0  5054.3     .16       0
  5264.3     .05       0  5560.5     .16       0
Bank Sta=4967.2,5032.2
XS Rating Curve= 0 ,0
Exp/Cntr=0.3,0.1

Type RM Length L Ch R = 1 ,19990   ,458,458,458
BEGIN DESCRIPTION:
SOUTH MINERAL CREEK 32 0
END DESCRIPTION:
XS GIS Cut Line= 3
      3513235.17     10372720.28      3514498.18     10372324.45
      3514880.99     10372001.54
#Sta/Elev= 30
  4154.4  402.08  4245.5  396.07  4366.6  384.49  4549.5  379.61  4821.5  374.68
  4926.4  373.01  4933.8  372.25    4939  370.02  4971.5  370.52  4989.6  367.41
  4991.8  365.16  4992.3  364.66  5005.6  365.16    5021  372.43  5031.1  374.41
  5094.4  372.49  5157.2  375.52  5312.4  375.65    5366  375.87  5441.3  379.33
  5473.8  381.52  5532.8  389.14  5567.9  388.81  5596.5  392.51  5617.3  391.41
  5674.5  395.56  5808.5  398.81  5863.4  399.19  5926.6  399.47  5978.8  399.86
#Mann= 10 ,-1 , 0
  4154.4     .16       0  4549.5     .05       0  4821.5     .16       0
  4926.4     .12       0  4991.8     .07       0  5005.6     .12       0
  5312.4     .05       0  5808.5     .16       0  5863.4     .05       0
  5926.6     .16       0
Bank Sta=4933.8,5021
XS Rating Curve= 0 ,0
Exp/Cntr=0.3,0.1

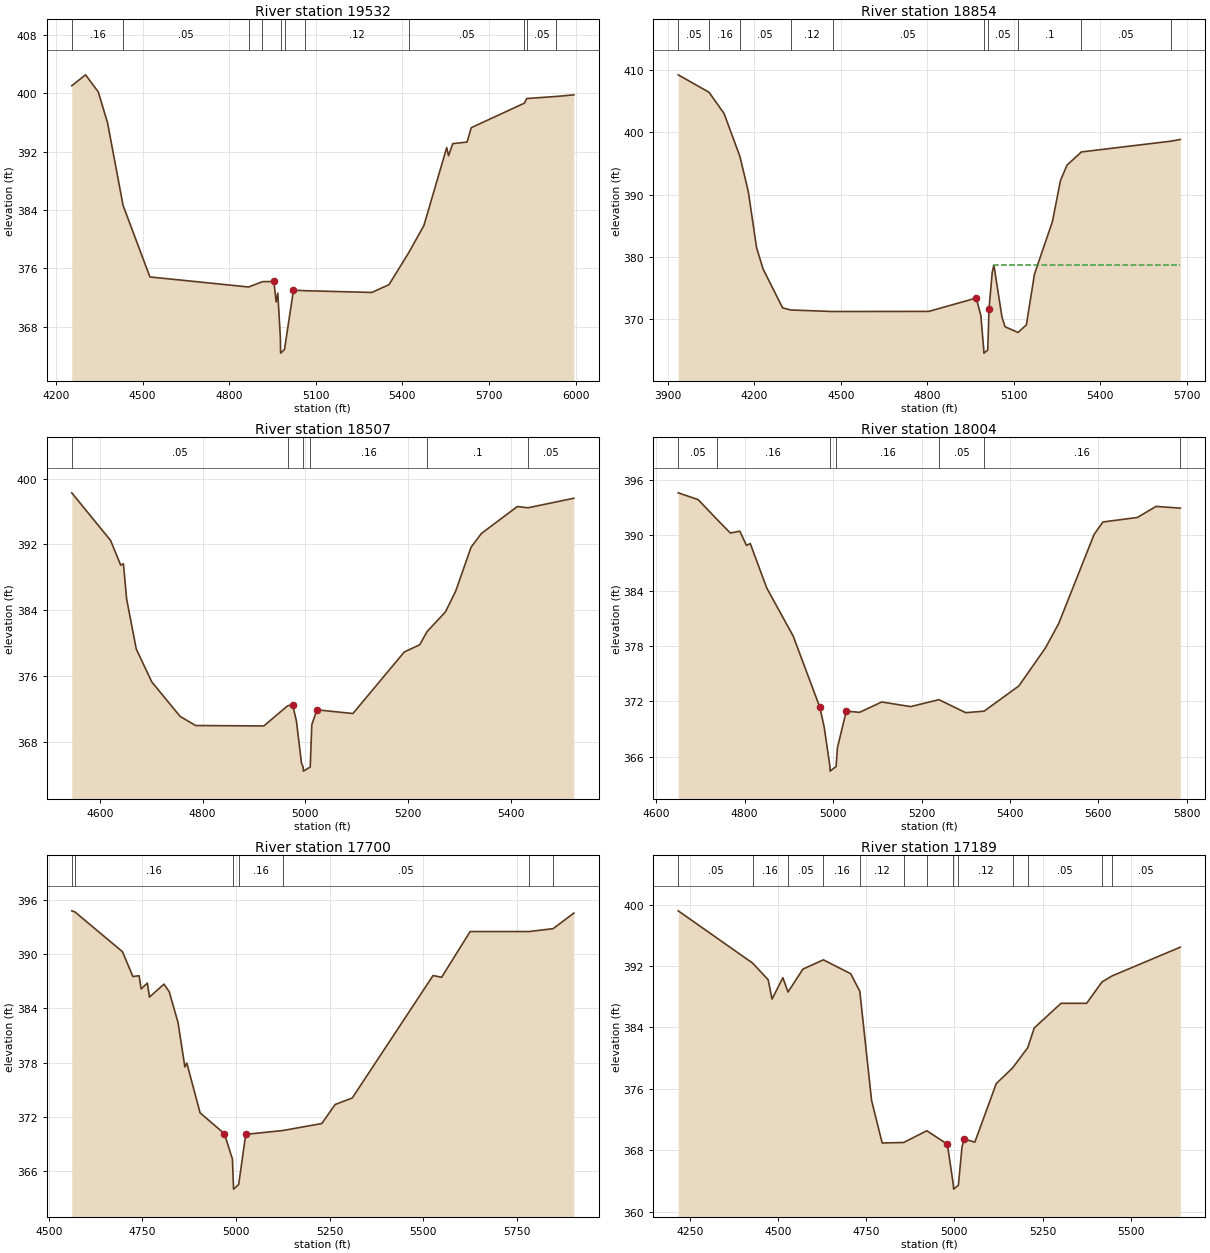
Type RM Length L Ch R = 1 ,19532   ,678,678,678
BEGIN DESCRIPTION:
SOUTH MINERAL CREEK 30 0
END DESCRIPTION:
XS GIS Cut Line= 3
      3513946.08     10373431.25      3514537.24     10372308.83
      3514907.07     10372017.13
#Sta/Elev= 30
  4254.5  401.06  4302.3  402.56  4346.3  400.22  4378.4  395.99  4432.3  384.63
  4525.3  374.81  4867.1  373.43  4915.3  374.16  4954.8  374.19  4962.6  371.37
  4968.3  372.59  4977.4  366.42  4977.8  364.85  4978.3  364.35  4991.6  364.85
  5022.6  372.99  5063.4  372.92  5293.9  372.68  5353.6  373.75  5421.4   378.1
  5474.5  381.86  5553.6  392.57    5560  391.45  5574.5  393.11  5624.1  393.33
  5638.6   395.3  5822.8  398.67  5831.1  399.31  5933.3  399.59  5994.1  399.81
#Mann= 11 ,-1 , 0
  4254.5     .16       0  4432.3     .05       0  4867.1     .16       0
  4915.3     .05       0  4977.8     .07       0  4991.6     .05       0
  5063.4     .12       0  5421.4     .05       0  5822.8     .16       0
  5831.1     .05       0  5933.3     .16       0
Bank Sta=4954.8,5022.6
XS Rating Curve= 0 ,0
Exp/Cntr=0.3,0.1

Type RM Length L Ch R = 1 ,18854   ,347,347,347
BEGIN DESCRIPTION:
SOUTH MINERAL CREEK 3 1
END DESCRIPTION:
XS GIS Cut Line= 3
      3514427.85     10373780.22      3515019.01     10372566.64
      3515328.02     10372327.74
#Sta/Elev= 30
  3936.7  409.23  4043.4  406.43  4095.6  403.02  4150.5  396.13  4179.8  390.43
  4208.3  381.48  4230.9  378.05  4298.5  371.82  4326.2  371.48  4471.9  371.23
  4805.5  371.25  4969.6  373.39  4985.8   370.6  4995.9  365.05  4996.4  364.55
  5009.7  365.05  5014.1  371.67  5025.2  377.52  5030.9   378.7    5059  370.33
  5069.7  368.78  5114.8  367.87  5143.6  369.09  5171.7  377.25  5233.8  385.66
  5261.9  392.28  5284.4  394.73  5334.3  396.85  5644.8  398.58  5677.2  398.85
#Mann= 10 ,-1 , 0
  3936.7     .05       0  4043.4     .16       0  4150.5     .05       0
  4326.2     .12       0  4471.9     .05       0  4995.9    .035       0
  5009.7     .05       0  5114.8      .1       0  5334.3     .05       0
  5644.8     .16       0
#XS Ineff= 2 , 0
                         5029.96          378.68
Permanent Ineff=
       F       F
Bank Sta=4969.6,5014.1
XS Rating Curve= 0 ,0
Exp/Cntr=0.3,0.1

Type RM Length L Ch R = 1 ,18507   ,503,503,503
BEGIN DESCRIPTION:
SOUTH MINERAL CREEK 29 0
END DESCRIPTION:
XS GIS Cut Line= 3
      3514992.11     10373491.62      3515142.11     10373091.64
      3515142.11     10372541.62
#Sta/Elev= 30
  4545.5  398.28  4621.1  392.48  4640.7  389.48    4646  389.65  4652.3  385.35
    4671  379.28  4701.2  375.27  4756.4  371.07  4786.7  369.96  4919.3  369.91
  4965.4  372.35  4975.2  372.51  4982.7  370.53  4992.7  365.35  4995.8  364.91
  4996.3  364.41  5009.6  364.91  5012.7  370.07  5022.7  371.87  5092.7  371.42
  5192.7  378.91  5222.7  379.79  5237.1   381.4  5272.7  383.78  5292.7  386.31
  5322.7  391.66  5342.7  393.33  5412.7  396.61  5433.5  396.46  5522.7  397.62
#Mann= 6 ,-1 , 0
  4545.5     .05       0  4965.4     .16       0  4995.8     .07       0
  5009.6     .16       0  5237.1      .1       0  5433.5     .05       0
Bank Sta=4975.2,5022.7
XS Rating Curve= 0 ,0
Exp/Cntr=0.3,0.1

Type RM Length L Ch R = 1 ,18004   ,304,304,304
BEGIN DESCRIPTION:
SOUTH MINERAL CREEK 28 0
END DESCRIPTION:
XS GIS Cut Line= 3
      3515463.62     10373626.06      3515551.17      10373488.7
      3515513.44     10372516.82
#Sta/Elev= 30
  4649.8  394.59    4695  393.85  4736.9  391.74  4767.8  390.23    4789  390.44
  4804.2  388.89  4812.7   389.1  4849.8   384.3  4909.8  379.07  4969.9  371.38
  4979.9  369.21  4992.9  364.94  4993.4  364.44  5006.8  364.94  5009.9  366.99
  5029.9  370.94  5059.9  370.81    5110  371.93  5175.2  371.43  5239.3  372.18
  5300.1  370.77  5341.7  370.94  5420.2  373.67  5480.2  377.78  5510.3  380.43
  5590.3  390.08  5610.3  391.43  5688.2  391.92  5730.4  393.12  5785.3  392.93
#Mann= 7 ,-1 , 0
  4649.8     .05       0  4736.9     .16       0  4992.9     .07       0
  5006.8     .16       0  5239.3     .05       0  5341.7     .16       0
  5785.3     .05       0
Bank Sta=4969.9,5029.9
XS Rating Curve= 0 ,0
Exp/Cntr=0.3,0.1

Type RM Length L Ch R = 1 ,17700   ,511,511,511
BEGIN DESCRIPTION:
Mapping XS 806c6549
END DESCRIPTION:
XS GIS Cut Line= 3
       3515502.9     10373653.16      3515625.12     10373416.26
      3516666.45     10373147.62
#Sta/Elev= 30
  4561.1  394.79  4569.5  394.67  4696.7  390.27  4724.5  387.53    4741  387.62
  4746.6  386.16  4763.2  386.81  4768.8  385.26  4807.5  386.69  4821.6  385.85
  4845.2  382.44  4863.4  377.54  4868.6  377.97  4904.1  372.47  4969.1  370.16
  4990.6  367.35  4993.1  364.54  4993.6  364.04  5007.2  364.54  5026.1  370.09
  5126.1  370.52  5229.5  371.29    5265  373.39  5310.8  374.11  5526.8  387.64
  5549.7  387.45  5625.9   392.5  5783.4   392.5  5847.7  392.82  5903.1  394.54
#Mann= 7 ,-1 , 0
  4561.1     .05       0  4569.5     .16       0  4993.1     .07       0
  5007.2     .16       0  5126.1     .05       0  5783.4     .16       0
  5847.7     .05       0
Bank Sta=4969.1,5026.1
XS Rating Curve= 0 ,0
Exp/Cntr=0.3,0.1

Type RM Length L Ch R = 1 ,17189   ,456,456,456
BEGIN DESCRIPTION:
SOUTH MINERAL CREEK 27 0
END DESCRIPTION:
XS GIS Cut Line= 3
      3515192.22     10373841.77      3515657.49     10373942.46
      3516535.94      10373588.3
#Sta/Elev= 30
  4217.2  399.18  4428.2  392.37  4472.2   390.2  4483.1  387.69  4513.8  390.47
  4528.4  388.61  4570.6  391.59  4628.6   392.8  4706.2  390.99  4731.9   388.7
  4765.3  374.48  4795.3  368.96  4856.1  369.02  4921.9  370.55  4980.1  368.79
  4997.2  363.45  4997.7  362.95  5011.3  363.45  5021.7  368.48  5028.4  369.47
  5057.9  369.06  5118.7  376.69  5164.8  378.72  5207.7  381.35  5226.5  383.94
  5302.3  387.14  5374.8  387.14  5418.6  389.93  5447.2  390.71  5640.4  394.45
#Mann= 13 ,-1 , 0
  4217.2     .05       0  4428.2     .16       0  4528.4     .05       0
  4628.6     .16       0  4731.9     .12       0  4856.1     .16       0
  4921.9     .12       0  4997.2     .07       0  5011.3     .12       0
  5164.8      .1       0  5207.7     .05       0  5418.6     .12       0
  5447.2     .05       0
Bank Sta=4980.1,5028.4
XS Rating Curve= 0 ,0
Exp/Cntr=0.3,0.1

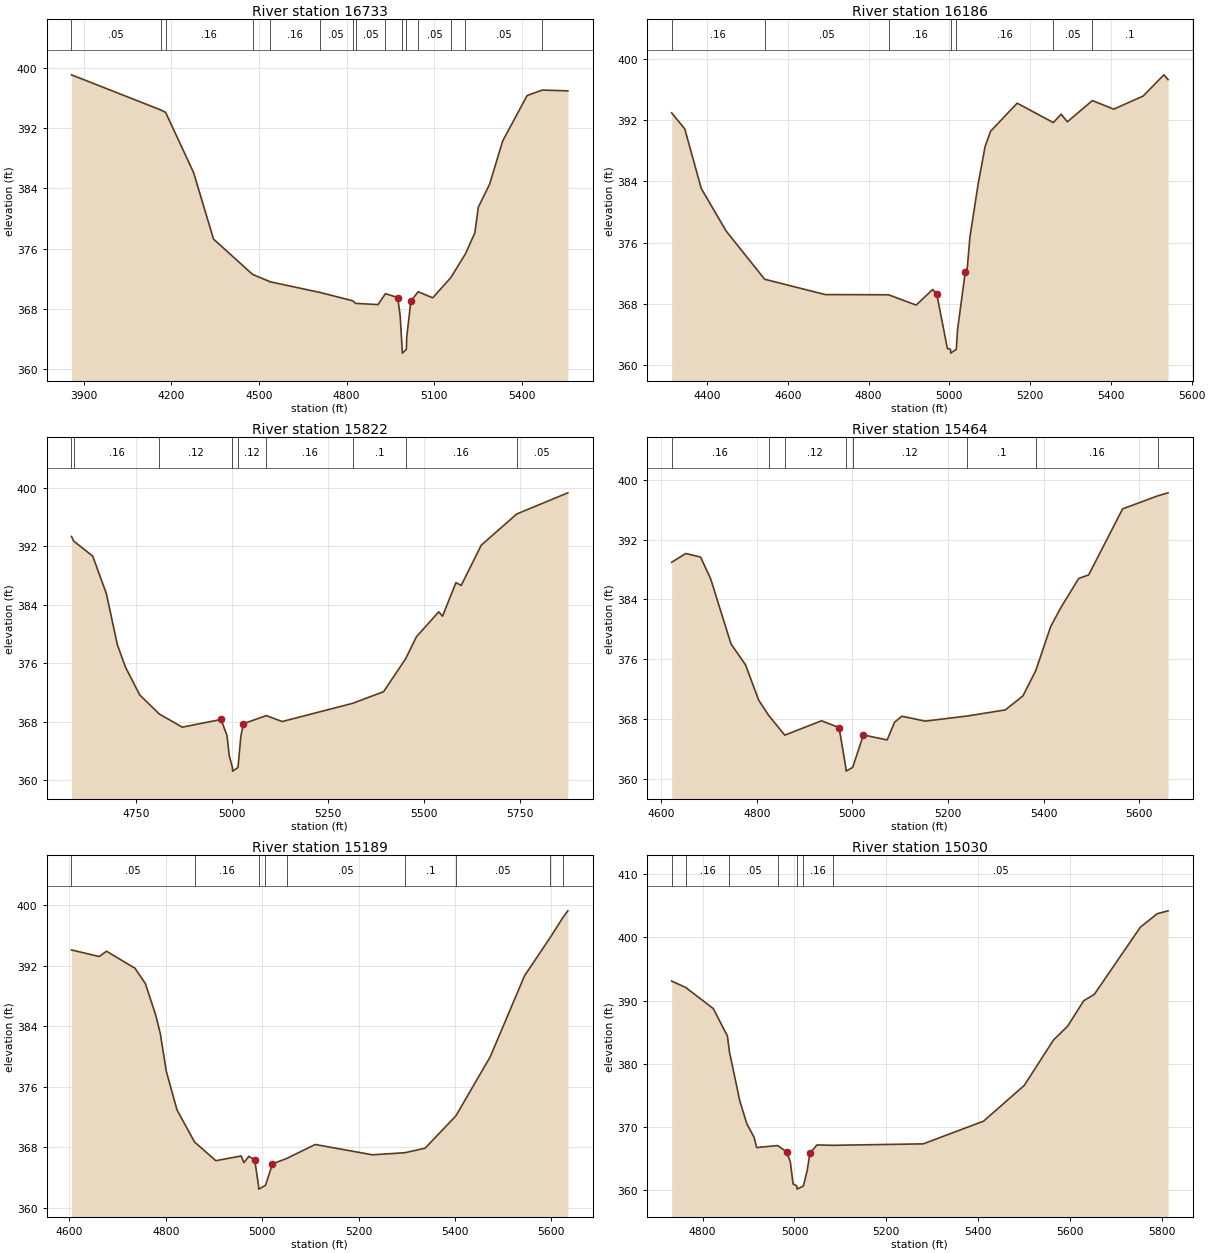
Type RM Length L Ch R = 1 ,16733   ,547,547,547
BEGIN DESCRIPTION:
SOUTH MINERAL CREEK 26 0
END DESCRIPTION:
XS GIS Cut Line= 3
      3515407.47     10374876.53      3515650.55     10374452.88
      3516737.21     10373918.23
#Sta/Elev= 30
    3858  399.12  4164.2  394.44  4180.2  394.13  4276.1  386.12  4344.3  377.27
  4477.9  372.57  4538.6  371.58  4708.1  370.17  4820.4  369.06  4830.8  368.71
  4907.6  368.55  4932.8     370    4975  369.49  4983.4  367.04  4990.3  362.59
  4990.8  362.09  5004.6  362.59  5005.7  364.15  5019.9     369  5045.1  370.26
  5094.9  369.45  5157.4  372.17    5207  375.31  5239.1   378.1  5250.9   381.5
  5289.6  384.57  5334.5  390.33  5418.1  396.36  5469.6  397.09  5557.5  396.99
#Mann= 15 ,-1 , 0
    3858     .05       0  4164.2      .1       0  4180.2     .16       0
  4477.9     .05       0  4538.6     .16       0  4708.1     .05       0
  4820.4     .16       0  4830.8     .05       0  4932.8     .12       0
  4990.3     .07       0  5004.6     .12       0  5045.1     .05       0
  5157.4      .1       0    5207     .05       0  5469.6      .1       0
Bank Sta=4975,5019.9
XS Rating Curve= 0 ,0
Exp/Cntr=0.3,0.1

Type RM Length L Ch R = 1 ,16186   ,364,364,364
BEGIN DESCRIPTION:
SOUTH MINERAL CREEK 25 0
END DESCRIPTION:
XS GIS Cut Line= 3
      3515730.41     10374820.93      3516549.85     10374643.85
      3516760.81      10374315.3
#Sta/Elev= 30
  4312.7  392.91  4345.1  390.83    4386  383.05  4447.4  377.51  4542.9  371.21
    4693  369.21  4849.5  369.18    4918  367.84    4959  369.88  4969.2  369.22
  4995.3  362.17    5003  362.07  5003.5  361.57  5017.3  362.07  5020.4  364.61
  5039.4   372.1  5044.5  372.68  5051.1  376.73  5071.5  383.67  5088.7  388.54
  5102.2  390.52    5168  394.18  5257.5  391.65    5277  392.75  5292.2  391.75
  5354.2  394.52  5407.1   393.4  5479.8  395.11  5531.3  397.88  5541.5  397.25
#Mann= 7 ,-1 , 0
  4312.7     .16       0  4542.9     .05       0  4849.5     .16       0
    5003     .07       0  5017.3     .16       0  5257.5     .05       0
  5354.2      .1       0
Bank Sta=4969.2,5039.4
XS Rating Curve= 0 ,0
Exp/Cntr=0.3,0.1

Type RM Length L Ch R = 1 ,15822   ,358,358,358
BEGIN DESCRIPTION:
SOUTH MINERAL CREEK 24 0
END DESCRIPTION:
XS GIS Cut Line= 2
       3516074.2     10375247.99      3517181.76     10374581.37
#Sta/Elev= 30
    4582  393.34    4588  392.71  4637.4  390.65  4672.9  385.51  4701.5  378.52
  4722.9  375.42  4759.8  371.65  4810.8  369.04  4870.5  367.24  4971.5  368.29
    4987   366.1  4992.9  363.33  5001.2  361.72  5001.7  361.22  5015.6  361.72
  5023.1  365.99  5029.8  367.72  5089.4  368.82  5130.8  368.01  5314.8  370.51
  5394.9   372.1  5452.5  376.63  5480.4  379.62  5538.6  383.03  5548.3  382.43
  5583.3  387.03  5596.9  386.64  5649.3  392.16  5741.5  396.42  5874.7  399.32
#Mann= 9 ,-1 , 0
    4582     .05       0    4588     .16       0  4810.8     .12       0
  5001.2     .07       0  5015.6     .12       0  5089.4     .16       0
  5314.8      .1       0  5452.5     .16       0  5741.5     .05       0
Bank Sta=4971.5,5029.8
XS Rating Curve= 0 ,0
Exp/Cntr=0.3,0.1

Type RM Length L Ch R = 1 ,15464   ,275,275,275
BEGIN DESCRIPTION:
SOUTH MINERAL CREEK 23 0
END DESCRIPTION:
XS GIS Cut Line= 3
      3516532.48     10375543.18      3516976.94     10374820.93
      3517118.18     10374693.47
#Sta/Elev= 30
  4621.9  388.97  4651.4  390.13  4682.3  389.66  4703.5  386.75  4746.1  378.05
  4776.3  375.29  4804.1  370.54  4824.7  368.54  4858.5  365.89  4935.4  367.81
  4972.1   366.9  4986.2  361.59  4986.7  361.09  5000.6  361.59  5022.9  365.92
  5072.7  365.25  5088.1  367.62  5103.5  368.42  5152.1  367.76  5240.5  368.45
    5320  369.26  5356.7  371.14  5383.5   374.5  5414.7  380.38  5435.9   382.9
  5473.3   386.8  5494.2  387.28  5565.2  396.09  5639.2  397.84  5660.2  398.23
#Mann= 8 ,-1 , 0
  4621.9     .16       0  4824.7     .05       0  4858.5     .12       0
  4986.2     .07       0  5000.6     .12       0  5240.5      .1       0
  5383.5     .16       0  5639.2     .05       0
Bank Sta=4972.1,5022.9
XS Rating Curve= 0 ,0
Exp/Cntr=0.3,0.1

Type RM Length L Ch R = 1 ,15189   ,159,159,159
BEGIN DESCRIPTION:
SOUTH MINERAL CREEK 22 0
END DESCRIPTION:
XS GIS Cut Line= 3
      3516742.08     10375741.68      3516942.11     10375391.64
      3517242.13      10374841.6
#Sta/Elev= 30
  4604.4  394.07    4662   393.2  4677.1   393.9  4736.2  391.65  4757.8  389.61
  4779.4   385.4  4788.7     383    4801  378.06  4823.3  372.92  4859.7  368.68
  4903.9  366.21  4956.4  366.83  4962.2  365.95  4972.3  366.79  4984.5  366.31
  4992.4  362.95  4992.9  362.45  5006.8  362.95  5021.3  365.79  5050.7   366.5
  5110.1  368.35  5228.3  366.99  5295.7  367.26  5337.9  367.86  5401.8  372.13
  5473.2  379.96  5544.3  390.66    5598  395.76  5624.3   398.4  5634.1  399.24
#Mann= 9 ,-1 , 0
  4604.4     .05       0  4859.7     .16       0  4992.4     .07       0
  5006.8     .16       0  5050.7     .05       0  5295.7      .1       0
  5401.8     .05       0    5598      .1       0  5624.3     .05       0
Bank Sta=4984.5,5021.3
XS Rating Curve= 0 ,0
Exp/Cntr=0.3,0.1

Type RM Length L Ch R = 1 ,15030   ,259,259,259
BEGIN DESCRIPTION:
SOUTH MINERAL CREEK 21 1
END DESCRIPTION:
XS GIS Cut Line= 2
      3516890.15     10375754.93      3517459.02     10374835.72
#Sta/Elev= 30
  4732.5  393.09    4763  392.08  4823.1  388.74  4853.9   384.4  4858.2  381.93
    4881   374.1  4896.4  370.47  4911.8  368.41  4917.7  366.76  4963.6  367.07
  4983.3  366.04    4991  364.45  4996.9     361    5005  360.68  5005.5  360.18
  5019.4  360.68  5027.6  363.11  5033.5  365.84  5048.9  367.17  5083.6  367.11
  5280.5  367.34  5411.7  370.93  5500.4  376.59  5564.1  383.77  5594.9  385.96
  5630.1     390  5652.8  390.97  5753.2  401.61  5789.9  403.74  5813.5   404.2
#Mann= 7 ,-1 , 0
  4732.5     .05       0    4763     .16       0  4858.2     .05       0
  4963.6     .16       0    5005     .07       0  5019.4     .16       0
  5083.6     .05       0
Bank Sta=4983.3,5033.5
XS Rating Curve= 0 ,0
Exp/Cntr=0.3,0.1

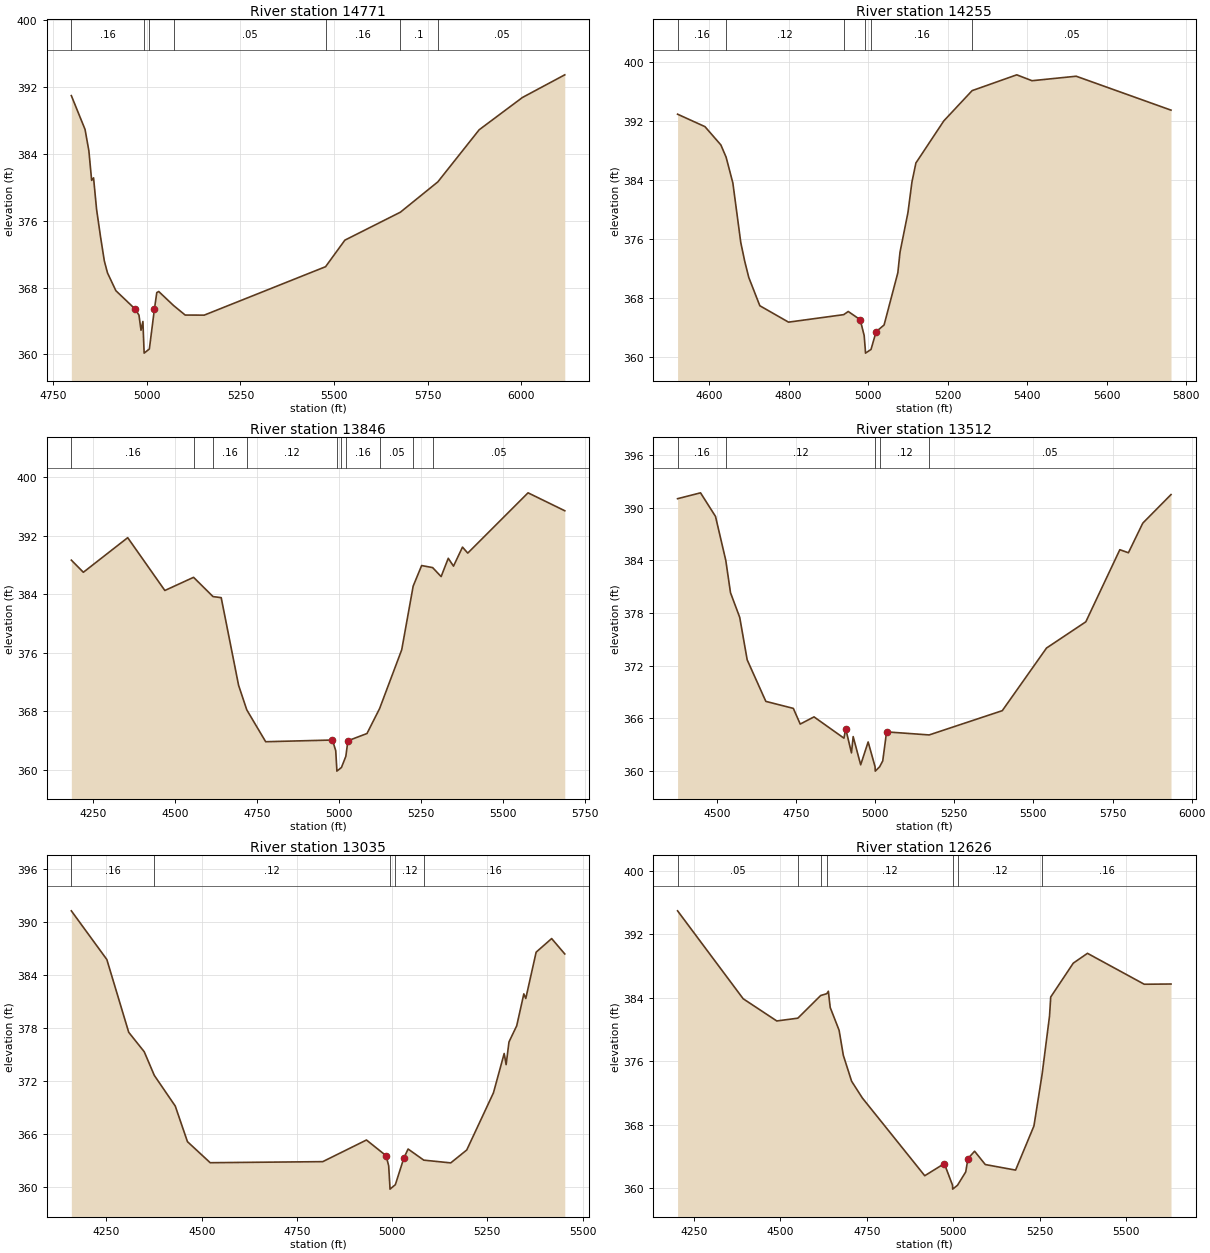
Type RM Length L Ch R = 1 ,14771   ,516,516,516
BEGIN DESCRIPTION:
SOUTH MINERAL CREEK 21 0
END DESCRIPTION:
XS GIS Cut Line= 3
      3516936.54     10375809.68      3517431.35     10375692.06
      3518234.29     10375600.92
#Sta/Elev= 30
  4798.8  390.99  4835.4  386.94  4845.6  384.38    4853  380.84  4858.1  381.14
  4866.2  377.35  4876.5  374.15  4886.8   371.2  4895.2  369.77  4917.6  367.63
    4969  365.43  4979.3   364.7  4984.7  362.89  4989.8  363.94  4992.6  360.65
  4993.1  360.15    5007  360.65  5020.4  365.39  5026.8   367.4    5032  367.53
  5071.6  365.85  5102.6  364.71  5153.4   364.7  5477.2   370.5  5528.7  373.68
  5676.9  377.03  5776.8  380.66  5887.1   386.9  6002.6  390.77  6115.5  393.48
#Mann= 7 ,-1 , 0
  4798.8     .16       0  4992.6     .07       0    5007     .16       0
  5071.6     .05       0  5477.2     .16       0  5676.9      .1       0
  5776.8     .05       0
Bank Sta=4969,5020.4
XS Rating Curve= 0 ,0
Exp/Cntr=0.3,0.1

Type RM Length L Ch R = 1 ,14255   ,409,409,409
BEGIN DESCRIPTION:
SOUTH MINERAL CREEK 20 0
END DESCRIPTION:
XS GIS Cut Line= 3
      3516803.29     10376268.85       3517518.6     10376227.18
      3518038.31     10376303.41
#Sta/Elev= 30
  4520.5  392.94  4589.4  391.25  4629.5  388.76  4642.7  387.09  4659.6   383.6
  4679.6  375.49  4689.6  372.93  4699.6  370.77  4727.5  366.91  4799.8  364.68
  4938.6   365.7    4950  366.13  4980.1  365.01  4990.1  362.86  4992.9  360.97
  4993.4  360.47  5007.3  360.97  5020.2  363.39  5040.2  364.29  5074.8  371.39
  5080.3  374.19  5100.3  379.58  5110.3  383.72  5120.3  386.31  5190.5  392.03
  5261.7  396.14  5374.1  398.29  5412.4  397.49  5523.6   398.1  5762.3  393.49
#Mann= 6 ,-1 , 0
  4520.5     .16       0  4642.7     .12       0  4938.6     .16       0
  4992.9     .07       0  5007.3     .16       0  5261.7     .05       0
Bank Sta=4980.1,5020.2
XS Rating Curve= 0 ,0
Exp/Cntr=0.3,0.1

Type RM Length L Ch R = 1 ,13846   ,334,334,334
BEGIN DESCRIPTION:
Mapping XS 702a465e
END DESCRIPTION:
XS GIS Cut Line= 4
      3516636.64     10376425.09      3516973.46     10376709.82
       3517556.8     10376602.18      3517966.53     10376373.01
#Sta/Elev= 30
  4184.8  388.68  4221.4  387.02  4356.6  391.75  4469.8  384.53  4557.3  386.33
  4616.5   383.7  4641.5  383.55  4694.5  371.57  4719.5  368.21    4777  363.86
  4980.4  364.09  4990.5  362.64  4993.5  360.34    4994  359.84  5007.9  360.34
  5021.3  361.86  5027.6  363.99  5085.7  364.98  5124.3   368.4  5191.6  376.43
  5226.5  385.13  5252.3  387.94  5285.8  387.66  5311.7  386.43  5333.4  388.93
  5349.4  387.86  5376.8  390.46  5392.8  389.64  5576.6  397.88  5688.5  395.43
#Mann= 10 ,-1 , 0
  4184.8     .16       0  4557.3     .12       0  4616.5     .16       0
  4719.5     .12       0  4993.5     .07       0  5007.9     .12       0
  5021.3     .16       0  5124.3     .05       0  5226.5     .16       0
  5285.8     .05       0
Bank Sta=4980.4,5027.6
XS Rating Curve= 0 ,0
Exp/Cntr=0.3,0.1

Type RM Length L Ch R = 1 ,13512   ,477,477,477
BEGIN DESCRIPTION:
SOUTH MINERAL CREEK 2 0
END DESCRIPTION:
XS GIS Cut Line= 3
      3516855.44     10377202.86      3517542.91     10376911.21
      3518317.12     10376666.64
#Sta/Elev= 30
  4376.1  391.04  4448.6  391.71  4495.9  389.02  4528.4     384  4543.3  380.31
  4572.4   377.5    4596  372.65  4654.9  367.91  4741.8  367.11  4763.5  365.32
  4807.1  366.14  4901.7  363.71  4907.2  364.78  4925.4  362.03  4930.8  363.89
  4954.5  360.67  4978.1  363.28    5000  360.45  5000.5  359.95  5014.4  360.45
  5024.2  361.12  5036.3  364.43  5170.8  364.08  5401.8  366.85  5541.6     374
  5665.7  376.99  5773.1  385.22  5800.2  384.87  5845.6  388.25  5934.8  391.51
#Mann= 5 ,-1 , 0
  4376.1     .16       0  4528.4     .12       0    5000     .07       0
  5014.4     .12       0  5170.8     .05       0
Bank Sta=4907.2,5036.3
XS Rating Curve= 0 ,0
Exp/Cntr=0.3,0.1

Type RM Length L Ch R = 1 ,13035   ,409,409,409
BEGIN DESCRIPTION:
SOUTH MINERAL CREEK 19 0
END DESCRIPTION:
XS GIS Cut Line= 2
      3516794.19     10377544.17      3518065.95     10377296.76
#Sta/Elev= 30
  4157.7  391.26  4250.9  385.75  4308.4  377.51  4349.1  375.31  4375.6  372.63
  4430.6  369.16  4462.6  365.13  4522.3  362.75  4817.8  362.87  4932.6  365.32
  4984.2  363.54  4990.9   362.4  4993.9  360.26  4994.4  359.76  5008.4  360.26
  5030.8  363.28  5041.9   364.3  5083.1  363.04  5153.9  362.73  5195.9  364.19
    5266  370.66  5294.2  375.11  5299.3  373.85  5306.8  376.42  5327.1  378.25
  5345.8  381.86  5350.9  381.34  5378.1  386.58  5418.8  388.12  5453.3  386.38
#Mann= 5 ,-1 , 0
  4157.7     .16       0  4375.6     .12       0  4993.9     .07       0
  5008.4     .12       0  5083.1     .16       0
Bank Sta=4984.2,5030.8
XS Rating Curve= 0 ,0
Exp/Cntr=0.3,0.1

Type RM Length L Ch R = 1 ,12626   ,474,474,474
BEGIN DESCRIPTION:
SOUTH MINERAL CREEK 18 0
END DESCRIPTION:
XS GIS Cut Line= 4
      3517009.04     10378097.56      3517375.81     10377893.56
      3517998.64     10377674.37      3518076.67     10377336.22
#Sta/Elev= 30
    4203  394.95  4392.7  383.86  4489.9  381.06  4550.8  381.41  4616.9  384.27
  4634.5   384.5  4639.1  384.81  4644.4  382.76  4670.1  379.89  4682.4  376.72
  4706.3  373.46  4737.3  371.35  4917.8  361.54  4974.4  363.07  4998.1  360.35
  4998.6  359.85  5012.7  360.35  5036.3  362.02  5042.8  363.71    5062  364.63
  5092.9  362.95  5180.5  362.25  5233.6  367.82  5257.3  374.37  5278.7  381.69
  5282.1  384.08  5347.3  388.35  5388.4  389.59  5552.6  385.69    5630  385.72
#Mann= 7 ,-1 , 0
    4203     .05       0  4550.8     .12       0  4616.9     .16       0
  4634.5     .12       0  4998.1     .07       0  5012.7     .12       0
  5257.3     .16       0
#XS Ineff= 2 , 0
         4636.28  383.97
Permanent Ineff=
       F       F
Bank Sta=4974.4,5042.8
XS Rating Curve= 0 ,0
Exp/Cntr=0.3,0.1