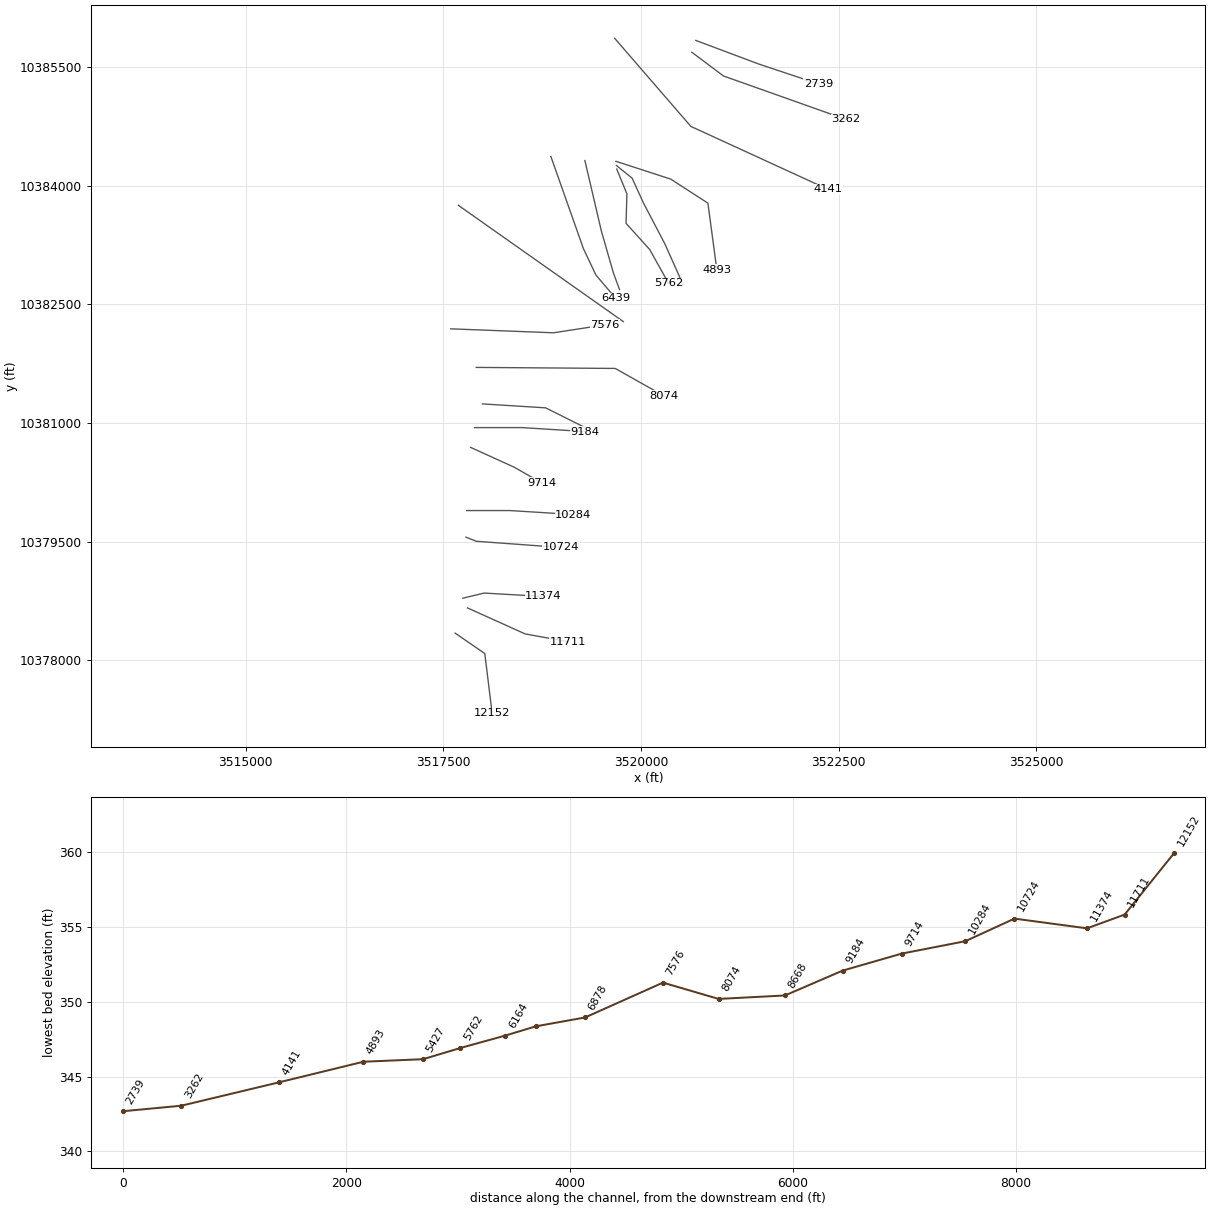
HEC-RAS study SOUTH MINERAL CREEK.prj: SOUTH MINERAL CREEK Base Level Engineering

--- SOUTH MINERAL CREEK.g01 (geometry) --- (continued)

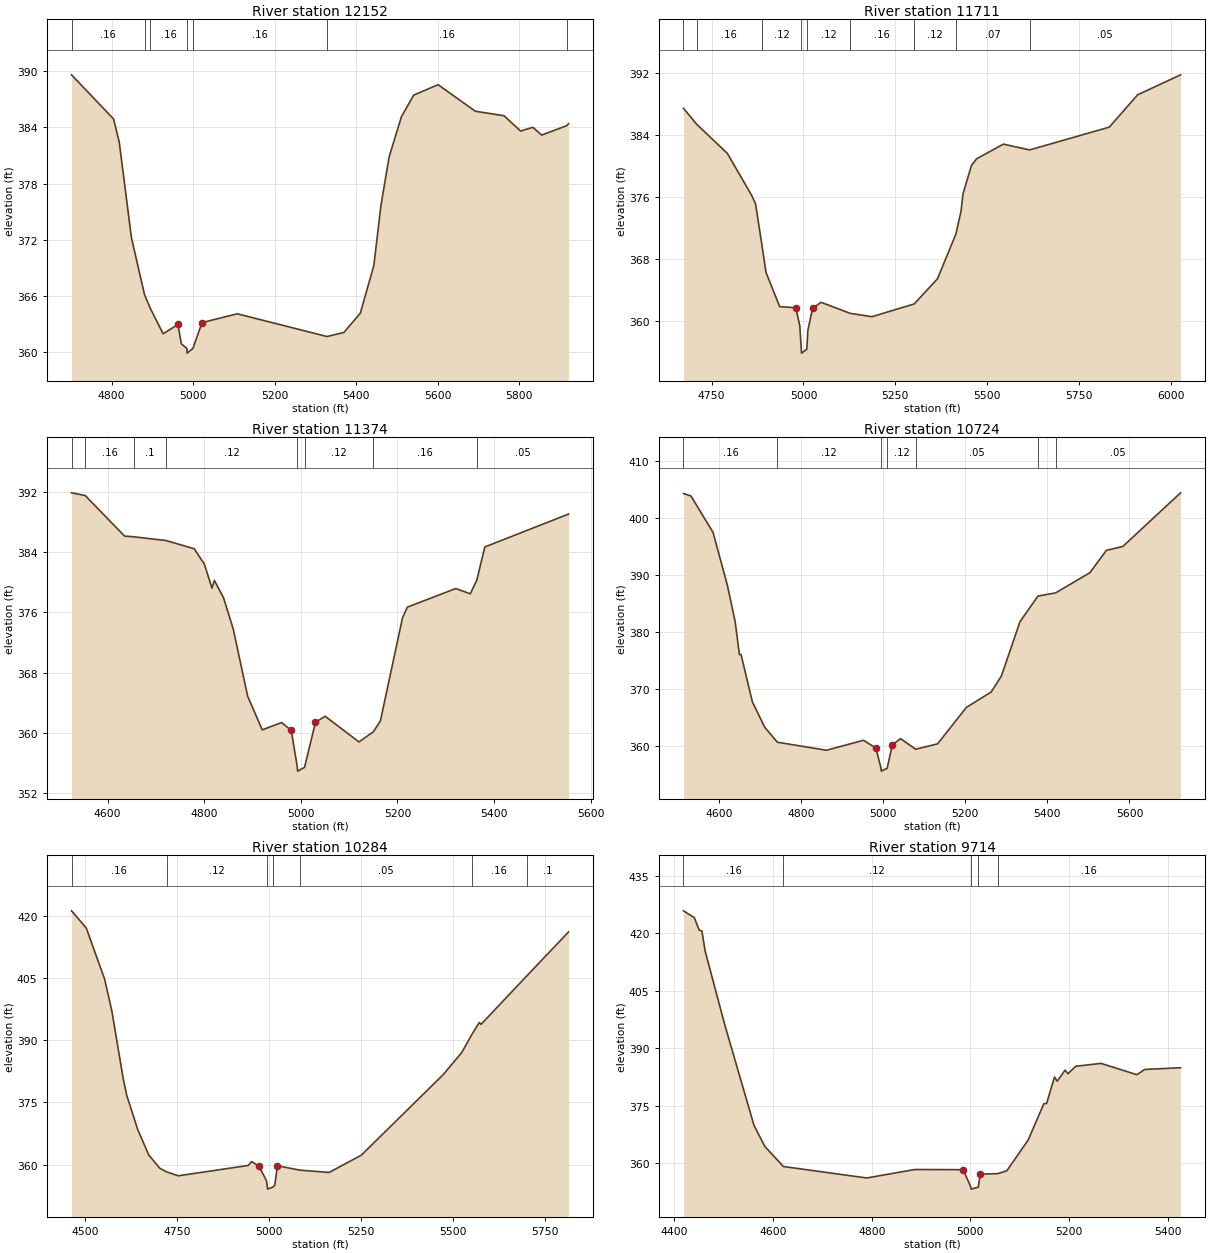
Type RM Length L Ch R = 1 ,12152   ,441,441,441
BEGIN DESCRIPTION:
Mapping XS 7424fb5b
END DESCRIPTION:
XS GIS Cut Line= 3
       3517647.1     10378340.59      3518022.51     10378082.36
      3518115.59     10377324.71
#Sta/Elev= 30
  4701.6  389.58  4804.8  384.87  4818.7   382.4  4848.5  372.23  4880.7  366.15
  4894.6  364.72  4926.3  361.99  4962.6  362.98  4970.9  360.92  4984.6  360.43
  4985.1  359.93  4999.2  360.43  5021.7  363.18  5108.2  364.12  5327.9   361.7
  5369.6  362.13  5409.9  364.19    5443  369.26  5460.2  375.58  5480.4  380.82
  5510.6  385.11  5540.8  387.42  5600.6  388.53    5692   385.7  5762.5  385.22
  5802.8  383.59    5833  383.99  5854.6  383.16  5915.9  384.16  5920.6  384.38
#Mann= 7 ,-1 , 0
  4701.6     .16       0  4880.7     .12       0  4894.6     .16       0
  4984.6     .07       0  4999.2     .16       0  5327.9     .16       0
  5915.9     .05       0
Bank Sta=4962.6,5021.7
XS Rating Curve= 0 ,0
Exp/Cntr=0.3,0.1

Type RM Length L Ch R = 1 ,11711   ,337,337,337
BEGIN DESCRIPTION:
Mapping XS c13c6141
END DESCRIPTION:
XS GIS Cut Line= 3
      3517803.37      10378659.6      3518534.66     10378329.76
      3519077.11     10378232.12
#Sta/Elev= 30
  4673.3  387.49    4709  385.44  4792.6  381.67  4858.4  376.28  4869.4  375.17
    4886  370.07  4898.1  366.26  4935.2  361.85  4979.1  361.71    4990  359.36
  4994.1  356.34  4994.6  355.84    5009  356.34    5012   358.8  5024.7  361.61
  5047.9  362.41  5127.4  360.98  5186.6  360.55  5301.4   362.2    5365  365.46
    5415  371.24  5428.9  374.17  5434.4  376.45  5457.5  380.12  5471.4  380.96
  5544.1  382.86  5615.8  382.11  5832.7  385.06  5909.9  389.24  6026.7  391.82
#Mann= 9 ,-1 , 0
  4673.3      .1       0    4709     .16       0    4886     .12       0
  4994.1     .07       0    5009     .12       0  5127.4     .16       0
  5301.4     .12       0    5415     .07       0  5615.8     .05       0
Bank Sta=4979.1,5024.7
XS Rating Curve= 0 ,0
Exp/Cntr=0.3,0.1

Type RM Length L Ch R = 1 ,11374   ,650,650,650
BEGIN DESCRIPTION:
SOUTH MINERAL CREEK 17 0
END DESCRIPTION:
XS GIS Cut Line= 3
      3517745.28     10378782.41      3518014.37     10378847.52
      3518765.26     10378804.11
#Sta/Elev= 30
  4525.2  391.88  4553.6  391.52  4635.1  386.13  4654.3  386.04  4721.2  385.54
  4779.2  384.45  4800.2  382.41    4816  379.22    4821  380.24  4839.9  377.94
  4859.9  373.81  4889.9  364.86    4920   360.4  4960.1  361.37  4980.1  360.34
  4992.7  355.42  4993.2  354.92  5007.6  355.42  5030.2   361.4  5050.2  362.21
  5120.3   358.8    5150  360.14  5164.6  361.58  5210.5  375.31  5220.5   376.7
  5320.7  379.17  5350.7  378.47  5364.2  380.27  5380.8  384.69  5554.2  389.06
#Mann= 8 ,-1 , 0
  4525.2     .05       0  4553.6     .16       0  4654.3      .1       0
  4721.2     .12       0  4992.7     .07       0  5007.6     .12       0
    5150     .16       0  5364.2     .05       0
Bank Sta=4980.1,5030.2
XS Rating Curve= 0 ,0
Exp/Cntr=0.3,0.1

Type RM Length L Ch R = 1 ,10724   ,440,440,440
BEGIN DESCRIPTION:
SOUTH MINERAL CREEK 16 0
END DESCRIPTION:
XS GIS Cut Line= 3
      3517784.37     10379554.97      3517914.55      10379502.9
      3518982.29     10379424.77
#Sta/Elev= 30
  4513.6  404.23  4531.7   403.8  4585.5  397.43  4620.5  388.15  4639.4  381.78
  4649.8  376.01  4653.8  376.01  4681.4   367.7  4711.5  363.26  4742.1  360.64
  4861.9  359.23  4952.2  360.98  4982.2   359.6  4994.8  356.07  4995.3  355.57
  5009.7  356.07  5022.3  360.17  5042.4  361.27    5079  359.41  5132.6  360.35
  5202.8  366.75    5263  369.43  5287.9  372.23  5333.2  381.75  5377.1  386.26
    5420  386.81  5503.6  390.35  5543.7  394.27  5583.8  394.95  5724.4  404.35
#Mann= 7 ,-1 , 0
  4513.6     .16       0  4742.1     .12       0  4994.8     .07       0
  5009.7     .12       0    5079     .05       0  5377.1     .16       0
    5420     .05       0
Bank Sta=4982.2,5022.3
XS Rating Curve= 0 ,0
Exp/Cntr=0.3,0.1

Type RM Length L Ch R = 1 ,10284   ,570,570,570
BEGIN DESCRIPTION:
SOUTH MINERAL CREEK 15 0
END DESCRIPTION:
XS GIS Cut Line= 3
      3517792.13     10379891.64      3518342.11     10379891.64
      3519142.07     10379841.64
#Sta/Elev= 30
  4463.3   421.3  4503.3  417.16  4553.3   404.8  4573.3  396.95  4603.3  381.04
  4613.3  376.75  4643.3  368.47  4673.3  362.31  4703.3  359.11  4721.9  358.23
  4753.3  357.28  4943.3  359.77  4953.3  360.72  4973.3  359.54  4993.3  356.12
  4995.8  354.56  4996.3  354.06  5010.7  354.56  5015.8  354.97  5023.3   359.7
  5084.5  358.64  5163.6  358.09  5251.2  362.26  5474.2  381.75  5524.3  387.07
  5551.3  391.34  5571.9  394.32  5576.9  393.88  5700.9  405.55  5814.8  416.21
#Mann= 7 ,-1 , 0
  4463.3     .16       0  4721.9     .12       0  4995.8     .07       0
  5010.7     .12       0  5084.5     .05       0  5551.3     .16       0
  5700.9      .1       0
Bank Sta=4973.3,5023.3
XS Rating Curve= 0 ,0
Exp/Cntr=0.3,0.1

Type RM Length L Ch R = 1 ,9714    ,530,530,530
BEGIN DESCRIPTION:
SOUTH MINERAL CREEK 14 0
END DESCRIPTION:
XS GIS Cut Line= 3
      3517842.14     10380691.62      3518392.11     10380441.64
      3518742.09     10380241.65
#Sta/Elev= 30
  4418.6  425.83  4440.5  424.05  4450.4   420.8  4455.9  420.58  4462.5  415.32
    4502  396.21  4561.4  369.89  4583.3  364.39    4621  359.13  4789.8  356.14
  4887.6  358.35  4985.4   358.3    5001  353.73  5001.5  353.23  5015.9  353.73
    5020  357.13  5055.9  357.28  5073.8  358.02    5117  366.04  5148.7   375.5
  5154.4  375.58  5170.3  382.46    5176   381.4  5191.9  384.29  5197.6  383.32
  5213.5  385.28  5264.6  386.03  5337.3  383.08  5353.1  384.45  5425.8   384.9
#Mann= 5 ,-1 , 0
  4418.6     .16       0    4621     .12       0    5001     .07       0
  5015.9     .12       0  5055.9     .16       0
Bank Sta=4985.4,5020
XS Rating Curve= 0 ,0
Exp/Cntr=0.3,0.1

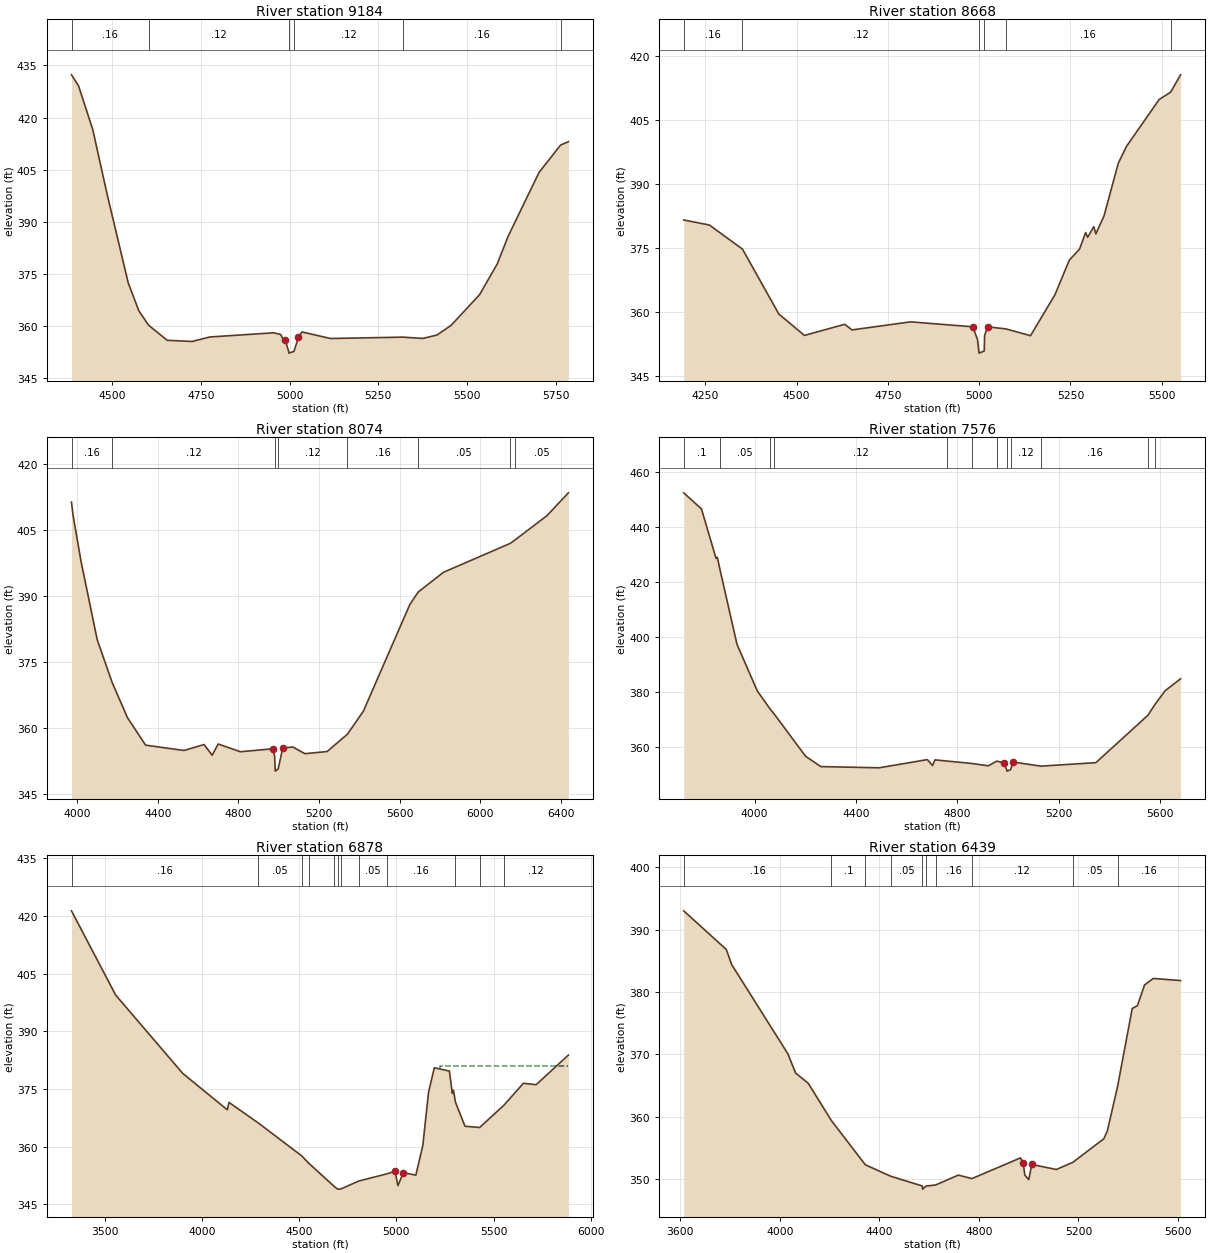
Type RM Length L Ch R = 1 ,9184    ,516,516,516
BEGIN DESCRIPTION:
SOUTH MINERAL CREEK 13 0
END DESCRIPTION:
XS GIS Cut Line= 3
      3517892.09     10380941.64      3518492.11     10380941.64
      3519292.13     10380891.64
#Sta/Elev= 30
  4384.7  432.31  4404.7  429.09  4444.7  416.52  4484.7  398.09  4544.7  372.33
  4574.7   364.3  4602.2  360.13  4654.7  355.79  4724.7  355.45  4774.7  356.74
  4954.7  357.95  4974.7  357.47  4982.2  355.99  4987.2  355.99  4997.3  352.59
  4997.8  352.09  5012.2  352.59  5024.8  356.62  5034.8   358.2    5115  356.31
  5319.9   356.7  5375.5  356.32  5415.6   357.3  5455.6   360.1  5535.8  368.94
  5585.9  377.83  5615.9  385.66  5703.6  404.18  5764.4  412.07  5786.3  413.03
#Mann= 6 ,-1 , 0
  4384.7     .16       0  4602.2     .12       0  4997.3     .07       0
  5012.2     .12       0  5319.9     .16       0  5764.4     .05       0
Bank Sta=4987.2,5024.8
XS Rating Curve= 0 ,0
Exp/Cntr=0.3,0.1

Type RM Length L Ch R = 1 ,8668    ,594,594,594
BEGIN DESCRIPTION:
SOUTH MINERAL CREEK 12 0
END DESCRIPTION:
XS GIS Cut Line= 3
      3517992.11     10381241.64      3518792.11     10381191.64
      3519292.13     10380941.63
#Sta/Elev= 30
  4190.9  381.64    4261  380.46  4351.8  374.81  4451.4  359.59  4521.5  354.58
  4631.8  357.19  4651.8  355.87  4812.1  357.76  4982.4   356.6  4995.3  353.68
    4999  350.93  4999.5  350.43  5013.9  350.93  5014.8  354.56  5023.2   356.6
  5073.6   356.1  5140.6  354.52  5207.7  364.14  5246.8  372.23  5274.8   374.8
  5291.5  378.69  5297.1  377.57  5313.9  380.07  5319.5  378.39  5341.8  382.57
    5381  394.95  5403.3  398.87  5492.8  409.86  5524.4   411.6  5551.5  415.65
#Mann= 6 ,-1 , 0
  4190.9     .16       0  4351.8     .12       0    4999     .07       0
  5013.9     .12       0  5073.6     .16       0  5524.4     .05       0
Bank Sta=4982.4,5023.2
XS Rating Curve= 0 ,0
Exp/Cntr=0.3,0.1

Type RM Length L Ch R = 1 ,8074    ,498,498,498
BEGIN DESCRIPTION:
SOUTH MINERAL CREEK 92 0
END DESCRIPTION:
XS GIS Cut Line= 3
      3517914.53     10381703.42      3519672.36      10381690.4
      3520287.91     10381343.61
#Sta/Elev= 30
    3972  411.39  3979.6  408.42  4019.6  397.84  4099.6  380.08  4174.1  370.31
  4249.6  362.36  4339.6  356.11  4529.6   354.9  4629.6  356.25  4669.6  353.82
  4699.6  356.37  4809.6  354.61  4969.6  355.28  4979.6  353.63  4982.2   350.7
  4982.7   350.2  4997.1   350.7  5019.6  355.47  5069.6  355.69  5129.6  354.17
  5239.6  354.65  5340.6   358.6  5419.6  363.83  5649.6  388.05  5691.4  390.94
  5817.3  395.44  6148.8  402.02  6172.7  402.82  6330.3  408.32  6436.4  413.51
#Mann= 8 ,-1 , 0
    3972     .16       0  4174.1     .12       0  4982.2     .07       0
  4997.1     .12       0  5340.6     .16       0  5691.4     .05       0
  6148.8      .1       0  6172.7     .05       0
Bank Sta=4969.6,5019.6
XS Rating Curve= 0 ,0
Exp/Cntr=0.3,0.1

Type RM Length L Ch R = 1 ,7576    ,698,698,698
BEGIN DESCRIPTION:
SOUTH MINERAL CREEK 9 0
END DESCRIPTION:
XS GIS Cut Line= 3
      3517592.15     10382191.64      3518892.11     10382141.64
      3519542.14     10382241.65
#Sta/Elev= 30
  3720.9  452.46  3790.9   446.6  3848.4  428.61  3853.4  429.04  3865.8  423.77
    3931  397.37  4011.1  380.43  4061.3   373.9  4078.1  371.99  4201.2  356.71
  4261.3  352.94  4491.4   352.5  4681.6  355.48  4701.6  353.34  4711.6  355.39
  4757.1  354.96  4856.1  354.08  4921.7  353.22  4955.1  354.94  4981.8   354.3
  4994.3  351.79  4994.8  351.29  5009.2  351.79  5019.3   354.6  5129.2   353.1
  5345.6  354.37  5551.1  371.62    5577  375.32  5618.8  380.54  5679.5  384.85
#Mann= 12 ,-1 , 0
  3720.9      .1       0  3865.8     .05       0  4061.3     .16       0
  4078.1     .12       0  4757.1     .05       0  4856.1     .16       0
  4955.1     .12       0  4994.3     .07       0  5009.2     .12       0
  5129.2     .16       0  5551.1     .05       0    5577     .12       0
Bank Sta=4981.8,5019.3
XS Rating Curve= 0 ,0
Exp/Cntr=0.3,0.1

Type RM Length L Ch R = 1 ,6878    ,439,439,439
BEGIN DESCRIPTION:
SOUTH MINERAL CREEK 91 0
END DESCRIPTION:
XS GIS Cut Line= 2
      3517688.13     10383755.09      3519774.97     10382282.85
#Sta/Elev= 30
  3330.1  421.35  3557.1  399.44    3902  379.05    4131  369.59  4139.6  371.52
    4291  366.14  4515.2  357.54  4548.5  355.75  4681.6  349.61  4698.1  348.96
  4713.1  348.96    4806  351.06  4949.2  352.91    4993  353.59  5007.8  349.88
  5036.1  353.25  5100.1   352.6  5135.8  360.28  5165.4  374.19    5195  380.53
  5272.5  379.67  5287.3   373.9  5293.4  374.68  5303.6   371.6  5352.6  365.32
    5428  364.99  5552.4  370.77    5653   376.5  5718.3  376.12    5884  383.82
#Mann= 12 ,-1 , 0
  3330.1     .16       0    4291     .05       0  4515.2     .12       0
  4548.5     .16       0  4681.6     .12       0  4698.1     .07       0
  4713.1     .12       0    4806     .05       0  4949.2     .16       0
  5303.6     .05       0    5428     .16       0  5552.4     .12       0
#XS Ineff= 2 , 0
                         5224.11          380.86
Permanent Ineff=
       F       F
Bank Sta=4993,5036.1
XS Rating Curve= 0 ,0
Exp/Cntr=0.3,0.1

Type RM Length L Ch R = 1 ,6439    ,275,275,275
BEGIN DESCRIPTION:
SOUTH MINERAL CREEK 8 0
END DESCRIPTION:
XS GIS Cut Line= 4
      3518858.25     10384373.19      3519271.45     10383203.01
       3519427.7     10382873.15      3519680.29     10382575.58
#Sta/Elev= 30
  3613.9  393.03  3785.2  386.82  3806.4  384.42  4032.7  370.07  4063.6  366.99
    4114  365.37  4206.8   359.4  4343.5  352.28  4446.2  350.43  4573.1  348.87
  4573.6  348.37  4588.1  348.87  4625.6  349.03  4717.4  350.62  4771.9  350.06
  4967.1  353.38  4978.1   352.6  4984.3  350.63  5000.2  349.89  5012.5  352.33
  5110.9  351.52  5176.9  352.66  5301.7  356.44    5316  357.71  5357.4   364.9
  5415.9  377.35  5436.8  377.81  5465.4  381.13  5500.5  382.18  5610.2  381.84
#Mann= 10 ,-1 , 0
  3613.9     .16       0  4206.8      .1       0  4343.5     .16       0
  4446.2     .05       0  4573.1     .07       0  4588.1     .05       0
  4625.6     .16       0  4771.9     .12       0  5176.9     .05       0
  5357.4     .16       0
Bank Sta=4978.1,5012.5
XS Rating Curve= 0 ,0
Exp/Cntr=0.3,0.1

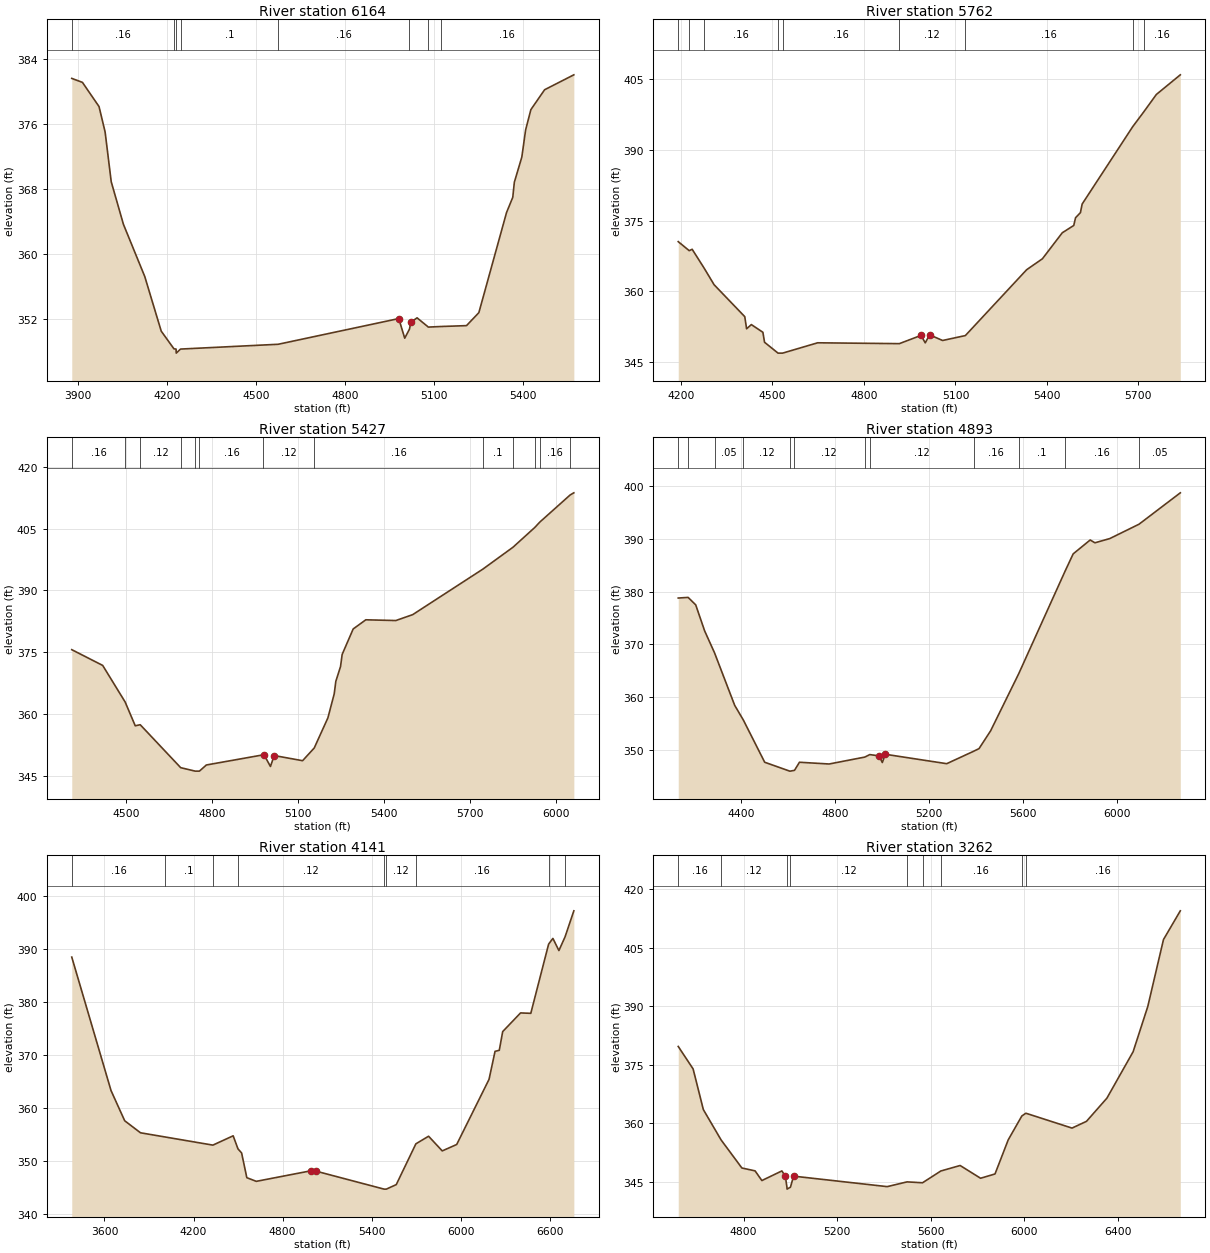
Type RM Length L Ch R = 1 ,6164    ,402,402,402
BEGIN DESCRIPTION:
SOUTH MINERAL CREEK 60 1
END DESCRIPTION:
XS GIS Cut Line= 4
      3519288.82     10384321.05      3519497.15     10383428.71
      3519649.93     10382897.46      3519726.31     10382689.14
#Sta/Elev= 30
  3879.6  381.62  3915.5  381.13  3971.4  378.15  3991.9  375.02  4012.5  368.88
  4053.6  363.63  4125.4   357.2  4180.9  350.46  4223.8  348.28  4230.9  348.25
  4231.4  347.75  4245.9  348.25  4574.6  348.84    4981  352.01    5001  349.59
    5017  350.71  5021.8  351.56  5042.6   352.1  5080.6  350.96  5121.9  351.03
  5209.1  351.14  5250.7  352.74  5343.9  365.08  5364.9  366.96  5370.2  368.82
  5395.4  371.92  5408.2  375.27  5425.9  377.77  5472.1  380.22  5570.6  382.06
#Mann= 8 ,-1 , 0
  3879.6     .16       0  4223.8      .1       0  4230.9     .07       0
  4245.9      .1       0  4574.6     .16       0    5017     .12       0
  5080.6     .05       0  5121.9     .16       0
Bank Sta=4981,5021.8
XS Rating Curve= 0 ,0
Exp/Cntr=0.3,0.1

Type RM Length L Ch R = 1 ,5762    ,335,335,335
BEGIN DESCRIPTION:
SOUTH MINERAL CREEK 51 0
END DESCRIPTION:
XS GIS Cut Line= 5
      3519691.59     10384213.44      3519820.07     10383900.93
      3519809.14     10383526.87      3520108.26     10383196.07
      3520346.07     10382769.46
#Sta/Elev= 30
  4190.9  370.55  4226.9  368.64  4236.6  368.93  4275.8  364.94  4308.5  361.42
  4409.1  354.65  4415.1  352.08  4430.7  352.97  4468.5  351.34    4474  349.22
  4518.2  346.92  4533.2  346.92  4648.1  349.11    4916  348.93  4986.8  350.67
    5001   349.1  5015.2   350.8  5057.8   349.6  5132.5  350.64  5333.5   364.6
  5385.2  366.92  5450.3  372.43    5488  373.98  5493.8  375.61  5509.8   376.7
  5515.5  378.52  5681.2  394.91  5718.5  398.14  5758.9  401.75  5837.4  405.91
#Mann= 9 ,-1 , 0
  4190.9     .16       0  4226.9      .1       0  4275.8     .16       0
  4518.2     .07       0  4533.2     .16       0    4916     .12       0
  5132.5     .16       0  5681.2      .1       0  5718.5     .16       0
Bank Sta=4986.8,5015.2
XS Rating Curve= 0 ,0
Exp/Cntr=0.3,0.1

Type RM Length L Ch R = 1 ,5427    ,534,534,534
BEGIN DESCRIPTION:
SOUTH MINERAL CREEK 5 1
END DESCRIPTION:
XS GIS Cut Line= 5
      3519688.15     10384258.55      3519886.04     10384098.85
       3520028.4     10383786.35      3520299.23     10383268.98
      3520531.88     10382748.14
#Sta/Elev= 30
  4309.1  375.64    4417  371.82  4495.4  362.94  4530.6  357.17    4548  357.43
  4689.2  347.01  4739.6  346.17  4754.6  346.17  4778.8  347.66    4978  350.13
  4979.8  350.18  5002.4   347.3  5015.6  349.95  5114.6   348.7  5155.3  351.79
  5202.9  359.09    5225  364.93  5230.6  367.96    5247  371.54  5252.7  374.49
  5291.2  380.67  5335.3  382.89    5440  382.71  5498.8  384.14  5743.6  395.18
  5848.9   400.5    5925   405.3  5942.6  406.61  6048.3  413.18  6061.2   413.7
#Mann= 13 ,-1 , 0
  4309.1     .16       0  4495.4     .05       0    4548     .12       0
  4689.2     .16       0  4739.6     .07       0  4754.6     .16       0
    4978     .12       0  5155.3     .16       0  5743.6      .1       0
  5848.9     .16       0    5925      .1       0  5942.6     .16       0
  6048.3      .1       0
Bank Sta=4979.8,5015.6
XS Rating Curve= 0 ,0
Exp/Cntr=0.3,0.1

Type RM Length L Ch R = 1 ,4893    ,752,752,752
BEGIN DESCRIPTION:
SOUTH MINERAL CREEK 4 1
END DESCRIPTION:
XS GIS Cut Line= 4
      3519681.37     10384311.85      3520375.79     10384086.16
      3520844.54     10383782.34      3520957.25     10382941.34
#Sta/Elev= 30
  4133.2  378.77  4175.3  378.89  4207.6  377.48  4245.7  372.54  4287.7   368.4
  4373.5  358.46  4410.8  355.64  4501.3  347.68  4607.7     346  4610.2     346
  4628.2  346.15  4649.2  347.68  4775.4  347.35  4927.5  348.66  4948.7  349.13
  4987.7  348.89    5002  347.63  5014.7  349.19  5276.1  347.41  5390.6  349.76
  5413.6  350.26    5463  353.63  5582.9  364.47  5780.4   383.9  5814.4  387.13
  5886.8  389.76    5907  389.23  5970.4  390.03  6094.8  392.75  6270.5  398.69
#Mann= 12 ,-1 , 0
  4133.2      .1       0  4175.3     .16       0  4287.7     .05       0
  4410.8     .12       0  4610.2     .07       0  4625.2     .12       0
  4927.5     .16       0  4948.7     .12       0  5390.6     .16       0
  5582.9      .1       0  5780.4     .16       0  6094.8     .05       0
Bank Sta=4987.7,5014.7
XS Rating Curve= 0 ,0
Exp/Cntr=0.3,0.1

Type RM Length L Ch R = 1 ,4141    ,879,879,879
BEGIN DESCRIPTION:
SOUTH MINERAL CREEK 41 0
END DESCRIPTION:
XS GIS Cut Line= 3
      3519665.52     10385868.32      3520629.07     10384753.72
      3522363.42     10383956.86
#Sta/Elev= 30
  3379.9  388.45  3644.4  363.24  3736.5  357.54  3842.9  355.27  4330.5  352.94
    4467   354.7  4499.4  352.24    4524  351.46  4559.1  346.79  4622.8   346.1
  4992.1   348.1  5021.7  348.05  5483.7  344.63  5498.7  344.63  5565.6  345.48
    5698  353.19  5783.4  354.62  5875.4  351.85  5972.8  353.06  6190.6  365.36
  6231.1  370.65  6259.6  370.85  6282.6  374.38    6403  377.91  6471.9  377.83
    6592   390.9  6620.8  391.98  6661.3  389.69  6702.8  392.28  6761.9  397.19
#Mann= 9 ,-1 , 0
  3379.9     .16       0  4008.5      .1       0  4330.5     .16       0
  4499.4     .12       0  5483.7     .07       0  5498.7     .12       0
    5698     .16       0    6592      .1       0  6702.8     .16       0
Bank Sta=4992.1,5021.7
XS Rating Curve= 0 ,0
Exp/Cntr=0.3,0.1

Type RM Length L Ch R = 1 ,3262    ,523,523,523
BEGIN DESCRIPTION:
SOUTH MINERAL CREEK 3 0
END DESCRIPTION:
XS GIS Cut Line= 3
      3520642.12     10385691.63      3521042.11     10385391.64
      3522592.13     10384841.63
#Sta/Elev= 30
  4521.2  379.66  4584.7   373.9  4628.5  363.46  4704.3  355.68  4793.1  348.48
  4849.3  347.75  4878.5  345.26  4963.9  347.73  4978.5   346.4  4985.6  343.56
  4986.1  343.06  5000.6  343.56  5013.9  346.39  5413.8   343.7  5498.8  344.92
  5564.7  344.69  5642.9  347.71  5725.4  349.12  5812.7  345.85  5874.4  346.95
  5930.8   355.7  5988.9  361.82  6006.2  362.53  6203.3  358.72  6265.1  360.45
  6352.4   366.4  6464.3   378.3    6527  389.91    6594  407.08  6665.9  414.45
#Mann= 9 ,-1 , 0
  4521.2     .16       0  4704.3     .12       0  4985.6     .07       0
  5000.6     .12       0  5498.8     .16       0  5564.7     .12       0
  5642.9     .16       0  5988.9     .12       0  6006.2     .16       0
Bank Sta=4978.5,5013.9
XS Rating Curve= 0 ,0
Exp/Cntr=0.3,0.1

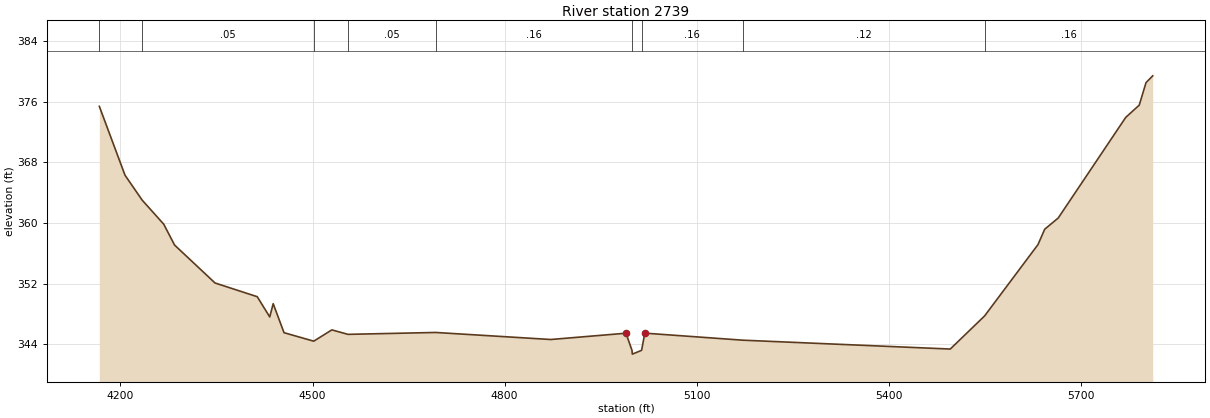
Type RM Length L Ch R = 1 ,2739    ,589,589,589
BEGIN DESCRIPTION:
SOUTH MINERAL CREEK 20 1
END DESCRIPTION:
XS GIS Cut Line= 3
      3520692.08     10385841.65      3521492.11     10385541.64
      3522242.11     10385291.64
#Sta/Elev= 30
  4167.1   375.4  4207.2  366.31    4234  363.02  4267.7  359.84  4284.6  357.09
  4347.8  352.08  4413.7  350.27  4433.2   347.6  4438.6  349.35  4455.5  345.52
  4501.9   344.4  4530.2  345.89  4555.4   345.3  4692.2  345.55    4872  344.62
  4989.5  345.45  4998.9  343.19  4999.4  342.69  5013.9  343.19  5018.9  345.46
    5172  344.53  5495.9  343.36  5549.5  347.73  5632.9  357.15  5643.4  359.18
  5664.5  360.66  5769.9  373.94    5791  375.56  5801.6  378.53  5812.1  379.43
#Mann= 9 ,-1 , 0
  4167.1     .16       0    4234     .05       0  4501.9     .16       0
  4555.4     .05       0  4692.2     .16       0  4998.9     .07       0
  5013.9     .16       0    5172     .12       0  5549.5     .16       0
Bank Sta=4989.5,5018.9
XS Rating Curve= 0 ,0
Exp/Cntr=0.3,0.1