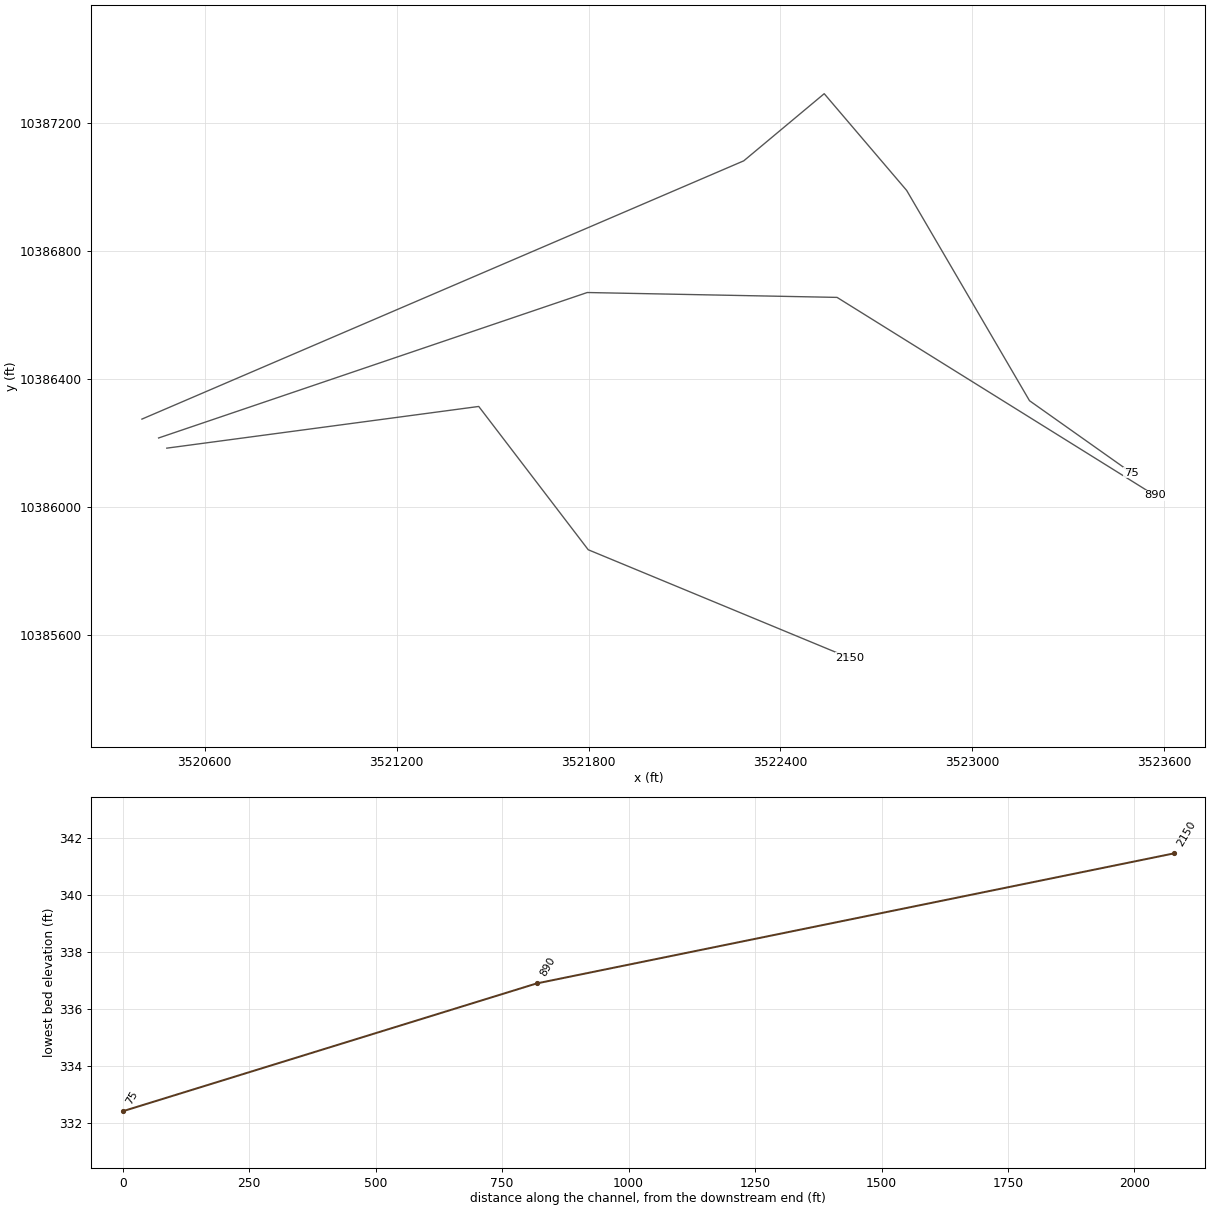
HEC-RAS study SOUTH MINERAL CREEK.prj: SOUTH MINERAL CREEK Base Level Engineering

--- SOUTH MINERAL CREEK.g01 (geometry) --- (continued)

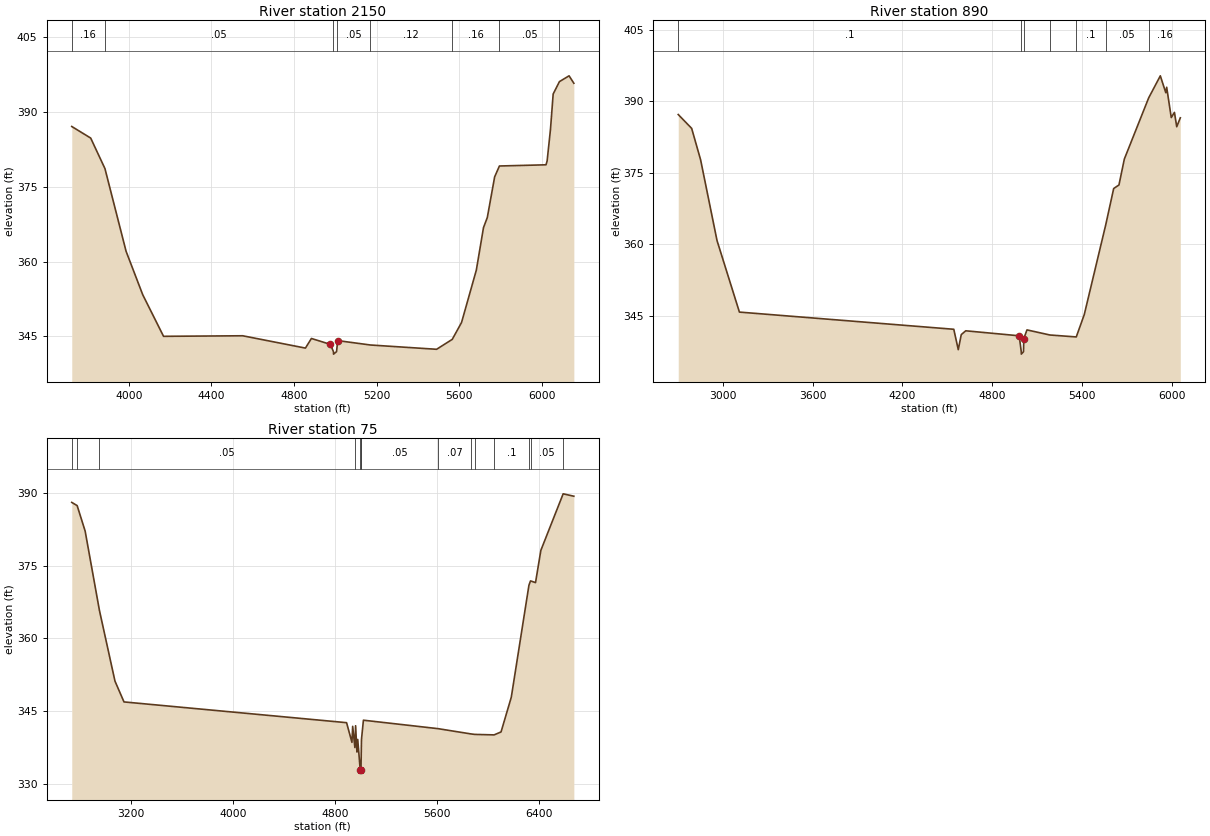
Type RM Length L Ch R = 1 ,2150    ,1260,1260,1260
BEGIN DESCRIPTION:
SOUTH MINERAL CREEK 31 0
END DESCRIPTION:
XS GIS Cut Line= 4
      3520481.22     10386183.34      3521456.62     10386313.73
      3521798.93     10385865.64      3522616.66     10385527.09
#Sta/Elev= 30
    3723   387.1  3814.7  384.78  3883.8  378.66  3986.2  362.08  4066.9  353.37
  4167.8  345.03  4551.2  345.14  4855.3  342.67  4884.3   344.6  4975.9  343.42
  4991.1  341.96  4991.6  341.46  5006.1  341.96  5011.7  344.17  5170.3  343.29
  5490.9  342.43  5566.8  344.42  5611.8   347.8  5683.4  358.29  5718.2  366.83
  5736.6  368.84  5772.3  377.01  5795.4  379.18  6021.1  379.42  6026.5  380.18
  6042.8  386.54  6055.8  393.61  6086.2   396.1  6132.9  397.26    6156  395.77
#Mann= 8 ,-1 , 0
    3723     .16       0  3883.8     .05       0  4991.1    .035       0
  5006.1     .05       0  5170.3     .12       0  5566.8     .16       0
  5795.4     .05       0  6086.2     .16       0
Bank Sta=4975.9,5011.7
XS Rating Curve= 0 ,0
Exp/Cntr=0.3,0.1

Type RM Length L Ch R = 1 ,890     ,818,818,818
BEGIN DESCRIPTION:
SOUTH MINERAL CREEK 11 0
END DESCRIPTION:
XS GIS Cut Line= 4
     3520455.581    10386215.166     3521795.858    10386670.028
      3522576.99     10386654.77       3523570.4     10386035.83
#Sta/Elev= 30
    2700  387.23 2789.85  384.32 2849.75  377.71 2959.56  360.75 3109.31  345.73
  4543.4  342.12  4573.4  337.84  4593.4     341  4623.4   341.8  4981.1  340.75
  4994.8   337.4  4995.3   336.9  5009.8   337.4  5011.7  340.13    5033  341.99
  5186.3  340.92  5362.8  340.51  5416.5  345.23  5559.8  364.05  5613.1  371.69
  5648.4  372.43  5684.4  377.88  5847.1  390.72  5925.1  395.36  5961.7  391.81
  5967.6  392.96  5998.3  386.59  6019.5  387.68  6034.9  384.66  6058.8  386.54
#Mann= 7 ,-1 , 0
    2700      .1       0  4994.8     .03       0  5009.8     .05       0
  5186.3     .12       0  5362.8      .1       0  5559.8     .05       0
  5847.1     .16       0
Bank Sta=4981.1,5011.7
XS Rating Curve= 0 ,0
Exp/Cntr=0.3,0.1

Type RM Length L Ch R = 1 ,75      ,0,0,0
BEGIN DESCRIPTION:
SOUTH MINERAL CREEK 1 0
END DESCRIPTION:
XS GIS Cut Line= 6
      3520403.48     10386274.19      3522285.32     10387081.85
      3522536.82     10387291.75      3522794.63     10386989.23
      3523178.74     10386331.68      3523496.98     10386106.53
#Sta/Elev= 30
  2736.7  388.05  2778.9  387.39  2841.5  382.14  2953.7  365.75  3075.3  351.19
    3146   346.9  4890.3  342.62  4932.2  338.56    4938  341.87  4955.3  337.49
  4960.9  341.99  4971.4  336.56  4977.6  339.16    4997  332.92  4999.8  332.42
    5003  332.92    5007  339.16  5022.2  343.13  5605.8  341.39  5864.6   340.3
  5894.4   340.2  6046.2   340.1  6100.8  340.71    6181  347.87  6319.3  370.96
  6331.7  371.86  6370.9  371.51  6412.7  378.16  6587.5  389.82  6671.2  389.33
#Mann= 14 ,-1 , 0
  2736.7     .16       0  2778.9      .1       0  2953.7     .05       0
  4955.3     .16       0    4997     .07       0    5003     .16       0
    5007     .05       0  5605.8     .07       0  5864.6     .05       0
  5894.4     .12       0  6046.2      .1       0  6319.3     .16       0
  6331.7     .05       0  6587.5     .16       0
Bank Sta=4997,5003
XS Rating Curve= 0 ,0
Exp/Cntr=0.3,0.1

Chan Stop Cuts=-1
Use User Specified Reach Order=0
Composite Channel Slope=5