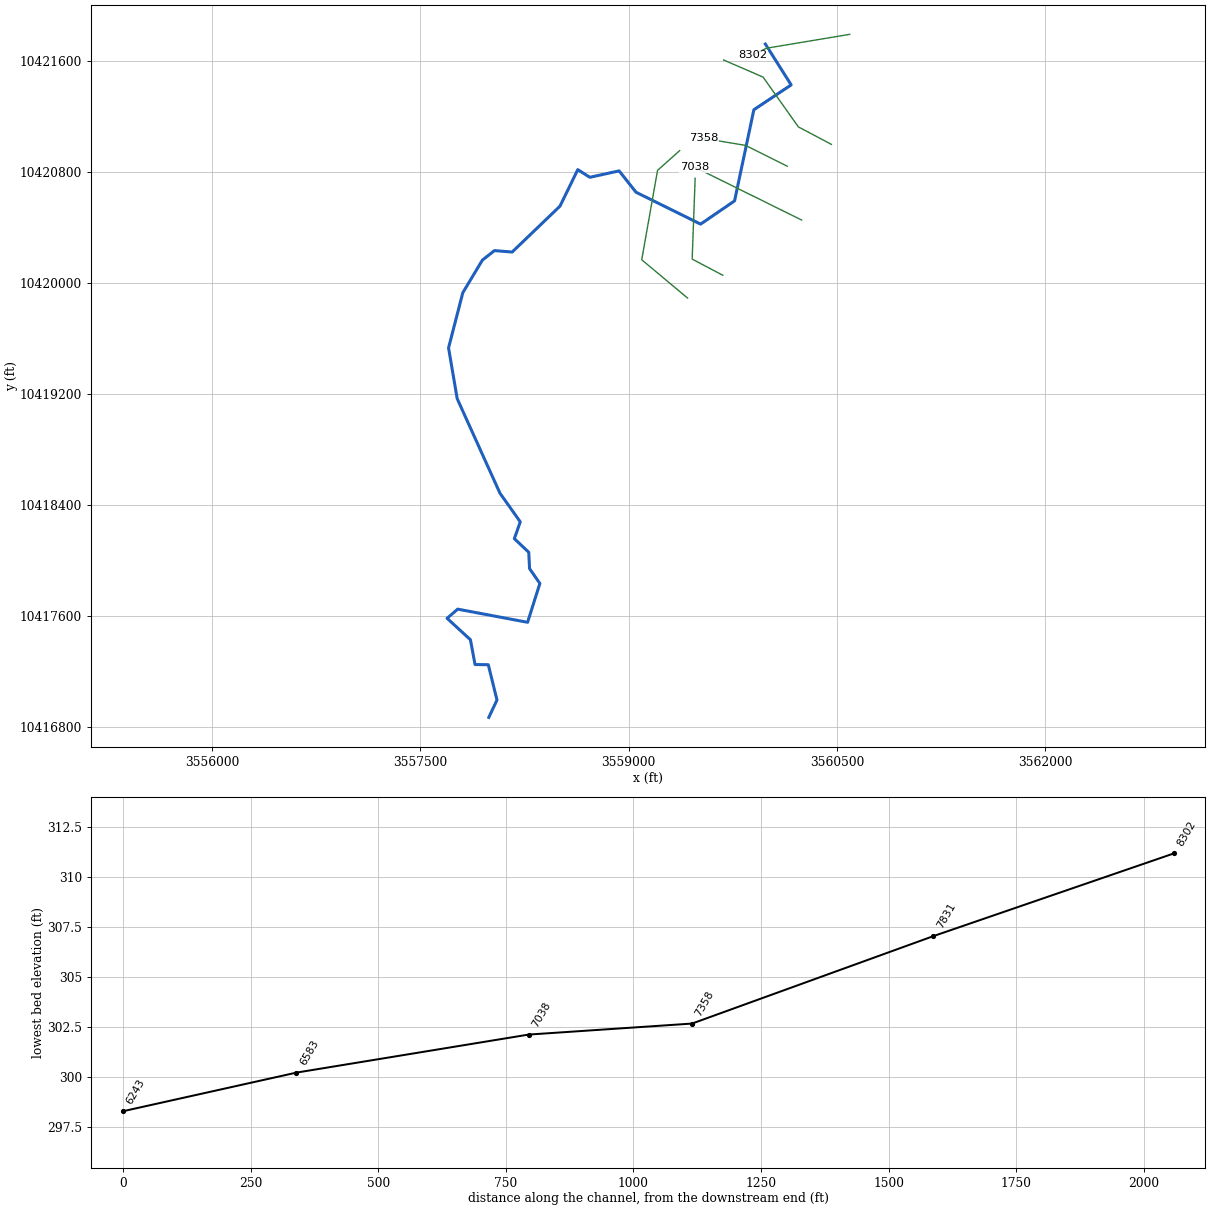
--- UNT0265 IN DUCK CR.prj (project) ---

Proj Title=UNT0265 IN DUCK CR Base Level Engineering
Current Plan=p01
Default Exp/Contr=0.3,0.1
English Units
Geom File=g01
Flow File=f01
Plan File=p01
BEGIN DESCRIPTION:
UNT0265 IN DUCK CR
END DESCRIPTION:

--- UNT0265 IN DUCK CR.p01 (plan) ---

Plan Title=Multiple Run
Short Identifier=Multiple
Geom File=g01
Flow File=f01
Subcritical Flow
K Sum by GR= 0
Std Step Tol= 0.01
Critical Tol= 0.01
Num of Std Step Trials= 20
Max Error Tol= 0.3
Flow Tol Ratio= 0.001
Split Flow NTrial= 30
Split Flow Tol= 0.02
Split Flow Ratio= 0.02
Log Output Level= 0
Friction Slope Method= 1
Unsteady Friction Slope Method= 2
Unsteady Bridges Friction Slope Method= 1
Parabolic Critical Depth
Global Vel Dist=  1 , 1 , 1
Global Log Level= 0
CheckData=True
Encroach Param= -1, 0, 0, 0
BEGIN DESCRIPTION:
Multiple Run
END DESCRIPTION:

--- UNT0265 IN DUCK CR.f01 (steady flow) ---

Flow Title=Multiple
Number of Profiles=7
Profile Names=10-year,25-year,50-year,1pct_min,100-year,1pct_plu,500-year
River Rch & RM= UNT0265 IN DUCK ,Reach-1,8302
    1105    1529    1882    1690    2285    3090    3359
Boundary for River Rch & Prof#=UNT0265 IN DUCK ,Reach-1,1
Up Type=0
Dn Type=3
Dn Slope=0.005
Boundary for River Rch & Prof#=UNT0265 IN DUCK ,Reach-1,2
Up Type=0
Dn Type=3
Dn Slope=0.005
Boundary for River Rch & Prof#=UNT0265 IN DUCK ,Reach-1,3
Up Type=0
Dn Type=3
Dn Slope=0.005
Boundary for River Rch & Prof#=UNT0265 IN DUCK ,Reach-1,4
Up Type=0
Dn Type=3
Dn Slope=0.005
Boundary for River Rch & Prof#=UNT0265 IN DUCK ,Reach-1,5
Up Type=0
Dn Type=3
Dn Slope=0.005
Boundary for River Rch & Prof#=UNT0265 IN DUCK ,Reach-1,6
Up Type=0
Dn Type=3
Dn Slope=0.005
Boundary for River Rch & Prof#=UNT0265 IN DUCK ,Reach-1,7
Up Type=0
Dn Type=3
Dn Slope=0.005

--- UNT0265 IN DUCK CR.g01 (geometry) ---

Geom Title=Existing Conditions

River Reach=UNT0265 IN DUCK ,Reach-1
Reach XY= 30
      3559984.27     10421721.66      3560170.27     10421427.30
      3559901.41     10421248.73      3559762.38     10420591.96
      3559517.84     10420424.65      3559052.91     10420654.08
      3558930.74     10420808.12      3558719.82     10420761.87
      3558633.08     10420816.98      3558504.69     10420553.90
      3558160.53     10420223.64      3558032.68     10420233.87
      3557945.49     10420164.94      3557804.86     10419930.50
      3557702.19     10419533.19      3557764.33     10419167.56
      3558072.29     10418486.72      3558218.79     10418280.02
      3558176.19     10418158.87      3558279.97     10418060.64
      3558285.64     10417943.21      3558359.94     10417836.25
      3558271.51     10417556.34      3557768.13     10417651.22
      3557691.59     10417585.32      3557859.82     10417430.79
      3557893.03     10417252.09      3557988.37     10417250.87
      3558051.09     10416996.60      3557992.11     10416871.64

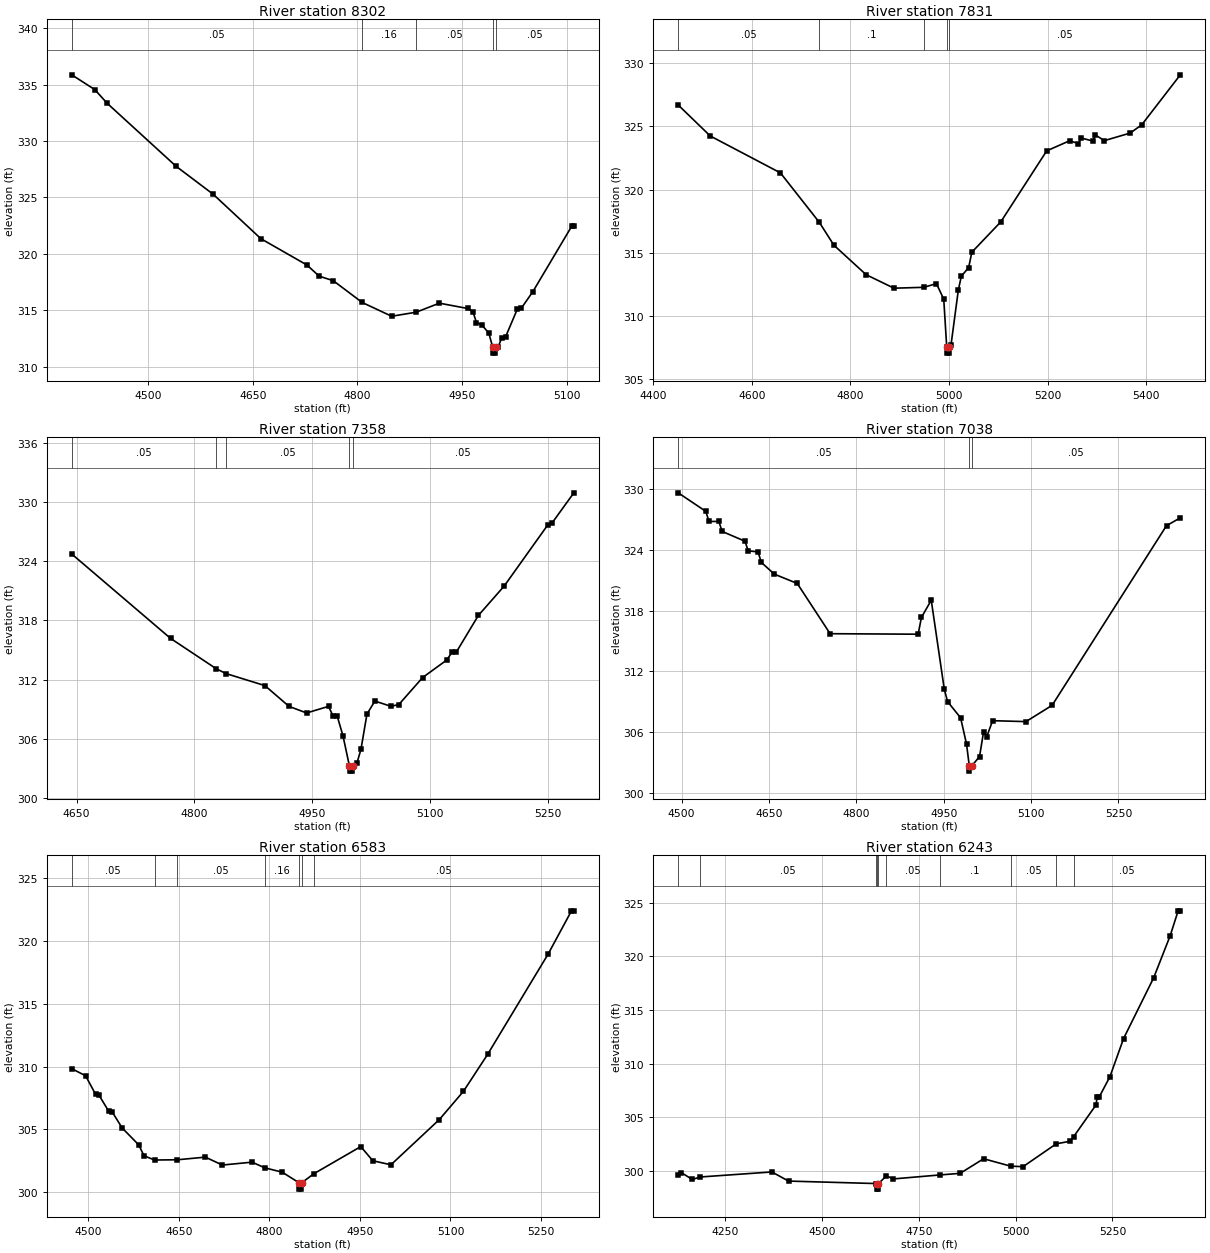
Type RM Length L Ch R = 1,8302,471,471,471
BEGIN DESCRIPTION:
UNT0265 IN DUCK CR 3 0
END DESCRIPTION:
XS GIS Cut Line= 3
      3560592.12     10421791.64      3559992.11     10421691.64
      3559892.10     10421641.64
#Sta/Elev= 30
  4390.2  335.87  4423.2  334.56  4440.9  333.35  4539.8  327.76  4593.0  325.28
  4661.4  321.34  4727.3  319.01  4745.0  318.02  4765.3  317.61  4806.8  315.68
  4849.0  314.46  4884.2  314.82  4917.4  315.62  4957.9  315.15  4965.5  314.88
  4970.6  313.90  4978.2  313.70  4988.4  312.96  4994.0  311.69  4994.2  311.19
  4997.7  311.19  4998.0  311.69  5001.3  311.69  5006.9  312.53  5012.5  312.65
  5029.2  315.09  5034.8  315.16  5051.6  316.65  5107.5  322.47  5110.3  322.47
#Mann=5,-1,0
  4390.2    0.05       0  4806.8    0.16       0  4884.2    0.05       0
  4994.0    0.03       0  4998.0    0.05       0
Bank Sta=4994,4998
Exp/Cntr=0.3,0.1

Type RM Length L Ch R = 1,7831,473,473,473
BEGIN DESCRIPTION:
UNT0265 IN DUCK CR 2 0
END DESCRIPTION:
XS GIS Cut Line= 4
      3560459.49     10420999.20      3560221.93     10421125.10
      3559967.76     10421483.79      3559683.48     10421606.98
#Sta/Elev= 30
  4450.9  326.70  4515.8  324.25  4658.1  321.33  4737.1  317.41  4766.7  315.60
  4831.9  313.27  4888.5  312.20  4949.0  312.27  4974.6  312.56  4989.4  311.33
  4995.4  307.56  4995.7  307.06  4999.2  307.06  4999.4  307.56  5004.2  307.72
  5019.0  312.06  5025.1  313.15  5039.9  313.83  5046.4  315.05  5105.1  317.45
  5198.2  323.07  5244.6  323.87  5262.7  323.65  5268.1  324.09  5291.6  323.85
  5297.0  324.33  5315.1  323.88  5367.5  324.48  5390.9  325.13  5469.2  329.09
#Mann=5,-1,0
  4450.9    0.05       0  4737.1     0.1       0  4949.0    0.05       0
  4995.4    0.03       0  4999.4    0.05       0
Bank Sta=4995.4,4999.4
Exp/Cntr=0.3,0.1

Type RM Length L Ch R = 1,7358,320,320,320
BEGIN DESCRIPTION:
UNT0265 IN DUCK CR 8 0
END DESCRIPTION:
XS GIS Cut Line= 3
      3560142.10     10420841.65      3559842.11     10420991.64
      3559542.15     10421041.64
#Sta/Elev= 30
  4643.8  324.75  4769.6  316.18  4827.5  313.11  4840.0  312.61  4889.8  311.38
  4920.5  309.27  4942.9  308.60  4970.8  309.27  4976.4  308.33  4981.7  308.33
  4989.3  306.26  4997.5  303.19  4997.7  302.69  5001.2  302.69  5001.5  303.19
  5007.1  303.52  5012.2  304.93  5019.8  308.49  5029.9  309.81  5050.2  309.28
  5060.3  309.45  5090.7  312.20  5121.1  313.96  5128.7  314.82  5133.8  314.81
  5161.7  318.51  5194.6  321.50  5250.4  327.74  5255.5  327.90  5283.3  330.97
#Mann=5,-1,0
  4643.8    0.05       0  4827.5     0.1       0  4840.0    0.05       0
  4997.5    0.03       0  5001.5    0.05       0
Bank Sta=4997.5,5001.5
Exp/Cntr=0.3,0.1

Type RM Length L Ch R = 1,7038,455,455,455
BEGIN DESCRIPTION:
UNT0265 IN DUCK CR 7 0
END DESCRIPTION:
XS GIS Cut Line= 2
      3560245.78     10420453.88      3559473.24     10420835.81
#Sta/Elev= 30
  4494.3  329.62  4541.6  327.79  4547.1  326.79  4564.0  326.80  4569.6  325.81
  4608.9  324.84  4614.4  323.89  4631.3  323.79  4636.9  322.75  4659.3  321.59
  4698.6  320.67  4755.0  315.71  4906.1  315.66  4911.7  317.31  4928.6  319.02
  4951.0  310.21  4956.6  309.01  4979.0  307.40  4989.2  304.80  4993.9  302.64
  4994.1  302.14  4997.9  302.64  5011.5  303.58  5018.3  305.99  5023.9  305.55
  5033.9  307.12  5091.2  307.03  5136.1  308.64  5332.4  326.38  5356.1  327.15
#Mann=3,-1,0
  4494.3    0.05       0  4993.9    0.03       0  4997.9    0.05       0
Bank Sta=4993.9,4997.9
Exp/Cntr=0.3,0.1

Type RM Length L Ch R = 1,6583,340,340,340
BEGIN DESCRIPTION:
UNT0265 IN DUCK CR 4 1
END DESCRIPTION:
XS GIS Cut Line= 3
      3559677.93     10420056.19      3559457.05     10420172.57
      3559478.43     10420754.52
#Sta/Elev= 30
  4472.4  309.84  4495.4  309.27  4511.8  307.80  4517.4  307.74  4533.8  306.43
  4539.4  306.39  4555.8  305.12  4583.5  303.76  4592.0  302.90  4609.7  302.56
  4647.6  302.58  4693.7  302.79  4722.0  302.16  4771.2  302.39  4792.1  301.94
  4821.2  301.59  4849.2  300.74  4849.5  300.24  4853.0  300.24  4853.2  300.74
  4874.0  301.48  4951.3  303.63  4971.3  302.50  5001.3  302.18  5081.4  305.78
  5121.4  308.03  5161.4  310.97  5261.5  318.95  5300.5  322.42  5304.4  322.42
#Mann=7,-1,0
  4472.4    0.05       0  4609.7    0.16       0  4647.6    0.05       0
  4792.1    0.16       0  4849.2   0.035       0  4853.2    0.16       0
  4874.0    0.05       0
Bank Sta=4849.2,4853.2
Exp/Cntr=0.3,0.1

Type RM Length L Ch R = 1,6243,0,0,0
BEGIN DESCRIPTION:
UNT0265 IN DUCK CR 2 1
END DESCRIPTION:
XS GIS Cut Line= 4
      3559423.81     10419892.26      3559093.62     10420167.82
      3559207.64     10420811.55      3559366.81     10420954.10
#Sta/Elev= 30
  4128.0  299.64  4135.8  299.85  4164.4  299.21  4184.7  299.44  4370.1  299.91
  4413.0  299.06  4638.1  298.83  4641.2  298.81  4641.5  298.31  4645.0  298.31
  4645.2  298.81  4665.9  299.55  4683.8  299.26  4803.8  299.63  4856.5  299.78
  4917.2  301.14  4987.0  300.45  5019.0  300.40  5104.9  302.53  5140.8  302.77
  5149.9  303.20  5207.8  306.16  5210.3  306.87  5215.6  306.87  5243.7  308.79
  5278.8  312.33  5356.6  317.99  5399.2  321.90  5419.9  324.23  5425.5  324.23
#Mann=10,-1,0
  4128.0     0.1       0  4184.7    0.05       0  4638.1     0.1       0
  4641.2    0.03       0  4645.2     0.1       0  4665.9    0.05       0
  4803.8     0.1       0  4987.0    0.05       0  5104.9     0.1       0
  5149.9    0.05       0
Bank Sta=4641.2,4645.2
Exp/Cntr=0.3,0.1

Chan Stop Cuts=-1