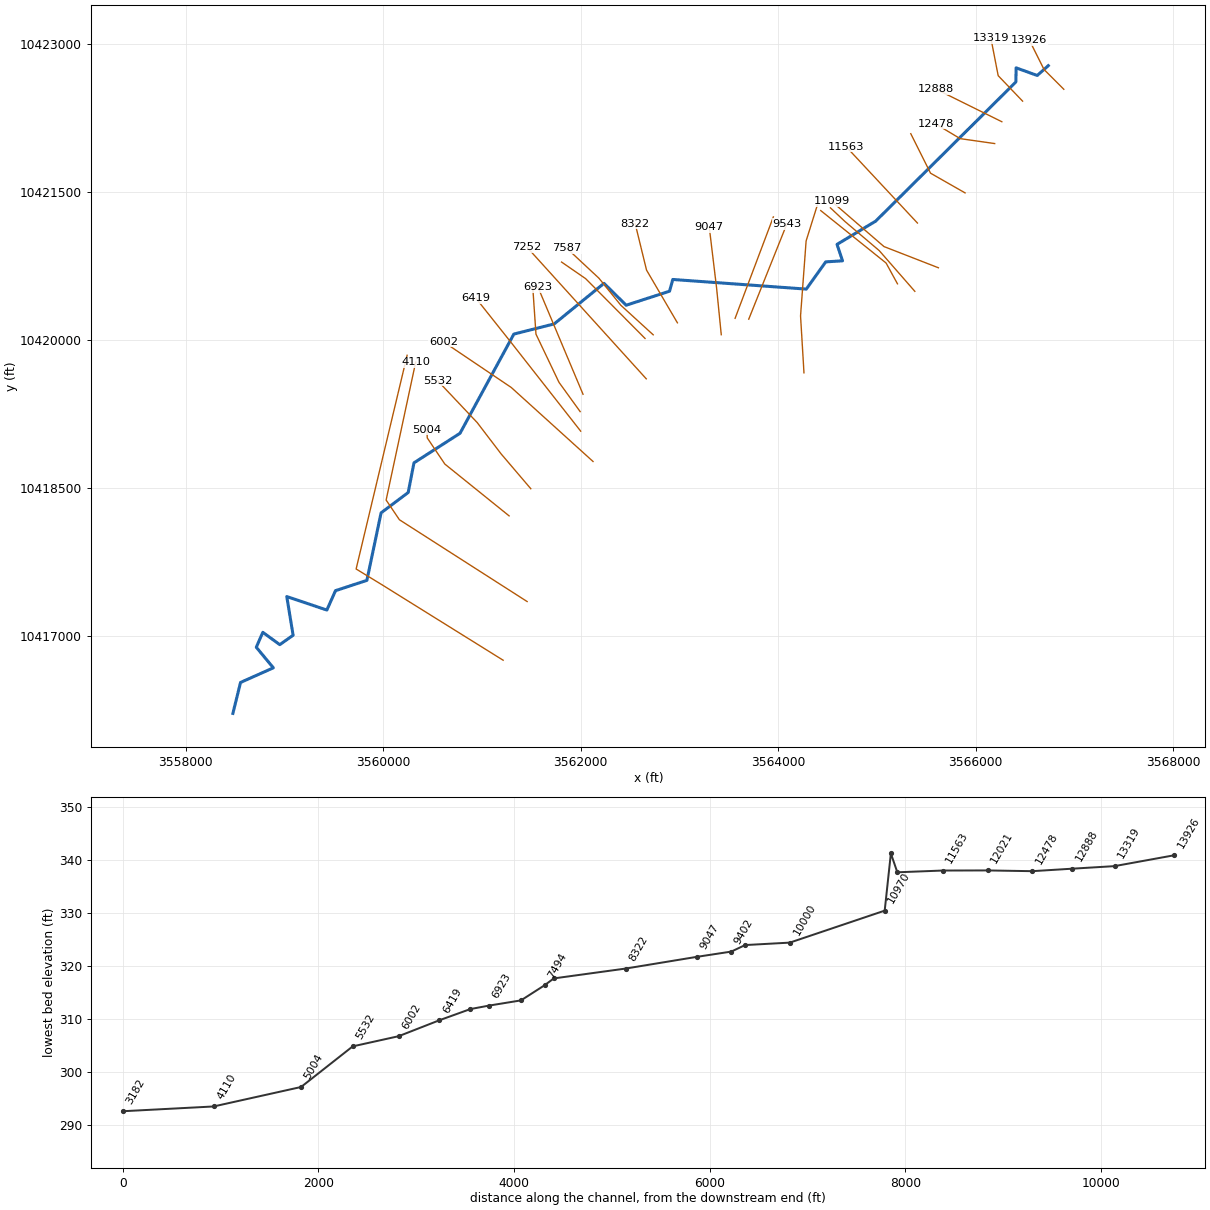
--- UNT0266 IN DUCK CR.prj (project) ---

Proj Title=UNT0266 IN DUCK CR Base Level Engineering
Current Plan=p01
Default Exp/Contr=0.3,0.1
English Units
Geom File=g01
Flow File=f01
Plan File=p01
BEGIN DESCRIPTION:
UNT0266 IN DUCK CR
END DESCRIPTION:

--- UNT0266 IN DUCK CR.p01 (plan) ---

Plan Title=Multiple Run
Short Identifier=Multiple
Geom File=g01
Flow File=f01
Subcritical Flow
K Sum by GR= 0
Std Step Tol= 0.01
Critical Tol= 0.01
Num of Std Step Trials= 20
Max Error Tol= 0.3
Flow Tol Ratio= 0.001
Split Flow NTrial= 30
Split Flow Tol= 0.02
Split Flow Ratio= 0.02
Log Output Level= 0
Friction Slope Method= 1
Unsteady Friction Slope Method= 2
Unsteady Bridges Friction Slope Method= 1
Parabolic Critical Depth
Global Vel Dist=  1 , 1 , 1
Global Log Level= 0
CheckData=True
Encroach Param= -1, 0, 0, 0
BEGIN DESCRIPTION:
Multiple Run
END DESCRIPTION:

--- UNT0266 IN DUCK CR.f01 (steady flow) ---

Flow Title=Multiple
Number of Profiles=7
Profile Names=10-year,25-year,50-year,1pct_min,100-year,1pct_plu,500-year
River Rch & RM= UNT0266 IN DUCK ,Reach-1,13926
    1322    1833    2255    2021    2734    3697    4008
River Rch & RM= UNT0266 IN DUCK ,Reach-1,6734
    1484    2066    2550    2291    3098    4190    4565
Boundary for River Rch & Prof#=UNT0266 IN DUCK ,Reach-1,1
Up Type=0
Dn Type=3
Dn Slope=0.005
Boundary for River Rch & Prof#=UNT0266 IN DUCK ,Reach-1,2
Up Type=0
Dn Type=3
Dn Slope=0.005
Boundary for River Rch & Prof#=UNT0266 IN DUCK ,Reach-1,3
Up Type=0
Dn Type=3
Dn Slope=0.005
Boundary for River Rch & Prof#=UNT0266 IN DUCK ,Reach-1,4
Up Type=0
Dn Type=3
Dn Slope=0.005
Boundary for River Rch & Prof#=UNT0266 IN DUCK ,Reach-1,5
Up Type=0
Dn Type=3
Dn Slope=0.005
Boundary for River Rch & Prof#=UNT0266 IN DUCK ,Reach-1,6
Up Type=0
Dn Type=3
Dn Slope=0.005
Boundary for River Rch & Prof#=UNT0266 IN DUCK ,Reach-1,7
Up Type=0
Dn Type=3
Dn Slope=0.005

--- UNT0266 IN DUCK CR.g01 (geometry) ---

Geom Title=Existing Conditions

River Reach=UNT0266 IN DUCK ,Reach-1
Reach XY= 30
      3566734.53     10422780.71      3566622.93     10422681.67
      3566408.80     10422758.86      3566406.84     10422616.14
      3564986.98     10421205.72      3564595.54     10420969.92
      3564651.09     10420803.26      3564480.95     10420792.84
      3564283.90     10420516.80      3562931.82     10420614.38
      3562899.26     10420495.47      3562459.83     10420353.39
      3562235.33     10420575.21      3561731.10     10420164.07
      3561322.41     10420060.90      3560777.28     10419055.66
      3560310.79     10418756.16      3560252.45     10418455.52
      3559977.69     10418249.17      3559833.94     10417565.14
      3559516.58     10417460.97      3559428.39     10417264.44
      3559022.65     10417401.06      3559086.86     10417009.03
      3558952.08     10416913.56      3558780.14     10417038.61
      3558714.00     10416887.38      3558886.56     10416678.83
      3558554.59     10416530.50      3558476.97     10416217.26

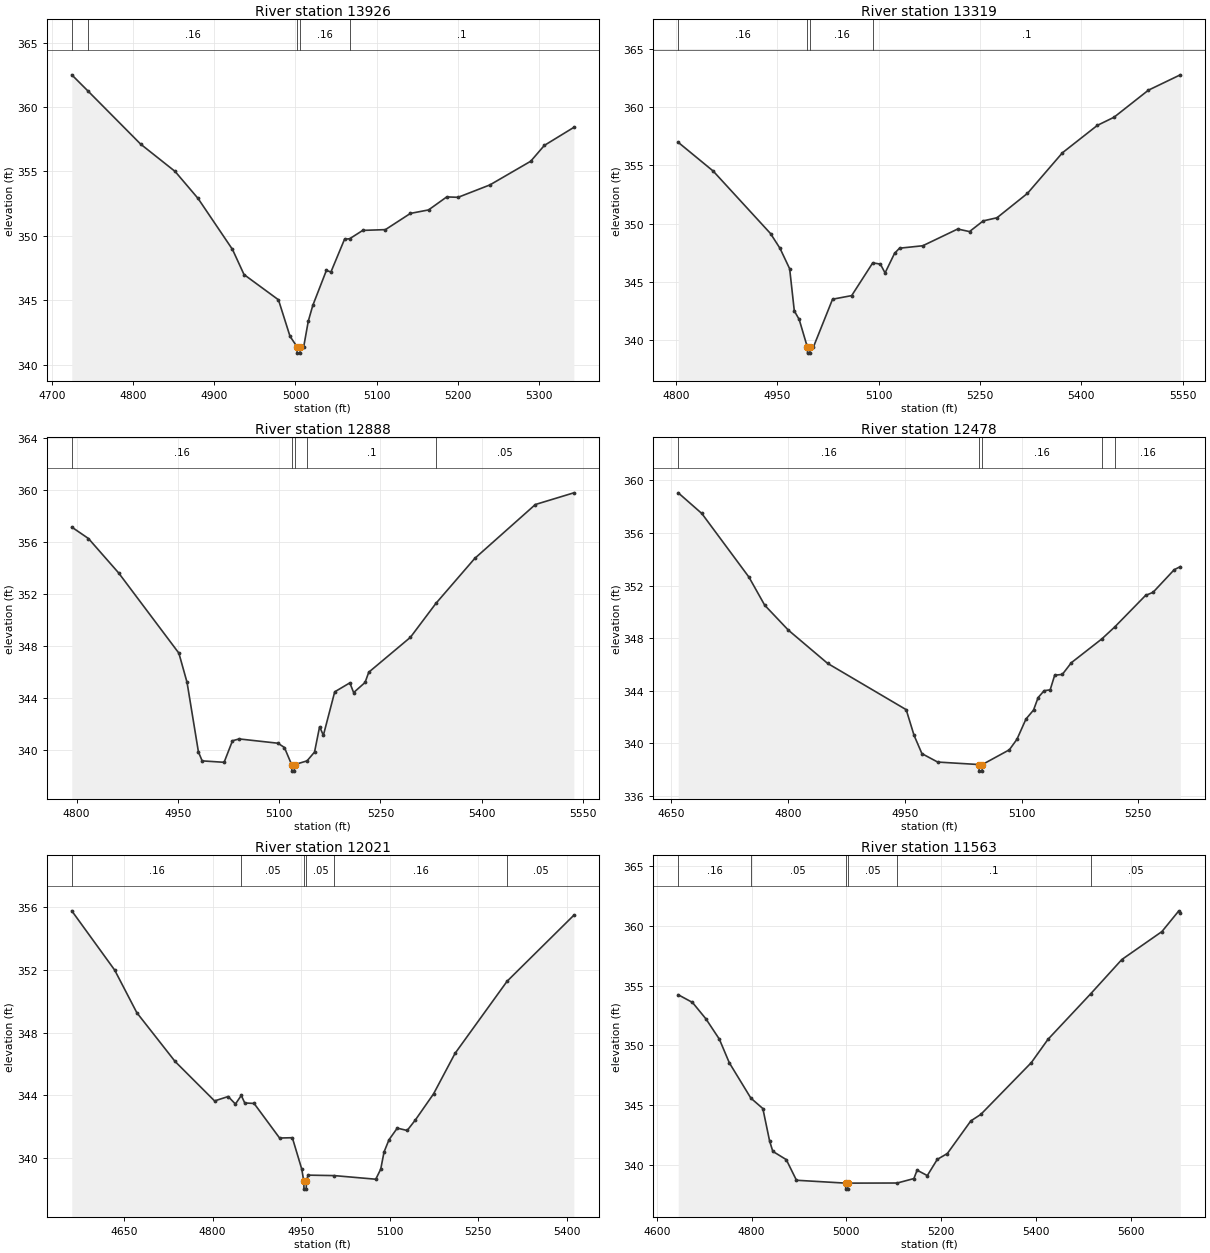
Type RM Length L Ch R = 1,13926,607,607,607
BEGIN DESCRIPTION:
UNT0266 IN DUCK CR 5 0
END DESCRIPTION:
XS GIS Cut Line= 3
      3566892.08     10422541.67      3566692.11     10422741.64
      3566542.11     10423041.63
#Sta/Elev= 30
  4724.6  362.50  4744.3  361.26  4809.4  357.12  4851.8  355.00  4880.1  352.90
  4922.5  348.94  4936.7  346.99  4979.1  345.03  4993.3  342.20  5001.9  341.39
  5002.1  340.89  5005.6  340.89  5005.9  341.39  5010.2  341.39  5015.8  343.37
  5021.4  344.60  5038.1  347.31  5043.7  347.19  5060.5  349.74  5066.7  349.77
  5082.9  350.42  5110.8  350.48  5141.6  351.74  5163.9  352.01  5186.3  353.02
  5200.3  352.99  5239.4  353.95  5289.7  355.79  5306.5  357.02  5342.8  358.42
#Mann=5,-1,0
  4724.6    0.05       0  4744.3    0.16       0  5001.9    0.07       0
  5005.9    0.16       0  5066.7     0.1       0
Bank Sta=5001.9,5005.9
Exp/Cntr=0.3,0.1

Type RM Length L Ch R = 1,13319,431,431,431
BEGIN DESCRIPTION:
UNT0266 IN DUCK CR 4 0
END DESCRIPTION:
XS GIS Cut Line= 3
      3566474.74     10422421.32      3566227.35     10422679.56
      3566153.83     10423057.96
#Sta/Elev= 30
  4803.4  356.99  4855.1  354.52  4940.0  349.14  4954.1  347.86  4968.3  346.11
  4975.2  342.48  4982.4  341.75  4994.6  339.35  4994.8  338.85  4998.3  338.85
  4998.6  339.35  5003.5  339.38  5031.8  343.49  5060.1  343.80  5091.3  346.62
  5102.6  346.51  5109.5  345.75  5123.6  347.44  5130.9  347.88  5165.3  348.09
  5217.0  349.53  5234.5  349.31  5254.8  350.23  5275.2  350.50  5320.3  352.60
  5372.0  356.09  5423.7  358.45  5448.4  359.15  5499.3  361.48  5546.5  362.80
#Mann=4,-1,0
  4803.4    0.16       0  4994.6    0.07       0  4998.6    0.16       0
  5091.3     0.1       0
Bank Sta=4994.6,4998.6
Exp/Cntr=0.3,0.1

Type RM Length L Ch R = 1,12888,410,410,410
BEGIN DESCRIPTION:
UNT0266 IN DUCK CR 24 0
END DESCRIPTION:
XS GIS Cut Line= 2
      3566264.28     10422212.96      3565597.97     10422542.86
#Sta/Elev= 30
  4792.9  357.17  4817.6  356.29  4862.3  353.64  4951.5  347.46  4963.6  345.21
  4980.5  339.84  4986.0  339.16  5018.5  339.05  5030.9  340.71  5040.8  340.85
  5098.2  340.52  5107.8  340.19  5118.5  338.87  5118.8  338.37  5122.5  338.37
  5122.8  338.87  5141.3  339.16  5152.4  339.84  5159.9  341.79  5165.5  341.13
  5182.3  344.48  5204.7  345.17  5210.3  344.42  5227.2  345.20  5232.7  345.99
  5294.4  348.68  5332.1  351.29  5389.7  354.76  5479.4  358.91  5536.4  359.81
#Mann=5,-1,0
  4792.9    0.16       0  5118.5    0.07       0  5122.8    0.16       0
  5141.3     0.1       0  5332.1    0.05       0
Bank Sta=5118.5,5122.8
Exp/Cntr=0.3,0.1

Type RM Length L Ch R = 1,12478,457,457,457
BEGIN DESCRIPTION:
UNT0266 IN DUCK CR 23 0
END DESCRIPTION:
XS GIS Cut Line= 3
      3566192.07     10421991.65      3565842.11     10422041.64
      3565592.08     10422191.66
#Sta/Elev= 30
  4658.8  359.05  4689.1  357.48  4749.7  352.64  4769.9  350.51  4800.2  348.62
  4850.7  346.09  4951.7  342.57  4961.8  340.62  4971.9  339.23  4992.1  338.59
  5045.2  338.40  5045.5  337.90  5049.2  337.90  5049.5  338.40  5084.2  339.52
  5094.0  340.32  5105.6  341.86  5115.3  342.54  5121.2  343.49  5128.9  344.01
  5136.7  344.08  5142.5  345.19  5152.3  345.25  5163.9  346.14  5203.1  347.95
  5219.7  348.86  5259.2  351.25  5268.9  351.49  5296.1  353.21  5303.9  353.44
#Mann=5,-1,0
  4658.8    0.16       0  5045.2    0.07       0  5049.5    0.16       0
  5203.1     0.1       0  5219.7    0.16       0
Bank Sta=5045.2,5049.5
Exp/Cntr=0.3,0.1

Type RM Length L Ch R = 1,12021,458,458,458
BEGIN DESCRIPTION:
UNT0266 IN DUCK CR 22 0
END DESCRIPTION:
XS GIS Cut Line= 3
      3565892.13     10421491.63      3565542.11     10421691.64
      3565342.09     10422091.68
#Sta/Elev= 30
  4561.4  355.74  4634.1  351.97  4671.6  349.26  4736.4  346.16  4803.3  343.65
  4826.3  343.93  4838.6  343.45  4848.5  344.00  4854.4  343.52  4870.2  343.49
  4913.4  341.29  4935.0  341.31  4950.9  339.32  4954.4  338.54  4954.7  338.04
  4958.5  338.04  4958.8  338.54  4961.7  338.93  5006.1  338.90  5076.3  338.67
  5084.7  339.31  5090.3  340.40  5098.7  341.18  5112.7  341.92  5129.5  341.77
  5143.4  342.44  5174.2  344.10  5210.5  346.67  5298.7  351.26  5411.8  355.46
#Mann=6,-1,0
  4561.4    0.16       0  4848.5    0.05       0  4954.4   0.033       0
  4958.8    0.05       0  5006.1    0.16       0  5298.7    0.05       0
Bank Sta=4954.4,4958.8
Exp/Cntr=0.3,0.1

Type RM Length L Ch R = 1,11563,464,464,464
BEGIN DESCRIPTION:
Mapping XS 73e09874
END DESCRIPTION:
XS GIS Cut Line= 2
      3565409.24     10421186.47      3564686.83     10421960.95
#Sta/Elev= 30
  4645.2  354.23  4675.2  353.59  4703.6  352.22  4731.9  350.53  4752.9  348.56
  4798.4  345.61  4823.7  344.74  4837.9  342.04  4844.7  341.17  4873.1  340.48
  4894.6  338.76  4998.3  338.52  4998.6  338.02  5002.5  338.02  5002.8  338.52
  5107.2  338.53  5142.3  338.90  5149.1  339.60  5170.6  339.15  5191.6  340.50
  5212.9  340.99  5262.4  343.71  5283.4  344.25  5390.0  348.57  5425.1  350.51
  5515.7  354.33  5581.0  357.17  5665.5  359.50  5701.2  361.23  5704.3  361.01
#Mann=6,-1,0
  4645.2    0.16       0  4798.4    0.05       0  4998.3   0.033       0
  5002.8    0.05       0  5107.2     0.1       0  5515.7    0.05       0
Bank Sta=4998.3,5002.8
Exp/Cntr=0.3,0.1

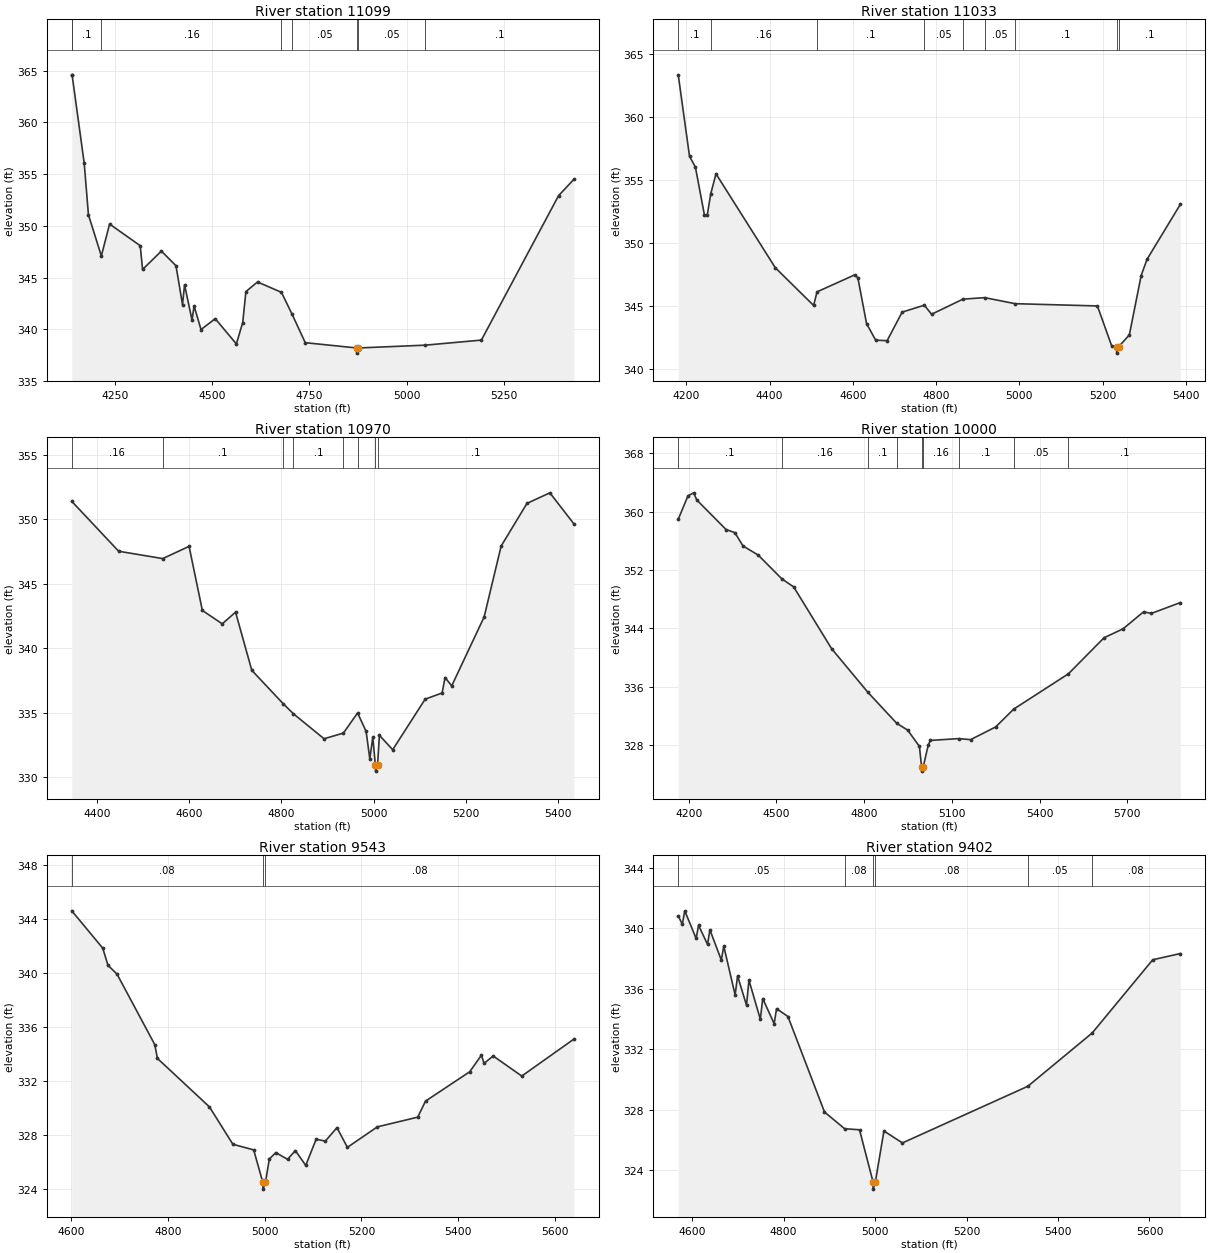
Type RM Length L Ch R = 1,11099,66,66,66
BEGIN DESCRIPTION:
UNT0266 IN DUCK CR 21 0
END DESCRIPTION:
XS GIS Cut Line= 3
      3565621.90     10420732.94      3565070.67     10420947.79
      3564541.12     10421405.71
#Sta/Elev= 30
  4138.6  364.60  4139.4  364.60  4170.6  356.06  4181.5  351.06  4214.7  347.09
  4235.9  350.17  4314.7  348.08  4320.8  345.78  4369.1  347.56  4406.7  346.14
  4423.5  342.38  4428.8  344.30  4448.0  340.88  4453.3  342.25  4471.1  339.97
  4507.7  341.02  4562.1  338.58  4578.4  340.65  4586.6  343.64  4616.5  344.57
  4678.0  343.57  4705.7  341.43  4739.3  338.70  4871.3  338.19  4871.7  337.69
  4876.1  338.19  5048.0  338.46  5192.4  338.95  5390.9  352.91  5430.3  354.49
#Mann=8,-1,0
  4138.6    0.16       0  4139.4     0.1       0  4214.7    0.16       0
  4678.0     0.1       0  4705.7    0.05       0  4871.3   0.033       0
  4876.1    0.05       0  5048.0     0.1       0
Bank Sta=4871.3,4876.1
Exp/Cntr=0.3,0.1

Type RM Length L Ch R = 1,11033,63,63,63
BEGIN DESCRIPTION:
UNT0266 IN DUCK CR 20 0
END DESCRIPTION:
XS GIS Cut Line= 4
      3565383.16     10420494.24      3565022.93     10420906.55
      3564675.70     10421201.69      3564528.12     10421340.60
#Sta/Elev= 30
  4180.7  363.37  4207.8  356.90  4222.0  356.03  4243.6  352.23  4250.5  352.24
  4258.7  353.90  4271.4  355.50  4413.8  348.04  4505.8  345.04  4514.1  346.12
  4604.5  347.47  4612.1  347.24  4633.0  343.60  4654.9  342.28  4682.4  342.24
  4718.5  344.51  4771.8  345.06  4789.2  344.34  4864.5  345.54  4916.7  345.66
  4990.1  345.18  5187.5  345.00  5221.8  341.82  5233.5  341.75  5233.9  341.25
  5238.3  341.75  5264.2  342.70  5292.6  347.42  5306.7  348.71  5386.6  353.07
#Mann=9,-1,0
  4180.7     0.1       0  4258.7    0.16       0  4514.1     0.1       0
  4771.8    0.05       0  4864.5     0.1       0  4916.7    0.05       0
  4990.1     0.1       0  5233.5    0.07       0  5238.3     0.1       0
Bank Sta=5233.5,5238.3
Exp/Cntr=0.3,0.1

Type RM Length L Ch R = 1,10970,970,970,970
BEGIN DESCRIPTION:
UNT0266 IN DUCK CR 19 0
END DESCRIPTION:
XS GIS Cut Line= 3
      3565207.39     10420570.18      3565092.37     10420780.69
      3564430.45     10421312.39
#Sta/Elev= 30
  4345.4  351.38  4447.1  347.51  4542.7  346.94  4599.8  347.89  4628.6  342.92
  4671.8  341.88  4700.6  342.79  4735.8  338.28  4803.6  335.70  4826.0  334.91
  4892.6  332.97  4934.5  333.41  4965.3  334.97  4983.8  333.54  4991.8  331.41
  4998.2  333.08  5003.8  330.96  5004.2  330.46  5008.6  330.96  5012.6  333.24
  5041.4  332.12  5111.8  336.04  5148.6  336.52  5155.0  337.72  5169.4  337.07
  5239.8  342.42  5276.6  347.91  5332.6  351.22  5382.3  352.04  5434.3  349.64
#Mann=8,-1,0
  4345.4    0.16       0  4542.7     0.1       0  4803.6    0.16       0
  4826.0     0.1       0  4934.5    0.16       0  4965.3     0.1       0
  5003.8    0.07       0  5008.6     0.1       0
Bank Sta=5003.8,5008.6
Exp/Cntr=0.3,0.1

Type RM Length L Ch R = 1,10000,457,457,457
BEGIN DESCRIPTION:
UNT0266 IN DUCK CR 18 0
END DESCRIPTION:
XS GIS Cut Line= 4
      3564260.57     10419668.32      3564225.85     10420245.53
      3564282.28     10421005.08      3564395.12     10421365.32
#Sta/Elev= 30
  4164.2  358.96  4197.6  362.19  4217.3  362.59  4227.6  361.61  4327.8  357.56
  4357.9  357.13  4385.7  355.31  4438.0  354.05  4518.4  350.80  4559.1  349.69
  4688.5  341.24  4813.1  335.23  4911.8  330.98  4949.1  330.05  4989.2  327.82
  4996.8  324.93  4997.1  324.43  5001.8  324.93  5019.3  328.01  5026.8  328.64
  5123.1  328.89  5164.5  328.75  5250.0  330.49  5311.6  332.93  5499.0  337.78
  5620.8  342.72  5685.7  343.94  5755.8  346.27  5783.0  346.06  5881.6  347.54
#Mann=9,-1,0
  4164.2     0.1       0  4518.4    0.16       0  4813.1     0.1       0
  4911.8    0.16       0  4996.8    0.07       0  5001.8    0.16       0
  5123.1     0.1       0  5311.6    0.05       0  5499.0     0.1       0
Bank Sta=4996.8,5001.8
Exp/Cntr=0.3,0.1

Type RM Length L Ch R = 1,9543,141,141,141
BEGIN DESCRIPTION:
UNT0266 IN DUCK CR 17 0
END DESCRIPTION:
XS GIS Cut Line= 2
      3563701.32     10420212.12      3564087.12     10421176.62
#Sta/Elev= 30
  4600.8  344.62  4664.9  341.85  4675.7  340.58  4694.5  339.92  4772.6  334.69
  4778.0  333.67  4885.7  330.07  4934.1  327.30  4977.2  326.88  4996.1  324.47
  4996.5  323.97  5001.5  324.47  5009.6  326.21  5023.0  326.68  5047.2  326.18
  5063.4  326.83  5084.9  325.73  5106.5  327.68  5125.3  327.53  5149.5  328.53
  5171.1  327.07  5233.0  328.59  5316.5  329.31  5332.7  330.50  5424.2  332.68
  5448.4  333.91  5453.8  333.30  5472.7  333.85  5531.9  332.36  5639.6  335.10
#Mann=3,-1,0
  4600.8    0.08       0  4996.1    0.07       0  5001.5    0.08       0
Bank Sta=4996.1,5001.5
Exp/Cntr=0.3,0.1

Type RM Length L Ch R = 1,9402,355,355,355
BEGIN DESCRIPTION:
UNT0266 IN DUCK CR 16 0
END DESCRIPTION:
XS GIS Cut Line= 2
      3563563.03     10420220.73      3563950.35     10421248.04
#Sta/Elev= 30
  4569.6  340.84  4578.5  340.28  4583.9  341.17  4608.7  339.34  4614.1  340.21
  4633.6  338.95  4638.9  339.91  4663.8  337.91  4669.2  338.83  4694.0  335.60
  4699.4  336.86  4718.9  334.91  4724.2  336.58  4749.1  333.99  4754.4  335.36
  4779.3  333.70  4784.6  334.69  4809.5  334.17  4889.4  327.85  4933.4  326.74
  4966.0  326.67  4995.4  323.24  4995.8  322.74  5000.8  323.24  5019.4  326.59
  5059.9  325.80  5334.0  329.55  5474.8  333.08  5607.2  337.93  5667.5  338.34
#Mann=6,-1,0
  4569.6    0.05       0  4933.4    0.08       0  4995.4    0.07       0
  5000.8    0.08       0  5334.0    0.05       0  5474.8    0.08       0
Bank Sta=4995.4,5000.8
Exp/Cntr=0.3,0.1

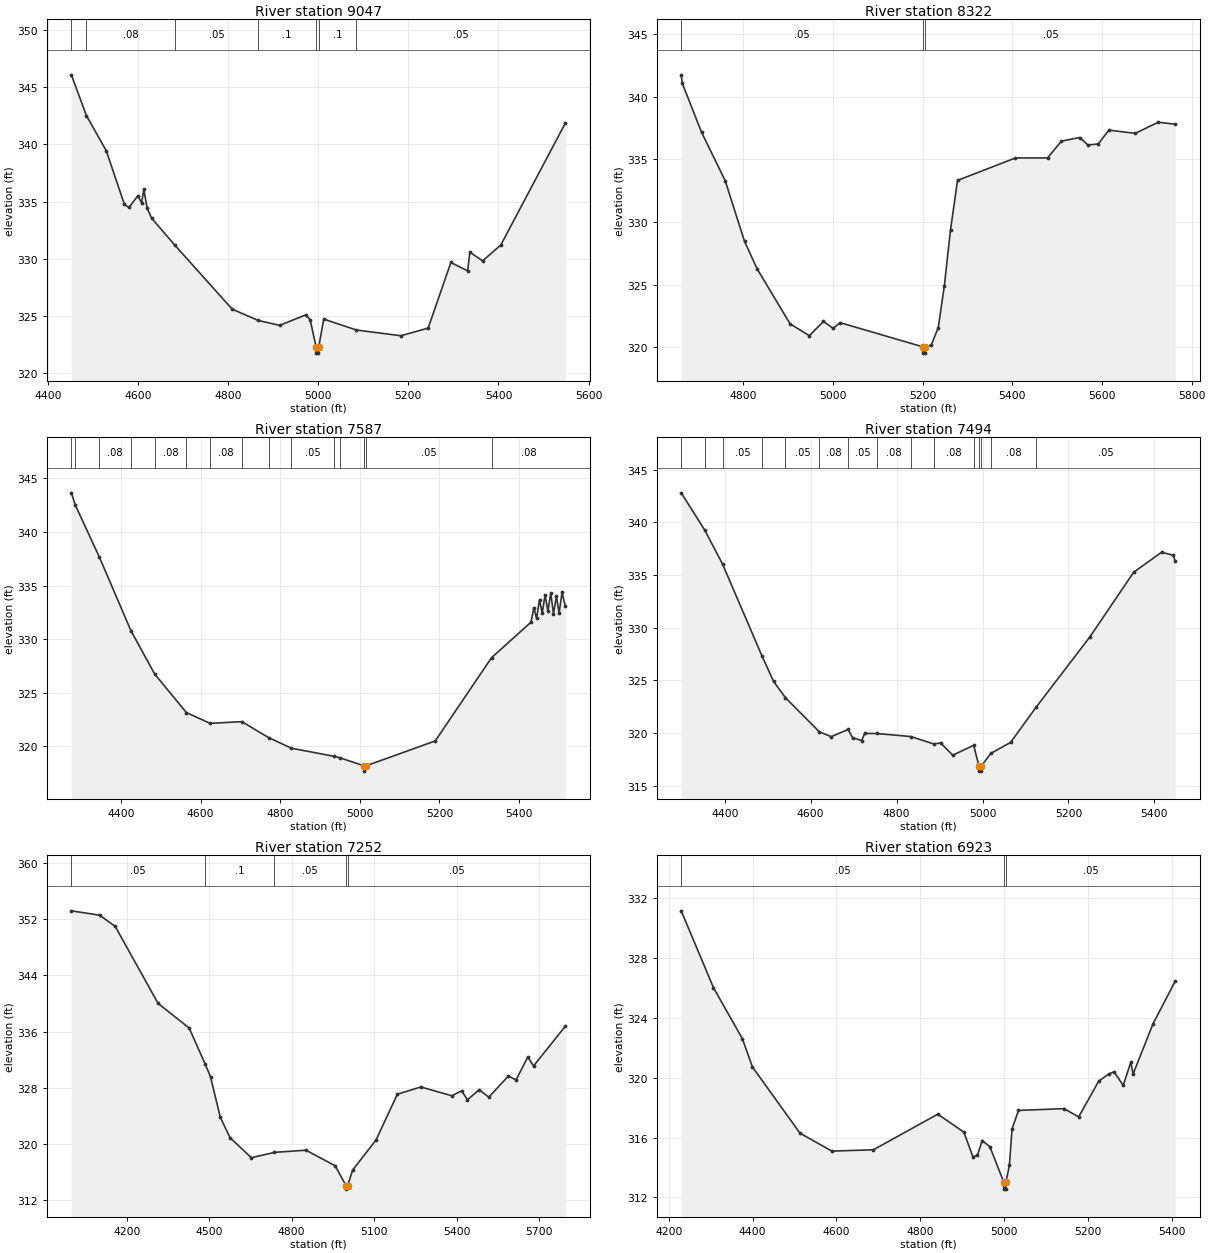
Type RM Length L Ch R = 1,9047,725,725,725
BEGIN DESCRIPTION:
UNT0266 IN DUCK CR 15 0
END DESCRIPTION:
XS GIS Cut Line= 3
      3563422.90     10420054.56      3563375.16     10420531.98
      3563301.37     10421143.95
#Sta/Elev= 30
  4452.3  346.09  4485.6  342.53  4529.8  339.44  4570.0  334.75  4580.0  334.49
  4600.1  335.52  4608.1  334.88  4613.1  336.08  4620.2  334.46  4630.3  333.55
  4682.1  331.18  4809.1  325.59  4866.8  324.60  4914.6  324.17  4972.0  325.08
  4982.1  324.67  4995.6  322.24  4996.0  321.74  5000.6  321.74  5001.0  322.24
  5012.3  324.72  5085.0  323.76  5183.6  323.26  5244.0  323.93  5294.4  329.67
  5331.6  328.94  5336.6  330.57  5364.9  329.81  5405.2  331.20  5548.5  341.87
#Mann=7,-1,0
  4452.3    0.05       0  4485.6    0.08       0  4682.1    0.05       0
  4866.8     0.1       0  4995.6    0.07       0  5001.0     0.1       0
  5085.0    0.05       0
Bank Sta=4995.6,5001
Exp/Cntr=0.3,0.1

Type RM Length L Ch R = 1,8322,735,735,735
BEGIN DESCRIPTION:
UNT0266 IN DUCK CR 14 0
END DESCRIPTION:
XS GIS Cut Line= 3
      3562978.63     10420175.26      3562666.16     10420709.07
      3562551.54     10421178.33
#Sta/Elev= 30
  4661.8  341.74  4664.1  341.07  4707.1  337.16  4759.9  333.29  4802.9  328.46
  4831.4  326.24  4904.5  321.88  4947.5  320.93  4978.9  322.07  5000.4  321.52
  5016.1  321.97  5200.8  320.04  5201.2  319.54  5206.0  319.54  5206.5  320.04
  5219.3  320.18  5235.0  321.58  5248.6  324.93  5262.3  329.38  5278.0  333.32
  5407.2  335.11  5478.6  335.11  5509.5  336.45  5550.6  336.74  5568.7  336.14
  5591.8  336.23  5615.5  337.33  5674.2  337.07  5725.6  337.96  5763.4  337.80
#Mann=3,-1,0
  4661.8    0.05       0  5200.8    0.03       0  5206.5    0.05       0
Bank Sta=5200.8,5206.5
Exp/Cntr=0.3,0.1

Type RM Length L Ch R = 1,7587,93,93,93
BEGIN DESCRIPTION:
UNT0266 IN DUCK CR 13 0
END DESCRIPTION:
XS GIS Cut Line= 4
      3562733.46     10420053.66      3562405.74     10420353.17
      3562184.38     10420626.61      3561858.89     10420930.40
#Sta/Elev= 30
  4275.5  343.66  4285.5  342.51  4346.1  337.64  4425.0  330.80  4485.0  326.73
  4564.4  323.15  4623.9  322.14  4703.9  322.30  4770.9  320.81  4828.2  319.82
  4936.0  319.06  4950.6  318.92  5010.1  318.18  5010.6  317.68  5016.1  318.18
  5189.6  320.50  5331.0  328.27  5430.0  331.58  5437.3  332.94  5444.1  331.94
  5451.5  333.70  5458.3  332.41  5465.6  334.15  5472.5  332.62  5479.8  334.28
  5486.6  332.38  5494.0  333.99  5500.8  332.44  5508.1  334.37  5516.5  333.06
#Mann=15,-1,0
  4275.5    0.08       0  4285.5    0.05       0  4346.1    0.08       0
  4425.0    0.05       0  4485.0    0.08       0  4564.4    0.05       0
  4623.9    0.08       0  4703.9    0.05       0  4770.9    0.08       0
  4828.2    0.05       0  4936.0    0.08       0  4950.6    0.05       0
  5010.1    0.04       0  5016.1    0.05       0  5331.0    0.08       0
Bank Sta=5010.1,5016.1
Exp/Cntr=0.3,0.1

Type RM Length L Ch R = 1,7494,242,242,242
BEGIN DESCRIPTION:
UNT0266 IN DUCK CR 12 0
END DESCRIPTION:
XS GIS Cut Line= 3
      3562651.00     10420016.77      3562049.84     10420622.27
      3561805.86     10420790.68
#Sta/Elev= 30
  4298.8  342.80  4354.0  339.23  4395.1  336.03  4487.1  327.29  4513.6  324.92
  4541.2  323.37  4620.2  320.13  4647.9  319.67  4687.2  320.35  4697.5  319.57
  4718.6  319.30  4725.7  319.97  4753.3  319.97  4833.3  319.68  4886.4  318.98
  4902.5  319.07  4930.8  317.91  4979.4  318.85  4991.5  316.90  4992.0  316.40
  4997.0  316.40  4997.5  316.90  5019.5  318.09  5065.2  319.12  5125.4  322.50
  5250.2  329.15  5351.6  335.26  5416.6  337.16  5444.2  336.88  5448.5  336.30
#Mann=15,-1,0
  4298.8    0.05       0  4354.0    0.08       0  4395.1    0.05       0
  4487.1    0.08       0  4541.2    0.05       0  4620.2    0.08       0
  4687.2    0.05       0  4753.3    0.08       0  4833.3    0.05       0
  4886.4    0.08       0  4979.4    0.05       0  4991.5    0.03       0
  4997.5    0.05       0  5019.5    0.08       0  5125.4    0.05       0
Bank Sta=4991.5,4997.5
Exp/Cntr=0.3,0.1

Type RM Length L Ch R = 1,7252,329,329,329
BEGIN DESCRIPTION:
UNT0266 IN DUCK CR 41 0
END DESCRIPTION:
XS GIS Cut Line= 2
      3562663.35     10419607.51      3561456.95     10420939.75
#Sta/Elev= 30
  3998.5  353.21  4101.2  352.59  4158.0  350.99  4314.1  340.01  4427.0  336.51
  4484.7  331.43  4504.7  329.55  4540.5  323.76  4575.7  320.88  4653.4  318.02
  4737.3  318.78  4852.1  319.09  4958.2  316.87  4997.8  314.04  4998.3  313.54
  5003.8  314.04  5021.8  316.26  5106.9  320.54  5184.6  327.07  5269.8  328.10
  5382.7  326.85  5418.5  327.56  5439.4  326.26  5482.0  327.72  5517.1  326.65
  5588.1  329.65  5616.5  329.11  5659.1  332.39  5680.0  331.10  5795.8  336.77
#Mann=5,-1,0
  3998.5    0.05       0  4484.7     0.1       0  4737.3    0.05       0
  4997.8    0.03       0  5003.8    0.05       0
Bank Sta=4997.8,5003.8
Exp/Cntr=0.3,0.1

Type RM Length L Ch R = 1,6923,189,189,189
BEGIN DESCRIPTION:
UNT0266 IN DUCK CR 41 1
END DESCRIPTION:
XS GIS Cut Line= 2
      3562023.01     10419450.78      3561566.83     10420535.99
#Sta/Elev= 30
  4230.0  331.15  4306.9  326.01  4375.8  322.60  4399.6  320.72  4513.0  316.29
  4588.9  315.09  4688.0  315.18  4841.3  317.56  4903.5  316.36  4925.2  314.70
  4936.0  314.82  4947.1  315.79  4965.5  315.39  4998.1  313.05  4998.6  312.55
  5003.6  312.55  5004.1  313.05  5012.0  314.14  5018.4  316.58  5033.7  317.81
  5142.1  317.93  5177.2  317.38  5224.7  319.76  5248.4  320.24  5261.5  320.39
  5283.2  319.48  5301.3  321.03  5306.8  320.25  5354.3  323.60  5407.2  326.45
#Mann=3,-1,0
  4230.0    0.05       0  4998.1    0.03       0  5004.1    0.05       0
Bank Sta=4998.1,5004.1
Exp/Cntr=0.3,0.1

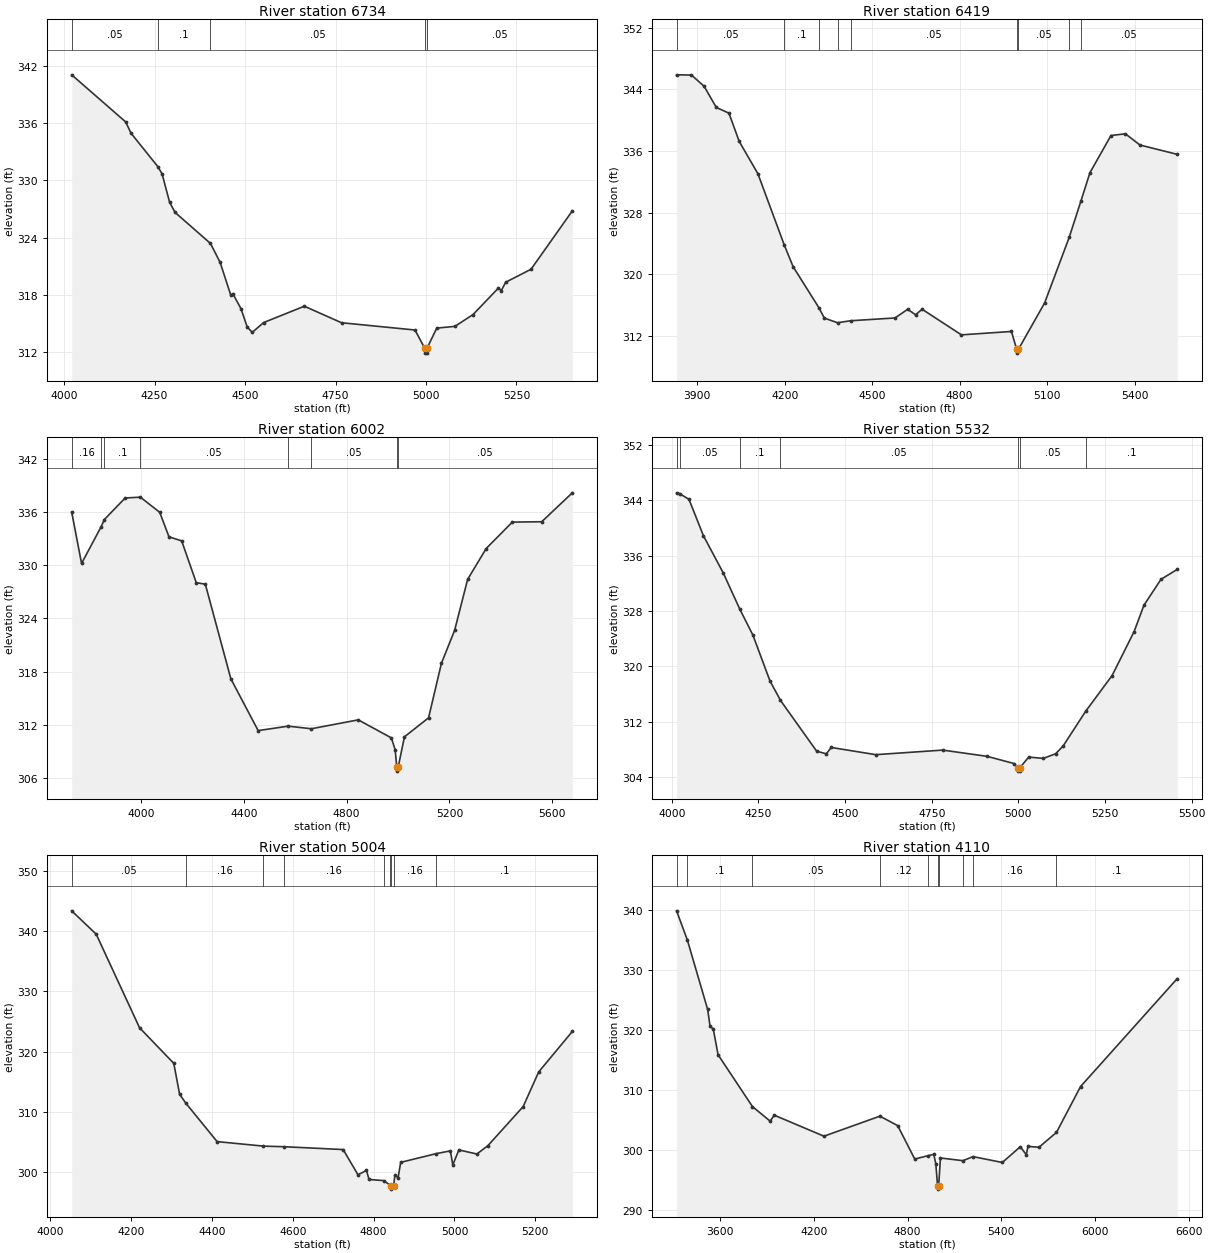
Type RM Length L Ch R = 1,6734,315,315,315
BEGIN DESCRIPTION:
UNT0266 IN DUCK CR 9 0
END DESCRIPTION:
XS GIS Cut Line= 4
      3561994.07     10419275.04      3561779.52     10419571.88
      3561546.44     10420060.17      3561513.89     10420535.43
#Sta/Elev= 30
  4020.8  341.03  4170.0  336.10  4184.8  334.92  4258.7  331.43  4270.6  330.66
  4291.5  327.69  4306.2  326.64  4404.4  323.38  4431.1  321.39  4460.6  317.96
  4466.1  318.13  4488.8  316.54  4505.9  314.64  4519.8  314.07  4551.3  315.10
  4663.8  316.81  4766.6  315.08  4969.7  314.32  4996.7  312.40  4997.2  311.90
  5002.3  311.90  5002.8  312.40  5029.8  314.52  5080.0  314.70  5130.1  315.94
  5200.2  318.71  5208.2  318.45  5220.3  319.32  5290.4  320.68  5404.5  326.79
#Mann=5,-1,0
  4020.8    0.05       0  4258.7     0.1       0  4404.4    0.05       0
  4996.7    0.03       0  5002.8    0.05       0
Bank Sta=4996.7,5002.8
Exp/Cntr=0.3,0.1

Type RM Length L Ch R = 1,6419,417,417,417
BEGIN DESCRIPTION:
UNT0266 IN DUCK CR 8 1
END DESCRIPTION:
XS GIS Cut Line= 3
      3561999.29     10419077.12      3561308.16     10419958.60
      3560936.95     10420425.88
#Sta/Elev= 30
  3829.1  345.89  3880.3  345.86  3923.7  344.40  3965.3  341.66  4008.7  340.92
  4043.9  337.26  4108.1  333.06  4198.3  323.84  4228.8  321.01  4317.4  315.68
  4335.9  314.34  4381.2  313.74  4426.1  314.00  4578.2  314.36  4621.6  315.48
  4648.7  314.78  4671.3  315.49  4806.0  312.17  4977.7  312.61  4995.4  310.30
  4995.9  309.80  5001.5  310.30  5091.4  316.31  5175.7  324.82  5216.3  329.57
  5246.8  333.20  5318.9  338.02  5368.5  338.24  5418.2  336.79  5546.0  335.58
#Mann=9,-1,0
  3829.1    0.05       0  4198.3     0.1       0  4317.4    0.05       0
  4381.2     0.1       0  4426.1    0.05       0  4995.4    0.03       0
  5001.5    0.05       0  5175.7     0.1       0  5216.3    0.05       0
Bank Sta=4995.4,5001.5
Exp/Cntr=0.3,0.1

Type RM Length L Ch R = 1,6002,470,470,470
BEGIN DESCRIPTION:
UNT0266 IN DUCK CR 8 0
END DESCRIPTION:
XS GIS Cut Line= 3
      3562124.25     10418769.86      3561296.16     10419519.83
      3560608.66     10419983.37
#Sta/Elev= 30
  3731.2  336.01  3769.5  330.21  3846.2  334.37  3858.2  335.16  3939.1  337.59
  3998.3  337.68  4073.6  335.97  4109.4  333.21  4158.8  332.75  4215.5  328.04
  4250.7  327.87  4350.0  317.20  4456.1  311.36  4572.6  311.86  4663.2  311.57
  4845.4  312.57  4973.9  310.54  4988.9  309.20  4994.8  307.29  4995.3  306.79
  5000.9  307.29  5024.9  310.66  5118.7  312.80  5168.8  318.96  5219.8  322.65
  5270.7  328.42  5342.7  331.89  5444.3  334.87  5558.6  334.91  5677.6  338.17
#Mann=8,-1,0
  3731.2    0.16       0  3846.2    0.05       0  3858.2     0.1       0
  3998.3    0.05       0  4572.6     0.1       0  4663.2    0.05       0
  4994.8    0.03       0  5000.9    0.05       0
Bank Sta=4994.8,5000.9
Exp/Cntr=0.3,0.1

Type RM Length L Ch R = 1,5532,528,528,528
BEGIN DESCRIPTION:
UNT0266 IN DUCK CR 7 1
END DESCRIPTION:
XS GIS Cut Line= 4
      3561494.04     10418493.83      3561193.58     10418846.62
      3560951.67     10419163.59      3560551.79     10419587.10
#Sta/Elev= 30
  4013.7  345.10  4022.2  344.99  4049.5  344.16  4091.2  338.90  4148.3  333.53
  4196.5  328.25  4233.9  324.54  4283.3  317.90  4313.5  315.10  4418.0  307.75
  4445.8  307.37  4460.1  308.29  4588.5  307.25  4781.8  307.91  4909.6  307.01
  4987.3  305.97  4998.3  305.37  4998.8  304.87  5004.0  304.87  5004.5  305.37
  5029.7  306.90  5072.2  306.71  5107.4  307.38  5128.9  308.48  5194.3  313.53
  5270.4  318.68  5334.0  325.04  5362.3  328.85  5411.6  332.60  5458.3  334.03
#Mann=7,-1,0
  4013.7     0.1       0  4022.2    0.05       0  4196.5     0.1       0
  4313.5    0.05       0  4998.3    0.03       0  5004.5    0.05       0
  5194.3     0.1       0
Bank Sta=4998.3,5004.5
Exp/Cntr=0.3,0.1

Type RM Length L Ch R = 1,5004,894,894,894
BEGIN DESCRIPTION:
UNT0266 IN DUCK CR 7 0
END DESCRIPTION:
XS GIS Cut Line= 4
      3561274.48     10418218.61      3560623.42     10418743.79
      3560445.47     10419008.55      3560442.11     10419091.60
#Sta/Elev= 30
  4053.0  343.35  4113.7  339.47  4220.9  323.96  4305.6  318.06  4320.0  312.94
  4335.7  311.43  4412.8  305.09  4527.2  304.34  4579.3  304.24  4724.7  303.77
  4761.4  299.58  4782.2  300.32  4788.7  298.81  4825.3  298.62  4841.5  297.82
  4843.1  297.71  4843.6  297.21  4849.3  297.71  4852.6  299.52  4860.6  299.13
  4867.0  301.65  4955.1  303.10  4989.9  303.55  4995.9  301.22  5010.9  303.71
  5055.6  303.03  5082.9  304.43  5169.9  310.89  5208.5  316.65  5291.6  323.35
#Mann=9,-1,0
  4053.0    0.05       0  4335.7    0.16       0  4527.2    0.05       0
  4579.3    0.16       0  4825.3     0.1       0  4841.5    0.16       0
  4843.1    0.07       0  4849.3    0.16       0  4955.1     0.1       0
Bank Sta=4843.1,4849.3
Exp/Cntr=0.3,0.1

Type RM Length L Ch R = 1,4110,928,928,928
BEGIN DESCRIPTION:
UNT0266 IN DUCK CR 6 0
END DESCRIPTION:
XS GIS Cut Line= 4
      3561456.79     10417350.54      3560163.35     10418179.55
      3560028.80     10418379.21      3560328.27     10419776.71
#Sta/Elev= 30
  3320.2  339.92  3389.2  335.06  3519.3  323.49  3534.5  320.74  3555.6  320.18
  3586.1  315.93  3806.2  307.30  3919.1  304.88  3946.2  305.86  4264.1  302.36
  4622.5  305.70  4736.6  304.12  4845.7  298.55  4931.5  299.12  4967.6  299.33
  4980.4  297.79  4992.0  294.04  4992.5  293.54  4998.6  294.04  5010.3  298.73
  5154.4  298.28  5218.7  298.96  5406.6  297.98  5521.4  300.60  5560.0  299.29
  5570.9  300.66  5641.8  300.52  5753.2  302.99  5907.7  310.64  6526.5  328.62
#Mann=10,-1,0
  3320.2    0.16       0  3389.2     0.1       0  3806.2    0.05       0
  4622.5    0.12       0  4931.5    0.16       0  4992.0    0.07       0
  4998.6    0.16       0  5154.4    0.12       0  5218.7    0.16       0
  5753.2     0.1       0
Bank Sta=4992,4998.6
Exp/Cntr=0.3,0.1

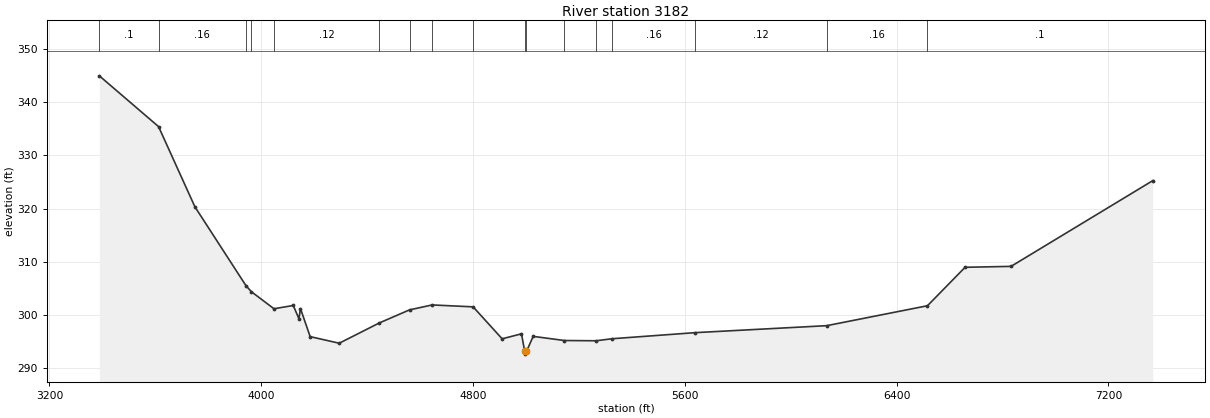
Type RM Length L Ch R = 1,3182,0,0,0
BEGIN DESCRIPTION:
UNT0266 IN DUCK CR 1 0
END DESCRIPTION:
XS GIS Cut Line= 4
      3561213.72     10416755.93      3559981.06     10417524.17
      3559724.98     10417680.42      3560241.48     10419846.24
#Sta/Elev= 30
  3388.4  344.97  3612.1  335.42  3749.3  320.35  3942.3  305.51  3963.1  304.36
  4048.2  301.17  4120.9  301.79  4142.3  299.30  4148.2  301.20  4184.7  295.93
  4294.5  294.69  4445.8  298.50  4560.0  300.96  4645.6  301.89  4800.3  301.53
  4909.9  295.52  4983.0  296.46  4995.2  293.14  4995.7  292.64  5001.8  293.14
  5027.1  295.98  5145.1  295.20  5265.3  295.15  5324.2  295.53  5639.5  296.68
  6135.8  297.99  6516.5  301.74  6658.6  308.97  6832.2  309.14  7367.4  325.26
#Mann=17,-1,0
  3388.4     0.1       0  3612.1    0.16       0  3942.3     0.1       0
  3963.1    0.16       0  4048.2    0.12       0  4445.8     0.1       0
  4560.0    0.12       0  4645.6     0.1       0  4800.3    0.12       0
  4995.2    0.07       0  5001.8    0.12       0  5145.1    0.16       0
  5265.3    0.12       0  5324.2    0.16       0  5639.5    0.12       0
  6135.8    0.16       0  6516.5     0.1       0
Bank Sta=4995.2,5001.8
Exp/Cntr=0.3,0.1

Chan Stop Cuts=-1