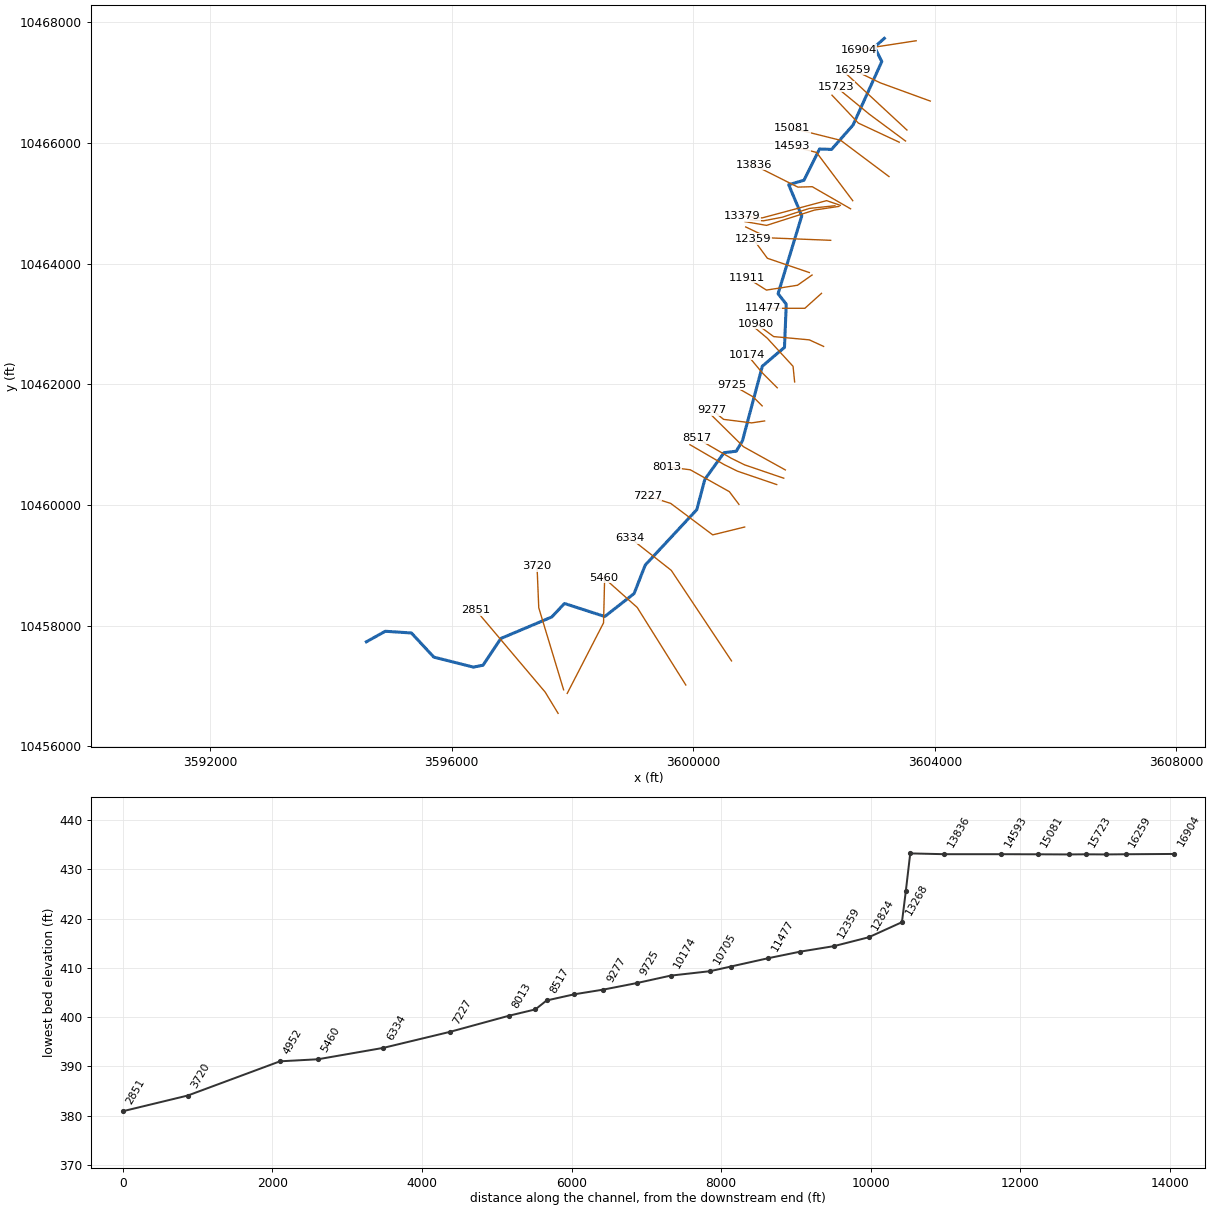
--- UNT0273 IN DUCK CR.prj (project) ---

Proj Title=UNT0273 IN DUCK CR Base Level Engineering
Current Plan=p01
Default Exp/Contr=0.3,0.1
English Units
Geom File=g01
Flow File=f01
Plan File=p01
BEGIN DESCRIPTION:
UNT0273 IN DUCK CR
END DESCRIPTION:

--- UNT0273 IN DUCK CR.p01 (plan) ---

Plan Title=Multiple Run
Short Identifier=Multiple
Geom File=g01
Flow File=f01
Subcritical Flow
K Sum by GR= 0
Std Step Tol= 0.01
Critical Tol= 0.01
Num of Std Step Trials= 20
Max Error Tol= 0.3
Flow Tol Ratio= 0.001
Split Flow NTrial= 30
Split Flow Tol= 0.02
Split Flow Ratio= 0.02
Log Output Level= 0
Friction Slope Method= 1
Unsteady Friction Slope Method= 2
Unsteady Bridges Friction Slope Method= 1
Parabolic Critical Depth
Global Vel Dist=  1 , 1 , 1
Global Log Level= 0
CheckData=True
Encroach Param= -1, 0, 0, 0
BEGIN DESCRIPTION:
Multiple Run
END DESCRIPTION:

--- UNT0273 IN DUCK CR.f01 (steady flow) ---

Flow Title=Multiple
Number of Profiles=7
Profile Names=10-year,25-year,50-year,1pct_min,100-year,1pct_plu,500-year
River Rch & RM= UNT0273 IN DUCK ,Reach-1,16904
    1061    1464    1799    1612    2180    2949    3194
River Rch & RM= UNT0273 IN DUCK ,Reach-1,15723
    1530    2156    2684    2436    3294    4455    4950
River Rch & RM= UNT0273 IN DUCK ,Reach-1,12824
    1921    2736    3432    3133    4238    5731    6449
River Rch & RM= UNT0273 IN DUCK ,Reach-1,6334
    2688    3882    4913    4521    6114    8269    9455
River Rch & RM= UNT0273 IN DUCK ,Reach-1,42
    4312    6350    8144    7584   10257   13871   16244
Boundary for River Rch & Prof#=UNT0273 IN DUCK ,Reach-1,1
Up Type=0
Dn Type=3
Dn Slope=0.005
Boundary for River Rch & Prof#=UNT0273 IN DUCK ,Reach-1,2
Up Type=0
Dn Type=3
Dn Slope=0.005
Boundary for River Rch & Prof#=UNT0273 IN DUCK ,Reach-1,3
Up Type=0
Dn Type=3
Dn Slope=0.005
Boundary for River Rch & Prof#=UNT0273 IN DUCK ,Reach-1,4
Up Type=0
Dn Type=3
Dn Slope=0.005
Boundary for River Rch & Prof#=UNT0273 IN DUCK ,Reach-1,5
Up Type=0
Dn Type=3
Dn Slope=0.005
Boundary for River Rch & Prof#=UNT0273 IN DUCK ,Reach-1,6
Up Type=0
Dn Type=3
Dn Slope=0.005
Boundary for River Rch & Prof#=UNT0273 IN DUCK ,Reach-1,7
Up Type=0
Dn Type=3
Dn Slope=0.005

--- UNT0273 IN DUCK CR.g01 (geometry) ---

Geom Title=Existing Conditions

River Reach=UNT0273 IN DUCK ,Reach-1
Reach XY= 30
      3603165.68     10467731.57      3603002.48     10467587.82
      3603123.32     10467346.85      3602646.84     10466294.42
      3602292.11     10465891.64      3602092.19     10465897.27
      3601834.32     10465380.09      3601581.67     10465306.35
      3601798.38     10464790.46      3601406.24     10463500.50
      3601541.43     10463326.25      3601512.11     10462611.64
      3601145.63     10462299.95      3600816.52     10461063.98
      3600713.75     10460890.72      3600511.54     10460866.06
      3600193.14     10460423.70      3600060.33     10459922.50
      3599206.92     10459004.43      3599021.56     10458531.73
      3598536.72     10458151.88      3597869.30     10458367.29
      3597658.97     10458143.94      3596815.65     10457787.67
      3596520.16     10457344.62      3596361.09     10457313.20
      3595705.71     10457478.99      3595334.68     10457878.94
      3594902.74     10457907.41      3594589.80     10457733.11

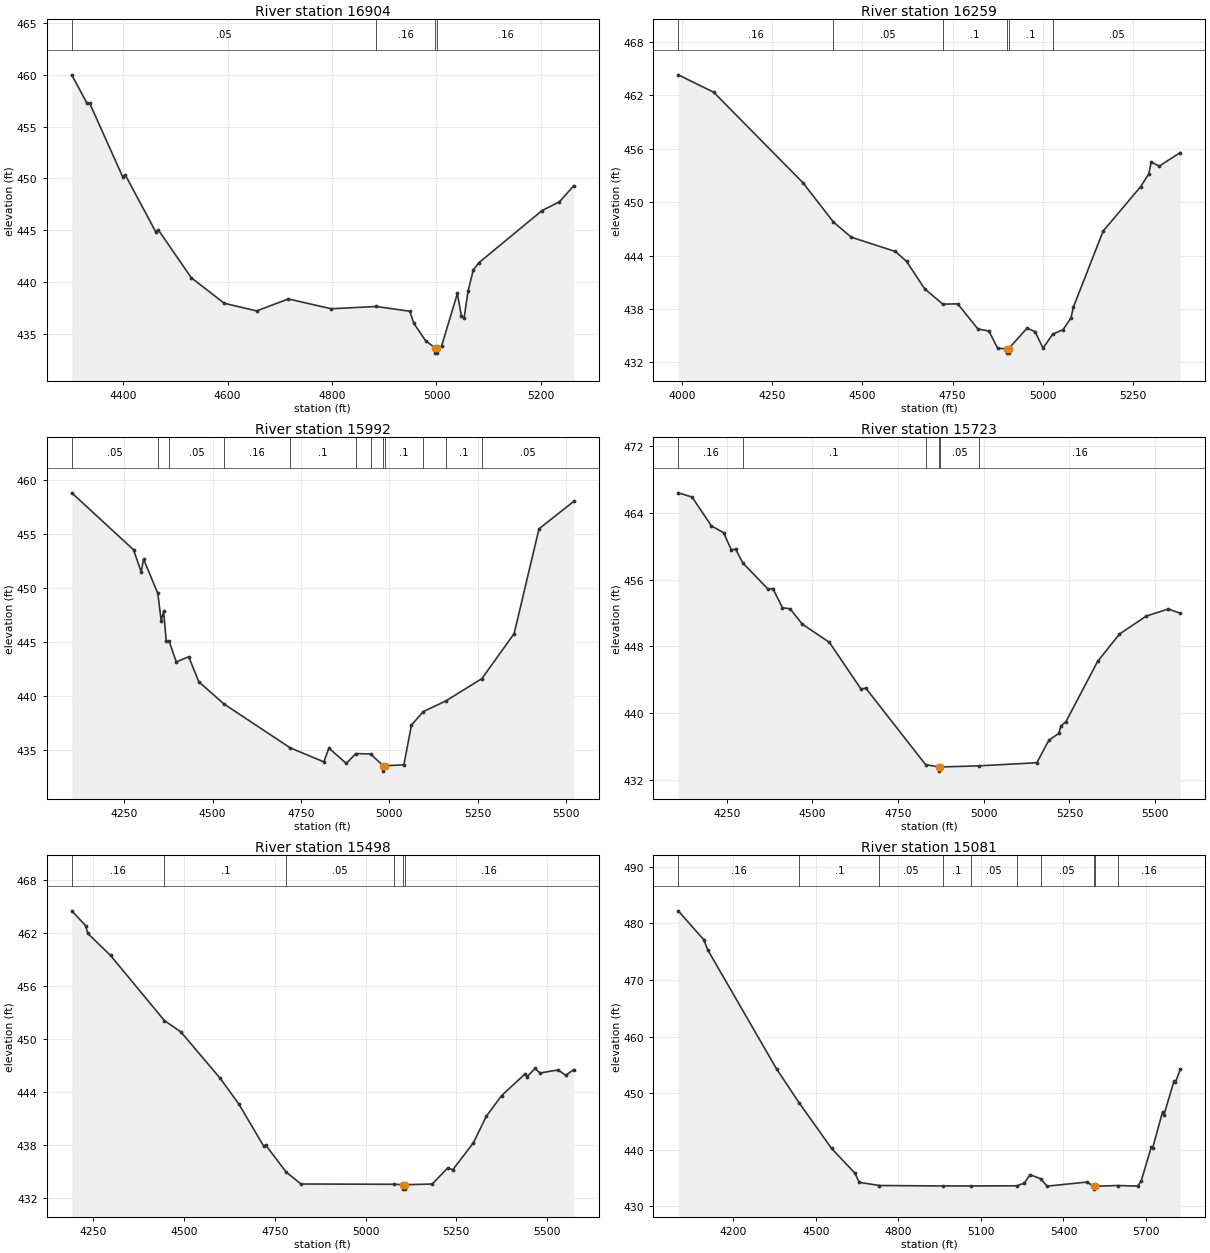
Type RM Length L Ch R = 1,16904,645,645,645
BEGIN DESCRIPTION:
UNT0273 IN DUCK CR 4 0
END DESCRIPTION:
XS GIS Cut Line= 3
      3603692.07     10467691.64      3603042.11     10467591.64
      3602742.15     10467541.65
#Sta/Elev= 30
  4301.4  460.02  4330.4  457.28  4335.5  457.30  4398.7  450.18  4403.8  450.35
  4462.0  444.86  4467.0  445.04  4530.3  440.40  4593.5  437.93  4655.5  437.19
  4716.2  438.35  4798.4  437.40  4884.6  437.62  4948.9  437.16  4956.5  436.00
  4979.3  434.30  4997.6  433.61  4997.8  433.11  5001.3  433.11  5001.6  433.61
  5009.7  433.79  5040.1  438.88  5047.7  436.68  5052.8  436.49  5060.4  439.08
  5070.5  441.15  5080.7  441.83  5202.3  446.90  5235.3  447.73  5263.1  449.31
#Mann=4,-1,0
  4301.4    0.05       0  4884.6    0.16       0  4997.6    0.07       0
  5001.6    0.16       0
Bank Sta=4997.6,5001.6
Exp/Cntr=0.3,0.1

Type RM Length L Ch R = 1,16259,267,267,267
BEGIN DESCRIPTION:
UNT0273 IN DUCK CR 22 1
END DESCRIPTION:
XS GIS Cut Line= 3
      3603926.36     10466691.98      3603099.55     10466993.63
      3602639.45     10467215.00
#Sta/Elev= 30
  3990.0  464.29  4088.1  462.34  4335.2  452.19  4419.8  447.77  4469.3  446.06
  4591.5  444.46  4622.6  443.34  4672.6  440.27  4722.8  438.55  4764.2  438.58
  4820.0  435.77  4850.6  435.53  4874.9  433.58  4901.0  433.55  4901.3  433.05
  4905.0  433.05  4905.2  433.55  4956.1  435.85  4978.2  435.47  5000.4  433.61
  5027.5  435.19  5055.9  435.68  5078.1  437.03  5084.2  438.18  5166.9  446.75
  5270.7  451.73  5293.4  453.17  5300.1  454.51  5322.3  454.04  5380.7  455.57
#Mann=6,-1,0
  3990.0    0.16       0  4419.8    0.05       0  4722.8     0.1       0
  4901.0    0.07       0  4905.2     0.1       0  5027.5    0.05       0
Bank Sta=4901,4905.2
Exp/Cntr=0.3,0.1

Type RM Length L Ch R = 1,15992,269,269,269
BEGIN DESCRIPTION:
UNT0273 IN DUCK CR 3 0
END DESCRIPTION:
XS GIS Cut Line= 2
      3603539.83     10466212.19      3602498.85     10467177.26
#Sta/Elev= 30
  4102.1  458.85  4276.8  453.56  4298.3  451.51  4305.1  452.70  4345.4  449.51
  4355.0  446.96  4361.8  447.84  4369.2  445.10  4377.2  445.08  4397.5  443.15
  4432.7  443.63  4461.0  441.32  4531.3  439.27  4719.8  435.17  4814.8  433.87
  4829.0  435.15  4878.3  433.72  4904.9  434.64  4946.8  434.60  4982.7  433.51
  4983.0  433.01  4987.1  433.51  5041.0  433.59  5062.5  437.28  5095.4  438.53
  5159.2  439.52  5261.6  441.60  5352.8  445.78  5423.1  455.51  5521.6  458.06
#Mann=12,-1,0
  4102.1    0.05       0  4345.4     0.1       0  4377.2    0.05       0
  4531.3    0.16       0  4719.8     0.1       0  4904.9    0.16       0
  4946.8     0.1       0  4982.7    0.07       0  4987.1     0.1       0
  5095.4    0.05       0  5159.2     0.1       0  5261.6    0.05       0
Bank Sta=4982.7,4987.1
Exp/Cntr=0.3,0.1

Type RM Length L Ch R = 1,15723,225,225,225
BEGIN DESCRIPTION:
UNT0273 IN DUCK CR 22 0
END DESCRIPTION:
XS GIS Cut Line= 3
      3603516.18     10466030.11      3602915.70     10466475.49
      3602361.73     10466930.66
#Sta/Elev= 30
  4108.7  466.42  4149.1  465.91  4205.4  462.46  4240.8  461.64  4263.2  459.62
  4276.3  459.63  4297.3  458.00  4370.2  454.89  4384.8  454.94  4412.6  452.64
  4434.9  452.51  4470.4  450.68  4549.5  448.49  4641.5  442.91  4656.1  442.98
  4830.0  433.83  4868.5  433.54  4868.8  433.04  4872.9  433.54  4984.9  433.67
  5154.8  434.05  5190.0  436.75  5218.7  437.56  5225.1  438.46  5239.5  438.96
  5332.0  446.20  5395.9  449.48  5474.1  451.64  5538.0  452.48  5573.3  451.98
#Mann=6,-1,0
  4108.7    0.16       0  4297.3     0.1       0  4830.0    0.05       0
  4868.5    0.07       0  4872.9    0.05       0  4984.9    0.16       0
Bank Sta=4868.5,4872.9
Exp/Cntr=0.3,0.1

Type RM Length L Ch R = 1,15498,417,417,417
BEGIN DESCRIPTION:
UNT0273 IN DUCK CR 23 0
END DESCRIPTION:
XS GIS Cut Line= 3
      3603412.06     10466010.55      3602734.96     10466327.39
      3602298.78     10466789.62
#Sta/Elev= 30
  4190.7  464.50  4229.0  462.81  4234.8  461.95  4297.5  459.45  4445.9  452.08
  4491.2  450.80  4599.2  445.57  4651.1  442.63  4719.6  437.86  4725.1  437.99
  4781.3  434.94  4822.0  433.59  5078.4  433.56  5103.9  433.51  5104.2  433.01
  5108.0  433.01  5108.3  433.51  5183.8  433.59  5226.3  435.41  5240.4  435.21
  5297.1  438.25  5332.3  441.23  5374.7  443.59  5438.7  446.02  5445.5  445.75
  5466.6  446.66  5480.7  446.15  5530.5  446.50  5551.5  445.89  5573.8  446.54
#Mann=6,-1,0
  4190.7    0.16       0  4445.9     0.1       0  4781.3    0.05       0
  5078.4    0.16       0  5103.9   0.033       0  5108.3    0.16       0
Bank Sta=5103.9,5108.3
Exp/Cntr=0.3,0.1

Type RM Length L Ch R = 1,15081,488,488,488
BEGIN DESCRIPTION:
UNT0273 IN DUCK CR 21 1
END DESCRIPTION:
XS GIS Cut Line= 3
      3603242.11     10465441.64      3602442.11     10466041.64
      3601642.13     10466241.64
#Sta/Elev= 30
  4000.0  482.23  4092.7  477.13  4107.3  475.32  4357.3  454.29  4439.0  448.32
  4557.3  440.23  4642.7  435.83  4657.3  434.25  4731.3  433.68  4961.4  433.60
  5062.2  433.60  5230.4  433.63  5257.7  434.10  5278.3  435.59  5316.9  434.88
  5340.2  433.56  5484.5  434.29  5510.6  433.54  5510.9  433.04  5515.1  433.54
  5596.4  433.68  5670.0  433.58  5682.9  434.55  5719.0  440.46  5724.1  440.30
  5760.2  446.74  5765.4  446.21  5801.4  452.09  5806.6  451.89  5824.6  454.22
#Mann=10,-1,0
  4000.0    0.16       0  4439.0     0.1       0  4731.3    0.05       0
  4961.4     0.1       0  5062.2    0.05       0  5230.4    0.16       0
  5316.9    0.05       0  5510.6    0.07       0  5515.1    0.05       0
  5596.4    0.16       0
Bank Sta=5510.6,5515.1
Exp/Cntr=0.3,0.1

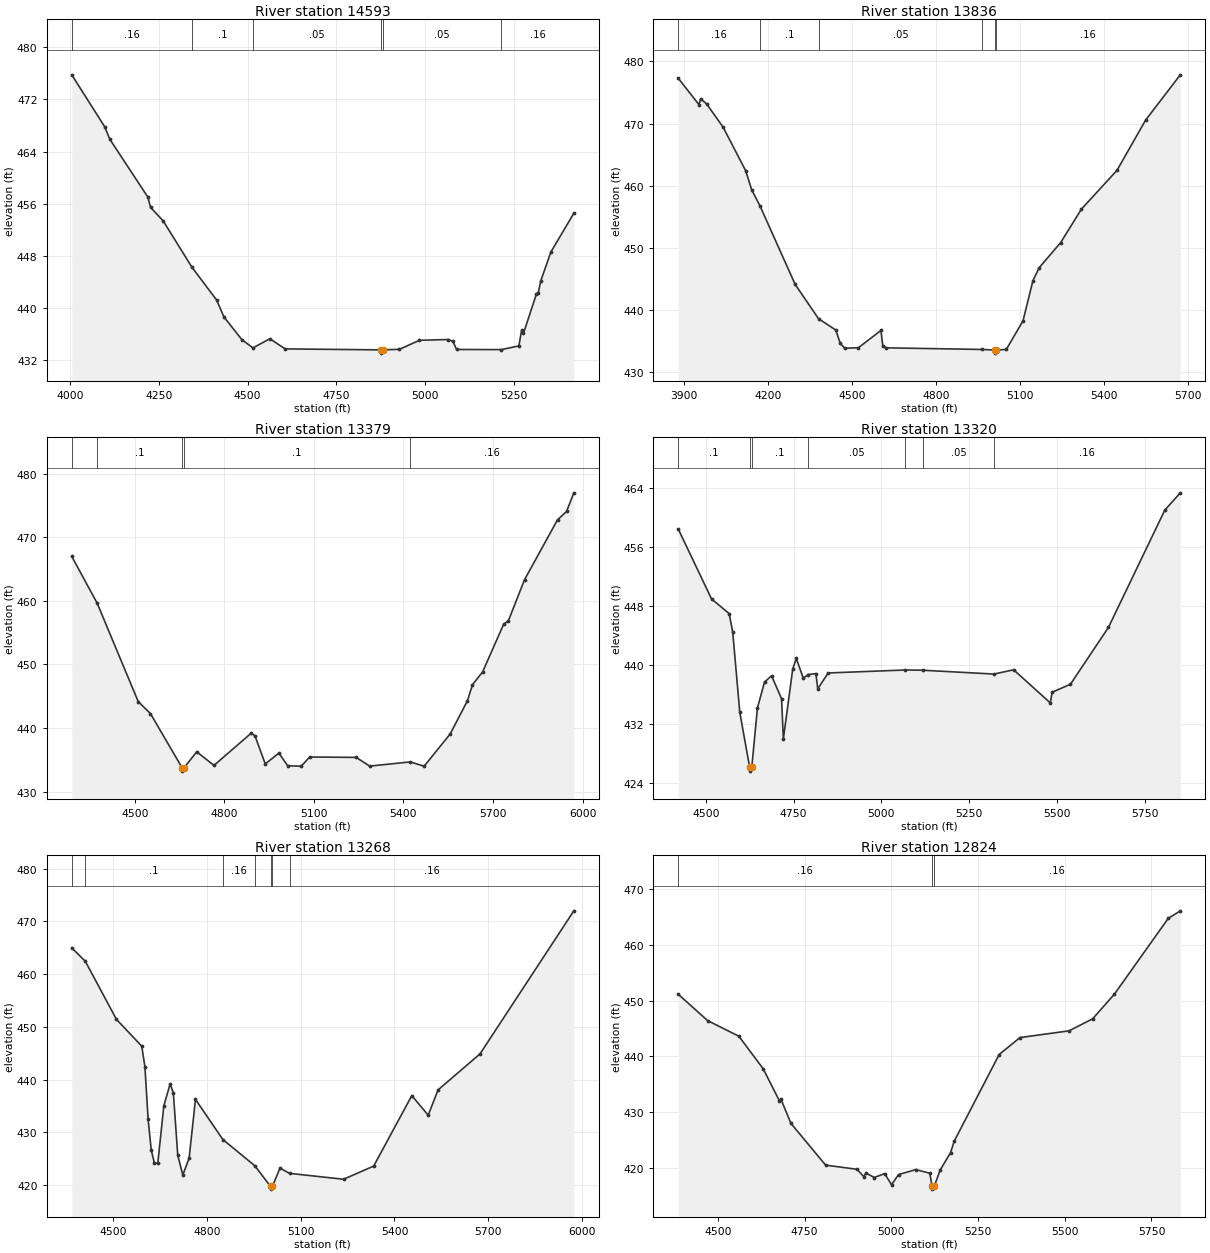
Type RM Length L Ch R = 1,14593,757,757,757
BEGIN DESCRIPTION:
UNT0273 IN DUCK CR 20 0
END DESCRIPTION:
XS GIS Cut Line= 3
      3602642.09     10465041.66      3602042.11     10465841.64
      3601642.09     10465941.65
#Sta/Elev= 30
  4005.5  475.77  4098.2  467.79  4112.8  465.86  4219.0  457.05  4227.3  455.42
  4262.8  453.34  4343.4  446.25  4412.8  441.22  4433.6  438.61  4483.6  435.15
  4515.1  433.86  4562.8  435.27  4605.5  433.71  4874.5  433.56  4874.9  433.06
  4880.2  433.56  4927.3  433.65  4983.6  435.03  5064.7  435.15  5077.6  434.86
  5087.9  433.62  5214.1  433.60  5263.2  434.17  5270.9  436.57  5276.1  436.10
  5312.1  442.06  5317.3  442.24  5325.0  444.18  5353.4  448.60  5417.8  454.53
#Mann=6,-1,0
  4005.5    0.16       0  4343.4     0.1       0  4515.1    0.05       0
  4874.5   0.033       0  4880.2    0.05       0  5214.1    0.16       0
Bank Sta=4874.5,4880.2
Exp/Cntr=0.3,0.1

Type RM Length L Ch R = 1,13836,457,457,457
BEGIN DESCRIPTION:
UNT0273 IN DUCK CR 24 0
END DESCRIPTION:
XS GIS Cut Line= 4
      3602606.55     10464907.09      3601971.14     10465273.40
      3601733.30     10465266.46      3601000.64     10465634.53
#Sta/Elev= 30
  3880.9  477.28  3954.8  473.04  3960.6  473.98  3982.1  473.16  4041.0  469.41
  4121.5  462.41  4143.0  459.33  4173.3  456.67  4298.1  444.11  4381.4  438.60
  4443.2  436.77  4459.0  434.63  4474.7  433.84  4523.7  433.93  4604.1  436.71
  4610.9  434.19  4623.4  433.91  4966.1  433.65  5009.4  433.56  5009.9  433.06
  5015.2  433.56  5051.3  433.65  5111.0  438.26  5146.2  444.69  5168.6  446.80
  5245.3  450.84  5319.3  456.22  5446.7  462.49  5548.2  470.54  5672.2  477.83
#Mann=6,-1,0
  3880.9    0.16       0  4173.3     0.1       0  4381.4    0.05       0
  4966.1    0.16       0  5009.4    0.07       0  5015.2    0.16       0
Bank Sta=5009.4,5015.2
Exp/Cntr=0.3,0.1

Type RM Length L Ch R = 1,13379,59,59,59
BEGIN DESCRIPTION:
UNT0273 IN DUCK CR 19 1
END DESCRIPTION:
XS GIS Cut Line= 4
      3602437.42     10464964.34      3602209.55     10465042.47
      3601141.84     10464756.01      3600807.68     10464786.39
#Sta/Elev= 30
  4289.1  466.97  4374.1  459.63  4511.7  444.15  4552.8  442.26  4659.0  433.72
  4659.5  433.22  4664.9  433.72  4707.7  436.26  4765.5  434.12  4889.7  439.17
  4902.5  438.81  4937.3  434.35  4982.9  436.05  5012.2  434.08  5057.4  433.99
  5086.4  435.44  5241.7  435.38  5287.0  434.01  5423.0  434.67  5469.5  433.99
  5556.7  439.06  5614.5  444.28  5631.5  446.81  5665.3  448.81  5735.6  456.29
  5751.8  456.87  5805.9  463.32  5916.3  472.73  5946.5  474.04  5971.0  476.97
#Mann=5,-1,0
  4289.1    0.16       0  4374.1     0.1       0  4659.0   0.033       0
  4664.9     0.1       0  5423.0    0.16       0
Bank Sta=4659,4664.9
Exp/Cntr=0.3,0.1

Type RM Length L Ch R = 1,13320,52,52,52
BEGIN DESCRIPTION:
UNT0273 IN DUCK CR 18 0
END DESCRIPTION:
XS GIS Cut Line= 6
      3602346.43     10464957.91      3601927.17     10464913.64
      3601648.53     10464825.10      3601476.65     10464767.80
      3601161.55     10464707.91      3600948.00     10464723.53
#Sta/Elev= 30
  4421.5  458.43  4516.3  448.95  4566.6  446.95  4576.7  444.44  4596.8  433.56
  4625.0  426.08  4625.5  425.58  4630.9  426.08  4647.1  434.15  4667.2  437.66
  4687.3  438.52  4715.8  435.40  4720.9  429.94  4747.6  439.43  4757.7  440.87
  4777.8  438.18  4791.2  438.68  4813.7  438.81  4818.8  436.74  4848.4  438.90
  5067.0  439.30  5118.5  439.27  5320.9  438.75  5376.8  439.33  5481.3  434.83
  5486.4  436.28  5538.6  437.37  5646.8  445.08  5807.3  460.99  5851.5  463.34
#Mann=7,-1,0
  4421.5     0.1       0  4625.0   0.033       0  4630.9     0.1       0
  4791.2    0.05       0  5067.0    0.16       0  5118.5    0.05       0
  5320.9    0.16       0
Bank Sta=4625,4630.9
Exp/Cntr=0.3,0.1

Type RM Length L Ch R = 1,13268,444,444,444
BEGIN DESCRIPTION:
Mapping XS 45ac4d9f
END DESCRIPTION:
XS GIS Cut Line= 4
      3602413.55     10464946.98      3602009.90     10464886.22
      3601215.63     10464632.31      3600856.24     10464695.10
#Sta/Elev= 30
  4367.3  465.00  4410.6  462.46  4510.3  451.44  4591.2  446.37  4601.4  442.46
  4611.5  432.60  4621.6  426.68  4631.7  424.22  4642.6  424.14  4662.0  435.07
  4682.3  439.25  4692.4  437.49  4706.5  425.68  4722.7  421.94  4742.9  425.14
  4763.2  436.28  4850.9  428.66  4953.4  423.68  5003.7  419.76  5004.2  419.26
  5009.6  419.76  5033.6  423.25  5064.4  422.25  5237.1  421.13  5333.6  423.63
  5455.6  436.99  5508.1  433.27  5539.6  438.07  5673.9  444.90  5974.2  472.02
#Mann=7,-1,0
  4367.3    0.16       0  4410.6     0.1       0  4850.9    0.16       0
  4953.4    0.05       0  5003.7   0.033       0  5009.6    0.05       0
  5064.4    0.16       0
Bank Sta=5003.7,5009.6
Exp/Cntr=0.3,0.1

Type RM Length L Ch R = 1,12824,465,465,465
BEGIN DESCRIPTION:
UNT0273 IN DUCK CR 17 0
END DESCRIPTION:
XS GIS Cut Line= 3
      3602276.78     10464384.92      3601248.18     10464426.15
      3600870.56     10464606.28
#Sta/Elev= 30
  4385.4  451.12  4470.1  446.40  4560.2  443.60  4630.3  437.77  4676.7  432.08
  4681.7  432.31  4710.3  427.99  4810.4  420.50  4900.5  419.76  4920.5  418.45
  4926.7  419.10  4950.5  418.28  4980.5  418.98  5000.6  416.98  5020.6  418.81
  5070.6  419.70  5110.7  419.05  5117.7  416.70  5118.2  416.20  5123.6  416.70
  5140.7  419.61  5170.7  422.75  5181.6  424.84  5310.8  440.32  5370.9  443.36
  5512.3  444.56  5580.4  446.72  5642.9  451.12  5798.3  464.71  5833.2  466.07
#Mann=3,-1,0
  4385.4    0.16       0  5117.7    0.07       0  5123.6    0.16       0
Bank Sta=5117.7,5123.6
Exp/Cntr=0.3,0.1

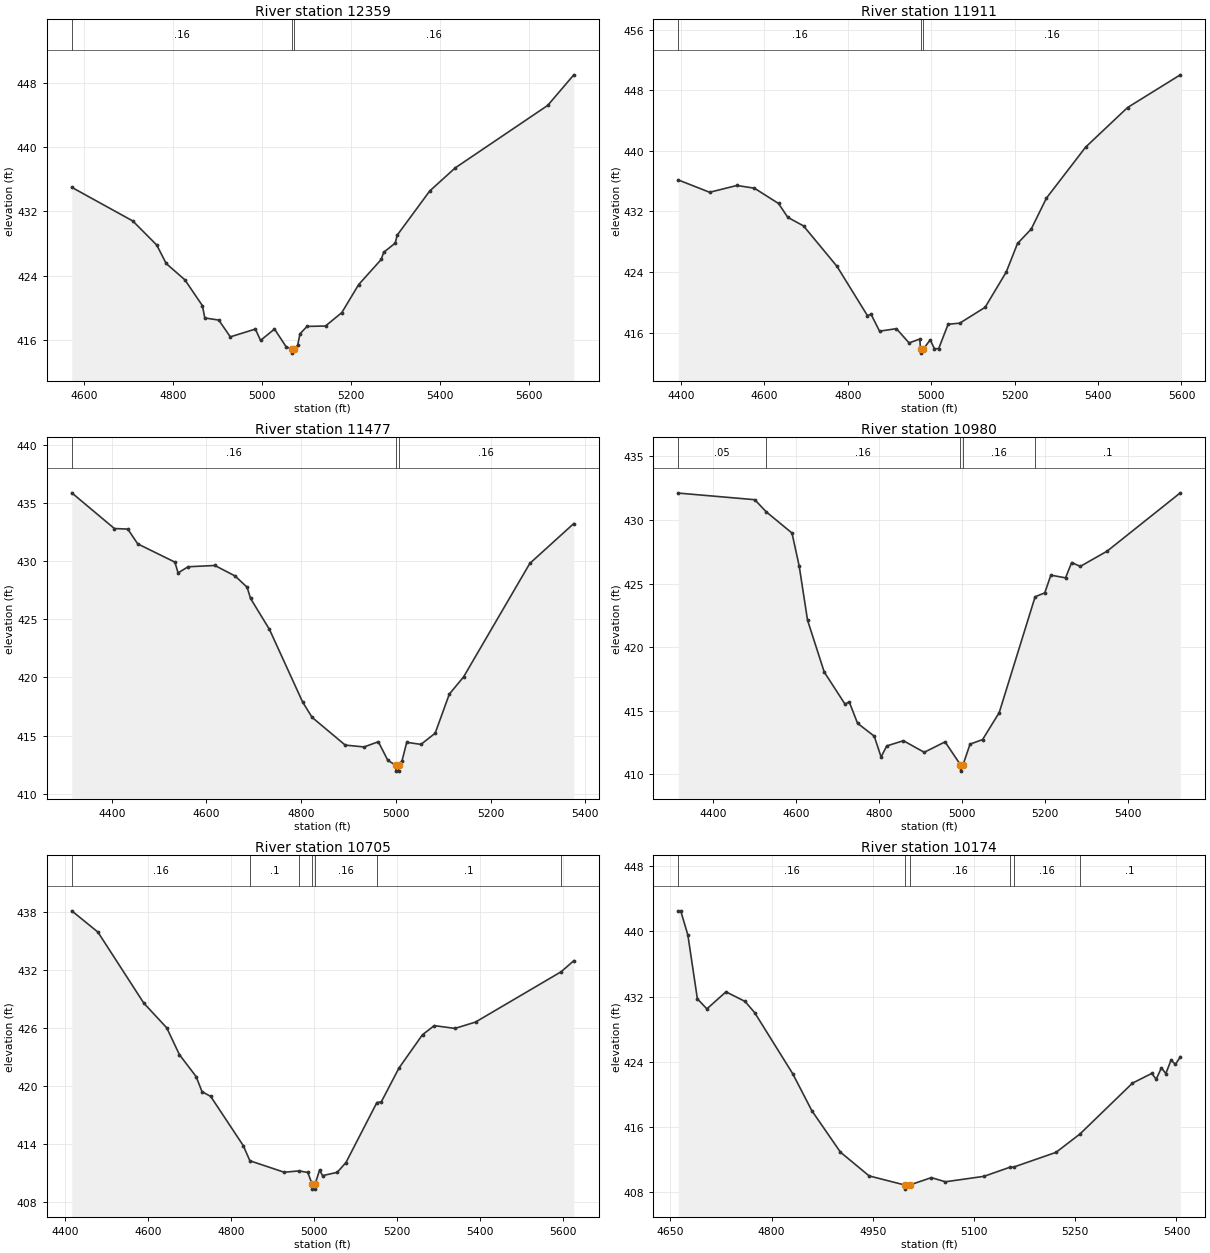
Type RM Length L Ch R = 1,12359,448,448,448
BEGIN DESCRIPTION:
UNT0273 IN DUCK CR 16 0
END DESCRIPTION:
XS GIS Cut Line= 3
      3601923.13     10463851.05      3601228.65     10464087.61
      3600994.28     10464406.60
#Sta/Elev= 30
  4572.4  435.00  4709.7  430.82  4763.6  427.83  4784.8  425.54  4827.0  423.50
  4866.4  420.29  4871.7  418.77  4903.1  418.51  4929.1  416.42  4985.5  417.39
  4997.1  415.98  5028.5  417.39  5054.6  415.20  5067.0  414.90  5067.5  414.40
  5073.0  414.90  5080.6  415.38  5085.9  416.80  5101.7  417.72  5143.3  417.77
  5180.0  419.44  5217.9  422.92  5268.8  426.05  5274.0  426.92  5300.1  428.07
  5304.6  429.06  5377.8  434.55  5435.2  437.42  5643.2  445.18  5701.9  448.98
#Mann=3,-1,0
  4572.4    0.16       0  5067.0    0.07       0  5073.0    0.16       0
Bank Sta=5067,5073
Exp/Cntr=0.3,0.1

Type RM Length L Ch R = 1,11911,434,434,434
BEGIN DESCRIPTION:
UNT0273 IN DUCK CR 15 0
END DESCRIPTION:
XS GIS Cut Line= 4
      3601968.69     10463809.84      3601727.78     10463640.56
      3601213.46     10463560.26      3600885.15     10463767.62
#Sta/Elev= 30
  4393.9  436.16  4469.1  434.53  4534.4  435.43  4576.3  435.07  4634.2  433.05
  4656.4  431.22  4694.1  430.09  4774.3  424.75  4847.2  418.25  4856.0  418.42
  4876.3  416.19  4916.7  416.52  4947.1  414.64  4972.7  415.15  4974.7  413.79
  4975.2  413.29  4980.8  413.79  4997.7  415.04  5007.8  413.88  5018.0  413.88
  5040.6  417.10  5068.6  417.25  5129.3  419.34  5179.9  423.99  5207.0  427.77
  5239.8  429.67  5276.3  433.76  5370.4  440.50  5470.7  445.72  5597.2  450.04
#Mann=3,-1,0
  4393.9    0.16       0  4974.7    0.07       0  4980.8    0.16       0
Bank Sta=4974.7,4980.8
Exp/Cntr=0.3,0.1

Type RM Length L Ch R = 1,11477,497,497,497
BEGIN DESCRIPTION:
UNT0273 IN DUCK CR 14 0
END DESCRIPTION:
XS GIS Cut Line= 3
      3602124.92     10463506.01      3601849.31     10463258.61
      3601159.17     10463258.61
#Sta/Elev= 30
  4315.4  435.88  4405.4  432.81  4433.8  432.76  4454.7  431.49  4533.2  429.92
  4540.0  428.99  4561.1  429.52  4617.7  429.63  4660.3  428.73  4685.8  427.76
  4693.0  426.80  4733.0  424.13  4803.0  417.89  4823.0  416.57  4893.0  414.18
  4933.0  414.02  4963.0  414.47  4983.0  412.87  4999.9  412.44  5000.4  411.94
  5005.6  411.94  5006.1  412.44  5013.0  412.82  5023.0  414.42  5053.0  414.24
  5083.0  415.20  5113.0  418.57  5143.0  420.04  5283.0  429.81  5375.9  433.24
#Mann=3,-1,0
  4315.4    0.16       0  4999.9    0.07       0  5006.1    0.16       0
Bank Sta=4999.9,5006.1
Exp/Cntr=0.3,0.1

Type RM Length L Ch R = 1,10980,275,275,275
BEGIN DESCRIPTION:
UNT0273 IN DUCK CR 13 0
END DESCRIPTION:
XS GIS Cut Line= 4
      3602159.68     10462627.08      3601923.09     10462735.61
      3601332.81     10462789.86      3601045.62     10463001.48
#Sta/Elev= 30
  4316.9  432.11  4501.3  431.59  4528.4  430.65  4590.9  428.97  4608.3  426.37
  4628.4  422.12  4668.6  418.05  4718.8  415.52  4728.8  415.71  4748.9  414.02
  4789.1  413.01  4805.6  411.37  4819.2  412.24  4859.4  412.65  4909.6  411.74
  4959.8  412.56  4996.9  410.76  4997.4  410.26  5003.1  410.76  5020.0  412.38
  5050.2  412.74  5090.3  414.86  5176.8  423.96  5200.1  424.27  5214.7  425.66
  5250.2  425.45  5264.8  426.65  5285.7  426.35  5350.5  427.55  5526.7  432.13
#Mann=5,-1,0
  4316.9    0.05       0  4528.4    0.16       0  4996.9    0.07       0
  5003.1    0.16       0  5176.8     0.1       0
Bank Sta=4996.9,5003.1
Exp/Cntr=0.3,0.1

Type RM Length L Ch R = 1,10705,531,531,531
BEGIN DESCRIPTION:
UNT0273 IN DUCK CR 12 0
END DESCRIPTION:
XS GIS Cut Line= 4
      3601680.03     10462039.02      3601654.00     10462297.24
      3601228.65     10462761.65      3600984.09     10462967.26
#Sta/Elev= 30
  4417.0  438.17  4479.9  435.97  4590.5  428.60  4645.7  426.04  4676.2  423.26
  4716.4  420.99  4730.6  419.43  4751.5  418.93  4829.8  413.84  4845.9  412.26
  4928.5  411.07  4964.2  411.21  4985.2  411.05  4996.0  409.82  4996.5  409.32
  5002.3  409.32  5002.8  409.82  5013.6  411.29  5021.0  410.72  5056.1  411.06
  5077.1  412.07  5151.7  418.30  5162.2  418.36  5204.8  421.87  5261.5  425.33
  5289.9  426.27  5339.8  425.98  5389.2  426.64  5595.5  431.86  5625.8  433.00
#Mann=7,-1,0
  4417.0    0.16       0  4845.9     0.1       0  4964.2    0.16       0
  4996.0    0.07       0  5002.8    0.16       0  5151.7     0.1       0
  5595.5    0.16       0
Bank Sta=4996,5002.8
Exp/Cntr=0.3,0.1

Type RM Length L Ch R = 1,10174,449,449,449
BEGIN DESCRIPTION:
UNT0273 IN DUCK CR 29 0
END DESCRIPTION:
XS GIS Cut Line= 3
      3601392.12     10461941.63      3601142.11     10462191.64
      3600892.10     10462491.65
#Sta/Elev= 30
  4661.6  442.53  4665.2  442.53  4675.8  439.57  4689.9  431.74  4704.0  430.51
  4732.3  432.60  4760.6  431.42  4774.8  430.05  4831.3  422.55  4859.6  418.02
  4902.0  412.94  4944.5  410.03  4997.6  408.91  4998.1  408.41  5004.4  408.91
  5036.7  409.82  5057.5  409.31  5114.8  409.98  5152.6  411.08  5158.9  411.12
  5221.5  412.92  5257.1  415.18  5334.7  421.40  5363.4  422.60  5369.9  421.88
  5377.7  423.28  5384.2  422.58  5392.0  424.23  5398.5  423.70  5405.7  424.64
#Mann=6,-1,0
  4661.6    0.16       0  4997.6    0.07       0  5004.4    0.16       0
  5152.6     0.1       0  5158.9    0.16       0  5257.1     0.1       0
Bank Sta=4997.6,5004.4
Exp/Cntr=0.3,0.1

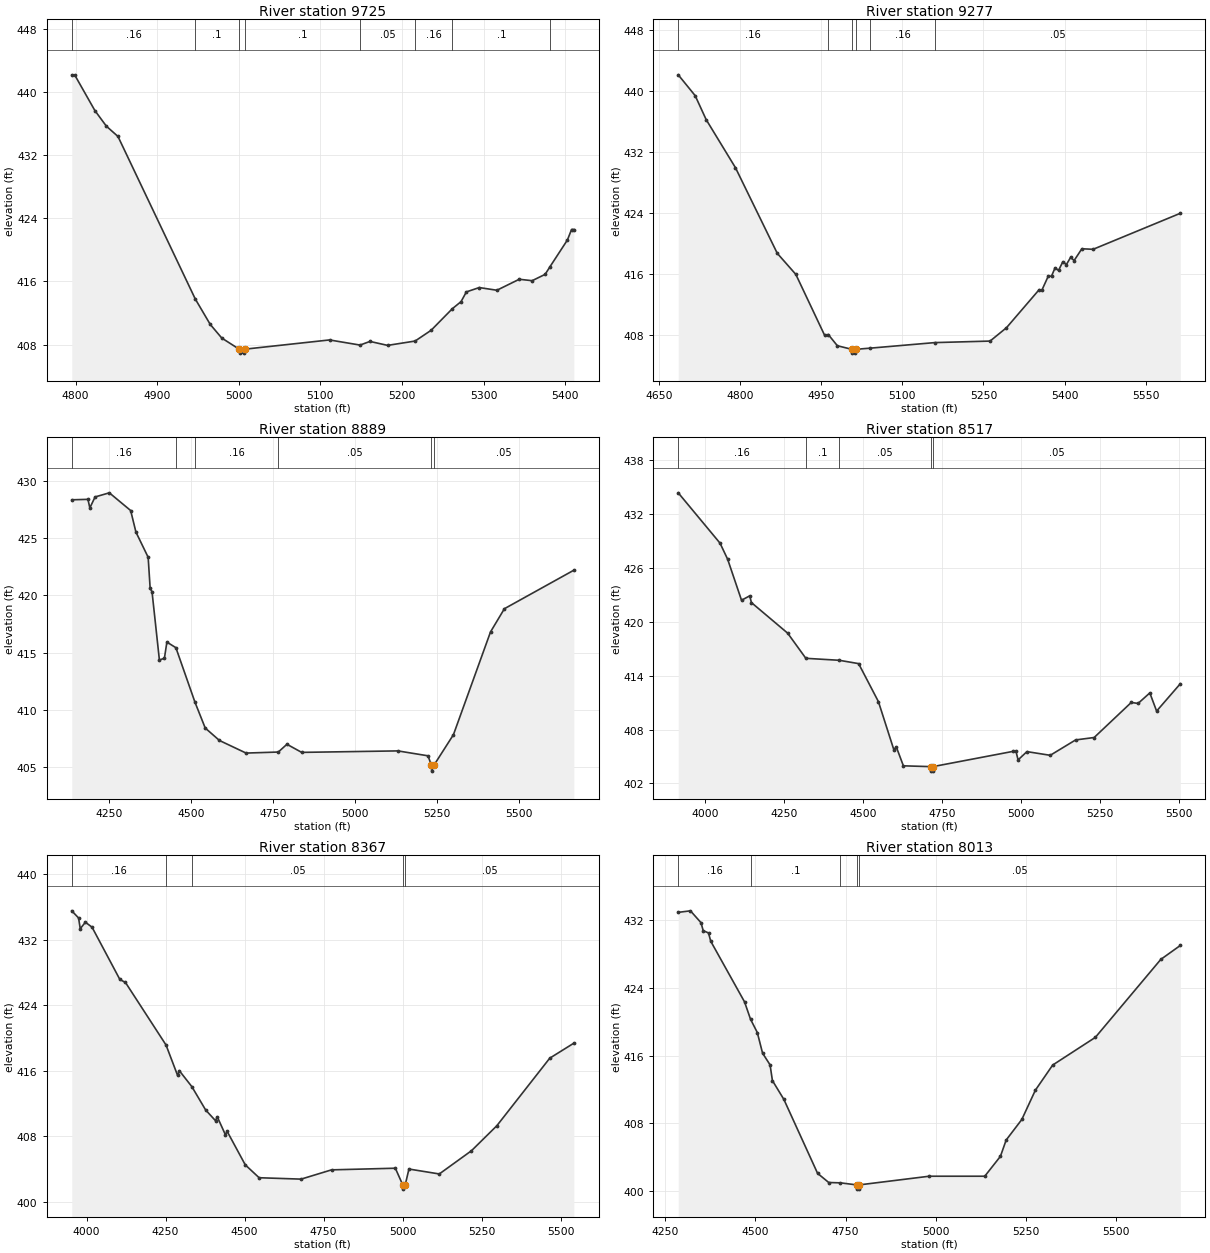
Type RM Length L Ch R = 1,9725,448,448,448
BEGIN DESCRIPTION:
UNT0273 IN DUCK CR 19 0
END DESCRIPTION:
XS GIS Cut Line= 3
      3601142.10     10461641.65      3600992.11     10461791.64
      3600642.13     10461991.63
#Sta/Elev= 30
  4795.4  442.14  4798.9  442.14  4823.7  437.62  4837.8  435.64  4852.0  434.34
  4946.7  413.77  4965.1  410.54  4979.2  408.82  5000.5  407.41  5001.0  406.91
  5006.9  406.91  5007.4  407.41  5111.2  408.58  5148.6  407.93  5160.8  408.39
  5182.4  407.89  5216.1  408.44  5235.7  409.80  5261.8  412.54  5272.4  413.43
  5278.9  414.66  5294.7  415.21  5316.3  414.87  5343.7  416.26  5359.5  416.08
  5375.4  416.88  5381.5  417.87  5402.7  421.23  5407.8  422.56  5410.6  422.56
#Mann=8,-1,0
  4795.4    0.16       0  4946.7     0.1       0  5000.5    0.07       0
  5007.4     0.1       0  5148.6    0.05       0  5216.1    0.16       0
  5261.8     0.1       0  5381.5    0.16       0
Bank Sta=5000.5,5007.4
Exp/Cntr=0.3,0.1

Type RM Length L Ch R = 1,9277,388,388,388
BEGIN DESCRIPTION:
UNT0273 IN DUCK CR 9 0
END DESCRIPTION:
XS GIS Cut Line= 4
      3601183.08     10461392.29      3600968.23     10461359.74
      3600503.82     10461418.34      3600316.09     10461571.54
#Sta/Elev= 30
  4686.0  442.06  4717.3  439.33  4737.6  436.19  4791.8  429.88  4869.0  418.66
  4903.3  415.90  4956.6  407.90  4963.2  408.02  4980.0  406.55  5006.7  406.08
  5007.2  405.58  5013.3  405.58  5013.8  406.08  5040.3  406.23  5160.1  406.96
  5262.2  407.16  5292.5  408.91  5352.9  413.90  5357.9  413.83  5369.7  415.67
  5375.7  415.67  5382.3  416.76  5388.7  416.42  5396.7  417.57  5403.1  417.18
  5411.0  418.13  5417.5  417.72  5431.8  419.26  5452.6  419.19  5613.7  423.91
#Mann=6,-1,0
  4686.0    0.16       0  4963.2     0.1       0  5006.7    0.07       0
  5013.8     0.1       0  5040.3    0.16       0  5160.1    0.05       0
Bank Sta=5006.7,5013.8
Exp/Cntr=0.3,0.1

Type RM Length L Ch R = 1,8889,372,372,372
BEGIN DESCRIPTION:
UNT0273 IN DUCK CR 8 0
END DESCRIPTION:
XS GIS Cut Line= 3
      3601526.12     10460580.31      3600833.72     10460964.54
      3600305.93     10461485.41
#Sta/Elev= 30
  4135.2  428.37  4184.6  428.41  4190.4  427.66  4206.4  428.62  4249.9  428.98
  4315.1  427.43  4331.1  425.55  4368.5  423.34  4374.6  420.62  4380.3  420.33
  4402.8  414.36  4418.1  414.50  4425.7  415.92  4453.2  415.43  4511.6  410.65
  4542.8  408.40  4586.3  407.31  4667.5  406.21  4766.0  406.30  4792.3  406.98
  4837.4  406.27  5131.2  406.40  5223.2  405.97  5233.8  405.13  5234.3  404.63
  5240.9  405.13  5300.9  407.82  5414.1  416.81  5456.5  418.84  5668.6  422.21
#Mann=6,-1,0
  4135.2    0.16       0  4453.2    0.05       0  4511.6    0.16       0
  4766.0    0.05       0  5233.8   0.033       0  5240.9    0.05       0
Bank Sta=5233.8,5240.9
Exp/Cntr=0.3,0.1

Type RM Length L Ch R = 1,8517,150,150,150
BEGIN DESCRIPTION:
UNT0273 IN DUCK CR 6 0
END DESCRIPTION:
XS GIS Cut Line= 4
      3601500.13     10460443.14      3600851.65     10460664.51
      3600630.30     10460773.88      3600062.63     10461104.59
#Sta/Elev= 30
  3915.5  434.33  4047.8  428.73  4071.9  426.94  4115.8  422.38  4141.8  422.87
  4147.1  422.12  4261.8  418.72  4319.4  415.92  4425.3  415.70  4486.4  415.33
  4549.1  411.10  4597.8  405.76  4605.7  406.06  4628.1  403.96  4714.2  403.87
  4714.7  403.37  4721.0  403.37  4721.5  403.87  4975.5  405.57  4984.4  405.57
  4991.2  404.62  5019.1  405.54  5092.9  405.13  5173.2  406.84  5231.9  407.11
  5349.4  411.01  5370.9  410.90  5408.1  412.07  5429.6  410.05  5504.6  413.09
#Mann=5,-1,0
  3915.5    0.16       0  4319.4     0.1       0  4425.3    0.05       0
  4714.2    0.03       0  4721.5    0.05       0
Bank Sta=4714.2,4721.5
Exp/Cntr=0.3,0.1

Type RM Length L Ch R = 1,8367,354,354,354
BEGIN DESCRIPTION:
UNT0273 IN DUCK CR 5 3
END DESCRIPTION:
XS GIS Cut Line= 4
      3601382.89     10460338.12      3600734.46     10460559.47
      3600513.11     10460668.85      3599946.25     10460999.08
#Sta/Elev= 30
  3953.2  435.50  3974.7  434.63  3980.0  433.32  3996.3  434.11  4017.4  433.50
  4105.3  427.13  4123.1  426.76  4251.3  419.14  4288.0  415.42  4293.3  416.01
  4333.0  414.06  4376.7  411.21  4408.0  409.90  4413.3  410.39  4439.3  408.18
  4444.6  408.61  4502.0  404.52  4545.8  402.95  4678.6  402.78  4774.8  403.91
  4976.7  404.11  5000.3  402.06  5000.8  401.56  5007.8  402.06  5019.7  404.01
  5115.7  403.41  5217.4  406.24  5297.7  409.29  5465.1  417.53  5541.3  419.36
#Mann=5,-1,0
  3953.2    0.16       0  4251.3     0.1       0  4333.0    0.05       0
  5000.3    0.03       0  5007.8    0.05       0
Bank Sta=5000.3,5007.8
Exp/Cntr=0.3,0.1

Type RM Length L Ch R = 1,8013,786,786,786
BEGIN DESCRIPTION:
UNT0273 IN DUCK CR 5 2
END DESCRIPTION:
XS GIS Cut Line= 4
      3600757.73     10460009.91      3600599.31     10460220.42
      3599952.61     10460582.83      3599568.45     10460630.58
#Sta/Elev= 30
  4286.1  432.86  4320.0  433.04  4349.1  431.65  4355.4  430.70  4370.0  430.44
  4376.2  429.46  4469.9  422.32  4486.5  420.28  4505.3  418.71  4519.9  416.28
  4540.7  414.90  4547.2  413.05  4578.9  410.84  4672.4  402.13  4703.3  401.05
  4735.7  401.01  4780.5  400.77  4781.0  400.27  4787.6  400.27  4788.1  400.77
  4982.0  401.79  5135.9  401.79  5179.3  404.13  5195.2  406.05  5238.6  408.47
  5276.2  411.92  5324.2  414.88  5442.5  418.14  5623.9  427.32  5678.0  428.96
#Mann=5,-1,0
  4286.1    0.16       0  4486.5     0.1       0  4735.7    0.05       0
  4780.5    0.03       0  4788.1    0.05       0
Bank Sta=4780.5,4788.1
Exp/Cntr=0.3,0.1

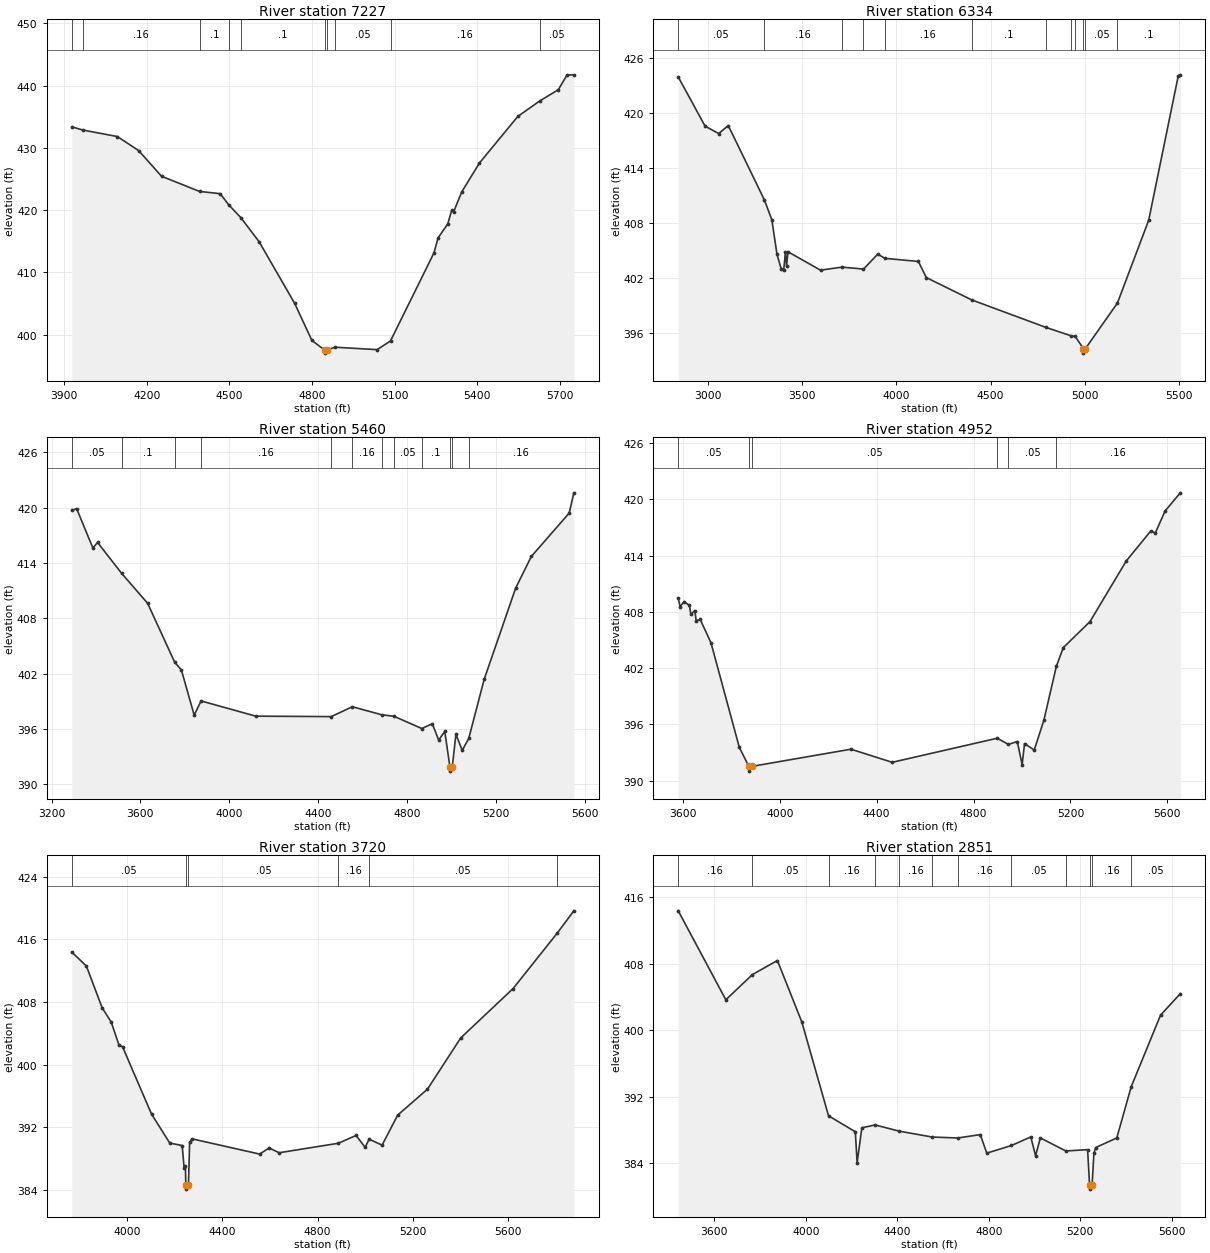
Type RM Length L Ch R = 1,7227,893,893,893
BEGIN DESCRIPTION:
UNT0273 IN DUCK CR 5 0
END DESCRIPTION:
XS GIS Cut Line= 4
      3600853.08     10459634.64      3600323.61     10459504.45
      3599629.17     10460025.28      3599238.54     10460151.15
#Sta/Elev= 30
  3927.4  433.38  3968.3  432.86  4093.2  431.82  4170.4  429.56  4253.4  425.44
  4391.5  423.00  4466.2  422.64  4498.4  420.81  4541.4  418.79  4607.7  414.93
  4736.9  405.02  4799.5  399.06  4845.7  397.51  4846.2  397.01  4853.4  397.51
  4884.1  397.96  5036.9  397.57  5085.2  398.98  5243.1  413.13  5257.7  415.51
  5293.1  417.78  5307.7  419.99  5314.0  419.67  5344.0  422.93  5408.1  427.56
  5547.7  435.06  5626.9  437.53  5694.8  439.35  5726.3  441.71  5751.1  441.74
#Mann=10,-1,0
  3927.4    0.05       0  3968.3    0.16       0  4391.5     0.1       0
  4498.4    0.16       0  4541.4     0.1       0  4845.7    0.03       0
  4853.4     0.1       0  4884.1    0.05       0  5085.2    0.16       0
  5626.9    0.05       0
Bank Sta=4845.7,4853.4
Exp/Cntr=0.3,0.1

Type RM Length L Ch R = 1,6334,874,874,874
BEGIN DESCRIPTION:
UNT0273 IN DUCK CR 21 0
END DESCRIPTION:
XS GIS Cut Line= 3
      3600634.99     10457416.21      3599637.59     10458916.42
      3598957.53     10459452.41
#Sta/Elev= 30
  2840.6  423.91  2983.2  418.54  3055.4  417.73  3106.5  418.60  3297.6  410.51
  3338.0  408.31  3365.0  404.56  3387.5  402.96  3401.1  402.87  3410.1  404.80
  3416.1  403.27  3423.5  404.82  3596.5  402.81  3709.9  403.14  3824.8  402.93
  3900.2  404.55  3939.6  404.10  4116.6  403.76  4158.7  402.00  4399.1  399.57
  4792.6  396.57  4926.6  395.65  4949.4  395.58  4993.1  394.25  4993.6  393.75
  5004.1  394.25  5173.9  399.22  5340.1  408.27  5497.2  424.04  5508.0  424.14
#Mann=12,-1,0
  2840.6    0.05       0  3297.6    0.16       0  3709.9    0.05       0
  3824.8     0.1       0  3939.6    0.16       0  4399.1     0.1       0
  4792.6    0.16       0  4926.6     0.1       0  4949.4    0.05       0
  4993.1    0.03       0  5004.1    0.05       0  5173.9     0.1       0
Bank Sta=4993.1,5004.1
Exp/Cntr=0.3,0.1

Type RM Length L Ch R = 1,5460,508,508,508
BEGIN DESCRIPTION:
UNT0273 IN DUCK CR 1 6
END DESCRIPTION:
XS GIS Cut Line= 3
      3599878.04     10457016.92      3599073.57     10458302.05
      3598517.54     10458797.05
#Sta/Elev= 30
  3291.2  419.70  3313.1  419.90  3386.2  415.63  3407.4  416.23  3515.8  412.88
  3632.6  409.64  3754.9  403.23  3784.7  402.41  3842.4  397.51  3873.4  399.05
  4119.5  397.40  4459.1  397.35  4554.6  398.42  4686.7  397.55  4741.5  397.39
  4867.1  396.06  4914.6  396.58  4943.1  394.81  4970.7  395.74  4993.6  391.94
  4994.1  391.44  5004.6  391.94  5020.8  395.43  5049.3  393.70  5078.6  394.98
  5147.9  401.38  5290.1  411.30  5360.3  414.71  5530.9  419.42  5551.8  421.61
#Mann=12,-1,0
  3291.2    0.05       0  3515.8     0.1       0  3754.9    0.05       0
  3873.4    0.16       0  4459.1    0.05       0  4554.6    0.16       0
  4686.7     0.1       0  4741.5    0.05       0  4867.1     0.1       0
  4993.6    0.07       0  5004.6     0.1       0  5078.6    0.16       0
Bank Sta=4993.6,5004.6
Exp/Cntr=0.3,0.1

Type RM Length L Ch R = 1,4952,1232,1232,1232
BEGIN DESCRIPTION:
UNT0273 IN DUCK CR 10 0
END DESCRIPTION:
XS GIS Cut Line= 3
      3597914.78     10456877.53      3598516.32     10458046.76
      3598534.55     10458804.55
#Sta/Elev= 30
  3580.7  409.47  3588.4  408.57  3604.9  409.11  3627.1  408.69  3632.7  407.75
  3649.3  408.14  3654.9  407.06  3671.4  407.20  3715.8  404.72  3832.7  393.57
  3872.2  391.52  3872.7  391.02  3883.2  391.52  4293.8  393.36  4464.1  391.96
  4897.7  394.53  4944.2  393.87  4980.5  394.18  5000.5  391.72  5010.5  393.96
  5050.5  393.27  5090.5  396.47  5141.8  402.20  5170.6  404.20  5280.6  406.97
  5430.6  413.45  5530.7  416.61  5550.7  416.45  5590.7  418.77  5653.6  420.71
#Mann=6,-1,0
  3580.7    0.05       0  3872.2    0.03       0  3883.2    0.05       0
  4897.7    0.16       0  4944.2    0.05       0  5141.8    0.16       0
Bank Sta=3872.2,3883.2
Exp/Cntr=0.3,0.1

Type RM Length L Ch R = 1,3720,869,869,869
BEGIN DESCRIPTION:
UNT0273 IN DUCK CR 1 3
END DESCRIPTION:
XS GIS Cut Line= 3
      3597854.87     10456937.36      3597443.40     10458296.76
      3597414.76     10458986.76
#Sta/Elev= 30
  3766.8  414.38  3828.4  412.59  3894.3  407.27  3932.5  405.44  3965.4  402.48
  3980.2  402.28  4102.3  393.66  4178.8  389.97  4231.0  389.65  4239.3  386.77
  4244.5  387.07  4246.3  384.58  4246.8  384.08  4257.4  384.58  4262.3  390.04
  4272.2  390.51  4556.6  388.56  4596.7  389.34  4638.5  388.73  4887.2  389.94
  4962.2  390.94  5000.3  389.41  5017.0  390.47  5071.4  389.70  5137.3  393.55
  5262.1  396.85  5402.2  403.41  5622.4  409.72  5807.0  416.77  5877.7  419.65
#Mann=6,-1,0
  3766.8    0.05       0  4246.3    0.07       0  4257.4    0.05       0
  4887.2    0.16       0  5017.0    0.05       0  5807.0     0.1       0
Bank Sta=4246.3,4257.4
Exp/Cntr=0.3,0.1

Type RM Length L Ch R = 1,2851,642,642,642
BEGIN DESCRIPTION:
UNT0273 IN DUCK CR 1 5
END DESCRIPTION:
XS GIS Cut Line= 3
      3597763.74     10456546.73      3597550.18     10456898.33
      3596399.13     10458260.31
#Sta/Elev= 30
  3442.4  414.37  3650.4  403.67  3766.9  406.71  3875.9  408.39  3982.5  401.01
  4099.4  389.71  4216.5  387.79  4224.3  384.08  4245.1  388.27  4303.2  388.61
  4407.3  387.87  4551.9  387.16  4663.8  387.04  4762.6  387.45  4791.2  385.22
  4899.1  386.14  4983.5  387.17  5004.4  384.90  5025.2  387.05  5136.7  385.48
  5231.8  385.64  5240.4  381.39  5240.9  380.89  5251.5  381.39  5259.2  385.18
  5267.0  385.89  5359.3  387.05  5422.5  393.22  5550.4  401.81  5637.0  404.41
#Mann=12,-1,0
  3442.4    0.16       0  3766.9    0.05       0  4099.4    0.16       0
  4303.2    0.05       0  4407.3    0.16       0  4551.9    0.05       0
  4663.8    0.16       0  4899.1    0.05       0  5136.7    0.16       0
  5240.4    0.03       0  5251.5    0.16       0  5422.5    0.05       0
Bank Sta=5240.4,5251.5
Exp/Cntr=0.3,0.1