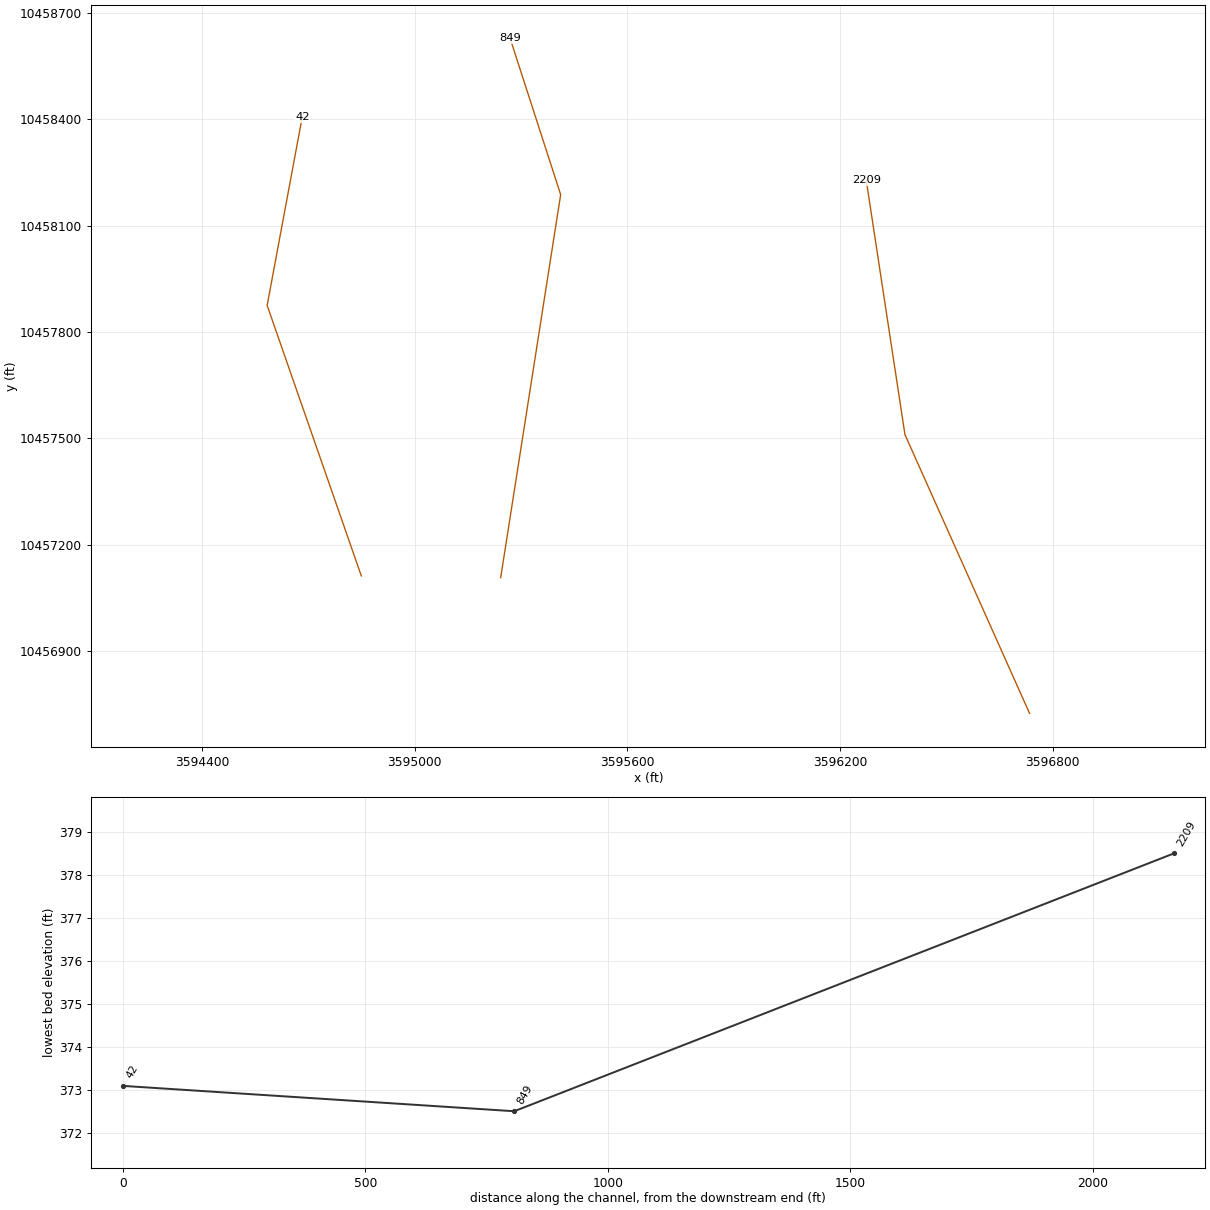
HEC-RAS study UNT0273 IN DUCK CR.prj: UNT0273 IN DUCK CR Base Level Engineering

--- UNT0273 IN DUCK CR.g01 (geometry) --- (continued)

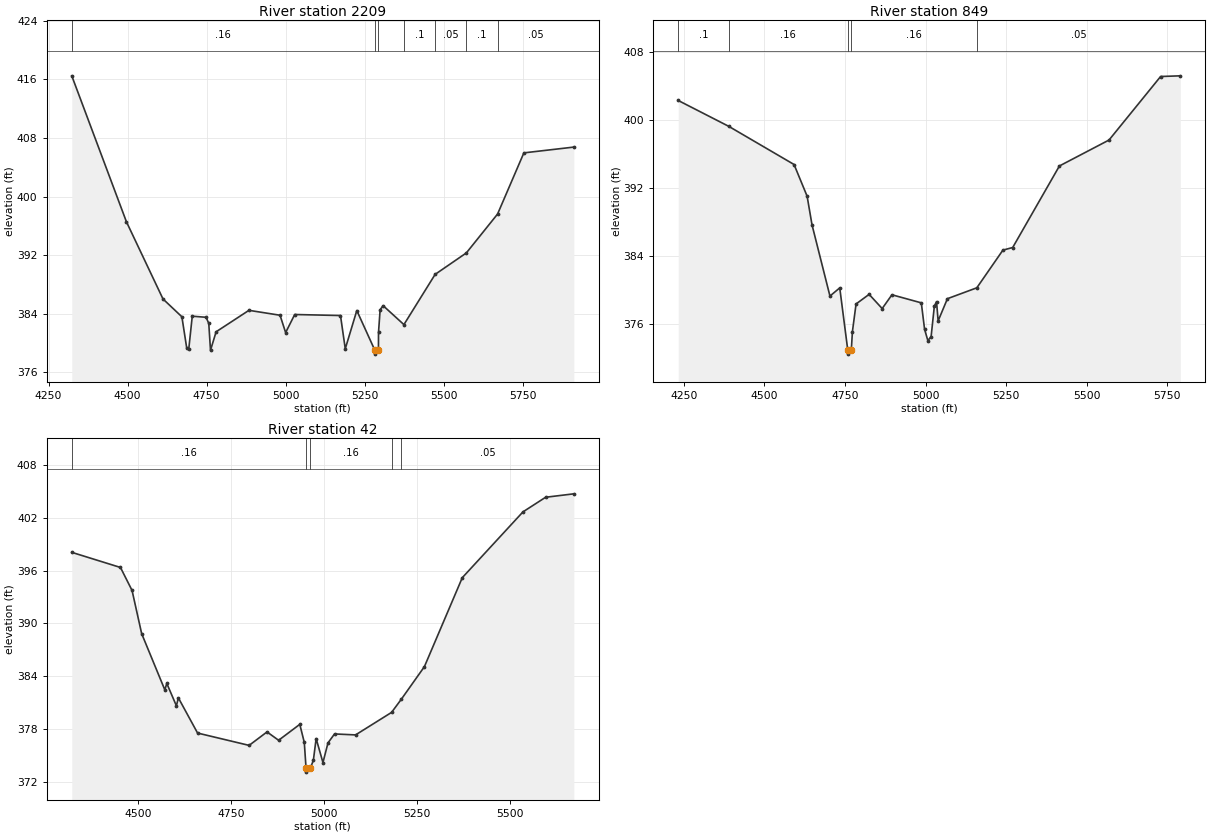
Type RM Length L Ch R = 1,2209,1360,1360,1360
BEGIN DESCRIPTION:
UNT0273 IN DUCK CR 11 0
END DESCRIPTION:
XS GIS Cut Line= 3
      3596735.06     10456723.88      3596383.51     10457510.31
      3596274.32     10458227.83
#Sta/Elev= 30
  4323.5  416.50  4496.3  396.57  4611.9  386.03  4671.6  383.60  4687.0  379.30
  4693.5  379.25  4704.4  383.68  4748.2  383.53  4756.6  382.69  4762.1  379.03
  4779.8  381.55  4883.6  384.48  4981.9  383.81  4999.6  381.44  5028.3  383.91
  5173.0  383.77  5188.1  379.23  5224.6  384.45  5281.9  379.00  5282.4  378.50
  5293.0  379.00  5293.2  381.46  5298.3  384.56  5307.7  385.12  5373.5  382.53
  5472.2  389.39  5570.9  392.32  5669.6  397.63  5752.7  405.98  5910.7  406.77
#Mann=7,-1,0
  4323.5    0.16       0  5281.9    0.07       0  5293.0    0.16       0
  5373.5     0.1       0  5472.2    0.05       0  5570.9     0.1       0
  5669.6    0.05       0
Bank Sta=5281.9,5293
Exp/Cntr=0.3,0.1

Type RM Length L Ch R = 1,849,807,807,807
BEGIN DESCRIPTION:
UNT0273 IN DUCK CR 1 4
END DESCRIPTION:
XS GIS Cut Line= 3
      3595242.89     10457106.68      3595412.15     10458187.39
      3595269.48     10458628.40
#Sta/Elev= 30
  4232.6  402.33  4389.3  399.29  4591.9  394.80  4632.4  391.07  4647.6  387.70
  4703.2  379.33  4733.6  380.29  4758.4  373.00  4758.9  372.50  4769.5  373.00
  4772.9  375.15  4784.2  378.40  4824.7  379.53  4865.2  377.86  4895.5  379.48
  4986.6  378.53  4996.8  375.41  5006.9  374.09  5017.0  374.56  5027.1  378.16
  5033.8  378.67  5038.8  376.41  5067.6  379.02  5158.8  380.30  5239.7  384.73
  5270.1  385.04  5415.0  394.63  5568.9  397.68  5728.9  405.15  5790.0  405.23
#Mann=5,-1,0
  4232.6     0.1       0  4389.3    0.16       0  4758.4    0.07       0
  4769.5    0.16       0  5158.8    0.05       0
Bank Sta=4758.4,4769.5
Exp/Cntr=0.3,0.1

Type RM Length L Ch R = 1,42,0,0,0
BEGIN DESCRIPTION:
UNT0273 IN DUCK CR 1 0
END DESCRIPTION:
XS GIS Cut Line= 3
      3594849.67     10457111.83      3594584.03     10457874.89
      3594682.99     10458406.17
#Sta/Elev= 30
  4322.2  398.07  4453.0  396.35  4484.1  393.74  4509.9  388.83  4572.1  382.44
  4577.4  383.17  4603.2  380.63  4608.5  381.53  4660.1  377.53  4798.5  376.13
  4846.6  377.66  4877.7  376.71  4934.6  378.52  4946.7  376.46  4951.3  373.59
  4951.8  373.09  4963.3  373.59  4971.0  374.42  4978.5  376.90  4996.8  374.18
  5010.3  376.41  5027.9  377.43  5084.4  377.32  5181.1  379.88  5207.7  381.40
  5269.3  385.08  5371.0  395.19  5534.0  402.67  5594.8  404.33  5670.6  404.72
#Mann=5,-1,0
  4322.2    0.16       0  4951.3    0.07       0  4963.3    0.16       0
  5181.1     0.1       0  5207.7    0.05       0
Bank Sta=4951.3,4963.3
Exp/Cntr=0.3,0.1

Chan Stop Cuts=-1