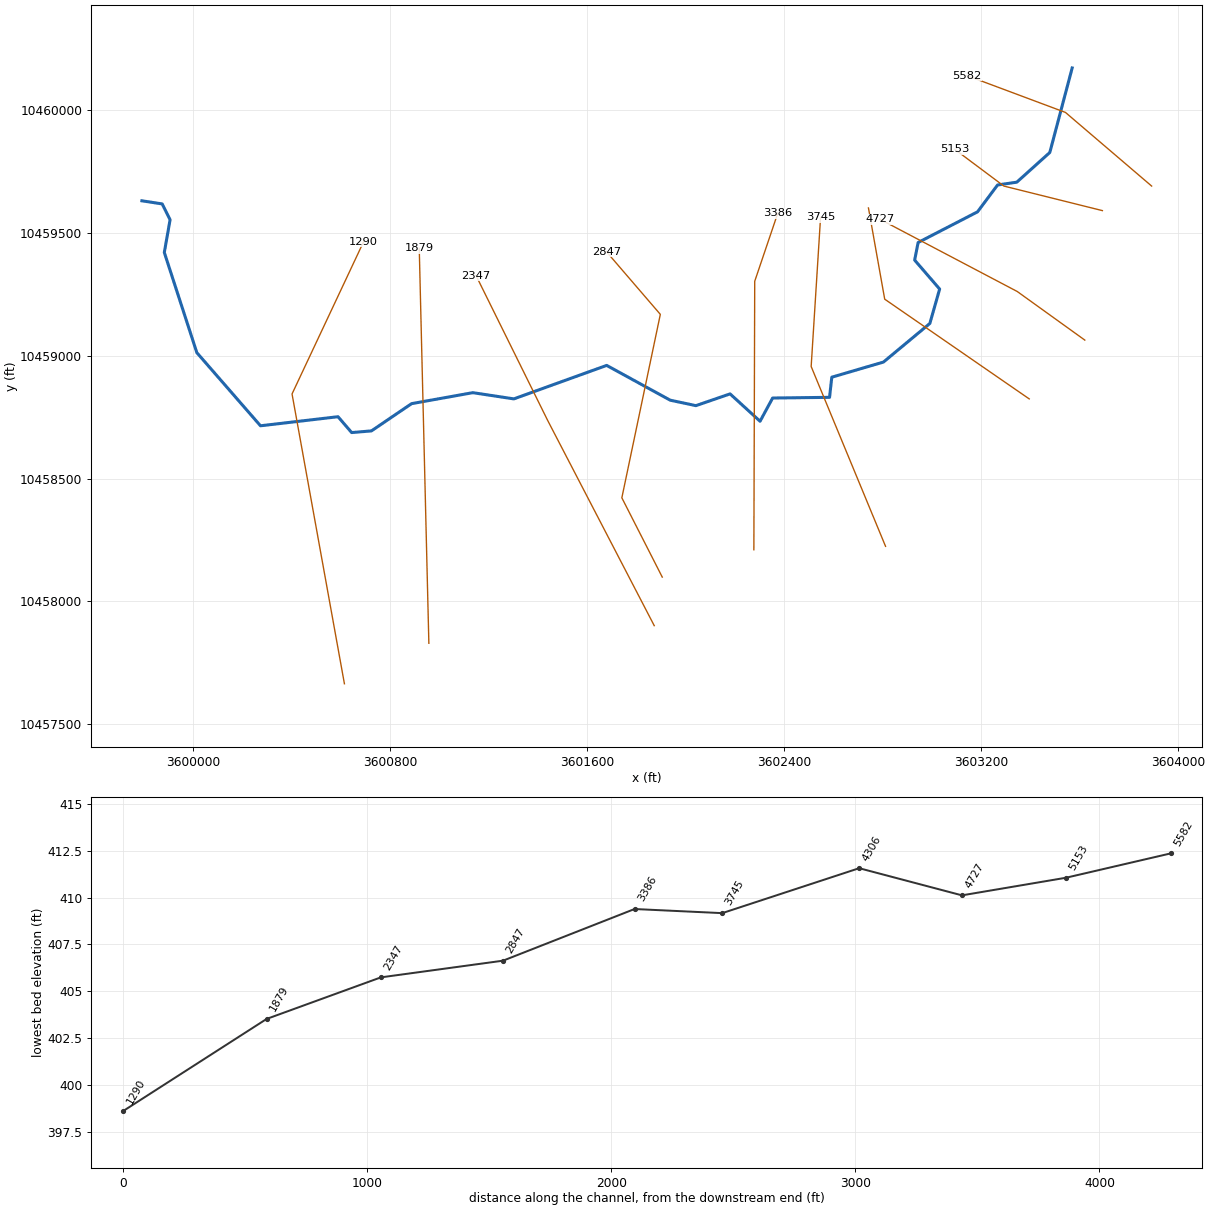
--- UNT0274 IN DUCK CR.prj (project) ---

Proj Title=UNT0274 IN DUCK CR Base Level Engineering
Current Plan=p01
Default Exp/Contr=0.3,0.1
English Units
Geom File=g01
Flow File=f01
Plan File=p01
Y Axis Title=Elevation
X Axis Title(PF)=Main Channel Distance
X Axis Title(XS)=Station
BEGIN DESCRIPTION:
UNT0274 IN DUCK CR
END DESCRIPTION:
DSS File=dss
DSS Export Rating Curves= 0
DSS Export Rating Curve Sorted= 0
DSS Export Volume Flow Curves= 0
DXF OffsetX= 0
DXF OffsetY= 0
DXF ScaleX= 1
DXF ScaleY= 10

--- UNT0274 IN DUCK CR.p01 (plan) ---

Plan Title=Multiple Run
Program Version=4.10
Geom File=g01
Flow File=f01
Subcritical Flow
K Sum by GR= 0
Std Step Tol= 0.01
Critical Tol= 0.01
Num of Std Step Trials= 20
Max Error Tol= 0.3
Flow Tol Ratio= 0.001
Split Flow NTrial= 30
Split Flow Tol= 0.02
Split Flow Ratio= 0.02
Log Output Level= 0
Friction Slope Method= 1
Unsteady Friction Slope Method= 2
Unsteady Bridges Friction Slope Method= 1
Parabolic Critical Depth
Global Vel Dist= 1 , 1 , 1
Global Log Level= 0
CheckData=True
Encroach Param=-1 ,0,0, 0
BEGIN DESCRIPTION:
Multiple Run
END DESCRIPTION:
Computation Interval=1HOUR
Output Interval=1HOUR
Run HTab= 0
Run UNet= 0
Run PostProcess= 0
Run WQNet= 0
UNET Theta= 1
UNET Theta Warmup= 1
UNET ZTol= 0.02
UNET ZSATol= 0.05
UNET MxIter= 20
UNET MaxInSteps= 0
UNET DtIC= 0
UNET DtMin= 0
UNET MaxCRTS= 20
UNET WFStab= 2
UNET SFStab= 1
UNET WFX= 1
UNET SFX= 1
UNET DSS MLevel= 4
UNET DZMax Abort= 100
UNET Convert EG Bridges= 0
UNET Use Existing IB Tables=-1
UNET Froude Reduction=False
UNET Froude Limit= 1
UNET Froude Power= 10
UNET Time Slicing=0,0, 5
UNET Junction Losses=0
Instantaneous Interval=1HOUR
DSS File=dss
Write IC File= 0
Write IC File at Sim End=0
Echo Input=False
Echo Parameters=False
Echo Output=False
Write Detailed= 0
WQ AD Non Conservative
WQ ULTIMATE=-1
WQ Max Comp Step=1HOUR
WQ Output Interval=15MIN
WQ Output Selected Increments= 0
WQ Output face flow=0
WQ Output face velocity=0
WQ Output face area=0
WQ Output face dispersion=0
WQ Output cell volume=0
WQ Output cell surface area=0
WQ Output cell continuity=0
WQ Output cumulative cell continuity=0
WQ Output face conc=0
WQ Output face dconc_dx=0
WQ Output face courant=0
WQ Output face peclet=0
WQ Output face adv mass=0
WQ Output face disp mass=0
WQ Output cell mass=0
WQ Output cell source sink temp=0
WQ Output cell source sink nsm=0
WQ Output MaxMinRange=-1
WQ Daily Max Min Mean=-1
WQ Daily Range=0
WQ Daily Time=0
WQ Create Restart=0
WQ Fixed Restart=0
WQ System Summary=0
WQ Use Fixed Temperature=0
Sorting and Armoring Iterations= 10
XS Update Threshold= 0.02
Hydraulics Update Threshold= 0.02
Energy Slope Method= 1
Volume Change Method= 0
XS Weighting Method= 0
Number of US Weighted Cross Sections= 1
Number of DS Weighted Cross Sections= 1
Upstream XS Weight=0.25
Main XS Weight=0.5
Downstream XS Weight=0.25
Number of DS XS's Weighted with US Boundary= 1
Upstream Boundary Weight= 1
Weight of XSs Associated with US Boundary= 0
Number of US XS's Weighted with DS Boundary= 1
Downstream Boundary Weight= 0.5
Weight of XSs Associated with DS Boundary= 0.5
Sediment Output Level= 4
Mass or Volume Output= 0
Output Increment Type= 1
Profile and TS Output Increment= 10
XS Output Flag= 0
XS Output Increment= 10
Disregard all LS=0
Disregard all Conn=0
Disregard all Breaches=0
Disregard all Pumps=0

--- UNT0274 IN DUCK CR.f01 (steady flow) ---

Flow Title=Multiple
Program Version=4.10
Number of Profiles= 7
Profile Names=10-year,25-year,50-year,1pct_min,100-year,1pct_plu,500-year
River Rch & RM=UNT0274 IN DUCK,Reach-1         ,5582
    1057    1454    1781    1590    2151    2909    3129
Boundary for River Rch & Prof#=UNT0274 IN DUCK,Reach-1         , 1
Up Type= 0
Dn Type= 3
Dn Slope=0.008
Boundary for River Rch & Prof#=UNT0274 IN DUCK,Reach-1         , 2
Up Type= 0
Dn Type= 3
Dn Slope=0.008
Boundary for River Rch & Prof#=UNT0274 IN DUCK,Reach-1         , 3
Up Type= 0
Dn Type= 3
Dn Slope=0.008
Boundary for River Rch & Prof#=UNT0274 IN DUCK,Reach-1         , 4
Up Type= 0
Dn Type= 3
Dn Slope=0.008
Boundary for River Rch & Prof#=UNT0274 IN DUCK,Reach-1         , 5
Up Type= 0
Dn Type= 3
Dn Slope=0.008
Boundary for River Rch & Prof#=UNT0274 IN DUCK,Reach-1         , 6
Up Type= 0
Dn Type= 3
Dn Slope=0.008
Boundary for River Rch & Prof#=UNT0274 IN DUCK,Reach-1         , 7
Up Type= 0
Dn Type= 3
Dn Slope=0.008
DSS Import GetInterval= 0
DSS Import GetPeak= 0
DSS Import FillOption= 0

--- UNT0274 IN DUCK CR.g01 (geometry) ---

Geom Title=Existing Conditions
Program Version=4.10

River Reach=UNT0274 IN DUCK ,Reach-1
Reach XY= 30
      3603569.48     10460172.79      3603478.57     10459828.31
      3603344.45     10459707.42      3603266.54     10459696.05
      3603185.12     10459586.61      3602943.89     10459461.68
      3602929.83     10459390.06      3603031.28     10459272.07
      3602991.48     10459131.82      3602803.26      10458974.7
      3602593.37     10458912.98      3602584.25     10458830.95
      3602353.15     10458828.12      3602302.12     10458733.48
      3602180.35     10458845.01      3602041.54     10458797.09
      3601937.08     10458819.43      3601679.33     10458961.03
      3601302.42     10458824.66      3601135.87     10458849.98
      3600887.14     10458805.22      3600724.19     10458694.23
      3600643.92     10458687.42      3600588.35     10458752.02
      3600273.62     10458715.03      3600015.14       10459013.
      3599883.07      10459421.1      3599906.55     10459554.48
      3599874.51     10459618.89      3599792.11     10459631.64

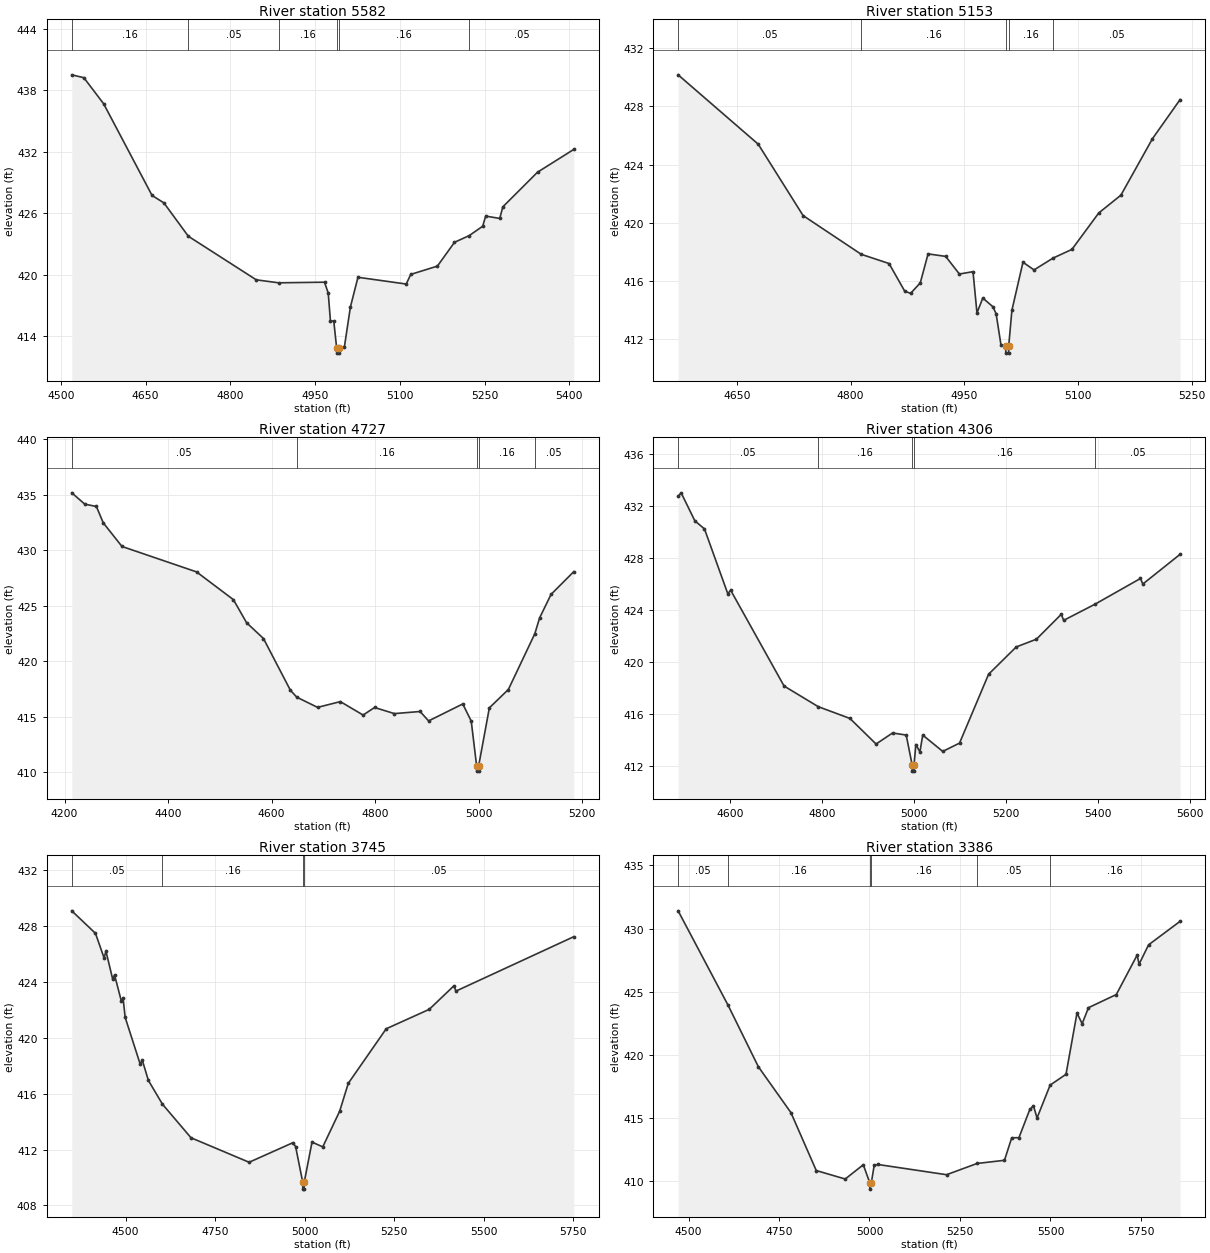
Type RM Length L Ch R = 1 ,5582    ,429,429,429
BEGIN DESCRIPTION:
UNT0274 IN DUCK CR 29 0
END DESCRIPTION:
XS GIS Cut Line= 3
       3603892.1     10459691.65      3603542.11     10459991.64
      3603142.07     10460141.65
#Sta/Elev= 30
  4519.5  439.51  4540.9  439.23    4576  436.68  4661.6  427.74  4682.5  427.02
  4725.8  423.76    4846  419.51  4885.5  419.22  4966.7  419.28  4973.3  418.22
  4977.2  415.49  4983.1  415.49  4988.2  412.86  4988.5  412.36  4992.1  412.36
  4992.3  412.86  5001.8  412.93  5012.5  416.85  5025.9  419.76  5111.3   419.1
  5119.3  420.04  5166.5  420.85  5196.7  423.17  5222.9  423.83  5246.6  424.74
  5251.9  425.73  5276.8   425.5  5282.2  426.63  5343.6  430.01  5407.7  432.23
#Mann= 6 ,-1 , 0
  4519.5     .16       0  4725.8     .05       0  4885.5     .16       0
  4988.2     .07       0  4992.3     .16       0  5222.9     .05       0
Bank Sta=4988.2,4992.3
XS Rating Curve= 0 ,0
Exp/Cntr=0.3,0.1

Type RM Length L Ch R = 1 ,5153    ,426,426,426
BEGIN DESCRIPTION:
UNT0274 IN DUCK CR 91 0
END DESCRIPTION:
XS GIS Cut Line= 3
       3603692.1     10459591.64      3603292.11     10459691.64
      3603092.11     10459841.64
#Sta/Elev= 30
  4572.4  430.16  4678.1   425.4  4737.3   420.5  4814.1  417.84  4850.7  417.21
  4871.3  415.32  4879.1  415.16  4891.9  415.88  4902.2  417.87  4925.4   417.7
  4943.5  416.49  4961.5  416.65  4966.7  413.82  4974.4  414.84  4987.8  414.24
    4992  413.76  4998.3  411.65  5004.5  411.56  5004.8  411.06  5008.4  411.06
  5008.6  411.56  5012.8     414  5027.4   417.3    5042  416.77    5067  417.58
    5092  418.18  5127.4  420.68  5156.6   421.9  5198.3  425.78  5234.7  428.46
#Mann= 5 ,-1 , 0
  4572.4     .05       0  4814.1     .16       0  5004.5     .07       0
  5008.6     .16       0    5067     .05       0
Bank Sta=5004.5,5008.6
XS Rating Curve= 0 ,0
Exp/Cntr=0.3,0.1

Type RM Length L Ch R = 1 ,4727    ,421,421,421
BEGIN DESCRIPTION:
UNT0274 IN DUCK CR 9 0
END DESCRIPTION:
XS GIS Cut Line= 3
      3603620.73     10459064.16      3603346.41     10459262.09
      3602787.94     10459556.93
#Sta/Elev= 30
  4213.8  435.18    4239  434.16  4261.4  433.95  4274.6  432.48  4310.8  430.35
  4454.9  428.06  4526.1  425.56  4551.6  423.48  4584.2  422.06  4636.1  417.41
  4648.5  416.78  4688.7  415.86  4732.7  416.38  4776.7  415.17  4798.8  415.85
  4837.1   415.3  4886.8  415.49  4903.2  414.64  4969.2  416.17  4985.6  414.62
  4995.9  410.62  4996.2  410.12  4999.8  410.12    5000  410.62  5020.6  415.82
  5057.3  417.47  5108.4  422.49  5117.7  423.92  5139.7  426.03  5183.6  428.08
#Mann= 5 ,-1 , 0
  4213.8     .05       0  4648.5     .16       0  4995.9     .07       0
    5000     .16       0  5108.4     .05       0
Bank Sta=4995.9,5000
XS Rating Curve= 0 ,0
Exp/Cntr=0.3,0.1

Type RM Length L Ch R = 1 ,4306    ,561,561,561
BEGIN DESCRIPTION:
UNT0274 IN DUCK CR 8 0
END DESCRIPTION:
XS GIS Cut Line= 3
      3603395.03     10458824.58      3602808.22     10459230.84
      3602742.24      10459602.4
#Sta/Elev= 30
  4487.3  432.75  4493.9  433.02  4523.7  430.86  4544.6  430.24  4595.3  425.24
  4601.4  425.52  4717.6  418.13  4791.8  416.54  4860.8  415.63  4917.6  413.66
  4953.4  414.51  4983.1  414.35  4995.9  412.07  4996.2  411.57  4999.8  411.57
  5000.1  412.07  5004.1  413.62  5012.9  413.05    5019  414.35  5062.5  413.09
    5099  413.73  5162.2  419.04  5222.2  421.14  5266.2  421.74  5320.2  423.66
  5325.3  423.19  5393.7  424.44  5492.3  426.42  5497.4  425.99  5578.4  428.28
#Mann= 5 ,-1 , 0
  4487.3     .05       0  4791.8     .16       0  4995.9     .07       0
  5000.1     .16       0  5393.7     .05       0
Bank Sta=4995.9,5000.1
XS Rating Curve= 0 ,0
Exp/Cntr=0.3,0.1

Type RM Length L Ch R = 1 ,3745    ,359,359,359
BEGIN DESCRIPTION:
UNT0274 IN DUCK CR 7 0
END DESCRIPTION:
XS GIS Cut Line= 3
      3602811.69     10458223.89      3602509.61     10458956.53
       3602547.8     10459564.16
#Sta/Elev= 30
  4349.7  429.06  4415.9  427.45  4439.8   425.7  4445.2  426.17  4463.8  424.19
  4469.2  424.47  4487.7  422.65  4493.1   422.8  4498.7  421.45    4541  418.08
  4546.4   418.4  4563.6  416.94  4602.9  415.24  4682.6  412.84  4844.8  411.09
  4967.2  412.49  4974.6  412.21  4994.4  409.67  4994.7  409.17  4998.4  409.17
  4998.7  409.67  5020.4  412.53  5050.4  412.19  5097.6  414.74  5121.6  416.73
  5227.5  420.63  5347.7  422.02  5416.9  423.71    5422  423.32    5751  427.21
#Mann= 4 ,-1 , 0
  4349.7     .05       0  4602.9     .16       0  4994.4     .03       0
  4998.7     .05       0
Bank Sta=4994.4,4998.7
XS Rating Curve= 0 ,0
Exp/Cntr=0.3,0.1

Type RM Length L Ch R = 1 ,3386    ,539,539,539
BEGIN DESCRIPTION:
UNT0274 IN DUCK CR 6 0
END DESCRIPTION:
XS GIS Cut Line= 3
      3602276.97     10458209.99      3602280.44     10459303.75
      3602374.18     10459581.49
#Sta/Elev= 30
  4471.3   431.4  4609.4  423.93    4693  419.07    4783  415.44    4853  410.86
    4933  410.19    4983  411.32  5000.8  409.89  5001.1  409.39  5005.1  409.89
    5013  411.26    5023  411.34    5213  410.53  5297.4  411.42    5373  411.67
    5393  413.45    5413  413.46    5443  415.69    5453  415.98    5463  415.02
  5499.2  417.62    5543  418.47  5573.4  423.32  5587.6  422.47  5605.1  423.74
    5682  424.78  5739.6   427.9  5744.9  427.18  5771.1  428.71  5858.2  430.57
#Mann= 6 ,-1 , 0
  4471.3     .05       0  4609.4     .16       0  5000.8     .07       0
  5005.1     .16       0  5297.4     .05       0  5499.2     .16       0
Bank Sta=5000.8,5005.1
XS Rating Curve= 0 ,0
Exp/Cntr=0.3,0.1

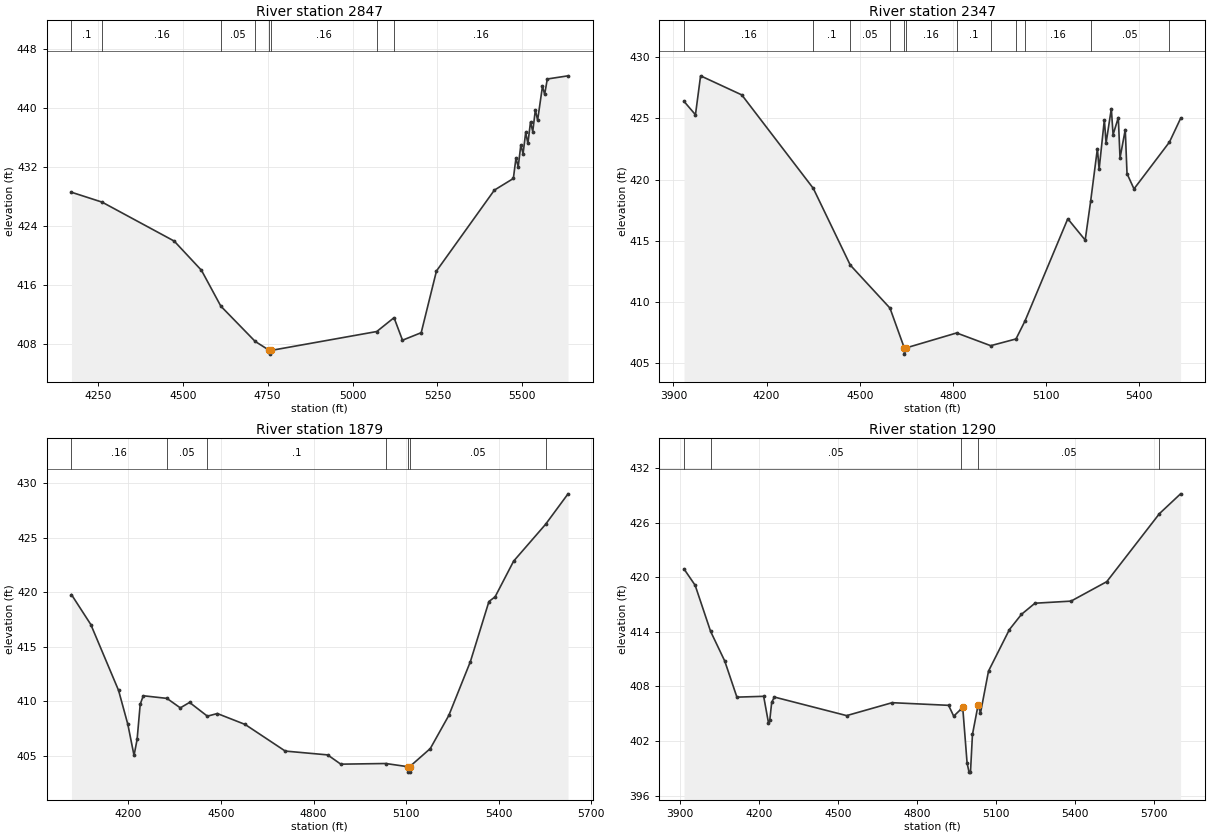
Type RM Length L Ch R = 1 ,2847    ,500,500,500
BEGIN DESCRIPTION:
UNT0274 IN DUCK CR 5 0
END DESCRIPTION:
XS GIS Cut Line= 4
      3601904.96     10458098.69      3601740.89     10458421.62
      3601897.14     10459169.02      3601678.39     10459424.23
#Sta/Elev= 30
  4172.6  428.61  4262.7  427.27    4475  421.98  4555.3  418.01  4612.2  413.15
  4713.3  408.36  4755.4  407.13  4755.7  406.63  4759.8  407.13  5071.4   409.7
  5122.2  411.58  5147.1  408.52  5202.2  409.54  5247.1  417.92  5417.6   428.9
  5473.5  430.48  5481.2  433.25  5487.8  432.07  5495.5  435.03  5502.1  433.84
  5509.8  436.73  5516.3  435.25    5524  438.15  5530.6  436.86  5538.3   439.8
  5544.9  438.39  5559.2  442.99  5565.7  441.91  5573.4  443.99  5634.5  444.42
#Mann= 8 ,-1 , 0
  4172.6      .1       0  4262.7     .16       0  4612.2     .05       0
  4713.3     .16       0  4755.4     .07       0  4759.8     .16       0
  5071.4      .1       0  5122.2     .16       0
Bank Sta=4755.4,4759.8
XS Rating Curve= 0 ,0
Exp/Cntr=0.3,0.1

Type RM Length L Ch R = 1 ,2347    ,468,468,468
BEGIN DESCRIPTION:
UNT0274 IN DUCK CR 4 0
END DESCRIPTION:
XS GIS Cut Line= 3
      3601872.39     10457900.81      3601439.41     10458737.39
      3601148.74     10459327.27
#Sta/Elev= 30
    3934  426.39  3970.8   425.3  3987.3  428.48  4120.1  426.92  4350.5  419.28
  4469.4  413.02  4597.4   409.5  4643.6  406.24  4643.9  405.74  4648.1  406.24
  4812.1  407.47  4921.9  406.43  5003.4  406.98  5032.4  408.45  5170.2   416.8
  5226.3  415.06  5243.9  418.24  5265.6  422.53  5271.2  420.85    5288  424.89
  5293.6  422.99  5310.5   425.8  5316.1  423.67    5333  425.07  5338.5  421.76
  5355.4  424.09    5361  420.49  5383.5  419.24  5497.8  423.07  5533.6     425
#Mann= 12 ,-1 , 0
    3934     .16       0  4350.5      .1       0  4469.4     .05       0
  4597.4     .16       0  4643.6     .07       0  4648.1     .16       0
  4812.1      .1       0  4921.9     .16       0  5003.4      .1       0
  5032.4     .16       0  5243.9     .05       0  5497.8      .1       0
Bank Sta=4643.6,4648.1
XS Rating Curve= 0 ,0
Exp/Cntr=0.3,0.1

Type RM Length L Ch R = 1 ,1879    ,589,589,589
BEGIN DESCRIPTION:
UNT0274 IN DUCK CR 2 0
END DESCRIPTION:
XS GIS Cut Line= 2
      3600957.29     10457829.05      3600918.26     10459437.98
#Sta/Elev= 30
  4015.3  419.79  4077.9  417.05  4167.9  411.01  4197.9   407.9    4218  405.05
    4228  406.52    4238  409.74    4248  410.52  4324.6  410.28    4368  409.41
    4398  409.91  4455.7  408.65    4488  408.89  4578.1  407.89  4708.1  405.45
  4845.5   405.1  4888.1  404.25  5033.8  404.31    5105  404.02  5105.5  403.52
  5110.9  403.52  5111.4  404.02  5178.2  405.68  5238.3  408.72  5308.3  413.66
  5368.3  419.16  5388.3  419.59  5448.3  422.86  5551.7  426.23  5624.7  429.03
#Mann= 7 ,-1 , 0
  4015.3     .16       0  4324.6     .05       0  4455.7      .1       0
  5033.8     .05       0    5105     .07       0  5111.4     .05       0
  5551.7      .1       0
Bank Sta=5105,5111.4
XS Rating Curve= 0 ,0
Exp/Cntr=0.3,0.1

Type RM Length L Ch R = 1 ,1290    ,0,0,0
BEGIN DESCRIPTION:
UNT0274 IN DUCK CR 1 0
END DESCRIPTION:
XS GIS Cut Line= 3
      3600614.42     10457664.13      3600401.74     10458844.72
      3600692.53     10459465.38
#Sta/Elev= 30
  3915.4  420.91  3957.6  419.12  4016.3  414.05  4069.9   410.8  4116.1  406.83
  4217.7  406.92  4235.8  404.03  4240.9   404.3  4248.2  406.26  4258.3  406.84
  4532.7   404.8  4705.4  406.22  4919.7  405.93  4939.1  404.74  4968.2  405.55
  4973.3  405.72  4989.9   399.6  4997.3  398.59  5002.8  398.59  5010.3  402.73
    5032  406.01  5040.7  405.06  5071.2  409.69  5150.7  414.26  5196.4  415.93
  5247.6  417.15  5384.5  417.38  5520.2  419.52  5720.3     427  5800.4  429.17
#Mann= 5 ,-1 , 0
  3915.4     .05       0  4016.3     .05       0  4968.2     .03       0
    5032     .05       0  5720.3     .16       0
Bank Sta=4973.3,5032
XS Rating Curve= 0 ,0
Exp/Cntr=0.3,0.1

Chan Stop Cuts=-1
Use User Specified Reach Order=0
Composite Channel Slope=5