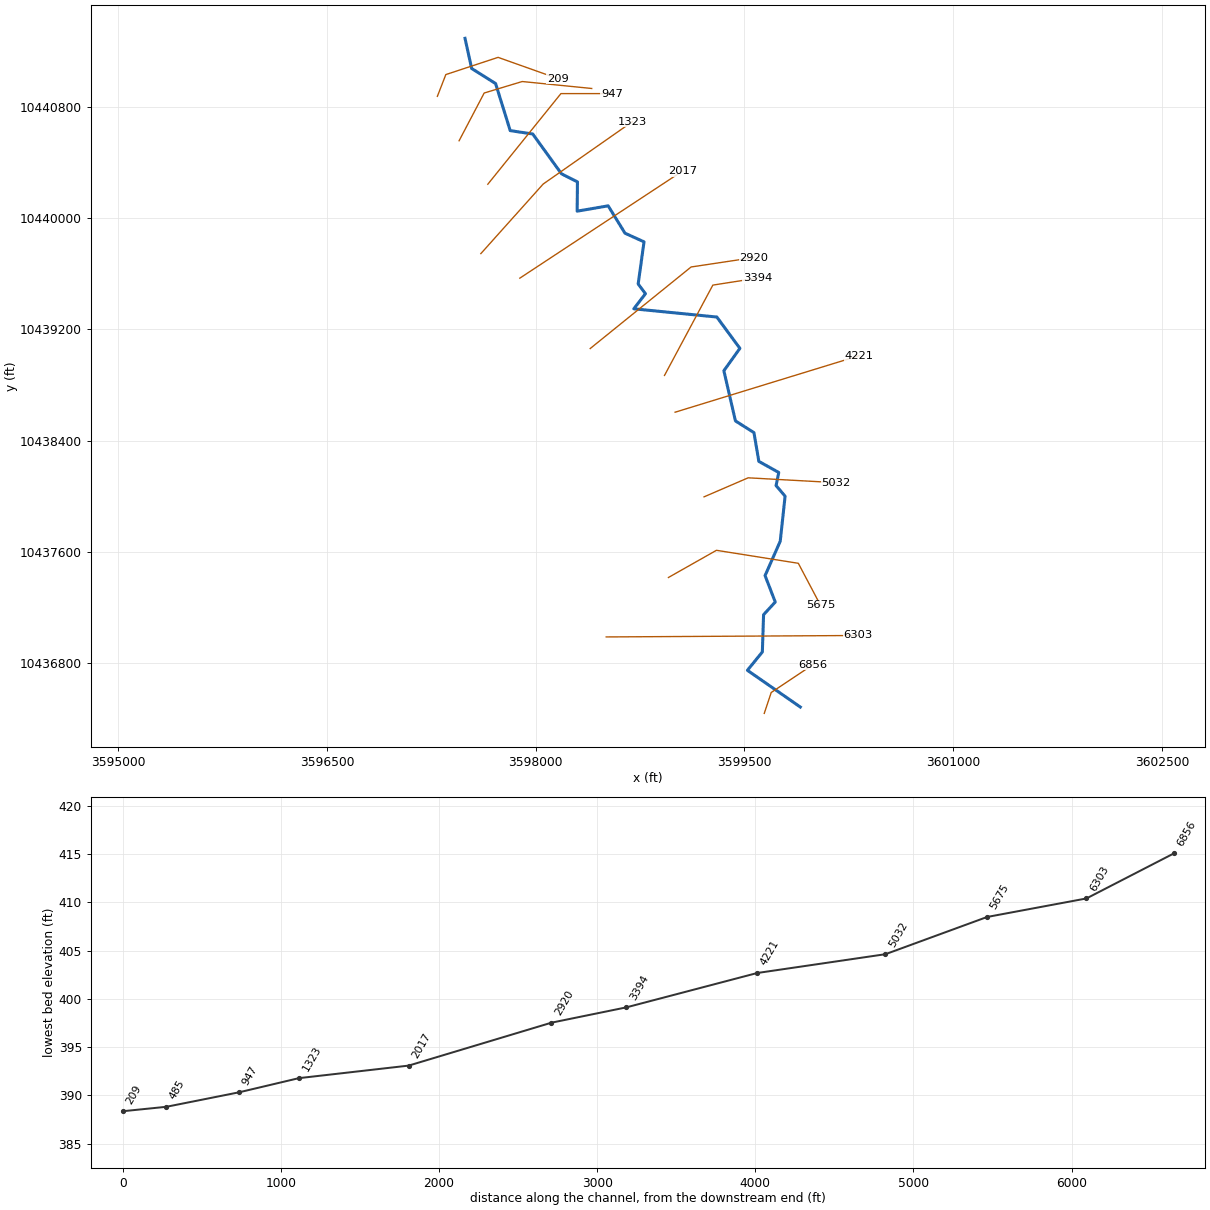
--- UNT0278 IN DUCK CR.prj (project) ---

Proj Title=UNT0278 IN DUCK CR Base Level Engineering
Current Plan=p01
Default Exp/Contr=0.3,0.1
English Units
Geom File=g01
Flow File=f01
Plan File=p01
BEGIN DESCRIPTION:
UNT0278 IN DUCK CR
END DESCRIPTION:

--- UNT0278 IN DUCK CR.p01 (plan) ---

Plan Title=Multiple Run
Short Identifier=Multiple
Geom File=g01
Flow File=f01
Subcritical Flow
K Sum by GR= 0
Std Step Tol= 0.01
Critical Tol= 0.01
Num of Std Step Trials= 20
Max Error Tol= 0.3
Flow Tol Ratio= 0.001
Split Flow NTrial= 30
Split Flow Tol= 0.02
Split Flow Ratio= 0.02
Log Output Level= 0
Friction Slope Method= 1
Unsteady Friction Slope Method= 2
Unsteady Bridges Friction Slope Method= 1
Parabolic Critical Depth
Global Vel Dist=  1 , 1 , 1
Global Log Level= 0
CheckData=True
Encroach Param= -1, 0, 0, 0
BEGIN DESCRIPTION:
Multiple Run
END DESCRIPTION:

--- UNT0278 IN DUCK CR.f01 (steady flow) ---

Flow Title=Multiple
Number of Profiles=7
Profile Names=10-year,25-year,50-year,1pct_min,100-year,1pct_plu,500-year
River Rch & RM= UNT0278 IN DUCK ,Reach-1,6856
    1708    2442    3072    2819    3813    5156    5857
River Rch & RM= UNT0278 IN DUCK ,Reach-1,4221
    2710    3947    5027    4662    6304    8526    9893
Boundary for River Rch & Prof#=UNT0278 IN DUCK ,Reach-1,1
Up Type=0
Dn Type=3
Dn Slope=0.005
Boundary for River Rch & Prof#=UNT0278 IN DUCK ,Reach-1,2
Up Type=0
Dn Type=3
Dn Slope=0.005
Boundary for River Rch & Prof#=UNT0278 IN DUCK ,Reach-1,3
Up Type=0
Dn Type=3
Dn Slope=0.005
Boundary for River Rch & Prof#=UNT0278 IN DUCK ,Reach-1,4
Up Type=0
Dn Type=3
Dn Slope=0.005
Boundary for River Rch & Prof#=UNT0278 IN DUCK ,Reach-1,5
Up Type=0
Dn Type=3
Dn Slope=0.005
Boundary for River Rch & Prof#=UNT0278 IN DUCK ,Reach-1,6
Up Type=0
Dn Type=3
Dn Slope=0.005
Boundary for River Rch & Prof#=UNT0278 IN DUCK ,Reach-1,7
Up Type=0
Dn Type=3
Dn Slope=0.005

--- UNT0278 IN DUCK CR.g01 (geometry) ---

Geom Title=Existing Conditions

River Reach=UNT0278 IN DUCK ,Reach-1
Reach XY= 30
      3599901.31     10436487.10      3599521.10     10436750.99
      3599628.38     10436883.03      3599637.22     10437150.51
      3599721.08     10437241.60      3599647.98     10437431.56
      3599756.91     10437678.44      3599791.83     10438001.91
      3599727.07     10438078.30      3599746.22     10438172.49
      3599603.20     10438252.08      3599568.11     10438458.88
      3599435.00     10438542.84      3599351.90     10438903.31
      3599467.03     10439064.05      3599301.36     10439289.28
      3598704.98     10439348.30      3598788.36     10439456.77
      3598736.19     10439526.80      3598778.27     10439829.49
      3598641.63     10439891.44      3598520.63     10440088.11
      3598297.98     10440050.01      3598299.88     10440260.27
      3598185.46     10440318.06      3597978.65     10440604.39
      3597816.87     10440628.55      3597711.85     10440966.60
      3597539.80     10441075.12      3597492.11     10441291.64

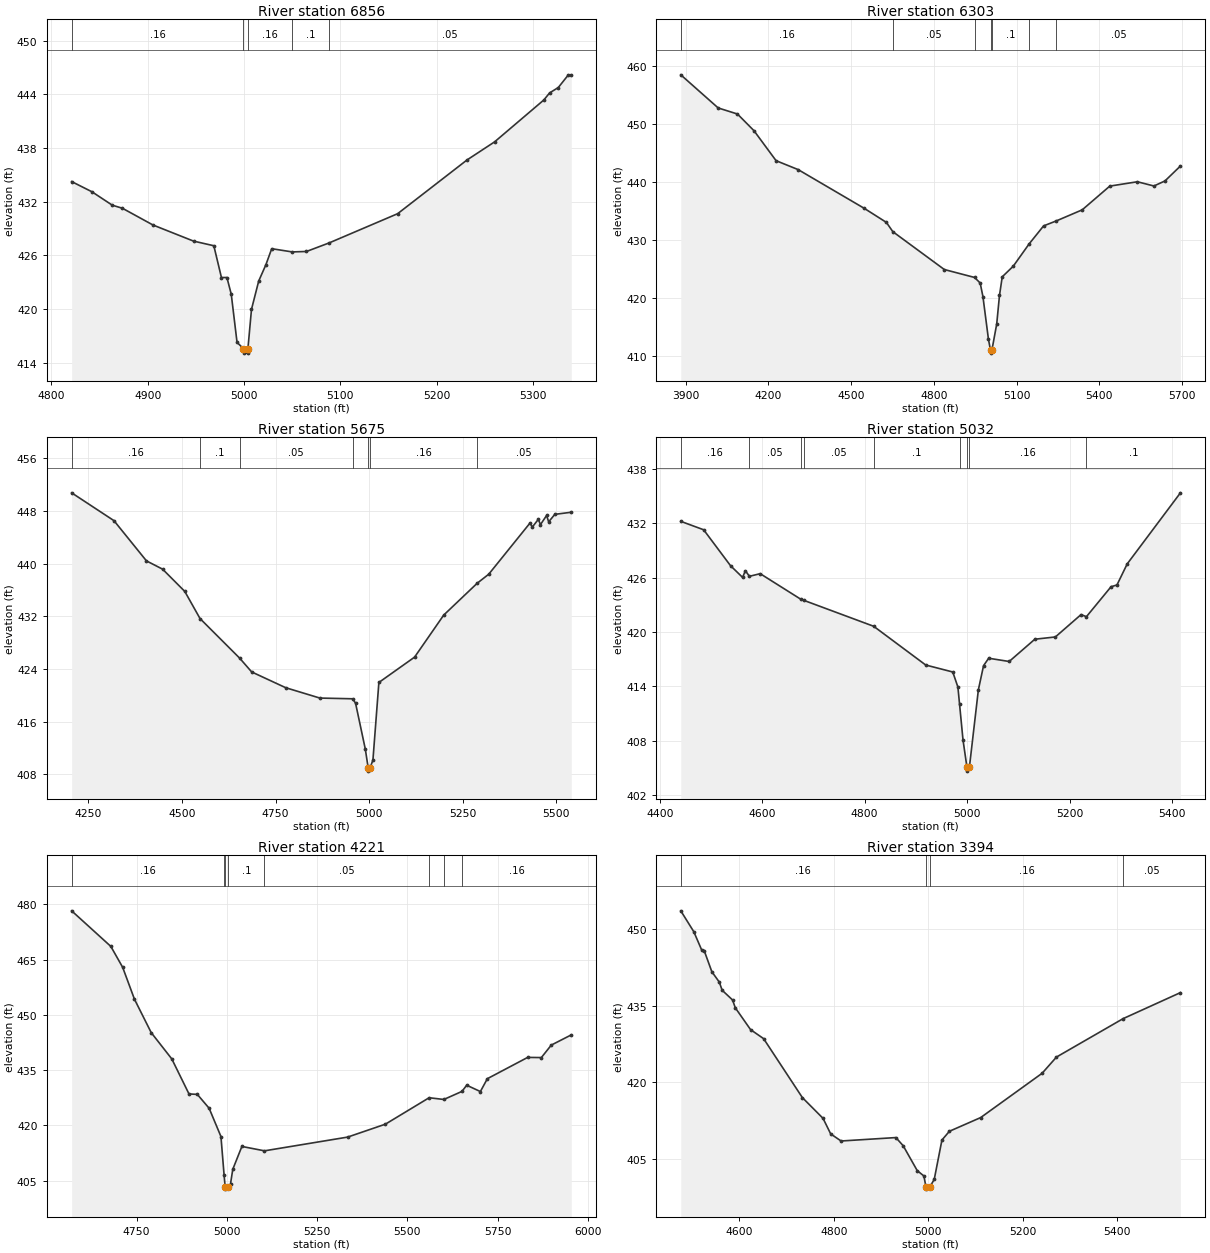
Type RM Length L Ch R = 1,6856,553,553,553
BEGIN DESCRIPTION:
UNT0278 IN DUCK CR 4 0
END DESCRIPTION:
XS GIS Cut Line= 3
      3599642.09     10436441.61      3599692.11     10436591.64
      3599992.10     10436791.64
#Sta/Elev= 30
  4821.1  434.25  4842.2  433.11  4863.3  431.61  4873.8  431.27  4905.5  429.40
  4947.6  427.60  4968.7  427.08  4976.6  423.53  4982.3  423.53  4986.8  421.66
  4992.8  416.28  4999.5  415.58  4999.8  415.08  5003.7  415.08  5004.1  415.58
  5007.8  419.97  5015.3  423.14  5022.8  424.97  5028.8  426.75  5050.1  426.39
  5064.9  426.44  5088.5  427.40  5159.5  430.66  5231.6  436.67  5260.2  438.69
  5311.3  443.37  5317.3  444.16  5326.3  444.76  5336.8  446.18  5339.8  446.18
#Mann=5,-1,0
  4821.1    0.16       0  4999.5    0.07       0  5004.1    0.16       0
  5050.1     0.1       0  5088.5    0.05       0
Bank Sta=4999.5,5004.1
Exp/Cntr=0.3,0.1

Type RM Length L Ch R = 1,6303,628,628,628
BEGIN DESCRIPTION:
UNT0278 IN DUCK CR 3 0
END DESCRIPTION:
XS GIS Cut Line= 2
      3598506.59     10436990.80      3600318.16     10437001.21
#Sta/Elev= 30
  3882.1  458.48  4017.6  452.76  4087.6  451.71  4147.6  448.82  4227.6  443.65
  4307.6  442.11  4547.6  435.41  4627.6  432.99  4650.9  431.39  4837.6  424.85
  4947.3  423.48  4967.6  422.52  4977.6  420.18  4997.6  412.81  5005.1  410.91
  5005.5  410.41  5010.1  410.91  5027.6  415.45  5037.6  420.37  5047.6  423.59
  5087.6  425.43  5145.0  429.27  5197.6  432.39  5243.8  433.25  5337.6  435.16
  5437.6  439.26  5537.6  440.01  5597.6  439.28  5637.6  440.15  5693.7  442.73
#Mann=7,-1,0
  3882.1    0.16       0  4650.9    0.05       0  4947.3     0.1       0
  5005.1    0.07       0  5010.1     0.1       0  5145.0    0.16       0
  5243.8    0.05       0
Bank Sta=5005.1,5010.1
Exp/Cntr=0.3,0.1

Type RM Length L Ch R = 1,5675,643,643,643
BEGIN DESCRIPTION:
UNT0278 IN DUCK CR 13 0
END DESCRIPTION:
XS GIS Cut Line= 4
      3598953.64     10437417.94      3599298.70     10437613.26
      3599886.81     10437519.94      3600047.11     10437216.68
#Sta/Elev= 30
  4205.3  450.77  4318.4  446.54  4405.2  440.43  4448.4  439.17  4507.6  435.79
  4548.3  431.67  4654.1  425.66  4686.3  423.56  4777.4  421.16  4868.5  419.59
  4956.1  419.48  4963.9  418.81  4990.0  411.82  4997.6  408.99  4998.0  408.49
  5002.6  408.99  5010.3  410.17  5026.2  421.96  5121.6  425.81  5199.5  432.20
  5289.0  437.04  5319.8  438.41  5430.3  446.20  5435.9  445.55  5452.3  446.75
  5457.9  445.94  5474.3  447.33  5479.9  446.36  5496.3  447.50  5540.3  447.82
#Mann=7,-1,0
  4205.3    0.16       0  4548.3     0.1       0  4654.1    0.05       0
  4956.1    0.16       0  4997.6    0.07       0  5002.6    0.16       0
  5289.0    0.05       0
Bank Sta=4997.6,5002.6
Exp/Cntr=0.3,0.1

Type RM Length L Ch R = 1,5032,811,811,811
BEGIN DESCRIPTION:
UNT0278 IN DUCK CR 92 0
END DESCRIPTION:
XS GIS Cut Line= 3
      3599209.75     10437997.39      3599526.57     10438134.09
      3600155.86     10438099.37
#Sta/Elev= 30
  4441.1  432.22  4485.7  431.29  4538.2  427.32  4561.7  426.03  4567.2  426.76
  4575.1  426.15  4596.1  426.44  4675.8  423.60  4681.0  423.50  4817.6  420.63
  4919.2  416.35  4972.0  415.58  4982.0  413.92  4985.2  412.05  4992.0  408.07
  4999.5  405.13  4999.8  404.63  5004.6  405.13  5022.0  413.62  5032.1  416.28
  5042.1  417.10  5082.1  416.74  5132.2  419.20  5172.3  419.45  5222.4  421.92
  5232.9  421.69  5281.0  425.00  5292.5  425.19  5312.5  427.52  5416.4  435.37
#Mann=9,-1,0
  4441.1    0.16       0  4575.1    0.05       0  4675.8    0.16       0
  4681.0    0.05       0  4817.6     0.1       0  4985.2    0.16       0
  4999.5    0.07       0  5004.6    0.16       0  5232.9     0.1       0
Bank Sta=4999.5,5004.6
Exp/Cntr=0.3,0.1

Type RM Length L Ch R = 1,4221,827,827,827
BEGIN DESCRIPTION:
UNT0278 IN DUCK CR 91 0
END DESCRIPTION:
XS GIS Cut Line= 2
      3599001.39     10438605.37      3600324.32     10439011.63
#Sta/Elev= 30
  4570.2  478.26  4678.8  468.59  4711.5  462.92  4744.2  454.25  4790.6  445.18
  4847.6  438.04  4895.2  428.53  4918.3  428.41  4951.0  424.64  4983.7  416.97
  4992.4  406.55  4995.5  403.18  4996.0  402.68  5004.1  403.18  5010.3  404.16
  5016.5  408.06  5041.7  414.27  5104.3  413.08  5334.6  416.81  5439.2  420.32
  5560.4  427.50  5601.1  427.03  5651.3  429.22  5664.4  430.90  5702.3  429.18
  5721.6  432.67  5833.2  438.45  5871.2  438.41  5898.7  441.80  5954.1  444.57
#Mann=8,-1,0
  4570.2    0.16       0  4992.4     0.1       0  4995.5    0.07       0
  5004.1     0.1       0  5104.3    0.05       0  5560.4    0.16       0
  5601.1    0.05       0  5651.3    0.16       0
Bank Sta=4995.5,5004.1
Exp/Cntr=0.3,0.1

Type RM Length L Ch R = 1,3394,474,474,474
BEGIN DESCRIPTION:
UNT0278 IN DUCK CR 9 0
END DESCRIPTION:
XS GIS Cut Line= 3
      3598925.44     10438869.78      3599272.66     10439518.64
      3599591.66     10439568.55
#Sta/Elev= 30
  4475.8  453.53  4503.4  449.44  4519.7  445.95  4525.3  445.77  4541.6  441.62
  4557.3  439.61  4563.5  438.00  4585.5  436.10  4591.3  434.57  4623.7  430.30
  4651.3  428.54  4733.4  417.02  4777.3  412.95  4793.5  409.91  4815.5  408.53
  4931.6  409.20  4947.1  407.60  4976.9  402.73  4991.0  401.69  4995.2  399.62
  4995.7  399.12  5004.0  399.62  5012.9  401.03  5029.2  408.72  5045.0  410.43
  5111.3  413.11  5241.5  421.77  5271.9  424.94  5413.1  432.45  5534.6  437.54
#Mann=4,-1,0
  4475.8    0.16       0  4995.2    0.07       0  5004.0    0.16       0
  5413.1    0.05       0
Bank Sta=4995.2,5004
Exp/Cntr=0.3,0.1

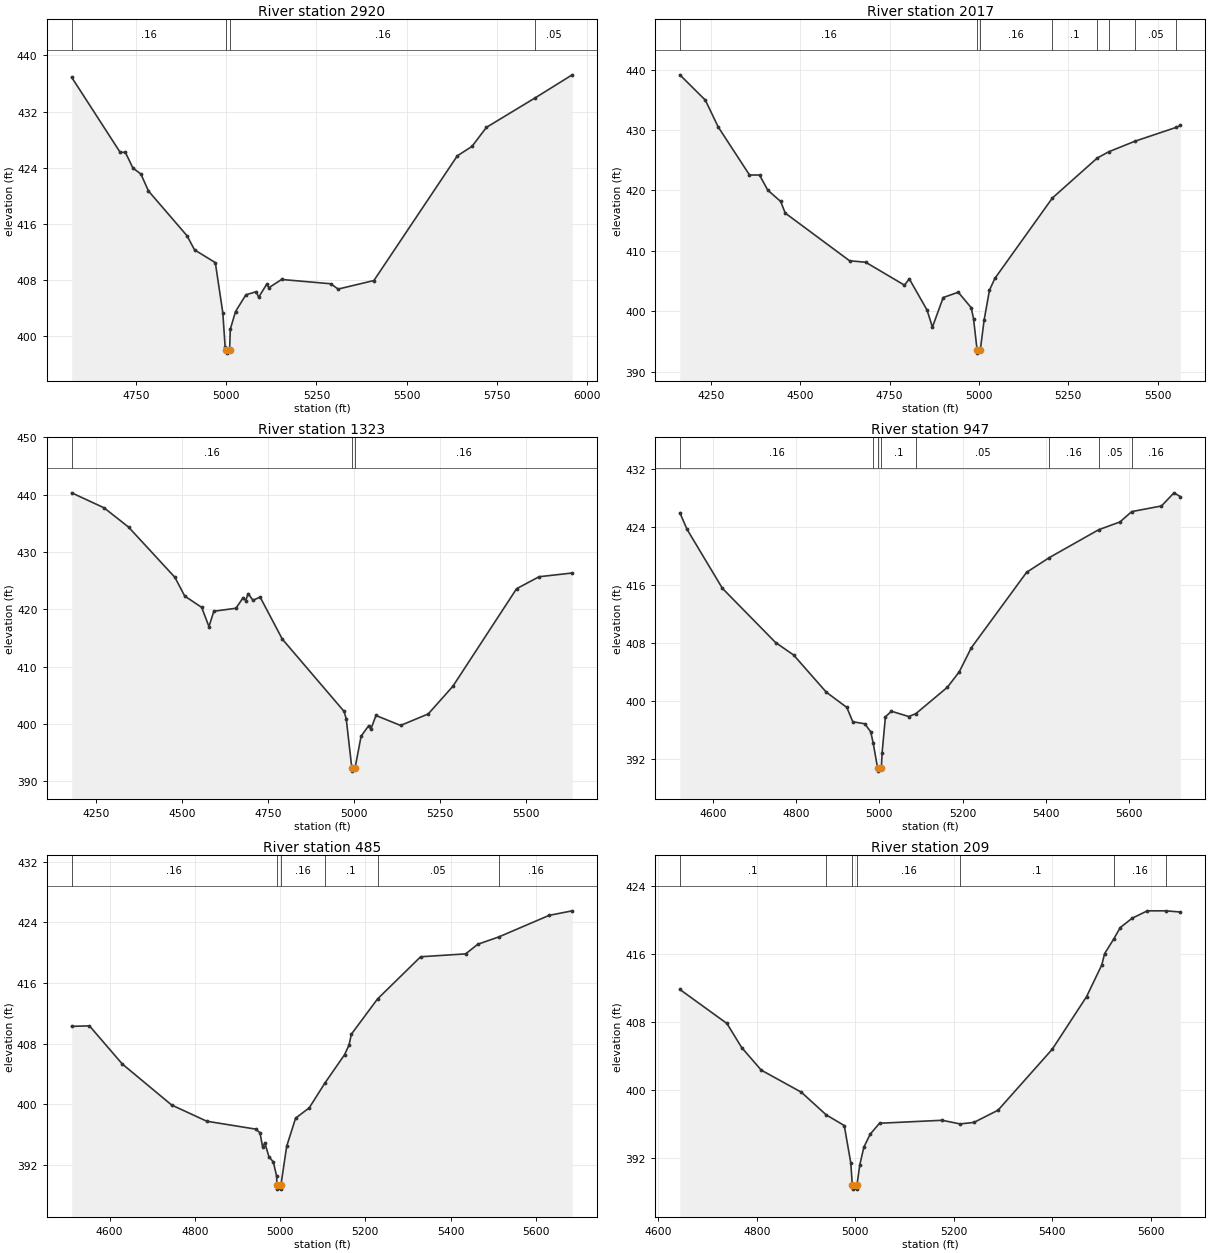
Type RM Length L Ch R = 1,2920,903,903,903
BEGIN DESCRIPTION:
UNT0278 IN DUCK CR 8 0
END DESCRIPTION:
XS GIS Cut Line= 3
      3598391.60     10439062.92      3599116.41     10439648.85
      3599567.12     10439716.64
#Sta/Elev= 30
  4571.5  436.89  4705.9  426.18  4720.3  426.19  4741.1  423.95  4763.5  423.08
  4784.3  420.67  4891.4  414.27  4912.2  412.26  4969.7  410.45  4990.5  403.30
  4997.0  398.39  5000.5  398.03  5001.0  397.53  5009.3  398.03  5011.3  400.94
  5025.7  403.46  5054.5  405.85  5083.3  406.30  5089.7  405.49  5112.0  407.34
  5118.4  406.87  5153.6  408.04  5289.5  407.43  5310.3  406.67  5409.5  407.89
  5640.7  425.68  5681.2  427.02  5721.6  429.75  5856.8  433.96  5959.3  437.24
#Mann=4,-1,0
  4571.5    0.16       0  5000.5    0.07       0  5009.3    0.16       0
  5856.8    0.05       0
Bank Sta=5000.5,5009.3
Exp/Cntr=0.3,0.1

Type RM Length L Ch R = 1,2017,694,694,694
BEGIN DESCRIPTION:
UNT0278 IN DUCK CR 7 0
END DESCRIPTION:
XS GIS Cut Line= 2
      3597885.91     10439568.54      3599055.61     10440338.93
#Sta/Elev= 30
  4163.0  439.14  4234.3  434.95  4270.4  430.50  4357.8  422.57  4385.9  422.55
  4409.0  420.05  4445.1  418.18  4457.8  416.26  4637.8  408.37  4683.0  408.12
  4791.5  404.33  4805.0  405.37  4854.7  400.21  4869.7  397.39  4899.9  402.28
  4942.0  403.16  4978.2  400.60  4984.7  398.81  4994.8  393.58  4995.3  393.08
  5003.7  393.58  5014.3  398.53  5029.4  403.50  5044.5  405.45  5205.5  418.76
  5330.7  425.36  5362.9  426.40  5436.3  428.15  5552.7  430.46  5563.6  430.77
#Mann=8,-1,0
  4163.0    0.16       0  4994.8    0.07       0  5003.7    0.16       0
  5205.5     0.1       0  5330.7    0.05       0  5362.9     0.1       0
  5436.3    0.05       0  5552.7    0.16       0
Bank Sta=4994.8,5003.7
Exp/Cntr=0.3,0.1

Type RM Length L Ch R = 1,1323,376,376,376
BEGIN DESCRIPTION:
UNT0278 IN DUCK CR 6 0
END DESCRIPTION:
XS GIS Cut Line= 3
      3597605.87     10439744.84      3598053.81     10440244.86
      3598694.43     10440692.78
#Sta/Elev= 30
  4180.0  440.34  4274.1  437.72  4345.1  434.36  4479.7  425.59  4508.1  422.33
  4557.4  420.35  4578.5  416.99  4592.6  419.68  4656.9  420.20  4677.8  422.06
  4685.3  421.54  4692.0  422.76  4706.2  421.60  4727.1  422.14  4791.4  414.82
  4970.9  402.19  4977.0  400.90  4993.3  392.28  4993.8  391.78  5002.5  392.28
  5020.1  397.87  5042.4  399.73  5048.5  399.10  5063.3  401.49  5134.8  399.75
  5215.1  401.76  5286.6  406.59  5471.5  423.61  5536.8  425.70  5633.0  426.35
#Mann=3,-1,0
  4180.0    0.16       0  4993.3    0.07       0  5002.5    0.16       0
Bank Sta=4993.3,5002.5
Exp/Cntr=0.3,0.1

Type RM Length L Ch R = 1,947,462,462,462
BEGIN DESCRIPTION:
Mapping XS 6def98de
END DESCRIPTION:
XS GIS Cut Line= 3
      3597655.89     10440243.45      3598181.08     10440894.51
      3598547.50     10440894.51
#Sta/Elev= 30
  4520.6  425.95  4538.0  423.65  4622.8  415.53  4750.7  408.05  4793.9  406.34
  4872.3  401.22  4921.9  399.10  4936.2  397.13  4965.0  396.85  4979.4  395.73
  4985.4  394.14  4995.6  390.82  4996.1  390.32  5004.8  390.82  5006.6  392.83
  5014.6  397.81  5029.0  398.58  5070.7  397.85  5087.8  398.25  5163.4  401.88
  5192.1  404.02  5220.9  407.32  5353.9  417.74  5408.9  419.78  5526.7  423.60
  5578.1  424.68  5606.6  426.11  5678.1  426.89  5708.1  428.70  5723.5  428.17
#Mann=8,-1,0
  4520.6    0.16       0  4985.4     0.1       0  4995.6    0.07       0
  5004.8     0.1       0  5087.8    0.05       0  5408.9    0.16       0
  5526.7    0.05       0  5606.6    0.16       0
Bank Sta=4995.6,5004.8
Exp/Cntr=0.3,0.1

Type RM Length L Ch R = 1,485,276,276,276
BEGIN DESCRIPTION:
Mapping XS 09714af0
END DESCRIPTION:
XS GIS Cut Line= 4
      3597449.73     10440555.94      3597629.86     10440898.85
      3597903.30     10440981.32      3598402.46     10440931.40
#Sta/Elev= 30
  4511.0  410.29  4552.7  410.35  4629.6  405.33  4745.5  399.91  4828.0  397.77
  4942.5  396.73  4952.9  396.25  4959.1  394.35  4964.3  394.91  4973.8  393.10
  4984.2  392.39  4992.0  390.51  4992.6  389.31  4993.1  388.81  5001.4  388.81
  5001.9  389.31  5015.6  394.48  5036.5  398.18  5068.4  399.53  5104.9  402.78
  5151.4  406.55  5161.8  407.82  5167.4  409.26  5228.7  413.90  5329.9  419.47
  5435.5  419.85  5464.1  421.12  5513.0  422.08  5631.4  424.93  5685.6  425.53
#Mann=6,-1,0
  4511.0    0.16       0  4992.6    0.07       0  5001.9    0.16       0
  5104.9     0.1       0  5228.7    0.05       0  5513.0    0.16       0
Bank Sta=4992.6,5001.9
Exp/Cntr=0.3,0.1

Type RM Length L Ch R = 1,209,0,0,0
BEGIN DESCRIPTION:
UNT0278 IN DUCK CR 1 0
END DESCRIPTION:
XS GIS Cut Line= 4
      3597293.49     10440874.96      3597354.26     10441031.23
      3597729.69     10441154.93      3598157.15     10441003.04
#Sta/Elev= 30
  4643.7  411.87  4739.3  407.86  4769.2  405.03  4808.9  402.37  4890.3  399.77
  4940.9  397.10  4977.6  395.84  4990.9  391.42  4993.9  388.85  4994.4  388.35
  5002.9  388.35  5003.4  388.85  5009.1  391.20  5017.4  393.29  5030.2  394.82
  5049.2  396.11  5176.3  396.46  5212.9  396.03  5241.1  396.21  5290.0  397.65
  5400.2  404.84  5469.8  411.03  5500.6  414.75  5506.4  416.09  5524.5  417.77
  5538.2  419.16  5562.3  420.26  5593.2  421.13  5630.8  421.13  5660.3  420.99
#Mann=7,-1,0
  4643.7     0.1       0  4940.9    0.16       0  4993.9    0.07       0
  5003.4    0.16       0  5212.9     0.1       0  5524.5    0.16       0
  5630.8    0.05       0
Bank Sta=4993.9,5003.4
Exp/Cntr=0.3,0.1

Chan Stop Cuts=-1