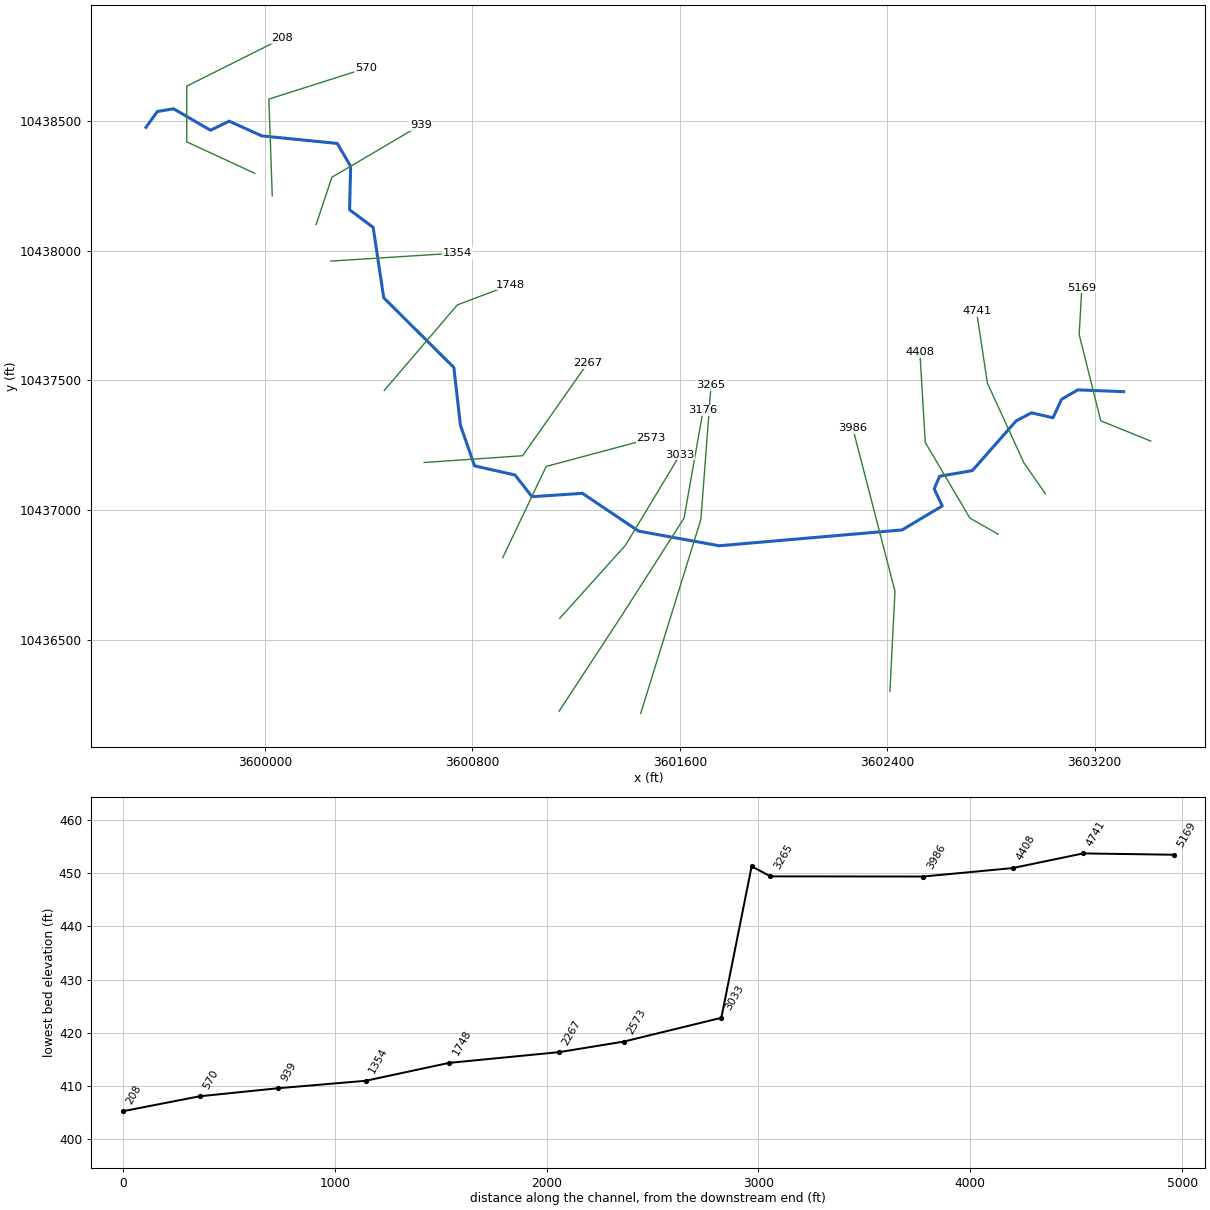
--- UNT0279 IN DUCK CR.prj (project) ---

Proj Title=UNT0279 IN DUCK CR Base Level Engineering
Current Plan=p01
Default Exp/Contr=0.3,0.1
English Units
Geom File=g01
Flow File=f01
Plan File=p01
Y Axis Title=Elevation
X Axis Title(PF)=Main Channel Distance
X Axis Title(XS)=Station
BEGIN DESCRIPTION:
UNT0279 IN DUCK CR
END DESCRIPTION:
DSS Export Rating Curves= 0
DSS Export Rating Curve Sorted= 0
DSS Export Volume Flow Curves= 0
DXF OffsetX= 0
DXF OffsetY= 0
DXF ScaleX= 1
DXF ScaleY= 10

--- UNT0279 IN DUCK CR.p01 (plan) ---

Plan Title=Multiple Run
Short Identifier=Multiple
Geom File=g01
Flow File=f01
Subcritical Flow
K Sum by GR= 0
Std Step Tol= 0.01
Critical Tol= 0.01
Num of Std Step Trials= 20
Max Error Tol= 0.3
Flow Tol Ratio= 0.001
Split Flow NTrial= 30
Split Flow Tol= 0.02
Split Flow Ratio= 0.02
Log Output Level= 0
Friction Slope Method= 1
Unsteady Friction Slope Method= 2
Unsteady Bridges Friction Slope Method= 1
Parabolic Critical Depth
Global Vel Dist=  1 , 1 , 1
Global Log Level= 0
CheckData=True
Encroach Param= -1, 0, 0, 0
BEGIN DESCRIPTION:
Multiple Run
END DESCRIPTION:

--- UNT0279 IN DUCK CR.f01 (steady flow) ---

Flow Title=Multiple
Program Version=4.10
Number of Profiles= 7
Profile Names=10-year,25-year,50-year,1pct_min,100-year,1pct_plu,500-year
River Rch & RM=UNT0279 IN DUCK,Reach-1         ,5169
    1276    1790    2224    2017    2728    3689    4090
River Rch & RM=UNT0279 IN DUCK,Reach-1         ,3986
    1462    2065    2577    2346    3173    4292    4797
Boundary for River Rch & Prof#=UNT0279 IN DUCK,Reach-1         , 1
Up Type= 0
Dn Type= 3
Dn Slope=0.008
Boundary for River Rch & Prof#=UNT0279 IN DUCK,Reach-1         , 2
Up Type= 0
Dn Type= 3
Dn Slope=0.008
Boundary for River Rch & Prof#=UNT0279 IN DUCK,Reach-1         , 3
Up Type= 0
Dn Type= 3
Dn Slope=0.008
Boundary for River Rch & Prof#=UNT0279 IN DUCK,Reach-1         , 4
Up Type= 0
Dn Type= 3
Dn Slope=0.008
Boundary for River Rch & Prof#=UNT0279 IN DUCK,Reach-1         , 5
Up Type= 0
Dn Type= 3
Dn Slope=0.008
Boundary for River Rch & Prof#=UNT0279 IN DUCK,Reach-1         , 6
Up Type= 0
Dn Type= 3
Dn Slope=0.008
Boundary for River Rch & Prof#=UNT0279 IN DUCK,Reach-1         , 7
Up Type= 0
Dn Type= 3
Dn Slope=0.008
DSS Import GetInterval= 0
DSS Import GetPeak= 0
DSS Import FillOption= 0

--- UNT0279 IN DUCK CR.g01 (geometry) ---

Geom Title=Existing Conditions
Program Version=4.10

River Reach=UNT0279 IN DUCK ,Reach-1
Reach XY= 30
      3603312.37     10437456.81      3603135.29     10437463.75
      3603072.79      10437427.3       3603039.8     10437356.11
      3602956.47     10437375.21      3602897.44     10437343.96
      3602728.71      10437152.4       3602602.3     10437130.42
      3602581.47     10437081.81      3602612.72     10437015.84
      3602457.62     10436923.44      3601752.03     10436862.36
      3601441.26     10436918.78       3601224.6     10437064.61
       3601029.8     10437051.59      3600964.75     10437135.19
       3600808.3     10437170.56      3600753.75     10437327.43
      3600728.45     10437550.11      3600457.84     10437819.08
      3600417.14     10438090.67      3600326.23     10438158.51
      3600330.33     10438326.13      3600278.69     10438414.38
      3599987.89     10438443.45      3599861.66     10438500.32
      3599789.52     10438465.35      3599647.02     10438548.16
      3599584.67     10438537.62      3599540.77     10438476.68

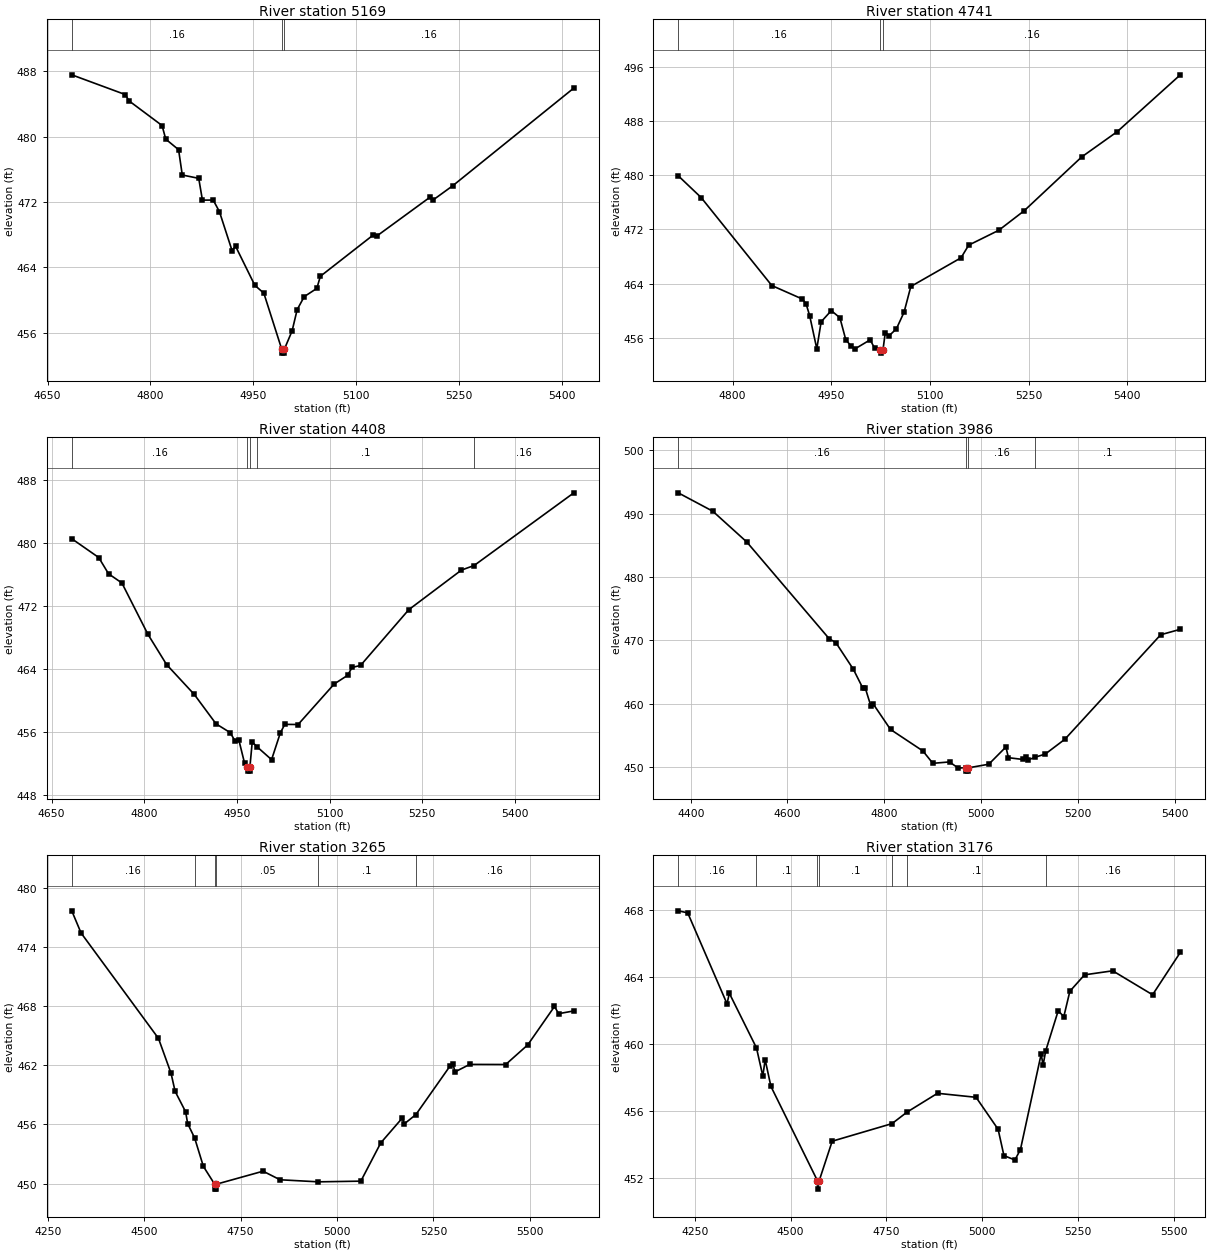
Type RM Length L Ch R = 1 ,5169    ,428,428,428
BEGIN DESCRIPTION:
UNT0279 IN DUCK CR 11
END DESCRIPTION:
XS GIS Cut Line= 4
      3603416.76     10437266.22      3603224.09     10437344.34
      3603140.75     10437677.67      3603151.07     10437858.28
#Sta/Elev= 30
  4685.4  487.59  4763.5  485.17  4768.9   484.4  4817.1  481.38  4822.5  479.71
  4841.2  478.42  4846.6  475.32  4870.6  474.91    4876  472.24  4891.7  472.25
  4900.8  470.83  4919.2  466.06  4924.3   466.6  4952.4  461.81  4965.6  460.84
  4991.6     454  4991.9   453.5  4995.4   453.5  4995.6     454  5006.8  456.22
  5014.2  458.83  5024.5  460.42  5042.9  461.43    5048  462.91  5125.3  467.98
  5130.5  467.85  5207.8  472.59    5213  472.29  5241.4  474.02  5417.8  485.97
#Mann= 3 ,-1 , 0
  4685.4     .16       0  4991.6     .07       0  4995.6     .16       0
Bank Sta=4991.6,4995.6
XS Rating Curve= 0 ,0
Exp/Cntr=0.3,0.1

Type RM Length L Ch R = 1 ,4741    ,333,333,333
BEGIN DESCRIPTION:
Mapping XS c8abbb76
END DESCRIPTION:
XS GIS Cut Line= 4
      3603010.56     10437063.07      3602927.21     10437182.88
      3602786.59     10437490.17      3602744.91     10437766.25
#Sta/Elev= 30
  4717.5  479.91  4752.3   476.7  4859.7  463.72  4906.1  461.73  4911.7  461.05
  4917.2   459.3  4928.1  454.39  4934.7  458.37  4950.1  460.02  4963.2  458.97
  4972.1  455.74  4980.7  454.73  4986.2  454.38  5009.2  455.71  5016.1  454.46
  5024.7  454.25    5025  453.75  5028.7  454.25  5032.2  456.79    5038  456.32
    5049  457.32  5060.7  459.78    5071  463.58  5147.3  467.81    5159  469.68
  5204.7  471.87  5243.3  474.75  5330.6  482.68  5384.9  486.43  5480.6   494.8
#Mann= 3 ,-1 , 0
  4717.5     .16       0  5024.7     .07       0  5028.7     .16       0
Bank Sta=5024.7,5028.7
XS Rating Curve= 0 ,0
Exp/Cntr=0.3,0.1

Type RM Length L Ch R = 1 ,4408    ,422,422,422
BEGIN DESCRIPTION:
Mapping XS 3bc71bea
END DESCRIPTION:
XS GIS Cut Line= 4
      3602828.23     10436906.85      3602718.88     10436969.34
        3602547.       10437261.      3602526.27      10437608.3
#Sta/Elev= 30
  4682.7  480.56  4726.3  478.17  4742.2   476.1  4763.8  474.93  4805.9   468.4
  4836.1  464.55    4881  460.74  4916.1  457.01    4939  455.89  4947.4  454.76
  4953.2   454.9  4962.2  452.03  4966.9  451.49  4967.1  450.99  4970.6  450.99
  4970.9  451.49  4974.7   454.7    4982  454.12    5006  452.45  5020.2  455.86
  5027.4  456.94  5048.9  456.92  5107.4  462.08  5128.9  463.17  5136.3  464.18
    5150  464.44    5228  471.53  5313.2  476.57  5333.7  477.15  5495.1   486.4
#Mann= 5 ,-1 , 0
  4682.7     .16       0  4966.9     .07       0  4970.9     .16       0
    4982      .1       0  5333.7     .16       0
Bank Sta=4966.9,4970.9
XS Rating Curve= 0 ,0
Exp/Cntr=0.3,0.1

Type RM Length L Ch R = 1 ,3986    ,721,721,721
BEGIN DESCRIPTION:
UNT0279 IN DUCK CR 11
END DESCRIPTION:
XS GIS Cut Line= 3
      3602410.68     10436300.35      3602430.21     10436686.61
       3602267.1     10437316.68
#Sta/Elev= 30
  4374.2  493.28  4445.6  490.38  4515.7  485.54  4685.9   470.3  4700.2  469.63
    4736  465.47    4756  462.44    4761  462.44  4772.3  459.66  4777.5  459.95
  4812.9  455.97  4879.8  452.58  4900.4  450.63  4934.8  450.85  4952.1  449.92
  4968.1   449.9  4968.3   449.4  4972.1   449.4  4972.4   449.9    5016  450.49
  5051.4  453.21  5056.6  451.52  5086.4  451.24    5092  451.61  5097.2  451.16
  5112.5  451.61  5132.7  452.09  5173.3  454.43  5371.2   470.9  5411.8  471.76
#Mann= 4 ,-1 , 0
  4374.2     .16       0  4968.1     .07       0  4972.4     .16       0
  5112.5      .1       0
Bank Sta=4968.1,4972.4
XS Rating Curve= 0 ,0
Exp/Cntr=0.3,0.1

Type RM Length L Ch R = 1 ,3265    ,89,89,89
BEGIN DESCRIPTION:
UNT0279 IN DUCK CR 10
END DESCRIPTION:
XS GIS Cut Line= 3
      3601449.32     10436215.74      3601681.51     10436964.39
      3601720.58     10437480.88
#Sta/Elev= 30
  4312.4  477.68  4336.5  475.43  4537.2  464.73  4569.8  461.19  4580.3  459.36
  4607.6  457.28  4612.9  456.08    4631  454.62  4653.6  451.74  4682.8  449.93
  4683.1  449.43    4687  449.43  4687.3  449.93  4808.4  451.25  4852.5  450.38
  4951.8  450.17  5061.9  450.24  5113.5  454.12  5169.5  456.65  5174.5  456.05
  5204.7     457    5294  461.97    5301  462.11    5306  461.33  5344.2  462.09
  5437.5  462.08  5494.6  464.07    5564  467.97  5574.8  467.24  5614.2  467.52
#Mann= 6 ,-1 , 0
  4312.4     .16       0    4631     .05       0  4682.8     .07       0
  4687.3     .05       0  4951.8      .1       0  5204.7     .16       0
Bank Sta=4682.8,4687.3
XS Rating Curve= 0 ,0
Exp/Cntr=0.3,0.1

Type RM Length L Ch R = 1 ,3176    ,143,143,143
BEGIN DESCRIPTION:
UNT0279 IN DUCK CR 2
END DESCRIPTION:
XS GIS Cut Line= 4
      3601134.63     10436224.36      3601373.35     10436588.95
      3601616.41     10436968.73      3601690.19     10437385.36
#Sta/Elev= 30
  4206.8  467.93  4231.5  467.81  4334.1  462.38  4340.1  463.01  4410.9  459.75
  4427.5  458.07  4433.5  459.05  4448.6  457.45    4570  451.82  4570.3  451.32
  4574.5  451.82  4608.4  454.18  4764.5  455.23  4803.9  455.92  4883.2  457.04
  4983.8   456.8  5041.3  454.89  5056.5  453.32  5085.1  453.06  5099.5  453.68
  5153.6  459.38  5158.6  458.72  5165.4  459.57    5198  461.96  5212.7  461.62
  5228.5  463.13  5266.8  464.11  5340.2  464.35  5444.2  462.92  5516.6  465.45
#Mann= 7 ,-1 , 0
  4206.8     .16       0  4410.9      .1       0    4570     .07       0
  4574.5      .1       0  4764.5     .16       0  4803.9      .1       0
  5165.4     .16       0
Bank Sta=4570,4574.5
XS Rating Curve= 0 ,0
Exp/Cntr=0.3,0.1

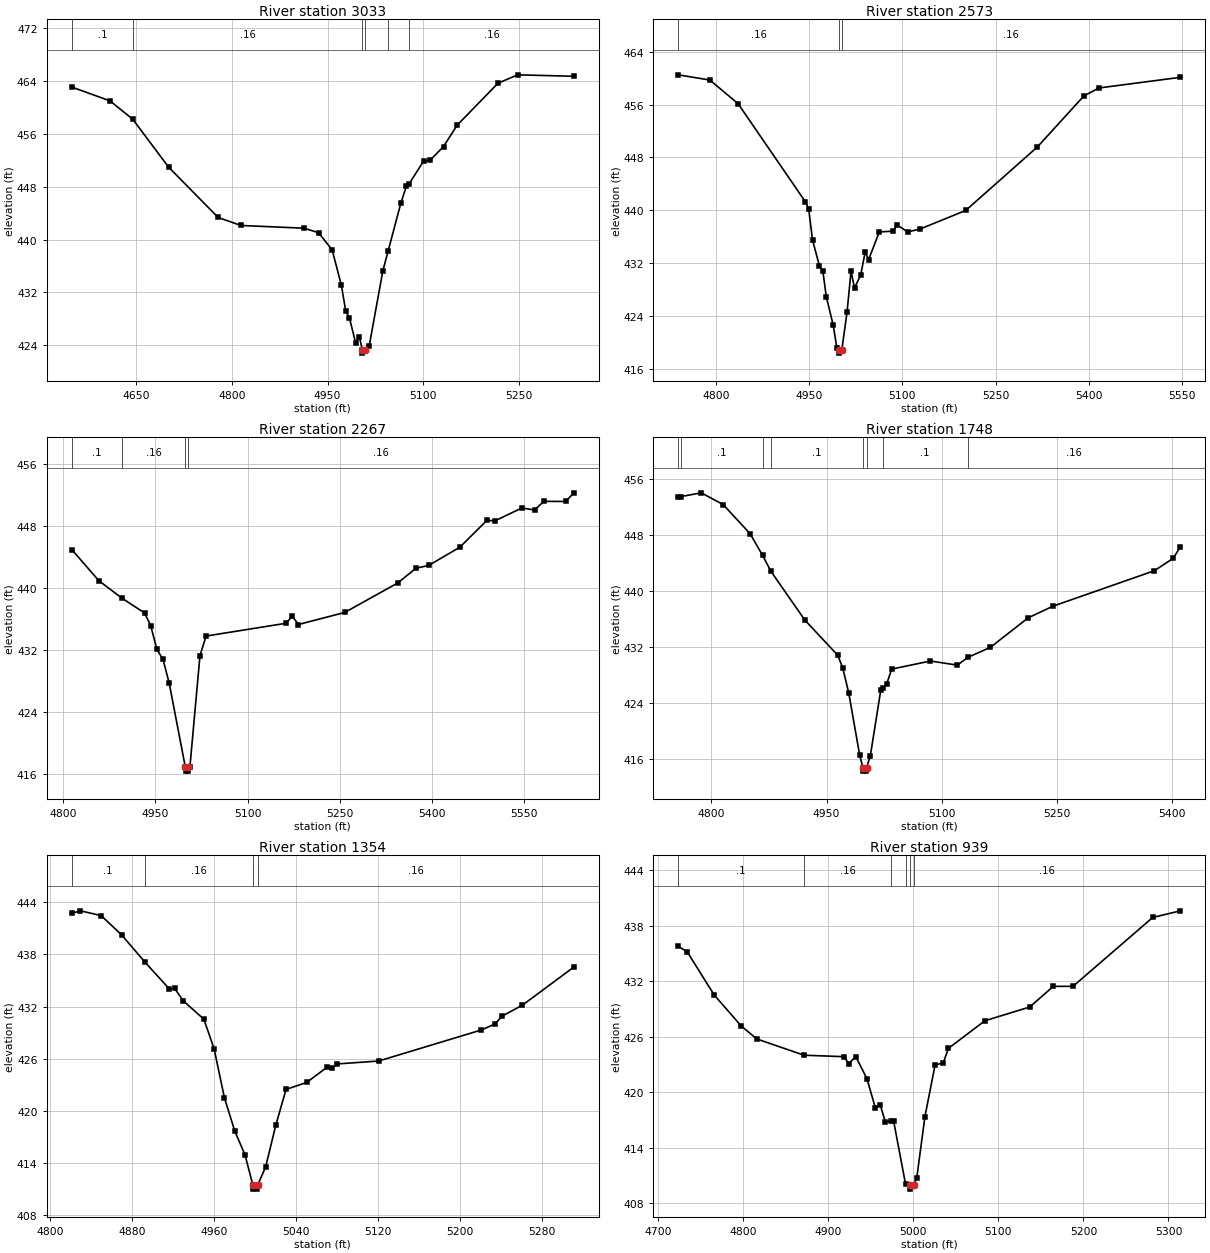
Type RM Length L Ch R = 1 ,3033    ,460,460,460
BEGIN DESCRIPTION:
UNT0279 IN DUCK CR 9 0
END DESCRIPTION:
XS GIS Cut Line= 3
      3601136.78     10436582.41      3601390.72     10436864.56
      3601601.22     10437213.95
#Sta/Elev= 30
  4548.7  463.08  4608.6  460.99  4644.4   458.2  4700.5  450.97  4778.3  443.34
  4814.1  442.13  4912.8  441.72  4935.7  441.04  4957.1  438.44  4971.6  433.07
  4978.4  429.18  4984.3  428.11    4994  424.32  4999.8   425.3  5004.4  423.31
  5004.7  422.81  5008.9  423.31  5015.3  423.95  5036.7   435.3    5045  438.29
    5065  445.57  5073.6  448.08  5077.9  448.44  5100.8  451.92  5110.5  451.98
  5131.8  454.08  5153.2  457.31  5217.3  463.67  5248.3  464.93  5336.2  464.71
#Mann= 6 ,-1 , 0
  4548.7      .1       0  4644.4     .16       0  5004.4     .07       0
  5008.9     .16       0    5045      .1       0  5077.9     .16       0
Bank Sta=5004.4,5008.9
XS Rating Curve= 0 ,0
Exp/Cntr=0.3,0.1

Type RM Length L Ch R = 1 ,2573    ,306,306,306
BEGIN DESCRIPTION:
UNT0279 IN DUCK CR 8 0
END DESCRIPTION:
XS GIS Cut Line= 3
      3600917.11     10436816.66      3601084.73     10437168.38
      3601488.33      10437276.3
#Sta/Elev= 30
  4739.5   460.5  4790.4  459.71  4835.8  456.12  4943.8  441.29  4949.3  440.16
  4955.5  435.45  4966.5  431.59    4972   430.8  4977.6  426.89  4988.7  422.58
  4994.7  419.07    4998  418.84  4998.3  418.34  5002.6  418.84  5010.9  424.51
  5017.4  430.72    5023  428.21    5033   430.2  5040.1  433.65  5045.7  432.52
  5062.8   436.7  5085.5  436.82  5091.1   437.8  5108.2   436.7  5128.2  437.13
  5201.9  439.96  5316.9  449.56  5391.9  457.31  5416.2  458.51  5546.9  460.12
#Mann= 3 ,-1 , 0
  4739.5     .16       0    4998     .07       0  5002.6     .16       0
Bank Sta=4998,5002.6
XS Rating Curve= 0 ,0
Exp/Cntr=0.3,0.1

Type RM Length L Ch R = 1 ,2267    ,519,519,519
BEGIN DESCRIPTION:
UNT0279 IN DUCK CR 7 0
END DESCRIPTION:
XS GIS Cut Line= 3
      3600613.82     10437183.57      3600993.58     10437209.61
      3601244.94     10437567.15
#Sta/Elev= 30
  4813.7  444.99  4857.8  440.96  4895.9  438.68  4932.3  436.79  4942.3  435.15
  4952.3  432.08  4962.3   430.8  4972.4  427.71  4998.7  416.85  4999.1  416.35
  5003.1  416.35  5003.4  416.85  5006.1  416.88  5022.5  431.28  5032.5  433.81
  5162.8  435.46  5172.8  436.38  5182.8   435.3  5258.3  436.86  5344.6  440.67
  5374.2  442.57  5395.1  442.94  5445.7  445.29  5490.1  448.78  5502.4  448.68
  5546.7  450.36  5567.6   450.1  5582.4  451.22  5618.2   451.2  5631.4  452.32
#Mann= 4 ,-1 , 0
  4813.7      .1       0  4895.9     .16       0  4998.7     .07       0
  5003.4     .16       0
Bank Sta=4998.7,5003.4
XS Rating Curve= 0 ,0
Exp/Cntr=0.3,0.1

Type RM Length L Ch R = 1 ,1748    ,394,394,394
BEGIN DESCRIPTION:
UNT0279 IN DUCK CR 6 0
END DESCRIPTION:
XS GIS Cut Line= 3
      3600459.73     10437461.36      3600742.11     10437791.64
      3600947.53     10437869.16
#Sta/Elev= 30
  4756.7  453.42  4760.6  453.43  4786.7  453.96  4815.2  452.29  4850.4  448.13
  4866.6  445.05  4877.6  442.76  4921.7  435.83  4964.6  430.82  4971.1  428.98
  4978.8  425.48  4993.1  416.59  4997.3  414.83  4997.7  414.33  5001.7  414.33
    5002  414.83    5007  416.53  5020.5  425.83  5023.1  426.13  5028.2  426.73
  5034.8  428.86  5085.3  430.01  5120.4  429.42  5133.8  430.52  5163.3  431.95
  5212.6  436.16  5244.7  437.81  5376.8  442.86  5401.7  444.64  5410.8  446.29
#Mann= 8 ,-1 , 0
  4756.7     .05       0  4760.6      .1       0  4866.6     .16       0
  4877.6      .1       0  4997.3     .07       0    5002      .1       0
  5023.1      .1       0  5133.8     .16       0
Bank Sta=4997.3,5002
XS Rating Curve= 0 ,0
Exp/Cntr=0.3,0.1

Type RM Length L Ch R = 1 ,1354    ,415,415,415
BEGIN DESCRIPTION:
UNT0279 IN DUCK CR 5 0
END DESCRIPTION:
XS GIS Cut Line= 2
      3600253.59     10437960.48       3600742.1     10437991.64
#Sta/Elev= 30
  4821.2  442.75  4829.7  443.03  4849.8  442.48  4869.8  440.26  4892.3  437.15
  4916.4  434.02  4921.4   434.1  4929.9  432.66    4950  430.54    4960  427.12
    4970   421.5    4980  417.69  4990.1  414.91  4997.7  411.46    4998  410.96
  5002.1  410.96  5002.5  411.46  5010.1  413.47  5020.1  418.32  5030.1  422.45
  5050.2  423.25  5070.1  425.01  5075.1  424.93  5080.2  425.39  5120.3  425.72
  5220.5   429.3  5233.9  429.99  5240.6  430.89  5260.6  432.16  5310.7  436.55
#Mann= 4 ,-1 , 0
  4821.2      .1       0  4892.3     .16       0  4997.7     .07       0
  5002.5     .16       0
Bank Sta=4997.7,5002.5
XS Rating Curve= 0 ,0
Exp/Cntr=0.3,0.1

Type RM Length L Ch R = 1 ,939     ,369,369,369
BEGIN DESCRIPTION:
UNT0279 IN DUCK CR 4 0
END DESCRIPTION:
XS GIS Cut Line= 3
      3600197.14     10438101.55       3600257.9     10438283.83
      3600600.77     10438485.65
#Sta/Elev= 30
  4723.9   435.8  4734.5  435.18  4766.2  430.52  4797.8  427.19  4816.1  425.78
  4871.7  424.02  4918.8  423.86  4924.2   423.1  4932.5  423.88  4945.6  421.49
  4955.5  418.34  4961.3  418.64  4967.3  416.81  4974.3  416.92  4976.9  416.96
    4991   410.1    4996  410.05  4996.3  409.55  5000.8  410.05  5004.2  410.77
  5013.8  417.39  5025.7  422.94  5035.5  423.22  5041.3  424.75  5084.2  427.74
    5137  429.23  5164.6  431.46  5187.8  431.46  5281.4   438.9  5313.9  439.62
#Mann= 6 ,-1 , 0
  4723.9      .1       0  4871.7     .16       0  4974.3      .1       0
    4991     .16       0    4996     .07       0  5000.8     .16       0
Bank Sta=4996,5000.8
XS Rating Curve= 0 ,0
Exp/Cntr=0.3,0.1

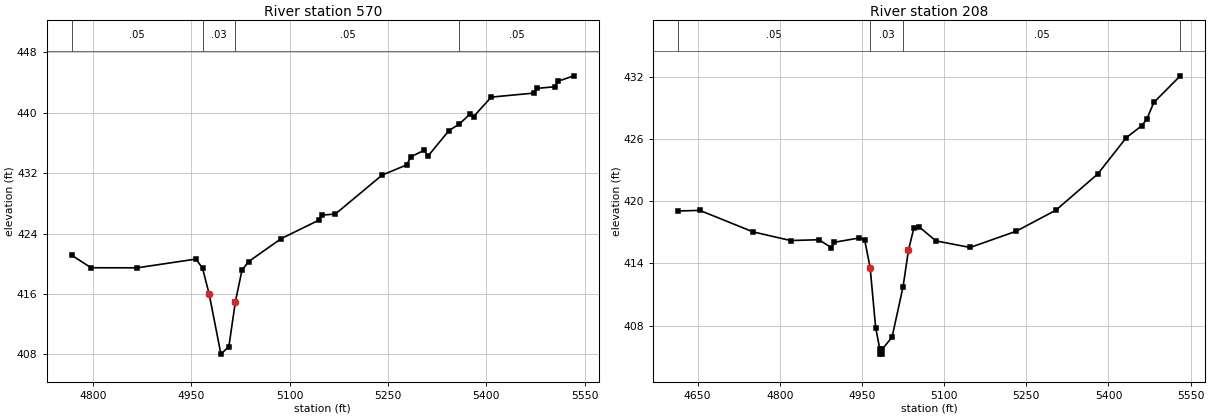
Type RM Length L Ch R = 1 ,570     ,362,362,362
BEGIN DESCRIPTION:
Mapping XS 6d7e45a7
END DESCRIPTION:
XS GIS Cut Line= 3
      3600027.87     10438212.22      3600014.85     10438585.48
      3600388.72     10438704.34
#Sta/Elev= 30
  4767.8  421.13  4797.2  419.48  4867.3  419.47  4957.3  420.63  4967.3  419.41
  4977.4  415.97  4995.3  408.04  5007.4  409.04  5017.4     415  5027.4  419.15
  5037.4  420.29  5087.4  423.35  5144.4  425.77  5149.6  426.45  5169.9   426.6
  5241.1  431.75  5278.6   433.1  5285.3  434.19  5305.6  435.05  5310.8  434.23
  5343.1  437.65  5358.8  438.51  5375.3  439.83  5380.6  439.49  5407.6  442.08
  5472.1  442.61  5477.3  443.24  5504.3  443.45  5509.6  444.19  5533.6   444.9
#Mann= 4 ,-1 , 0
  4767.8     .05       0  4967.3     .03       0  5017.4     .05       0
  5358.8     .05       0
Bank Sta=4977.4,5017.4
XS Rating Curve= 0 ,0
Exp/Cntr=0.3,0.1

Type RM Length L Ch R = 1 ,208     ,0,0,0
BEGIN DESCRIPTION:
UNT0279 IN DUCK CR 1 0
END DESCRIPTION:
XS GIS Cut Line= 4
       3599960.6     10438299.02      3599698.01     10438420.55
      3599698.01      10438635.4      3600066.96     10438819.87
#Sta/Elev= 30
  4614.5  419.08  4653.9  419.14  4751.1  417.06  4819.9  416.22  4871.3   416.3
  4894.2  415.53  4899.2  416.05  4944.9  416.47  4954.9  416.28  4964.9   413.6
  4974.9   407.8  4982.5  405.73  4982.9  405.23    4987  405.23  4987.4  405.73
  5004.9  406.88  5024.9  411.72  5034.9   415.3  5044.9  417.47  5054.9  417.52
  5084.9  416.19  5147.5  415.55  5231.4  417.12  5304.1  419.16  5380.4  422.66
  5432.6  426.18  5460.6  427.32  5469.9  427.95  5482.9  429.59  5531.2  432.16
#Mann= 4 ,-1 , 0
  4614.5     .05       0  4964.9     .03       0  5024.9     .05       0
  5531.2     .05       0
Bank Sta=4964.9,5034.9
XS Rating Curve= 0 ,0
Exp/Cntr=0.3,0.1

Chan Stop Cuts=-1
Use User Specified Reach Order=0
Composite Channel Slope=5