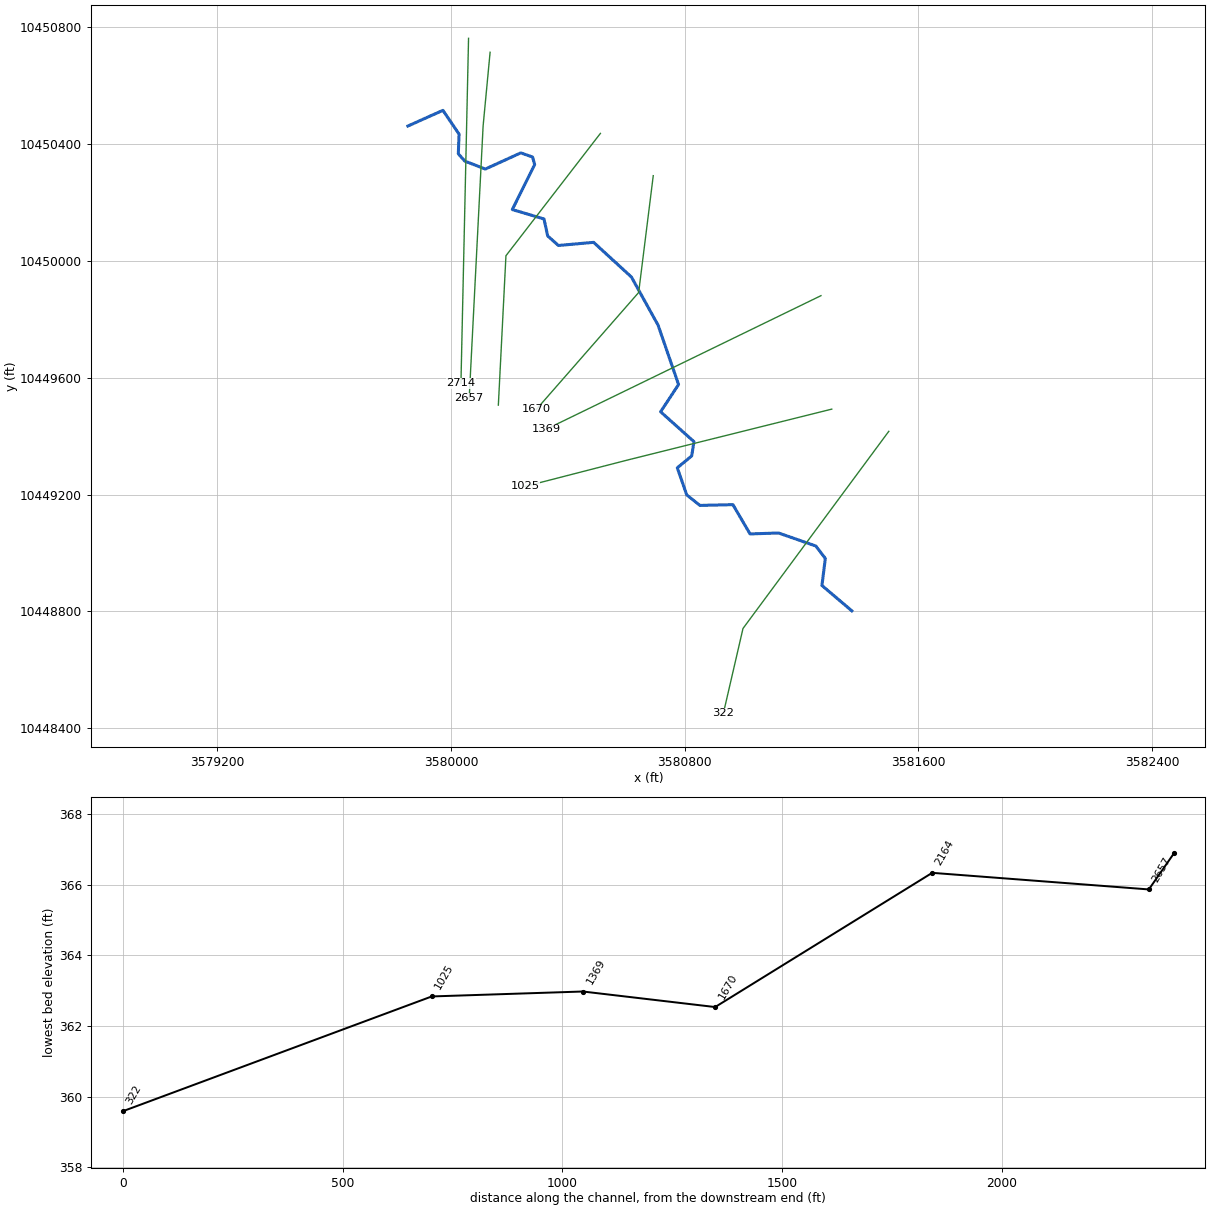
--- UNT0282 IN DUCK CR.prj (project) ---

Proj Title=UNT0282 IN DUCK CR Base Level Engineering
Current Plan=p01
Default Exp/Contr=0.3,0.1
English Units
Geom File=g01
Flow File=f01
Plan File=p01
BEGIN DESCRIPTION:
UNT0282 IN DUCK CR
END DESCRIPTION:

--- UNT0282 IN DUCK CR.p01 (plan) ---

Plan Title=Multiple Run
Short Identifier=Multiple
Geom File=g01
Flow File=f01
Subcritical Flow
K Sum by GR= 0
Std Step Tol= 0.01
Critical Tol= 0.01
Num of Std Step Trials= 20
Max Error Tol= 0.3
Flow Tol Ratio= 0.001
Split Flow NTrial= 30
Split Flow Tol= 0.02
Split Flow Ratio= 0.02
Log Output Level= 0
Friction Slope Method= 1
Unsteady Friction Slope Method= 2
Unsteady Bridges Friction Slope Method= 1
Parabolic Critical Depth
Global Vel Dist=  1 , 1 , 1
Global Log Level= 0
CheckData=True
Encroach Param= -1, 0, 0, 0
BEGIN DESCRIPTION:
Multiple Run
END DESCRIPTION:

--- UNT0282 IN DUCK CR.f01 (steady flow) ---

Flow Title=Multiple
Number of Profiles=7
Profile Names=10-year,25-year,50-year,1pct_min,100-year,1pct_plu,500-year
River Rch & RM= UNT0282 IN DUCK ,Reach-1,2714
    1226    1711    2116    1909    2582    3492    3835
Boundary for River Rch & Prof#=UNT0282 IN DUCK ,Reach-1,1
Up Type=0
Dn Type=3
Dn Slope=0.005
Boundary for River Rch & Prof#=UNT0282 IN DUCK ,Reach-1,2
Up Type=0
Dn Type=3
Dn Slope=0.005
Boundary for River Rch & Prof#=UNT0282 IN DUCK ,Reach-1,3
Up Type=0
Dn Type=3
Dn Slope=0.005
Boundary for River Rch & Prof#=UNT0282 IN DUCK ,Reach-1,4
Up Type=0
Dn Type=3
Dn Slope=0.005
Boundary for River Rch & Prof#=UNT0282 IN DUCK ,Reach-1,5
Up Type=0
Dn Type=3
Dn Slope=0.005
Boundary for River Rch & Prof#=UNT0282 IN DUCK ,Reach-1,6
Up Type=0
Dn Type=3
Dn Slope=0.005
Boundary for River Rch & Prof#=UNT0282 IN DUCK ,Reach-1,7
Up Type=0
Dn Type=3
Dn Slope=0.005

--- UNT0282 IN DUCK CR.g01 (geometry) ---

Geom Title=Existing Conditions

River Reach=UNT0282 IN DUCK ,Reach-1
Reach XY= 30
      3579852.11     10450461.64      3579971.98     10450515.23
      3580027.23     10450434.00      3580024.65     10450366.65
      3580046.75     10450341.68      3580117.12     10450314.29
      3580238.64     10450369.64      3580278.93     10450355.44
      3580286.07     10450329.62      3580209.57     10450175.61
      3580317.94     10450143.47      3580330.73     10450085.19
      3580367.37     10450052.65      3580488.00     10450063.35
      3580617.34     10449944.58      3580708.52     10449780.16
      3580778.72     10449576.50      3580717.25     10449483.29
      3580831.50     10449380.94      3580823.66     10449332.02
      3580774.44     10449291.43      3580806.73     10449198.54
      3580851.97     10449162.69      3580964.84     10449165.30
      3581023.47     10449065.07      3581121.07     10449068.27
      3581248.69     10449023.74      3581281.22     10448981.31
      3581269.62     10448888.55      3581372.11     10448801.64

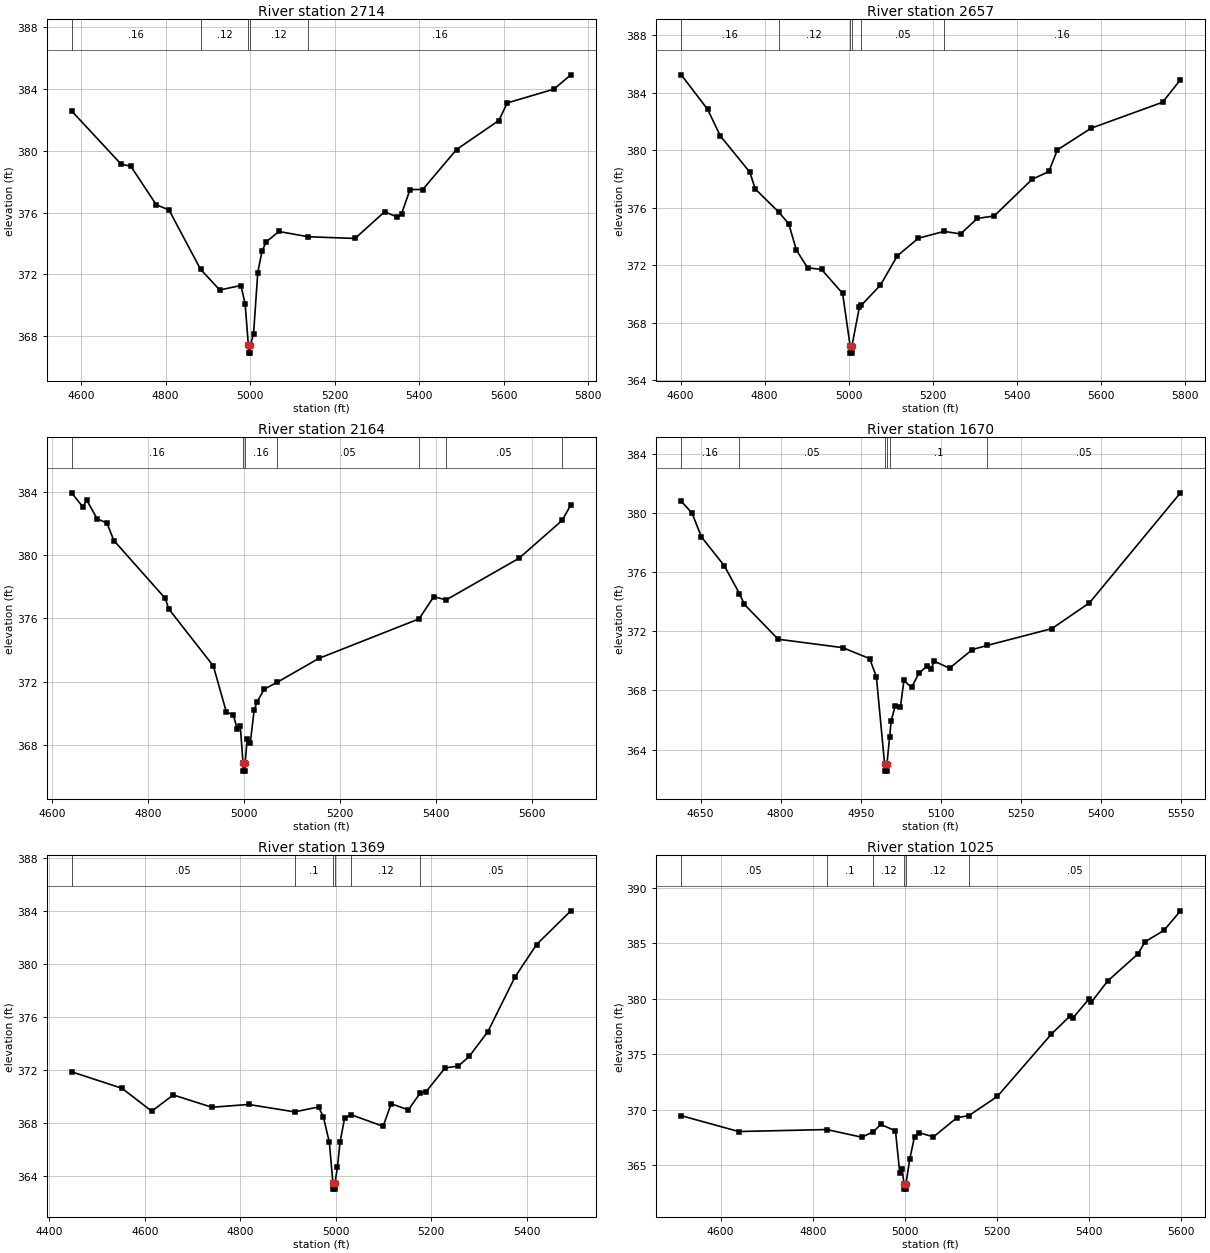
Type RM Length L Ch R = 1,2714,57,57,57
BEGIN DESCRIPTION:
UNT0282 IN DUCK CR 6 0
END DESCRIPTION:
XS GIS Cut Line= 2
      3580059.71     10450761.83      3580033.67     10449581.32
#Sta/Elev= 30
  4577.9  382.58  4694.6  379.14  4718.1  378.99  4778.1  376.50  4808.1  376.17
  4882.9  372.32  4928.2  370.98  4978.2  371.27  4988.2  370.10  4996.0  367.39
  4996.3  366.89  5000.0  366.89  5000.3  367.39  5008.2  368.15  5018.2  372.11
  5028.2  373.50  5038.2  374.10  5068.2  374.77  5137.4  374.43  5248.3  374.32
  5318.3  376.05  5348.3  375.70  5358.3  375.92  5378.3  377.49  5408.3  377.49
  5488.3  380.08  5588.3  381.96  5608.3  383.10  5718.4  383.99  5758.7  384.92
#Mann=5,-1,0
  4577.9    0.16       0  4882.9    0.12       0  4996.0    0.07       0
  5000.3    0.12       0  5137.4    0.16       0
Bank Sta=4996,5000.3
Exp/Cntr=0.3,0.1

Type RM Length L Ch R = 1,2657,493,493,493
BEGIN DESCRIPTION:
Mapping XS 5fb59af4
END DESCRIPTION:
XS GIS Cut Line= 3
      3580133.50     10450714.14      3580109.62     10450462.38
      3580061.88     10449529.19
#Sta/Elev= 30
  4601.6  385.25  4664.3  382.85  4694.5  381.00  4764.8  378.47  4777.6  377.30
  4833.2  375.70  4857.4  374.87  4875.3  373.06  4902.0  371.81  4935.3  371.70
  4985.4  370.03  5003.3  366.37  5003.5  365.87  5007.3  365.87  5007.6  366.37
  5025.4  369.08  5030.2  369.21  5075.5  370.61  5115.6  372.65  5165.6  373.87
  5227.1  374.35  5265.8  374.17  5305.8  375.25  5345.9  375.42  5436.0  377.97
  5476.0  378.52  5496.1  380.02  5576.2  381.53  5746.4  383.34  5788.9  384.91
#Mann=6,-1,0
  4601.6    0.16       0  4833.2    0.12       0  5003.3    0.07       0
  5007.6    0.12       0  5030.2    0.05       0  5227.1    0.16       0
Bank Sta=5003.3,5007.6
Exp/Cntr=0.3,0.1

Type RM Length L Ch R = 1,2164,494,494,494
BEGIN DESCRIPTION:
UNT0282 IN DUCK CR 5 0
END DESCRIPTION:
XS GIS Cut Line= 3
      3580511.10     10450436.34      3580187.75     10450017.50
      3580161.74     10449505.99
#Sta/Elev= 30
  4640.1  383.94  4664.0  383.03  4671.3  383.50  4693.0  382.31  4713.8  382.02
  4728.3  380.92  4835.5  377.26  4842.4  376.61  4935.7  372.99  4962.9  370.07
  4977.4  369.91  4985.5  368.99  4991.9  369.19  4997.6  366.84  4997.9  366.34
  5001.7  366.34  5002.0  366.84  5006.4  368.40  5012.7  368.11  5020.9  370.22
  5027.2  370.74  5041.7  371.52  5069.5  371.97  5155.8  373.47  5364.8  375.97
  5395.4  377.37  5421.3  377.17  5573.2  379.80  5663.4  382.20  5681.4  383.18
#Mann=7,-1,0
  4640.1    0.16       0  4997.6    0.07       0  5002.0    0.16       0
  5069.5    0.05       0  5364.8    0.16       0  5421.3    0.05       0
  5663.4    0.16       0
Bank Sta=4997.6,5002
Exp/Cntr=0.3,0.1

Type RM Length L Ch R = 1,1670,301,301,301
BEGIN DESCRIPTION:
UNT0282 IN DUCK CR 4 0
END DESCRIPTION:
XS GIS Cut Line= 3
      3580692.11     10450291.66      3580642.11     10449891.64
      3580292.13     10449491.67
#Sta/Elev= 30
  4613.8  380.79  4634.0  379.99  4651.6  378.38  4694.4  376.43  4722.7  374.55
  4732.2  373.81  4795.2  371.46  4916.2  370.89  4966.5  370.15  4979.1  368.93
  4994.5  363.04  4994.8  362.54  4998.7  362.54  4999.0  363.04  5004.0  364.88
  5006.9  365.95  5014.4  366.95  5024.1  366.87  5030.7  368.67  5044.9  368.20
  5059.2  369.18  5073.4  369.62  5081.0  369.42  5087.6  369.97  5116.1  369.50
  5158.8  370.76  5186.5  371.04  5307.8  372.18  5378.1  373.92  5548.4  381.36
#Mann=6,-1,0
  4613.8    0.16       0  4722.7    0.05       0  4994.5    0.03       0
  4999.0    0.05       0  5004.0     0.1       0  5186.5    0.05       0
Bank Sta=4994.5,4999
Exp/Cntr=0.3,0.1

Type RM Length L Ch R = 1,1369,344,344,344
BEGIN DESCRIPTION:
Mapping XS d777e8c8
END DESCRIPTION:
XS GIS Cut Line= 2
      3581266.34     10449880.80      3580325.81     10449423.53
#Sta/Elev= 30
  4446.6  371.85  4552.3  370.60  4614.4  368.87  4659.5  370.10  4740.4  369.17
  4817.4  369.38  4913.8  368.82  4963.8  369.19  4973.9  368.45  4986.4  366.53
  4993.9  363.48  4994.2  362.98  4998.1  362.98  4998.4  363.48  5003.4  364.63
  5008.9  366.53  5018.4  368.34  5031.6  368.61  5099.1  367.73  5116.1  369.44
  5151.8  368.97  5177.0  370.25  5189.4  370.36  5228.9  372.14  5257.0  372.29
  5279.6  373.02  5318.6  374.89  5375.3  379.01  5420.5  381.47  5492.4  384.02
#Mann=6,-1,0
  4446.6    0.05       0  4913.8     0.1       0  4993.9    0.07       0
  4998.4     0.1       0  5031.6    0.12       0  5177.0    0.05       0
Bank Sta=4993.9,4998.4
Exp/Cntr=0.3,0.1

Type RM Length L Ch R = 1,1025,703,703,703
BEGIN DESCRIPTION:
UNT0282 IN DUCK CR 3 0
END DESCRIPTION:
XS GIS Cut Line= 3
      3581303.25     10449492.34      3580606.59     10449318.71
      3580252.81     10449227.56
#Sta/Elev= 30
  4514.6  369.46  4639.4  368.03  4830.3  368.21  4906.3  367.52  4931.1  368.00
  4947.6  368.67  4979.5  368.09  4988.9  364.28  4994.0  364.66  4997.9  363.34
  4998.2  362.84  5002.1  362.84  5002.4  363.34  5010.5  365.55  5020.8  367.56
  5030.2  367.93  5062.0  367.55  5112.7  369.27  5138.9  369.47  5200.5  371.19
  5317.8  376.81  5358.5  378.45  5363.7  378.22  5399.2  379.97  5404.4  379.68
  5439.9  381.59  5505.7  384.04  5521.3  385.14  5562.0  386.15  5597.9  387.92
#Mann=6,-1,0
  4514.6    0.05       0  4830.3     0.1       0  4931.1    0.12       0
  4997.9    0.07       0  5002.4    0.12       0  5138.9    0.05       0
Bank Sta=4997.9,5002.4
Exp/Cntr=0.3,0.1

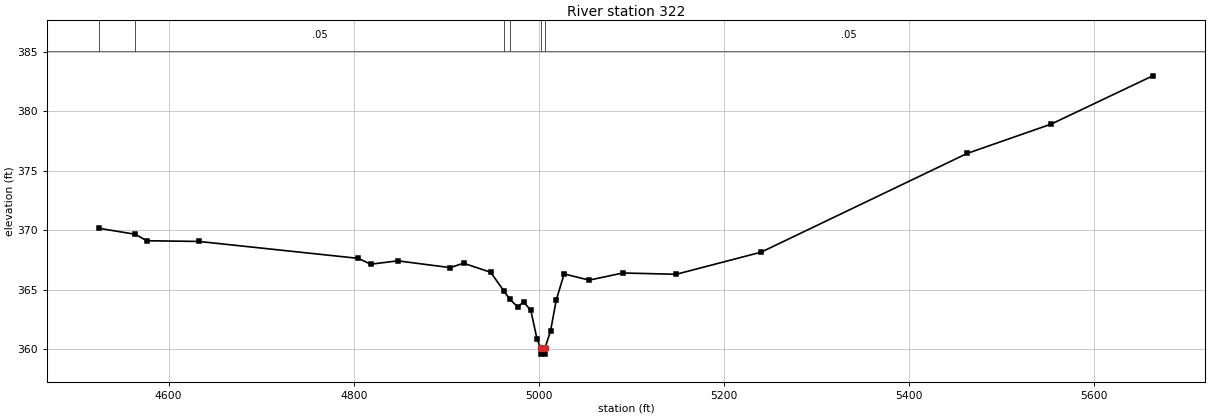
Type RM Length L Ch R = 1,322,0,0,0
BEGIN DESCRIPTION:
UNT0282 IN DUCK CR 1 0
END DESCRIPTION:
XS GIS Cut Line= 3
      3581498.52     10449416.39      3580999.38     10448741.46
      3580932.11     10448450.69
#Sta/Elev= 30
  4525.1  370.16  4564.1  369.66  4576.2  369.12  4632.6  369.06  4804.6  367.64
  4818.3  367.15  4847.6  367.43  4904.1  366.86  4918.5  367.23  4947.8  366.47
  4961.8  364.93  4968.3  364.22  4977.1  363.55  4983.3  363.99  4991.2  363.26
  4997.9  360.86  5001.8  360.09  5002.1  359.59  5006.1  359.59  5006.5  360.09
  5012.5  361.54  5018.7  364.15  5027.2  366.33  5054.2  365.81  5090.7  366.41
  5148.2  366.30  5240.0  368.16  5462.6  376.46  5553.2  378.92  5663.0  382.98
#Mann=6,-1,0
  4525.1    0.16       0  4564.1    0.05       0  4961.8    0.12       0
  4968.3    0.05       0  5001.8    0.03       0  5006.5    0.05       0
Bank Sta=5001.8,5006.5
Exp/Cntr=0.3,0.1

Chan Stop Cuts=-1