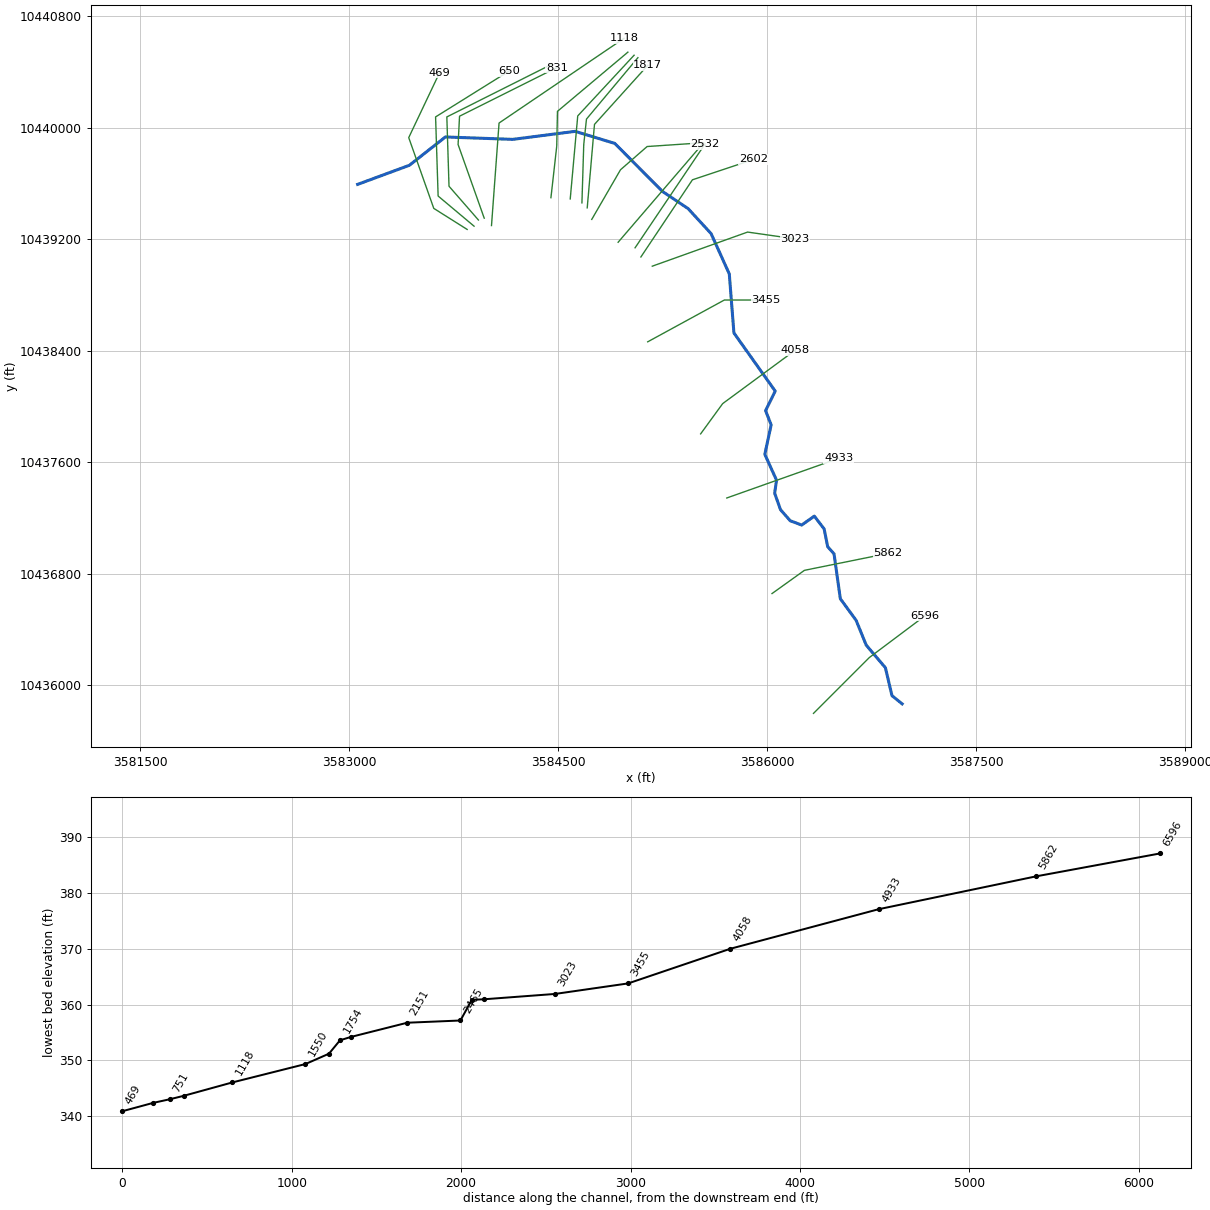
--- UNT0283 IN DUCK CR.prj (project) ---

Proj Title=UNT0283 IN DUCK CR Base Level Engineering
Current Plan=p01
Default Exp/Contr=0.3,0.1
English Units
Geom File=g01
Flow File=f01
Plan File=p01
BEGIN DESCRIPTION:
UNT0283 IN DUCK CR
END DESCRIPTION:

--- UNT0283 IN DUCK CR.p01 (plan) ---

Plan Title=Multiple Run
Short Identifier=Multiple
Geom File=g01
Flow File=f01
Subcritical Flow
K Sum by GR= 0
Std Step Tol= 0.01
Critical Tol= 0.01
Num of Std Step Trials= 20
Max Error Tol= 0.3
Flow Tol Ratio= 0.001
Split Flow NTrial= 30
Split Flow Tol= 0.02
Split Flow Ratio= 0.02
Log Output Level= 0
Friction Slope Method= 1
Unsteady Friction Slope Method= 2
Unsteady Bridges Friction Slope Method= 1
Parabolic Critical Depth
Global Vel Dist=  1 , 1 , 1
Global Log Level= 0
CheckData=True
Encroach Param= -1, 0, 0, 0
BEGIN DESCRIPTION:
Multiple Run
END DESCRIPTION:

--- UNT0283 IN DUCK CR.f01 (steady flow) ---

Flow Title=Multiple
Number of Profiles=7
Profile Names=10-year,25-year,50-year,1pct_min,100-year,1pct_plu,500-year
River Rch & RM= UNT0283 IN DUCK ,Reach-1,6596
    1824    2628    3326    3070    4152    5615    6454
Boundary for River Rch & Prof#=UNT0283 IN DUCK ,Reach-1,1
Up Type=0
Dn Type=3
Dn Slope=0.005
Boundary for River Rch & Prof#=UNT0283 IN DUCK ,Reach-1,2
Up Type=0
Dn Type=3
Dn Slope=0.005
Boundary for River Rch & Prof#=UNT0283 IN DUCK ,Reach-1,3
Up Type=0
Dn Type=3
Dn Slope=0.005
Boundary for River Rch & Prof#=UNT0283 IN DUCK ,Reach-1,4
Up Type=0
Dn Type=3
Dn Slope=0.005
Boundary for River Rch & Prof#=UNT0283 IN DUCK ,Reach-1,5
Up Type=0
Dn Type=3
Dn Slope=0.005
Boundary for River Rch & Prof#=UNT0283 IN DUCK ,Reach-1,6
Up Type=0
Dn Type=3
Dn Slope=0.005
Boundary for River Rch & Prof#=UNT0283 IN DUCK ,Reach-1,7
Up Type=0
Dn Type=3
Dn Slope=0.005

--- UNT0283 IN DUCK CR.g01 (geometry) ---

Geom Title=Existing Conditions

River Reach=UNT0283 IN DUCK ,Reach-1
Reach XY= 30
      3586969.19     10435865.55      3586896.29     10435924.07
      3586848.95     10436124.79      3586711.67     10436286.37
      3586638.96     10436464.55      3586525.53     10436620.01
      3586480.50     10436941.85      3586435.04     10436992.74
      3586409.52     10437120.54      3586338.96     10437212.65
      3586248.39     10437148.37      3586165.85     10437179.42
      3586096.42     10437258.64      3586054.19     10437377.42
      3586067.97     10437470.21      3585983.78     10437655.84
      3586029.26     10437867.29      3585989.13     10437969.28
      3586058.37     10438109.60      3585762.10     10438526.75
      3585728.87     10438950.30      3585598.38     10439239.50
      3585433.59     10439418.89      3585249.56     10439542.15
      3584907.20     10439886.77      3584622.85     10439973.40
      3584175.45     10439915.85      3583691.86     10439933.04
      3583433.35     10439729.82      3583062.04     10439592.84

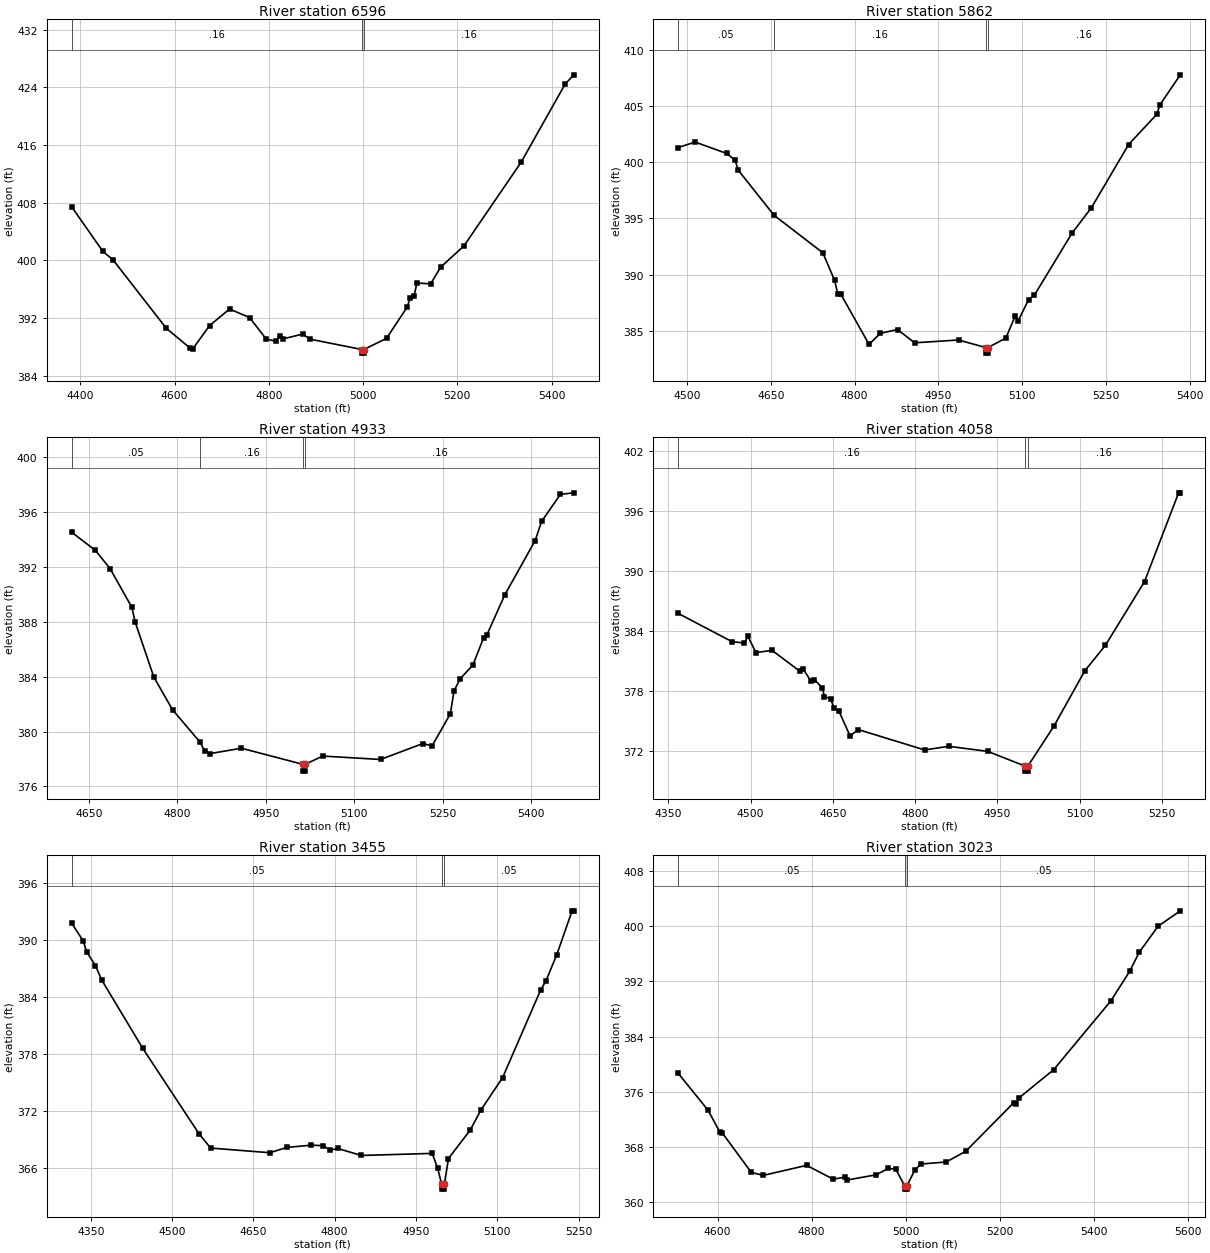
Type RM Length L Ch R = 1,6596,734,734,734
BEGIN DESCRIPTION:
UNT0283 IN DUCK CR 3 2
END DESCRIPTION:
XS GIS Cut Line= 3
      3586333.05     10435797.17      3586733.08     10436197.20
      3587132.73     10436496.94
#Sta/Elev= 30
  4382.0  407.40  4448.1  401.22  4469.4  400.07  4582.5  390.57  4632.0  387.88
  4639.1  387.74  4674.4  390.94  4716.8  393.24  4759.3  392.05  4794.6  389.07
  4815.8  388.77  4822.9  389.56  4830.0  389.09  4872.4  389.77  4886.5  389.07
  4997.8  387.62  4998.0  387.12  5001.5  387.12  5001.8  387.62  5049.8  389.17
  5093.5  393.49  5099.8  394.76  5108.1  395.02  5114.4  396.85  5143.5  396.73
  5164.4  399.02  5214.4  402.02  5335.2  413.58  5429.0  424.46  5447.3  425.73
#Mann=3,-1,0
  4382.0    0.16       0  4997.8    0.07       0  5001.8    0.16       0
Bank Sta=4997.8,5001.8
Exp/Cntr=0.3,0.1

Type RM Length L Ch R = 1,5862,929,929,929
BEGIN DESCRIPTION:
UNT0283 IN DUCK CR 3 1
END DESCRIPTION:
XS GIS Cut Line= 3
      3586035.49     10436656.90      3586268.16     10436823.59
      3586867.99     10436944.94
#Sta/Elev= 30
  4484.4  401.32  4514.6  401.81  4571.2  400.79  4585.9  400.20  4592.0  399.29
  4655.9  395.28  4743.1  391.94  4764.0  389.50  4770.0  388.26  4775.2  388.26
  4825.7  383.78  4846.1  384.77  4876.7  385.10  4907.3  383.92  4985.8  384.17
  5034.4  383.50  5034.7  383.00  5038.2  383.00  5038.5  383.50  5070.5  384.34
  5087.2  386.31  5092.3  385.86  5111.3  387.77  5121.5  388.16  5188.7  393.68
  5223.6  395.96  5290.1  401.59  5340.8  404.30  5346.0  405.12  5382.6  407.80
#Mann=4,-1,0
  4484.4    0.05       0  4655.9    0.16       0  5034.4    0.07       0
  5038.5    0.16       0
Bank Sta=5034.4,5038.5
Exp/Cntr=0.3,0.1

Type RM Length L Ch R = 1,4933,875,875,875
BEGIN DESCRIPTION:
UNT0283 IN DUCK CR 11 0
END DESCRIPTION:
XS GIS Cut Line= 2
      3585710.88     10437342.69      3586513.61     10437627.02
#Sta/Elev= 30
  4620.9  394.53  4661.0  393.21  4685.9  391.88  4722.8  389.06  4728.3  388.00
  4760.1  383.97  4791.9  381.58  4839.0  379.20  4846.3  378.57  4855.6  378.39
  4908.6  378.78  5012.6  377.61  5012.9  377.11  5016.6  377.11  5016.9  377.61
  5046.6  378.21  5144.6  377.96  5216.3  379.12  5232.0  378.95  5262.9  381.28
  5269.3  382.97  5279.9  383.86  5301.2  384.84  5319.3  386.82  5324.6  387.01
  5355.5  389.98  5406.7  393.91  5417.9  395.33  5449.7  397.30  5472.5  397.41
#Mann=4,-1,0
  4620.9    0.05       0  4839.0    0.16       0  5012.6    0.07       0
  5016.9    0.16       0
Bank Sta=5012.6,5016.9
Exp/Cntr=0.3,0.1

Type RM Length L Ch R = 1,4058,603,603,603
BEGIN DESCRIPTION:
UNT0283 IN DUCK CR 10 0
END DESCRIPTION:
XS GIS Cut Line= 3
      3585523.36     10437802.74      3585681.35     10438019.77
      3586202.15     10438403.42
#Sta/Elev= 30
  4368.2  385.79  4465.8  382.98  4488.9  382.82  4495.1  383.52  4509.8  381.87
  4539.1  382.10  4589.4  380.03  4595.6  380.26  4610.2  379.01  4616.4  379.17
  4631.1  378.35  4634.7  377.46  4646.0  377.28  4652.2  376.29  4660.7  376.08
  4681.5  373.53  4696.1  374.18  4817.3  372.14  4861.1  372.50  4932.2  372.00
  5000.7  370.52  5001.0  370.02  5005.2  370.02  5005.6  370.52  5053.3  374.54
  5109.6  380.07  5146.8  382.59  5218.3  388.98  5280.4  397.85  5283.5  397.85
#Mann=3,-1,0
  4368.2    0.16       0  5000.7    0.07       0  5005.6    0.16       0
Bank Sta=5000.7,5005.6
Exp/Cntr=0.3,0.1

Type RM Length L Ch R = 1,3455,432,432,432
BEGIN DESCRIPTION:
UNT0283 IN DUCK CR 9 0
END DESCRIPTION:
XS GIS Cut Line= 3
      3585143.47     10438463.16      3585693.49     10438763.17
      3585993.47     10438763.17
#Sta/Elev= 30
  4314.9  391.77  4336.1  389.92  4342.4  388.77  4358.6  387.33  4370.3  385.80
  4445.9  378.62  4549.4  369.66  4571.2  368.13  4680.4  367.64  4712.0  368.20
  4756.3  368.43  4778.1  368.39  4791.8  367.91  4805.7  368.09  4849.3  367.35
  4980.0  367.57  4990.0  366.02  4997.6  364.31  4997.9  363.81  5002.1  363.81
  5002.5  364.31  5010.0  367.03  5050.0  370.01  5070.0  372.14  5110.0  375.55
  5180.0  384.74  5190.0  385.73  5210.0  388.49  5238.2  393.09  5241.4  393.09
#Mann=3,-1,0
  4314.9    0.05       0  4997.6    0.03       0  5002.5    0.05       0
Bank Sta=4997.6,5002.5
Exp/Cntr=0.3,0.1

Type RM Length L Ch R = 1,3023,421,421,421
BEGIN DESCRIPTION:
Mapping XS 5b4bbf0a
END DESCRIPTION:
XS GIS Cut Line= 3
      3585176.18     10439005.89      3585860.17     10439250.67
      3586198.76     10439202.30
#Sta/Elev= 30
  4516.2  378.69  4579.4  373.36  4604.8  370.18  4610.1  370.04  4671.7  364.34
  4697.1  363.91  4789.4  365.36  4845.7  363.37  4871.1  363.65  4876.4  363.25
  4938.0  364.00  4963.4  364.93  4979.2  364.79  4998.0  362.42  4998.3  361.92
  5002.5  361.92  5002.9  362.42  5019.7  364.67  5032.3  365.55  5086.5  365.85
  5127.9  367.39  5229.8  374.40  5235.1  374.27  5241.0  375.10  5315.3  379.22
  5436.6  389.15  5477.0  393.45  5497.2  396.21  5537.6  399.99  5584.7  402.21
#Mann=3,-1,0
  4516.2    0.05       0  4998.0    0.03       0  5002.9    0.05       0
Bank Sta=4998,5002.9
Exp/Cntr=0.3,0.1

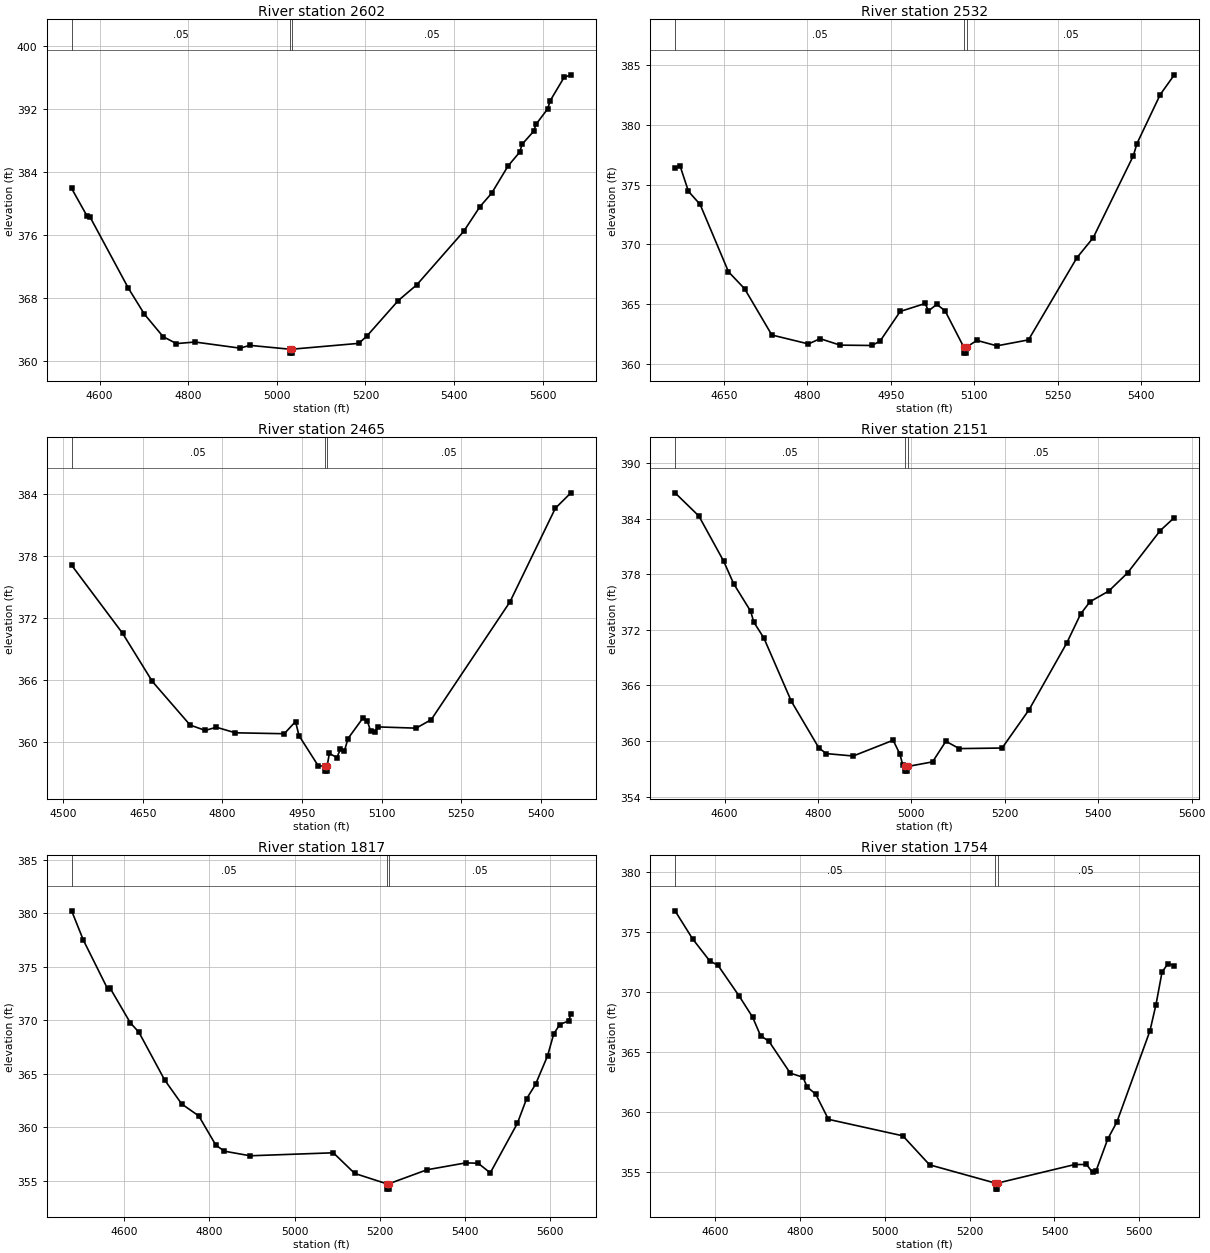
Type RM Length L Ch R = 1,2602,70,70,70
BEGIN DESCRIPTION:
UNT0283 IN DUCK CR 4 1
END DESCRIPTION:
XS GIS Cut Line= 3
      3585094.55     10439071.85      3585464.34     10439625.67
      3585901.85     10439771.50
#Sta/Elev= 30
  4536.9  381.88  4572.1  378.34  4578.1  378.29  4665.2  369.19  4701.3  365.90
  4743.3  363.06  4773.4  362.17  4815.4  362.37  4917.5  361.59  4938.6  361.95
  5029.2  361.46  5029.5  360.96  5033.8  360.96  5034.2  361.46  5184.9  362.20
  5202.8  363.09  5274.3  367.64  5316.4  369.66  5421.8  376.42  5458.8  379.58
  5485.1  381.28  5522.1  384.74  5548.3  386.49  5553.7  387.49  5579.9  389.15
  5585.3  390.04  5611.6  392.00  5616.9  393.00  5648.5  395.99  5664.0  396.32
#Mann=3,-1,0
  4536.9    0.05       0  5029.2    0.03       0  5034.2    0.05       0
Bank Sta=5029.2,5034.2
Exp/Cntr=0.3,0.1

Type RM Length L Ch R = 1,2532,67,67,67
BEGIN DESCRIPTION:
Mapping XS 933682d4
END DESCRIPTION:
XS GIS Cut Line= 2
      3585052.86     10439137.79      3585554.64     10439882.64
#Sta/Elev= 30
  4562.0  376.36  4571.1  376.55  4586.1  374.43  4607.1  373.33  4658.1  367.69
  4687.2  366.26  4736.1  362.39  4802.0  361.64  4823.0  362.08  4859.0  361.54
  4916.3  361.51  4931.0  361.89  4967.0  364.36  5011.9  365.03  5017.9  364.41
  5032.9  364.96  5047.9  364.40  5081.4  361.37  5081.7  360.87  5086.0  360.87
  5086.4  361.37  5104.9  361.94  5140.9  361.48  5197.8  361.98  5284.8  368.86
  5314.2  370.54  5386.5  377.42  5392.7  378.41  5434.8  382.54  5460.1  384.19
#Mann=3,-1,0
  4562.0    0.05       0  5081.4    0.03       0  5086.4    0.05       0
Bank Sta=5081.4,5086.4
Exp/Cntr=0.3,0.1

Type RM Length L Ch R = 1,2465,314,314,314
BEGIN DESCRIPTION:
Mapping XS edc41911
END DESCRIPTION:
XS GIS Cut Line= 2
      3584931.34     10439177.74      3585544.19     10439891.28
#Sta/Elev= 30
  4515.8  377.09  4611.7  370.51  4667.7  365.85  4739.0  361.62  4767.5  361.10
  4788.4  361.41  4824.1  360.87  4916.4  360.78  4937.6  361.96  4944.2  360.59
  4980.4  357.67  4992.2  357.66  4992.5  357.16  4996.8  357.16  4997.2  357.66
  5001.3  358.88  5015.5  358.47  5022.1  359.28  5029.8  359.13  5036.4  360.31
  5064.9  362.32  5072.6  362.06  5079.2  361.01  5086.9  360.97  5093.4  361.44
  5164.8  361.32  5193.2  362.14  5341.5  373.54  5427.1  382.61  5456.4  384.10
#Mann=3,-1,0
  4515.8    0.05       0  4992.2    0.03       0  4997.2    0.05       0
Bank Sta=4992.2,4997.2
Exp/Cntr=0.3,0.1

Type RM Length L Ch R = 1,2151,334,334,334
BEGIN DESCRIPTION:
UNT0283 IN DUCK CR 3 0
END DESCRIPTION:
XS GIS Cut Line= 4
      3584742.08     10439341.60      3584948.31     10439697.81
      3585139.29     10439864.47      3585542.10     10439891.64
#Sta/Elev= 30
  4494.1  386.77  4545.1  384.27  4598.1  379.41  4619.7  376.96  4655.9  374.01
  4662.7  372.83  4684.3  371.11  4743.1  364.29  4801.9  359.27  4817.7  358.65
  4875.5  358.39  4961.0  360.09  4975.2  358.62  4981.8  357.39  4987.0  357.26
  4987.3  356.76  4991.6  356.76  4992.0  357.26  5045.4  357.76  5073.9  359.98
  5102.4  359.19  5194.2  359.25  5252.2  363.40  5332.4  370.55  5362.5  373.72
  5382.5  375.03  5422.6  376.18  5462.7  378.13  5532.8  382.70  5562.9  384.10
#Mann=3,-1,0
  4494.1    0.05       0  4987.0    0.03       0  4992.0    0.05       0
Bank Sta=4987,4992
Exp/Cntr=0.3,0.1

Type RM Length L Ch R = 1,1817,63,63,63
BEGIN DESCRIPTION:
UNT0283 IN DUCK CR 7 0
END DESCRIPTION:
XS GIS Cut Line= 4
      3584709.52     10439424.35      3584751.19     10439903.50
      3584761.60     10440023.29      3585143.88     10440447.17
#Sta/Elev= 30
  4476.6  380.24  4504.0  377.51  4561.7  372.89  4566.7  373.02  4614.4  369.76
  4634.5  368.88  4694.7  364.43  4734.9  362.17  4775.0  361.05  4815.2  358.31
  4835.2  357.75  4895.5  357.32  5090.9  357.60  5141.0  355.67  5216.2  354.70
  5216.5  354.20  5220.8  354.20  5221.2  354.70  5310.6  356.01  5402.5  356.66
  5430.9  356.62  5459.3  355.72  5522.9  360.36  5544.5  362.65  5565.5  364.00
  5593.9  366.68  5608.1  368.71  5622.3  369.60  5643.2  369.94  5648.6  370.56
#Mann=3,-1,0
  4476.6    0.05       0  5216.2    0.03       0  5221.2    0.05       0
Bank Sta=5216.2,5221.2
Exp/Cntr=0.3,0.1

Type RM Length L Ch R = 1,1754,65,65,65
BEGIN DESCRIPTION:
UNT0283 IN DUCK CR 6 0
END DESCRIPTION:
XS GIS Cut Line= 4
      3584671.54     10439460.21      3584684.56     10439879.06
      3584704.09     10440061.35      3585073.02     10440501.89
#Sta/Elev= 30
  4505.5  376.74  4546.9  374.41  4587.0  372.59  4607.0  372.20  4657.0  369.64
  4688.3  367.91  4707.0  366.37  4727.0  365.89  4777.1  363.25  4807.1  362.91
  4817.1  362.09  4837.1  361.51  4867.1  359.41  5042.5  358.04  5105.5  355.63
  5260.7  354.11  5261.1  353.61  5265.5  353.61  5265.8  354.11  5447.4  355.65
  5475.4  355.66  5489.7  355.00  5497.5  355.08  5525.7  357.79  5547.0  359.18
  5625.0  366.76  5639.3  368.95  5653.6  371.66  5667.9  372.36  5682.5  372.17
#Mann=3,-1,0
  4505.5    0.05       0  5260.7    0.03       0  5265.8    0.05       0
Bank Sta=5260.7,5265.8
Exp/Cntr=0.3,0.1

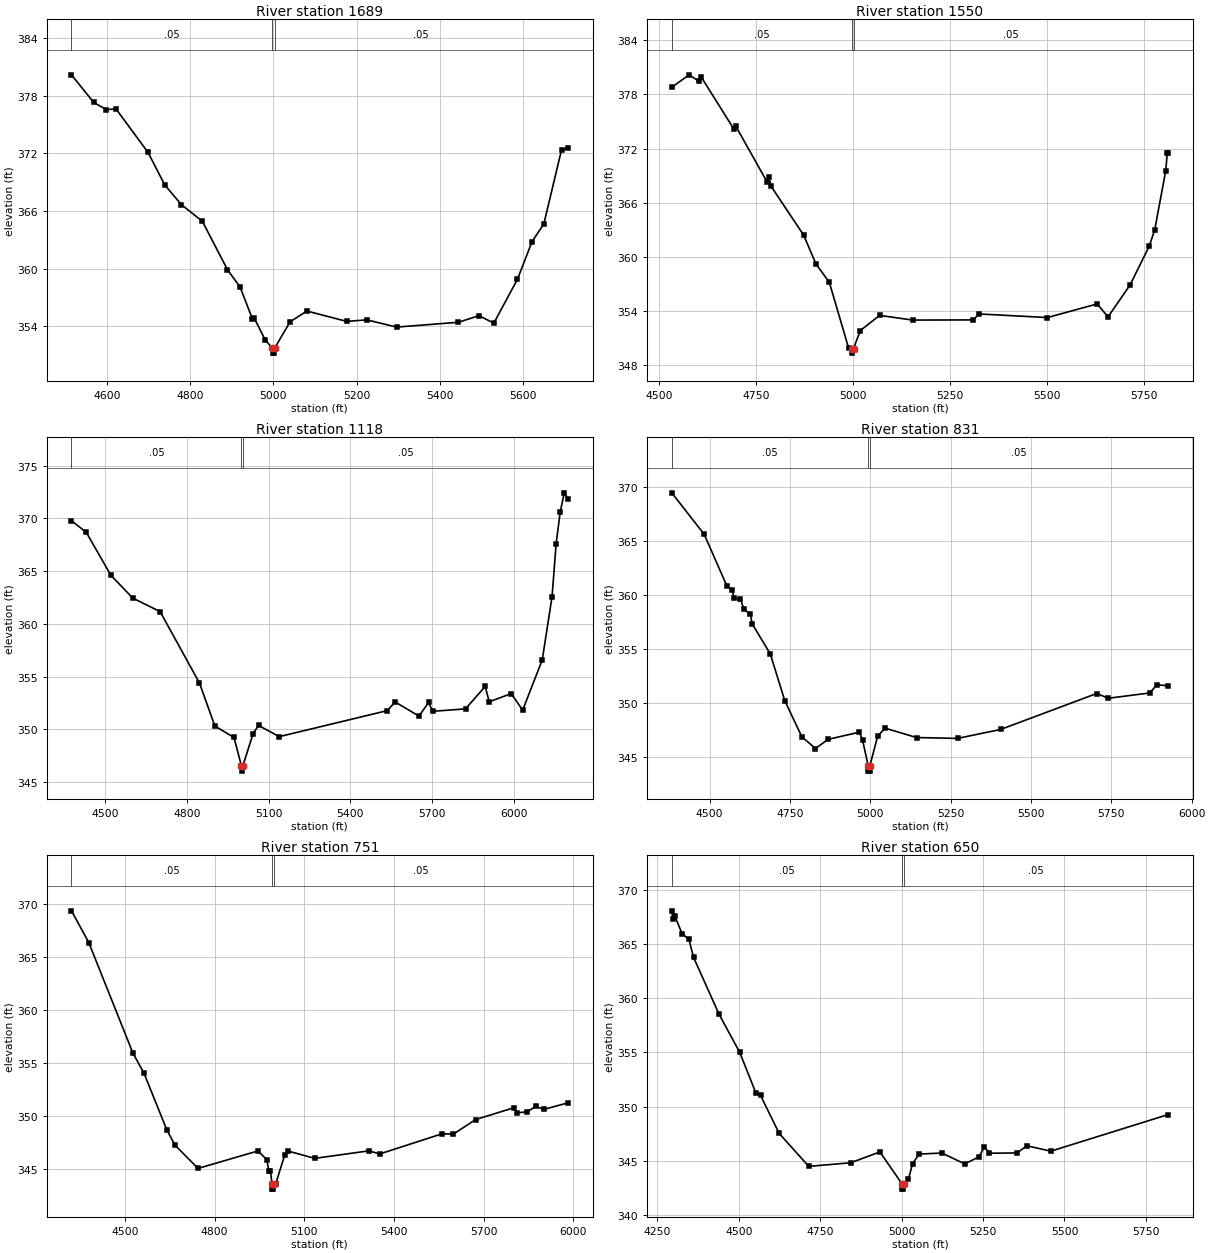
Type RM Length L Ch R = 1,1689,139,139,139
BEGIN DESCRIPTION:
Mapping XS 4052446e
END DESCRIPTION:
XS GIS Cut Line= 3
      3584587.60     10439488.49      3584641.42     10440084.00
      3585045.92     10440519.75
#Sta/Elev= 30
  4515.2  380.18  4568.6  377.30  4598.7  376.57  4622.3  376.62  4699.1  372.10
  4739.3  368.71  4779.4  366.66  4829.6  364.93  4889.9  359.89  4920.0  358.10
  4949.6  354.80  4954.6  354.82  4980.2  352.61  4997.8  351.71  4998.1  351.21
  5002.5  351.21  5002.9  351.71  5040.5  354.48  5080.7  355.59  5175.8  354.52
  5225.1  354.67  5296.0  353.92  5444.5  354.42  5493.9  355.11  5529.6  354.33
  5586.3  358.89  5621.4  362.81  5649.8  364.67  5692.3  372.38  5707.7  372.54
#Mann=3,-1,0
  4515.2    0.05       0  4997.8    0.03       0  5002.9    0.05       0
Bank Sta=4997.8,5002.9
Exp/Cntr=0.3,0.1

Type RM Length L Ch R = 1,1550,432,432,432
BEGIN DESCRIPTION:
UNT0283 IN DUCK CR 8 0
END DESCRIPTION:
XS GIS Cut Line= 4
      3584449.10     10439497.23      3584490.77     10439867.04
      3584495.98     10440117.04      3585001.21     10440541.54
#Sta/Elev= 30
  4531.8  378.79  4576.5  380.17  4602.5  379.44  4607.5  379.95  4692.4  374.14
  4697.4  374.46  4777.3  368.35  4782.4  368.90  4787.8  367.85  4872.3  362.42
  4903.8  359.25  4938.6  357.19  4988.6  349.89  4996.0  349.85  4996.4  349.35
  5001.1  349.85  5018.6  351.85  5068.6  353.53  5153.8  353.01  5310.5  353.03
  5324.8  353.69  5501.8  353.29  5630.5  354.80  5658.3  353.36  5715.1  356.89
  5764.5  361.17  5778.8  362.98  5807.4  369.55  5811.2  371.49  5813.9  371.49
#Mann=3,-1,0
  4531.8    0.05       0  4996.0    0.03       0  5001.1    0.05       0
Bank Sta=4996,5001.1
Exp/Cntr=0.3,0.1

Type RM Length L Ch R = 1,1118,287,287,287
BEGIN DESCRIPTION:
UNT0283 IN DUCK CR 2 0
END DESCRIPTION:
XS GIS Cut Line= 3
      3584022.67     10439297.49      3584076.92     10440033.14
      3584973.21     10440640.79
#Sta/Elev= 30
  4377.2  369.78  4431.5  368.68  4521.7  364.61  4602.0  362.45  4702.2  361.17
  4846.5  354.40  4902.8  350.33  4973.0  349.24  5000.4  346.55  5000.8  346.05
  5005.6  346.55  5043.2  349.61  5063.2  350.38  5139.1  349.32  5534.4  351.78
  5564.3  352.60  5651.2  351.27  5687.1  352.56  5701.0  351.72  5822.0  351.95
  5894.3  354.08  5908.8  352.62  5989.6  353.40  6031.6  351.83  6103.5  356.60
  6139.4  362.60  6154.4  367.62  6169.3  370.63  6184.3  372.43  6197.7  371.86
#Mann=3,-1,0
  4377.2    0.05       0  5000.4    0.03       0  5005.6    0.05       0
Bank Sta=5000.4,5005.6
Exp/Cntr=0.3,0.1

Type RM Length L Ch R = 1,831,80,80,80
BEGIN DESCRIPTION:
Mapping XS 8ad3884d
END DESCRIPTION:
XS GIS Cut Line= 4
      3583970.40     10439350.36      3583782.92     10439878.97
      3583793.33     10440082.09      3584491.29     10440431.07
#Sta/Elev= 30
  4382.6  369.50  4483.5  365.64  4553.7  360.87  4570.8  360.46  4576.1  359.69
  4596.2  359.65  4607.0  358.67  4627.2  358.23  4632.5  357.34  4689.0  354.54
  4734.1  350.20  4787.2  346.84  4829.6  345.75  4868.9  346.60  4966.2  347.27
  4976.2  346.52  4993.6  344.15  4994.0  343.65  4998.4  343.65  4998.8  344.15
  5023.3  346.92  5046.3  347.64  5144.1  346.77  5271.5  346.69  5405.6  347.52
  5704.5  350.86  5741.0  350.42  5869.6  350.91  5892.0  351.68  5927.2  351.57
#Mann=3,-1,0
  4382.6    0.05       0  4993.6    0.03       0  4998.8    0.05       0
Bank Sta=4993.6,4998.8
Exp/Cntr=0.3,0.1

Type RM Length L Ch R = 1,751,101,101,101
BEGIN DESCRIPTION:
UNT0283 IN DUCK CR 4 2
END DESCRIPTION:
XS GIS Cut Line= 4
      3583928.73     10439337.33      3583717.81     10439579.49
      3583702.19     10440076.88      3584454.79     10440454.49
#Sta/Elev= 30
  4321.6  369.38  4379.4  366.38  4527.4  355.90  4563.5  354.06  4640.8  348.64
  4667.6  347.22  4744.9  345.01  4945.0  346.66  4975.1  345.85  4981.9  344.73
  4986.9  344.78  4992.5  343.55  4992.9  343.05  4997.3  343.05  4997.7  343.55
  5005.1  343.58  5035.1  346.30  5045.1  346.66  5135.1  345.96  5316.0  346.67
  5352.9  346.38  5561.7  348.29  5599.0  348.26  5673.4  349.63  5800.4  350.74
  5813.0  350.28  5845.1  350.35  5874.4  350.87  5902.3  350.60  5982.4  351.21
#Mann=3,-1,0
  4321.6    0.05       0  4992.5    0.03       0  4997.7    0.05       0
Bank Sta=4992.5,4997.7
Exp/Cntr=0.3,0.1

Type RM Length L Ch R = 1,650,181,181,181
BEGIN DESCRIPTION:
UNT0283 IN DUCK CR 4 0
END DESCRIPTION:
XS GIS Cut Line= 4
      3583897.48     10439293.05      3583639.69     10439509.18
      3583621.46     10440076.88      3584147.33     10440404.90
#Sta/Elev= 30
  4294.4  368.05  4297.4  367.27  4304.0  367.54  4326.1  365.94  4346.9  365.42
  4361.2  363.76  4439.3  358.52  4503.0  354.99  4552.5  351.25  4566.8  351.03
  4624.0  347.52  4714.8  344.48  4843.4  344.81  4933.4  345.81  5000.9  342.88
  5001.3  342.38  5005.7  342.38  5006.1  342.88  5020.7  343.27  5033.5  344.72
  5053.5  345.61  5123.5  345.71  5193.6  344.71  5238.5  345.37  5253.8  346.30
  5269.2  345.69  5354.1  345.72  5384.8  346.38  5457.9  345.88  5818.6  349.26
#Mann=3,-1,0
  4294.4    0.05       0  5000.9    0.03       0  5006.1    0.05       0
Bank Sta=5000.9,5006.1
Exp/Cntr=0.3,0.1

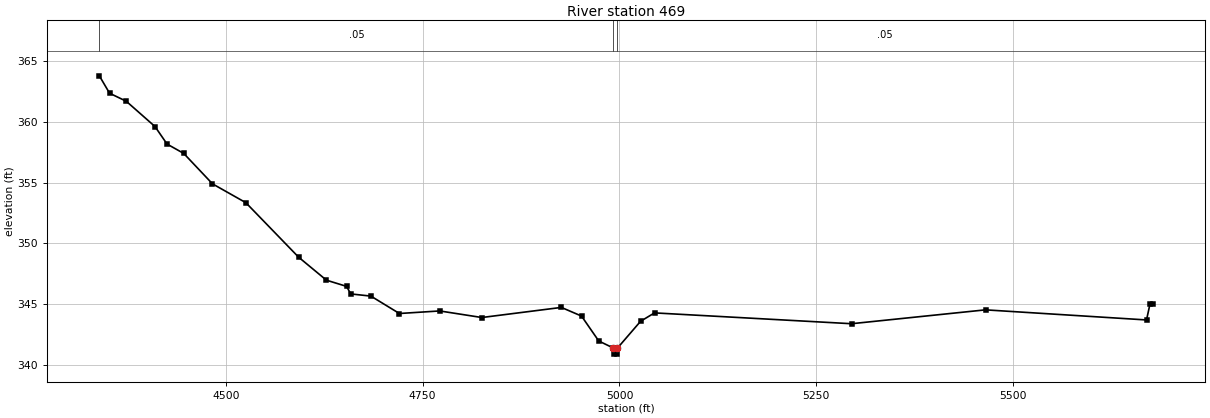
Type RM Length L Ch R = 1,469,0,0,0
BEGIN DESCRIPTION:
UNT0283 IN DUCK CR 3 3
END DESCRIPTION:
XS GIS Cut Line= 4
      3583848.01     10439269.60      3583608.44     10439420.63
      3583428.75     10439928.45      3583650.10     10440394.59
#Sta/Elev= 30
  4339.4  363.77  4352.4  362.34  4373.6  361.68  4410.1  359.60  4425.4  358.16
  4446.6  357.39  4483.1  354.89  4525.5  353.34  4592.5  348.86  4627.8  346.97
  4653.4  346.46  4658.7  345.84  4684.3  345.66  4720.5  344.23  4771.7  344.44
  4825.2  343.90  4926.2  344.73  4951.8  344.02  4973.7  341.97  4992.3  341.39
  4992.7  340.89  4997.1  340.89  4997.5  341.39  5026.8  343.59  5044.5  344.28
  5294.7  343.39  5464.9  344.53  5669.4  343.70  5673.8  345.01  5677.3  345.01
#Mann=3,-1,0
  4339.4    0.05       0  4992.3    0.03       0  4997.5    0.05       0
Bank Sta=4992.3,4997.5
Exp/Cntr=0.3,0.1

Chan Stop Cuts=-1