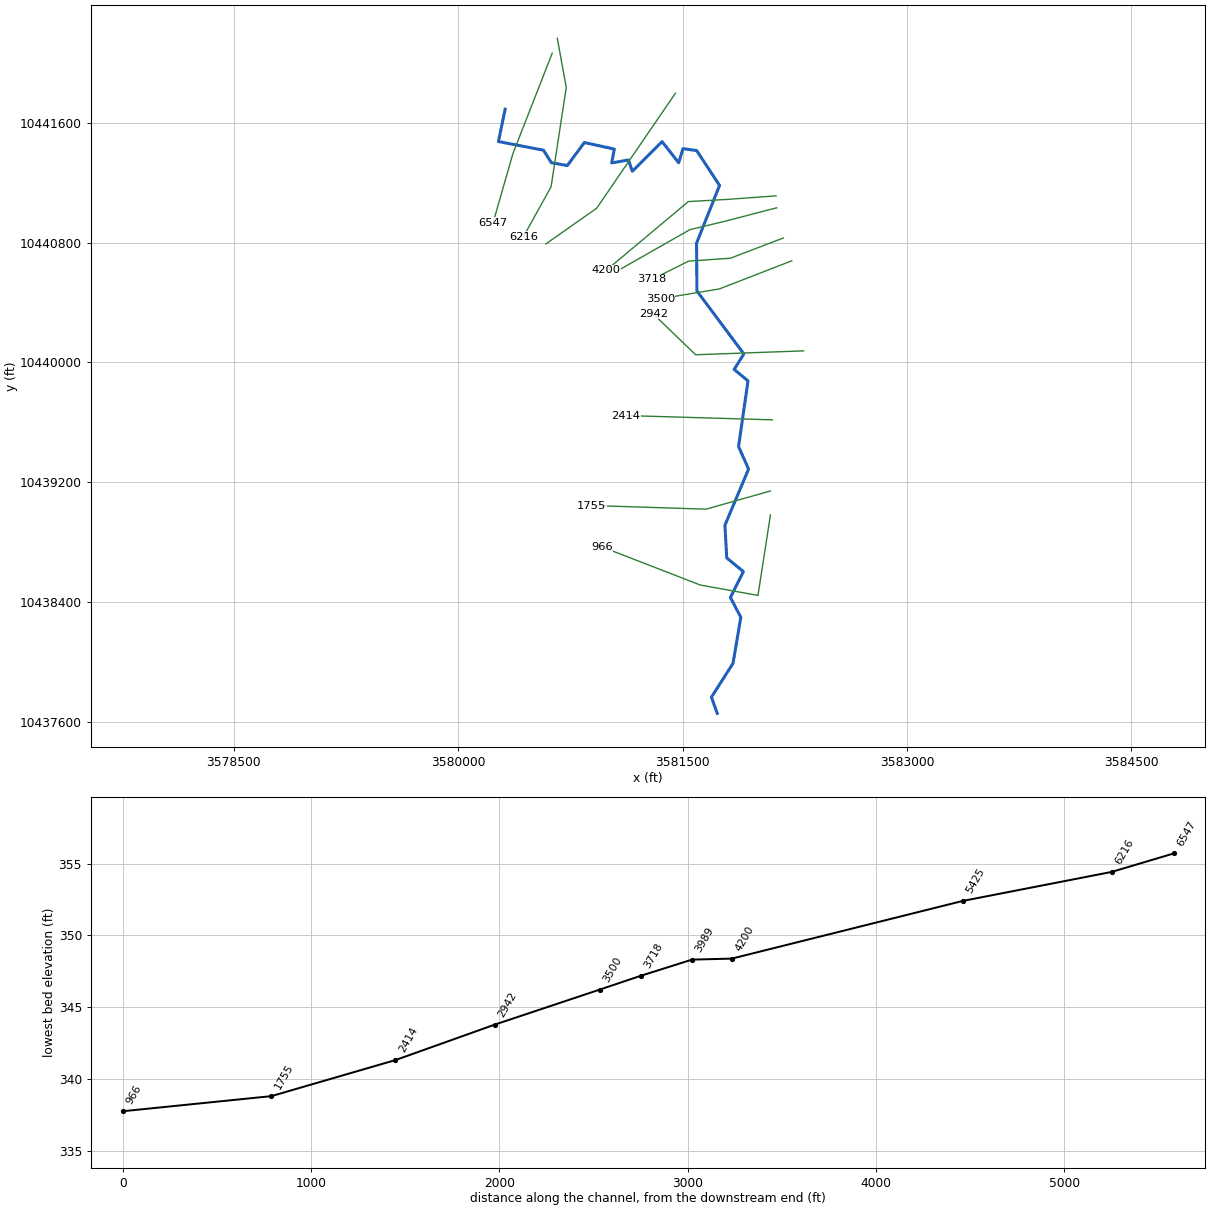
--- UNT0284 IN DUCK CR.prj (project) ---

Proj Title=UNT0284 IN DUCK CR Base Level Engineering
Current Plan=p01
Default Exp/Contr=0.3,0.1
English Units
Geom File=g01
Flow File=f01
Plan File=p01
BEGIN DESCRIPTION:
UNT0284 IN DUCK CR
END DESCRIPTION:

--- UNT0284 IN DUCK CR.p01 (plan) ---

Plan Title=Multiple Run
Short Identifier=Multiple
Geom File=g01
Flow File=f01
Subcritical Flow
K Sum by GR= 0
Std Step Tol= 0.01
Critical Tol= 0.01
Num of Std Step Trials= 20
Max Error Tol= 0.3
Flow Tol Ratio= 0.001
Split Flow NTrial= 30
Split Flow Tol= 0.02
Split Flow Ratio= 0.02
Log Output Level= 0
Friction Slope Method= 1
Unsteady Friction Slope Method= 2
Unsteady Bridges Friction Slope Method= 1
Parabolic Critical Depth
Global Vel Dist=  1 , 1 , 1
Global Log Level= 0
CheckData=True
Encroach Param= -1, 0, 0, 0
BEGIN DESCRIPTION:
Multiple Run
END DESCRIPTION:

--- UNT0284 IN DUCK CR.f01 (steady flow) ---

Flow Title=Multiple
Number of Profiles=7
Profile Names=10-year,25-year,50-year,1pct_min,100-year,1pct_plu,500-year
River Rch & RM= UNT0284 IN DUCK ,Reach-1,6547
    1017    1388    1690    1500    2029    2743    2916
Boundary for River Rch & Prof#=UNT0284 IN DUCK ,Reach-1,1
Up Type=0
Dn Type=3
Dn Slope=0.005
Boundary for River Rch & Prof#=UNT0284 IN DUCK ,Reach-1,2
Up Type=0
Dn Type=3
Dn Slope=0.005
Boundary for River Rch & Prof#=UNT0284 IN DUCK ,Reach-1,3
Up Type=0
Dn Type=3
Dn Slope=0.005
Boundary for River Rch & Prof#=UNT0284 IN DUCK ,Reach-1,4
Up Type=0
Dn Type=3
Dn Slope=0.005
Boundary for River Rch & Prof#=UNT0284 IN DUCK ,Reach-1,5
Up Type=0
Dn Type=3
Dn Slope=0.005
Boundary for River Rch & Prof#=UNT0284 IN DUCK ,Reach-1,6
Up Type=0
Dn Type=3
Dn Slope=0.005
Boundary for River Rch & Prof#=UNT0284 IN DUCK ,Reach-1,7
Up Type=0
Dn Type=3
Dn Slope=0.005

--- UNT0284 IN DUCK CR.g01 (geometry) ---

Geom Title=Existing Conditions

River Reach=UNT0284 IN DUCK ,Reach-1
Reach XY= 30
      3580314.47     10441691.81      3580269.87     10441475.66
      3580570.79     10441417.97      3580622.95     10441334.57
      3580729.97     10441315.32      3580844.18     10441469.33
      3581044.18     10441425.06      3581026.47     10441332.88
      3581138.97     10441352.67      3581164.49     10441277.15
      3581363.45     10441475.06      3581474.39     10441333.92
      3581503.03     10441428.19      3581594.70     10441415.17
      3581747.30     10441182.36      3581593.66     10440796.42
      3581596.22     10440476.93      3581909.85     10440056.48
      3581844.97     10439952.85      3581937.52     10439876.41
      3581874.43     10439437.39      3581941.20     10439286.78
      3581783.39     10438912.02      3581795.40     10438693.19
      3581906.94     10438601.43      3581819.79     10438429.56
      3581889.47     10438296.04      3581837.28     10437988.30
      3581693.05     10437762.63      3581731.85     10437654.30

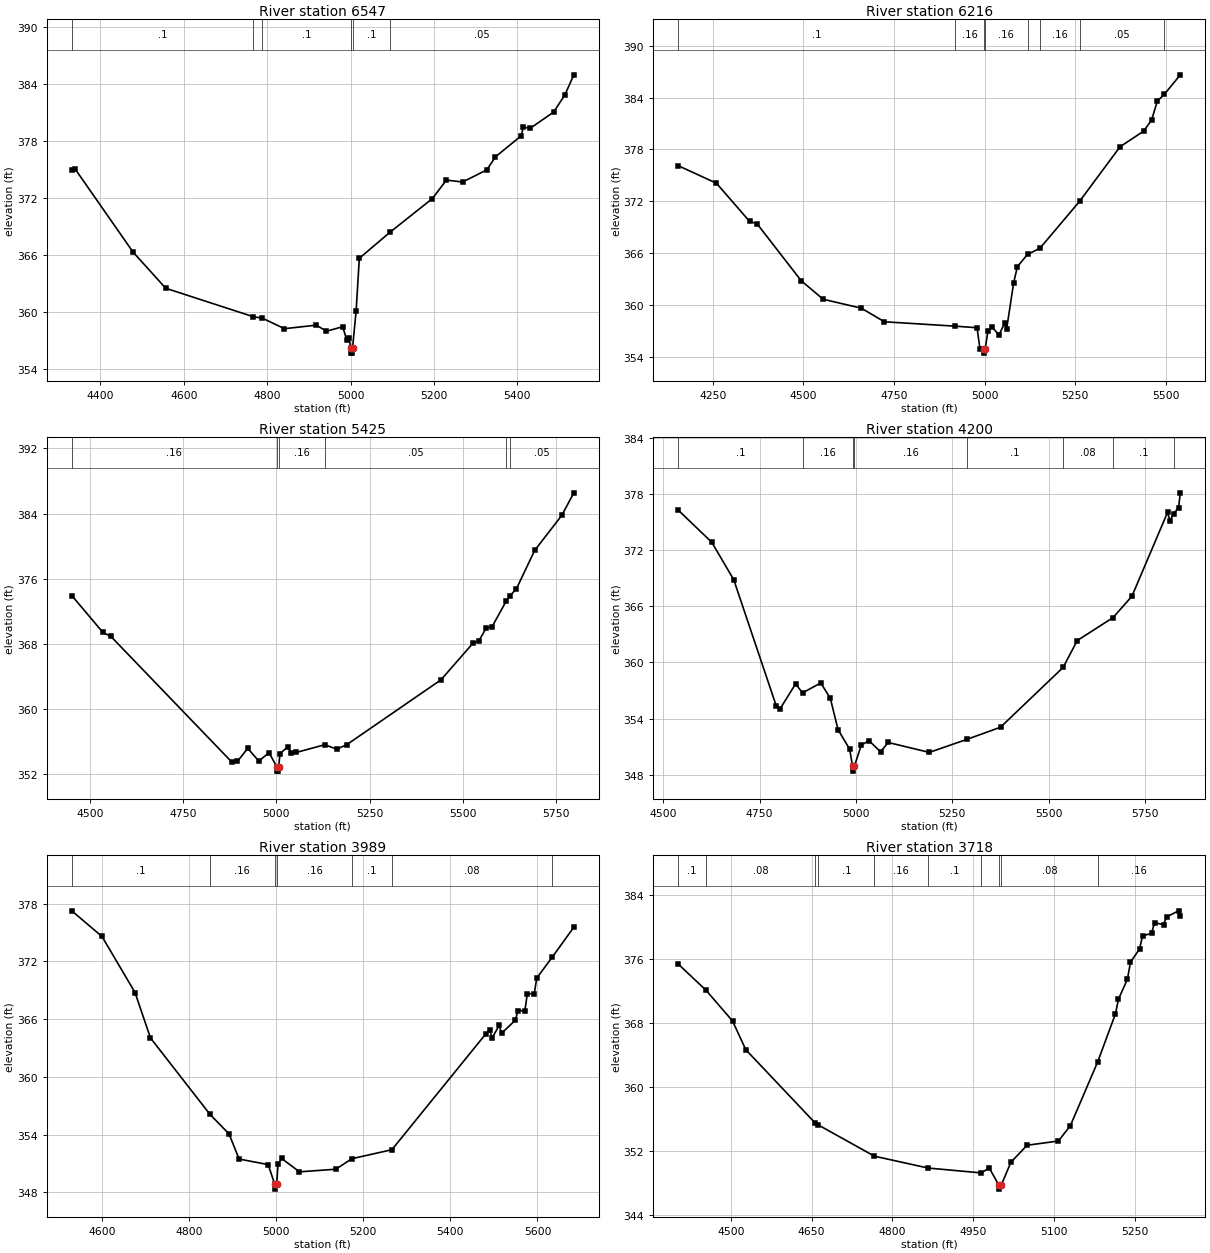
Type RM Length L Ch R = 1,6547,331,331,331
BEGIN DESCRIPTION:
UNT0284 IN DUCK CR 3 0
END DESCRIPTION:
XS GIS Cut Line= 3
      3580629.26     10442066.44      3580366.25     10441394.59
      3580233.44     10440931.04
#Sta/Elev= 30
  4331.6  375.00  4339.8  375.06  4478.2  366.35  4556.9  362.53  4766.7  359.54
  4788.8  359.38  4841.5  358.28  4917.8  358.65  4942.3  358.01  4981.1  358.49
  4991.2  357.05  4996.5  357.32  5000.4  356.21  5000.7  355.71  5004.4  355.71
  5004.7  356.21  5013.3  360.14  5021.0  365.68  5094.5  368.42  5195.9  371.95
  5229.7  373.90  5268.6  373.70  5326.6  374.98  5347.4  376.35  5408.9  378.55
  5414.1  379.47  5430.7  379.35  5486.8  381.05  5513.9  382.87  5535.3  384.97
#Mann=6,-1,0
  4331.6     0.1       0  4766.7    0.16       0  4788.8     0.1       0
  5000.4    0.07       0  5004.7     0.1       0  5094.5    0.05       0
Bank Sta=5000.4,5004.7
Exp/Cntr=0.3,0.1

Type RM Length L Ch R = 1,6216,791,791,791
BEGIN DESCRIPTION:
UNT0284 IN DUCK CR 2 0
END DESCRIPTION:
XS GIS Cut Line= 4
      3580663.12     10442165.45      3580723.02     10441837.30
      3580621.46     10441173.24      3580436.82     10440840.37
#Sta/Elev= 30
  4154.5  376.12  4260.0  374.09  4351.5  369.67  4371.8  369.41  4493.8  362.81
  4554.5  360.66  4660.1  359.62  4723.5  358.05  4919.3  357.54  4979.4  357.36
  4987.3  354.94  4997.5  354.92  4997.8  354.42  5001.8  354.92  5009.7  357.02
  5019.8  357.47  5040.1  356.53  5055.8  357.93  5060.9  357.17  5080.5  362.58
  5090.7  364.43  5118.7  365.85  5153.0  366.56  5263.1  372.03  5374.1  378.31
  5439.3  380.12  5461.1  381.40  5477.1  383.59  5496.2  384.37  5540.5  386.64
#Mann=8,-1,0
  4154.5     0.1       0  4919.3    0.16       0  4997.5    0.07       0
  5001.8    0.16       0  5118.7    0.05       0  5153.0    0.16       0
  5263.1    0.05       0  5496.2     0.1       0
Bank Sta=4997.5,5001.8
Exp/Cntr=0.3,0.1

Type RM Length L Ch R = 1,5425,1225,1225,1225
BEGIN DESCRIPTION:
UNT0284 IN DUCK CR 11 0
END DESCRIPTION:
XS GIS Cut Line= 3
      3581452.18     10441798.23      3580926.15     10441030.01
      3580586.09     10440791.19
#Sta/Elev= 30
  4451.3  373.95  4534.6  369.43  4556.2  368.93  4881.2  353.48  4895.6  353.60
  4923.2  355.19  4953.0  353.64  4980.4  354.66  5001.6  352.90  5001.9  352.40
  5005.7  352.40  5006.0  352.90  5009.9  354.56  5030.8  355.38  5039.7  354.66
  5053.2  354.69  5130.0  355.64  5162.2  355.09  5189.3  355.66  5441.4  363.60
  5527.6  368.11  5542.4  368.33  5563.4  370.00  5578.2  370.09  5616.1  373.23
  5626.6  373.93  5643.5  374.74  5692.8  379.48  5765.5  383.78  5797.9  386.55
#Mann=6,-1,0
  4451.3    0.16       0  5001.6    0.07       0  5006.0    0.16       0
  5130.0    0.05       0  5616.1     0.1       0  5626.6    0.05       0
Bank Sta=5001.6,5006
Exp/Cntr=0.3,0.1

Type RM Length L Ch R = 1,4200,211,211,211
BEGIN DESCRIPTION:
UNT0284 IN DUCK CR 10 0
END DESCRIPTION:
XS GIS Cut Line= 4
      3582125.72     10441112.74      3581788.88     10441088.43
      3581538.88     10441074.54      3580991.02     10440615.90
#Sta/Elev= 30
  4539.0  376.27  4625.8  372.85  4683.0  368.84  4793.3  355.36  4803.3  355.05
  4843.4  357.71  4861.5  356.75  4908.8  357.81  4933.6  356.17  4953.6  352.82
  4983.7  350.74  4991.4  348.89  4991.8  348.39  4995.9  348.89  5013.7  351.16
  5033.7  351.65  5063.8  350.46  5083.8  351.45  5190.4  350.39  5287.8  351.78
  5375.1  353.08  5537.6  359.47  5574.2  362.34  5667.0  364.79  5716.0  367.07
  5808.4  376.02  5815.0  375.13  5824.0  375.87  5837.1  376.54  5841.6  378.12
#Mann=8,-1,0
  4539.0     0.1       0  4861.5    0.16       0  4991.4    0.07       0
  4995.9    0.16       0  5287.8     0.1       0  5537.6    0.08       0
  5667.0     0.1       0  5824.0    0.08       0
Bank Sta=4991.4,4995.9
Exp/Cntr=0.3,0.1

Type RM Length L Ch R = 1,3989,271,271,271
BEGIN DESCRIPTION:
UNT0284 IN DUCK CR 6 0
END DESCRIPTION:
XS GIS Cut Line= 4
      3582129.11     10441032.87      3581781.94     10440942.60
      3581549.30     10440887.04      3581066.77     10440612.42
#Sta/Elev= 30
  4530.4  377.27  4599.8  374.60  4675.7  368.77  4711.1  364.05  4847.6  356.11
  4891.6  354.06  4914.7  351.45  4981.5  350.87  4996.6  348.82  4996.9  348.32
  5001.1  348.82  5004.0  350.91  5012.3  351.51  5053.4  350.12  5136.6  350.39
  5174.1  351.49  5265.6  352.42  5481.8  364.50  5490.3  364.88  5496.0  364.05
  5511.9  365.35  5517.6  364.53  5549.4  365.91  5555.1  366.90  5571.0  366.87
  5576.7  368.65  5592.6  368.65  5598.3  370.28  5633.6  372.43  5683.5  375.57
#Mann=7,-1,0
  4530.4     0.1       0  4847.6    0.16       0  4996.6    0.07       0
  5001.1    0.16       0  5174.1     0.1       0  5265.6    0.08       0
  5633.6     0.1       0
Bank Sta=4996.6,5001.1
Exp/Cntr=0.3,0.1

Type RM Length L Ch R = 1,3718,218,218,218
BEGIN DESCRIPTION:
UNT0284 IN DUCK CR 9 0
END DESCRIPTION:
XS GIS Cut Line= 4
      3582174.32     10440831.50      3581820.13     10440696.07
      3581539.96     10440676.46      3581296.46     10440554.03
#Sta/Elev= 30
  4402.3  375.37  4454.0  372.08  4503.1  368.25  4527.8  364.65  4655.9  355.53
  4662.2  355.24  4766.8  351.32  4866.4  349.84  4965.2  349.23  4980.0  349.85
  4997.8  347.70  4998.1  347.20  5002.3  347.70  5020.1  350.55  5050.2  352.69
  5108.4  353.22  5130.7  355.14  5181.4  363.12  5214.4  369.13  5220.0  370.97
  5236.7  373.48  5242.3  375.61  5259.1  377.24  5264.7  378.88  5281.4  379.22
  5287.0  380.54  5303.7  380.31  5309.3  381.26  5331.6  382.03  5334.9  381.44
#Mann=10,-1,0
  4402.3     0.1       0  4454.0    0.08       0  4655.9    0.12       0
  4662.2     0.1       0  4766.8    0.16       0  4866.4     0.1       0
  4965.2    0.08       0  4997.8    0.07       0  5002.3    0.08       0
  5181.4    0.16       0
Bank Sta=4997.8,5002.3
Exp/Cntr=0.3,0.1

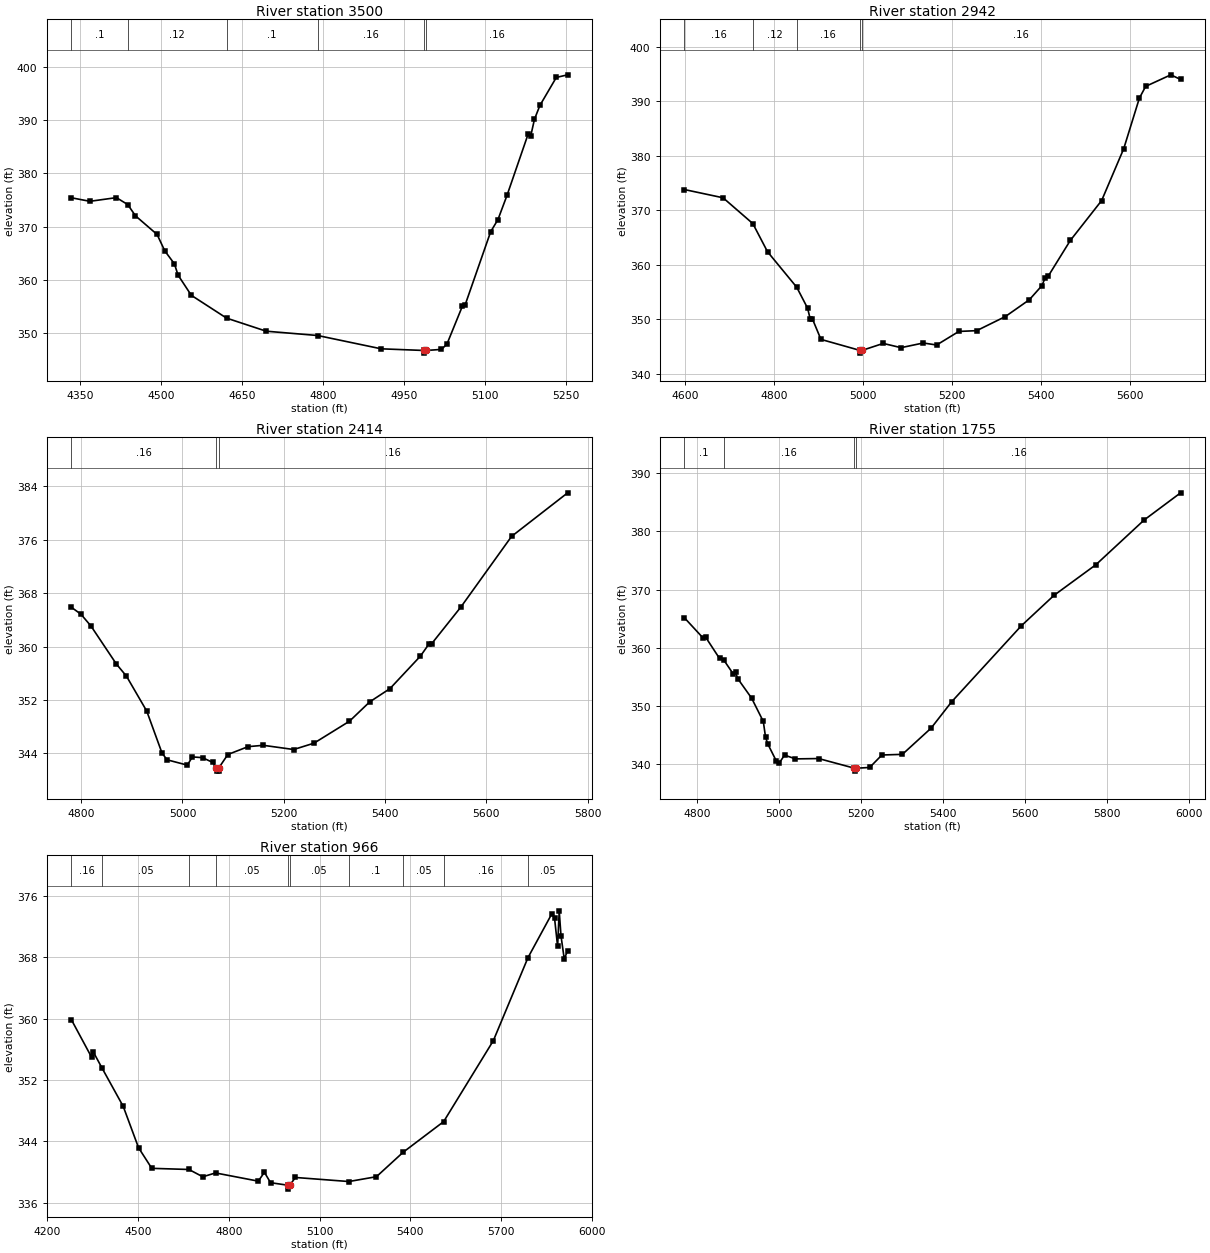
Type RM Length L Ch R = 1,3500,558,558,558
BEGIN DESCRIPTION:
UNT0284 IN DUCK CR 7 0
END DESCRIPTION:
XS GIS Cut Line= 3
      3582229.91     10440678.62      3581747.25     10440491.11
      3581351.41     10440425.14
#Sta/Elev= 30
  4333.9  375.42  4368.0  374.76  4417.1  375.45  4438.1  374.15  4452.4  372.04
  4492.5  368.53  4506.8  365.44  4524.6  363.01  4531.3  360.90  4555.9  357.10
  4621.1  352.82  4694.6  350.36  4789.9  349.55  4907.6  347.05  4986.4  346.74
  4986.8  346.24  4991.0  346.74  5019.1  346.94  5029.3  347.91  5058.0  355.06
  5063.1  355.30  5110.4  369.05  5123.9  371.33  5140.8  375.91  5179.6  387.33
  5184.7  387.08  5191.5  390.16  5201.6  392.77  5232.0  398.03  5253.0  398.52
#Mann=6,-1,0
  4333.9     0.1       0  4438.1    0.12       0  4621.1     0.1       0
  4789.9    0.16       0  4986.4    0.07       0  4991.0    0.16       0
Bank Sta=4986.4,4991
Exp/Cntr=0.3,0.1

Type RM Length L Ch R = 1,2942,528,528,528
BEGIN DESCRIPTION:
Mapping XS e564ee39
END DESCRIPTION:
XS GIS Cut Line= 3
      3582308.93     10440076.88      3581587.60     10440050.84
      3581303.77     10440324.26
#Sta/Elev= 30
  4598.5  373.80  4685.4  372.29  4752.4  367.55  4785.4  362.39  4851.1  355.88
  4875.5  352.04  4881.4  350.05  4886.4  350.06  4905.5  346.32  4993.3  344.30
  4993.6  343.80  4997.9  344.30  5045.6  345.58  5085.6  344.80  5135.7  345.66
  5165.7  345.29  5215.7  347.78  5255.8  347.92  5320.3  350.51  5374.2  353.59
  5402.5  356.18  5409.7  357.60  5416.7  357.92  5466.3  364.46  5536.8  371.78
  5586.5  381.30  5621.7  390.57  5635.8  392.72  5692.4  394.84  5714.4  393.99
#Mann=5,-1,0
  4598.5    0.16       0  4752.4    0.12       0  4851.1    0.16       0
  4993.3    0.07       0  4997.9    0.16       0
Bank Sta=4993.3,4997.9
Exp/Cntr=0.3,0.1

Type RM Length L Ch R = 1,2414,659,659,659
BEGIN DESCRIPTION:
UNT0284 IN DUCK CR 5 0
END DESCRIPTION:
XS GIS Cut Line= 2
      3582100.67     10439615.95      3581121.48     10439644.59
#Sta/Elev= 30
  4780.9  365.88  4799.5  364.86  4819.5  363.07  4869.5  357.39  4889.5  355.56
  4929.5  350.33  4959.5  344.07  4969.5  343.03  5009.6  342.23  5019.6  343.46
  5039.6  343.35  5059.6  342.64  5067.2  341.83  5067.6  341.33  5071.6  341.33
  5071.9  341.83  5089.6  343.82  5129.6  345.00  5159.6  345.20  5219.6  344.57
  5259.7  345.52  5329.7  348.81  5369.7  351.71  5409.7  353.70  5469.8  358.57
  5486.7  360.39  5491.7  360.40  5549.8  365.94  5649.8  376.52  5760.5  383.05
#Mann=3,-1,0
  4780.9    0.16       0  5067.2    0.07       0  5071.9    0.16       0
Bank Sta=5067.2,5071.9
Exp/Cntr=0.3,0.1

Type RM Length L Ch R = 1,1755,789,789,789
BEGIN DESCRIPTION:
UNT0284 IN DUCK CR 4 0
END DESCRIPTION:
XS GIS Cut Line= 3
      3582087.46     10439140.51      3581656.94     10439018.99
      3580893.06     10439043.29
#Sta/Elev= 30
  4768.2  365.15  4814.7  361.61  4819.9  361.83  4853.9  358.17  4864.1  357.92
  4887.9  355.46  4893.1  355.78  4898.4  354.70  4932.2  351.36  4960.8  347.35
  4966.2  344.69  4971.4  343.53  4992.0  340.64  5000.2  340.27  5012.7  341.57
  5039.4  340.92  5095.9  340.98  5183.4  339.32  5183.7  338.82  5188.2  339.32
  5220.5  339.45  5250.4  341.59  5300.4  341.70  5370.5  346.20  5420.5  350.71
  5590.6  363.76  5670.6  369.00  5773.2  374.28  5890.7  381.94  5979.8  386.61
#Mann=4,-1,0
  4768.2     0.1       0  4864.1    0.16       0  5183.4    0.07       0
  5188.2    0.16       0
Bank Sta=5183.4,5188.2
Exp/Cntr=0.3,0.1

Type RM Length L Ch R = 1,966,0,0,0
BEGIN DESCRIPTION:
UNT0284 IN DUCK CR 1 0
END DESCRIPTION:
XS GIS Cut Line= 4
      3582087.49     10438980.79      3582004.16     10438442.60
      3581618.74     10438512.04      3580961.55     10438766.89
#Sta/Elev= 30
  4279.4  359.83  4345.8  354.97  4350.9  355.70  4379.9  353.59  4450.6  348.55
  4501.2  343.17  4545.0  340.48  4667.9  340.33  4713.7  339.38  4755.8  339.88
  4897.2  338.81  4917.5  339.96  4937.9  338.61  4996.4  338.27  4996.8  337.77
  5001.2  338.27  5020.1  339.29  5196.9  338.76  5288.1  339.39  5376.5  342.58
  5510.4  346.57  5674.7  357.12  5789.3  367.94  5868.1  373.65  5877.0  373.14
  5887.3  369.40  5892.6  374.04  5898.5  370.77  5909.2  367.78  5920.5  368.84
#Mann=10,-1,0
  4279.4    0.16       0  4379.9    0.05       0  4667.9    0.16       0
  4755.8    0.05       0  4996.4   0.035       0  5001.2    0.05       0
  5196.9     0.1       0  5376.5    0.05       0  5510.4    0.16       0
  5789.3    0.05       0
Bank Sta=4996.4,5001.2
Exp/Cntr=0.3,0.1

Chan Stop Cuts=-1