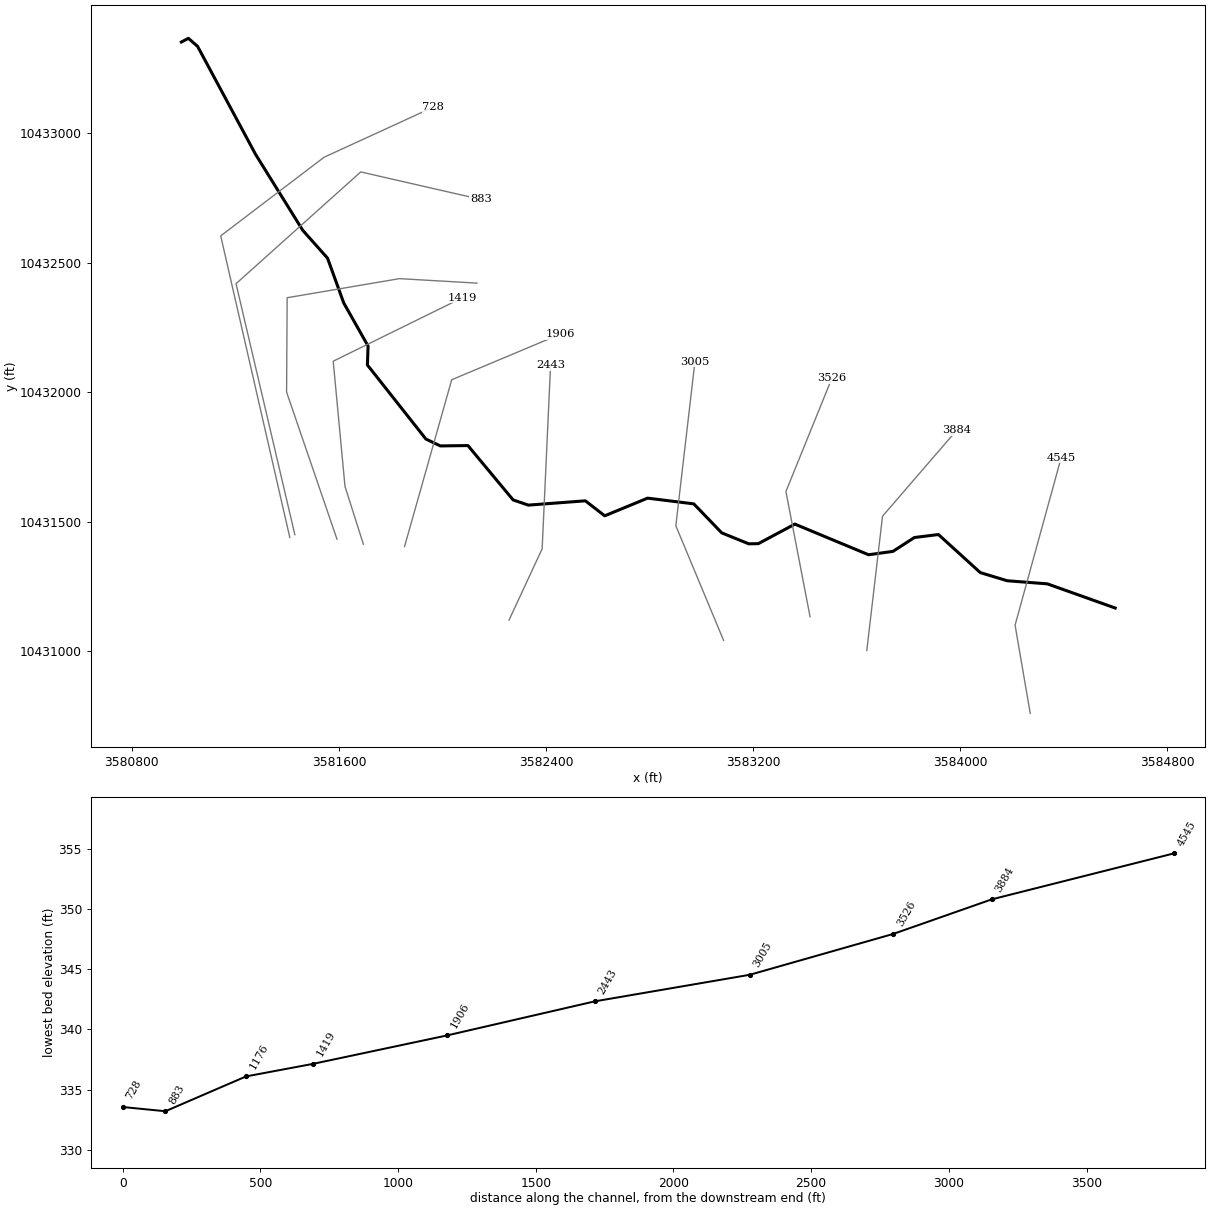
--- UNT0285 IN DUCK CR.prj (project) ---

Proj Title=UNT0285 IN DUCK CR Base Level Engineering
Current Plan=p01
Default Exp/Contr=0.3,0.1
English Units
Geom File=g01
Flow File=f01
Plan File=p01
Y Axis Title=Elevation
X Axis Title(PF)=Main Channel Distance
X Axis Title(XS)=Station
BEGIN DESCRIPTION:
UNT0285 IN DUCK CR
END DESCRIPTION:
DSS Export Rating Curves= 0
DSS Export Rating Curve Sorted= 0
DSS Export Volume Flow Curves= 0
DXF OffsetX= 0
DXF OffsetY= 0
DXF ScaleX= 1
DXF ScaleY= 10

--- UNT0285 IN DUCK CR.p01 (plan) ---

Plan Title=Multiple Run
Short Identifier=Multiple
Geom File=g01
Flow File=f01
Subcritical Flow
K Sum by GR= 0
Std Step Tol= 0.01
Critical Tol= 0.01
Num of Std Step Trials= 20
Max Error Tol= 0.3
Flow Tol Ratio= 0.001
Split Flow NTrial= 30
Split Flow Tol= 0.02
Split Flow Ratio= 0.02
Log Output Level= 0
Friction Slope Method= 1
Unsteady Friction Slope Method= 2
Unsteady Bridges Friction Slope Method= 1
Parabolic Critical Depth
Global Vel Dist=  1 , 1 , 1
Global Log Level= 0
CheckData=True
Encroach Param= -1, 0, 0, 0
BEGIN DESCRIPTION:
Multiple Run
END DESCRIPTION:

--- UNT0285 IN DUCK CR.f01 (steady flow) ---

Flow Title=Multiple
Program Version=4.10
Number of Profiles= 7
Profile Names=10-year,25-year,50-year,1pct_min,100-year,1pct_plu,500-year
River Rch & RM=UNT0285 IN DUCK,Reach-1         ,4545
    1684    2420    3056    2817    3810    5153    5905
Boundary for River Rch & Prof#=UNT0285 IN DUCK,Reach-1         , 1
Up Type= 0
Dn Type= 3
Dn Slope=0.01
Boundary for River Rch & Prof#=UNT0285 IN DUCK,Reach-1         , 2
Up Type= 0
Dn Type= 3
Dn Slope=0.01
Boundary for River Rch & Prof#=UNT0285 IN DUCK,Reach-1         , 3
Up Type= 0
Dn Type= 3
Dn Slope=0.01
Boundary for River Rch & Prof#=UNT0285 IN DUCK,Reach-1         , 4
Up Type= 0
Dn Type= 3
Dn Slope=0.01
Boundary for River Rch & Prof#=UNT0285 IN DUCK,Reach-1         , 5
Up Type= 0
Dn Type= 3
Dn Slope=0.01
Boundary for River Rch & Prof#=UNT0285 IN DUCK,Reach-1         , 6
Up Type= 0
Dn Type= 3
Dn Slope=0.01
Boundary for River Rch & Prof#=UNT0285 IN DUCK,Reach-1         , 7
Up Type= 0
Dn Type= 3
Dn Slope=0.01
DSS Import GetInterval= 0
DSS Import GetPeak= 0
DSS Import FillOption= 0

--- UNT0285 IN DUCK CR.g01 (geometry) ---

Geom Title=Existing Conditions
Program Version=4.10

River Reach=UNT0285 IN DUCK ,Reach-1
Reach XY= 30
      3584599.31     10431166.28      3584337.02     10431259.71
      3584182.11     10431271.64      3584078.06     10431303.13
      3583916.35     10431450.21      3583823.38     10431438.66
      3583740.65     10431385.11      3583646.45     10431372.07
      3583361.71     10431490.49      3583220.53     10431414.94
      3583183.56     10431414.36      3583079.17     10431456.58
      3582971.15     10431568.71      3582792.61     10431590.79
      3582627.03     10431522.54      3582552.15     10431580.47
      3582331.95     10431563.86      3582273.09      10431583.9
       3582098.4     10431793.97      3581991.86     10431792.56
      3581936.03      10431819.2      3581710.07     10432105.31
      3581712.64     10432178.51      3581618.63     10432344.92
      3581556.04     10432517.97       3581460.3      10432625.6
      3581277.84      10432919.3       3581054.1     10433336.12
      3581018.51     10433367.37      3580991.35     10433353.21

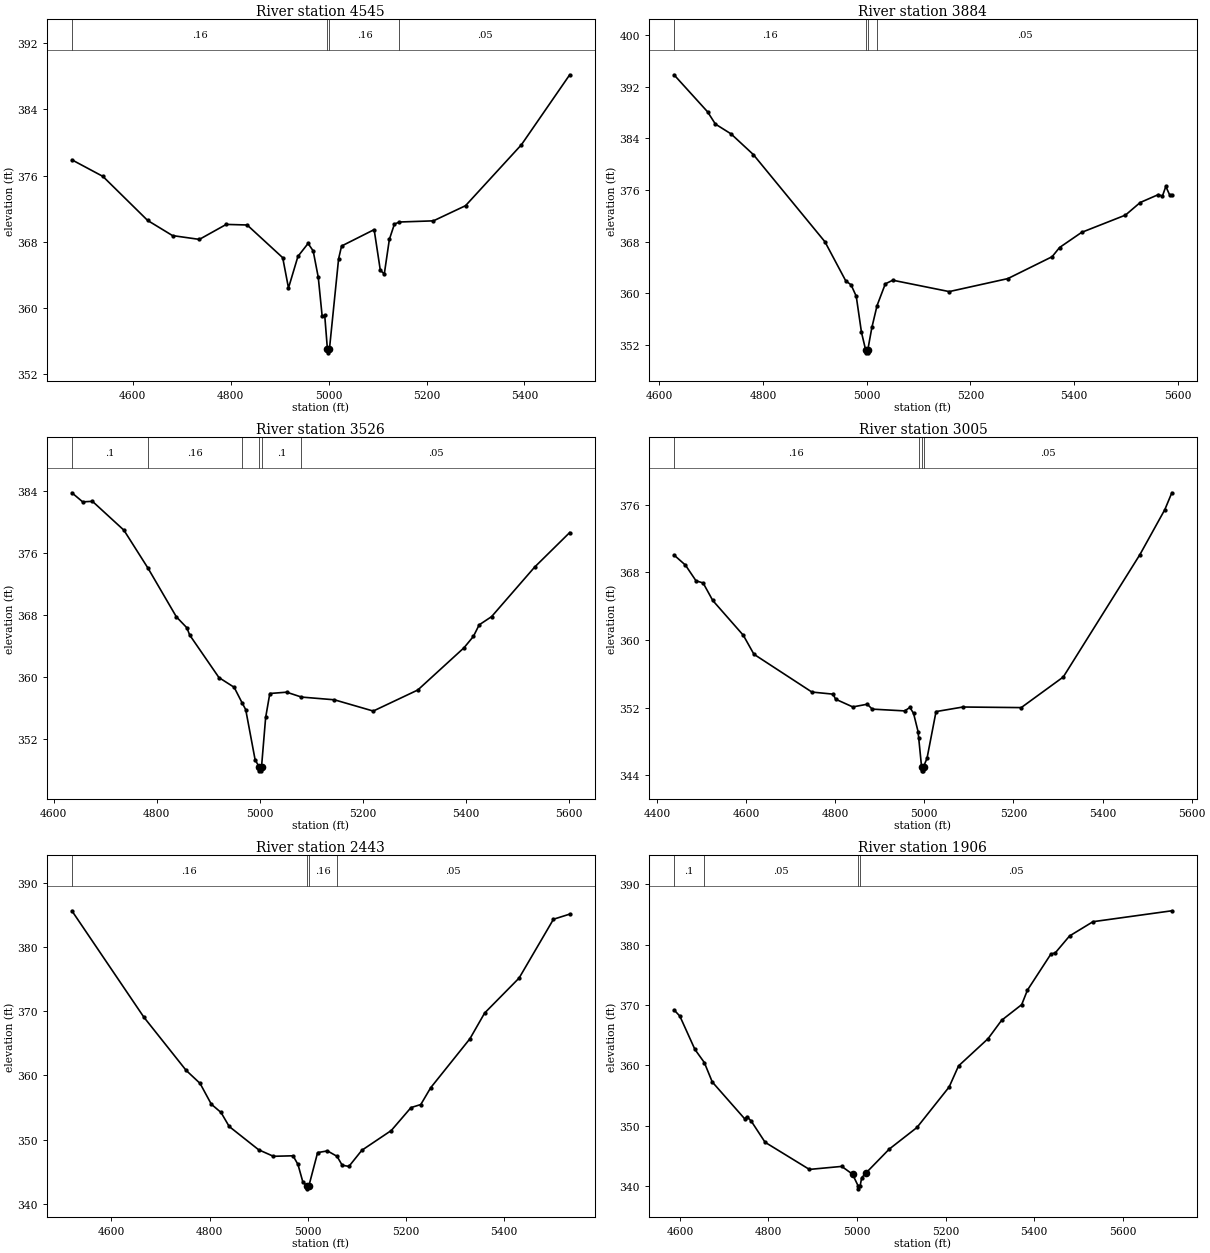
Type RM Length L Ch R = 1 ,4545    ,661,661,661
BEGIN DESCRIPTION:
UNT0285 IN DUCK CR 5 0
END DESCRIPTION:
XS GIS Cut Line= 3
      3584271.09     10430759.22      3584212.49     10431099.95
      3584390.45     10431746.68
#Sta/Elev= 30
  4475.9  377.91  4539.2  375.91  4630.6  370.59  4681.4  368.76  4736.2   368.3
  4791.1  370.11  4833.8  370.04  4906.4  366.09  4918.2  362.43  4937.5  366.25
  4958.2  367.81  4968.6  366.91    4979  363.72    4987  358.99  4992.2  359.11
  4997.6   355.1  4997.9   354.6  5001.9   355.1  5020.5  365.95  5026.6   367.5
  5093.1  369.48  5105.7  364.57  5113.8  364.12  5124.2  368.31  5134.5  370.15
  5144.7   370.4  5214.1  370.54  5279.7  372.37  5393.8  379.73  5492.4  388.18
#Mann= 4 ,-1 , 0
  4475.9     .16       0  4997.6     .07       0  5001.9     .16       0
  5144.7     .05       0
Bank Sta=4997.6,5001.9
XS Rating Curve= 0 ,0
Exp/Cntr=0.3,0.1

Type RM Length L Ch R = 1 ,3884    ,358,358,358
BEGIN DESCRIPTION:
UNT0285 IN DUCK CR 11 0
END DESCRIPTION:
XS GIS Cut Line= 3
      3583639.57      10431002.3      3583700.34     10431520.95
      3583986.78     10431852.96
#Sta/Elev= 30
  4628.1  393.83  4692.9   388.1    4708   386.2  4738.2  384.68  4781.1  381.49
  4919.4  367.98  4959.7  361.91  4969.8  361.32  4979.8  359.55  4989.9  353.96
  4997.8  351.29  4998.1  350.79  5001.9  350.79  5002.2  351.29    5010  354.73
    5020  358.11  5035.9  361.47  5050.3  362.03  5159.2  360.27  5272.3  362.28
  5357.8  365.67  5372.1  367.09  5414.8  369.44  5499.3  372.11  5527.8  374.06
    5563  375.29  5570.6  375.04  5577.2  376.55  5584.6  375.23  5588.8  375.23
#Mann= 4 ,-1 , 0
  4628.1     .16       0  4997.8     .07       0  5002.2     .16       0
    5020     .05       0
Bank Sta=4997.8,5002.2
XS Rating Curve= 0 ,0
Exp/Cntr=0.3,0.1

Type RM Length L Ch R = 1 ,3526    ,521,521,521
BEGIN DESCRIPTION:
Mapping XS c7b102b8
END DESCRIPTION:
XS GIS Cut Line= 3
      3583420.39     10431132.48      3583327.07     10431616.44
      3583505.03     10432054.82
#Sta/Elev= 30
  4635.6  383.73  4656.6  382.56  4675.5  382.63  4736.6  378.91  4783.5     374
  4838.4  367.75  4858.8  366.34  4864.1  365.42    4921  359.93  4950.5  358.68
  4966.1  356.65  4972.9  355.81  4991.2  349.33  4999.2  348.42  4999.5  347.92
  5003.3  347.92  5003.6  348.42  5011.6  354.79  5019.7  357.88  5052.3  358.05
  5081.1  357.42  5144.9  357.07  5220.4  355.62  5306.8  358.33  5396.5  363.77
  5414.7  365.23  5425.9  366.72    5450  367.78  5533.4  374.15  5601.6  378.61
#Mann= 6 ,-1 , 0
  4635.6      .1       0  4783.5     .16       0  4966.1      .1       0
  4999.2     .07       0  5003.6      .1       0  5081.1     .05       0
Bank Sta=4999.2,5003.6
XS Rating Curve= 0 ,0
Exp/Cntr=0.3,0.1

Type RM Length L Ch R = 1 ,3005    ,562,562,562
BEGIN DESCRIPTION:
UNT0285 IN DUCK CR 10 0
END DESCRIPTION:
XS GIS Cut Line= 3
      3583086.21     10431041.31      3582901.73     10431484.06
      3582975.45     10432117.23
#Sta/Elev= 30
  4438.4  370.06    4464  368.87  4487.8  367.01  4503.8  366.75  4525.4  364.68
    4594  360.56  4617.8  358.32  4747.8  353.85  4795.5   353.6  4800.9  353.01
  4839.6  352.09  4872.1  352.41  4883.2  351.83  4955.9  351.62  4967.8  352.03
    4976  351.32  4986.1  349.17  4987.6  348.37  4993.9  345.03  4994.3  344.53
  4998.1  344.53  4998.4  345.03  5006.2  346.02  5026.4  351.54  5086.8  352.08
  5217.6  352.01  5311.9  355.63  5483.9  370.11  5539.8  375.43  5555.5  377.42
#Mann= 4 ,-1 , 0
  4438.4     .16       0  4987.6     .05       0  4993.9     .03       0
  4998.4     .05       0
Bank Sta=4993.9,4998.4
XS Rating Curve= 0 ,0
Exp/Cntr=0.3,0.1

Type RM Length L Ch R = 1 ,2443    ,537,537,537
BEGIN DESCRIPTION:
UNT0285 IN DUCK CR 9 0
END DESCRIPTION:
XS GIS Cut Line= 3
      3582257.19     10431119.47      3582385.23     10431395.08
      3582417.78     10432104.73
#Sta/Elev= 30
  4519.5  385.66  4666.2  369.08  4752.3  360.79  4780.7  358.76  4803.6  355.52
  4823.4  354.23    4840  352.05    4900  348.42  4930.1   347.4  4970.1  347.48
  4980.1  346.14  4990.1   343.4  4997.9  342.83  4998.2  342.33  5002.5  342.83
  5020.2  347.98  5040.2  348.24  5059.7   347.4  5070.2  346.02  5083.9  345.82
  5110.3  348.34  5170.3  351.42  5210.4  354.99  5230.4  355.47  5250.4  358.07
  5330.5  365.72  5360.5  369.73  5430.6  375.17  5500.7  384.34  5533.8  385.14
#Mann= 4 ,-1 , 0
  4519.5     .16       0  4997.9     .07       0  5002.5     .16       0
  5059.7     .05       0
Bank Sta=4997.9,5002.5
XS Rating Curve= 0 ,0
Exp/Cntr=0.3,0.1

Type RM Length L Ch R = 1 ,1906    ,487,487,487
BEGIN DESCRIPTION:
UNT0285 IN DUCK CR 7 0
END DESCRIPTION:
XS GIS Cut Line= 3
      3581853.54     10431403.75      3582035.84      10432048.3
      3582454.71     10432224.09
#Sta/Elev= 30
  4586.7  369.17  4599.9  368.14  4633.9  362.62  4655.2  360.44  4673.1  357.22
  4746.2  351.12  4751.4  351.47  4761.2  350.72  4792.4  347.22  4892.4  342.72
  4965.5  343.22  4989.8  341.93  5002.4     340  5002.7   339.5    5007     340
  5010.6  341.36    5021  342.19  5072.6  346.08  5135.3  349.67    5208  356.39
  5229.2  359.88  5295.9   364.4  5326.4  367.44  5371.8  370.04  5384.8  372.45
  5437.7  378.42  5447.7  378.63  5479.8  381.42  5532.8  383.79  5710.8   385.6
#Mann= 4 ,-1 , 0
  4586.7      .1       0  4655.2     .05       0  5002.4     .03       0
    5007     .05       0
Bank Sta=4989.8,5021
XS Rating Curve= 0 ,0
Exp/Cntr=0.3,0.1

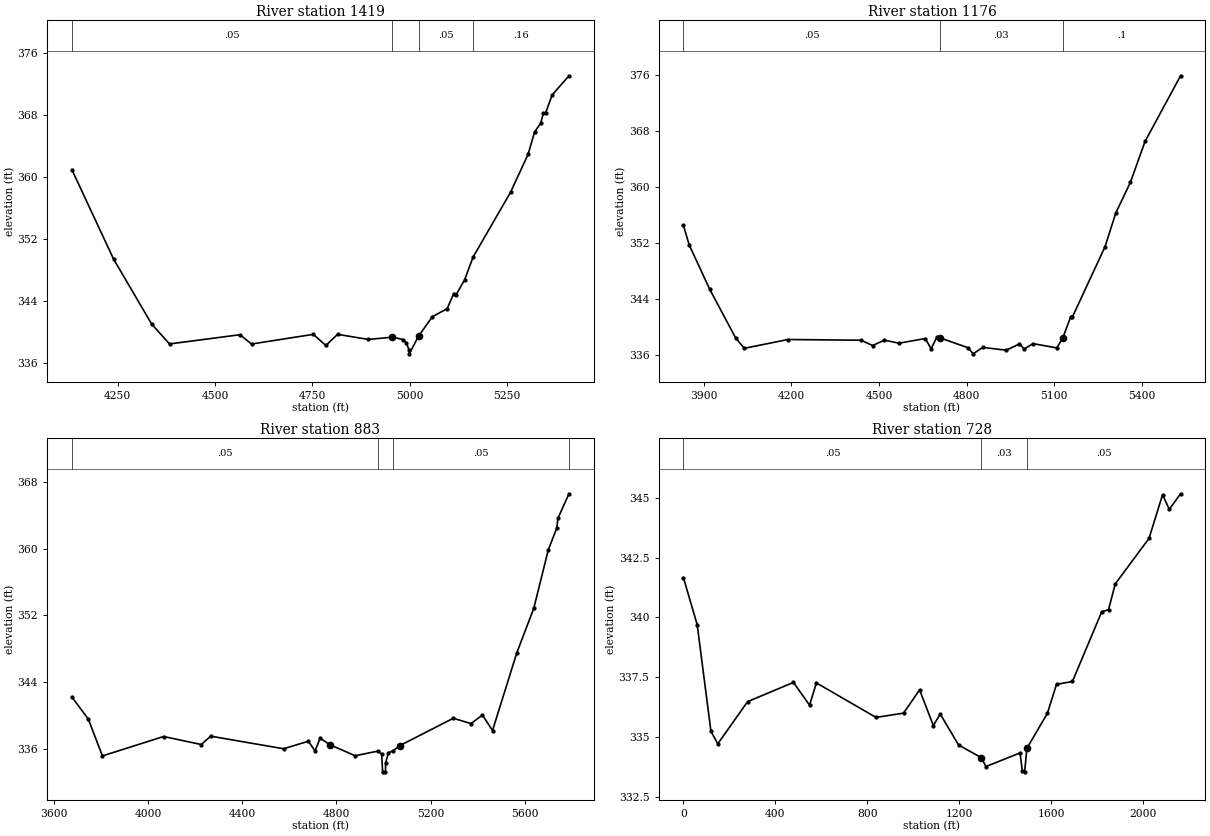
Type RM Length L Ch R = 1 ,1419    ,243,243,243
BEGIN DESCRIPTION:
UNT0285 IN DUCK CR 2 0
END DESCRIPTION:
XS GIS Cut Line= 4
     3581694.509     10431412.73      3581623.51       10431636.
      3581577.94     10432119.91       3582077.1     10432365.15
#Sta/Elev= 30
    4132  360.96 4239.58  349.36 4337.38  340.97    4383  338.42  4563.8  339.61
  4593.9  338.41  4752.6  339.66  4784.8  338.22  4814.9  339.66  4894.1     339
    4956   339.3  4984.1  338.98  4991.7  338.52  4998.7  337.64    4999  337.14
  5023.5  339.47  5058.5  341.94  5096.5  342.98  5113.4  344.94  5118.9  344.72
  5141.4  346.72  5163.2  349.66  5259.4  358.03  5304.4  362.93  5321.3  365.84
  5337.1  366.98  5343.8  368.29  5349.3  368.26  5366.2   370.6  5409.5  373.09
#Mann= 4 ,-1 , 0
    4132     .05       0    4956     .03       0  5023.5     .05       0
  5163.2     .16       0
Bank Sta=4956,5023.5
XS Rating Curve= 0 ,0
Exp/Cntr=0.3,0.1

Type RM Length L Ch R = 1 ,1176    ,293,293,293
BEGIN DESCRIPTION:
Mapping XS 1ee70af0
END DESCRIPTION:
XS GIS Cut Line= 5
     3581592.512    10431432.261      3581397.82     10432000.56
      3581399.99     10432365.14      3581834.02     10432438.92
      3582133.47     10432421.56
#Sta/Elev= 30
    3831  354.48 3850.86  351.68 3920.36  345.39 4009.72  338.37 4039.51  336.89
 4188.45  338.15  4438.6  338.05  4478.6  337.29  4518.6  338.06  4568.6  337.62
  4658.6  338.29  4678.6  336.83  4698.6   338.5  4708.6  338.39  4805.3  336.97
  4822.7   336.1  4855.1  337.02  4936.2  336.62    4981  337.52  4997.1   336.8
  5027.5  337.56  5108.7  336.95    5129  338.35  5156.7  341.44  5161.8  341.34
  5273.6  351.41  5310.6  356.25  5360.6  360.64  5410.7  366.49  5532.3  375.89
#Mann= 3 , 0 , 0
    3831     .05       0  4708.6     .03       0    5129      .1       0
Bank Sta=4708.6,5129
XS Rating Curve= 0 ,0
Exp/Cntr=0.3,0.1

Type RM Length L Ch R = 1 ,883     ,155,155,155
BEGIN DESCRIPTION:
Mapping XS ff311bfe
END DESCRIPTION:
XS GIS Cut Line= 4
     3581429.752    10431449.622      3581202.48     10432419.37
      3581684.28     10432851.25      3582147.85      10432745.1
#Sta/Elev= 30
    3676   342.2 3745.97  339.54 3805.95  335.12 4065.85  337.45 4225.79  336.49
 4265.77  337.49 4575.66  335.98  4680.8  336.88  4709.2  335.72  4730.9  337.25
  4772.7  336.46  4879.6  335.14  4978.3  335.71  4992.5  335.32 4996.29  333.21
 5008.39  333.21  5009.1  334.31  5020.9  335.47  5041.8  335.76  5070.3  336.37
  5296.8  339.64  5371.9     339  5420.4  340.03  5463.3  338.17  5566.8  347.52
  5638.6  352.83  5700.1  359.83  5736.2  362.47  5741.3  363.64  5788.1  366.58
#Mann= 4 ,-1 , 0
    3676     .05       0  4978.3     .03       0  5041.8     .05       0
  5788.1      .1       0
Bank Sta=4772.7,5070.3
XS Rating Curve= 0 ,0
Exp/Cntr=0.3,0.1

Type RM Length L Ch R = 1 ,728     ,0,0,0
XS GIS Cut Line= 4
      3581410.22    10431438.771     3581143.293    10432604.136
     3581542.599    10432907.955     3581963.606    10433101.098
#Sta/Elev= 30
       0  341.66   59.83   339.7  119.67  335.25  149.59  334.73  279.23  336.49
  478.68  337.29  548.49  336.34   578.4  337.27  837.69  335.83  957.36  336.01
 1027.17  336.98    1087  335.49 1116.92  335.97  1196.7  334.68 1295.76  334.15
 1315.57  333.78 1464.16  334.35 1474.07  333.58 1483.98  333.56 1493.88  334.54
 1583.04     336 1622.66  337.21    1692  337.33 1819.44  340.24 1848.82  340.32
  1878.2   341.4 2025.11   343.3 2083.88  345.12 2113.26  344.51 2162.23  345.16
#Mann= 3 , 0 , 0
       0     .05       0 1295.76     .03       0 1493.88     .05       0
Bank Sta=1295.76,1493.88
XS Rating Curve= 0 ,0
Exp/Cntr=0.3,0.1

Chan Stop Cuts=-1
Use User Specified Reach Order=0
Composite Channel Slope=5