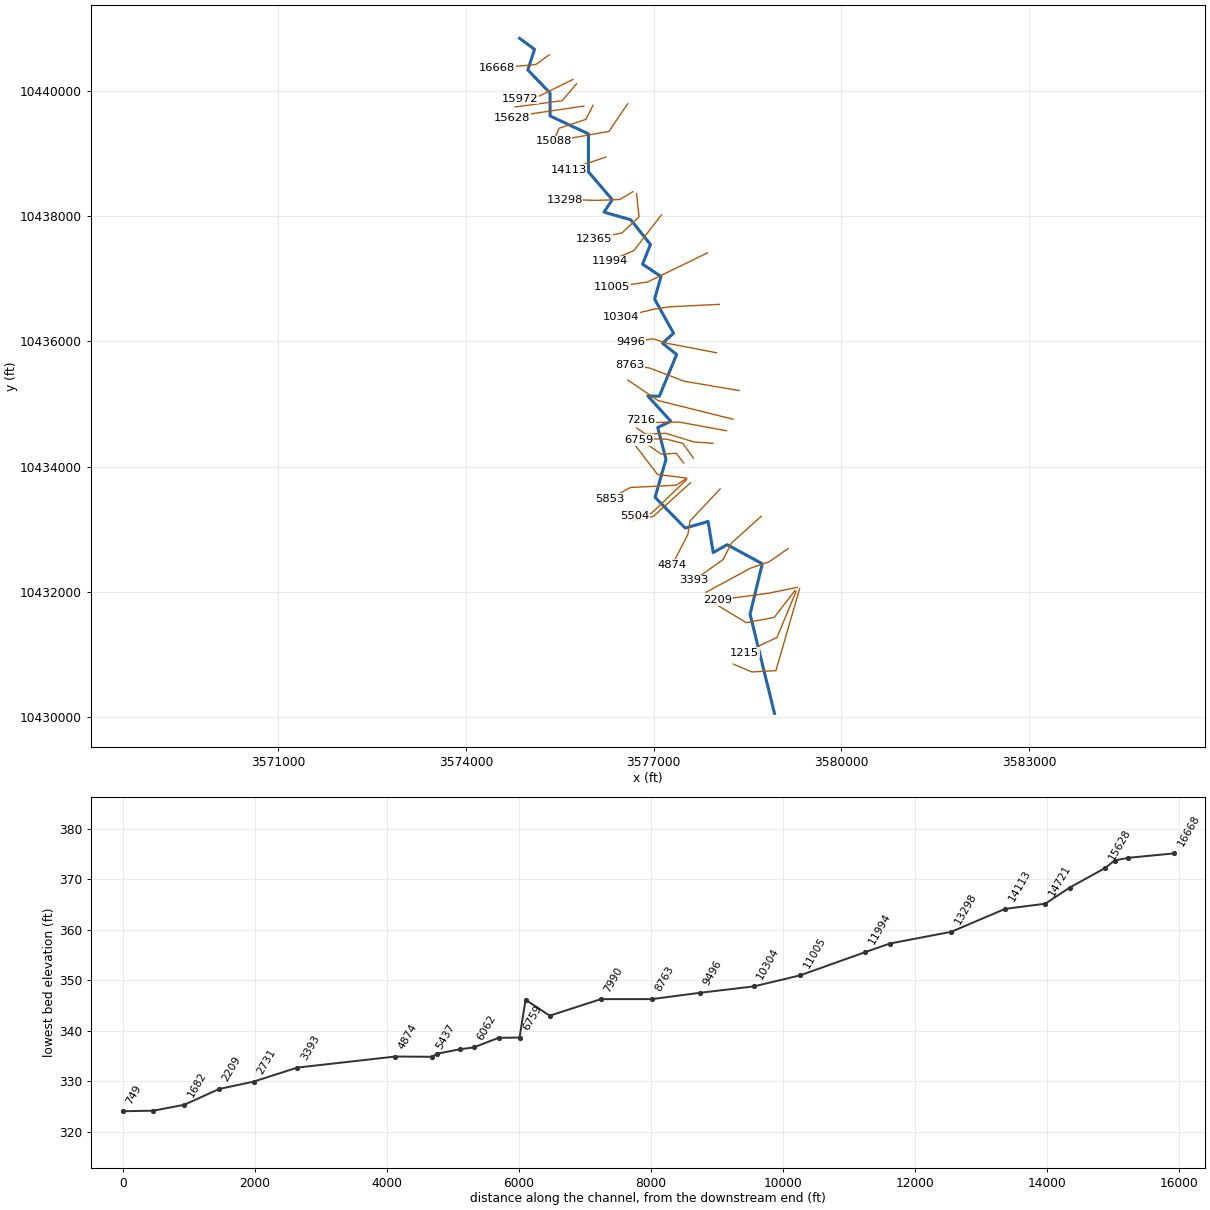
--- UNT0286 IN DUCK CR.prj (project) ---

Proj Title=UNT0286 IN DUCK CR Base Level Engineering
Current Plan=p01
Default Exp/Contr=0.3,0.1
English Units
Geom File=g01
Flow File=f01
Plan File=p01
BEGIN DESCRIPTION:
UNT0286 IN DUCK CR
END DESCRIPTION:

--- UNT0286 IN DUCK CR.p01 (plan) ---

Plan Title=Multiple Run
Short Identifier=Multiple
Geom File=g01
Flow File=f01
Subcritical Flow
K Sum by GR= 0
Std Step Tol= 0.01
Critical Tol= 0.01
Num of Std Step Trials= 20
Max Error Tol= 0.3
Flow Tol Ratio= 0.001
Split Flow NTrial= 30
Split Flow Tol= 0.02
Split Flow Ratio= 0.02
Log Output Level= 0
Friction Slope Method= 1
Unsteady Friction Slope Method= 2
Unsteady Bridges Friction Slope Method= 1
Parabolic Critical Depth
Global Vel Dist=  1 , 1 , 1
Global Log Level= 0
CheckData=True
Encroach Param= -1, 0, 0, 0
BEGIN DESCRIPTION:
Multiple Run
END DESCRIPTION:

--- UNT0286 IN DUCK CR.f01 (steady flow) ---

Flow Title=Multiple
Number of Profiles=7
Profile Names=10-year,25-year,50-year,1pct_min,100-year,1pct_plu,500-year
River Rch & RM= UNT0286 IN DUCK ,Reach-1,16668
    1149    1566    1905    1688    2282    3086    3268
River Rch & RM= UNT0286 IN DUCK ,Reach-1,5853
    1772    2472    3055    2744    3711    5019    5467
Boundary for River Rch & Prof#=UNT0286 IN DUCK ,Reach-1,1
Up Type=0
Dn Type=3
Dn Slope=0.005
Boundary for River Rch & Prof#=UNT0286 IN DUCK ,Reach-1,2
Up Type=0
Dn Type=3
Dn Slope=0.005
Boundary for River Rch & Prof#=UNT0286 IN DUCK ,Reach-1,3
Up Type=0
Dn Type=3
Dn Slope=0.005
Boundary for River Rch & Prof#=UNT0286 IN DUCK ,Reach-1,4
Up Type=0
Dn Type=3
Dn Slope=0.005
Boundary for River Rch & Prof#=UNT0286 IN DUCK ,Reach-1,5
Up Type=0
Dn Type=3
Dn Slope=0.005
Boundary for River Rch & Prof#=UNT0286 IN DUCK ,Reach-1,6
Up Type=0
Dn Type=3
Dn Slope=0.005
Boundary for River Rch & Prof#=UNT0286 IN DUCK ,Reach-1,7
Up Type=0
Dn Type=3
Dn Slope=0.005

--- UNT0286 IN DUCK CR.g01 (geometry) ---

Geom Title=Existing Conditions

River Reach=UNT0286 IN DUCK ,Reach-1
Reach XY= 30
      3574858.61     10440848.66      3575097.85     10440672.61
      3574989.86     10440343.45      3575345.07     10439974.00
      3575346.25     10439607.38      3575959.16     10439320.29
      3575957.81     10438713.52      3576339.59     10438268.84
      3576207.51     10438069.17      3576635.08     10437946.95
      3576949.63     10437550.66      3576823.59     10437236.88
      3577118.60     10437040.53      3577016.18     10436678.30
      3577319.21     10436131.69      3577142.83     10435972.13
      3577367.89     10435790.88      3577091.85     10435123.18
      3576907.47     10435128.91      3577275.70     10434723.87
      3577065.63     10434624.91      3577198.41     10434116.53
      3577024.25     10433507.43      3577505.64     10433015.25
      3577871.41     10433121.08      3577953.00     10432624.10
      3578176.12     10432749.64      3578737.22     10432444.31
      3578542.15     10431638.06      3578932.11     10430051.64

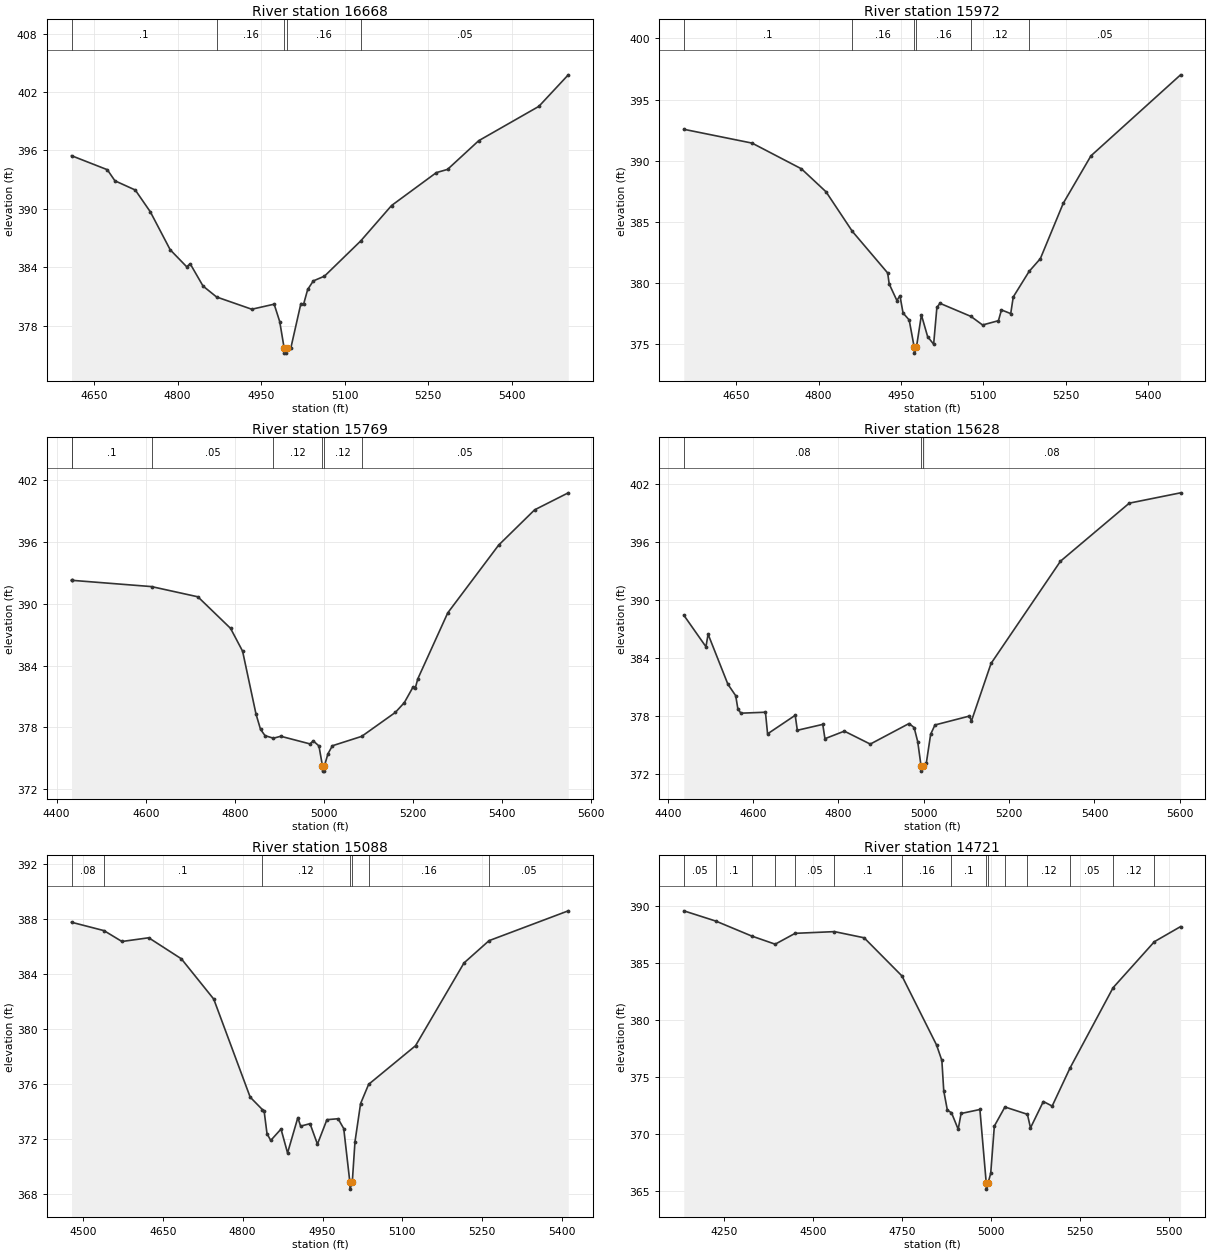
Type RM Length L Ch R = 1,16668,696,696,696
BEGIN DESCRIPTION:
UNT0286 IN DUCK CR 4 0
END DESCRIPTION:
XS GIS Cut Line= 3
      3575335.57     10440586.72      3575116.79     10440430.45
      3574496.14     10440371.50
#Sta/Elev= 30
  4609.4  395.46  4673.7  394.02  4687.4  392.88  4724.0  391.93  4751.1  389.68
  4786.7  385.79  4816.2  384.05  4822.6  384.35  4845.7  382.06  4870.0  380.94
  4933.2  379.68  4973.4  380.20  4983.4  378.41  4991.4  375.67  4991.7  375.17
  4995.3  375.17  4995.6  375.67  5003.5  375.73  5021.4  380.26  5026.4  380.22
  5033.6  381.71  5043.7  382.59  5063.8  383.08  5128.9  386.70  5184.3  390.34
  5264.7  393.72  5284.8  394.05  5340.8  397.00  5448.9  400.53  5501.7  403.77
#Mann=5,-1,0
  4609.4     0.1       0  4870.0    0.16       0  4991.4    0.07       0
  4995.6    0.16       0  5128.9    0.05       0
Bank Sta=4991.4,4995.6
Exp/Cntr=0.3,0.1

Type RM Length L Ch R = 1,15972,203,203,203
BEGIN DESCRIPTION:
UNT0286 IN DUCK CR 26 0
END DESCRIPTION:
XS GIS Cut Line= 4
      3575710.52     10440190.85      3575372.26     10440024.13
      3575168.87     10439923.50      3574870.30     10439881.84
#Sta/Elev= 30
  4554.2  392.58  4678.7  391.45  4768.6  389.35  4813.5  387.47  4861.4  384.24
  4925.8  380.84  4928.6  379.94  4942.6  378.59  4948.2  378.98  4953.8  377.57
  4965.0  377.00  4974.1  374.79  4974.4  374.29  4978.3  374.79  4987.3  377.41
  4998.7  375.63  5009.6  375.02  5015.5  378.02  5021.1  378.36  5077.6  377.29
  5098.8  376.59  5127.7  376.94  5133.2  377.82  5150.1  377.52  5154.7  378.88
  5183.5  380.96  5204.1  382.01  5245.8  386.53  5296.3  390.41  5459.7  397.03
#Mann=6,-1,0
  4554.2     0.1       0  4861.4    0.16       0  4974.1    0.07       0
  4978.3    0.16       0  5077.6    0.12       0  5183.5    0.05       0
Bank Sta=4974.1,4978.3
Exp/Cntr=0.3,0.1

Type RM Length L Ch R = 1,15769,141,141,141
BEGIN DESCRIPTION:
UNT0286 IN DUCK CR 3 0
END DESCRIPTION:
XS GIS Cut Line= 3
      3575769.71     10440124.15      3575538.83     10439851.61
      3574787.14     10439750.92
#Sta/Elev= 30
  4433.3  392.26  4433.6  392.26  4613.0  391.65  4717.1  390.66  4790.5  387.60
  4817.5  385.39  4847.7  379.28  4857.8  377.81  4867.9  377.20  4886.7  376.95
  4903.2  377.14  4968.8  376.40  4976.2  376.69  4989.0  376.20  4996.9  374.26
  4997.2  373.76  5000.9  373.76  5001.2  374.26  5009.2  375.44  5019.2  376.22
  5085.0  377.13  5160.5  379.45  5180.7  380.40  5200.1  381.90  5205.2  381.79
  5210.9  382.70  5278.2  389.10  5392.5  395.67  5473.3  399.09  5548.9  400.74
#Mann=7,-1,0
  4433.3    0.05       0  4433.6     0.1       0  4613.0    0.05       0
  4886.7    0.12       0  4996.9    0.07       0  5001.2    0.12       0
  5085.0    0.05       0
Bank Sta=4996.9,5001.2
Exp/Cntr=0.3,0.1

Type RM Length L Ch R = 1,15628,540,540,540
BEGIN DESCRIPTION:
UNT0286 IN DUCK CR 25 0
END DESCRIPTION:
XS GIS Cut Line= 3
      3575884.31     10439764.80      3575094.38     10439648.48
      3574736.90     10439572.12
#Sta/Elev= 30
  4437.7  388.43  4489.6  385.16  4494.6  386.46  4541.0  381.28  4559.3  380.09
  4564.3  378.75  4571.3  378.28  4629.0  378.38  4634.0  376.14  4698.7  378.06
  4703.7  376.51  4763.3  377.12  4768.4  375.64  4813.9  376.42  4874.6  375.08
  4965.5  377.21  4977.4  376.79  4985.8  375.33  4993.7  372.78  4994.0  372.28
  4998.0  372.78  5006.0  373.13  5016.1  376.10  5026.2  377.06  5106.7  377.98
  5111.8  377.49  5157.6  383.43  5320.3  394.02  5481.5  400.03  5601.7  401.10
#Mann=3,-1,0
  4437.7    0.08       0  4993.7    0.07       0  4998.0    0.08       0
Bank Sta=4993.7,4998
Exp/Cntr=0.3,0.1

Type RM Length L Ch R = 1,15088,367,367,367
BEGIN DESCRIPTION:
UNT0286 IN DUCK CR 28 0
END DESCRIPTION:
XS GIS Cut Line= 4
      3576031.89     10439776.97      3575919.04     10439552.99
      3575488.48     10439408.90      3575399.94     10439198.82
#Sta/Elev= 30
  4478.7  387.79  4539.7  387.18  4573.4  386.39  4623.7  386.66  4685.0  385.13
  4745.8  382.20  4814.2  375.07  4837.0  374.17  4840.5  374.03  4845.8  372.41
  4852.8  371.92  4872.1  372.75  4884.4  371.01  4903.7  373.58  4908.9  372.96
  4926.6  373.14  4940.5  371.65  4958.3  373.43  4979.3  373.50  4989.9  372.78
  5001.4  368.88  5001.7  368.38  5005.9  368.88  5011.0  371.83  5021.5  374.60
  5036.6  376.00  5124.7  378.81  5215.7  384.83  5262.7  386.45  5411.5  388.62
#Mann=7,-1,0
  4478.7    0.08       0  4539.7     0.1       0  4837.0    0.12       0
  5001.4    0.07       0  5005.9    0.12       0  5036.6    0.16       0
  5262.7    0.05       0
Bank Sta=5001.4,5005.9
Exp/Cntr=0.3,0.1

Type RM Length L Ch R = 1,14721,608,608,608
BEGIN DESCRIPTION:
Mapping XS 69733b5a
END DESCRIPTION:
XS GIS Cut Line= 3
      3576585.71     10439801.27      3576287.09     10439360.29
      3575436.76     10439209.31
#Sta/Elev= 30
  4137.4  389.56  4227.6  388.66  4328.5  387.35  4394.2  386.64  4450.3  387.59
  4560.8  387.74  4644.2  387.20  4750.5  383.86  4847.7  377.82  4862.7  376.46
  4868.0  373.80  4878.2  372.10  4889.7  371.89  4908.6  370.44  4916.7  371.82
  4969.6  372.17  4987.5  365.70  4987.8  365.20  4992.3  365.70  5000.0  366.59
  5010.2  370.72  5039.9  372.39  5103.1  371.75  5111.8  370.56  5147.9  372.87
  5172.7  372.47  5222.7  375.79  5343.9  382.83  5460.0  386.86  5533.6  388.18
#Mann=15,-1,0
  4137.4    0.05       0  4227.6     0.1       0  4328.5    0.05       0
  4394.2     0.1       0  4450.3    0.05       0  4560.8     0.1       0
  4750.5    0.16       0  4889.7     0.1       0  4987.5    0.07       0
  4992.3     0.1       0  5039.9    0.16       0  5103.1    0.12       0
  5222.7    0.05       0  5343.9    0.12       0  5460.0    0.05       0
Bank Sta=4987.5,4992.3
Exp/Cntr=0.3,0.1

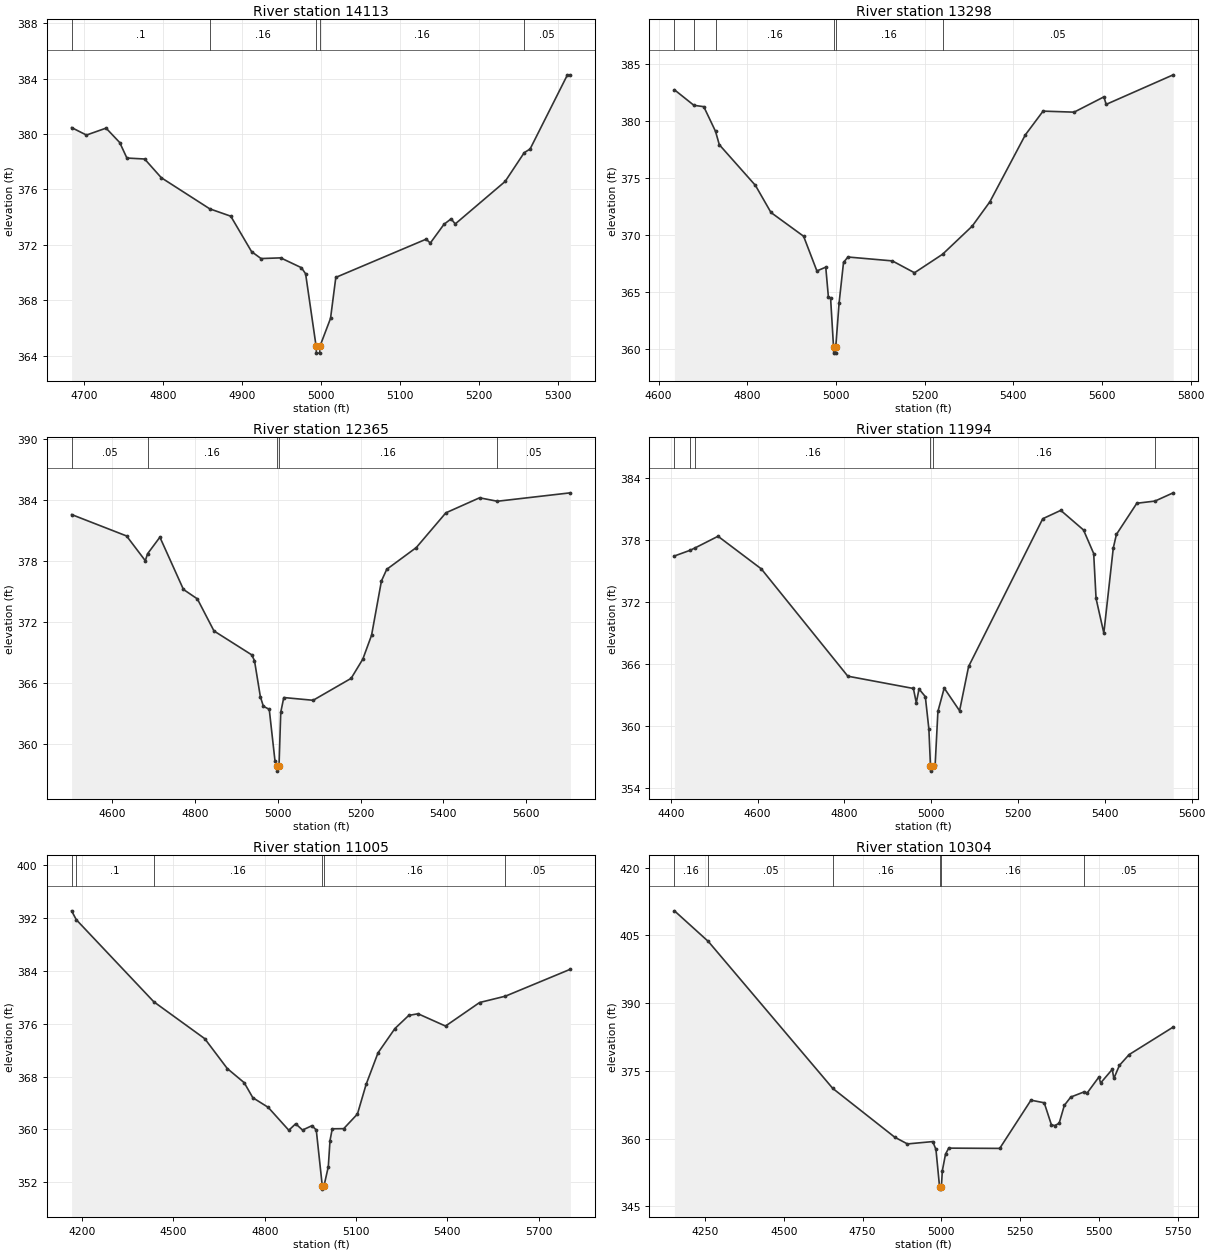
Type RM Length L Ch R = 1,14113,815,815,815
BEGIN DESCRIPTION:
UNT0286 IN DUCK CR 24 0
END DESCRIPTION:
XS GIS Cut Line= 3
      3576239.95     10438950.01      3575939.97     10438850.02
      3575640.00     10438750.03
#Sta/Elev= 30
  4683.8  380.47  4702.6  379.93  4727.5  380.43  4744.8  379.39  4753.9  378.27
  4776.4  378.20  4797.5  376.85  4859.0  374.60  4885.6  374.07  4912.0  371.51
  4924.0  371.01  4948.9  371.06  4975.2  370.35  4980.5  369.91  4993.8  364.68
  4994.2  364.18  4998.3  364.18  4998.7  364.68  5012.1  366.69  5018.8  369.65
  5133.3  372.41  5138.6  372.13  5155.9  373.48  5165.0  373.88  5170.2  373.51
  5233.5  376.58  5257.7  378.66  5265.1  378.92  5312.5  384.28  5316.2  384.28
#Mann=5,-1,0
  4683.8     0.1       0  4859.0    0.16       0  4993.8    0.07       0
  4998.7    0.16       0  5257.7    0.05       0
Bank Sta=4993.8,4998.7
Exp/Cntr=0.3,0.1

Type RM Length L Ch R = 1,13298,933,933,933
BEGIN DESCRIPTION:
UNT0286 IN DUCK CR 23 0
END DESCRIPTION:
XS GIS Cut Line= 4
      3576668.85     10438395.71      3576460.54     10438270.72
      3576102.90     10438256.84      3575578.62     10438270.72
#Sta/Elev= 30
  4635.6  382.70  4679.5  381.34  4701.8  381.22  4728.3  379.06  4736.8  377.89
  4818.4  374.32  4853.4  371.95  4927.0  369.87  4957.0  366.83  4977.0  367.16
  4982.9  364.57  4987.9  364.46  4994.6  360.13  4995.0  359.63  4999.2  359.63
  4999.5  360.13  5007.1  364.03  5017.1  367.58  5027.1  368.05  5127.2  367.71
  5177.2  366.67  5240.5  368.29  5307.3  370.75  5347.3  372.89  5427.3  378.75
  5467.3  380.83  5537.3  380.74  5604.6  382.08  5609.6  381.42  5760.9  384.01
#Mann=6,-1,0
  4635.6    0.05       0  4679.5     0.1       0  4728.3    0.16       0
  4994.6    0.07       0  4999.5    0.16       0  5240.5    0.05       0
Bank Sta=4994.6,4999.5
Exp/Cntr=0.3,0.1

Type RM Length L Ch R = 1,12365,371,371,371
BEGIN DESCRIPTION:
UNT0286 IN DUCK CR 21 0
END DESCRIPTION:
XS GIS Cut Line= 4
      3576728.07     10438363.71      3576767.99     10437992.23
      3576493.69     10437735.29      3576047.55     10437643.28
#Sta/Elev= 30
  4501.8  382.58  4634.6  380.47  4679.9  378.03  4685.2  378.71  4715.1  380.35
  4772.0  375.20  4805.6  374.27  4845.8  371.11  4936.8  368.76  4943.6  368.19
  4957.8  364.64  4965.1  363.69  4979.3  363.39  4993.1  358.33  4997.7  357.80
  4998.1  357.30  5002.9  357.80  5007.1  363.10  5014.4  364.55  5085.3  364.28
  5177.1  366.44  5205.4  368.34  5226.5  370.69  5250.3  376.03  5263.1  377.18
  5334.6  379.33  5406.0  382.75  5487.4  384.23  5530.3  383.89  5706.8  384.72
#Mann=5,-1,0
  4501.8    0.05       0  4685.2    0.16       0  4997.7    0.07       0
  5002.9    0.16       0  5530.3    0.05       0
Bank Sta=4997.7,5002.9
Exp/Cntr=0.3,0.1

Type RM Length L Ch R = 1,11994,989,989,989
BEGIN DESCRIPTION:
UNT0286 IN DUCK CR 2 0
END DESCRIPTION:
XS GIS Cut Line= 4
      3577127.24     10438027.71      3576835.54     10437649.20
      3576686.23     10437454.75      3576295.51     10437285.32
#Sta/Elev= 30
  4408.6  376.45  4444.6  377.00  4457.0  377.25  4509.0  378.36  4608.7  375.20
  4808.0  364.80  4959.0  363.61  4965.7  362.23  4972.0  363.56  4986.5  362.82
  4994.7  359.68  4998.4  356.10  4998.8  355.60  5003.6  356.10  5009.2  356.24
  5015.5  361.38  5030.0  363.65  5065.4  361.45  5086.2  365.74  5257.0  380.06
  5298.5  380.87  5350.9  378.97  5374.3  376.69  5379.8  372.33  5397.7  368.98
  5419.5  377.23  5426.7  378.54  5473.7  381.56  5515.5  381.77  5557.5  382.57
#Mann=6,-1,0
  4408.6    0.05       0  4444.6     0.1       0  4457.0    0.16       0
  4998.4    0.07       0  5003.6    0.16       0  5515.5    0.05       0
Bank Sta=4998.4,5003.6
Exp/Cntr=0.3,0.1

Type RM Length L Ch R = 1,11005,701,701,701
BEGIN DESCRIPTION:
UNT0286 IN DUCK CR 19 0
END DESCRIPTION:
XS GIS Cut Line= 3
      3577861.71     10437417.56      3576906.88     10436952.30
      3576337.41     10436865.49
#Sta/Elev= 30
  4165.8  393.05  4181.1  391.71  4435.8  379.30  4603.2  373.72  4677.1  369.21
  4732.7  367.07  4761.0  364.80  4811.6  363.34  4879.2  359.88  4901.8  360.86
  4924.3  359.91  4955.2  360.57  4969.4  359.92  4989.1  351.48  4989.6  350.98
  4994.8  351.48  5008.9  354.36  5014.5  358.32  5021.9  360.10  5059.5  360.12
  5104.6  362.33  5133.1  366.81  5172.2  371.58  5227.8  375.26  5273.2  377.24
  5303.6  377.49  5393.9  375.63  5505.9  379.19  5590.7  380.15  5804.0  384.22
#Mann=6,-1,0
  4165.8    0.16       0  4181.1     0.1       0  4435.8    0.16       0
  4989.1    0.07       0  4994.8    0.16       0  5590.7    0.05       0
Bank Sta=4989.1,4994.8
Exp/Cntr=0.3,0.1

Type RM Length L Ch R = 1,10304,808,808,808
BEGIN DESCRIPTION:
UNT0286 IN DUCK CR 18 0
END DESCRIPTION:
XS GIS Cut Line= 4
      3578050.80     10436593.64      3577266.09     10436555.45
      3576995.26     10436513.78      3576485.95     10436392.52
#Sta/Elev= 30
  4153.0  410.43  4260.5  403.65  4655.5  371.11  4852.5  360.29  4892.6  358.81
  4973.0  359.33  4983.1  357.58  4994.6  349.30  4995.0  348.80  5000.3  349.30
  5003.4  352.89  5013.5  356.56  5023.6  357.88  5185.5  357.82  5284.7  368.50
  5326.8  367.92  5349.5  363.06  5359.8  362.87  5374.1  363.37  5390.6  367.35
  5411.1  369.19  5451.8  370.29  5463.5  370.13  5500.5  373.64  5505.7  372.29
  5542.7  375.32  5547.8  373.31  5565.4  376.20  5596.2  378.59  5736.2  384.69
#Mann=6,-1,0
  4153.0    0.16       0  4260.5    0.05       0  4655.5    0.16       0
  4994.6    0.07       0  5000.3    0.16       0  5451.8    0.05       0
Bank Sta=4994.6,5000.3
Exp/Cntr=0.3,0.1

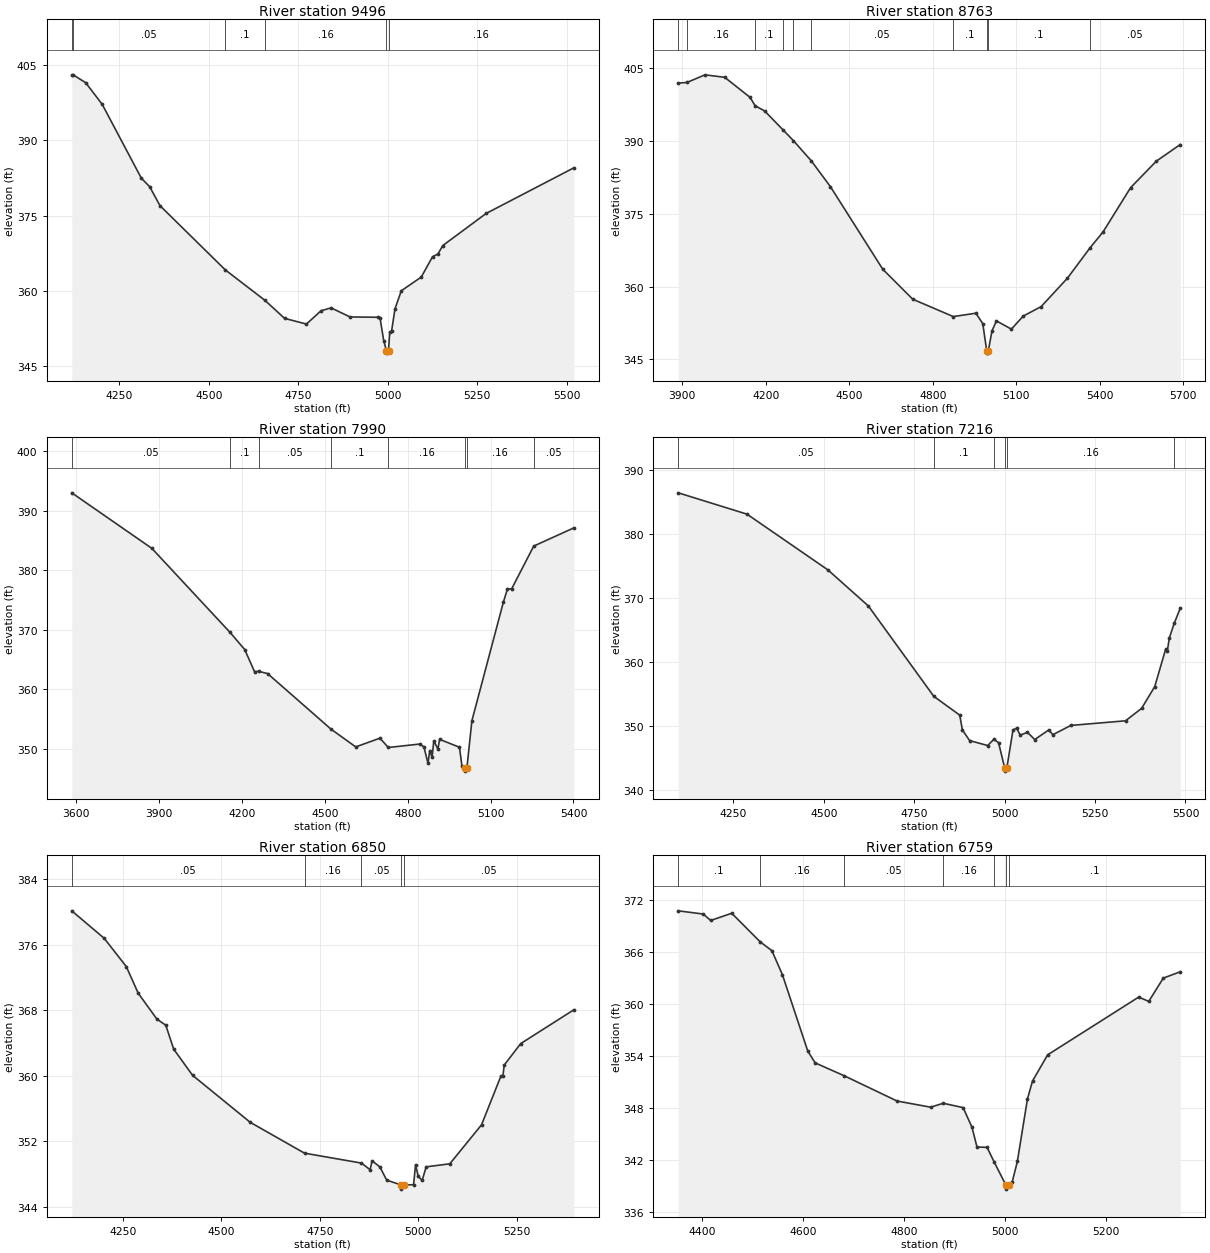
Type RM Length L Ch R = 1,9496,733,733,733
BEGIN DESCRIPTION:
UNT0286 IN DUCK CR 16 0
END DESCRIPTION:
XS GIS Cut Line= 5
      3578005.68     10435819.33      3577304.29     10435954.75
      3577234.84     10435965.17      3576992.11     10436041.64
      3576631.59     10435996.53
#Sta/Elev= 30
  4117.3  403.06  4121.1  403.06  4156.2  401.49  4202.4  397.16  4311.7  382.43
  4334.8  380.76  4363.6  376.97  4546.3  364.14  4657.2  358.06  4711.7  354.48
  4772.8  353.35  4813.5  356.00  4841.6  356.58  4894.5  354.77  4973.1  354.70
  4978.4  354.54  4988.6  350.06  4996.2  348.05  4996.7  347.55  5002.0  348.05
  5005.5  351.74  5010.7  351.98  5020.1  356.39  5037.8  359.99  5093.5  362.72
  5124.9  366.77  5140.2  367.34  5153.7  369.01  5274.7  375.41  5519.7  384.51
#Mann=6,-1,0
  4117.3    0.16       0  4121.1    0.05       0  4546.3     0.1       0
  4657.2    0.16       0  4996.2    0.07       0  5002.0    0.16       0
Bank Sta=4996.2,5002
Exp/Cntr=0.3,0.1

Type RM Length L Ch R = 1,8763,773,773,773
BEGIN DESCRIPTION:
UNT0286 IN DUCK CR 15 0
END DESCRIPTION:
XS GIS Cut Line= 4
      3578366.82     10435215.16      3577488.32     10435364.47
      3576932.76     10435576.28      3576616.93     10435621.40
#Sta/Elev= 30
  3885.2  401.89  3916.7  402.03  3981.3  403.60  4052.3  403.09  4143.6  398.95
  4161.4  397.25  4195.9  396.15  4262.3  392.24  4299.3  390.04  4363.3  385.90
  4431.9  380.60  4620.3  363.57  4728.2  357.39  4873.8  353.82  4955.2  354.51
  4979.9  352.36  4994.0  346.79  4994.5  346.29  4999.9  346.79  5013.0  350.89
  5029.1  352.93  5082.6  351.23  5125.4  353.92  5189.6  355.87  5284.1  361.72
  5365.7  368.00  5411.9  371.22  5511.4  380.38  5603.9  385.83  5689.9  389.25
#Mann=10,-1,0
  3885.2    0.05       0  3916.7    0.16       0  4161.4     0.1       0
  4262.3    0.05       0  4299.3     0.1       0  4363.3    0.05       0
  4873.8     0.1       0  4994.0    0.07       0  4999.9     0.1       0
  5365.7    0.05       0
Bank Sta=4994,4999.9
Exp/Cntr=0.3,0.1

Type RM Length L Ch R = 1,7990,774,774,774
BEGIN DESCRIPTION:
UNT0286 IN DUCK CR 13 0
END DESCRIPTION:
XS GIS Cut Line= 3
      3578269.57     10434756.83      3577071.65     10435055.45
      3576589.03     10435381.82
#Sta/Elev= 30
  3584.1  393.04  3874.0  383.71  4157.1  369.58  4210.2  366.70  4245.5  362.99
  4260.0  363.05  4292.6  362.68  4522.2  353.34  4611.9  350.35  4699.6  351.82
  4729.7  350.25  4843.5  350.83  4858.5  350.37  4873.4  347.59  4879.4  349.65
  4888.4  348.65  4894.4  351.36  4909.4  349.99  4915.4  351.62  4987.3  350.29
  4996.3  347.13  5008.3  346.78  5008.7  346.28  5014.2  346.78  5032.2  354.72
  5146.1  374.65  5161.1  376.92  5176.0  376.89  5256.1  384.09  5401.3  387.15
#Mann=8,-1,0
  3584.1    0.05       0  4157.1     0.1       0  4260.0    0.05       0
  4522.2     0.1       0  4729.7    0.16       0  5008.3    0.07       0
  5014.2    0.16       0  5256.1    0.05       0
Bank Sta=5008.3,5014.2
Exp/Cntr=0.3,0.1

Type RM Length L Ch R = 1,7216,366,366,366
BEGIN DESCRIPTION:
UNT0286 IN DUCK CR 11 0
END DESCRIPTION:
XS GIS Cut Line= 4
      3578165.39     10434572.81      3577401.51     10434711.70
      3577054.29     10434704.75      3576792.07     10434741.65
#Sta/Elev= 30
  4097.3  386.41  4287.6  383.08  4511.2  374.39  4623.0  368.77  4804.0  354.67
  4875.9  351.73  4883.1  349.42  4903.1  347.77  4953.1  346.99  4970.0  347.96
  4983.1  347.45  5000.1  343.50  5000.6  343.00  5006.1  343.50  5023.1  349.43
  5033.1  349.70  5043.1  348.62  5063.1  349.05  5083.2  347.93  5122.3  349.43
  5133.2  348.68  5183.2  350.13  5334.3  350.85  5378.9  352.80  5415.1  356.19
  5445.1  361.99  5450.1  361.81  5455.5  363.79  5468.9  366.04  5485.8  368.44
#Mann=6,-1,0
  4097.3    0.05       0  4804.0     0.1       0  4970.0    0.16       0
  5000.1    0.07       0  5006.1    0.16       0  5468.9    0.05       0
Bank Sta=5000.1,5006.1
Exp/Cntr=0.3,0.1

Type RM Length L Ch R = 1,6850,91,91,91
BEGIN DESCRIPTION:
UNT0286 IN DUCK CR 12 0
END DESCRIPTION:
XS GIS Cut Line= 5
      3577950.27     10434370.70      3577641.26     10434393.27
      3577191.61     10434532.16      3576877.37     10434513.06
      3576730.20     10434616.95
#Sta/Elev= 30
  4120.2  380.12  4202.7  376.76  4258.7  373.32  4288.8  370.08  4336.5  366.90
  4359.0  366.16  4379.1  363.24  4427.1  360.04  4573.7  354.30  4711.4  350.54
  4856.0  349.33  4878.0  348.52  4883.2  349.61  4902.9  348.86  4920.2  347.25
  4957.2  346.65  4957.7  346.15  4963.3  346.65  4988.5  346.69  4993.5  349.13
  5000.3  347.71  5010.3  347.21  5020.4  348.87  5080.5  349.24  5161.1  354.00
  5210.6  359.98  5215.5  359.98  5218.7  361.29  5260.5  363.91  5395.6  368.04
#Mann=5,-1,0
  4120.2    0.05       0  4711.4    0.16       0  4856.0    0.05       0
  4957.2    0.04       0  4963.3    0.05       0
Bank Sta=4957.2,4963.3
Exp/Cntr=0.3,0.1

Type RM Length L Ch R = 1,6759,318,318,318
BEGIN DESCRIPTION:
UNT0286 IN DUCK CR 30 0
END DESCRIPTION:
XS GIS Cut Line= 5
      3577636.07     10434136.30      3577465.91     10434370.70
      3577202.02     10434438.41      3576990.22     10434440.15
      3576769.77     10434424.52
#Sta/Elev= 30
  4352.8  370.73  4402.4  370.36  4417.1  369.62  4458.8  370.45  4515.3  367.15
  4538.4  366.14  4559.3  363.36  4609.5  354.57  4624.2  353.21  4681.3  351.74
  4786.4  348.82  4852.9  348.11  4878.0  348.56  4917.3  348.06  4934.8  345.81
  4944.8  343.52  4964.8  343.48  4978.4  341.85  5001.8  339.17  5002.3  338.67
  5007.9  339.17  5014.8  339.54  5024.8  341.86  5044.8  349.06  5054.8  351.12
  5084.8  354.14  5265.2  360.79  5285.2  360.30  5314.0  362.98  5347.7  363.71
#Mann=7,-1,0
  4352.8     0.1       0  4515.3    0.16       0  4681.3    0.05       0
  4878.0    0.16       0  4978.4     0.1       0  5001.8    0.07       0
  5007.9     0.1       0
Bank Sta=5001.8,5007.9
Exp/Cntr=0.3,0.1

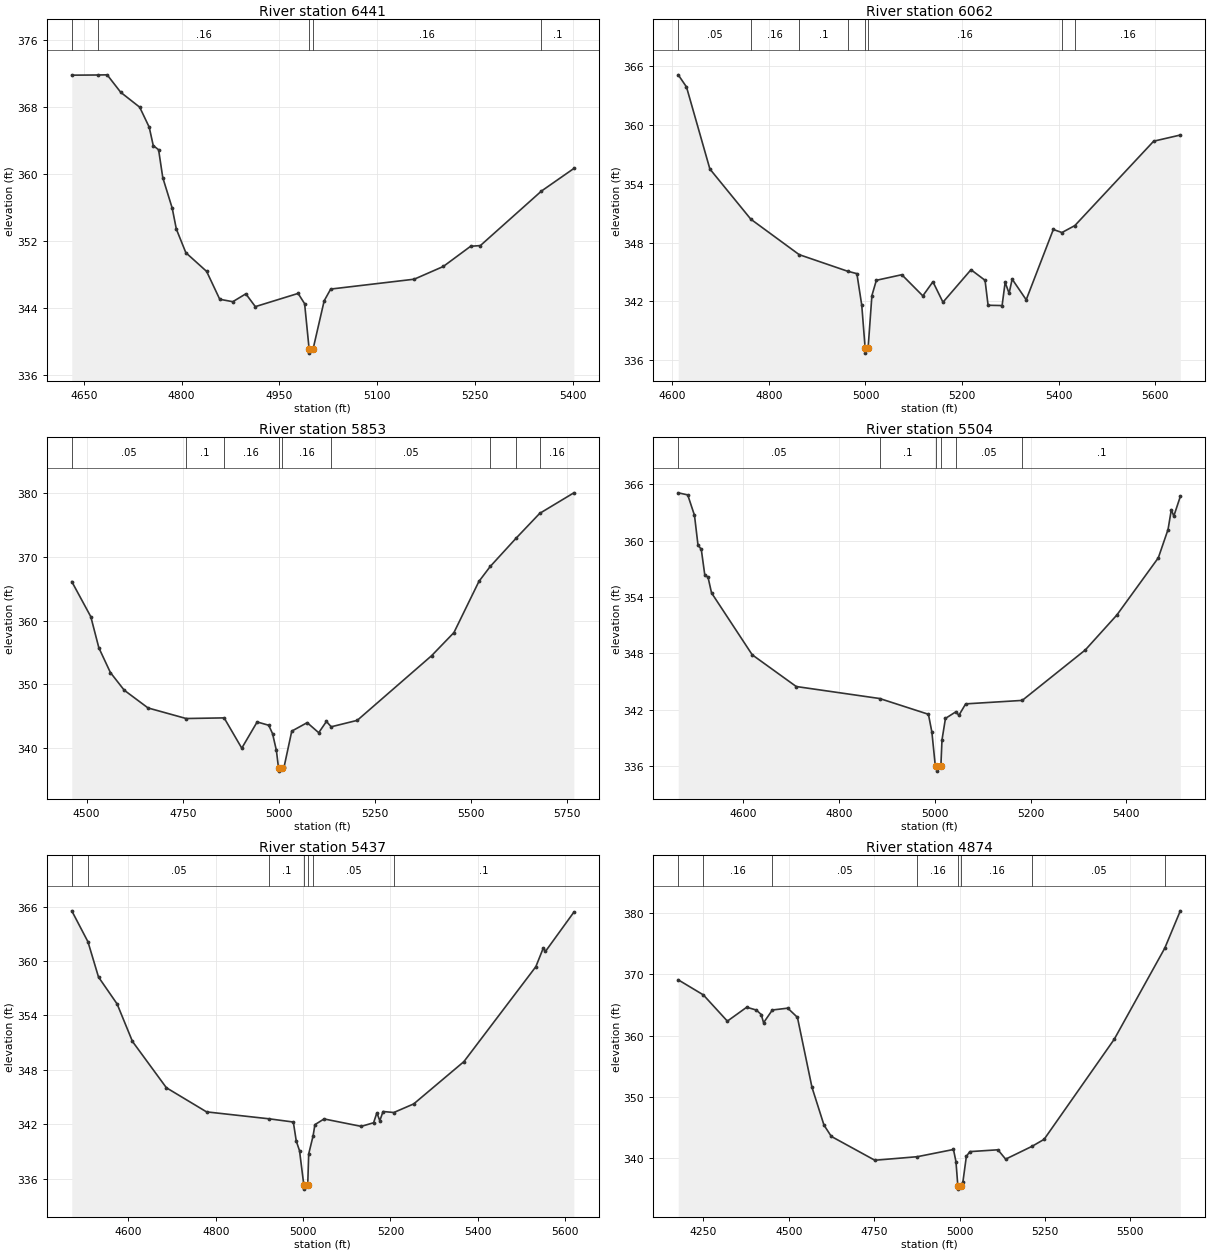
Type RM Length L Ch R = 1,6441,379,379,379
BEGIN DESCRIPTION:
UNT0286 IN DUCK CR 31 0
END DESCRIPTION:
XS GIS Cut Line= 4
      3577481.40     10434055.41      3577363.21     10434211.53
      3577123.73     10434197.81      3576848.07     10434387.33
#Sta/Elev= 30
  4631.5  371.85  4671.2  371.87  4685.8  371.89  4706.6  369.80  4735.7  368.02
  4750.3  365.63  4756.5  363.43  4764.7  362.93  4771.1  359.60  4785.6  355.94
  4791.9  353.45  4806.5  350.62  4838.4  348.38  4858.5  345.05  4878.5  344.76
  4898.5  345.70  4913.1  344.17  4978.7  345.75  4988.7  344.52  4995.6  339.11
  4996.1  338.61  5001.7  339.11  5018.7  344.87  5028.7  346.27  5156.8  347.45
  5201.4  348.97  5243.4  351.39  5258.3  351.47  5352.0  357.99  5401.7  360.69
#Mann=5,-1,0
  4631.5     0.1       0  4671.2    0.16       0  4995.6    0.07       0
  5001.7    0.16       0  5352.0     0.1       0
Bank Sta=4995.6,5001.7
Exp/Cntr=0.3,0.1

Type RM Length L Ch R = 1,6062,209,209,209
BEGIN DESCRIPTION:
UNT0286 IN DUCK CR 9 1
END DESCRIPTION:
XS GIS Cut Line= 3
      3577509.13     10433818.28      3577063.83     10433872.97
      3576704.45     10434341.72
#Sta/Elev= 30
  4612.4  365.13  4629.5  363.89  4677.9  355.51  4762.7  350.38  4862.8  346.76
  4962.8  345.07  4982.2  344.82  4992.3  341.59  4999.3  337.20  4999.8  336.70
  5005.4  337.20  5013.3  342.58  5022.5  344.14  5075.2  344.71  5118.7  342.55
  5139.6  343.99  5160.4  341.90  5218.4  345.22  5247.5  344.14  5253.8  341.59
  5282.8  341.56  5289.1  343.93  5297.3  342.81  5303.6  344.26  5332.7  342.15
  5388.8  349.33  5406.7  349.02  5433.4  349.73  5596.5  358.35  5651.7  358.98
#Mann=8,-1,0
  4612.4    0.05       0  4762.7    0.16       0  4862.8     0.1       0
  4962.8    0.16       0  4999.3    0.07       0  5005.4    0.16       0
  5406.7     0.1       0  5433.4    0.16       0
Bank Sta=4999.3,5005.4
Exp/Cntr=0.3,0.1

Type RM Length L Ch R = 1,5853,349,349,349
BEGIN DESCRIPTION:
Mapping XS 1d63a4d3
END DESCRIPTION:
XS GIS Cut Line= 4
      3577529.97     10433813.07      3577363.31     10433701.10
      3576628.93     10433664.64      3576306.52     10433482.63
#Sta/Elev= 30
  4461.4  366.14  4510.9  360.62  4531.9  355.72  4561.9  351.84  4597.9  349.06
  4659.9  346.27  4759.0  344.61  4857.8  344.71  4903.7  339.95  4943.7  344.07
  4973.8  343.55  4983.8  342.23  4993.8  339.59  4999.3  336.84  4999.8  336.34
  5008.4  336.84  5013.8  337.00  5033.8  342.63  5073.9  343.96  5103.9  342.38
  5124.0  344.15  5136.4  343.31  5204.1  344.32  5397.5  354.48  5455.7  358.12
  5520.7  366.16  5550.1  368.51  5618.1  373.00  5678.9  376.86  5767.7  380.09
#Mann=9,-1,0
  4461.4    0.05       0  4759.0     0.1       0  4857.8    0.16       0
  4999.3    0.07       0  5008.4    0.16       0  5136.4    0.05       0
  5550.1    0.16       0  5618.1     0.1       0  5678.9    0.16       0
Bank Sta=4999.3,5008.4
Exp/Cntr=0.3,0.1

Type RM Length L Ch R = 1,5504,67,67,67
BEGIN DESCRIPTION:
UNT0286 IN DUCK CR 9 0
END DESCRIPTION:
XS GIS Cut Line= 3
      3577524.79     10433787.06      3576964.87     10433250.57
      3576696.88     10433203.74
#Sta/Elev= 30
  4465.0  365.11  4484.8  364.89  4498.9  362.71  4506.2  359.55  4513.1  359.08
  4520.3  356.39  4527.2  356.10  4534.5  354.44  4619.4  347.84  4711.2  344.46
  4885.3  343.18  4987.0  341.50  4994.2  339.60  5001.2  336.06  5003.8  335.94
  5004.3  335.44  5012.9  335.94  5015.3  338.77  5022.5  341.06  5044.4  341.77
  5050.5  341.39  5064.7  342.61  5182.7  342.98  5314.3  348.36  5379.9  352.07
  5466.6  358.18  5486.9  361.20  5493.8  363.32  5498.9  362.62  5512.5  364.72
#Mann=6,-1,0
  4465.0    0.05       0  4885.3     0.1       0  5003.8    0.07       0
  5012.9     0.1       0  5044.4    0.05       0  5182.7     0.1       0
Bank Sta=5003.8,5012.9
Exp/Cntr=0.3,0.1

Type RM Length L Ch R = 1,5437,563,563,563
BEGIN DESCRIPTION:
Mapping XS 704b5a4c
END DESCRIPTION:
XS GIS Cut Line= 3
      3577589.84     10433740.13      3576998.72     10433203.70
      3576657.59     10433120.37
#Sta/Elev= 30
  4470.4  365.54  4507.5  362.12  4531.6  358.24  4574.2  355.27  4609.3  351.14
  4687.0  346.03  4778.9  343.37  4922.9  342.60  4977.6  342.25  4984.4  340.14
  4991.8  339.09  5001.5  335.35  5002.0  334.85  5010.6  335.35  5012.8  338.73
  5022.9  340.73  5027.0  341.96  5048.0  342.59  5133.1  341.77  5161.4  342.17
  5168.9  343.27  5175.6  342.39  5183.0  343.41  5207.7  343.30  5253.3  344.25
  5368.1  348.91  5532.8  359.38  5549.7  361.42  5554.9  361.07  5619.8  365.39
#Mann=7,-1,0
  4470.4     0.1       0  4507.5    0.05       0  4922.9     0.1       0
  5001.5    0.07       0  5010.6     0.1       0  5022.9    0.05       0
  5207.7     0.1       0
Bank Sta=5001.5,5010.6
Exp/Cntr=0.3,0.1

Type RM Length L Ch R = 1,4874,1481,1481,1481
BEGIN DESCRIPTION:
UNT0286 IN DUCK CR 8 0
END DESCRIPTION:
XS GIS Cut Line= 4
      3578064.73     10433642.28      3577582.93     10433130.10
      3577548.21     10432913.09      3577296.79     10432427.57
#Sta/Elev= 30
  4176.4  369.11  4249.9  366.65  4320.2  362.36  4376.8  364.63  4405.1  364.17
  4419.3  363.44  4426.2  362.10  4451.9  364.18  4497.0  364.48  4525.3  362.98
  4567.8  351.56  4603.0  345.37  4624.4  343.52  4751.9  339.62  4876.1  340.20
  4982.1  341.38  4989.4  339.39  4994.9  335.40  4995.4  334.90  5004.1  335.40
  5009.7  336.07  5019.8  340.25  5029.9  341.03  5112.2  341.33  5134.8  339.80
  5212.5  341.91  5247.4  343.04  5452.7  359.40  5600.7  374.30  5646.1  380.39
#Mann=8,-1,0
  4176.4    0.05       0  4249.9    0.16       0  4451.9    0.05       0
  4876.1    0.16       0  4994.9    0.07       0  5004.1    0.16       0
  5212.5    0.05       0  5600.7     0.1       0
Bank Sta=4994.9,5004.1
Exp/Cntr=0.3,0.1

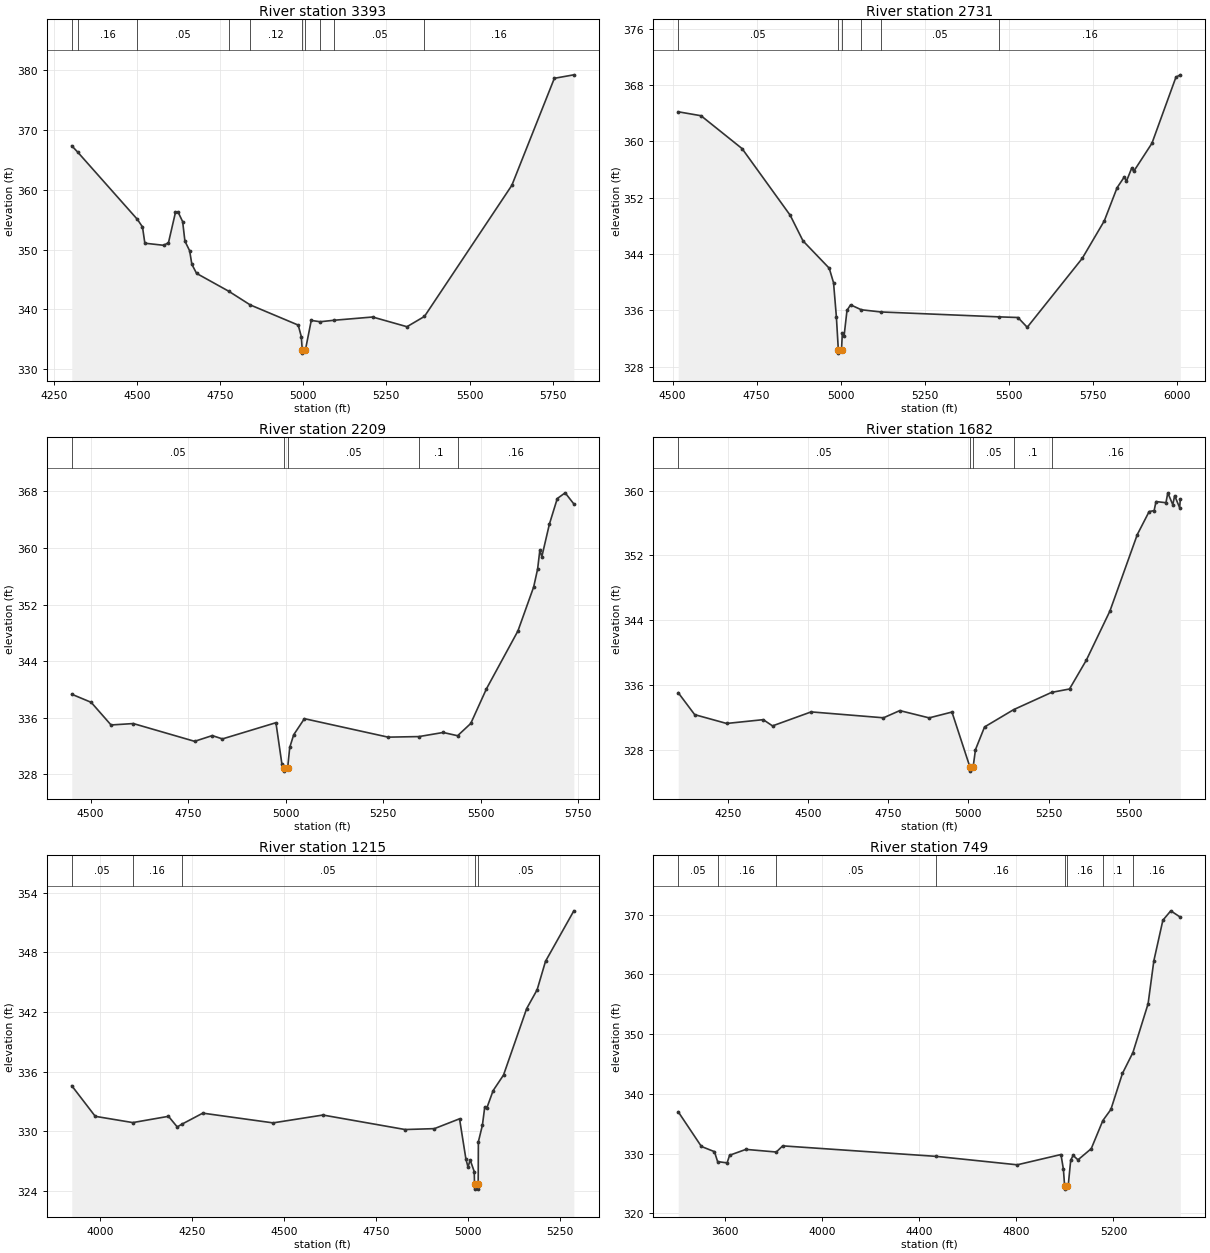
Type RM Length L Ch R = 1,3393,662,662,662
BEGIN DESCRIPTION:
UNT0286 IN DUCK CR 7 0
END DESCRIPTION:
XS GIS Cut Line= 4
      3578720.11     10433203.91      3578242.66     10432774.20
      3578112.45     10432513.78      3577643.70     10432179.58
#Sta/Elev= 30
  4304.4  367.32  4321.9  366.29  4501.9  355.02  4517.0  353.77  4524.1  351.06
  4580.9  350.71  4595.1  351.15  4616.1  356.21  4623.5  356.31  4637.7  354.66
  4644.5  351.41  4658.7  349.80  4665.4  347.53  4679.6  346.02  4776.3  343.04
  4840.8  340.76  4985.1  337.39  4994.3  335.48  4997.3  333.21  4997.8  332.71
  5006.6  333.21  5024.3  338.17  5051.0  337.95  5093.3  338.20  5208.7  338.74
  5312.0  337.12  5364.6  338.84  5627.2  360.72  5755.0  378.59  5813.6  379.17
#Mann=10,-1,0
  4304.4    0.05       0  4321.9    0.16       0  4501.9    0.05       0
  4776.3     0.1       0  4840.8    0.12       0  4997.3    0.07       0
  5006.6    0.12       0  5051.0     0.1       0  5093.3    0.05       0
  5364.6    0.16       0
Bank Sta=4997.3,5006.6
Exp/Cntr=0.3,0.1

Type RM Length L Ch R = 1,2731,522,522,522
BEGIN DESCRIPTION:
UNT0286 IN DUCK CR 6 0
END DESCRIPTION:
XS GIS Cut Line= 4
      3579149.80     10432687.41      3578845.96     10432474.72
      3578550.82     10432374.89      3577839.02     10431988.61
#Sta/Elev= 30
  4516.9  364.21  4584.6  363.65  4706.7  358.98  4849.7  349.51  4887.8  345.87
  4965.7  341.99  4978.5  339.93  4986.9  335.12  4992.7  330.43  4993.2  329.93
  5002.2  330.43  5004.7  332.79  5009.9  332.39  5018.5  336.00  5029.1  336.79
  5061.0  336.09  5118.5  335.78  5471.0  335.08  5526.6  334.99  5554.2  333.60
  5717.7  343.39  5783.3  348.72  5821.3  353.43  5843.2  354.99  5848.9  354.33
  5865.0  356.24  5870.7  355.75  5924.9  359.74  5996.2  369.13  6009.2  369.46
#Mann=6,-1,0
  4516.9    0.05       0  4992.7    0.03       0  5002.2    0.05       0
  5061.0    0.12       0  5118.5    0.05       0  5471.0    0.16       0
Bank Sta=4992.7,5002.2
Exp/Cntr=0.3,0.1

Type RM Length L Ch R = 1,2209,527,527,527
BEGIN DESCRIPTION:
UNT0286 IN DUCK CR 22 0
END DESCRIPTION:
XS GIS Cut Line= 3
      3579300.79     10432068.28      3578826.85     10431971.93
      3578030.00     10431865.16
#Sta/Elev= 30
  4451.6  339.33  4501.3  338.19  4552.3  334.99  4609.4  335.19  4766.6  332.68
  4811.9  333.49  4838.0  333.02  4975.2  335.31  4990.5  329.47  4995.8  328.97
  4996.3  328.47  5005.3  328.97  5010.6  331.82  5020.7  333.60  5048.2  335.88
  5262.9  333.27  5342.0  333.35  5404.1  333.93  5441.1  333.47  5474.8  335.20
  5515.1  340.10  5595.8  348.27  5636.2  354.49  5646.3  357.02  5652.0  359.68
  5657.1  358.76  5676.5  363.36  5696.7  366.97  5716.9  367.78  5739.2  366.21
#Mann=5,-1,0
  4451.6    0.05       0  4995.8    0.03       0  5005.3    0.05       0
  5342.0     0.1       0  5441.1    0.16       0
Bank Sta=4995.8,5005.3
Exp/Cntr=0.3,0.1

Type RM Length L Ch R = 1,1682,467,467,467
BEGIN DESCRIPTION:
Mapping XS dcc8290d
END DESCRIPTION:
XS GIS Cut Line= 4
      3579259.16     10432016.23      3578928.41     10431586.51
      3578480.49     10431503.18      3577994.16     10431797.06
#Sta/Elev= 30
  4094.8  335.03  4146.1  332.32  4245.7  331.23  4359.9  331.70  4388.9  330.93
  4509.4  332.66  4735.0  331.93  4785.9  332.82  4877.4  331.92  4948.6  332.64
  5004.7  325.84  5005.2  325.34  5014.6  325.84  5022.0  328.00  5050.3  330.80
  5141.1  332.94  5259.4  335.07  5315.3  335.49  5367.7  339.05  5441.3  345.12
  5526.8  354.58  5563.7  357.42  5579.2  357.53  5585.1  358.65  5616.1  358.51
  5621.9  359.73  5637.4  358.26  5643.3  359.38  5658.8  357.89  5660.9  358.95
#Mann=5,-1,0
  4094.8    0.05       0  5004.7    0.03       0  5014.6    0.05       0
  5141.1     0.1       0  5259.4    0.16       0
Bank Sta=5004.7,5014.6
Exp/Cntr=0.3,0.1

Type RM Length L Ch R = 1,1215,466,466,466
BEGIN DESCRIPTION:
Mapping XS 348a9188
END DESCRIPTION:
XS GIS Cut Line= 3
      3579277.37     10432000.57      3578972.68     10431266.20
      3578457.09     10431024.03
#Sta/Elev= 30
  3922.4  334.58  3986.2  331.50  4088.3  330.87  4185.3  331.50  4209.1  330.43
  4220.8  330.69  4278.5  331.82  4469.5  330.84  4605.1  331.63  4828.5  330.17
  4908.0  330.26  4976.4  331.25  4993.7  327.21  4999.3  326.40  5005.4  327.10
  5016.4  325.93  5017.1  324.67  5017.6  324.17  5026.6  324.17  5027.1  324.67
  5027.6  328.94  5038.5  330.59  5044.9  332.43  5050.4  332.32  5067.7  334.09
  5096.0  335.66  5158.9  342.35  5187.3  344.24  5210.1  347.11  5287.1  352.19
#Mann=5,-1,0
  3922.4    0.05       0  4088.3    0.16       0  4220.8    0.05       0
  5017.1    0.03       0  5027.1    0.05       0
Bank Sta=5017.1,5027.1
Exp/Cntr=0.3,0.1

Type RM Length L Ch R = 1,749,0,0,0
BEGIN DESCRIPTION:
UNT0286 IN DUCK CR 1 0
END DESCRIPTION:
XS GIS Cut Line= 4
      3579334.67     10432044.86      3578954.45     10430734.95
      3578571.64     10430714.12      3578275.94     10430838.62
#Sta/Elev= 30
  3407.1  337.00  3502.5  331.20  3556.2  330.33  3569.3  328.67  3608.3  328.45
  3618.8  329.73  3685.9  330.71  3811.1  330.27  3837.4  331.30  4470.1  329.54
  4803.5  328.13  4983.7  329.85  4993.8  327.36  4998.8  324.56  4999.3  324.06
  5008.8  324.56  5013.8  324.76  5023.8  328.91  5033.8  329.70  5053.8  328.96
  5108.4  330.83  5156.3  335.54  5189.3  337.39  5236.8  343.41  5280.0  346.91
  5342.6  355.08  5366.3  362.27  5403.5  369.06  5436.1  370.63  5475.3  369.57
#Mann=8,-1,0
  3407.1    0.05       0  3569.3    0.16       0  3811.1    0.05       0
  4470.1    0.16       0  4998.8    0.03       0  5008.8    0.16       0
  5156.3     0.1       0  5280.0    0.16       0
Bank Sta=4998.8,5008.8
Exp/Cntr=0.3,0.1

Chan Stop Cuts=-1