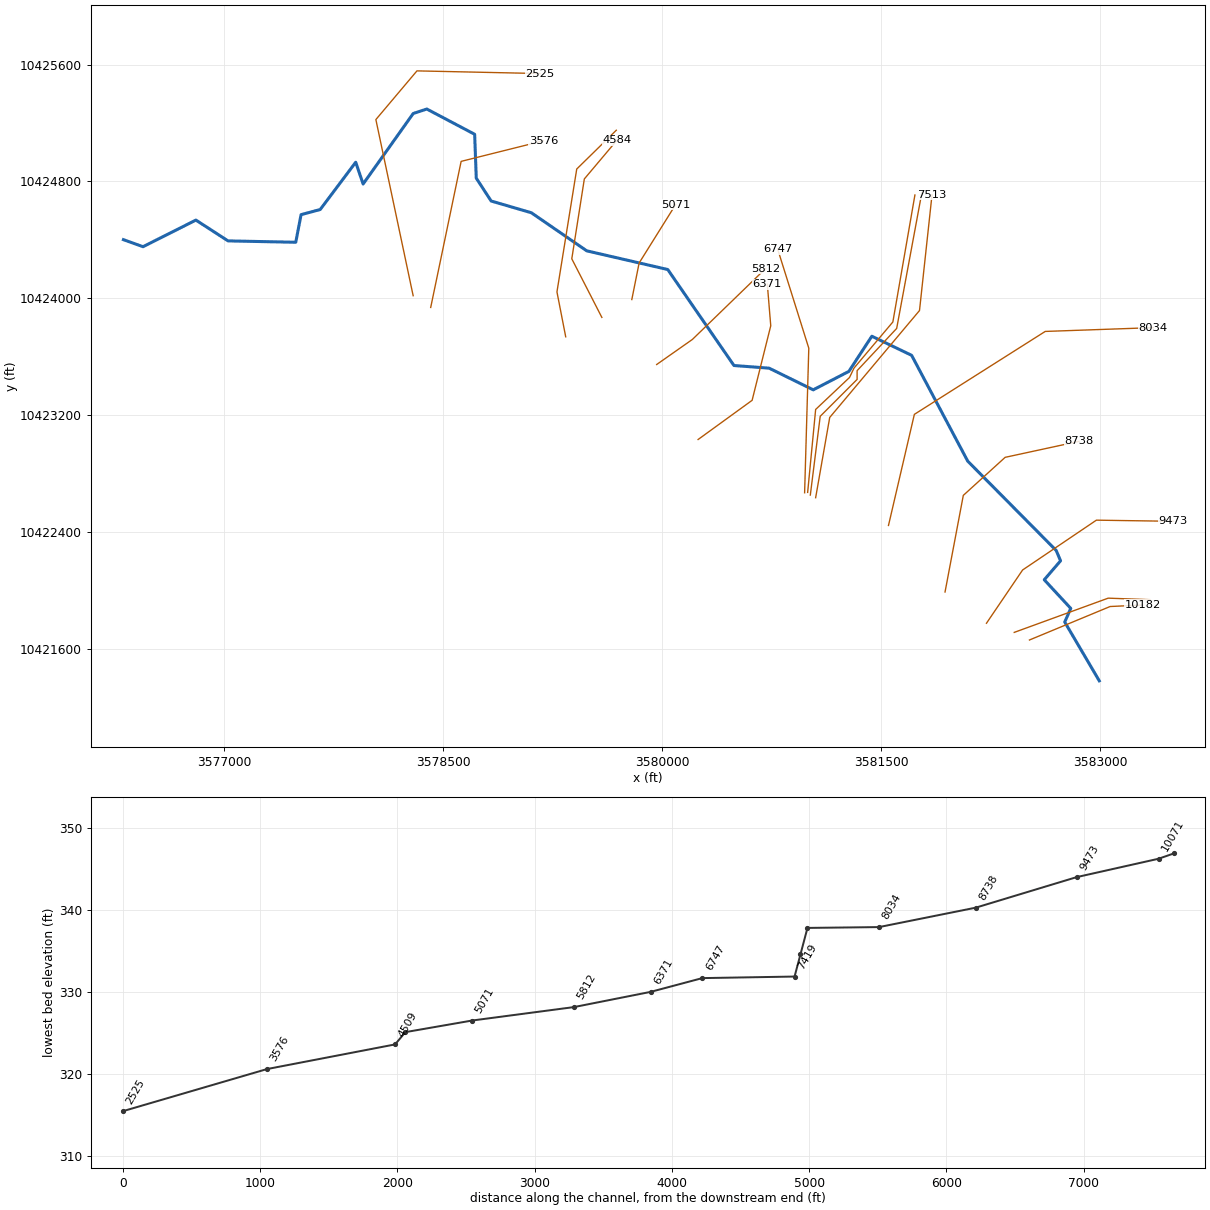
--- UNT0288 IN DUCK CR.prj (project) ---

Proj Title=UNT0288 IN DUCK CR Base Level Engineering
Current Plan=p01
Default Exp/Contr=0.3,0.1
English Units
Geom File=g01
Flow File=f01
Plan File=p01
BEGIN DESCRIPTION:
UNT0288 IN DUCK CR
END DESCRIPTION:

--- UNT0288 IN DUCK CR.p01 (plan) ---

Plan Title=Multiple Run
Short Identifier=Multiple
Geom File=g01
Flow File=f01
Subcritical Flow
K Sum by GR= 0
Std Step Tol= 0.01
Critical Tol= 0.01
Num of Std Step Trials= 20
Max Error Tol= 0.3
Flow Tol Ratio= 0.001
Split Flow NTrial= 30
Split Flow Tol= 0.02
Split Flow Ratio= 0.02
Log Output Level= 0
Friction Slope Method= 1
Unsteady Friction Slope Method= 2
Unsteady Bridges Friction Slope Method= 1
Parabolic Critical Depth
Global Vel Dist=  1 , 1 , 1
Global Log Level= 0
CheckData=True
Encroach Param= -1, 0, 0, 0
BEGIN DESCRIPTION:
Multiple Run
END DESCRIPTION:

--- UNT0288 IN DUCK CR.f01 (steady flow) ---

Flow Title=Multiple
Number of Profiles=7
Profile Names=10-year,25-year,50-year,1pct_min,100-year,1pct_plu,500-year
River Rch & RM= UNT0288 IN DUCK ,Reach-1,10182
    2033    2939    3727    3446    4661    6303    7269
River Rch & RM= UNT0288 IN DUCK ,Reach-1,4584
    2545    3714    4739    4405    5957    8056    9391
Boundary for River Rch & Prof#=UNT0288 IN DUCK ,Reach-1,1
Up Type=0
Dn Type=3
Dn Slope=0.005
Boundary for River Rch & Prof#=UNT0288 IN DUCK ,Reach-1,2
Up Type=0
Dn Type=3
Dn Slope=0.005
Boundary for River Rch & Prof#=UNT0288 IN DUCK ,Reach-1,3
Up Type=0
Dn Type=3
Dn Slope=0.005
Boundary for River Rch & Prof#=UNT0288 IN DUCK ,Reach-1,4
Up Type=0
Dn Type=3
Dn Slope=0.005
Boundary for River Rch & Prof#=UNT0288 IN DUCK ,Reach-1,5
Up Type=0
Dn Type=3
Dn Slope=0.005
Boundary for River Rch & Prof#=UNT0288 IN DUCK ,Reach-1,6
Up Type=0
Dn Type=3
Dn Slope=0.005
Boundary for River Rch & Prof#=UNT0288 IN DUCK ,Reach-1,7
Up Type=0
Dn Type=3
Dn Slope=0.005

--- UNT0288 IN DUCK CR.g01 (geometry) ---

Geom Title=Existing Conditions

River Reach=UNT0288 IN DUCK ,Reach-1
Reach XY= 30
      3582992.11     10421381.64      3582755.60     10421784.12
      3582796.91     10421877.48      3582615.46     10422073.42
      3582727.04     10422203.31      3582696.94     10422274.12
      3582091.64     10422885.37      3581707.50     10423609.95
      3581435.17     10423740.59      3581277.93     10423499.76
      3581034.02     10423373.64      3580732.10     10423521.94
      3580491.38     10423540.09      3580038.26     10424197.15
      3579483.55     10424325.14      3579104.43     10424585.85
      3578829.18     10424666.25      3578727.32     10424822.72
      3578716.34     10425122.97      3578388.80     10425295.80
      3578295.69     10425265.28      3577952.81     10424782.57
      3577902.11     10424931.64      3577659.07     10424608.02
      3577528.08     10424572.86      3577491.67     10424383.81
      3577027.99     10424393.18      3576808.14     10424535.61
      3576446.33     10424353.49      3576312.11     10424401.64

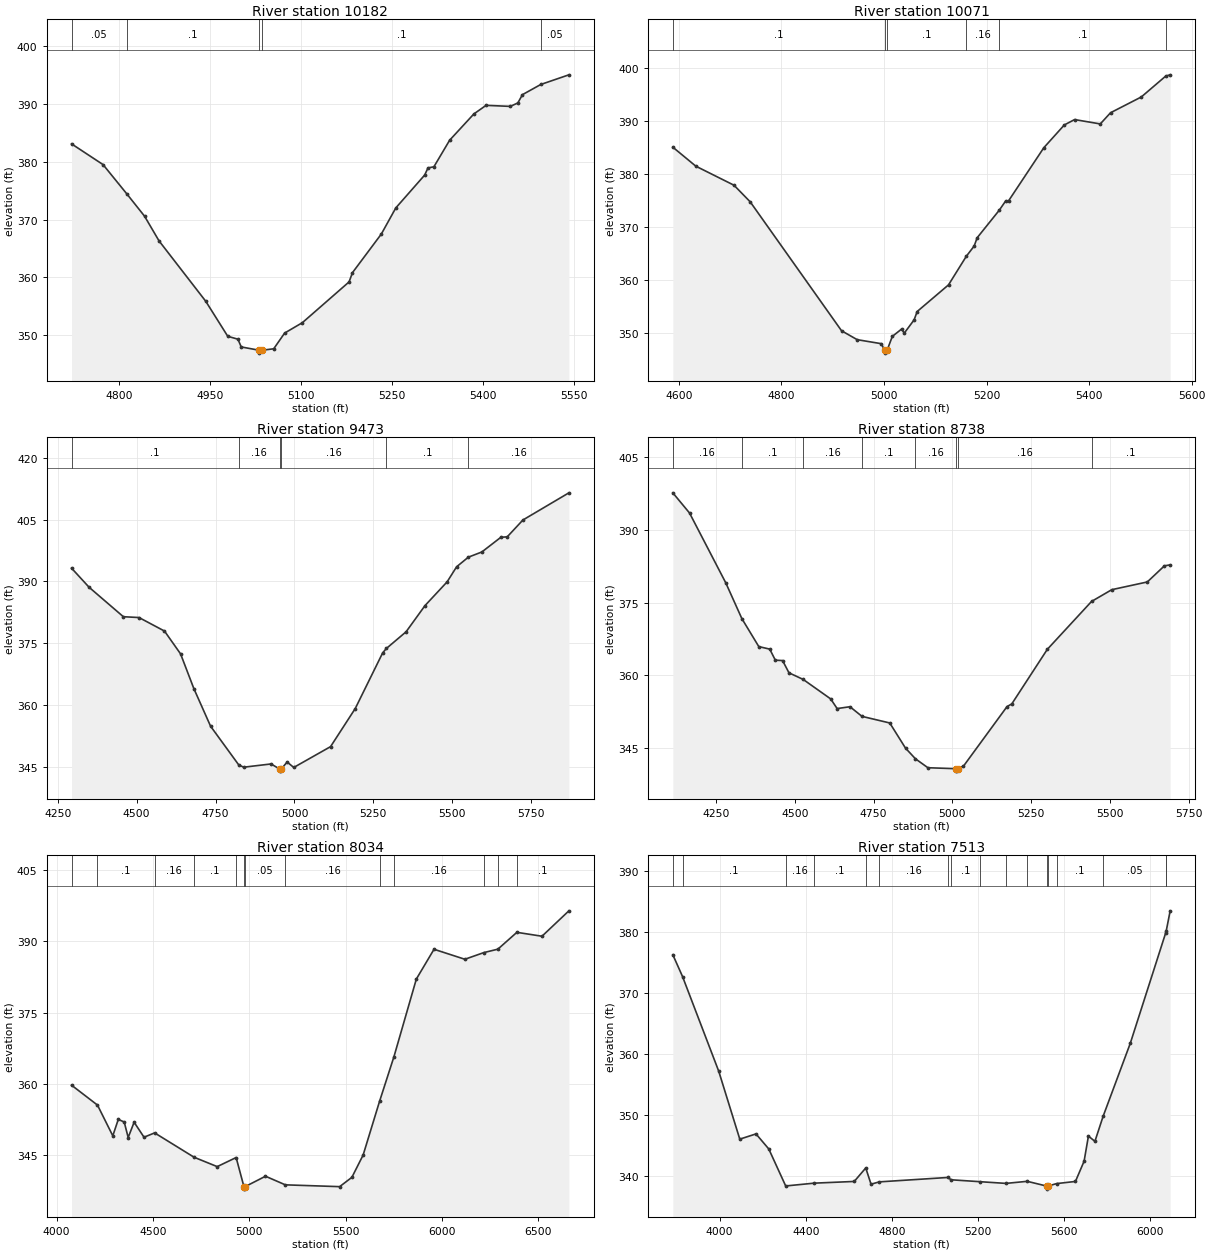
Type RM Length L Ch R = 1,10182,111,111,111
BEGIN DESCRIPTION:
UNT0288 IN DUCK CR 3 0
END DESCRIPTION:
XS GIS Cut Line= 3
      3582514.10     10421661.18      3583066.14     10421890.33
      3583288.59     10421900.68
#Sta/Elev= 30
  4720.9  383.10  4772.9  379.51  4812.3  374.42  4841.4  370.58  4865.2  366.32
  4942.3  355.87  4978.6  349.81  4995.4  349.31  5000.8  347.97  5030.4  347.40
  5030.7  346.90  5035.1  347.40  5054.4  347.65  5072.4  350.37  5101.7  352.17
  5178.7  359.22  5184.3  360.82  5231.9  367.50  5255.8  372.02  5303.4  377.70
  5308.9  378.94  5318.6  379.13  5344.6  383.73  5384.6  388.28  5404.7  389.76
  5444.7  389.58  5457.1  390.18  5464.7  391.61  5494.9  393.37  5541.3  395.04
#Mann=5,-1,0
  4720.9    0.05       0  4812.3     0.1       0  5030.4    0.07       0
  5035.1     0.1       0  5494.9    0.05       0
Bank Sta=5030.4,5035.1
Exp/Cntr=0.3,0.1

Type RM Length L Ch R = 1,10071,598,598,598
BEGIN DESCRIPTION:
Mapping XS 45885eda
END DESCRIPTION:
XS GIS Cut Line= 3
      3582409.91     10421713.26      3583053.12     10421947.62
      3583338.36     10421937.25
#Sta/Elev= 30
  4588.1  385.14  4633.0  381.55  4707.5  377.95  4739.1  374.81  4917.2  350.47
  4947.7  348.79  4994.9  348.03  5001.2  346.75  5001.6  346.25  5005.9  346.75
  5016.2  349.41  5034.1  350.78  5039.5  350.03  5058.7  352.53  5064.7  354.11
  5125.8  359.14  5160.6  364.55  5175.8  366.47  5181.7  368.04  5224.8  373.24
  5237.5  375.02  5242.8  374.99  5311.7  385.04  5351.7  389.34  5371.7  390.35
  5421.8  389.53  5441.8  391.64  5501.8  394.62  5549.4  398.56  5558.1  398.80
#Mann=6,-1,0
  4588.1     0.1       0  5001.2    0.07       0  5005.9     0.1       0
  5160.6    0.16       0  5224.8     0.1       0  5549.4    0.05       0
Bank Sta=5001.2,5005.9
Exp/Cntr=0.3,0.1

Type RM Length L Ch R = 1,9473,735,735,735
BEGIN DESCRIPTION:
UNT0288 IN DUCK CR 2 0
END DESCRIPTION:
XS GIS Cut Line= 4
      3582219.79     10421775.75      3582467.18     10422140.33
      3582972.39     10422481.48      3583497.74     10422473.68
#Sta/Elev= 30
  4293.8  393.22  4349.3  388.59  4458.0  381.44  4507.6  381.24  4588.3  377.96
  4639.2  372.43  4681.2  364.03  4734.3  354.89  4823.4  345.52  4839.0  344.95
  4925.9  345.74  4953.4  344.50  4953.7  344.00  4958.1  344.50  4976.8  346.21
  4997.8  344.89  5114.4  349.94  5192.6  359.18  5279.5  372.68  5291.2  373.74
  5353.7  377.79  5413.7  384.15  5483.7  389.90  5513.7  393.55  5550.9  395.88
  5593.7  397.14  5653.7  400.69  5674.2  400.82  5723.7  404.89  5869.4  411.48
#Mann=6,-1,0
  4293.8     0.1       0  4823.4    0.16       0  4953.4    0.07       0
  4958.1    0.16       0  5291.2     0.1       0  5550.9    0.16       0
Bank Sta=4953.4,4958.1
Exp/Cntr=0.3,0.1

Type RM Length L Ch R = 1,8738,704,704,704
BEGIN DESCRIPTION:
UNT0288 IN DUCK CR 16 0
END DESCRIPTION:
XS GIS Cut Line= 4
      3581936.28     10421989.61      3582061.29     10422651.11
      3582347.75     10422911.52      3582853.00     10423020.91
#Sta/Elev= 30
  4113.5  397.66  4166.5  393.50  4281.5  379.09  4332.4  371.73  4386.2  365.95
  4420.9  365.43  4438.6  363.15  4461.6  363.07  4481.9  360.54  4526.9  359.18
  4614.2  355.16  4634.6  353.17  4675.3  353.55  4713.5  351.56  4801.5  350.20
  4851.5  345.01  4883.0  342.81  4922.5  340.97  5011.9  340.77  5012.3  340.27
  5016.8  340.77  5035.3  341.30  5173.4  353.58  5188.5  354.13  5301.1  365.38
  5441.4  375.26  5505.7  377.69  5618.3  379.28  5672.6  382.61  5690.8  382.80
#Mann=8,-1,0
  4113.5    0.16       0  4332.4     0.1       0  4526.9    0.16       0
  4713.5     0.1       0  4883.0    0.16       0  5011.9    0.07       0
  5016.8    0.16       0  5441.4     0.1       0
Bank Sta=5011.9,5016.8
Exp/Cntr=0.3,0.1

Type RM Length L Ch R = 1,8034,521,521,521
BEGIN DESCRIPTION:
UNT0288 IN DUCK CR 15 0
END DESCRIPTION:
XS GIS Cut Line= 4
      3581549.18     10422445.27      3581726.26     10423205.69
      3582622.09     10423773.40      3583361.70     10423799.44
#Sta/Elev= 30
  4077.2  359.75  4211.9  355.56  4291.4  349.10  4319.9  352.56  4350.7  352.00
  4371.2  348.75  4402.0  351.96  4453.4  348.81  4508.5  349.72  4713.3  344.60
  4833.3  342.63  4931.5  344.54  4972.1  338.40  4972.5  337.90  4977.0  338.40
  5083.9  340.61  5187.0  338.80  5468.7  338.42  5532.3  340.38  5590.7  345.07
  5675.8  356.34  5750.5  365.72  5866.9  382.06  5958.6  388.31  6118.7  386.21
  6216.9  387.61  6289.9  388.33  6388.6  391.87  6518.9  391.05  6658.6  396.39
#Mann=13,-1,0
  4077.2    0.16       0  4211.9     0.1       0  4508.5    0.16       0
  4713.3     0.1       0  4931.5    0.05       0  4972.1   0.033       0
  4977.0    0.05       0  5187.0    0.16       0  5675.8     0.1       0
  5750.5    0.16       0  6216.9     0.1       0  6289.9    0.16       0
  6388.6     0.1       0
Bank Sta=4972.1,4977
Exp/Cntr=0.3,0.1

Type RM Length L Ch R = 1,7513,51,51,51
BEGIN DESCRIPTION:
UNT0288 IN DUCK CR 13 0
END DESCRIPTION:
XS GIS Cut Line= 4
      3581050.51     10422635.09      3581146.87     10423184.60
      3581761.46     10423916.37      3581847.25     10424709.33
#Sta/Elev= 30
  3782.5  376.26  3827.6  372.68  3995.8  357.15  4093.7  346.00  4169.0  346.86
  4228.4  344.39  4307.0  338.32  4439.2  338.78  4625.5  339.06  4679.0  341.27
  4703.6  338.61  4742.1  338.99  5059.0  339.71  5076.7  339.33  5209.7  339.02
  5330.3  338.74  5429.4  339.08  5520.0  338.30  5520.4  337.80  5525.3  338.30
  5566.2  338.71  5653.4  339.06  5693.6  342.38  5713.7  346.50  5743.9  345.64
  5781.7  349.72  5908.1  361.71  6073.0  379.87  6074.8  380.08  6093.6  383.46
#Mann=17,-1,0
  3782.5    0.16       0  3827.6     0.1       0  4307.0    0.16       0
  4439.2     0.1       0  4679.0    0.05       0  4742.1    0.16       0
  5059.0    0.05       0  5076.7     0.1       0  5209.7    0.05       0
  5330.3     0.1       0  5429.4    0.16       0  5520.0    0.07       0
  5525.3    0.16       0  5566.2     0.1       0  5781.7    0.05       0
  6073.0     0.1       0  6074.8    0.05       0
Bank Sta=5520,5525.3
Exp/Cntr=0.3,0.1

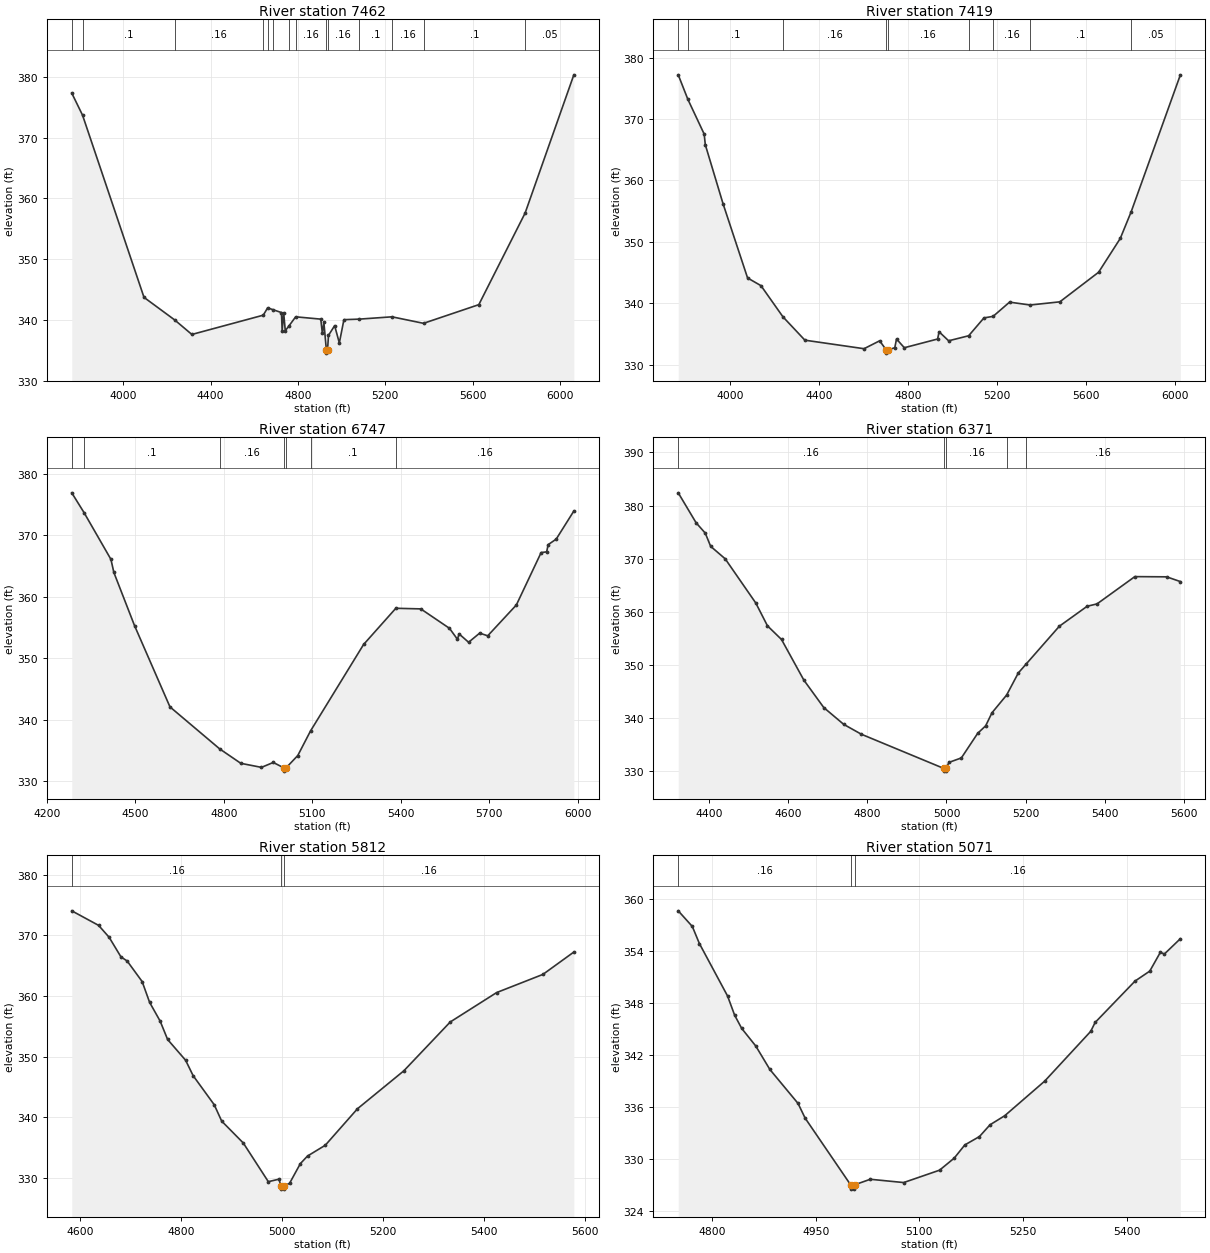
Type RM Length L Ch R = 1,7462,43,43,43
BEGIN DESCRIPTION:
Mapping XS 4437eced
END DESCRIPTION:
XS GIS Cut Line= 6
      3581014.06     10422653.38      3581081.77     10423192.41
      3581334.37     10423445.02      3581334.37     10423504.91
      3581605.21     10423793.98      3581777.08     10424721.06
#Sta/Elev= 30
  3764.6  377.33  3814.0  373.69  4095.4  343.74  4235.8  340.03  4314.6  337.64
  4641.6  340.81  4661.7  342.02  4684.5  341.73  4725.0  341.24  4728.2  338.23
  4735.0  341.22  4742.4  338.26  4757.8  338.97  4790.0  340.54  4905.0  340.16
  4912.3  337.80  4919.2  339.62  4930.7  335.07  4931.1  334.57  4936.0  335.07
  4940.2  337.48  4968.5  339.09  4990.0  336.25  5011.0  340.07  5080.9  340.16
  5231.1  340.54  5375.5  339.47  5628.8  342.54  5840.8  357.60  6064.0  380.33
#Mann=14,-1,0
  3764.6    0.16       0  3814.0     0.1       0  4235.8    0.16       0
  4641.6     0.1       0  4661.7    0.05       0  4684.5    0.16       0
  4757.8    0.05       0  4790.0    0.16       0  4930.7    0.07       0
  4936.0    0.16       0  5080.9     0.1       0  5231.1    0.16       0
  5375.5     0.1       0  5840.8    0.05       0
Bank Sta=4930.7,4936
Exp/Cntr=0.3,0.1

Type RM Length L Ch R = 1,7419,672,672,672
BEGIN DESCRIPTION:
Mapping XS b5da56fc
END DESCRIPTION:
XS GIS Cut Line= 6
      3580995.83     10422671.60      3581050.52     10423239.29
      3581282.29     10423458.04      3581313.54     10423523.14
      3581579.16     10423838.25      3581730.09     10424707.38
#Sta/Elev= 30
  3767.8  377.21  3811.0  373.22  3884.4  367.55  3889.4  365.82  3968.8  356.24
  4079.3  344.11  4139.6  342.85  4238.1  337.78  4336.8  333.97  4602.5  332.58
  4672.7  333.87  4702.5  332.36  4702.9  331.86  4707.9  332.36  4740.6  332.74
  4748.4  334.16  4783.5  332.74  4933.0  334.16  4939.6  335.34  4982.5  333.87
  5072.5  334.69  5141.2  337.60  5182.3  337.85  5256.2  340.17  5348.6  339.70
  5482.2  340.22  5656.2  345.04  5753.6  350.55  5802.6  354.90  6023.3  377.18
#Mann=9,-1,0
  3767.8    0.16       0  3811.0     0.1       0  4238.1    0.16       0
  4702.5    0.07       0  4707.9    0.16       0  5072.5     0.1       0
  5182.3    0.16       0  5348.6     0.1       0  5802.6    0.05       0
Bank Sta=4702.5,4707.9
Exp/Cntr=0.3,0.1

Type RM Length L Ch R = 1,6747,376,376,376
BEGIN DESCRIPTION:
UNT0288 IN DUCK CR 82 0
END DESCRIPTION:
XS GIS Cut Line= 3
      3580975.00     10422669.00      3581003.64     10423658.56
      3580790.35     10424337.46
#Sta/Elev= 30
  4284.8  376.94  4326.3  373.73  4417.5  366.12  4427.5  363.98  4497.5  355.34
  4617.6  342.12  4786.3  335.28  4857.7  332.94  4927.7  332.28  4967.7  333.08
  5004.9  332.17  5005.4  331.67  5010.5  332.17  5050.8  334.21  5093.9  338.20
  5273.8  352.27  5383.1  358.16  5467.7  358.06  5564.9  354.90  5592.0  353.11
  5597.3  354.00  5629.7  352.63  5667.3  354.12  5694.5  353.68  5791.6  358.70
  5875.5  367.22  5894.2  367.34  5899.4  368.51  5926.6  369.41  5986.4  373.98
#Mann=7,-1,0
  4284.8    0.16       0  4326.3     0.1       0  4786.3    0.16       0
  5004.9    0.07       0  5010.5    0.16       0  5093.9     0.1       0
  5383.1    0.16       0
Bank Sta=5004.9,5010.5
Exp/Cntr=0.3,0.1

Type RM Length L Ch R = 1,6371,559,559,559
BEGIN DESCRIPTION:
Mapping XS 7ef4347b
END DESCRIPTION:
XS GIS Cut Line= 4
      3580245.87     10423033.59      3580615.62     10423301.79
      3580743.23     10423812.21      3580719.79     10424096.03
#Sta/Elev= 30
  4322.8  382.40  4367.9  376.76  4391.1  374.81  4404.6  372.33  4441.4  369.97
  4518.7  361.64  4548.1  357.35  4583.6  354.78  4640.0  347.13  4690.3  341.96
  4740.6  338.80  4785.1  336.94  4993.6  330.49  4994.1  329.99  4998.9  329.99
  4999.3  330.49  5006.2  331.63  5037.7  332.48  5078.9  337.11  5099.0  338.52
  5115.0  340.98  5152.0  344.32  5181.4  348.47  5201.4  350.17  5285.1  357.28
  5355.3  361.04  5380.2  361.48  5475.7  366.62  5556.0  366.58  5590.5  365.69
#Mann=5,-1,0
  4322.8    0.16       0  4993.6    0.07       0  4999.3    0.16       0
  5152.0     0.1       0  5201.4    0.16       0
Bank Sta=4993.6,4999.3
Exp/Cntr=0.3,0.1

Type RM Length L Ch R = 1,5812,741,741,741
BEGIN DESCRIPTION:
UNT0288 IN DUCK CR 81 0
END DESCRIPTION:
XS GIS Cut Line= 3
      3579962.34     10423546.94      3580207.12     10423718.82
      3580707.09     10424203.16
#Sta/Elev= 30
  4583.2  374.05  4636.4  371.65  4657.3  369.68  4680.7  366.45  4693.0  365.77
  4722.7  362.38  4737.5  358.95  4758.4  355.85  4773.2  352.82  4808.9  349.39
  4823.7  346.86  4865.6  342.05  4880.4  339.35  4923.2  335.74  4972.8  329.36
  4993.9  329.77  4998.0  328.63  4998.5  328.13  5003.3  328.13  5003.8  328.63
  5015.0  329.10  5036.3  332.34  5050.5  333.59  5085.7  335.37  5149.5  341.39
  5241.4  347.65  5333.4  355.71  5425.3  360.56  5517.1  363.56  5578.4  367.25
#Mann=3,-1,0
  4583.2    0.16       0  4998.0    0.07       0  5003.8    0.16       0
Bank Sta=4998,5003.8
Exp/Cntr=0.3,0.1

Type RM Length L Ch R = 1,5071,487,487,487
BEGIN DESCRIPTION:
UNT0288 IN DUCK CR 8 0
END DESCRIPTION:
XS GIS Cut Line= 3
      3579792.10     10423991.61      3579842.11     10424241.64
      3580092.12     10424641.66
#Sta/Elev= 30
  4750.9  358.67  4771.3  356.86  4781.5  354.89  4822.3  348.82  4832.5  346.61
  4842.7  345.08  4863.1  343.04  4883.5  340.33  4924.3  336.40  4934.5  334.71
  5000.4  326.99  5000.9  326.49  5005.8  326.49  5006.2  326.99  5028.9  327.63
  5077.2  327.25  5129.1  328.68  5150.3  330.07  5165.7  331.60  5186.9  332.57
  5202.2  333.93  5223.5  334.98  5281.2  338.97  5347.9  344.73  5354.3  345.76
  5412.1  350.55  5433.4  351.70  5448.7  353.87  5454.6  353.68  5477.6  355.44
#Mann=3,-1,0
  4750.9    0.16       0  5000.4    0.07       0  5006.2    0.16       0
Bank Sta=5000.4,5006.2
Exp/Cntr=0.3,0.1

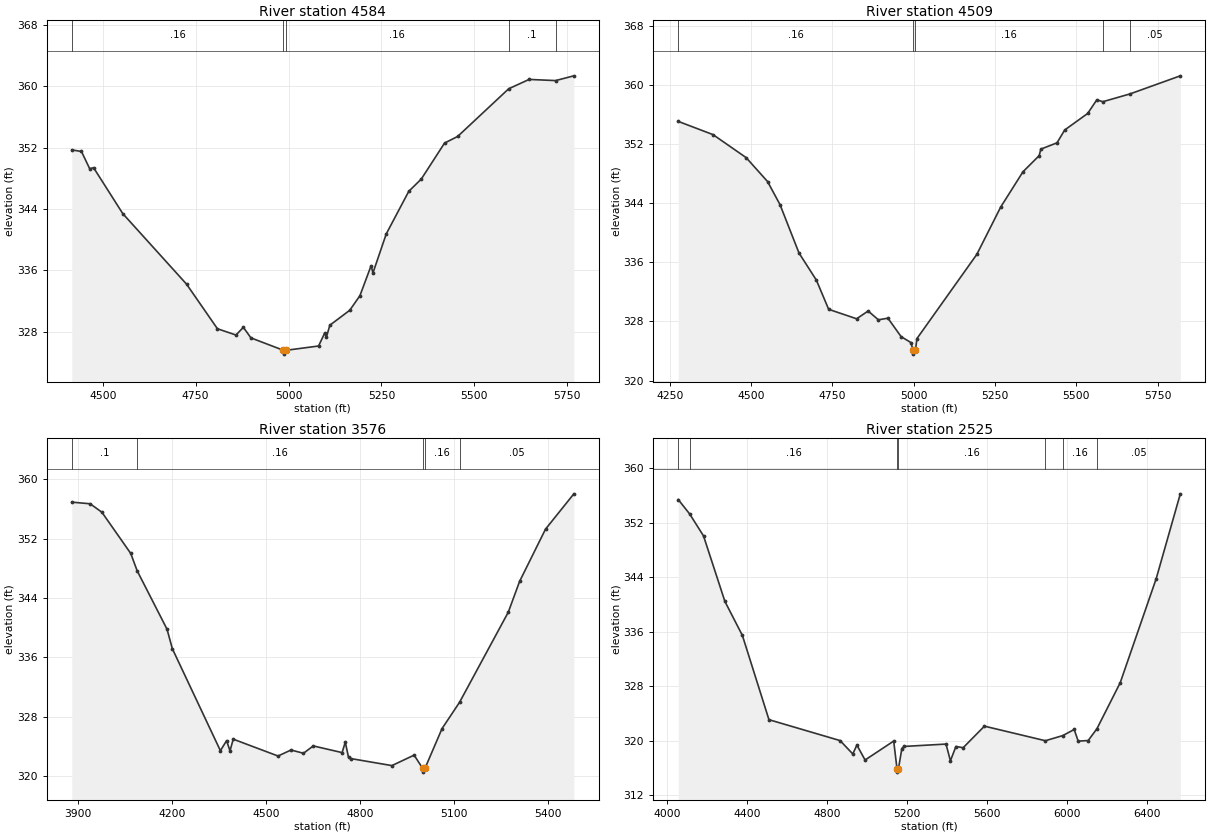
Type RM Length L Ch R = 1,4584,75,75,75
BEGIN DESCRIPTION:
UNT0288 IN DUCK CR 7 0
END DESCRIPTION:
XS GIS Cut Line= 4
      3579587.00     10423869.46      3579381.25     10424270.54
      3579467.18     10424817.41      3579691.14     10425083.04
#Sta/Elev= 30
  4416.4  351.71  4442.5  351.50  4464.7  349.25  4475.1  349.39  4553.7  343.40
  4725.4  334.20  4808.6  328.38  4858.6  327.56  4878.4  328.57  4898.7  327.19
  4986.2  325.57  4986.7  325.07  4993.4  325.57  5080.9  326.13  5097.1  327.79
  5102.2  327.31  5111.2  328.84  5164.8  330.79  5192.2  332.69  5222.3  336.60
  5227.3  335.66  5263.1  340.75  5323.8  346.31  5357.5  347.91  5420.1  352.60
  5455.3  353.46  5592.7  359.68  5647.7  360.90  5719.1  360.75  5768.2  361.37
#Mann=5,-1,0
  4416.4    0.16       0  4986.2    0.07       0  4993.4    0.16       0
  5592.7     0.1       0  5719.1    0.05       0
Bank Sta=4986.2,4993.4
Exp/Cntr=0.3,0.1

Type RM Length L Ch R = 1,4509,933,933,933
BEGIN DESCRIPTION:
Mapping XS 36f1288d
END DESCRIPTION:
XS GIS Cut Line= 4
      3579339.59     10423736.65      3579279.68     10424043.98
      3579415.10     10424885.12      3579685.91     10425150.72
#Sta/Elev= 30
  4275.5  355.04  4382.5  353.25  4484.4  350.14  4550.2  346.91  4588.6  343.78
  4647.0  337.24  4700.5  333.57  4738.2  329.63  4824.2  328.35  4859.7  329.40
  4891.1  328.21  4920.5  328.43  4961.0  325.94  4991.4  325.13  4997.9  324.07
  4998.4  323.57  5005.1  324.07  5009.7  325.67  5194.0  337.06  5267.2  343.44
  5335.8  348.22  5385.8  350.41  5390.9  351.29  5440.6  352.14  5464.4  353.88
  5534.9  356.11  5563.2  357.96  5581.5  357.70  5664.9  358.75  5819.9  361.20
#Mann=5,-1,0
  4275.5    0.16       0  4997.9    0.07       0  5005.1    0.16       0
  5581.5     0.1       0  5664.9    0.05       0
Bank Sta=4997.9,5005.1
Exp/Cntr=0.3,0.1

Type RM Length L Ch R = 1,3576,1051,1051,1051
BEGIN DESCRIPTION:
UNT0288 IN DUCK CR 5 0
END DESCRIPTION:
XS GIS Cut Line= 3
      3578415.46     10423937.60      3578623.79     10424937.57
      3579186.34     10425078.20
#Sta/Elev= 30
  3881.5  356.92  3940.2  356.70  3977.6  355.56  4069.5  350.02  4090.0  347.68
  4185.3  339.81  4202.3  337.18  4355.5  323.45  4375.3  324.80  4386.2  323.42
  4396.4  325.00  4539.4  322.73  4580.7  323.54  4620.5  323.10  4651.7  324.09
  4743.7  323.19  4753.9  324.60  4764.1  322.56  4770.7  322.39  4902.5  321.44
  4973.4  322.85  5000.7  321.06  5001.2  320.56  5007.9  321.06  5062.5  326.43
  5118.2  329.96  5273.8  342.11  5309.9  346.26  5392.4  353.28  5482.8  358.04
#Mann=5,-1,0
  3881.5     0.1       0  4090.0    0.16       0  5000.7    0.07       0
  5007.9    0.16       0  5118.2    0.05       0
Bank Sta=5000.7,5007.9
Exp/Cntr=0.3,0.1

Type RM Length L Ch R = 1,2525,0,0,0
BEGIN DESCRIPTION:
UNT0288 IN DUCK CR 1 0
END DESCRIPTION:
XS GIS Cut Line= 4
      3578295.31     10424017.93      3578040.10     10425223.66
      3578321.35     10425557.00      3579162.48     10425538.77
#Sta/Elev= 30
  4056.7  355.43  4114.4  353.29  4183.1  350.09  4290.0  340.47  4377.4  335.48
  4510.2  323.11  4865.9  320.04  4929.3  318.08  4949.8  319.38  4990.7  317.19
  5133.8  319.97  5150.3  315.91  5150.8  315.41  5157.6  315.91  5174.6  318.87
  5184.9  319.18  5395.4  319.53  5417.3  317.07  5444.8  319.17  5481.2  319.00
  5587.4  322.16  5892.1  320.02  5979.4  320.78  6036.1  321.67  6056.1  319.96
  6106.1  320.05  6149.6  321.77  6266.2  328.54  6446.2  343.83  6566.6  356.27
#Mann=7,-1,0
  4056.7     0.1       0  4114.4    0.16       0  5150.3    0.07       0
  5157.6    0.16       0  5892.1    0.05       0  5979.4    0.16       0
  6149.6    0.05       0
Bank Sta=5150.3,5157.6
Exp/Cntr=0.3,0.1

Chan Stop Cuts=-1