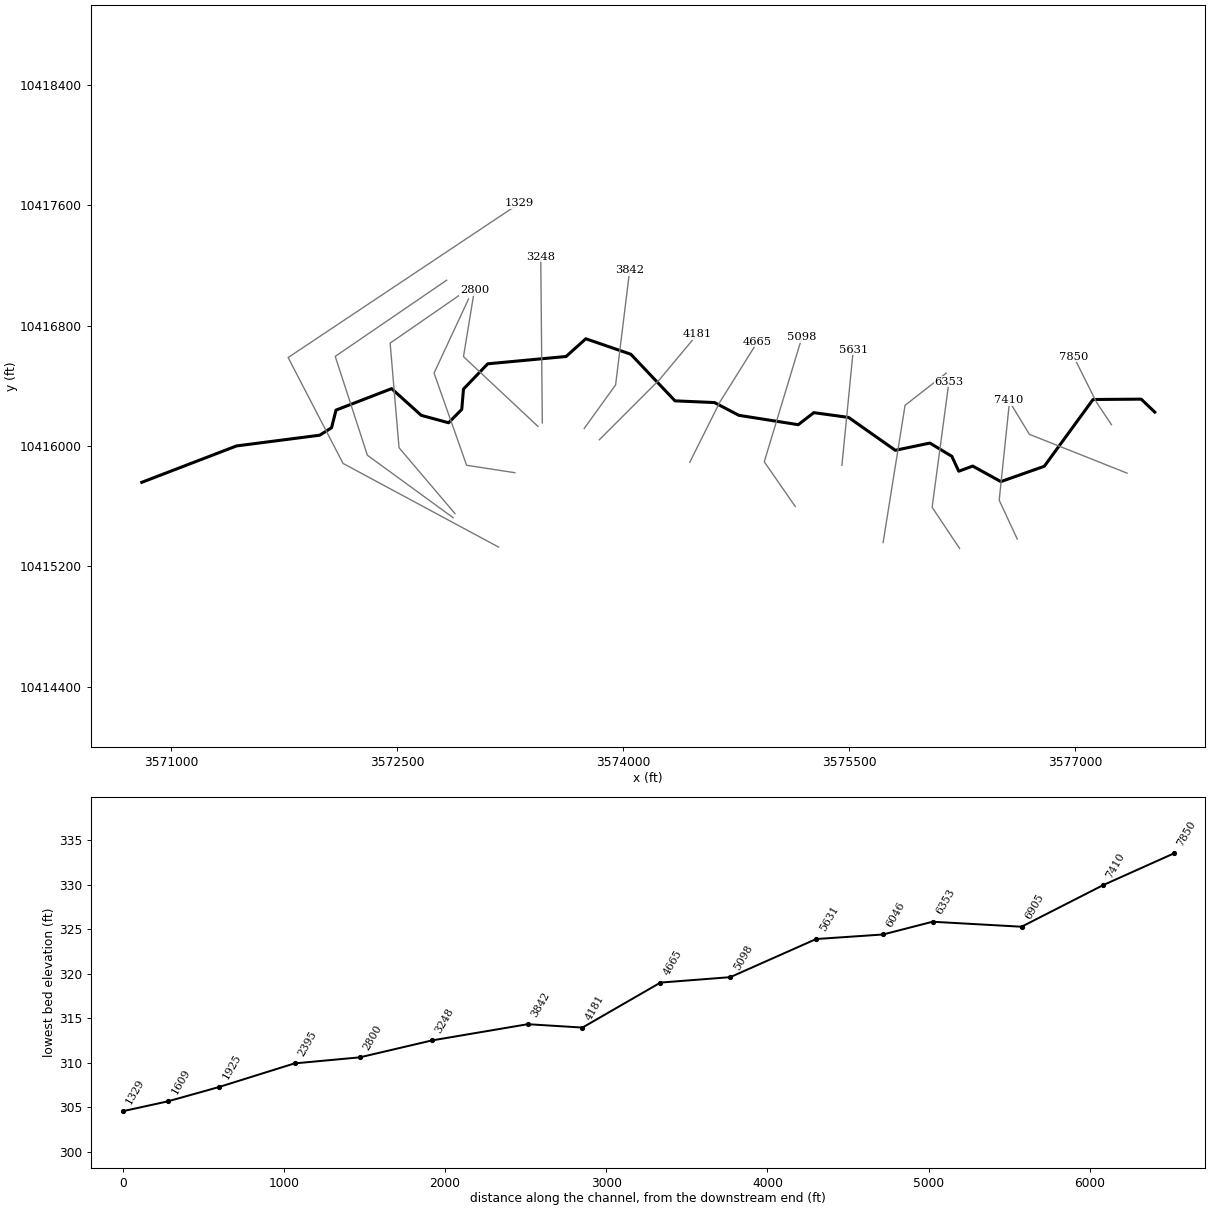
--- UNT0291 IN DUCK CR.prj (project) ---

Proj Title=UNT0291 IN DUCK CR Base Level Engineering
Current Plan=p01
Default Exp/Contr=0.3,0.1
English Units
Geom File=g01
Flow File=f01
Plan File=p01
BEGIN DESCRIPTION:
UNT0291 IN DUCK CR
END DESCRIPTION:

--- UNT0291 IN DUCK CR.p01 (plan) ---

Plan Title=Multiple Run
Short Identifier=Multiple
Geom File=g01
Flow File=f01
Subcritical Flow
K Sum by GR= 0
Std Step Tol= 0.01
Critical Tol= 0.01
Num of Std Step Trials= 20
Max Error Tol= 0.3
Flow Tol Ratio= 0.001
Split Flow NTrial= 30
Split Flow Tol= 0.02
Split Flow Ratio= 0.02
Log Output Level= 0
Friction Slope Method= 1
Unsteady Friction Slope Method= 2
Unsteady Bridges Friction Slope Method= 1
Parabolic Critical Depth
Global Vel Dist=  1 , 1 , 1
Global Log Level= 0
CheckData=True
Encroach Param= -1, 0, 0, 0
BEGIN DESCRIPTION:
Multiple Run
END DESCRIPTION:

--- UNT0291 IN DUCK CR.f01 (steady flow) ---

Flow Title=Multiple
Number of Profiles=7
Profile Names=10-year,25-year,50-year,1pct_min,100-year,1pct_plu,500-year
River Rch & RM= UNT0291 IN DUCK ,Reach-1,7850
    1965    2830    3578    3299    4462    6034    6919
River Rch & RM= UNT0291 IN DUCK ,Reach-1,4181
    2086    3001    3792    3491    4721    6384    7298
Boundary for River Rch & Prof#=UNT0291 IN DUCK ,Reach-1,1
Up Type=0
Dn Type=3
Dn Slope=0.005
Boundary for River Rch & Prof#=UNT0291 IN DUCK ,Reach-1,2
Up Type=0
Dn Type=3
Dn Slope=0.005
Boundary for River Rch & Prof#=UNT0291 IN DUCK ,Reach-1,3
Up Type=0
Dn Type=3
Dn Slope=0.005
Boundary for River Rch & Prof#=UNT0291 IN DUCK ,Reach-1,4
Up Type=0
Dn Type=3
Dn Slope=0.005
Boundary for River Rch & Prof#=UNT0291 IN DUCK ,Reach-1,5
Up Type=0
Dn Type=3
Dn Slope=0.005
Boundary for River Rch & Prof#=UNT0291 IN DUCK ,Reach-1,6
Up Type=0
Dn Type=3
Dn Slope=0.005
Boundary for River Rch & Prof#=UNT0291 IN DUCK ,Reach-1,7
Up Type=0
Dn Type=3
Dn Slope=0.005

--- UNT0291 IN DUCK CR.g01 (geometry) ---

Geom Title=Existing Conditions

River Reach=UNT0291 IN DUCK ,Reach-1
Reach XY= 30
      3577529.72     10416225.01      3577439.57     10416311.16
      3577119.78     10416308.79      3576796.25     10415865.44
      3576507.83     10415763.53      3576321.10     10415866.70
      3576228.21     10415832.59      3576182.30     10415931.69
      3576036.36     10416019.45      3575807.12     10415971.52
      3575496.56     10416189.83      3575265.95     10416221.37
      3575162.53     10416141.46      3574768.01     10416203.78
      3574606.43     10416288.50      3574344.33     10416299.78
      3574051.04     10416609.24      3573752.15     10416712.06
      3573621.01     10416594.29      3573100.82     10416545.74
      3572939.90     10416377.91      3572928.47     10416243.12
      3572840.95     10416154.16      3572659.17     10416203.71
      3572462.65     10416380.91      3572093.47     10416238.36
      3572063.96     10416121.17      3571984.97     10416071.69
      3571432.73     10416000.43      3570804.11     10415758.91

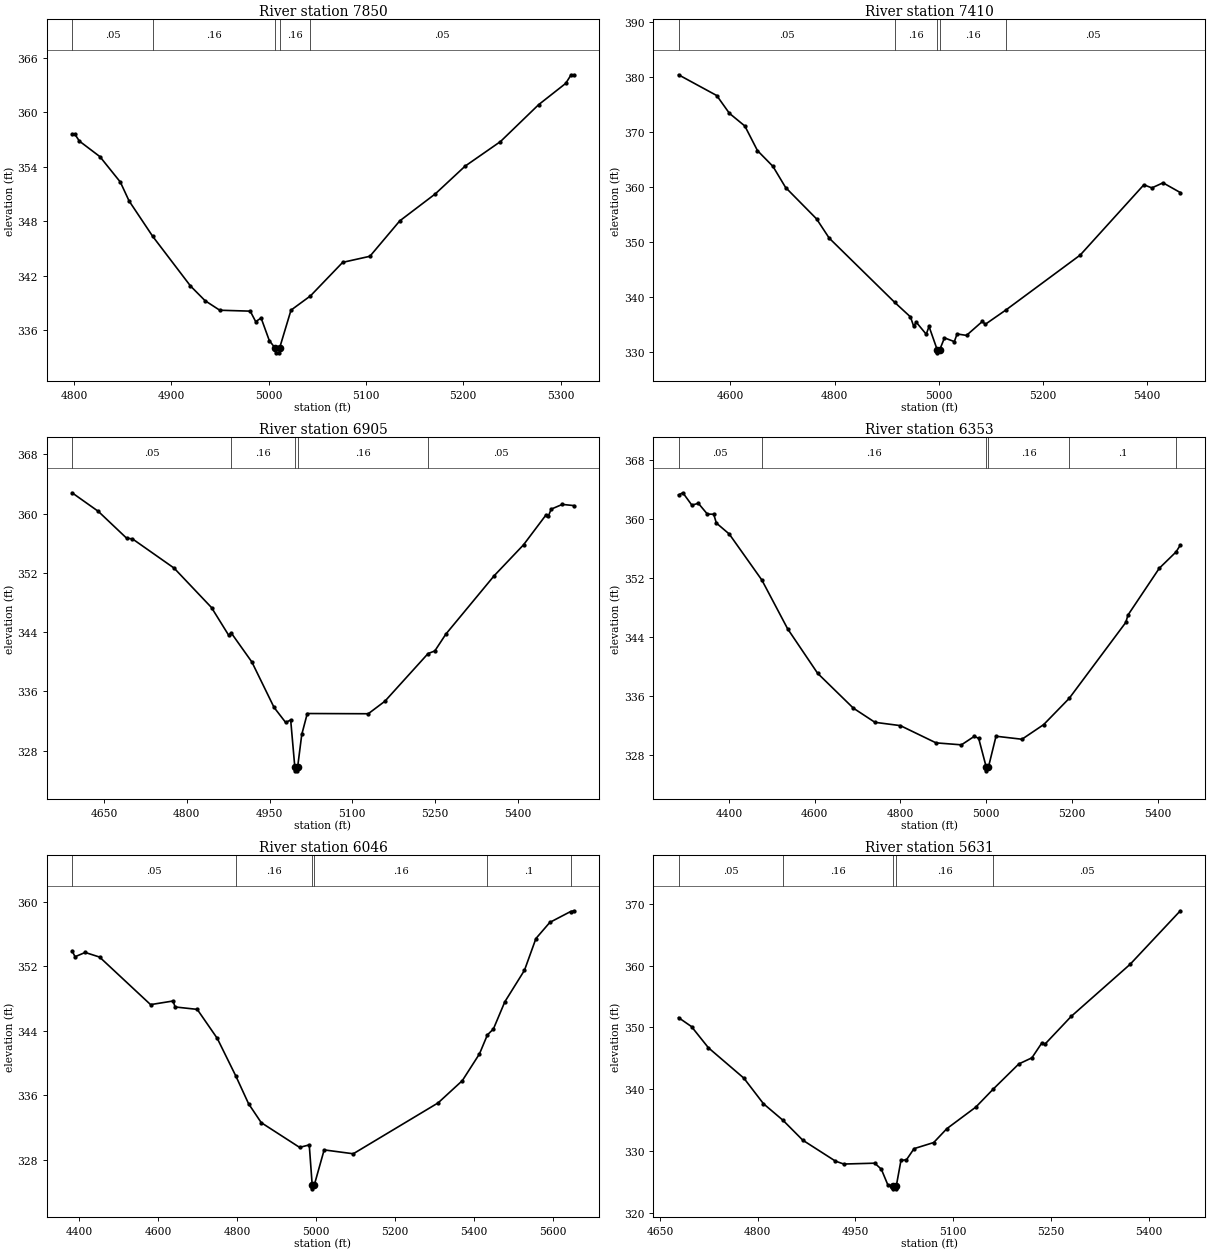
Type RM Length L Ch R = 1,7850,440,440,440
BEGIN DESCRIPTION:
UNT0291 IN DUCK CR 3 0
END DESCRIPTION:
XS GIS Cut Line= 3
      3577242.12     10416141.62      3577142.11     10416291.64
      3576992.11     10416591.63
#Sta/Elev= 30
  4798.0  357.55  4801.0  357.55  4805.5  356.81  4826.6  355.10  4847.6  352.30
  4856.6  350.22  4880.9  346.32  4919.7  340.86  4934.7  339.24  4949.8  338.19
  4981.1  338.09  4986.7  336.94  4992.3  337.33  5000.7  334.85  5006.9  334.00
  5007.2  333.50  5010.9  333.50  5011.2  334.00  5023.0  338.20  5043.0  339.77
  5076.1  343.46  5104.1  344.13  5134.8  348.03  5171.2  350.99  5201.9  354.05
  5238.3  356.76  5277.4  360.81  5305.3  363.16  5310.9  364.11  5313.7  364.11
#Mann=5,-1,0
  4798.0    0.05       0  4880.9    0.16       0  5006.9    0.07       0
  5011.2    0.16       0  5043.0    0.05       0
Bank Sta=5006.9,5011.2
Exp/Cntr=0.3,0.1

Type RM Length L Ch R = 1,7410,505,505,505
BEGIN DESCRIPTION:
UNT0291 IN DUCK CR 2 0
END DESCRIPTION:
XS GIS Cut Line= 3
      3577345.73     10415819.78      3576697.32     10416077.58
      3576559.29     10416304.16
#Sta/Elev= 30
  4500.4  380.45  4573.7  376.68  4598.0  373.45  4627.7  371.14  4651.9  366.67
  4681.6  363.81  4705.9  359.97  4765.3  354.27  4789.6  350.77  4915.4  339.09
  4945.5  336.46  4951.5  334.82  4956.9  335.47  4975.8  333.31  4981.2  334.72
  4997.1  330.43  4997.4  329.93  5001.5  330.43  5010.8  332.65  5029.7  331.97
  5035.1  333.36  5053.1  333.10  5083.7  335.65  5089.1  335.11  5128.5  337.70
  5271.4  347.70  5393.5  360.46  5408.9  359.90  5430.3  360.82  5463.5  359.05
#Mann=5,-1,0
  4500.4    0.05       0  4915.4    0.16       0  4997.1    0.07       0
  5001.5    0.16       0  5128.5    0.05       0
Bank Sta=4997.1,5001.5
Exp/Cntr=0.3,0.1

Type RM Length L Ch R = 1,6905,552,552,552
BEGIN DESCRIPTION:
UNT0291 IN DUCK CR 15 0
END DESCRIPTION:
XS GIS Cut Line= 3
      3576616.59     10415382.26      3576496.80     10415640.08
      3576561.91     10416262.49
#Sta/Elev= 30
  4591.8  362.82  4639.4  360.31  4690.7  356.69  4701.4  356.59  4776.8  352.65
  4844.7  347.32  4876.1  343.55  4880.3  343.91  4917.9  339.97  4958.1  333.84
  4979.2  331.80  4988.3  332.14  4995.8  325.77  4996.2  325.27  5000.5  325.27
  5000.9  325.77  5008.4  330.18  5018.4  333.01  5129.0  332.98  5159.2  334.67
  5237.5  341.11  5249.7  341.46  5269.8  343.74  5357.4  351.62  5410.6  355.79
  5450.7  359.76  5455.8  359.70  5460.8  360.61  5480.9  361.25  5501.9  361.09
#Mann=5,-1,0
  4591.8    0.05       0  4880.3    0.16       0  4995.8    0.07       0
  5000.9    0.16       0  5237.5    0.05       0
Bank Sta=4995.8,5000.9
Exp/Cntr=0.3,0.1

Type RM Length L Ch R = 1,6353,307,307,307
BEGIN DESCRIPTION:
UNT0291 IN DUCK CR 14 0
END DESCRIPTION:
XS GIS Cut Line= 3
      3576233.76     10415319.80      3576051.49     10415593.20
      3576163.30     10416427.86
#Sta/Elev= 30
  4282.2  363.30  4292.3  363.59  4313.3  361.91  4328.4  362.16  4349.4  360.70
  4364.4  360.67  4370.4  359.48  4400.5  357.99  4476.6  351.74  4536.8  345.11
  4606.8  339.07  4689.9  334.35  4740.4  332.42  4799.8  331.97  4882.9  329.63
  4942.2  329.36  4972.4  330.52  4982.5  330.23  5000.1  326.33  5000.5  325.83
  5005.2  326.33  5022.9  330.53  5083.4  330.12  5133.9  332.10  5193.6  335.67
  5325.6  345.98  5330.8  346.99  5403.8  353.34  5442.8  355.55  5452.9  356.48
#Mann=6,-1,0
  4282.2    0.05       0  4476.6    0.16       0  5000.1    0.07       0
  5005.2    0.16       0  5193.6     0.1       0  5442.8    0.05       0
Bank Sta=5000.1,5005.2
Exp/Cntr=0.3,0.1

Type RM Length L Ch R = 1,6046,415,415,415
BEGIN DESCRIPTION:
UNT0291 IN DUCK CR 13 0
END DESCRIPTION:
XS GIS Cut Line= 3
      3575725.97     10415358.85      3575871.80     10416270.29
      3576145.26     10416483.84
#Sta/Elev= 30
  4382.8  353.93  4390.3  353.19  4416.0  353.72  4452.4  353.15  4581.5  347.25
  4638.5  347.70  4643.5  346.96  4699.6  346.66  4750.2  343.07  4797.5  338.37
  4829.6  334.95  4861.6  332.61  4958.7  329.54  4983.1  329.85  4990.5  324.90
  4991.0  324.40  4996.0  324.90  5020.8  329.23  5094.5  328.75  5309.2  335.06
  5370.5  337.82  5413.9  341.14  5434.0  343.50  5449.1  344.22  5478.1  347.60
  5527.8  351.51  5556.8  355.45  5592.0  357.45  5644.3  358.79  5652.8  358.89
#Mann=6,-1,0
  4382.8    0.05       0  4797.5    0.16       0  4990.5    0.07       0
  4996.0    0.16       0  5434.0     0.1       0  5644.3    0.05       0
Bank Sta=4990.5,4996
Exp/Cntr=0.3,0.1

Type RM Length L Ch R = 1,5631,533,533,533
BEGIN DESCRIPTION:
UNT0291 IN DUCK CR 12 0
END DESCRIPTION:
XS GIS Cut Line= 2
      3575452.53     10415871.86      3575527.88     10416638.36
#Sta/Elev= 30
  4678.6  351.58  4698.5  350.13  4724.5  346.70  4778.9  341.79  4809.0  337.65
  4839.0  334.97  4869.3  331.76  4919.5  328.37  4932.2  327.90  4979.8  328.04
  4989.9  327.06  4999.9  324.52  5007.1  324.39  5007.6  323.89  5012.4  323.89
  5012.9  324.39  5020.0  328.48  5028.5  328.60  5040.1  330.39  5070.3  331.38
  5090.4  333.62  5134.9  337.11  5161.8  340.04  5200.9  344.09  5221.0  345.08
  5236.2  347.48  5241.3  347.32  5281.3  351.78  5371.7  360.20  5448.8  368.86
#Mann=5,-1,0
  4678.6    0.05       0  4839.0    0.16       0  5007.1    0.07       0
  5012.9    0.16       0  5161.8    0.05       0
Bank Sta=5007.1,5012.9
Exp/Cntr=0.3,0.1

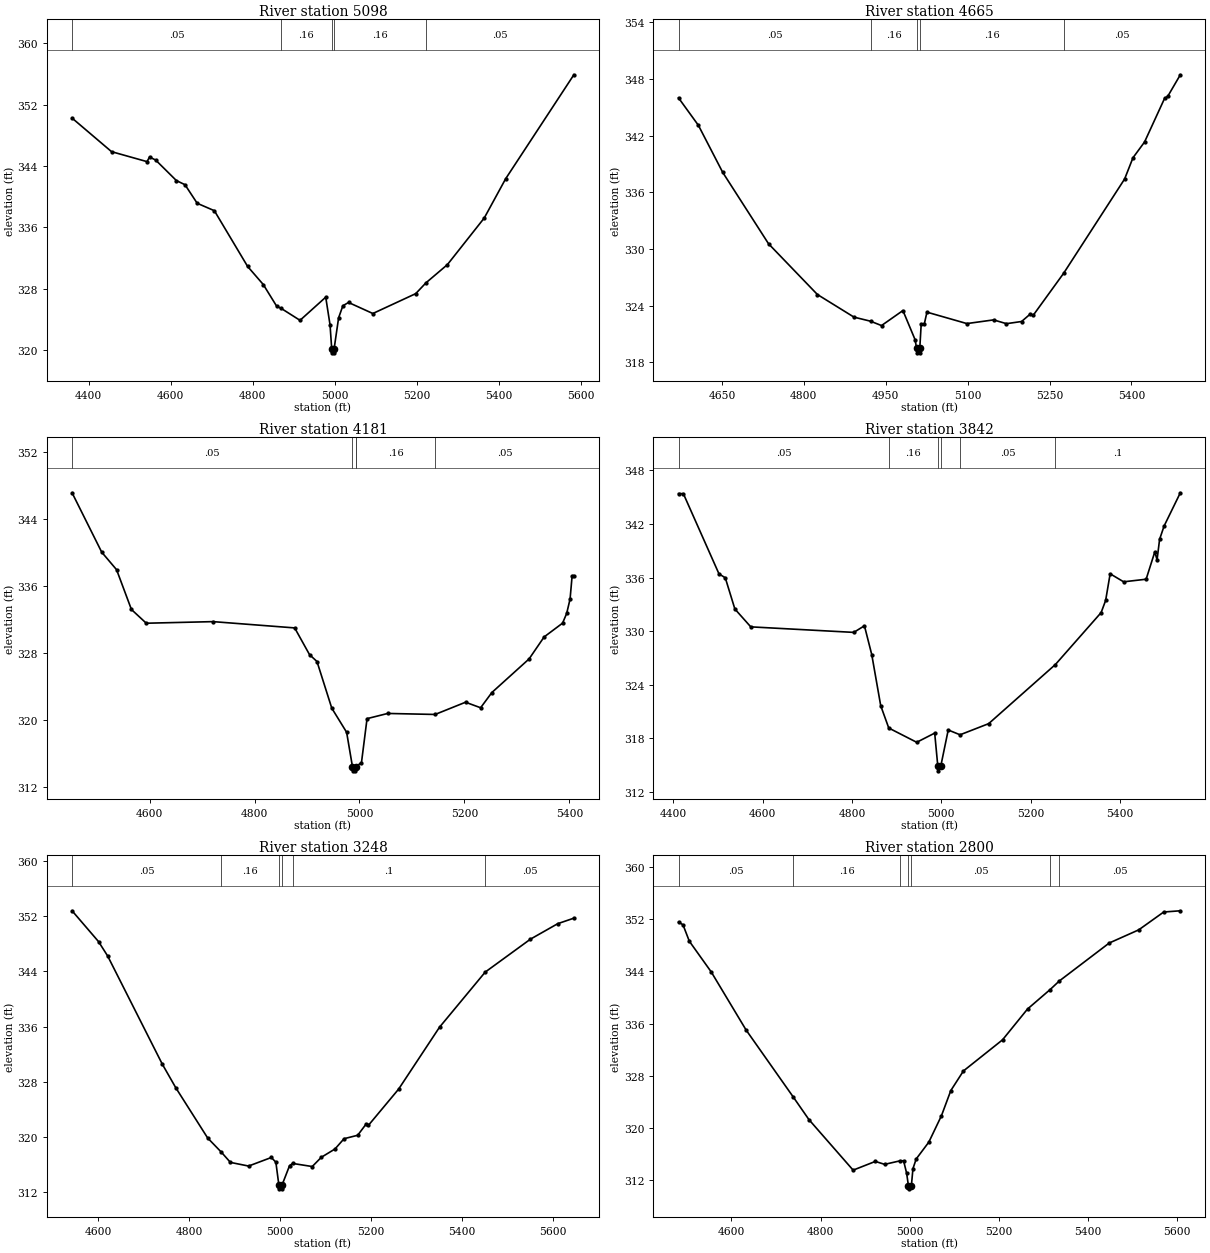
Type RM Length L Ch R = 1,5098,433,433,433
BEGIN DESCRIPTION:
UNT0291 IN DUCK CR 11 0
END DESCRIPTION:
XS GIS Cut Line= 3
      3575142.64     10415598.40      3574936.90     10415895.29
      3575186.89     10416720.76
#Sta/Elev= 30
  4359.9  350.23  4456.2  345.85  4542.7  344.55  4548.8  345.15  4563.7  344.76
  4614.3  342.08  4635.3  341.54  4665.0  339.12  4706.9  338.15  4788.0  330.88
  4826.2  328.52  4859.1  325.67  4869.2  325.43  4915.8  323.85  4978.5  326.87
  4989.0  323.26  4993.1  320.11  4993.5  319.61  4998.4  319.61  4998.9  320.11
  5009.9  324.18  5020.3  325.75  5034.1  326.18  5093.4  324.74  5197.9  327.33
  5222.9  328.74  5275.1  331.11  5365.1  337.20  5417.3  342.32  5583.6  355.88
#Mann=5,-1,0
  4359.9    0.05       0  4869.2    0.16       0  4993.1    0.07       0
  4998.9    0.16       0  5222.9    0.05       0
Bank Sta=4993.1,4998.9
Exp/Cntr=0.3,0.1

Type RM Length L Ch R = 1,4665,484,484,484
BEGIN DESCRIPTION:
UNT0291 IN DUCK CR 10 0
END DESCRIPTION:
XS GIS Cut Line= 3
      3574442.11     10415891.66      3574642.11     10416291.64
      3574892.11     10416691.65
#Sta/Elev= 30
  4570.6  346.01  4606.9  343.11  4651.6  338.11  4735.5  330.55  4824.9  325.18
  4892.0  322.78  4922.3  322.35  4942.3  321.89  4981.5  323.48  5003.8  320.39
  5006.5  319.50  5007.0  319.00  5011.9  319.00  5012.4  319.50  5015.0  322.07
  5020.7  322.07  5025.5  323.31  5098.6  322.10  5147.5  322.49  5171.1  322.09
  5198.8  322.32  5214.1  323.08  5220.0  322.97  5275.7  327.42  5387.5  337.42
  5402.8  339.67  5424.0  341.34  5460.6  345.95  5466.5  346.18  5489.5  348.46
#Mann=5,-1,0
  4570.6    0.05       0  4922.3    0.16       0  5006.5    0.07       0
  5012.4    0.16       0  5275.7    0.05       0
Bank Sta=5006.5,5012.4
Exp/Cntr=0.3,0.1

Type RM Length L Ch R = 1,4181,339,339,339
BEGIN DESCRIPTION:
UNT0291 IN DUCK CR 9 0
END DESCRIPTION:
XS GIS Cut Line= 3
      3573842.13     10416041.66      3574242.11     10416441.64
      3574492.13     10416741.67
#Sta/Elev= 30
  4452.3  347.14  4508.8  340.05  4537.1  337.96  4565.4  333.21  4593.7  331.57
  4721.0  331.76  4876.5  331.01  4904.8  327.82  4919.0  327.00  4947.2  321.43
  4975.5  318.55  4986.6  314.45  4987.1  313.95  4992.3  313.95  4992.8  314.45
  4993.8  314.49  5003.8  314.94  5014.4  320.18  5053.8  320.80  5144.1  320.68
  5202.1  322.14  5230.8  321.48  5252.3  323.30  5323.2  327.31  5351.8  329.93
  5387.0  331.58  5394.8  332.74  5401.3  334.46  5405.2  337.24  5408.5  337.24
#Mann=5,-1,0
  4452.3    0.05       0  4986.6    0.07       0  4992.8    0.05       0
  4993.8    0.16       0  5144.1    0.05       0
Bank Sta=4986.6,4992.8
Exp/Cntr=0.3,0.1

Type RM Length L Ch R = 1,3842,594,594,594
BEGIN DESCRIPTION:
UNT0291 IN DUCK CR 8 0
END DESCRIPTION:
XS GIS Cut Line= 3
      3573741.62     10416116.67      3573949.93     10416405.70
      3574043.55     10417167.70
#Sta/Elev= 30
  4411.3  345.41  4422.1  345.40  4501.9  336.41  4516.0  335.97  4537.5  332.47
  4573.1  330.47  4803.8  329.85  4827.7  330.59  4844.1  327.36  4864.2  321.63
  4882.2  319.13  4944.8  317.53  4985.1  318.56  4992.1  314.83  4992.6  314.33
  4998.6  314.83  5015.4  318.91  5041.9  318.37  5106.0  319.62  5255.5  326.25
  5357.9  332.07  5368.0  333.43  5378.1  336.42  5408.3  335.52  5458.7  335.81
  5478.1  338.87  5483.2  337.99  5488.9  340.29  5499.0  341.78  5535.3  345.50
#Mann=6,-1,0
  4411.3    0.05       0  4882.2    0.16       0  4992.1    0.07       0
  4998.6    0.16       0  5041.9    0.05       0  5255.5     0.1       0
Bank Sta=4992.1,4998.6
Exp/Cntr=0.3,0.1

Type RM Length L Ch R = 1,3248,448,448,448
BEGIN DESCRIPTION:
UNT0291 IN DUCK CR 7 0
END DESCRIPTION:
XS GIS Cut Line= 2
      3573463.24     10416153.37      3573452.83     10417257.12
#Sta/Elev= 30
  4541.9  352.78  4600.2  348.31  4620.2  346.23  4740.2  330.59  4770.2  327.13
  4840.2  319.87  4870.0  317.84  4890.2  316.34  4930.2  315.81  4980.2  317.05
  4990.2  316.37  4996.9  313.01  4997.4  312.51  5003.0  312.51  5003.5  313.01
  5020.2  315.85  5027.0  316.19  5070.2  315.74  5090.2  317.08  5120.2  318.28
  5140.2  319.77  5170.2  320.27  5188.7  321.89  5193.7  321.70  5260.2  326.95
  5350.2  335.92  5450.7  343.90  5550.2  348.67  5610.2  350.91  5645.7  351.71
#Mann=6,-1,0
  4541.9    0.05       0  4870.0    0.16       0  4996.9    0.07       0
  5003.5    0.16       0  5027.0     0.1       0  5450.7    0.05       0
Bank Sta=4996.9,5003.5
Exp/Cntr=0.3,0.1

Type RM Length L Ch R = 1,2800,405,405,405
BEGIN DESCRIPTION:
UNT0291 IN DUCK CR 6 0
END DESCRIPTION:
XS GIS Cut Line= 3
      3573434.57     10416129.98      3572939.80     10416593.50
      3573012.71     10417036.16
#Sta/Elev= 30
  4481.1  351.58  4491.1  351.16  4505.3  348.64  4554.6  343.91  4632.7  335.01
  4738.8  324.70  4773.9  321.24  4873.1  313.48  4922.9  314.82  4943.9  314.37
  4978.3  314.91  4986.4  314.92  4993.2  313.01  4997.2  311.11  4997.7  310.61
  5003.9  311.11  5007.4  313.71  5014.7  315.20  5043.1  317.79  5071.4  321.84
  5092.4  325.70  5120.7  328.71  5208.5  333.49  5264.6  338.22  5315.2  341.20
  5336.0  342.53  5448.1  348.36  5514.3  350.38  5570.4  353.12  5607.7  353.31
#Mann=7,-1,0
  4481.1    0.05       0  4738.8    0.16       0  4978.3    0.05       0
  4997.2    0.03       0  5003.9    0.05       0  5315.2     0.1       0
  5336.0    0.05       0
Bank Sta=4997.2,5003.9
Exp/Cntr=0.3,0.1

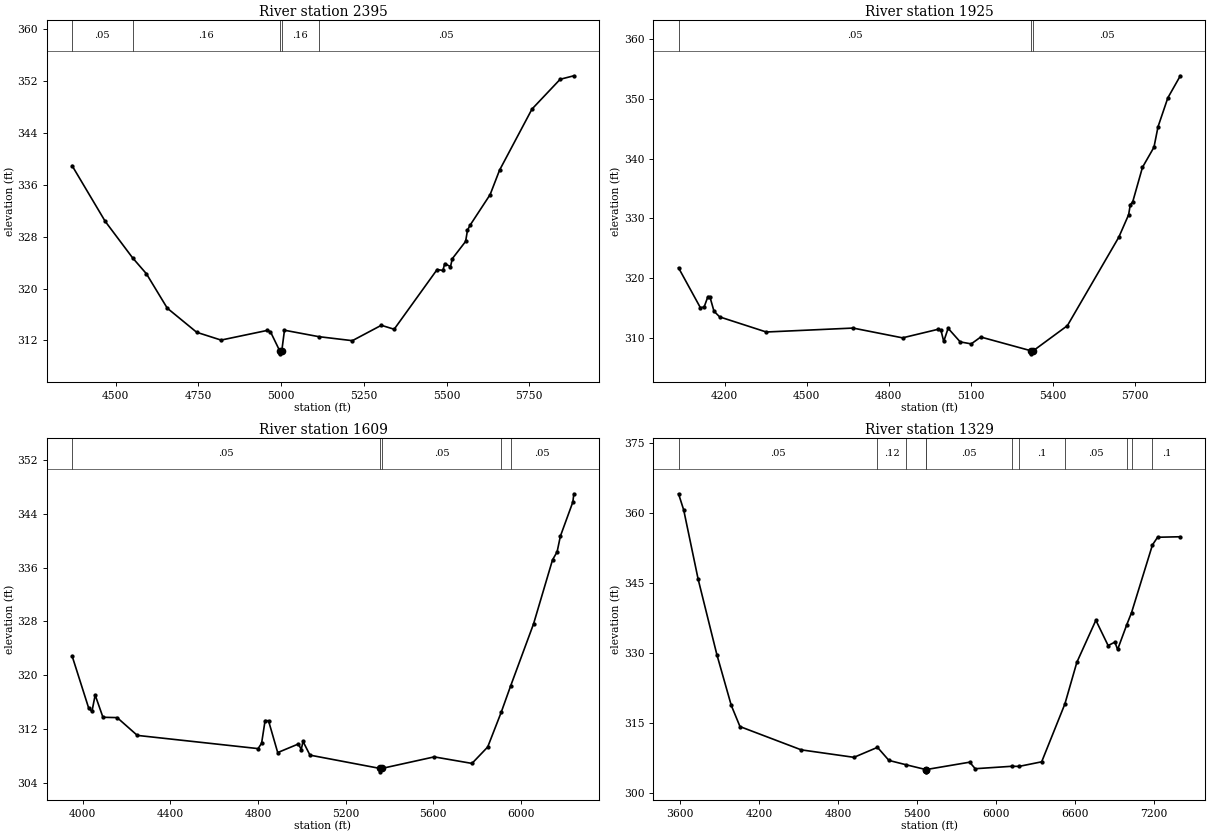
Type RM Length L Ch R = 1,2395,470,470,470
BEGIN DESCRIPTION:
UNT0291 IN DUCK CR 5 0
END DESCRIPTION:
XS GIS Cut Line= 4
      3573280.92     10415822.67      3572960.64     10415872.14
      3572744.49     10416484.12      3572973.64     10416976.28
#Sta/Elev= 30
  4368.5  338.94  4468.5  330.36  4551.3  324.73  4593.0  322.28  4656.1  316.97
  4745.1  313.25  4818.7  312.05  4957.2  313.53  4967.8  313.34  4995.5  310.43
  4996.0  309.93  5002.2  310.43  5010.2  313.57  5113.6  312.58  5215.3  311.96
  5302.8  314.33  5341.6  313.72  5471.5  322.93  5488.9  322.78  5494.4  323.84
  5511.8  323.37  5517.3  324.60  5557.5  327.26  5563.0  328.96  5570.5  329.72
  5631.6  334.48  5660.0  338.24  5758.0  347.66  5843.1  352.25  5884.5  352.79
#Mann=5,-1,0
  4368.5    0.05       0  4551.3    0.16       0  4995.5    0.07       0
  5002.2    0.16       0  5113.6    0.05       0
Bank Sta=4995.5,5002.2
Exp/Cntr=0.3,0.1

Type RM Length L Ch R = 1,1925,316,316,316
BEGIN DESCRIPTION:
UNT0291 IN DUCK CR 4 0
END DESCRIPTION:
XS GIS Cut Line= 4
      3572883.50     10415551.03      3572511.95     10415988.56
      3572452.92     10416683.00      3572914.75     10417002.46
#Sta/Elev= 30
  4031.9  321.69  4111.4  315.03  4125.1  315.09  4139.3  316.88  4147.1  316.72
  4161.4  314.41  4182.2  313.46  4352.4  310.93  4669.2  311.59  4849.9  309.95
  4980.3  311.39  4990.4  311.19  5000.4  309.35  5016.4  311.55  5060.6  309.27
  5100.8  308.94  5135.6  310.09  5320.1  307.77  5320.6  307.27  5326.8  307.77
  5451.9  311.99  5639.7  326.82  5675.6  330.59  5681.6  332.26  5690.4  332.73
  5726.2  338.54  5768.1  341.90  5783.0  345.34  5818.8  350.18  5864.4  353.88
#Mann=3,-1,0
  4031.9    0.05       0  5320.1    0.03       0  5326.8    0.05       0
Bank Sta=5320.1,5326.8
Exp/Cntr=0.3,0.1

Type RM Length L Ch R = 1,1609,280,280,280
BEGIN DESCRIPTION:
Mapping XS 1a73d4d0
END DESCRIPTION:
XS GIS Cut Line= 4
      3572871.32     10415523.77      3572301.86     10415938.70
      3572088.32     10416594.95      3572828.41     10417101.06
#Sta/Elev= 30
  3951.1  322.89  4027.2  315.11  4041.9  314.64  4056.6  317.07  4092.1  313.77
  4157.0  313.72  4249.0  311.08  4800.5  309.12  4816.5  309.91  4832.5  313.28
  4848.1  313.26  4890.1  308.53  4984.8  309.81  4997.4  308.98  5005.8  310.18
  5037.4  308.15  5358.1  306.17  5358.6  305.67  5364.8  306.17  5604.8  307.89
  5777.2  306.92  5849.0  309.36  5910.4  314.49  5953.1  318.37  6058.3  327.63
  6144.9  337.13  6165.9  338.33  6180.8  340.65  6237.7  345.72  6242.4  346.95
#Mann=5,-1,0
  3951.1    0.05       0  5358.1    0.03       0  5364.8    0.05       0
  5910.4     0.1       0  5953.1    0.05       0
Bank Sta=5358.1,5364.8
Exp/Cntr=0.3,0.1

Type RM Length L Ch R = 1,1329,0,0,0
BEGIN DESCRIPTION:
UNT0291 IN DUCK CR 1 0
END DESCRIPTION:
XS GIS Cut Line= 4
      3573173.22     10415328.75      3572140.22     10415884.31
      3571775.64     10416587.44      3573312.07     10417611.73
#Sta/Elev= 30
  3588.6  364.16  3628.0  360.67  3737.5  345.86  3879.6  329.70  3989.1  318.81
  4055.4  314.26  4520.9  309.27  4921.1  307.67  5099.8  309.81  5186.6  307.01
  5317.9  306.07  5465.3  305.06  5465.8  304.56  5472.0  305.06  5800.1  306.63
  5842.1  305.23  6119.8  305.75  6175.8  305.73  6346.9  306.71  6523.0  319.09
  6614.3  328.05  6758.6  337.05  6851.7  331.63  6902.8  332.36  6923.8  330.79
  6993.1  336.08  7029.6  338.69  7188.5  353.21  7227.3  354.84  7400.1  354.95
#Mann=11,-1,0
  3588.6    0.05       0  5099.8    0.12       0  5317.9    0.05       0
  5465.3    0.03       0  5472.0    0.05       0  6119.8    0.16       0
  6175.8     0.1       0  6523.0    0.05       0  6993.1    0.16       0
  7029.6    0.05       0  7188.5     0.1       0
Bank Sta=5465.3,5472
Exp/Cntr=0.3,0.1

Chan Stop Cuts=-1