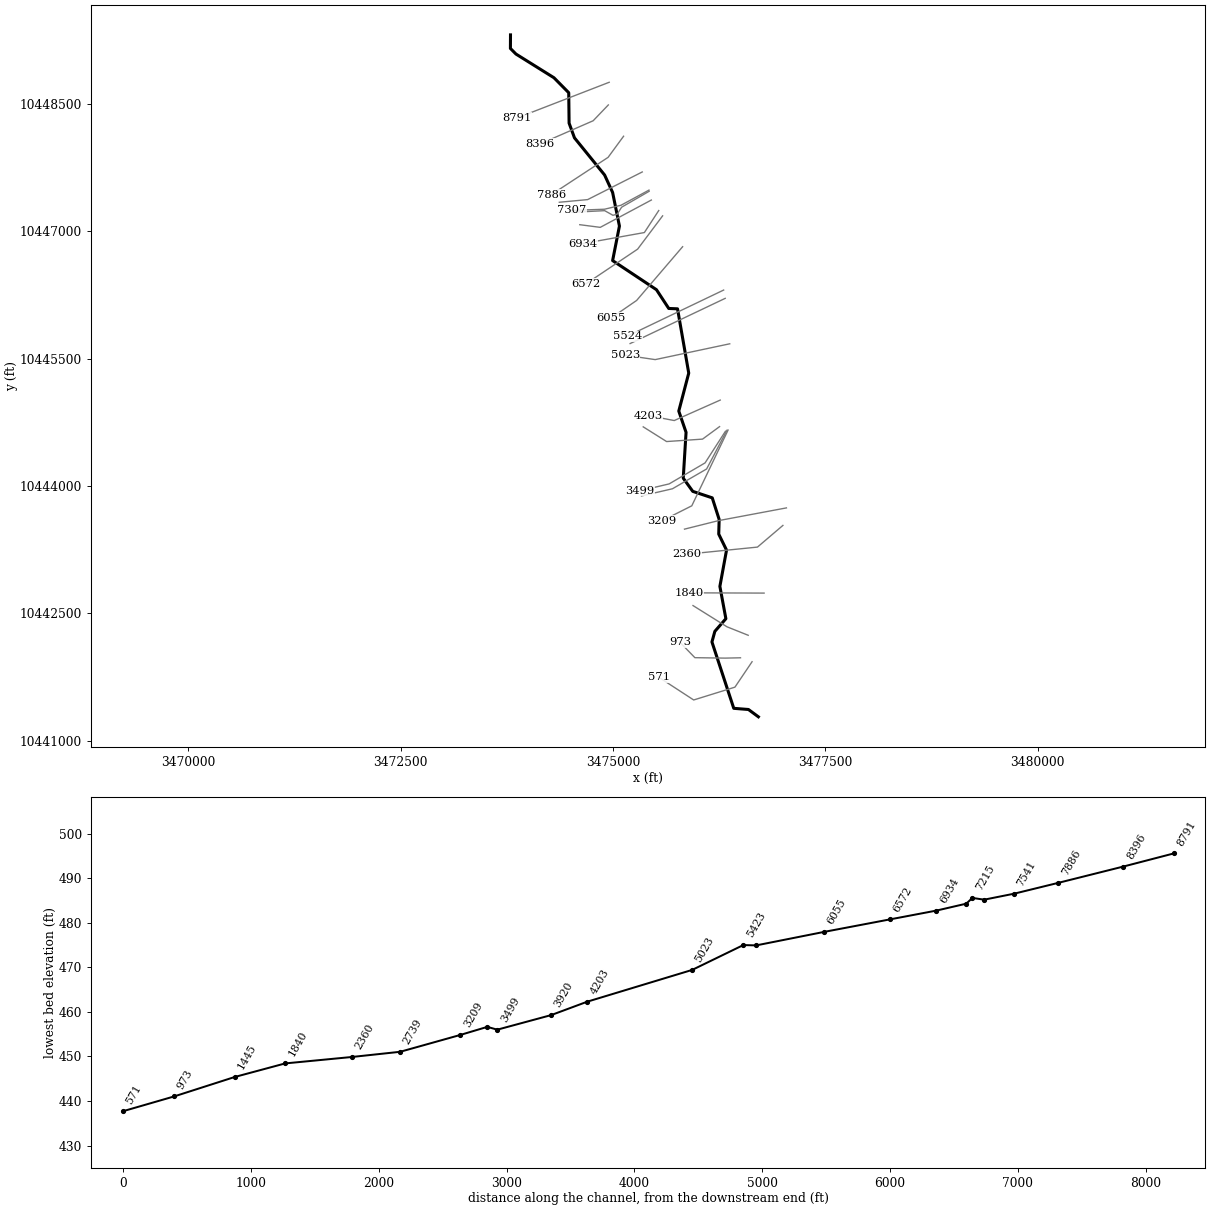
--- UNT0297 IN DUCK CR.prj (project) ---

Proj Title=UNT0297 IN DUCK CR Base Level Engineering
Current Plan=p01
Default Exp/Contr=0.3,0.1
English Units
Geom File=g01
Flow File=f01
Plan File=p01
BEGIN DESCRIPTION:
UNT0297 IN DUCK CR
END DESCRIPTION:

--- UNT0297 IN DUCK CR.p01 (plan) ---

Plan Title=Multiple Run
Short Identifier=Multiple
Geom File=g01
Flow File=f01
Subcritical Flow
K Sum by GR= 0
Std Step Tol= 0.01
Critical Tol= 0.01
Num of Std Step Trials= 20
Max Error Tol= 0.3
Flow Tol Ratio= 0.001
Split Flow NTrial= 30
Split Flow Tol= 0.02
Split Flow Ratio= 0.02
Log Output Level= 0
Friction Slope Method= 1
Unsteady Friction Slope Method= 2
Unsteady Bridges Friction Slope Method= 1
Parabolic Critical Depth
Global Vel Dist=  1 , 1 , 1
Global Log Level= 0
CheckData=True
Encroach Param= -1, 0, 0, 0
BEGIN DESCRIPTION:
Multiple Run
END DESCRIPTION:

--- UNT0297 IN DUCK CR.f01 (steady flow) ---

Flow Title=Multiple
Number of Profiles=7
Profile Names=10-year,25-year,50-year,1pct_min,100-year,1pct_plu,500-year
River Rch & RM= UNT0297 IN DUCK ,Reach-1,8791
    1364    1910    2366    2136    2889    3907    4299
River Rch & RM= UNT0297 IN DUCK ,Reach-1,1445
    1759    2497    3123    2844    3847    5202    5825
Boundary for River Rch & Prof#=UNT0297 IN DUCK ,Reach-1,1
Up Type=0
Dn Type=3
Dn Slope=0.005
Boundary for River Rch & Prof#=UNT0297 IN DUCK ,Reach-1,2
Up Type=0
Dn Type=3
Dn Slope=0.005
Boundary for River Rch & Prof#=UNT0297 IN DUCK ,Reach-1,3
Up Type=0
Dn Type=3
Dn Slope=0.005
Boundary for River Rch & Prof#=UNT0297 IN DUCK ,Reach-1,4
Up Type=0
Dn Type=3
Dn Slope=0.005
Boundary for River Rch & Prof#=UNT0297 IN DUCK ,Reach-1,5
Up Type=0
Dn Type=3
Dn Slope=0.005
Boundary for River Rch & Prof#=UNT0297 IN DUCK ,Reach-1,6
Up Type=0
Dn Type=3
Dn Slope=0.005
Boundary for River Rch & Prof#=UNT0297 IN DUCK ,Reach-1,7
Up Type=0
Dn Type=3
Dn Slope=0.005

--- UNT0297 IN DUCK CR.g01 (geometry) ---

Geom Title=Existing Conditions

River Reach=UNT0297 IN DUCK ,Reach-1
Reach XY= 30
      3473793.14     10449311.21      3473792.11     10449151.64
      3473857.43     10449085.71      3474304.76     10448806.67
      3474478.95     10448630.34      3474483.08     10448272.17
      3474546.55     10448098.77      3474901.33     10447661.37
      3474995.57     10447455.91      3475075.80     10447060.11
      3474995.62     10446653.72      3475511.93     10446310.82
      3475656.60     10446089.93      3475759.98     10446085.77
      3475891.95     10445328.84      3475774.62     10444881.61
      3475860.34     10444631.62      3475827.18     10444091.47
      3475939.18     10443936.44      3476168.79     10443859.93
      3476250.01     10443605.87      3476245.12     10443432.90
      3476337.00     10443244.79      3476258.64     10442817.57
      3476329.20     10442437.14      3476199.47     10442288.03
      3476165.10     10442163.27      3476422.11     10441381.64
      3476595.06     10441367.87      3476712.11     10441281.64

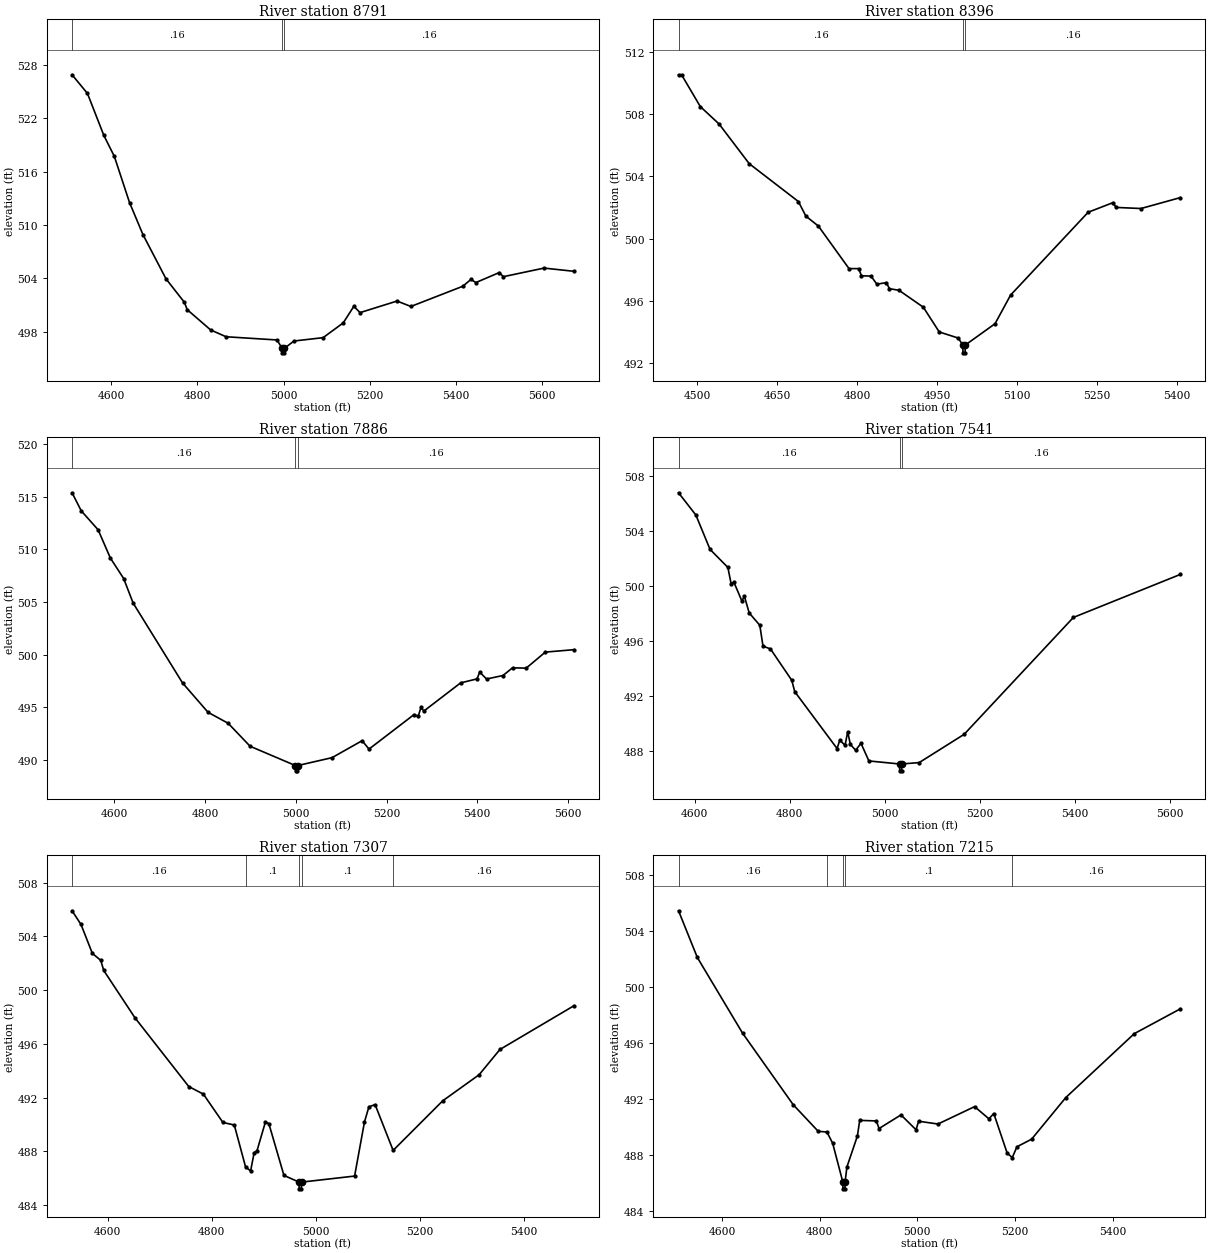
Type RM Length L Ch R = 1,8791,395,395,395
BEGIN DESCRIPTION:
UNT0297 IN DUCK CR 2 0
END DESCRIPTION:
XS GIS Cut Line= 2
      3474955.37     10448753.34      3473869.47     10448332.78
#Sta/Elev= 30
  4509.0  526.91  4544.7  524.81  4582.6  520.10  4607.1  517.72  4642.4  512.52
  4673.4  508.93  4727.0  503.94  4769.9  501.28  4776.0  500.48  4830.5  498.19
  4866.4  497.42  4984.3  497.06  4997.0  496.11  4997.3  495.61  5001.3  495.61
  5001.6  496.11  5023.9  496.94  5091.6  497.32  5138.3  498.98  5162.8  500.84
  5177.4  500.14  5263.2  501.44  5295.3  500.83  5416.1  503.11  5434.7  503.88
  5446.1  503.52  5500.6  504.65  5509.8  504.18  5604.2  505.15  5673.5  504.79
#Mann=3,-1,0
  4509.0    0.16       0  4997.0    0.07       0  5001.6    0.16       0
Bank Sta=4997,5001.6
Exp/Cntr=0.3,0.1

Type RM Length L Ch R = 1,8396,510,510,510
BEGIN DESCRIPTION:
UNT0297 IN DUCK CR 19 0
END DESCRIPTION:
XS GIS Cut Line= 3
      3474944.99     10448486.44      3474766.58     10448300.22
      3474140.27     10448026.78
#Sta/Elev= 30
  4465.2  510.52  4470.9  510.52  4506.0  508.48  4541.2  507.36  4597.8  504.81
  4690.0  502.38  4704.1  501.44  4727.6  500.80  4785.0  498.07  4803.0  498.07
  4808.4  497.61  4826.2  497.59  4837.3  497.07  4855.2  497.17  4860.7  496.78
  4878.6  496.68  4924.4  495.59  4954.3  494.00  4989.9  493.61  4998.4  493.16
  4998.8  492.66  5002.8  492.66  5003.1  493.16  5058.9  494.53  5088.1  496.37
  5233.6  501.69  5280.4  502.31  5285.9  502.00  5332.7  501.93  5406.5  502.63
#Mann=3,-1,0
  4465.2    0.16       0  4998.4    0.07       0  5003.1    0.16       0
Bank Sta=4998.4,5003.1
Exp/Cntr=0.3,0.1

Type RM Length L Ch R = 1,7886,345,345,345
BEGIN DESCRIPTION:
UNT0297 IN DUCK CR 18 0
END DESCRIPTION:
XS GIS Cut Line= 3
      3475124.65     10448117.93      3474942.36     10447869.23
      3474275.78     10447431.34
#Sta/Elev= 30
  4507.0  515.36  4527.2  513.65  4564.4  511.85  4591.4  509.17  4620.7  507.23
  4641.6  504.90  4750.4  497.33  4806.7  494.54  4851.0  493.50  4899.4  491.32
  4999.3  489.49  4999.6  488.99  5003.7  488.99  5004.1  489.49  5080.0  490.24
  5146.3  491.85  5161.4  491.05  5260.8  494.33  5269.9  494.17  5275.9  495.00
  5282.3  494.66  5363.3  497.33  5399.4  497.71  5405.4  498.35  5420.5  497.70
  5456.7  498.03  5477.7  498.76  5507.9  498.73  5550.0  500.25  5612.9  500.48
#Mann=3,-1,0
  4507.0    0.16       0  4999.3    0.07       0  5004.1    0.16       0
Bank Sta=4999.3,5004.1
Exp/Cntr=0.3,0.1

Type RM Length L Ch R = 1,7541,234,234,234
BEGIN DESCRIPTION:
Mapping XS 08f846be
END DESCRIPTION:
XS GIS Cut Line= 3
      3475344.68     10447697.34      3474701.48     10447371.83
      3474368.11     10447340.58
#Sta/Elev= 30
  4565.8  506.79  4602.3  505.17  4632.1  502.67  4669.6  501.36  4676.6  500.14
  4682.2  500.29  4698.9  498.93  4704.5  499.25  4714.4  498.05  4736.8  497.15
  4743.5  495.63  4759.2  495.43  4804.0  493.15  4810.3  492.32  4899.4  488.18
  4905.0  488.79  4916.1  488.42  4921.7  489.40  4927.3  488.48  4938.4  488.06
  4949.7  488.56  4966.3  487.28  5030.7  487.06  5031.1  486.56  5035.2  486.56
  5035.5  487.06  5072.1  487.16  5166.8  489.22  5396.5  497.72  5621.5  500.85
#Mann=3,-1,0
  4565.8    0.16       0  5030.7    0.07       0  5035.5    0.16       0
Bank Sta=5030.7,5035.5
Exp/Cntr=0.3,0.1

Type RM Length L Ch R = 1,7307,92,92,92
BEGIN DESCRIPTION:
UNT0297 IN DUCK CR 16 0
END DESCRIPTION:
XS GIS Cut Line= 4
      3475424.10     10447483.80      3475094.70     10447305.43
      3474900.69     10447258.55      3474510.04     10447244.23
#Sta/Elev= 30
  4531.3  505.91  4548.5  504.89  4570.3  502.74  4586.5  502.22  4592.2  501.47
  4652.2  497.95  4755.8  492.83  4783.8  492.27  4821.4  490.16  4843.3  489.97
  4865.0  486.85  4874.7  486.55  4881.4  487.90  4887.1  488.07  4903.2  490.20
  4909.8  490.07  4938.8  486.22  4967.9  485.72  4968.2  485.22  4972.3  485.22
  4972.7  485.72  5074.7  486.17  5093.7  490.20  5102.2  491.32  5114.1  491.49
  5148.8  488.08  5244.2  491.77  5314.2  493.71  5354.2  495.59  5496.4  498.84
#Mann=5,-1,0
  4531.3    0.16       0  4865.0     0.1       0  4967.9    0.07       0
  4972.7     0.1       0  5148.8    0.16       0
Bank Sta=4967.9,4972.7
Exp/Cntr=0.3,0.1

Type RM Length L Ch R = 1,7215,48,48,48
BEGIN DESCRIPTION:
UNT0297 IN DUCK CR 17 0
END DESCRIPTION:
XS GIS Cut Line= 6
      3475425.39     10447469.47      3475101.21     10447281.99
      3475050.43     10447201.26      3474999.65     10447186.94
      3474902.00     10447241.63      3474517.92     10447222.10
#Sta/Elev= 30
  4511.0  505.43  4549.5  502.10  4642.1  496.71  4745.8  491.61  4797.1  489.71
  4815.0  489.66  4826.7  488.86  4847.4  486.11  4847.8  485.61  4851.9  485.61
  4852.2  486.11  4855.9  487.17  4877.4  489.38  4882.1  490.49  4916.2  490.45
  4921.7  489.91  4966.6  490.88  4997.5  489.82  5002.7  490.43  5042.4  490.23
  5117.4  491.47  5146.8  490.60  5156.7  490.98  5184.2  488.15  5194.6  487.84
  5204.2  488.61  5234.2  489.15  5304.3  492.12  5444.4  496.67  5538.8  498.44
#Mann=5,-1,0
  4511.0    0.16       0  4815.0     0.1       0  4847.4    0.07       0
  4852.2     0.1       0  5194.6    0.16       0
Bank Sta=4847.4,4852.2
Exp/Cntr=0.3,0.1

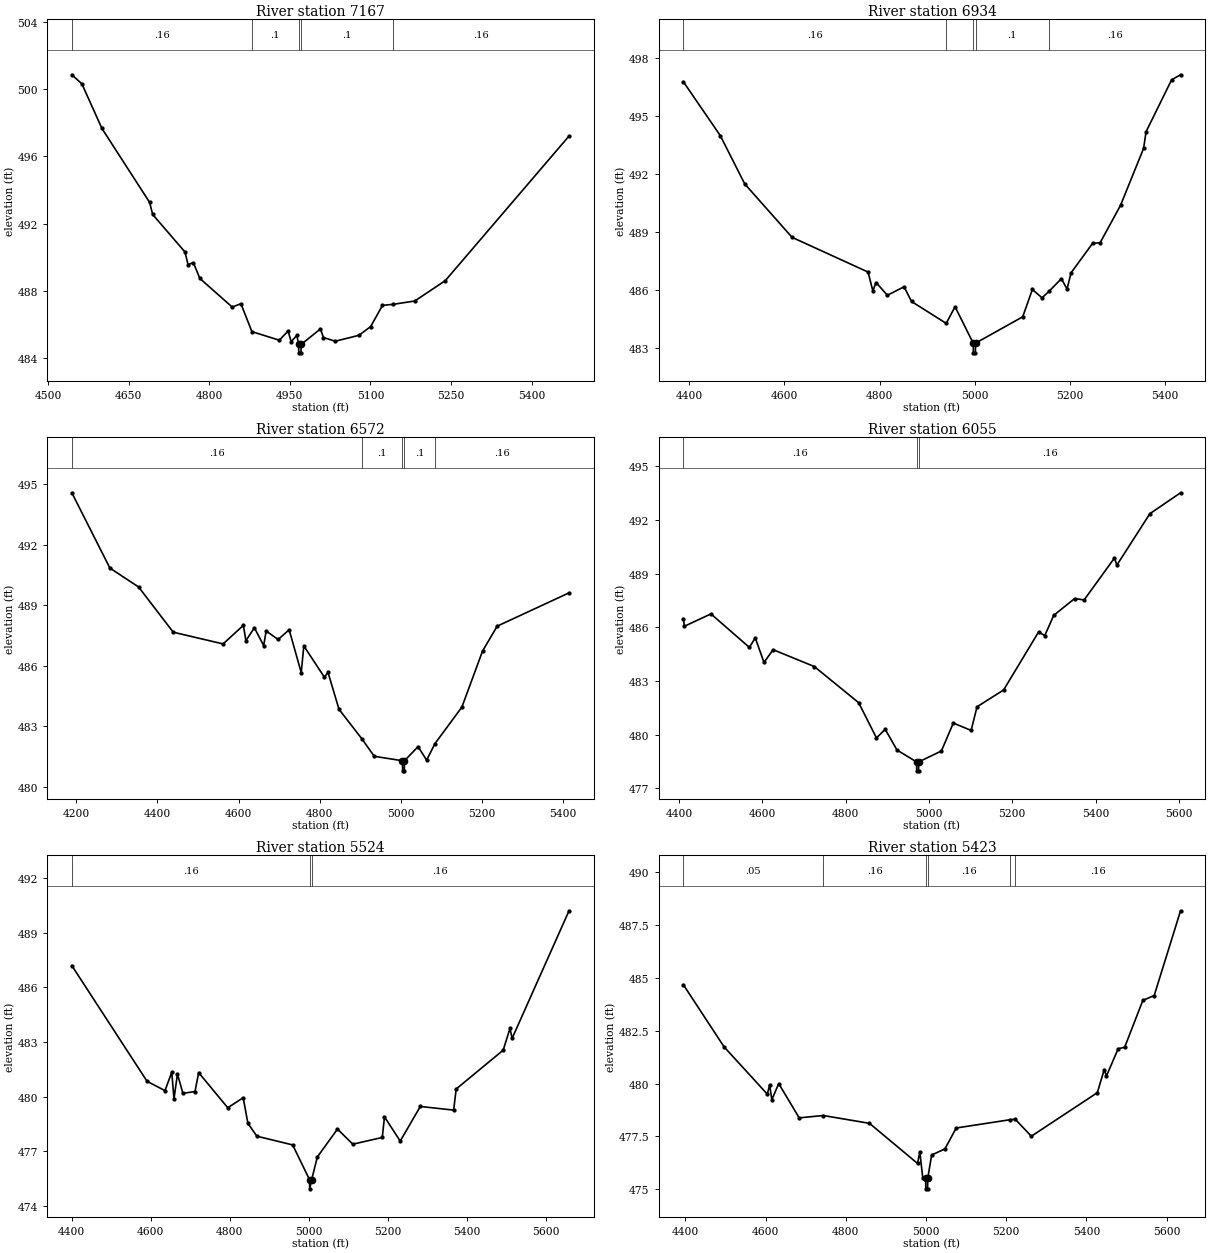
Type RM Length L Ch R = 1,7167,233,233,233
BEGIN DESCRIPTION:
UNT0297 IN DUCK CR 15 0
END DESCRIPTION:
XS GIS Cut Line= 3
      3475451.48     10447366.63      3474849.91     10447045.01
      3474608.98     10447076.27
#Sta/Elev= 30
  4544.5  500.84  4563.2  500.30  4600.5  497.65  4689.2  493.26  4694.9  492.54
  4755.1  490.31  4760.7  489.56  4770.6  489.68  4782.7  488.74  4842.9  487.04
  4859.1  487.24  4879.5  485.58  4930.6  485.07  4946.9  485.62  4952.6  484.98
  4963.2  485.36  4966.4  484.82  4966.8  484.32  4970.9  484.32  4971.2  484.82
  5007.1  485.74  5012.7  485.23  5034.7  485.01  5078.6  485.36  5100.5  485.88
  5122.5  487.14  5141.9  487.20  5182.6  487.40  5239.4  488.61  5469.6  497.20
#Mann=5,-1,0
  4544.5    0.16       0  4879.5     0.1       0  4966.4    0.07       0
  4971.2     0.1       0  5141.9    0.16       0
Bank Sta=4966.4,4971.2
Exp/Cntr=0.3,0.1

Type RM Length L Ch R = 1,6934,362,362,362
BEGIN DESCRIPTION:
Mapping XS b84b995b
END DESCRIPTION:
XS GIS Cut Line= 3
      3475538.71     10447242.93      3475369.44     10446983.81
      3474645.62     10446853.86
#Sta/Elev= 30
  4387.6  496.76  4465.2  493.98  4516.5  491.49  4616.1  488.73  4775.7  486.94
  4785.8  485.97  4792.6  486.40  4816.3  485.74  4851.4  486.18  4867.1  485.42
  4940.0  484.29  4958.6  485.15  4996.7  483.27  4997.1  482.77  5001.3  482.77
  5001.6  483.27  5100.8  484.63  5121.1  486.04  5141.4  485.61  5155.9  485.94
  5182.1  486.60  5193.9  486.06  5202.4  486.90  5247.6  488.42  5263.4  488.45
  5306.3  490.38  5354.8  493.32  5360.0  494.18  5413.7  496.86  5432.5  497.12
#Mann=5,-1,0
  4387.6    0.16       0  4940.0     0.1       0  4996.7    0.07       0
  5001.6     0.1       0  5155.9    0.16       0
Bank Sta=4996.7,5001.6
Exp/Cntr=0.3,0.1

Type RM Length L Ch R = 1,6572,517,517,517
BEGIN DESCRIPTION:
UNT0297 IN DUCK CR 15 1
END DESCRIPTION:
XS GIS Cut Line= 3
      3475584.29     10447180.43      3475290.02     10446788.50
      3474679.38     10446378.37
#Sta/Elev= 30
  4189.0  494.58  4282.8  490.85  4353.6  489.91  4439.0  487.67  4561.9  487.09
  4611.9  488.01  4618.1  487.25  4639.0  487.89  4661.9  487.01  4668.1  487.73
  4697.5  487.31  4724.8  487.79  4754.5  485.67  4760.9  486.99  4811.6  485.44
  4820.5  485.68  4847.6  483.85  4903.5  482.40  4934.6  481.52  5004.1  481.30
  5004.5  480.80  5008.7  480.80  5009.0  481.30  5042.6  482.00  5063.6  481.33
  5084.2  482.15  5150.6  483.96  5201.6  486.74  5237.6  487.97  5414.7  489.62
#Mann=5,-1,0
  4189.0    0.16       0  4903.5     0.1       0  5004.1    0.07       0
  5009.0     0.1       0  5084.2    0.16       0
Bank Sta=5004.1,5009
Exp/Cntr=0.3,0.1

Type RM Length L Ch R = 1,6055,531,531,531
BEGIN DESCRIPTION:
UNT0297 IN DUCK CR 14 0
END DESCRIPTION:
XS GIS Cut Line= 3
      3475819.95     10446817.12      3475278.30     10446184.33
      3474981.42     10445979.91
#Sta/Elev= 30
  4410.5  486.49  4413.0  486.06  4476.7  486.75  4568.9  484.88  4583.1  485.41
  4604.0  484.04  4626.0  484.75  4724.7  483.81  4831.2  481.79  4874.0  479.82
  4894.9  480.30  4923.4  479.14  4970.2  478.48  4970.6  477.98  4975.0  477.98
  4975.4  478.48  5029.9  479.09  5058.4  480.65  5101.2  480.24  5115.4  481.56
  5179.2  482.50  5263.1  485.74  5278.0  485.54  5299.5  486.67  5349.7  487.61
  5372.4  487.53  5445.1  489.87  5451.1  489.48  5530.2  492.35  5603.9  493.52
#Mann=3,-1,0
  4410.5    0.16       0  4970.2    0.07       0  4975.4    0.16       0
Bank Sta=4970.2,4975.4
Exp/Cntr=0.3,0.1

Type RM Length L Ch R = 1,5524,101,101,101
BEGIN DESCRIPTION:
UNT0297 IN DUCK CR 13 0
END DESCRIPTION:
XS GIS Cut Line= 2
      3476303.06     10446306.74      3475168.94     10445763.77
#Sta/Elev= 30
  4400.7  487.20  4591.0  480.85  4636.3  480.34  4653.4  481.35  4659.0  479.88
  4667.8  481.25  4681.6  480.19  4712.2  480.29  4721.4  481.33  4795.0  479.40
  4834.1  479.95  4845.9  478.55  4868.5  477.84  4959.2  477.36  5001.9  475.45
  5002.3  474.95  5007.2  475.45  5021.6  476.70  5072.5  478.23  5111.3  477.40
  5185.8  477.77  5191.4  478.90  5231.2  477.57  5282.0  479.47  5366.3  479.27
  5372.7  480.43  5491.6  482.56  5508.7  483.75  5514.2  483.21  5658.1  490.21
#Mann=3,-1,0
  4400.7    0.16       0  5001.9    0.07       0  5007.2    0.16       0
Bank Sta=5001.9,5007.2
Exp/Cntr=0.3,0.1

Type RM Length L Ch R = 1,5423,400,400,400
BEGIN DESCRIPTION:
Mapping XS ef2cd45e
END DESCRIPTION:
XS GIS Cut Line= 2
      3476321.23     10446209.06      3475201.60     10445676.58
#Sta/Elev= 30
  4395.1  484.68  4496.6  481.74  4604.5  479.50  4610.2  479.94  4615.7  479.24
  4632.9  480.00  4683.9  478.38  4744.1  478.49  4859.2  478.12  4979.1  476.22
  4984.7  476.78  4992.1  475.53  4999.2  475.52  4999.6  475.02  5004.1  475.02
  5004.5  475.52  5014.2  476.62  5047.3  476.91  5075.5  477.90  5209.4  478.29
  5222.8  478.31  5262.8  477.51  5427.3  479.57  5444.5  480.66  5450.1  480.36
  5479.3  481.65  5495.5  481.72  5540.9  483.94  5569.2  484.17  5634.9  488.18
#Mann=6,-1,0
  4395.1    0.05       0  4744.1    0.16       0  4999.2    0.07       0
  5004.5    0.16       0  5209.4    0.05       0  5222.8    0.16       0
Bank Sta=4999.2,5004.5
Exp/Cntr=0.3,0.1

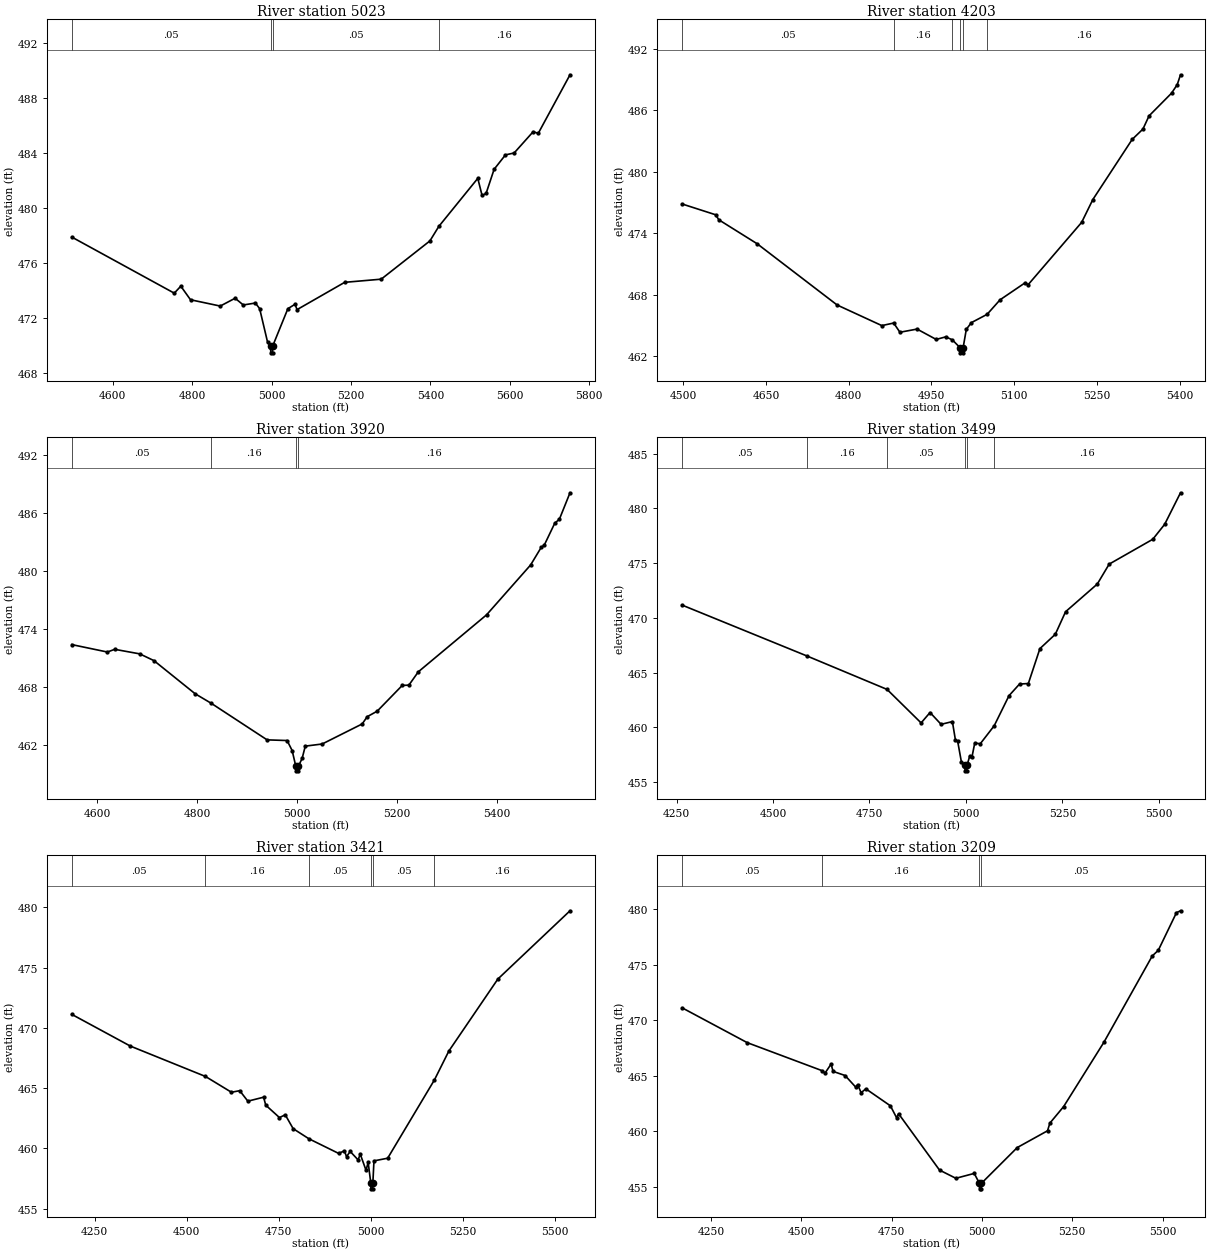
Type RM Length L Ch R = 1,5023,820,820,820
BEGIN DESCRIPTION:
UNT0297 IN DUCK CR 12 0
END DESCRIPTION:
XS GIS Cut Line= 3
      3476374.67     10445673.92      3475497.05     10445487.72
      3475142.91     10445539.80
#Sta/Elev= 30
  4496.5  477.88  4754.7  473.79  4771.2  474.30  4795.6  473.31  4870.5  472.85
  4908.0  473.42  4928.5  472.93  4959.1  473.07  4969.8  472.66  4989.8  470.21
  4997.4  469.94  4997.8  469.44  5002.3  469.44  5002.7  469.94  5040.9  472.66
  5058.9  472.98  5064.0  472.59  5184.0  474.58  5276.0  474.81  5398.7  477.60
  5421.2  478.66  5519.3  482.16  5530.1  480.91  5540.2  481.06  5560.4  482.82
  5589.0  483.87  5610.9  484.01  5658.8  485.56  5671.6  485.44  5751.6  489.71
#Mann=4,-1,0
  4496.5    0.05       0  4997.4    0.04       0  5002.7    0.05       0
  5421.2    0.16       0
Bank Sta=4997.4,5002.7
Exp/Cntr=0.3,0.1

Type RM Length L Ch R = 1,4203,283,283,283
BEGIN DESCRIPTION:
UNT0297 IN DUCK CR 11 0
END DESCRIPTION:
XS GIS Cut Line= 3
      3476262.69     10445011.17      3475721.01     10444770.27
      3475416.08     10444828.66
#Sta/Elev= 30
  4498.4  476.84  4559.0  475.79  4564.7  475.30  4634.2  472.96  4779.2  466.98
  4860.2  464.97  4881.7  465.22  4893.0  464.32  4924.1  464.63  4958.7  463.62
  4976.1  463.87  4988.0  463.58  5002.1  462.81  5002.5  462.31  5007.1  462.31
  5007.6  462.81  5013.4  464.61  5022.6  465.26  5051.1  466.07  5074.6  467.49
  5120.3  469.16  5125.4  468.96  5222.5  475.05  5242.8  477.28  5314.1  483.15
  5333.6  484.16  5344.7  485.45  5385.4  487.66  5395.8  488.50  5401.7  489.46
#Mann=6,-1,0
  4498.4    0.05       0  4881.7    0.16       0  4988.0    0.05       0
  5002.1    0.04       0  5007.6    0.05       0  5051.1    0.16       0
Bank Sta=5002.1,5007.6
Exp/Cntr=0.3,0.1

Type RM Length L Ch R = 1,3920,421,421,421
BEGIN DESCRIPTION:
Mapping XS c3af4a4f
END DESCRIPTION:
XS GIS Cut Line= 4
      3476254.84     10444698.64      3476054.34     10444551.52
      3475631.16     10444522.88      3475356.01     10444695.98
#Sta/Elev= 30
  4549.3  472.37  4620.6  471.60  4635.3  471.88  4685.4  471.41  4713.9  470.71
  4796.3  467.28  4828.9  466.28  4940.5  462.50  4980.6  462.43  4990.7  461.39
  4997.9  459.79  4998.4  459.29  5003.0  459.29  5003.4  459.79  5010.7  460.58
  5017.0  461.85  5050.8  462.07  5131.0  464.15  5141.0  464.90  5161.0  465.47
  5211.2  468.14  5224.5  468.17  5243.4  469.55  5380.0  475.45  5468.3  480.62
  5489.5  482.44  5495.4  482.65  5516.6  484.94  5526.0  485.37  5547.2  488.10
#Mann=4,-1,0
  4549.3    0.05       0  4828.9    0.16       0  4997.9    0.07       0
  5003.4    0.16       0
Bank Sta=4997.9,5003.4
Exp/Cntr=0.3,0.1

Type RM Length L Ch R = 1,3499,78,78,78
BEGIN DESCRIPTION:
UNT0297 IN DUCK CR 10 0
END DESCRIPTION:
XS GIS Cut Line= 4
      3476323.89     10444644.00      3476084.29     10444271.57
      3475661.11     10444024.18      3475312.16     10443942.15
#Sta/Elev= 30
  4264.8  471.16  4587.1  466.53  4795.7  463.46  4883.9  460.40  4907.1  461.35
  4935.7  460.27  4965.0  460.52  4972.9  458.83  4978.7  458.72  4988.2  456.86
  4997.3  456.52  4997.8  456.02  5002.5  456.02  5003.0  456.52  5010.1  457.40
  5015.9  457.31  5022.9  458.55  5037.4  458.50  5073.4  460.14  5111.8  462.89
  5139.0  463.95  5161.9  464.00  5191.9  467.19  5231.8  468.50  5258.4  470.56
  5340.6  473.09  5371.4  474.91  5484.4  477.18  5515.3  478.55  5556.3  481.43
#Mann=6,-1,0
  4264.8    0.05       0  4587.1    0.16       0  4795.7    0.05       0
  4997.3    0.04       0  5003.0    0.05       0  5073.4    0.16       0
Bank Sta=4997.3,5003
Exp/Cntr=0.3,0.1

Type RM Length L Ch R = 1,3421,212,212,212
BEGIN DESCRIPTION:
Mapping XS cb445a9e
END DESCRIPTION:
XS GIS Cut Line= 4
      3476342.10     10444655.68      3476102.52     10444199.96
      3475700.17     10443966.89      3475335.74     10443882.59
#Sta/Elev= 30
  4187.5  471.12  4346.6  468.49  4550.8  465.97  4621.4  464.66  4643.9  464.79
  4666.0  463.92  4708.8  464.25  4714.6  463.59  4751.9  462.56  4767.6  462.79
  4789.1  461.64  4832.0  460.80  4912.6  459.59  4928.3  459.80  4934.1  459.32
  4944.1  459.75  4965.6  459.05  4971.4  459.53  4987.1  458.19  4992.9  458.84
  5000.0  457.15  5000.5  456.65  5005.2  456.65  5005.7  457.15  5008.7  458.97
  5045.9  459.19  5173.1  465.69  5212.2  468.08  5345.4  474.05  5541.4  479.71
#Mann=6,-1,0
  4187.5    0.05       0  4550.8    0.16       0  4832.0    0.05       0
  5000.0    0.04       0  5005.7    0.05       0  5173.1    0.16       0
Bank Sta=5000,5005.7
Exp/Cntr=0.3,0.1

Type RM Length L Ch R = 1,3209,470,470,470
BEGIN DESCRIPTION:
UNT0297 IN DUCK CR 9 0
END DESCRIPTION:
XS GIS Cut Line= 3
      3476355.10     10444658.25      3475928.04     10443766.36
      3475579.07     10443590.58
#Sta/Elev= 30
  4170.2  471.13  4350.1  468.00  4557.0  465.48  4565.6  465.26  4582.3  466.07
  4587.8  465.41  4621.0  465.04  4650.3  464.00  4655.8  464.22  4665.4  463.49
  4678.5  463.84  4746.5  462.31  4763.6  461.24  4769.1  461.60  4882.5  456.52
  4927.8  455.78  4978.7  456.22  4992.9  455.33  4993.4  454.83  4998.2  454.83
  4998.6  455.33  5097.8  458.55  5181.6  460.06  5188.1  460.75  5226.2  462.24
  5337.8  468.04  5471.6  475.81  5488.3  476.32  5538.6  479.71  5549.8  479.88
#Mann=4,-1,0
  4170.2    0.05       0  4557.0    0.16       0  4992.9    0.03       0
  4998.6    0.05       0
Bank Sta=4992.9,4998.6
Exp/Cntr=0.3,0.1

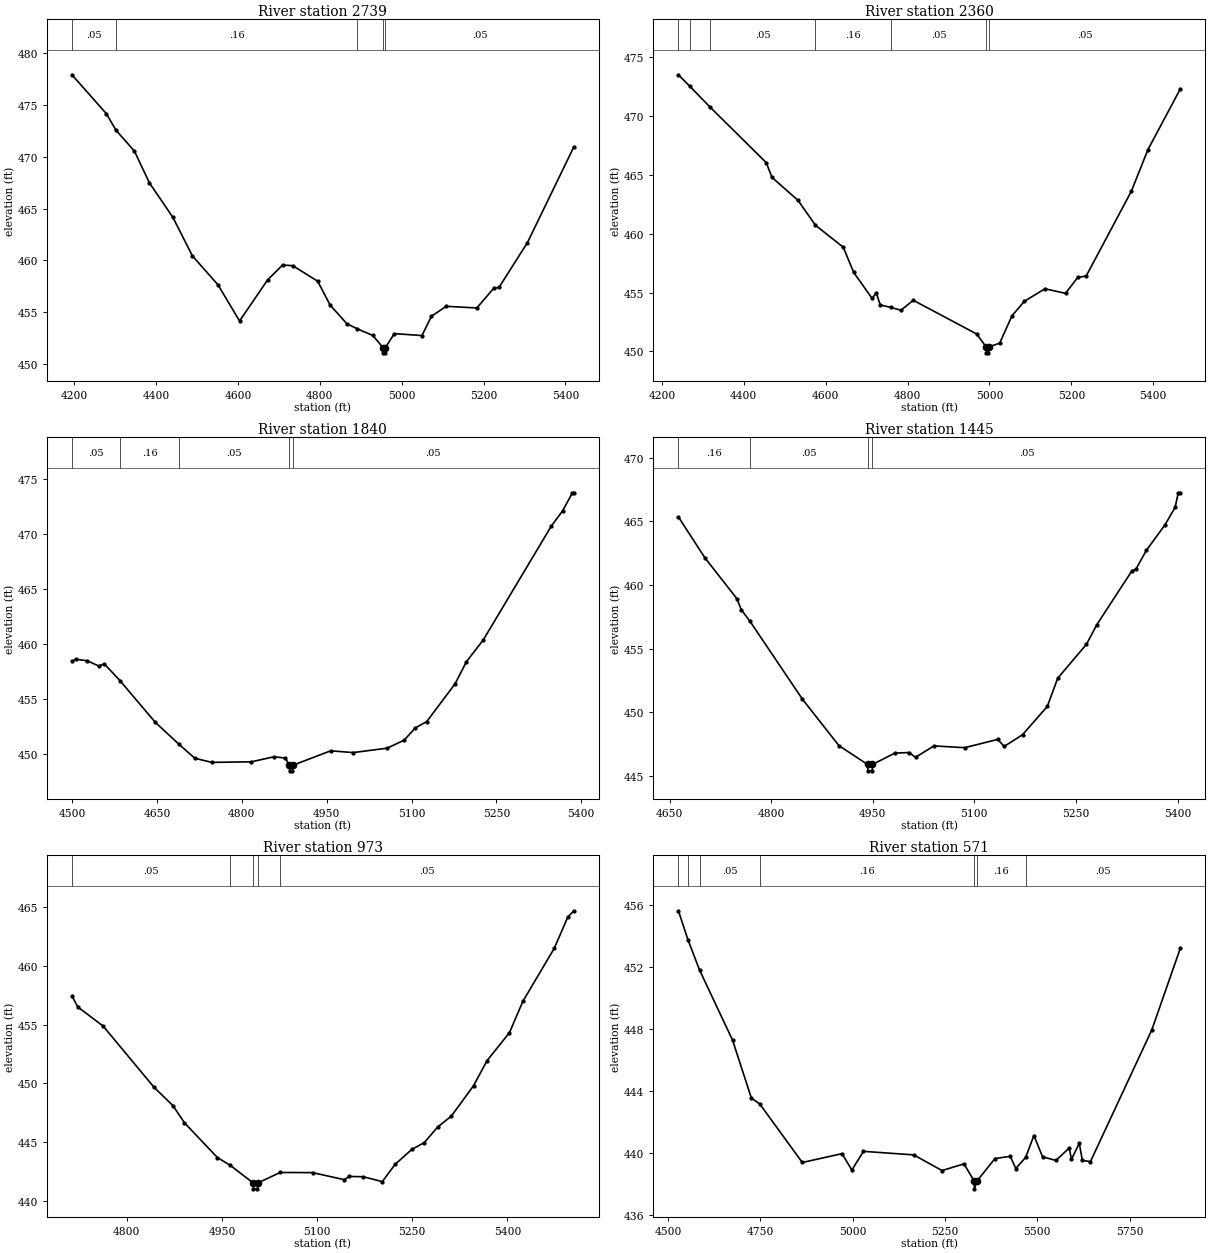
Type RM Length L Ch R = 1,2739,379,379,379
BEGIN DESCRIPTION:
UNT0297 IN DUCK CR 8 0
END DESCRIPTION:
XS GIS Cut Line= 3
      3477042.13     10443741.65      3476242.11     10443591.64
      3475842.08     10443491.64
#Sta/Elev= 30
  4194.4  477.94  4278.4  474.18  4302.2  472.57  4347.0  470.56  4383.5  467.50
  4441.2  464.14  4488.6  460.43  4551.4  457.62  4603.9  454.13  4672.6  458.11
  4709.1  459.54  4733.7  459.48  4794.7  457.98  4825.2  455.67  4865.9  453.87
  4891.2  453.38  4929.5  452.73  4954.6  451.55  4955.1  451.05  4959.9  451.05
  4960.3  451.55  4982.1  452.91  5049.6  452.72  5072.8  454.59  5108.9  455.55
  5183.6  455.39  5224.8  457.29  5237.7  457.37  5307.3  461.71  5420.7  470.97
#Mann=5,-1,0
  4194.4    0.05       0  4302.2    0.16       0  4891.2    0.05       0
  4954.6    0.03       0  4960.3    0.05       0
Bank Sta=4954.6,4960.3
Exp/Cntr=0.3,0.1

Type RM Length L Ch R = 1,2360,520,520,520
BEGIN DESCRIPTION:
UNT0297 IN DUCK CR 7 0
END DESCRIPTION:
XS GIS Cut Line= 3
      3477000.69     10443535.32      3476701.24     10443280.14
      3475873.16     10443196.81
#Sta/Elev= 30
  4240.5  473.53  4267.7  472.57  4318.7  470.75  4454.9  466.06  4469.1  464.80
  4532.8  462.84  4574.9  460.74  4643.1  458.86  4668.6  456.72  4713.5  454.51
  4723.5  454.97  4733.6  453.95  4758.9  453.75  4783.8  453.50  4814.0  454.35
  4969.1  451.48  4992.0  450.38  4992.5  449.88  4997.3  449.88  4997.8  450.38
  5025.0  450.70  5055.2  453.04  5085.3  454.26  5135.6  455.33  5185.8  454.94
  5216.0  456.31  5236.1  456.40  5346.7  463.63  5386.9  467.15  5466.2  472.33
#Mann=7,-1,0
  4240.5    0.05       0  4267.7    0.16       0  4318.7    0.05       0
  4574.9    0.16       0  4758.9    0.05       0  4992.0    0.03       0
  4997.8    0.05       0
Bank Sta=4992,4997.8
Exp/Cntr=0.3,0.1

Type RM Length L Ch R = 1,1840,395,395,395
BEGIN DESCRIPTION:
UNT0297 IN DUCK CR 6 0
END DESCRIPTION:
XS GIS Cut Line= 2
      3476779.36     10442738.47      3475892.06     10442741.64
#Sta/Elev= 30
  4499.7  458.39  4507.0  458.58  4527.0  458.44  4547.0  457.97  4557.0  458.16
  4584.4  456.65  4647.0  452.85  4689.2  450.84  4717.0  449.58  4747.0  449.21
  4817.0  449.26  4857.0  449.72  4877.0  449.60  4884.1  448.94  4884.6  448.44
  4889.4  448.44  4889.9  448.94  4957.0  450.26  4997.0  450.10  5057.0  450.50
  5087.0  451.23  5107.0  452.35  5127.0  452.92  5177.0  456.35  5197.0  458.35
  5227.0  460.35  5347.0  470.67  5367.0  472.06  5384.5  473.71  5387.0  473.71
#Mann=5,-1,0
  4499.7    0.05       0  4584.4    0.16       0  4689.2    0.05       0
  4884.1    0.03       0  4889.9    0.05       0
Bank Sta=4884.1,4889.9
Exp/Cntr=0.3,0.1

Type RM Length L Ch R = 1,1445,472,472,472
BEGIN DESCRIPTION:
UNT0297 IN DUCK CR 5 0
END DESCRIPTION:
XS GIS Cut Line= 3
      3476592.14     10442241.63      3476342.11     10442341.64
      3475942.10     10442591.65
#Sta/Elev= 30
  4663.1  465.34  4702.2  462.13  4749.3  458.93  4756.0  458.04  4768.9  457.13
  4846.2  451.02  4900.1  447.37  4942.3  445.89  4942.8  445.39  4949.1  445.39
  4949.6  445.89  4982.5  446.78  5003.7  446.83  5013.2  446.45  5040.3  447.35
  5085.7  447.21  5134.6  447.86  5144.1  447.31  5171.2  448.23  5207.7  450.45
  5223.1  452.67  5265.5  455.33  5280.9  456.88  5332.7  461.11  5338.6  461.24
  5354.0  462.72  5381.1  464.69  5396.4  466.09  5401.1  467.24  5404.1  467.24
#Mann=4,-1,0
  4663.1    0.16       0  4768.9    0.05       0  4942.3    0.03       0
  4949.6    0.05       0
Bank Sta=4942.3,4949.6
Exp/Cntr=0.3,0.1

Type RM Length L Ch R = 1,973,402,402,402
BEGIN DESCRIPTION:
UNT0297 IN DUCK CR 3 0
END DESCRIPTION:
XS GIS Cut Line= 4
      3476501.36     10441976.73      3476321.03     10441972.85
      3475964.26     10441978.06      3475787.19     10442160.33
#Sta/Elev= 30
  4713.5  457.43  4722.8  456.50  4762.8  454.87  4842.8  449.68  4872.8  448.11
  4890.8  446.66  4942.8  443.70  4963.3  443.03  4999.2  441.54  4999.7  441.04
  5006.0  441.04  5006.5  441.54  5041.7  442.43  5092.8  442.42  5142.8  441.82
  5150.8  442.09  5172.8  442.07  5202.8  441.65  5222.8  443.11  5249.3  444.39
  5269.0  444.97  5290.1  446.30  5311.4  447.21  5346.7  449.81  5367.8  451.93
  5403.3  454.32  5424.4  456.98  5474.0  461.50  5495.1  464.13  5504.8  464.68
#Mann=5,-1,0
  4713.5    0.05       0  4963.3    0.16       0  4999.2    0.07       0
  5006.5    0.16       0  5041.7    0.05       0
Bank Sta=4999.2,5006.5
Exp/Cntr=0.3,0.1

Type RM Length L Ch R = 1,571,0,0,0
BEGIN DESCRIPTION:
UNT0297 IN DUCK CR 1 0
END DESCRIPTION:
XS GIS Cut Line= 4
      3476637.68     10441930.44      3476435.85     10441630.95
      3475950.17     10441479.91      3475539.84     10441747.40
#Sta/Elev= 30
  4528.0  455.64  4554.3  453.74  4585.2  451.82  4674.7  447.29  4725.7  443.55
  4748.2  443.18  4863.6  439.40  4971.3  439.97  4997.8  438.91  5029.2  440.12
  5165.4  439.89  5242.1  438.88  5301.5  439.31  5329.3  438.20  5329.8  437.70
  5336.6  438.20  5385.3  439.65  5426.9  439.80  5442.0  439.01  5468.6  439.73
  5491.0  441.14  5514.4  439.77  5550.6  439.53  5586.5  440.33  5592.8  439.61
  5613.9  440.64  5622.3  439.53  5644.2  439.46  5810.1  447.94  5887.6  453.22
#Mann=7,-1,0
  4528.0    0.05       0  4554.3    0.16       0  4585.2    0.05       0
  4748.2    0.16       0  5329.3    0.07       0  5336.6    0.16       0
  5468.6    0.05       0
Bank Sta=5329.3,5336.6
Exp/Cntr=0.3,0.1

Chan Stop Cuts=-1