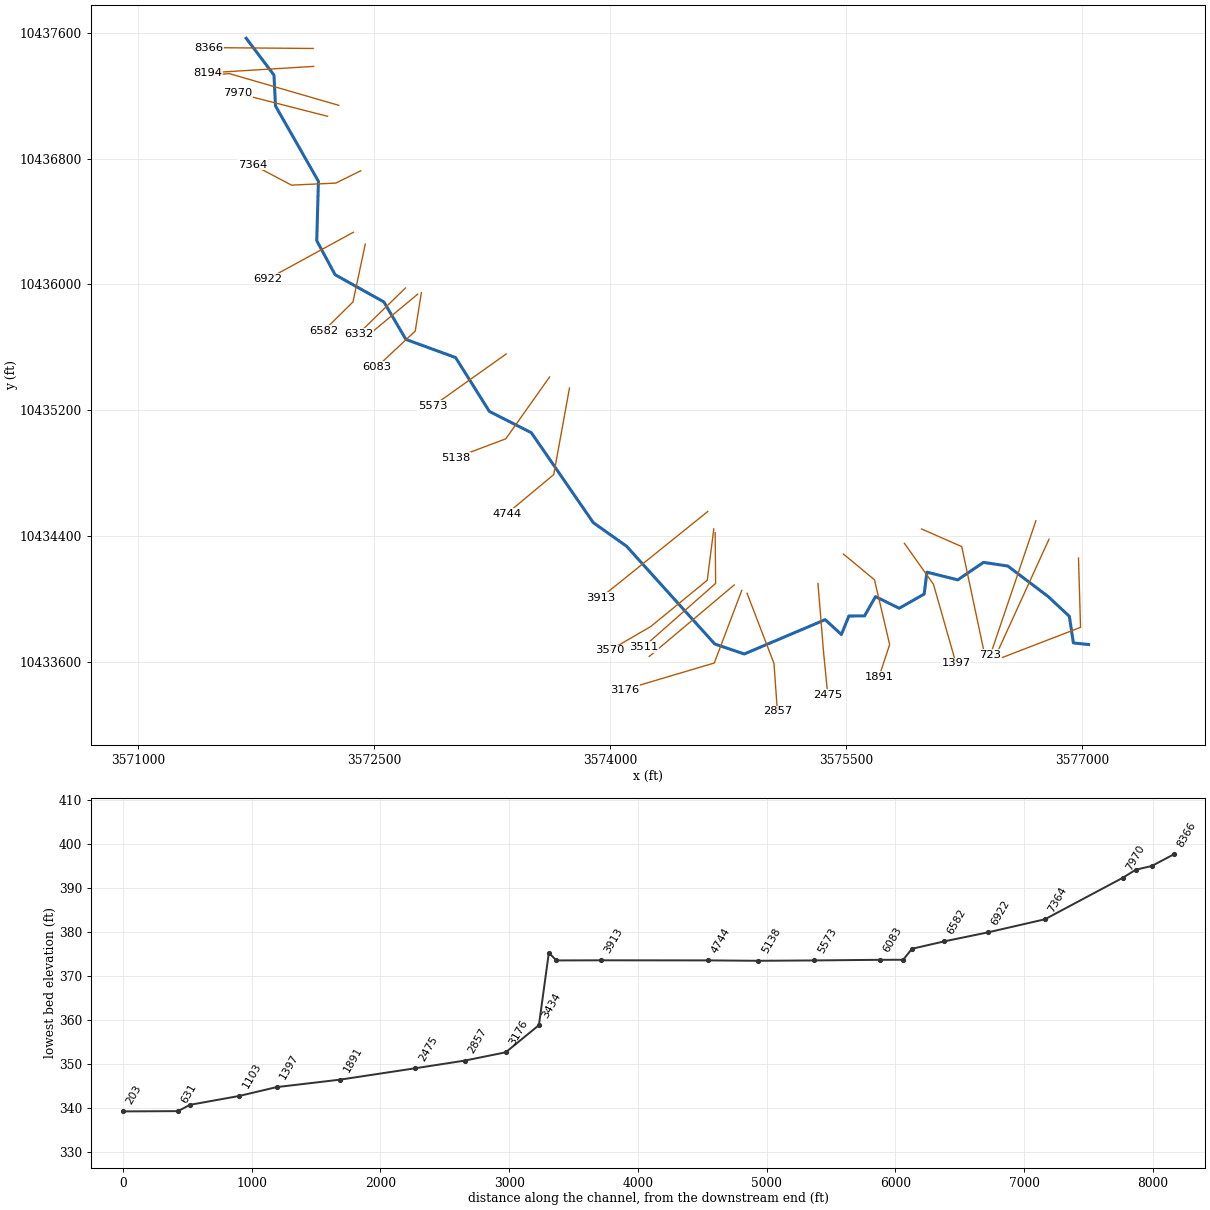
--- UNT03099 IN DUCK CR.prj (project) ---

Proj Title=UNT03099 IN DUCK CR Base Level Engineering
Current Plan=p01
Default Exp/Contr=0.3,0.1
English Units
Geom File=g01
Flow File=f01
Plan File=p01
Y Axis Title=Elevation
X Axis Title(PF)=Main Channel Distance
X Axis Title(XS)=Station
BEGIN DESCRIPTION:
UNT03099 IN DUCK CR
END DESCRIPTION:
DSS Export Rating Curves= 0
DSS Export Rating Curve Sorted= 0
DSS Export Volume Flow Curves= 0
DXF OffsetX= 0
DXF OffsetY= 0
DXF ScaleX= 1
DXF ScaleY= 10

--- UNT03099 IN DUCK CR.p01 (plan) ---

Plan Title=Multiple Run
Short Identifier=Multiple
Geom File=g01
Flow File=f01
Subcritical Flow
K Sum by GR= 0
Std Step Tol= 0.01
Critical Tol= 0.01
Num of Std Step Trials= 20
Max Error Tol= 0.3
Flow Tol Ratio= 0.001
Split Flow NTrial= 30
Split Flow Tol= 0.02
Split Flow Ratio= 0.02
Log Output Level= 0
Friction Slope Method= 1
Unsteady Friction Slope Method= 2
Unsteady Bridges Friction Slope Method= 1
Parabolic Critical Depth
Global Vel Dist=  1 , 1 , 1
Global Log Level= 0
CheckData=True
Encroach Param= -1, 0, 0, 0
BEGIN DESCRIPTION:
Multiple Run
END DESCRIPTION:

--- UNT03099 IN DUCK CR.f01 (steady flow) ---

Flow Title=Multiple
Number of Profiles=7
Profile Names=10-year,25-year,50-year,1pct_min,100-year,1pct_plu,500-year
River Rch & RM= UNT03099 IN DUCK,Reach-1,8366
    1078    1492    1835    1648    2229    3014    3276
Boundary for River Rch & Prof#=UNT03099 IN DUCK,Reach-1,1
Up Type=0
Dn Type=3
Dn Slope=0.005
Boundary for River Rch & Prof#=UNT03099 IN DUCK,Reach-1,2
Up Type=0
Dn Type=3
Dn Slope=0.005
Boundary for River Rch & Prof#=UNT03099 IN DUCK,Reach-1,3
Up Type=0
Dn Type=3
Dn Slope=0.005
Boundary for River Rch & Prof#=UNT03099 IN DUCK,Reach-1,4
Up Type=0
Dn Type=3
Dn Slope=0.005
Boundary for River Rch & Prof#=UNT03099 IN DUCK,Reach-1,5
Up Type=0
Dn Type=3
Dn Slope=0.005
Boundary for River Rch & Prof#=UNT03099 IN DUCK,Reach-1,6
Up Type=0
Dn Type=3
Dn Slope=0.005
Boundary for River Rch & Prof#=UNT03099 IN DUCK,Reach-1,7
Up Type=0
Dn Type=3
Dn Slope=0.005

--- UNT03099 IN DUCK CR.g01 (geometry) ---

Geom Title=Existing Conditions
Program Version=4.10

River Reach=UNT03099 IN DUCK,Reach-1
Reach XY= 30
      3571687.04     10437564.23      3571863.57     10437330.22
      3571873.56     10437133.61      3572146.21     10436655.57
      3572135.58     10436278.19      3572252.25     10436061.53
      3572562.66     10435888.61      3572702.25     10435650.42
      3573018.13      10435535.3      3573232.98     10435192.85
       3573499.9     10435057.43      3573893.36      10434486.2
      3574104.95     10434336.46      3574665.55     10433715.19
      3574853.09     10433651.56      3575367.81     10433869.61
      3575470.72       10433775.      3575518.21     10433892.79
      3575617.79      10433893.6      3575687.58     10434016.26
       3575838.1     10433942.04      3575996.69     10434032.15
       3576014.4     10434171.47      3576210.24     10434122.51
      3576373.78     10434233.71      3576528.36     10434210.48
      3576784.97     10434016.75      3576919.81     10433890.75
      3576945.42      10433721.6      3577042.11     10433711.64

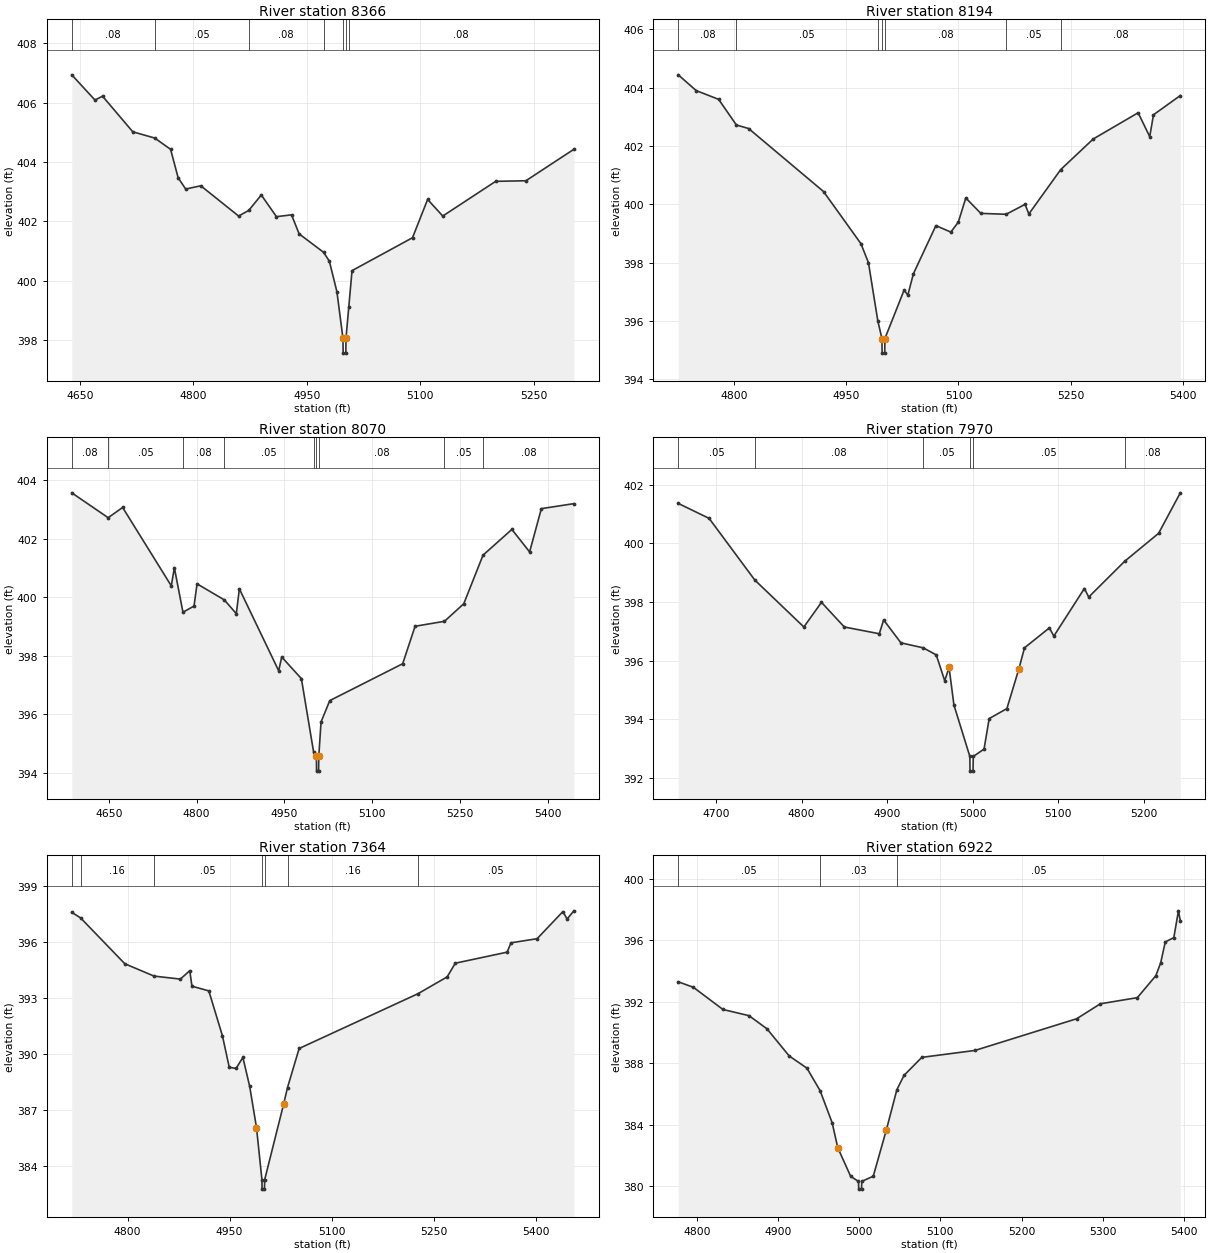
Type RM Length L Ch R = 1 ,8366    ,172,172,172
BEGIN DESCRIPTION:
UNT03099 IN DUCK CR 3 0
END DESCRIPTION:
XS GIS Cut Line= 2
      3572112.82     10437499.25      3571448.74     10437504.68
#Sta/Elev= 30
  4639.2  406.94  4669.9  406.09  4679.9  406.22  4719.9  405.02  4748.8  404.81
  4769.9  404.43  4779.9  403.47  4789.9  403.09  4809.9   403.2  4859.9  402.18
  4873.3  402.37  4889.9  402.89  4909.9  402.16  4929.9  402.22  4939.9  401.58
  4972.2  400.96  4979.9  400.66  4989.9  399.63  4997.9  398.06  4998.2  397.56
  5001.7  397.56  5001.9  398.06  5005.6  399.11  5009.9  400.34  5089.9  401.45
  5109.9  402.74  5129.9  402.18  5199.9  403.35  5239.9  403.37  5303.3  404.43
#Mann= 7 ,-1 , 0
  4639.2     .08       0  4748.8     .05       0  4873.3     .08       0
  4972.2     .05       0  4997.9     .04       0  5001.9     .05       0
  5005.6     .08       0
Bank Sta=4997.9,5001.9
XS Rating Curve= 0 ,0
Exp/Cntr=0.3,0.1

Type RM Length L Ch R = 1 ,8194    ,124,124,124
BEGIN DESCRIPTION:
UNT03099 IN DUCK CR 3 8
END DESCRIPTION:
XS GIS Cut Line= 2
      3572116.03     10437385.32      3571445.79     10437344.17
#Sta/Elev= 30
  4725.2  404.44  4749.2   403.9  4779.2   403.6    4803  402.72  4819.3   402.6
  4919.5  400.44  4969.6  398.65  4979.6     398  4992.1  396.01  4997.6   395.4
  4997.9   394.9  5001.4   394.9  5001.6   395.4  5027.3  397.06  5032.3  396.89
  5039.7  397.62  5069.8  399.27  5089.8  399.05  5099.8  399.39  5109.8  400.22
  5129.9  399.69  5163.8  399.66  5189.1     400  5194.1  399.67  5236.7  401.19
  5280.2  402.24  5340.3  403.14  5355.8  402.32  5360.8  403.07  5396.7  403.73
#Mann= 7 ,-1 , 0
  4725.2     .08       0    4803     .05       0  4992.1     .08       0
  4997.6     .07       0  5001.6     .08       0  5163.8     .05       0
  5236.7     .08       0
Bank Sta=4997.6,5001.6
XS Rating Curve= 0 ,0
Exp/Cntr=0.3,0.1

Type RM Length L Ch R = 1 ,8070    ,100,100,100
BEGIN DESCRIPTION:
UNT03099 IN DUCK CR 3 7
END DESCRIPTION:
XS GIS Cut Line= 3
      3572275.59     10437137.91      3571578.94     10437339.75
      3571446.88     10437326.76
#Sta/Elev= 30
  4586.7  403.57  4648.9  402.72  4673.6  403.07  4756.8  400.39    4762  401.01
  4776.7  399.49  4795.6   399.7  4800.8  400.46  4847.5  399.91  4867.9  399.44
  4873.1  400.29  4940.3  397.49  4945.5  397.96  4979.1  397.22    5000  394.71
  5004.8  394.56    5005  394.06  5008.5  394.06  5008.8  394.56  5012.7  395.74
  5027.6  396.47  5152.2  397.73  5173.4  399.01  5223.6  399.18  5256.6  399.78
  5289.5  401.44  5338.8  402.32  5369.1  401.55  5389.2  403.03  5444.7   403.2
#Mann= 9 ,-1 , 0
  4586.7     .08       0  4648.9     .05       0  4776.7     .08       0
  4847.5     .05       0    5000     .08       0  5004.8     .07       0
  5008.8     .08       0  5223.6     .05       0  5289.5     .08       0
Bank Sta=5004.8,5008.8
XS Rating Curve= 0 ,0
Exp/Cntr=0.3,0.1

Type RM Length L Ch R = 1 ,7970    ,606,606,606
BEGIN DESCRIPTION:
UNT03099 IN DUCK CR 3 9
END DESCRIPTION:
XS GIS Cut Line= 2
      3572204.41     10437068.29      3571635.61     10437213.74
#Sta/Elev= 30
  4655.8  401.36  4691.9  400.85  4745.3  398.75  4802.7  397.15  4823.3  397.99
    4850  397.15  4890.9  396.92    4896  397.39  4916.2  396.61  4942.3  396.44
  4957.5   396.2  4967.4  395.32  4972.5  395.77  4978.2  394.49  4996.8  392.74
    4997  392.24  5000.5  392.24  5000.8  392.74  5013.4  392.99  5019.4  394.03
  5040.1  394.37  5054.2  395.73  5060.7  396.44  5089.8  397.12    5095  396.84
  5130.7  398.46  5135.8  398.17  5177.9  399.39  5217.5  400.34  5242.9  401.72
#Mann= 6 ,-1 , 0
  4655.8     .05       0  4745.3     .08       0  4942.3     .05       0
  4996.8     .03       0  5000.8     .05       0  5177.9     .08       0
Bank Sta=4972.5,5054.2
XS Rating Curve= 0 ,0
Exp/Cntr=0.3,0.1

Type RM Length L Ch R = 1 ,7364    ,442,442,442
BEGIN DESCRIPTION:
UNT03099 IN DUCK CR 2 0
END DESCRIPTION:
XS GIS Cut Line= 4
      3572415.41     10436721.94      3572256.54      10436643.8
      3571975.29     10436630.78      3571727.86     10436761.01
#Sta/Elev= 30
    4718  397.59    4731  397.29    4796  394.84    4839  394.18  4877.7  394.02
  4891.5  394.47  4894.7  393.64  4919.5  393.39  4939.5  390.99  4949.5  389.31
  4959.5  389.24  4969.6  389.83  4979.6  388.28  4989.6  386.08  4997.6  383.29
  4997.8  382.79  5001.3  382.79  5001.6  383.29  5029.6  387.35  5035.2  388.22
  5052.3  390.31  5227.1  393.24    5270  394.14  5281.9  394.87  5358.1  395.46
  5363.8  395.96  5402.2  396.18  5440.1  397.63  5446.3  397.23  5456.2  397.67
#Mann= 7 ,-1 , 0
    4718     .05       0    4731     .16       0    4839     .05       0
  4997.6     .04       0  5001.6     .05       0  5035.2     .16       0
  5227.1     .05       0
Bank Sta=4989.6,5029.6
XS Rating Curve= 0 ,0
Exp/Cntr=0.3,0.1

Type RM Length L Ch R = 1 ,6922    ,340,340,340
BEGIN DESCRIPTION:
UNT03099 IN DUCK CR 18 0
END DESCRIPTION:
XS GIS Cut Line= 2
      3572368.55     10436331.32      3571825.66      10436035.2
#Sta/Elev= 30
  4777.1  393.29  4795.8  392.93  4832.2  391.49  4864.2  391.09  4886.3  390.24
  4913.8  388.47  4935.6  387.68  4951.8  386.22  4966.7  384.13  4973.6  382.51
  4989.5  380.65  4999.1  380.32  4999.4  379.82  5002.9  379.82  5003.1  380.32
  5017.3  380.66  5033.4  383.66  5046.4  386.28  5055.2  387.21  5077.1  388.38
  5142.6  388.83  5267.9  390.89    5297  391.86  5342.6  392.26  5365.4  393.69
  5371.3  394.52    5377  395.88  5387.5  396.16  5393.2   397.9  5395.5  397.25
#Mann= 3 ,-1 , 0
  4777.1     .05       0  4951.8     .03       0  5046.4     .05       0
Bank Sta=4973.6,5033.4
XS Rating Curve= 0 ,0
Exp/Cntr=0.3,0.1

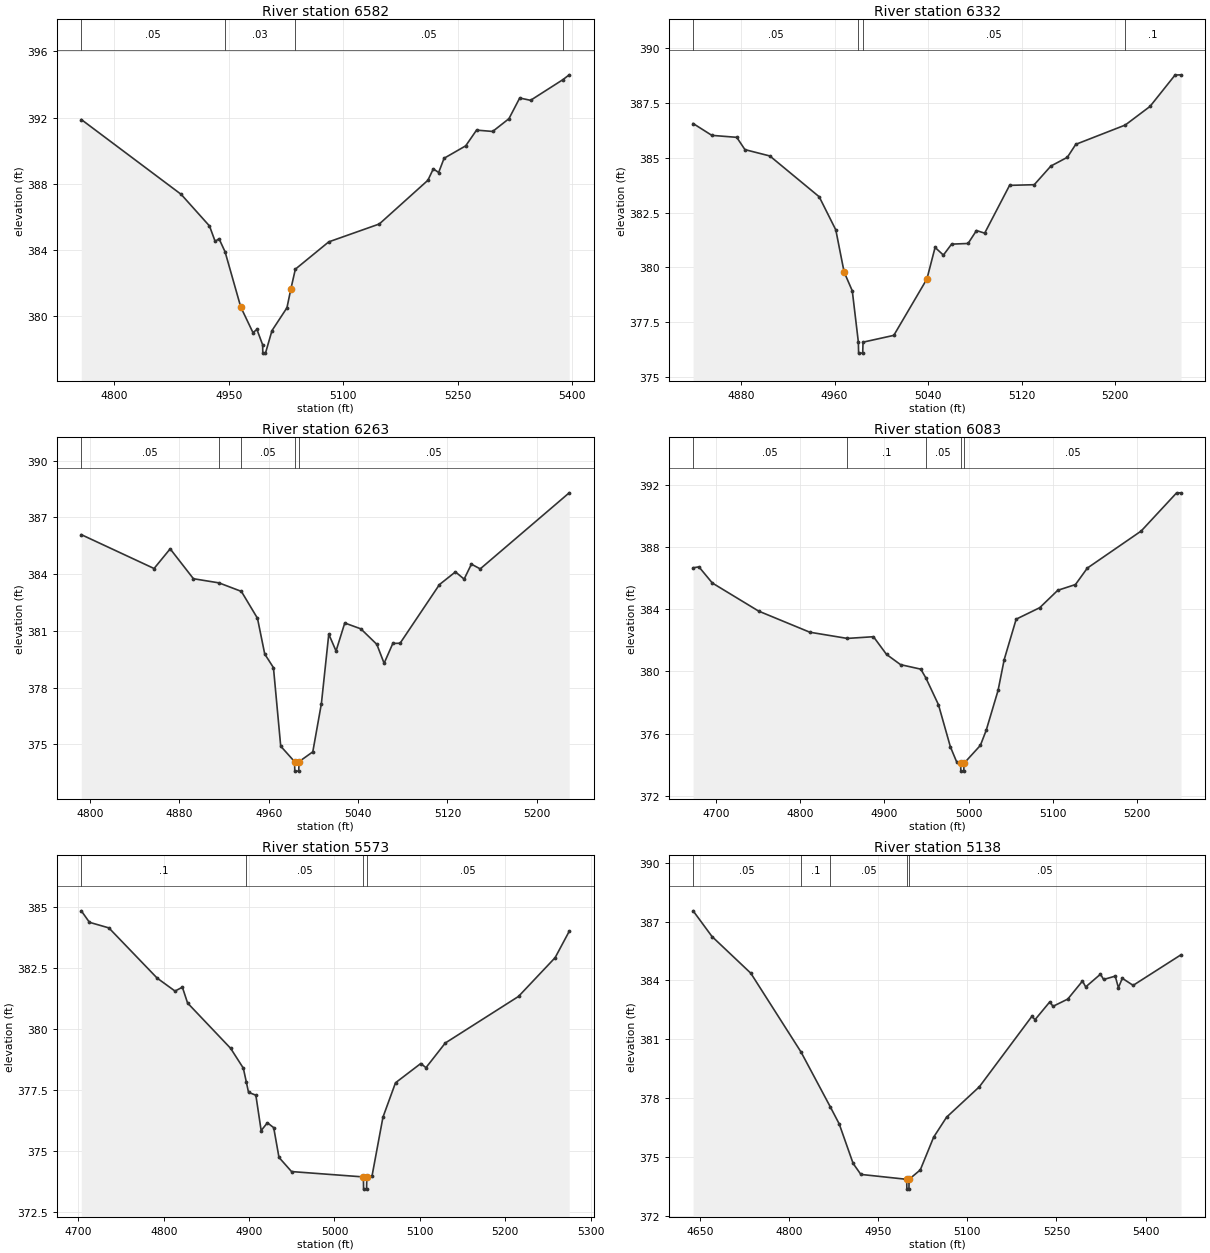
Type RM Length L Ch R = 1 ,6582    ,250,250,250
BEGIN DESCRIPTION:
UNT03099 IN DUCK CR 16 0
END DESCRIPTION:
XS GIS Cut Line= 3
      3572444.03     10436255.76      3572365.91      10435888.6
      3572178.42     10435703.71
#Sta/Elev= 30
  4757.1  391.88  4887.8  387.36  4924.9  385.45  4932.3  384.52  4937.4  384.68
  4945.3  383.89  4965.8  380.56  4981.8  379.01    4987   379.2  4994.5  378.27
  4994.7  377.77  4998.2  377.77  5006.7  379.13  5026.3  380.51  5031.4  381.64
  5037.3  382.84    5081  384.49  5147.2  385.57  5210.8  388.21  5217.9   388.9
  5224.9  388.68    5232  389.54  5260.3  390.29  5274.5  391.24  5295.6  391.16
  5316.9  391.93    5331  393.18  5345.2  393.04  5387.6  394.29  5395.8  394.58
#Mann= 4 ,-1 , 0
  4757.1     .05       0  4945.3     .03       0  5037.3     .05       0
  5387.6     .16       0
Bank Sta=4965.8,5031.4
XS Rating Curve= 0 ,0
Exp/Cntr=0.3,0.1

Type RM Length L Ch R = 1 ,6332    ,69,69,69
BEGIN DESCRIPTION:
Mapping XS 1e2cf211
END DESCRIPTION:
XS GIS Cut Line= 2
      3572699.23     10435977.13      3572400.36     10435686.05
#Sta/Elev= 30
  4839.1  386.56  4855.1  386.02  4876.4  385.93  4883.4  385.37  4904.7  385.08
  4946.9  383.22  4961.1  381.71  4968.2  379.79  4975.2  378.93  4980.4  376.59
  4980.6  376.09  4984.1  376.09  4984.4  376.59  5010.7   376.9    5039  379.47
    5046  380.91  5053.1  380.56  5060.1  381.06  5074.2  381.09  5081.4  381.68
  5088.4  381.56  5109.7  383.74  5130.8  383.77    5145  384.62  5159.1  385.02
  5166.3  385.61  5208.6  386.49  5229.8  387.34  5251.2  388.77  5256.3  388.78
#Mann= 4 ,-1 , 0
  4839.1     .05       0  4980.4     .03       0  4984.4     .05       0
  5208.6      .1       0
Bank Sta=4968.2,5039
XS Rating Curve= 0 ,0
Exp/Cntr=0.3,0.1

Type RM Length L Ch R = 1 ,6263    ,180,180,180
BEGIN DESCRIPTION:
Mapping XS 7a8d0fd1
END DESCRIPTION:
XS GIS Cut Line= 2
       3572777.4      10435938.1      3572441.43     10435659.43
#Sta/Elev= 30
  4792.4  386.09  4857.5   384.3  4871.9  385.34  4892.7  383.76  4915.6  383.54
  4935.6  383.09    4950  381.67  4956.5  379.78  4964.3  379.06  4970.8  374.91
  4983.2  374.09  4983.4  373.59  4986.9  373.59  4987.2  374.09  4999.5  374.61
  5007.2  377.16  5013.8  380.83  5020.3  379.94  5028.1  381.42  5042.5  381.11
  5056.8  380.29  5063.3  379.29  5071.1  380.34  5077.6  380.35  5112.8  383.45
  5127.1  384.12  5134.9  383.74  5141.4  384.53  5149.3  384.28  5228.9   388.3
#Mann= 5 ,-1 , 0
  4792.4     .05       0  4915.6      .1       0  4935.6     .05       0
  4983.2     .03       0  4987.2     .05       0
Bank Sta=4983.2,4987.2
XS Rating Curve= 0 ,0
Exp/Cntr=0.3,0.1

Type RM Length L Ch R = 1 ,6083    ,510,510,510
BEGIN DESCRIPTION:
UNT03099 IN DUCK CR 15 0
END DESCRIPTION:
XS GIS Cut Line= 3
      3572800.81     10435948.48      3572761.74      10435703.7
      3572519.57     10435477.15
#Sta/Elev= 30
  4672.9  386.68  4679.8  386.74  4695.7   385.7  4750.7  383.89  4811.5  382.53
    4856  382.13  4887.1  382.24  4902.6   381.1  4919.3  380.44  4943.3  380.15
  4949.3  379.59  4964.3  377.86  4978.5  375.14  4985.8  374.19  4990.6  374.08
  4990.9  373.58  4994.4  373.58  4994.6  374.08  5014.1  375.24    5021  376.21
  5035.1  378.78  5042.4  380.77  5056.6  383.37  5084.6  384.11    5106  385.23
    5127   385.6  5141.1  386.66  5205.1  389.05  5247.2  391.51  5252.4  391.51
#Mann= 5 ,-1 , 0
  4672.9     .05       0    4856      .1       0  4949.3     .05       0
  4990.6     .03       0  4994.6     .05       0
Bank Sta=4990.6,4994.6
XS Rating Curve= 0 ,0
Exp/Cntr=0.3,0.1

Type RM Length L Ch R = 1 ,5573    ,435,435,435
BEGIN DESCRIPTION:
UNT03099 IN DUCK CR 14 0
END DESCRIPTION:
XS GIS Cut Line= 2
      3573339.87     10435557.87      3572873.69     10435227.11
#Sta/Elev= 30
  4703.4  384.85  4712.9  384.38  4735.7  384.15  4792.3  382.09  4813.2  381.56
  4821.8  381.72  4827.9  381.07  4878.4  379.21  4893.2   378.4  4896.8  377.82
  4899.3  377.41  4907.9  377.29  4914.1  375.84  4921.4  376.16  4928.8  375.96
    4935  374.74  4949.7  374.16  5033.9  373.94  5034.1  373.44  5037.6  373.44
  5037.9  373.94    5044  373.98  5056.8  376.39  5071.5   377.8  5101.1  378.59
  5107.2  378.42  5129.8  379.43  5215.6  381.34  5258.5  382.93    5275  384.01
#Mann= 4 ,-1 , 0
  4703.4      .1       0  4896.8     .05       0  5033.9    .033       0
  5037.9     .05       0
Bank Sta=5033.9,5037.9
XS Rating Curve= 0 ,0
Exp/Cntr=0.3,0.1

Type RM Length L Ch R = 1 ,5138    ,394,394,394
BEGIN DESCRIPTION:
UNT03099 IN DUCK CR 13 0
END DESCRIPTION:
XS GIS Cut Line= 3
      3573615.92     10435412.05      3573337.27      10435018.8
      3573019.57     10434899.02
#Sta/Elev= 30
  4638.3  387.55  4670.1  386.24  4735.4  384.37    4820  380.35    4869  377.57
  4884.2  376.69  4907.7  374.67  4920.7  374.11  4997.9  373.86  4998.2  373.36
  5001.7  373.36  5001.9  373.86  5020.8  374.34  5043.3  376.01  5065.1  377.03
  5120.3  378.58  5208.7  382.17    5214     382  5238.9  382.91  5244.2  382.68
  5269.1  383.05  5293.9  383.97  5299.3  383.67  5324.2  384.32  5329.5  384.05
    5349  384.22  5354.4  383.63  5360.9  384.11  5379.2  383.75  5459.8  385.31
#Mann= 5 ,-1 , 0
  4638.3     .05       0    4820      .1       0    4869     .05       0
  4997.9    .033       0  5001.9     .05       0
Bank Sta=4997.9,5001.9
XS Rating Curve= 0 ,0
Exp/Cntr=0.3,0.1

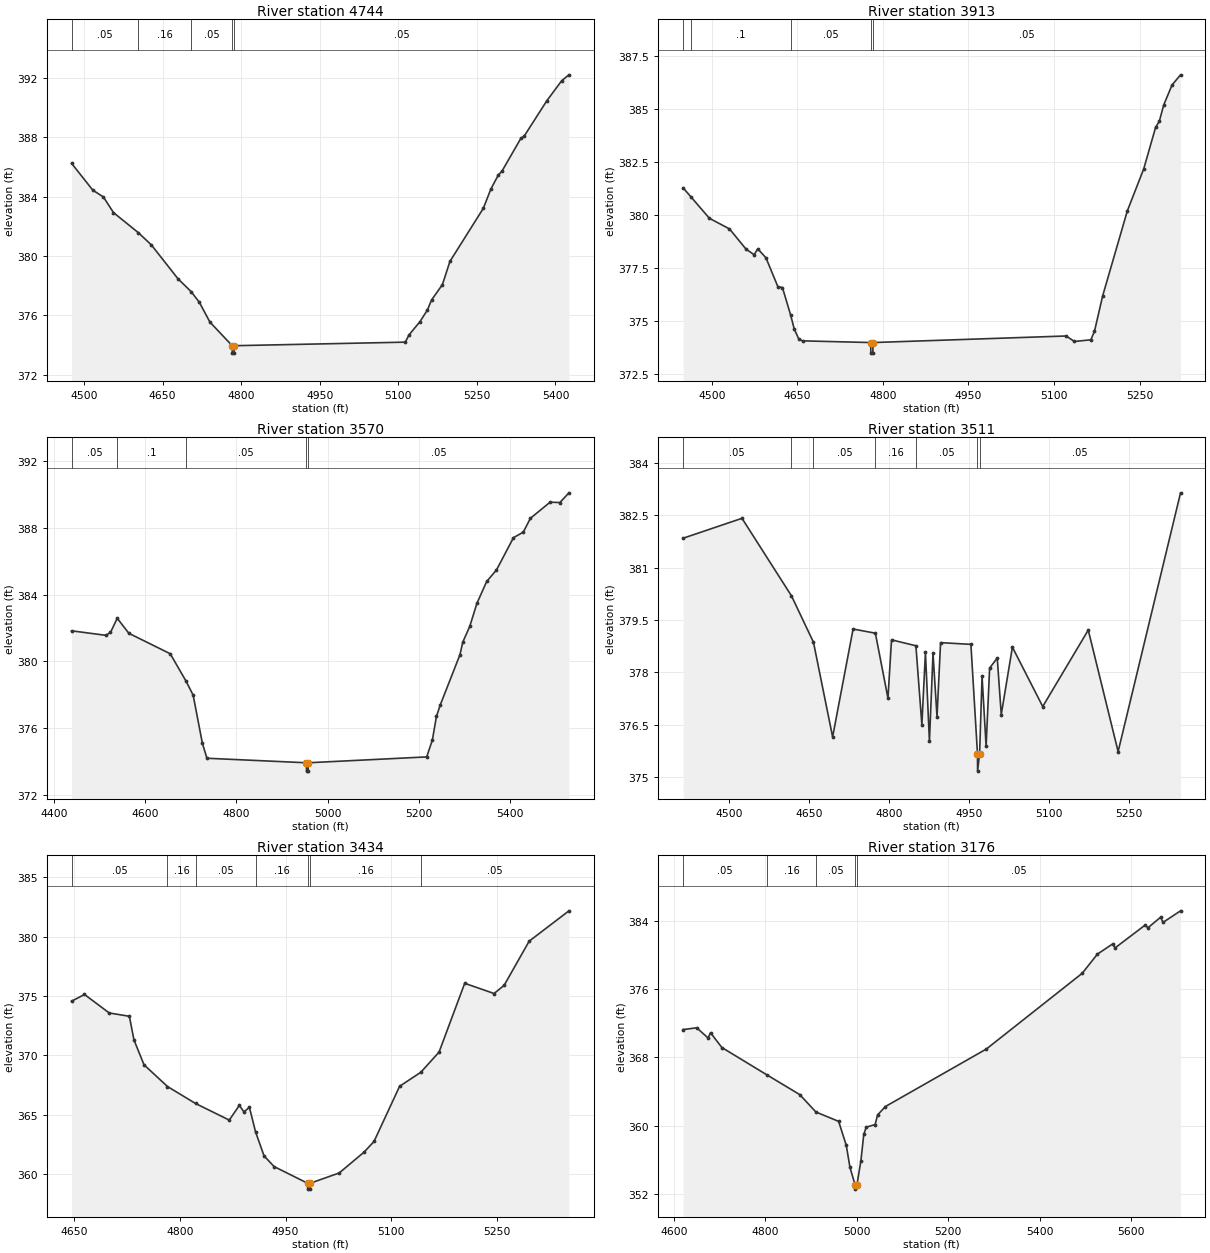
Type RM Length L Ch R = 1 ,4744    ,831,831,831
BEGIN DESCRIPTION:
UNT03099 IN DUCK CR 12 0
END DESCRIPTION:
XS GIS Cut Line= 3
       3573742.1     10435341.61      3573642.11     10434791.64
       3573342.1     10434541.64
#Sta/Elev= 30
  4476.3  386.24  4516.9  384.43  4537.2  383.97  4556.3  382.92    4604  381.56
  4628.7  380.74  4679.5  378.46  4704.4   377.6  4720.2  376.88  4740.5  375.54
    4783  373.95  4783.2  373.45  4786.7  373.45    4787  373.95  5113.4  374.19
  5120.5  374.68  5141.4  375.57  5155.7  376.36  5163.5  377.03  5184.3  378.07
  5198.6  379.63  5262.4  383.21  5276.7   384.5  5291.1  385.46  5297.6  385.69
    5334  387.92  5340.5  388.08  5383.5  390.45  5412.1  391.81  5425.8   392.2
#Mann= 5 ,-1 , 0
  4476.3     .05       0    4604     .16       0  4704.4     .05       0
    4783    .033       0    4787     .05       0
Bank Sta=4783,4787
XS Rating Curve= 0 ,0
Exp/Cntr=0.3,0.1

Type RM Length L Ch R = 1 ,3913    ,343,343,343
BEGIN DESCRIPTION:
UNT03099 IN DUCK CR 21 0
END DESCRIPTION:
XS GIS Cut Line= 2
      3574621.22     10434557.05      3573941.92     10434010.13
#Sta/Elev= 30
  4449.8  381.28  4463.6  380.85  4495.9  379.84  4531.1  379.34  4559.9  378.39
  4574.3  378.12  4580.7   378.4  4595.1  377.97  4615.9  376.61  4623.9  376.57
  4638.2  375.28  4644.7   374.6  4652.7  374.13  4659.1  374.05  4778.7  373.97
  4778.9  373.47  4782.4  373.47  4782.7  373.97  5121.4  374.28  5135.8  374.02
  5164.6   374.1    5171   374.5  5185.4  376.18  5228.6  380.19  5257.4  382.18
  5278.2  384.14  5284.6  384.42  5292.6  385.21    5307  386.14  5321.9  386.62
#Mann= 5 ,-1 , 0
  4449.8     .05       0  4463.6      .1       0  4638.2     .05       0
  4778.7    .033       0  4782.7     .05       0
Bank Sta=4778.7,4782.7
XS Rating Curve= 0 ,0
Exp/Cntr=0.3,0.1

Type RM Length L Ch R = 1 ,3570    ,59,59,59
BEGIN DESCRIPTION:
UNT03099 IN DUCK CR 20 0
END DESCRIPTION:
XS GIS Cut Line= 4
       3574659.6     10434446.38      3574618.02     10434120.31
      3574259.85     10433826.79      3574000.77     10433676.11
#Sta/Elev= 30
  4438.2  381.83  4513.5  381.56  4523.6  381.73  4538.5  382.58    4564  381.68
  4654.7  380.46  4689.7  378.81  4705.1  377.98  4725.2  375.12  4735.3  374.21
  4953.6  373.94  4953.8  373.44  4957.3  373.44  4957.6  373.94  5217.5  374.29
    5230   375.3  5238.9  376.71  5247.5  377.41  5290.5   380.4  5296.8  381.16
    5312  382.09  5327.7  383.47  5349.2  384.78  5370.7  385.47    5408   387.4
  5429.5  387.73  5445.2  388.56  5488.3  389.52  5509.8   389.5  5529.7  390.08
#Mann= 5 ,-1 , 0
  4438.2     .05       0  4538.5      .1       0  4689.7     .05       0
  4953.6    .033       0  4957.6     .05       0
Bank Sta=4953.6,4957.6
XS Rating Curve= 0 ,0
Exp/Cntr=0.3,0.1

Type RM Length L Ch R = 1 ,3511    ,77,77,77
BEGIN DESCRIPTION:
Mapping XS e33d8f58
END DESCRIPTION:
XS GIS Cut Line= 3
      3574668.29     10434422.08       3574671.1     10434099.94
      3574212.67     10433696.24
#Sta/Elev= 30
  4413.2  381.84  4523.6  382.41  4616.4  380.19  4657.7  378.86  4693.6  376.15
    4732  379.24  4773.8  379.12  4797.4  377.26  4804.1  378.93  4849.8  378.76
    4861   376.5  4867.7  378.57  4875.2  376.02  4881.9  378.54  4889.4  376.73
  4896.1  378.85    4953   378.8  4965.3  375.67  4965.5  375.17  4969.3  375.67
  4973.9  377.88  4981.5  375.88  4988.1  378.12  5002.4  378.41  5009.9  376.79
  5030.8  378.72  5087.7  377.02  5173.1  379.21  5229.1  375.73  5346.2  383.14
#Mann= 7 ,-1 , 0
  4413.2     .05       0  4616.4      .1       0  4657.7     .05       0
  4773.8     .16       0  4849.8     .05       0  4965.3    .033       0
  4969.3     .05       0
Bank Sta=4965.3,4969.3
XS Rating Curve= 0 ,0
Exp/Cntr=0.3,0.1

Type RM Length L Ch R = 1 ,3434    ,258,258,258
BEGIN DESCRIPTION:
Mapping XS 360eacdf
END DESCRIPTION:
XS GIS Cut Line= 2
      3574789.16     10434090.13      3574248.86     10433635.54
#Sta/Elev= 30
  4646.1  374.57  4664.5  375.14  4699.6  373.58  4728.2   373.3  4734.7  371.31
    4749  369.21  4782.3  367.38  4822.1  365.95    4870  364.55  4884.3  365.79
  4890.8  365.24  4898.6  365.63  4907.3  363.56  4919.4  361.53  4933.7  360.63
  4981.1  359.23  4981.4  358.73  4984.9  358.73  4985.1  359.23    5026  360.09
  5061.2  361.84  5075.5  362.75  5111.8   367.4  5141.9  368.58  5167.8  370.28
  5204.2  376.08  5245.9  375.22  5260.2  375.91  5295.7  379.63  5352.2  382.19
#Mann= 7 ,-1 , 0
  4646.1     .05       0  4782.3     .16       0  4822.1     .05       0
  4907.3     .16       0  4981.1     .07       0  4985.1     .16       0
  5141.9     .05       0
Bank Sta=4981.1,4985.1
XS Rating Curve= 0 ,0
Exp/Cntr=0.3,0.1

Type RM Length L Ch R = 1 ,3176    ,319,319,319
BEGIN DESCRIPTION:
UNT03099 IN DUCK CR 9 0
END DESCRIPTION:
XS GIS Cut Line= 3
      3574837.28      10434055.3      3574662.79     10433594.32
      3574092.48     10433425.05
#Sta/Elev= 30
  4620.5  371.26  4650.2  371.47    4675  370.28  4680.4  370.89  4705.2  369.16
  4804.4  365.93  4875.5  363.64  4910.9   361.6  4960.6   360.5  4977.3  357.69
  4985.4   355.1  4996.6  353.06  4996.9  352.56  5000.6  353.06  5009.3   355.9
  5015.6  358.99  5020.9  359.82  5040.4  360.13  5045.7  361.25  5062.8  362.24
  5283.6  368.98  5493.3  377.86  5526.6  380.11  5559.8   381.3    5565  380.83
  5631.4  383.53  5636.7  383.18  5664.7  384.43  5669.9  383.82  5708.3  385.18
#Mann= 5 ,-1 , 0
  4620.5     .05       0  4804.4     .16       0  4910.9     .05       0
  4996.6     .03       0  5000.6     .05       0
Bank Sta=4996.6,5000.6
XS Rating Curve= 0 ,0
Exp/Cntr=0.3,0.1

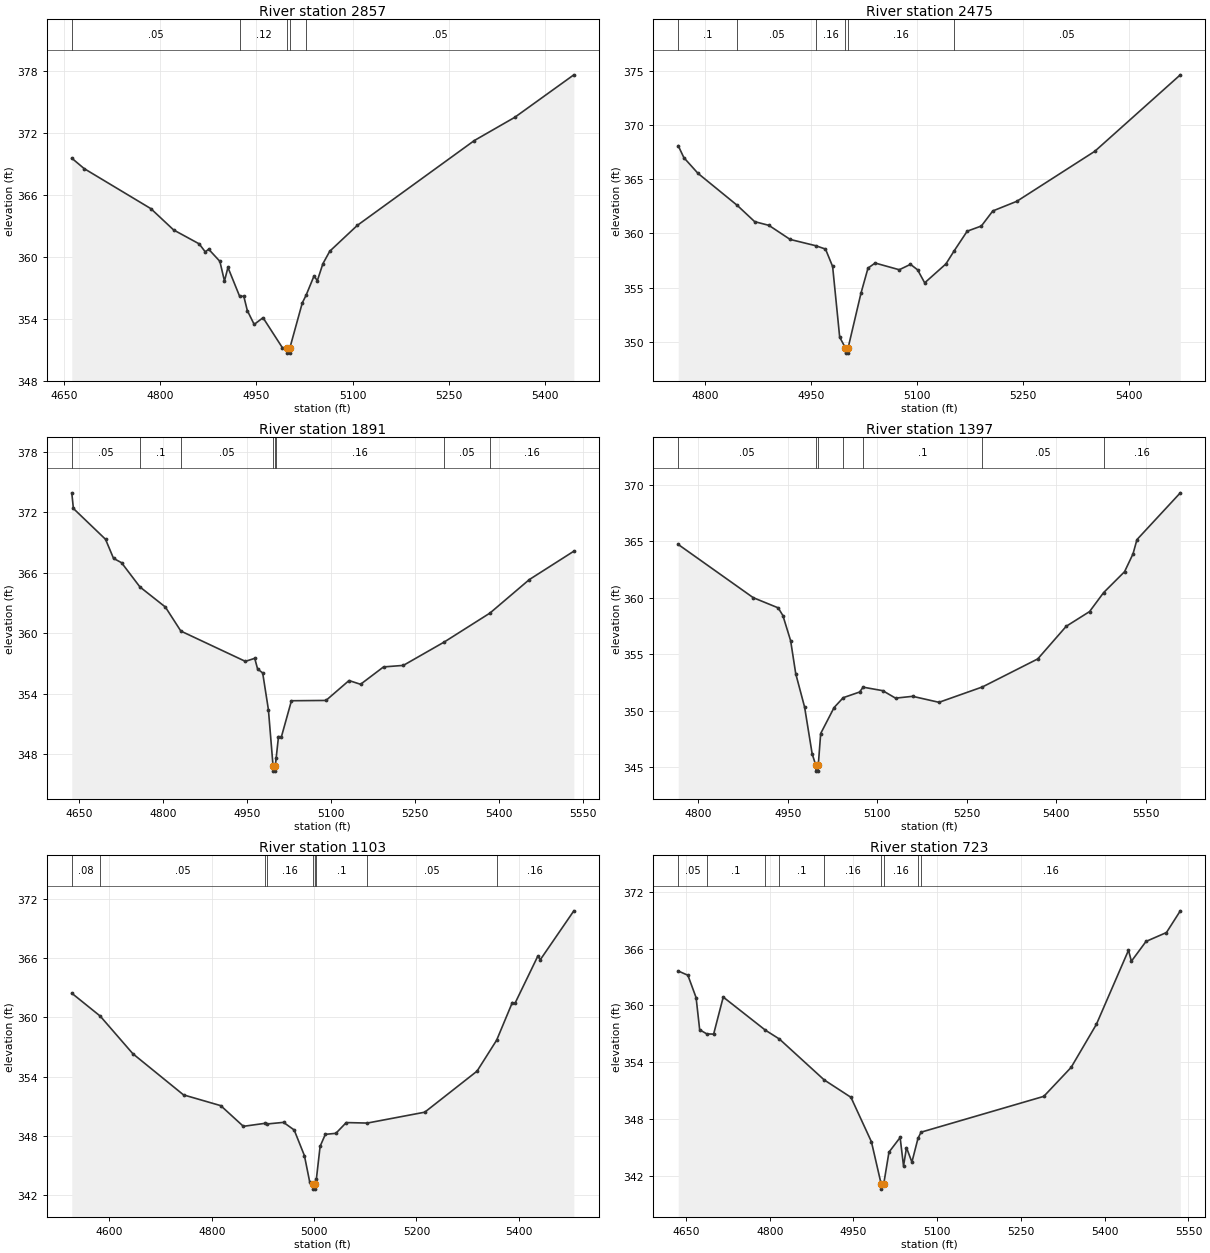
Type RM Length L Ch R = 1 ,2857    ,382,382,382
BEGIN DESCRIPTION:
UNT03099 IN DUCK CR 8 0
END DESCRIPTION:
XS GIS Cut Line= 3
       3574871.1     10434037.07      3575042.11     10433591.64
      3575063.83     10433287.04
#Sta/Elev= 30
  4662.2  369.55  4681.5  368.54  4785.5  364.66  4820.9   362.6  4860.8  361.25
  4870.2  360.48  4875.6  360.73    4893  359.56  4900.2  357.65  4905.6  358.97
  4923.9  356.16  4930.3  356.18  4935.8  354.79  4946.5  353.45  4960.3   354.1
  4990.3  351.21  4998.1  351.17  4998.3  350.67  5001.8  350.67  5002.1  351.17
  5021.5  355.54  5027.5  356.29  5039.6  358.12    5045   357.7  5053.6  359.33
  5064.3  360.54  5107.2  363.04  5289.7  371.26  5352.5   373.5  5444.7  377.62
#Mann= 5 ,-1 , 0
  4662.2     .05       0  4923.9     .12       0  4998.1     .07       0
  5002.1     .12       0  5027.5     .05       0
Bank Sta=4998.1,5002.1
XS Rating Curve= 0 ,0
Exp/Cntr=0.3,0.1

Type RM Length L Ch R = 1 ,2475    ,584,584,584
BEGIN DESCRIPTION:
UNT03099 IN DUCK CR 7 0
END DESCRIPTION:
XS GIS Cut Line= 3
      3575321.64     10434099.58       3575358.1     10433654.22
      3575384.14     10433391.16
#Sta/Elev= 30
  4761.8  368.09  4769.8  366.99  4789.8  365.54  4845.3  362.59  4870.1  361.08
  4890.2  360.74  4920.3  359.44  4956.5  358.86  4970.4  358.55  4980.5  356.94
  4990.5  350.41  4998.5  349.44  4998.8  348.94  5002.3  348.94  5002.5  349.44
  5020.6  354.46  5030.6  356.79  5040.7  357.26  5074.9  356.64  5090.8  357.14
  5100.9  356.63  5110.9  355.43    5141  357.18  5152.8   358.4  5171.1   360.2
  5191.2  360.68  5207.4  362.07  5241.4  362.96  5351.9  367.58    5473  374.64
#Mann= 6 ,-1 , 0
  4761.8      .1       0  4845.3     .05       0  4956.5     .16       0
  4998.5     .07       0  5002.5     .16       0  5152.8     .05       0
Bank Sta=4998.5,5002.5
XS Rating Curve= 0 ,0
Exp/Cntr=0.3,0.1

Type RM Length L Ch R = 1 ,1891    ,494,494,494
BEGIN DESCRIPTION:
UNT03099 IN DUCK CR 6 0
END DESCRIPTION:
XS GIS Cut Line= 4
      3575483.14       10434287.      3575681.02     10434122.97
      3575777.37     10433711.51      3575709.82     10433506.26
#Sta/Elev= 30
  4637.4  373.91  4640.3  372.36  4697.6  369.31  4711.9  367.42  4726.2  366.99
    4759  364.59  4804.4   362.6    4832  360.22  4947.1  357.22  4963.8  357.52
  4968.9  356.47    4978  356.07  4988.2  352.44  4996.5  346.85  4996.7  346.35
  5000.2  346.35  5000.5  346.85  5002.1  347.67  5006.2  349.77  5011.4  349.75
  5029.3  353.32  5090.9  353.35    5132  355.32  5152.6  354.95  5193.6  356.67
  5228.9  356.82  5301.7  359.13  5383.4     362  5453.7  365.32  5533.1  368.13
#Mann= 8 ,-1 , 0
  4637.4     .05       0    4759      .1       0    4832     .05       0
  4996.5    .035       0  5000.5     .05       0  5002.1     .16       0
  5301.7     .05       0  5383.4     .16       0
Bank Sta=4996.5,5000.5
XS Rating Curve= 0 ,0
Exp/Cntr=0.3,0.1

Type RM Length L Ch R = 1 ,1397    ,294,294,294
BEGIN DESCRIPTION:
UNT03099 IN DUCK CR 5 0
END DESCRIPTION:
XS GIS Cut Line= 3
      3575871.11     10434354.75      3576056.02     10434094.32
      3576199.24     10433591.73
#Sta/Elev= 30
  4766.1  364.71  4891.9     360  4933.7   359.1  4941.6  358.42  4954.6  356.19
  4963.2  353.26    4978  350.32  4990.7  346.18  4996.9  345.15  4997.2  344.65
  5000.7  344.65  5000.9  345.15    5005  347.98  5027.5  350.28  5042.8  351.15
  5070.2  351.65  5076.2  352.08  5109.1  351.77  5130.5  351.11  5159.2  351.27
  5203.4  350.74  5276.2   352.1    5369  354.58  5416.8  357.47  5455.9  358.77
  5479.5  360.45  5514.6   362.3  5528.8  363.88  5535.4  365.14  5608.1  369.28
#Mann= 7 ,-1 , 0
  4766.1     .05       0  4996.9    .035       0  5000.9     .05       0
  5042.8     .16       0  5076.2      .1       0  5276.2     .05       0
  5479.5     .16       0
Bank Sta=4996.9,5000.9
XS Rating Curve= 0 ,0
Exp/Cntr=0.3,0.1

Type RM Length L Ch R = 1 ,1103    ,380,380,380
BEGIN DESCRIPTION:
UNT03099 IN DUCK CR 4 0
END DESCRIPTION:
XS GIS Cut Line= 3
      3575980.54     10434445.87       3576235.7     10434333.91
      3576381.51     10433646.55
#Sta/Elev= 30
  4526.3  362.43  4581.8  360.12  4645.7  356.31  4744.7  352.15  4817.5  351.06
  4861.7  348.97  4904.9  349.28  4908.4  349.21  4940.2  349.37    4961   348.6
    4981  346.01  4991.3  343.36  4998.4  343.12  4998.7  342.62  5002.2  342.62
  5002.4  343.12  5004.4  343.65  5011.7  346.95  5021.9  348.16  5042.4  348.26
  5062.8  349.35  5103.9   349.3  5216.2   350.4  5318.4  354.55  5356.7  357.68
  5387.4  361.49  5392.5   361.4  5437.1  366.17  5442.2  365.83  5507.6  370.76
#Mann= 9 ,-1 , 0
  4526.3     .08       0  4581.8     .05       0  4904.9      .1       0
  4908.4     .16       0  4998.4     .07       0  5002.4     .16       0
  5004.4      .1       0  5103.9     .05       0  5356.7     .16       0
Bank Sta=4998.4,5002.4
XS Rating Curve= 0 ,0
Exp/Cntr=0.3,0.1

Type RM Length L Ch R = 1 ,723     ,92,92,92
BEGIN DESCRIPTION:
Mapping XS ad4e12de
END DESCRIPTION:
XS GIS Cut Line= 2
      3576707.06     10434497.98      3576418.03      10433646.5
#Sta/Elev= 30
  4636.2  363.64  4653.5  363.19  4668.2  360.83  4674.6  357.44  4687.4     357
  4699.6  356.98  4716.8  360.89  4792.4  357.39  4817.4  356.46  4897.5  352.15
  4945.5  350.31  4982.2  345.62  4999.8  341.12  5000.1  340.62  5004.1  341.12
  5013.6  344.52  5033.6  346.07  5039.7  343.06    5045     345  5054.7  343.47
  5065.6  345.98  5071.1  346.63  5290.9  350.41  5339.9  353.47  5385.1  358.01
  5442.6  365.83  5447.8  364.67    5474  366.76  5510.6   367.7  5535.4  369.99
#Mann= 9 ,-1 , 0
  4636.2     .05       0  4687.4      .1       0  4792.4     .16       0
  4817.4      .1       0  4897.5     .16       0  4999.8     .07       0
  5004.1     .16       0  5065.6     .05       0  5071.1     .16       0
Bank Sta=4999.8,5004.1
XS Rating Curve= 0 ,0
Exp/Cntr=0.3,0.1

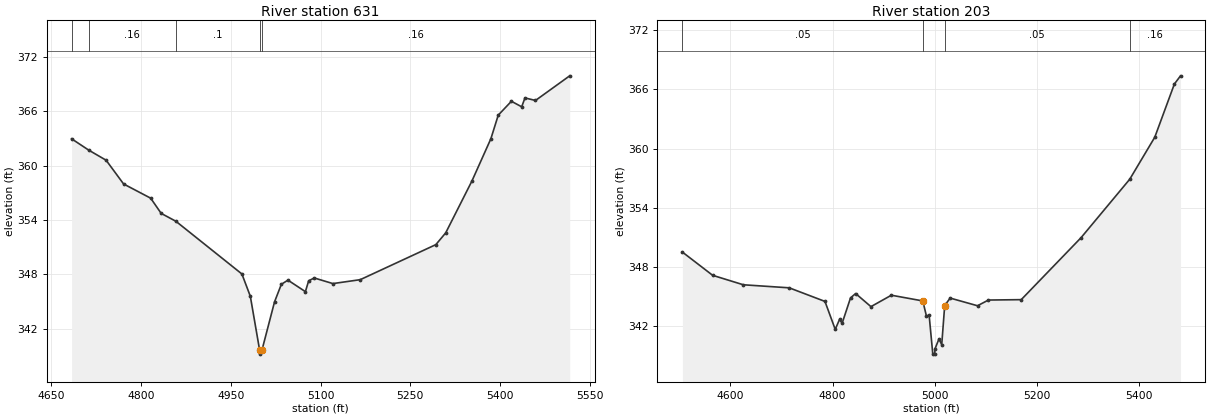
Type RM Length L Ch R = 1 ,631     ,428,428,428
BEGIN DESCRIPTION:
Mapping XS 14d9ceaa
END DESCRIPTION:
XS GIS Cut Line= 2
      3576790.39     10434380.78      3576444.04     10433622.98
#Sta/Elev= 30
  4683.6  362.97  4712.2  361.72  4741.4   360.6  4770.6  357.98  4815.9  356.41
  4833.5  354.73  4858.1  353.86  4968.5  348.04  4982.6  345.58    4998  339.69
  4998.3  339.19  5002.3  339.69  5023.1  344.96  5034.5   346.9  5045.5  347.36
  5074.7  346.09  5080.2  347.29  5089.5   347.6  5120.7  346.98  5166.4  347.41
  5292.9  351.28  5309.4  352.58  5353.3  358.31    5385  362.98  5397.3  365.58
  5419.3  367.11  5436.5   366.5    5442  367.48  5459.6   367.2  5516.8  369.92
#Mann= 5 ,-1 , 0
  4683.6      .1       0  4712.2     .16       0  4858.1      .1       0
    4998     .07       0  5002.3     .16       0
Bank Sta=4998,5002.3
XS Rating Curve= 0 ,0
Exp/Cntr=0.3,0.1

Type RM Length L Ch R = 1 ,203     ,0,0,0
BEGIN DESCRIPTION:
UNT03099 IN DUCK CR 1 0
END DESCRIPTION:
XS GIS Cut Line= 3
      3576977.89     10434260.97      3576990.91     10433820.89
      3576490.93     10433628.19
#Sta/Elev= 30
  4505.8  349.49  4565.1  347.13  4625.2  346.17  4715.2  345.86  4785.2  344.48
  4805.3  341.64  4813.8  342.66  4818.8  342.26  4835.3  344.84  4845.3  345.28
  4875.3  343.95  4915.3  345.11  4976.9  344.53    4984     343  4989.3  343.09
  4996.5  339.13  5000.3  339.13  5000.5  339.63  5008.6  340.67    5014  340.09
  5019.8  344.06  5030.5  344.82  5084.1  344.04  5105.5  344.62  5169.8  344.66
    5287  350.95  5382.5  356.89  5431.5  361.15  5469.9  366.55  5481.9  367.38
#Mann= 4 ,-1 , 0
  4505.8     .05       0  4976.9     .03       0  5019.8     .05       0
  5382.5     .16       0
Bank Sta=4976.9,5019.8
XS Rating Curve= 0 ,0
Exp/Cntr=0.3,0.1

Chan Stop Cuts=-1
Use User Specified Reach Order=0
Composite Channel Slope=5