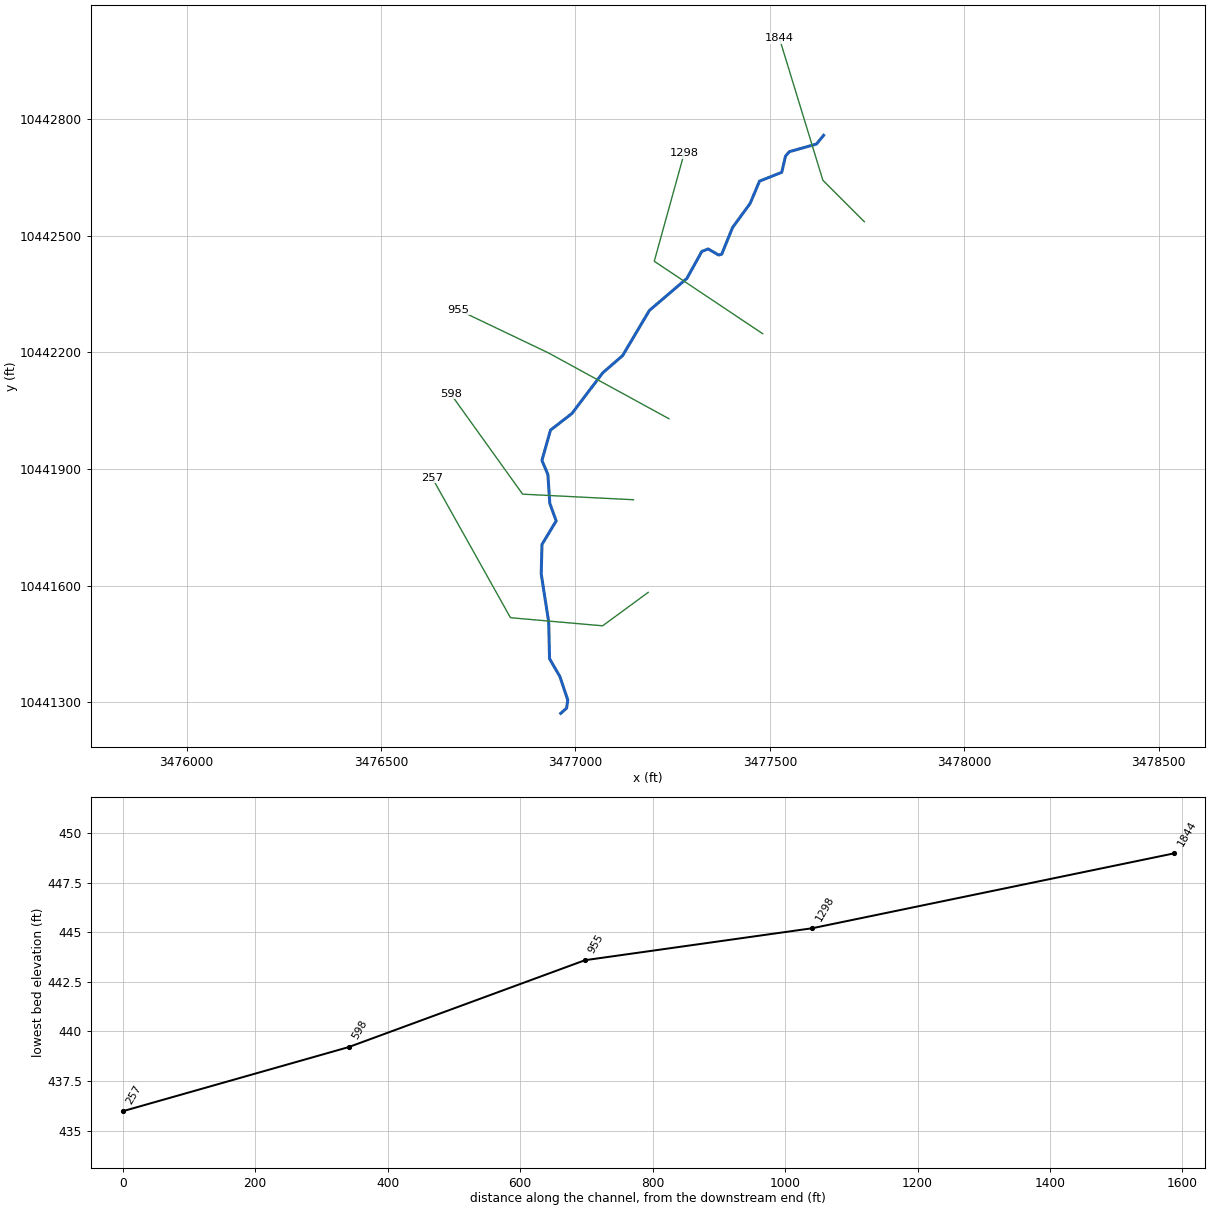
--- UNT03205 IN DUCK CR.prj (project) ---

Proj Title=UNT03205 IN DUCK CR Base Level Engineering
Current Plan=p01
Default Exp/Contr=0.3,0.1
English Units
Geom File=g01
Flow File=f01
Plan File=p01
Y Axis Title=Elevation
X Axis Title(PF)=Main Channel Distance
X Axis Title(XS)=Station
BEGIN DESCRIPTION:
UNT03205 IN DUCK CR
END DESCRIPTION:
DSS Export Rating Curves= 0
DSS Export Rating Curve Sorted= 0
DSS Export Volume Flow Curves= 0
DXF OffsetX= 0
DXF OffsetY= 0
DXF ScaleX= 1
DXF ScaleY= 10

--- UNT03205 IN DUCK CR.p01 (plan) ---

Plan Title=Multiple Run
Short Identifier=Multiple
Geom File=g01
Flow File=f01
Subcritical Flow
K Sum by GR= 0
Std Step Tol= 0.01
Critical Tol= 0.01
Num of Std Step Trials= 20
Max Error Tol= 0.3
Flow Tol Ratio= 0.001
Split Flow NTrial= 30
Split Flow Tol= 0.02
Split Flow Ratio= 0.02
Log Output Level= 0
Friction Slope Method= 1
Unsteady Friction Slope Method= 2
Unsteady Bridges Friction Slope Method= 1
Parabolic Critical Depth
Global Vel Dist=  1 , 1 , 1
Global Log Level= 0
CheckData=True
Encroach Param= -1, 0, 0, 0
BEGIN DESCRIPTION:
Multiple Run
END DESCRIPTION:

--- UNT03205 IN DUCK CR.f01 (steady flow) ---

Flow Title=Multiple
Program Version=4.10
Number of Profiles= 7
Profile Names=10-year,25-year,50-year,1pct_min,100-year,1pct_plu,500-year
River Rch & RM=UNT03205 IN DUCK,Reach-1         ,1844
     235     295     340     287     388     525     504
Boundary for River Rch & Prof#=UNT03205 IN DUCK,Reach-1         , 1
Up Type= 0
Dn Type= 3
Dn Slope=0.0106
Boundary for River Rch & Prof#=UNT03205 IN DUCK,Reach-1         , 2
Up Type= 0
Dn Type= 3
Dn Slope=0.0106
Boundary for River Rch & Prof#=UNT03205 IN DUCK,Reach-1         , 3
Up Type= 0
Dn Type= 3
Dn Slope=0.0106
Boundary for River Rch & Prof#=UNT03205 IN DUCK,Reach-1         , 4
Up Type= 0
Dn Type= 3
Dn Slope=0.0106
Boundary for River Rch & Prof#=UNT03205 IN DUCK,Reach-1         , 5
Up Type= 0
Dn Type= 3
Dn Slope=0.0106
Boundary for River Rch & Prof#=UNT03205 IN DUCK,Reach-1         , 6
Up Type= 0
Dn Type= 3
Dn Slope=0.0106
Boundary for River Rch & Prof#=UNT03205 IN DUCK,Reach-1         , 7
Up Type= 0
Dn Type= 3
Dn Slope=0.0106
DSS Import GetInterval= 0
DSS Import GetPeak= 0
DSS Import FillOption= 0

--- UNT03205 IN DUCK CR.g01 (geometry) ---

Geom Title=Existing Conditions
Program Version=4.10

River Reach=UNT03205 IN DUCK,Reach-1
Reach XY= 30
      3477638.31     10442758.25      3477619.86     10442735.74
      3477550.13     10442716.14      3477540.25     10442704.56
      3477530.66     10442663.12      3477473.47     10442640.38
      3477449.24     10442582.93      3477403.91     10442520.71
      3477376.29     10442452.39      3477368.29     10442450.39
      3477341.39     10442465.93      3477325.11     10442459.72
      3477286.66     10442390.19      3477190.21      10442307.8
      3477121.49     10442191.83      3477070.18      10442147.3
      3476990.95     10442042.77      3476935.87     10442000.03
      3476913.92     10441922.18       3476929.2     10441885.88
       3476934.1      10441811.7      3476950.54     10441766.65
      3476914.05     10441706.15      3476912.03     10441630.42
      3476931.31     10441506.31      3476933.46      10441412.2
      3476959.92     10441366.71      3476980.38     10441305.96
      3476977.22      10441284.9      3476962.11     10441271.64

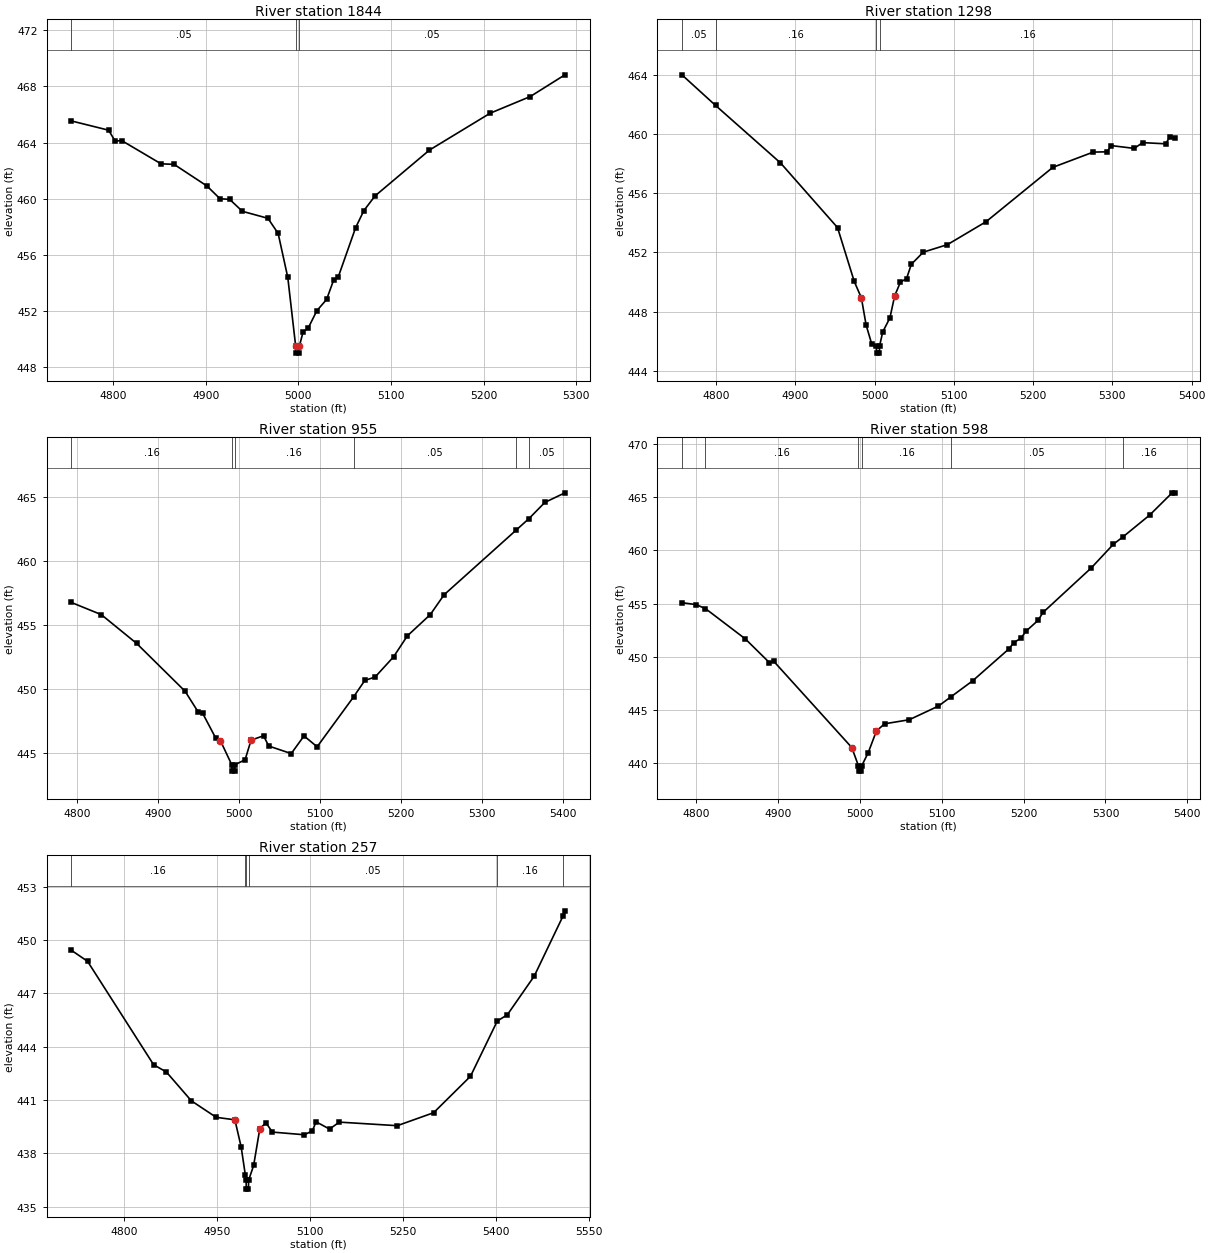
Type RM Length L Ch R = 1 ,1844    ,546,546,546
BEGIN DESCRIPTION:
UNT03205 IN DUCK CR 4 0
END DESCRIPTION:
XS GIS Cut Line= 3
      3477743.17     10442535.86      3477636.37     10442642.67
      3477524.68     10443007.62
#Sta/Elev= 30
    4755  465.54  4795.2  464.88  4802.3   464.1  4809.3  464.14  4851.8  462.48
  4865.9  462.44  4901.3   460.9  4915.4  459.99  4925.9  459.94  4939.6  459.09
  4967.2  458.59  4978.2  457.51  4988.6  454.37  4997.1  449.47  4997.3  448.97
  5000.8  448.97  5001.1  449.47  5005.2   450.5  5010.4  450.73    5020     452
  5030.5   452.8    5038  454.17  5043.2  454.43  5061.8  457.92  5070.7  459.14
  5082.8  460.19  5141.5  463.46    5207  466.09  5250.3  467.28  5287.7  468.83
#Mann= 3 ,-1 , 0
    4755     .05       0  4997.1     .03       0  5001.1     .05       0
Bank Sta=4997.1,5001.1
XS Rating Curve= 0 ,0
Exp/Cntr=0.3,0.1

Type RM Length L Ch R = 1 ,1298    ,343,343,343
BEGIN DESCRIPTION:
UNT03205 IN DUCK CR 3 0
END DESCRIPTION:
XS GIS Cut Line= 3
      3477481.41     10442248.15      3477202.78     10442434.33
       3477279.6     10442711.68
#Sta/Elev= 30
  4756.7     464  4799.2  461.93  4881.1  458.05  4953.1  453.68  4974.2  450.04
  4983.2  448.93  4989.2  447.09  4996.4  445.79  5002.2   445.7  5002.4   445.2
  5005.9   445.2  5006.2   445.7  5010.2  446.64  5019.2  447.58  5025.2  449.07
  5032.5     450  5040.2  450.23  5046.2   451.2  5061.3  452.02  5091.8  452.53
  5140.6  454.08  5224.8  457.75  5275.8  458.78  5293.3   458.8  5298.5  459.22
  5327.6  459.03  5338.1  459.42  5367.1  459.34  5372.3  459.78  5379.6  459.72
#Mann= 4 ,-1 , 0
  4756.7     .05       0  4799.2     .16       0  5002.2     .07       0
  5006.2     .16       0
Bank Sta=4983.2,5025.2
XS Rating Curve= 0 ,0
Exp/Cntr=0.3,0.1

Type RM Length L Ch R = 1 ,955     ,357,357,357
BEGIN DESCRIPTION:
UNT03205 IN DUCK CR 5 0
END DESCRIPTION:
XS GIS Cut Line= 3
      3477240.52     10442029.39      3476930.64     10442198.66
       3476698.9     10442309.32
#Sta/Elev= 30
  4792.4  456.76  4829.4  455.81  4873.1  453.56  4932.9  449.83    4949  448.22
  4954.7   448.1  4970.8  446.17  4976.5  445.98  4990.6  444.09  4990.9  443.59
  4994.4  443.59  4994.6  444.09  5007.1  444.48  5014.5  446.01  5029.9  446.35
  5036.3  445.55  5064.1  444.96  5079.9  446.34  5096.1  445.49  5141.2  449.39
    5155  450.67  5167.8  450.94  5190.5  452.51  5207.6  454.15  5235.9  455.81
    5253  457.36  5341.9   462.4  5357.9  463.31  5377.5  464.57  5402.3  465.32
#Mann= 6 ,-1 , 0
  4792.4     .16       0  4990.6     .07       0  4994.6     .16       0
  5141.2     .05       0  5341.9     .16       0  5357.9     .05       0
Bank Sta=4976.5,5014.5
XS Rating Curve= 0 ,0
Exp/Cntr=0.3,0.1

Type RM Length L Ch R = 1 ,598     ,341,341,341
BEGIN DESCRIPTION:
UNT03205 IN DUCK CR 2 0
END DESCRIPTION:
XS GIS Cut Line= 3
      3477149.39     10441821.05      3476864.24     10441835.38
      3476679.33     10442093.21
#Sta/Elev= 30
  4782.7  455.08    4800   454.9  4811.5  454.52  4860.1  451.67  4889.6  449.43
  4894.6  449.58  4990.2  441.43  4998.3  439.71  4998.5  439.21    5002  439.21
  5002.3  439.71  5010.3  440.96  5020.3     443  5030.3  443.67  5060.3  444.05
    5096  445.34  5111.6  446.23  5137.8  447.72    5182  450.72  5188.1  451.32
  5196.7  451.73  5202.9  452.39  5217.6  453.41  5223.7  454.16  5282.7  458.36
  5309.7  460.59  5321.7   461.3  5353.9  463.33  5381.4  465.43  5385.5  465.43
#Mann= 6 ,-1 , 0
  4782.7     .05       0  4811.5     .16       0  4998.3     .07       0
  5002.3     .16       0  5111.6     .05       0  5321.7     .16       0
Bank Sta=4990.2,5020.3
XS Rating Curve= 0 ,0
Exp/Cntr=0.3,0.1

Type RM Length L Ch R = 1 ,257     ,0,0,0
BEGIN DESCRIPTION:
UNT03205 IN DUCK CR 1 0
END DESCRIPTION:
XS GIS Cut Line= 4
      3477187.16     10441582.77      3477069.96     10441496.83
      3476832.99     10441517.67      3476631.66     10441877.45
#Sta/Elev= 30
  4715.2  449.42  4741.3   448.8  4847.8  442.98  4868.4  442.57  4908.6  440.95
  4948.7  440.02  4978.8  439.88  4988.9  438.35  4995.6  436.78  4996.9  436.48
  4997.2  435.98  5000.7  435.98  5000.9  436.48    5009  437.31    5019  439.39
    5029  439.71  5039.1  439.19  5090.5  439.04  5103.6  439.25  5109.6  439.77
  5131.3  439.36  5147.2  439.75  5240.5  439.55  5299.1  440.28  5358.5  442.33
  5401.7  445.44  5417.9  445.79  5461.3  447.97  5507.4  451.33  5510.7  451.64
#Mann= 6 ,-1 , 0
  4715.2     .16       0  4995.6     .05       0  4996.9     .03       0
  5000.9     .05       0  5401.7     .16       0  5507.4     .05       0
Bank Sta=4978.8,5019
XS Rating Curve= 0 ,0
Exp/Cntr=0.3,0.1

Chan Stop Cuts=-1
Use User Specified Reach Order=0
Composite Channel Slope=5