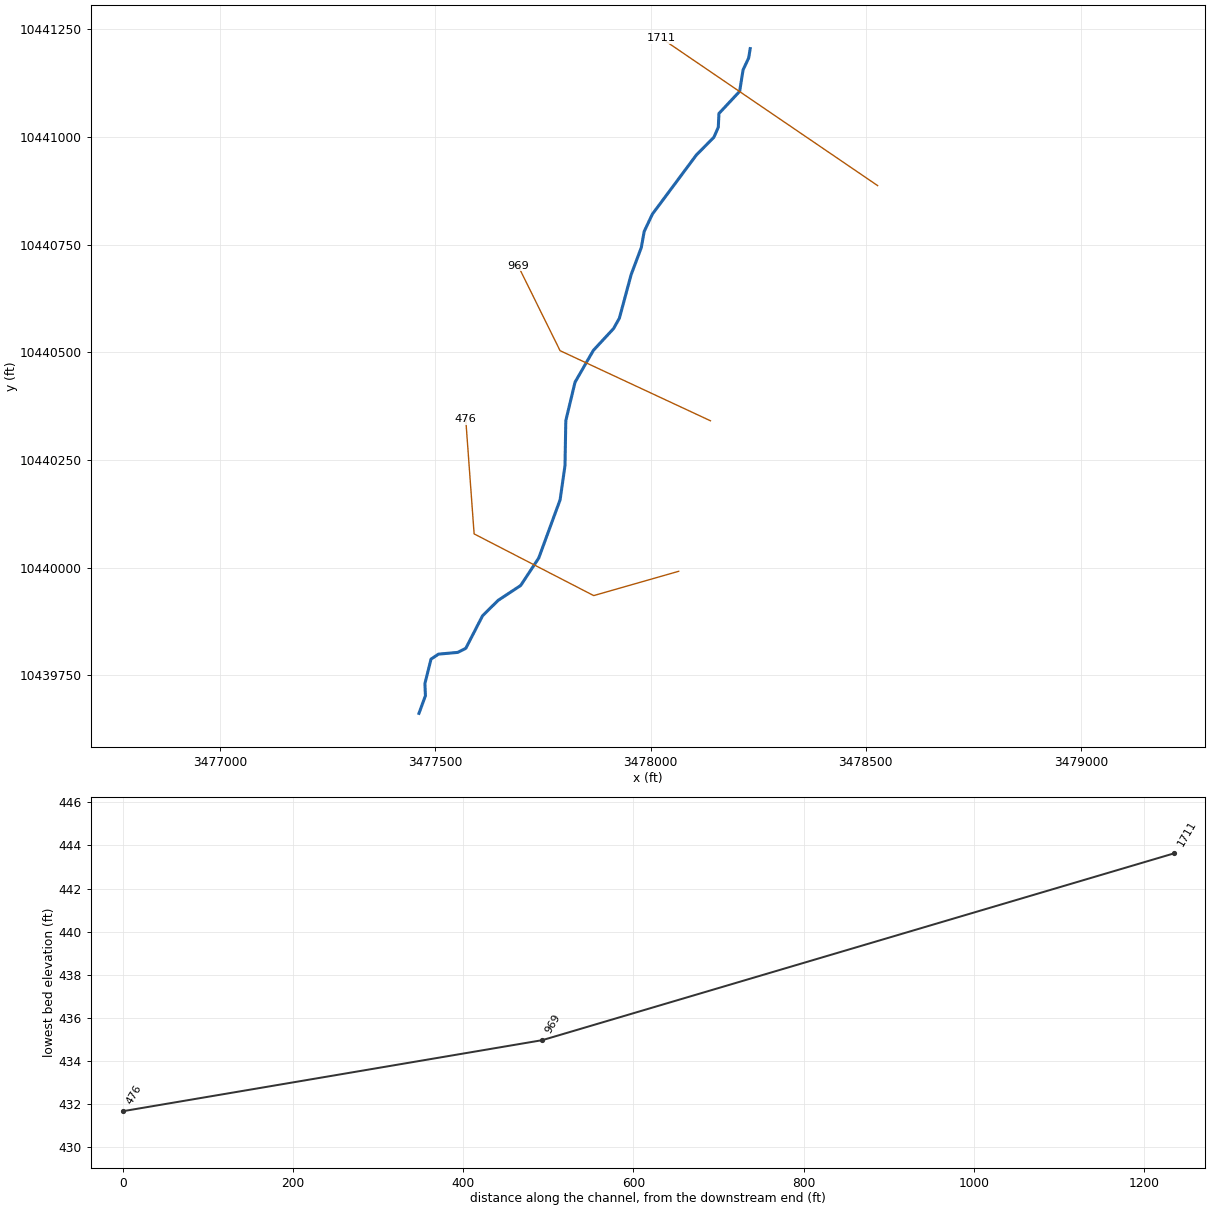
--- UNT03206 IN DUCK CR.prj (project) ---

Proj Title=UNT03206 IN DUCK CR Base Level Engineering
Current Plan=p01
Default Exp/Contr=0.3,0.1
English Units
Geom File=g01
Flow File=f01
Plan File=p01
BEGIN DESCRIPTION:
UNT03206 IN DUCK CR
END DESCRIPTION:

--- UNT03206 IN DUCK CR.p01 (plan) ---

Plan Title=Multiple Run
Short Identifier=Multiple
Geom File=g01
Flow File=f01
Subcritical Flow
K Sum by GR= 0
Std Step Tol= 0.01
Critical Tol= 0.01
Num of Std Step Trials= 20
Max Error Tol= 0.3
Flow Tol Ratio= 0.001
Split Flow NTrial= 30
Split Flow Tol= 0.02
Split Flow Ratio= 0.02
Log Output Level= 0
Friction Slope Method= 1
Unsteady Friction Slope Method= 2
Unsteady Bridges Friction Slope Method= 1
Parabolic Critical Depth
Global Vel Dist=  1 , 1 , 1
Global Log Level= 0
CheckData=True
Encroach Param= -1, 0, 0, 0
BEGIN DESCRIPTION:
Multiple Run
END DESCRIPTION:

--- UNT03206 IN DUCK CR.f01 (steady flow) ---

Flow Title=Multiple
Number of Profiles=7
Profile Names=10-year,25-year,50-year,1pct_min,100-year,1pct_plu,500-year
River Rch & RM= UNT03206 IN DUCK,Reach-1,1711
     280     357     416     355     480     649     637
Boundary for River Rch & Prof#=UNT03206 IN DUCK,Reach-1,1
Up Type=0
Dn Type=3
Dn Slope=0.005
Boundary for River Rch & Prof#=UNT03206 IN DUCK,Reach-1,2
Up Type=0
Dn Type=3
Dn Slope=0.005
Boundary for River Rch & Prof#=UNT03206 IN DUCK,Reach-1,3
Up Type=0
Dn Type=3
Dn Slope=0.005
Boundary for River Rch & Prof#=UNT03206 IN DUCK,Reach-1,4
Up Type=0
Dn Type=3
Dn Slope=0.005
Boundary for River Rch & Prof#=UNT03206 IN DUCK,Reach-1,5
Up Type=0
Dn Type=3
Dn Slope=0.005
Boundary for River Rch & Prof#=UNT03206 IN DUCK,Reach-1,6
Up Type=0
Dn Type=3
Dn Slope=0.005
Boundary for River Rch & Prof#=UNT03206 IN DUCK,Reach-1,7
Up Type=0
Dn Type=3
Dn Slope=0.005

--- UNT03206 IN DUCK CR.g01 (geometry) ---

Geom Title=Existing Conditions

River Reach=UNT03206 IN DUCK,Reach-1
Reach XY= 30
      3478231.58     10441204.93      3478228.05     10441183.29
      3478214.97     10441155.37      3478207.13     10441105.72
      3478158.94     10441054.26      3478157.50     10441022.42
      3478147.12     10440998.95      3478106.62     10440958.06
      3478004.38     10440820.70      3477985.28     10440780.33
      3477978.65     10440743.07      3477955.08     10440680.41
      3477927.59     10440578.80      3477914.17     10440554.95
      3477867.34     10440504.46      3477824.71     10440430.56
      3477803.25     10440341.17      3477801.37     10440236.95
      3477790.02     10440157.51      3477740.39     10440022.33
      3477698.44     10439958.57      3477645.81     10439923.86
      3477609.72     10439887.98      3477570.96     10439812.69
      3477552.28     10439803.22      3477507.47     10439799.20
      3477490.11     10439787.53      3477475.97     10439731.12
      3477477.14     10439702.58      3477462.11     10439661.64

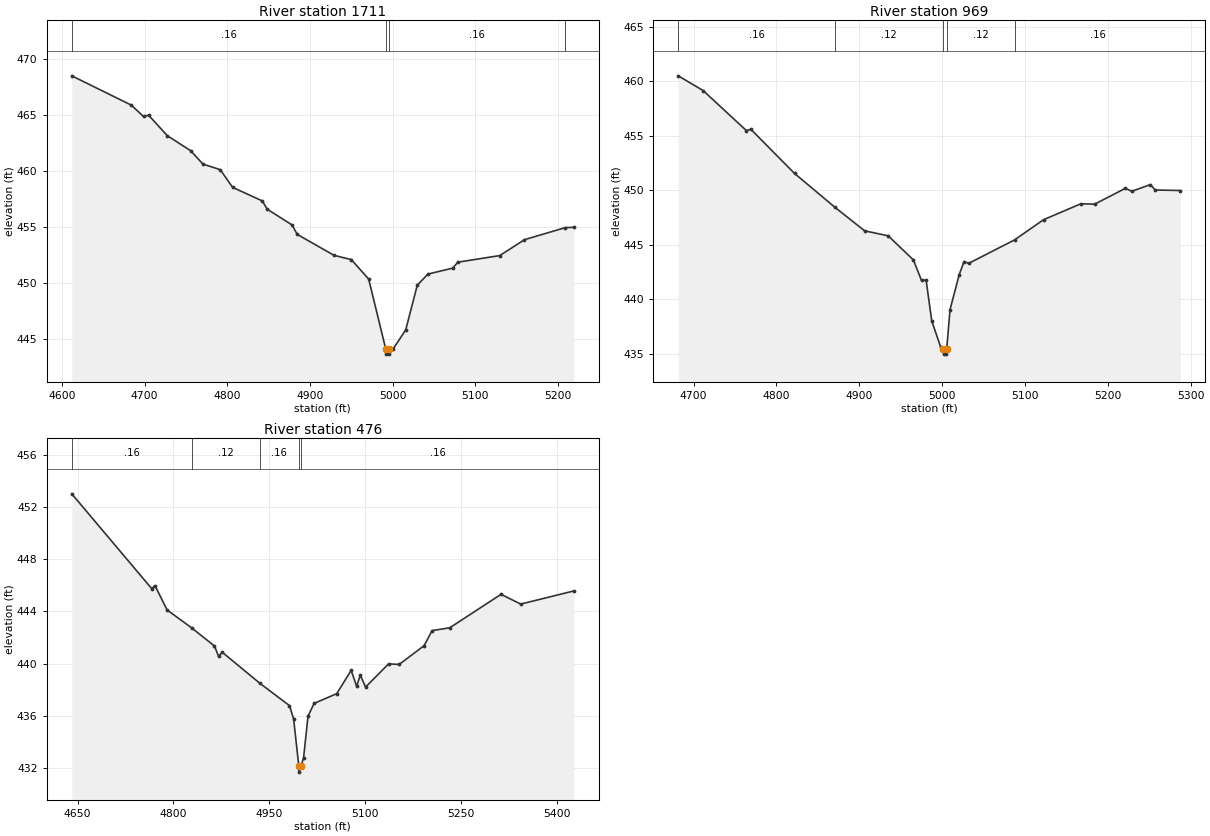
Type RM Length L Ch R = 1,1711,742,742,742
BEGIN DESCRIPTION:
UNT03206 IN DUCK CR 3 0
END DESCRIPTION:
XS GIS Cut Line= 2
      3478527.61     10440886.89      3478025.57     10441228.80
#Sta/Elev= 30
  4611.9  468.48  4683.8  465.87  4698.7  464.85  4704.8  464.97  4727.4  463.14
  4755.6  461.80  4770.6  460.60  4791.5  460.10  4806.5  458.52  4842.4  457.31
  4848.4  456.57  4878.3  455.17  4884.7  454.32  4929.2  452.45  4950.1  452.07
  4971.1  450.33  4991.6  444.13  4991.9  443.63  4995.4  443.63  4995.6  444.13
  5001.0  444.13  5015.9  445.79  5029.9  449.79  5042.9  450.78  5072.8  451.31
  5078.9  451.84  5129.7  452.43  5159.6  453.85  5209.1  454.93  5219.3  454.95
#Mann=4,-1,0
  4611.9    0.16       0  4991.6    0.07       0  4995.6    0.16       0
  5209.1    0.05       0
Bank Sta=4991.6,4995.6
Exp/Cntr=0.3,0.1

Type RM Length L Ch R = 1,969,493,493,493
BEGIN DESCRIPTION:
UNT03206 IN DUCK CR 2 0
END DESCRIPTION:
XS GIS Cut Line= 3
      3478139.30     10440340.91      3477789.91     10440503.67
      3477692.27     10440701.11
#Sta/Elev= 30
  4681.5  460.51  4711.5  459.16  4763.6  455.49  4769.1  455.60  4821.8  451.55
  4870.7  448.43  4906.4  446.28  4934.8  445.82  4965.2  443.61  4975.0  441.72
  4980.5  441.77  4987.3  438.02  4997.9  435.65  5001.4  435.46  5001.6  434.96
  5005.1  434.96  5005.4  435.46  5009.4  439.05  5020.4  442.24  5026.3  443.46
  5031.8  443.29  5087.3  445.45  5122.2  447.30  5167.1  448.76  5183.9  448.73
  5220.9  450.18  5228.8  449.91  5251.2  450.53  5256.8  450.03  5287.2  449.98
#Mann=5,-1,0
  4681.5    0.16       0  4870.7    0.12       0  5001.4    0.07       0
  5005.4    0.12       0  5087.3    0.16       0
Bank Sta=5001.4,5005.4
Exp/Cntr=0.3,0.1

Type RM Length L Ch R = 1,476,0,0,0
BEGIN DESCRIPTION:
UNT03206 IN DUCK CR 1 0
END DESCRIPTION:
XS GIS Cut Line= 4
      3478065.50     10439991.51      3477868.03     10439935.09
      3477590.26     10440078.32      3477570.73     10440345.21
#Sta/Elev= 30
  4640.9  453.04  4765.9  445.76  4771.1  445.99  4790.0  444.12  4828.5  442.74
  4864.2  441.35  4870.6  440.55  4876.3  440.87  4935.3  438.48  4981.5  436.77
  4988.0  435.75  4996.0  432.16  4996.2  431.66  5000.0  432.16  5003.6  432.78
  5010.5  435.96  5020.1  436.94  5055.5  437.69  5078.0  439.48  5086.6  438.25
  5092.3  439.12  5100.5  438.19  5136.6  439.98  5153.1  439.93  5192.2  441.38
  5204.6  442.53  5232.3  442.75  5312.5  445.32  5343.3  444.57  5426.4  445.58
#Mann=5,-1,0
  4640.9    0.16       0  4828.5    0.12       0  4935.3    0.16       0
  4996.0    0.07       0  5000.0    0.16       0
Bank Sta=4996,5000
Exp/Cntr=0.3,0.1

Chan Stop Cuts=-1