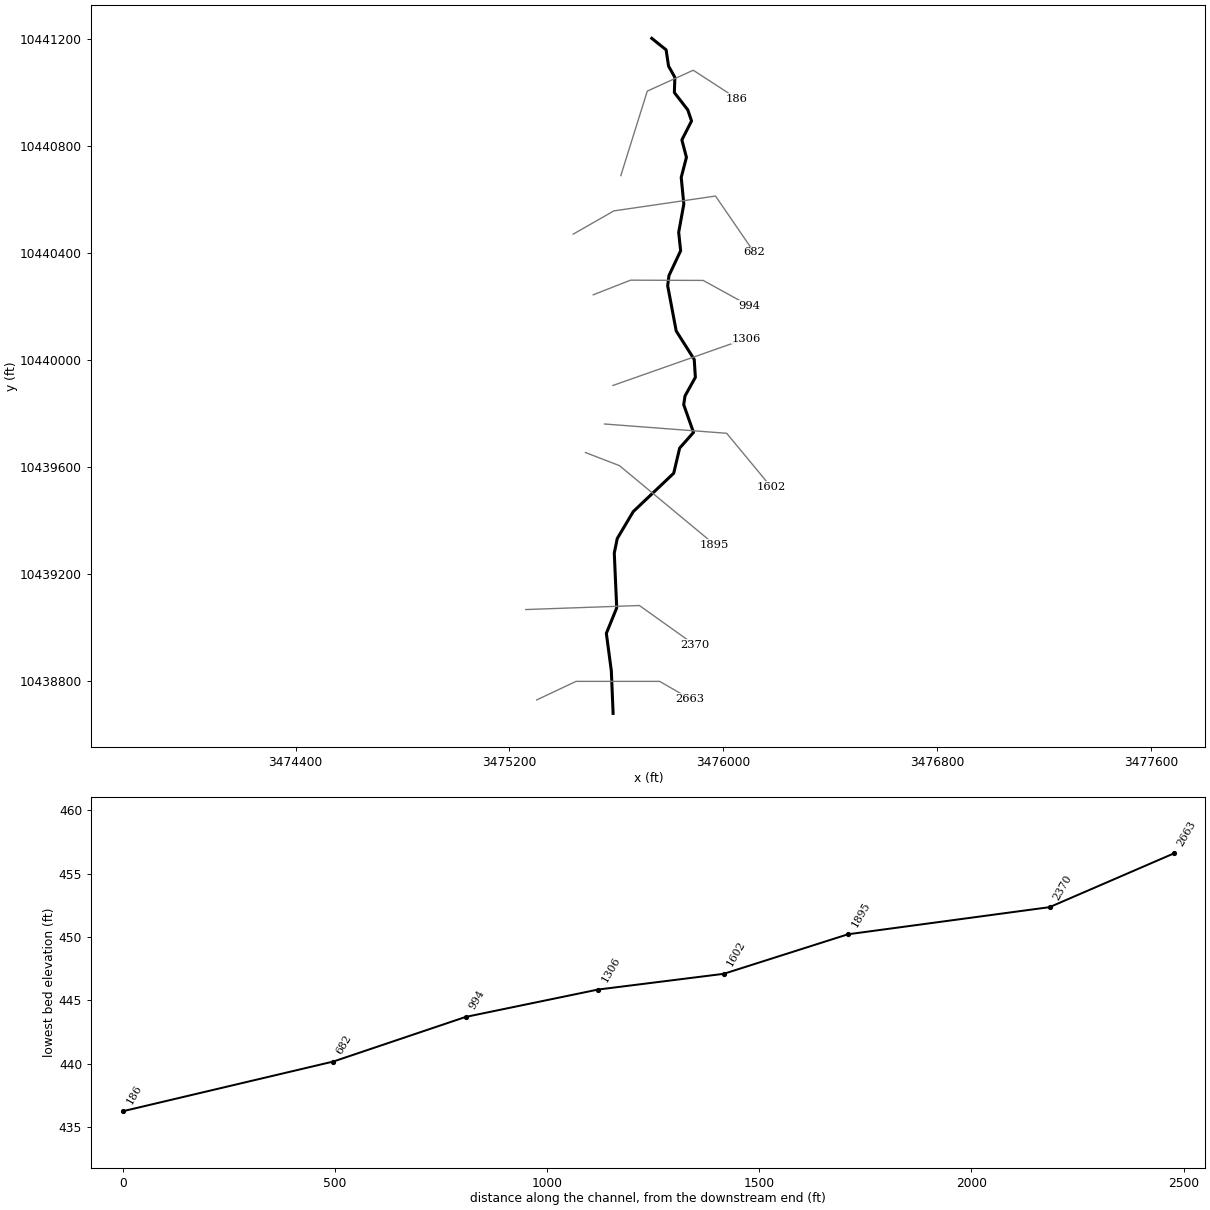
--- UNT1037 IN DUCK CR.prj (project) ---

Proj Title=UNT1037 IN DUCK CR Base Level Engineering
Current Plan=p01
Default Exp/Contr=0.3,0.1
English Units
Geom File=g01
Flow File=f01
Plan File=p01
Y Axis Title=Elevation
X Axis Title(PF)=Main Channel Distance
X Axis Title(XS)=Station
BEGIN DESCRIPTION:
UNT1037 IN DUCK CR
END DESCRIPTION:
DSS Export Rating Curves= 0
DSS Export Rating Curve Sorted= 0
DSS Export Volume Flow Curves= 0
DXF OffsetX= 0
DXF OffsetY= 0
DXF ScaleX= 1
DXF ScaleY= 10

--- UNT1037 IN DUCK CR.p01 (plan) ---

Plan Title=Multiple Run
Short Identifier=Multiple
Geom File=g01
Flow File=f01
Subcritical Flow
K Sum by GR= 0
Std Step Tol= 0.01
Critical Tol= 0.01
Num of Std Step Trials= 20
Max Error Tol= 0.3
Flow Tol Ratio= 0.001
Split Flow NTrial= 30
Split Flow Tol= 0.02
Split Flow Ratio= 0.02
Log Output Level= 0
Friction Slope Method= 1
Unsteady Friction Slope Method= 2
Unsteady Bridges Friction Slope Method= 1
Parabolic Critical Depth
Global Vel Dist=  1 , 1 , 1
Global Log Level= 0
CheckData=True
Encroach Param= -1, 0, 0, 0
BEGIN DESCRIPTION:
Multiple Run
END DESCRIPTION:

--- UNT1037 IN DUCK CR.f01 (steady flow) ---

Flow Title=Multiple
Program Version=4.10
Number of Profiles= 7
Profile Names=10-year,25-year,50-year,1pct_min,100-year,1pct_plu,500-year
River Rch & RM=UNT1037 IN DUCK,Reach-1         ,2663
     799    1086    1320    1170    1583    2140    2271
Boundary for River Rch & Prof#=UNT1037 IN DUCK,Reach-1         , 1
Up Type= 0
Dn Type= 3
Dn Slope=0.005
Boundary for River Rch & Prof#=UNT1037 IN DUCK,Reach-1         , 2
Up Type= 0
Dn Type= 3
Dn Slope=0.005
Boundary for River Rch & Prof#=UNT1037 IN DUCK,Reach-1         , 3
Up Type= 0
Dn Type= 3
Dn Slope=0.005
Boundary for River Rch & Prof#=UNT1037 IN DUCK,Reach-1         , 4
Up Type= 0
Dn Type= 3
Dn Slope=0.005
Boundary for River Rch & Prof#=UNT1037 IN DUCK,Reach-1         , 5
Up Type= 0
Dn Type= 3
Dn Slope=0.005
Boundary for River Rch & Prof#=UNT1037 IN DUCK,Reach-1         , 6
Up Type= 0
Dn Type= 3
Dn Slope=0.005
Boundary for River Rch & Prof#=UNT1037 IN DUCK,Reach-1         , 7
Up Type= 0
Dn Type= 3
Dn Slope=0.005
DSS Import GetInterval= 0
DSS Import GetPeak= 0
DSS Import FillOption= 0

--- UNT1037 IN DUCK CR.g01 (geometry) ---

Geom Title=Existing Conditions
Program Version=4.10

River Reach=UNT1037 IN DUCK ,Reach-1
Reach XY= 30
      3475587.63     10438677.36      3475581.02     10438836.11
      3475562.34     10438976.54      3475601.11     10439072.01
      3475592.03     10439276.68      3475603.05     10439331.03
      3475663.02     10439431.99       3475814.3     10439575.37
      3475836.42      10439669.3      3475888.29     10439728.12
      3475851.64     10439831.66      3475856.51     10439864.39
      3475895.26     10439934.01      3475890.96     10440001.01
      3475823.58     10440107.25      3475791.67      10440276.7
      3475796.49     10440314.45      3475840.14     10440407.28
      3475832.87     10440476.29      3475852.05     10440581.62
      3475842.34     10440681.47      3475861.82      10440756.7
      3475844.83     10440821.62      3475880.96     10440892.65
      3475866.88     10440934.01      3475816.69     10440998.86
      3475818.57     10441055.84      3475794.98     10441097.78
      3475785.87     10441158.55      3475732.11     10441201.64

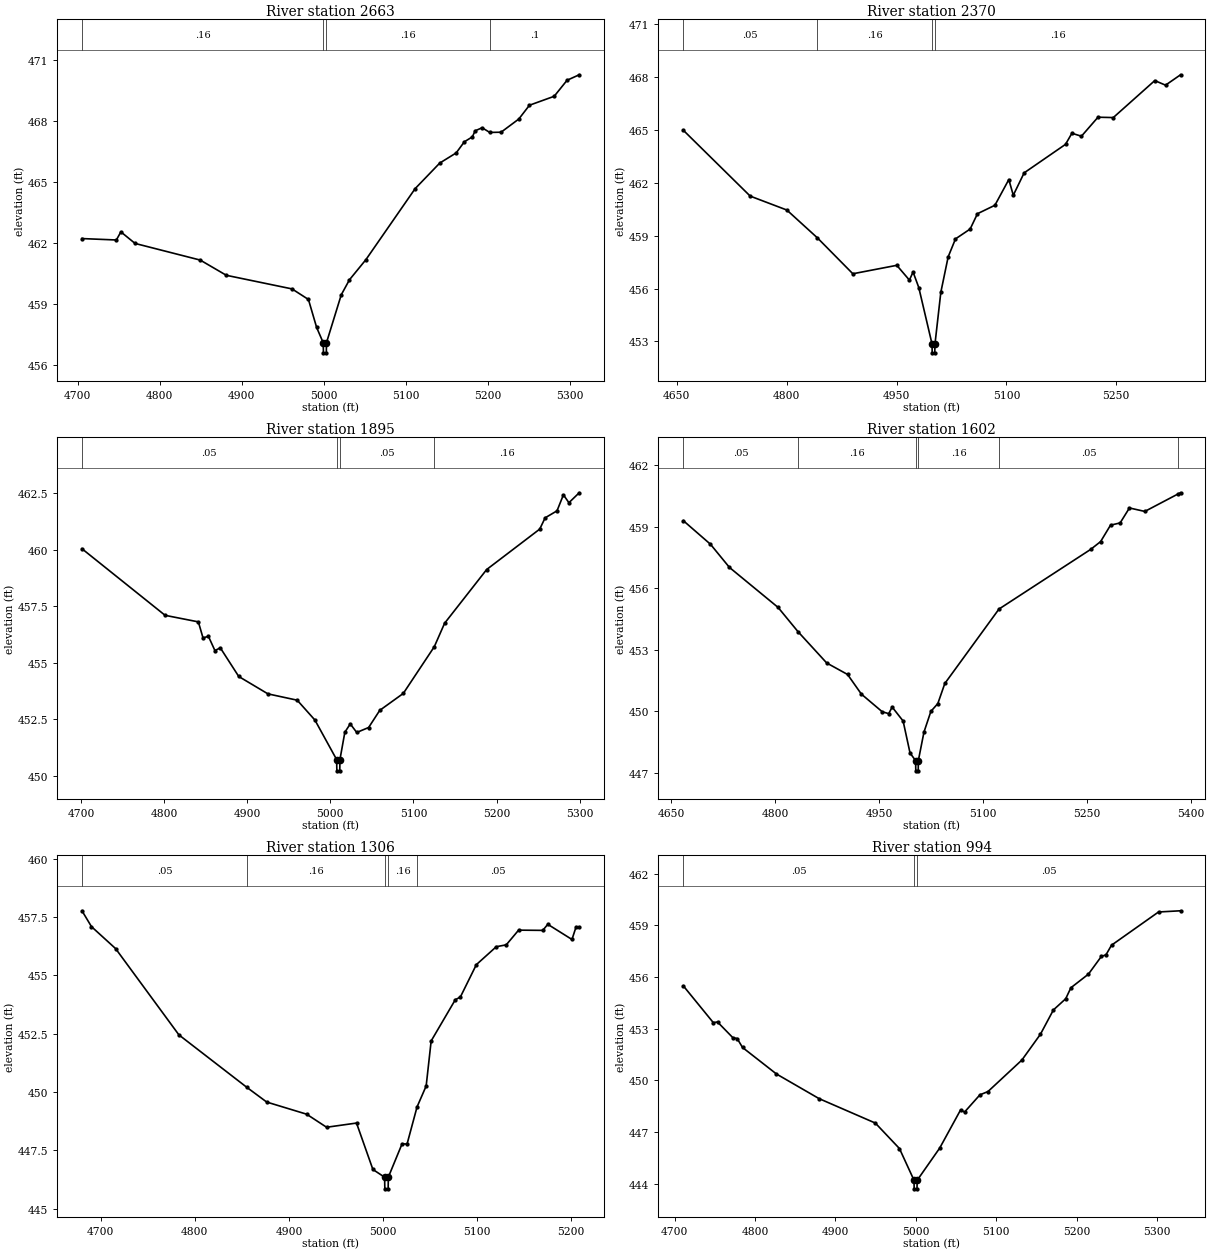
Type RM Length L Ch R = 1 ,2663    ,293,293,293
BEGIN DESCRIPTION:
UNT1037 IN DUCK CR 7 0
END DESCRIPTION:
XS GIS Cut Line= 4
      3475301.72     10438727.62      3475449.25     10438797.05
      3475761.75     10438797.05      3475874.57     10438731.96
#Sta/Elev= 30
  4705.2  462.22  4747.1  462.15  4752.6  462.55  4769.9  461.98  4849.3  461.16
  4881.1  460.41  4961.1  459.74  4981.1  459.22  4991.1  457.84  4999.1  457.09
  4999.4  456.59  5002.9  456.59  5003.1  457.09  5021.1  459.45  5031.1  460.19
  5051.1  461.18  5111.1  464.68  5141.1  465.94  5161.1  466.44  5171.1  466.99
  5180.8  467.23  5184.2  467.53  5192.7  467.68    5202  467.45  5215.8  467.46
  5237.4  468.11  5250.4  468.79  5280.5  469.23  5296.2  470.02    5311  470.29
#Mann= 4 ,-1 , 0
  4705.2     .16       0  4999.1     .07       0  5003.1     .16       0
    5202      .1       0
Bank Sta=4999.1,5003.1
XS Rating Curve= 0 ,0
Exp/Cntr=0.3,0.1

Type RM Length L Ch R = 1 ,2370    ,475,475,475
BEGIN DESCRIPTION:
UNT1037 IN DUCK CR 7 0
END DESCRIPTION:
XS GIS Cut Line= 3
      3475260.86     10439065.63       3475685.9     10439080.71
      3475892.29     10438933.69
#Sta/Elev= 30
    4659  464.99  4750.3  461.25  4800.3  460.46    4842  458.88  4890.4  456.84
  4950.4  457.32  4967.6  456.48  4972.6  456.94  4980.4  456.06  4998.5  452.85
  4998.7  452.35  5002.2  452.35  5002.5  452.85  5010.5  455.79  5020.5   457.8
  5030.5  458.82  5050.5  459.38  5060.5  460.25  5084.3  460.73  5103.3  462.19
  5109.4   461.3  5124.2  462.57  5180.7  464.19  5189.4  464.82  5202.4  464.65
    5225  465.73  5245.9  465.71  5302.5  467.81  5317.2  467.55  5337.7  468.14
#Mann= 4 ,-1 , 0
    4659     .05       0    4842     .16       0  4998.5     .07       0
  5002.5     .16       0
Bank Sta=4998.5,5002.5
XS Rating Curve= 0 ,0
Exp/Cntr=0.3,0.1

Type RM Length L Ch R = 1 ,1895    ,293,293,293
BEGIN DESCRIPTION:
UNT1037 IN DUCK CR 5 0
END DESCRIPTION:
XS GIS Cut Line= 3
      3475484.19     10439652.75      3475611.45     10439603.73
       3475966.7     10439308.78
#Sta/Elev= 30
  4701.3  460.05  4801.3   457.1  4841.3  456.81  4846.9   456.1  4853.4  456.17
  4861.2  455.54  4867.7  455.66  4889.9  454.39    4925  453.62  4960.2  453.34
  4981.5  452.46  5007.6  450.71  5007.9  450.21  5011.4  450.21  5011.6  450.71
  5017.5  451.92    5024  452.29  5031.8  451.91  5046.1  452.13  5059.5  452.89
  5087.8  453.64  5125.1  455.71  5137.5  456.75  5188.1  459.13  5251.9  460.92
  5258.4  461.42  5272.7  461.73  5280.4  462.44    5287  462.09  5299.4  462.53
#Mann= 4 ,-1 , 0
  4701.3     .05       0  5007.6     .03       0  5011.6     .05       0
  5125.1     .16       0
Bank Sta=5007.6,5011.6
XS Rating Curve= 0 ,0
Exp/Cntr=0.3,0.1

Type RM Length L Ch R = 1 ,1602    ,296,296,296
BEGIN DESCRIPTION:
UNT1037 IN DUCK CR 6 0
END DESCRIPTION:
XS GIS Cut Line= 3
      3475555.73     10439759.45      3476012.29     10439724.73
      3476178.01     10439524.49
#Sta/Elev= 30
  4667.2  459.29  4706.4  458.14  4733.8  457.01    4804  455.06  4832.7  453.88
  4874.2  452.35  4904.3  451.79  4924.3  450.83  4954.4  449.97  4963.7  449.88
  4968.7   450.2  4984.5  449.52  4994.5  447.96  5002.5  447.59  5002.8  447.09
  5006.3  447.09  5006.5  447.59  5014.6  448.98  5024.6  449.99  5034.6  450.37
  5044.7  451.35  5122.9  454.98  5255.3  457.89  5269.6  458.27  5283.9  459.07
  5297.8  459.18  5311.2  459.91  5333.4  459.74  5381.8   460.6    5385  460.65
#Mann= 6 ,-1 , 0
  4667.2     .05       0  4832.7     .16       0  5002.5     .07       0
  5006.5     .16       0  5122.9     .05       0  5381.8     .16       0
Bank Sta=5002.5,5006.5
XS Rating Curve= 0 ,0
Exp/Cntr=0.3,0.1

Type RM Length L Ch R = 1 ,1306    ,312,312,312
BEGIN DESCRIPTION:
UNT1037 IN DUCK CR 4 1
END DESCRIPTION:
XS GIS Cut Line= 2
      3475586.91     10439903.53      3476085.25     10440078.91
#Sta/Elev= 30
  4680.1  457.77  4690.2  457.09  4715.8  456.15  4783.1  452.45  4855.3   450.2
  4876.4  449.57  4918.8  449.05    4940  448.49  4971.8  448.67  4989.2  446.68
  5001.6  446.35  5001.9  445.85  5005.4  445.85  5005.6  446.35  5020.2  447.78
  5025.5  447.77  5036.1  449.36  5045.8  450.26  5051.1  452.19  5076.8  453.96
  5082.1  454.07  5099.1  455.46  5120.3  456.23  5130.9  456.31    5144  456.94
  5169.7  456.93    5175  457.19  5200.7  456.54    5205  457.07  5208.4  457.07
#Mann= 5 ,-1 , 0
  4680.1     .05       0  4855.3     .16       0  5001.6     .07       0
  5005.6     .16       0  5036.1     .05       0
Bank Sta=5001.6,5005.6
XS Rating Curve= 0 ,0
Exp/Cntr=0.3,0.1

Type RM Length L Ch R = 1 ,994     ,312,312,312
BEGIN DESCRIPTION:
UNT1037 IN DUCK CR 4 0
END DESCRIPTION:
XS GIS Cut Line= 4
      3475513.48     10440242.68      3475652.91     10440297.32
      3475924.32     10440296.38      3476097.39     10440201.38
#Sta/Elev= 30
  4710.7  455.48  4747.9  453.35  4753.3  453.38  4772.3  452.47  4777.7  452.42
  4784.4   451.9  4826.6  450.36  4879.6  448.93  4949.6  447.51  4979.6  446.03
  4997.7  444.19  4997.9  443.69  5001.4  443.69  5001.7  444.19  5029.7  446.06
  5055.6  448.27  5060.6  448.15  5079.7  449.15  5089.7  449.34  5131.9  451.17
    5155  452.67  5171.1  454.08  5186.4  454.73  5192.9  455.37  5214.7  456.16
  5230.8  457.19  5236.5  457.28  5243.4  457.84  5301.9  459.77  5329.3  459.84
#Mann= 3 ,-1 , 0
  4710.7     .05       0  4997.7     .03       0  5001.7     .05       0
Bank Sta=4997.7,5001.7
XS Rating Curve= 0 ,0
Exp/Cntr=0.3,0.1

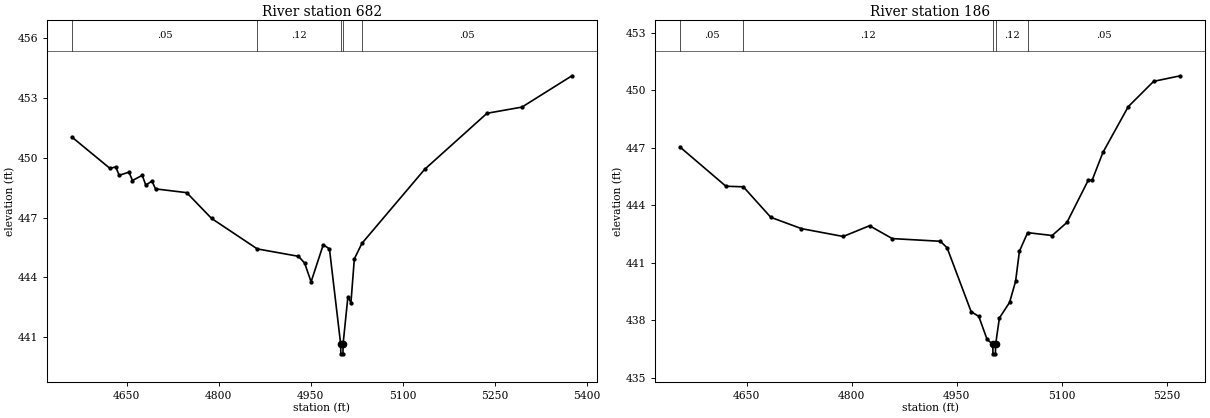
Type RM Length L Ch R = 1 ,682     ,496,496,496
BEGIN DESCRIPTION:
UNT1037 IN DUCK CR 2 0
END DESCRIPTION:
XS GIS Cut Line= 4
      3475438.33     10440469.39      3475590.42     10440556.33
      3475970.63     10440611.88      3476114.74     10440401.79
#Sta/Elev= 30
  4560.9  451.04  4622.8  449.47  4632.3  449.54    4638  449.12  4653.9  449.28
  4659.6  448.86  4675.5  449.12  4681.2  448.63  4691.3  448.83  4697.1  448.44
  4747.9  448.25  4788.3  446.96  4862.8  445.43  4929.8  445.06  4939.9  444.72
  4950.4  443.78  4970.2  445.64  4980.3  445.43  4998.5  440.67  4998.8  440.17
  5002.3  440.17  5002.5  440.67  5010.3  443.02  5015.3  442.74  5020.8  444.93
  5033.2  445.71  5135.3  449.42  5236.8  452.23  5293.7  452.54  5375.1  454.11
#Mann= 5 ,-1 , 0
  4560.9     .05       0  4862.8     .12       0  4998.5     .07       0
  5002.5     .12       0  5033.2     .05       0
Bank Sta=4998.5,5002.5
XS Rating Curve= 0 ,0
Exp/Cntr=0.3,0.1

Type RM Length L Ch R = 1 ,186     ,0,0,0
BEGIN DESCRIPTION:
UNT1037 IN DUCK CR 1 0
END DESCRIPTION:
XS GIS Cut Line= 4
      3475616.47     10440688.31      3475715.42     10441004.24
      3475887.29     10441082.37      3476050.32     10440976.58
#Sta/Elev= 30
  4555.1  447.02  4620.2  444.99  4645.1  444.96  4684.3  443.37    4728  442.78
  4787.7  442.37  4825.3  442.93  4857.8  442.26  4926.5  442.12  4936.1  441.78
  4970.4  438.45  4981.4   438.2  4993.2     437  5001.4  436.75  5001.6  436.25
  5005.1  436.25  5005.4  436.75  5010.8  438.12  5025.3  438.93  5033.9  440.03
  5039.4   441.6  5051.1  442.57  5086.1  442.42  5107.2   443.1  5137.5  445.29
  5143.4  445.32  5158.6  446.75  5194.8  449.14  5231.1  450.46  5269.3  450.75
#Mann= 5 ,-1 , 0
  4555.1     .05       0  4645.1     .12       0  5001.4     .07       0
  5005.4     .12       0  5051.1     .05       0
Bank Sta=5001.4,5005.4
XS Rating Curve= 0 ,0
Exp/Cntr=0.3,0.1

Chan Stop Cuts=-1
Use User Specified Reach Order=0
Composite Channel Slope=5