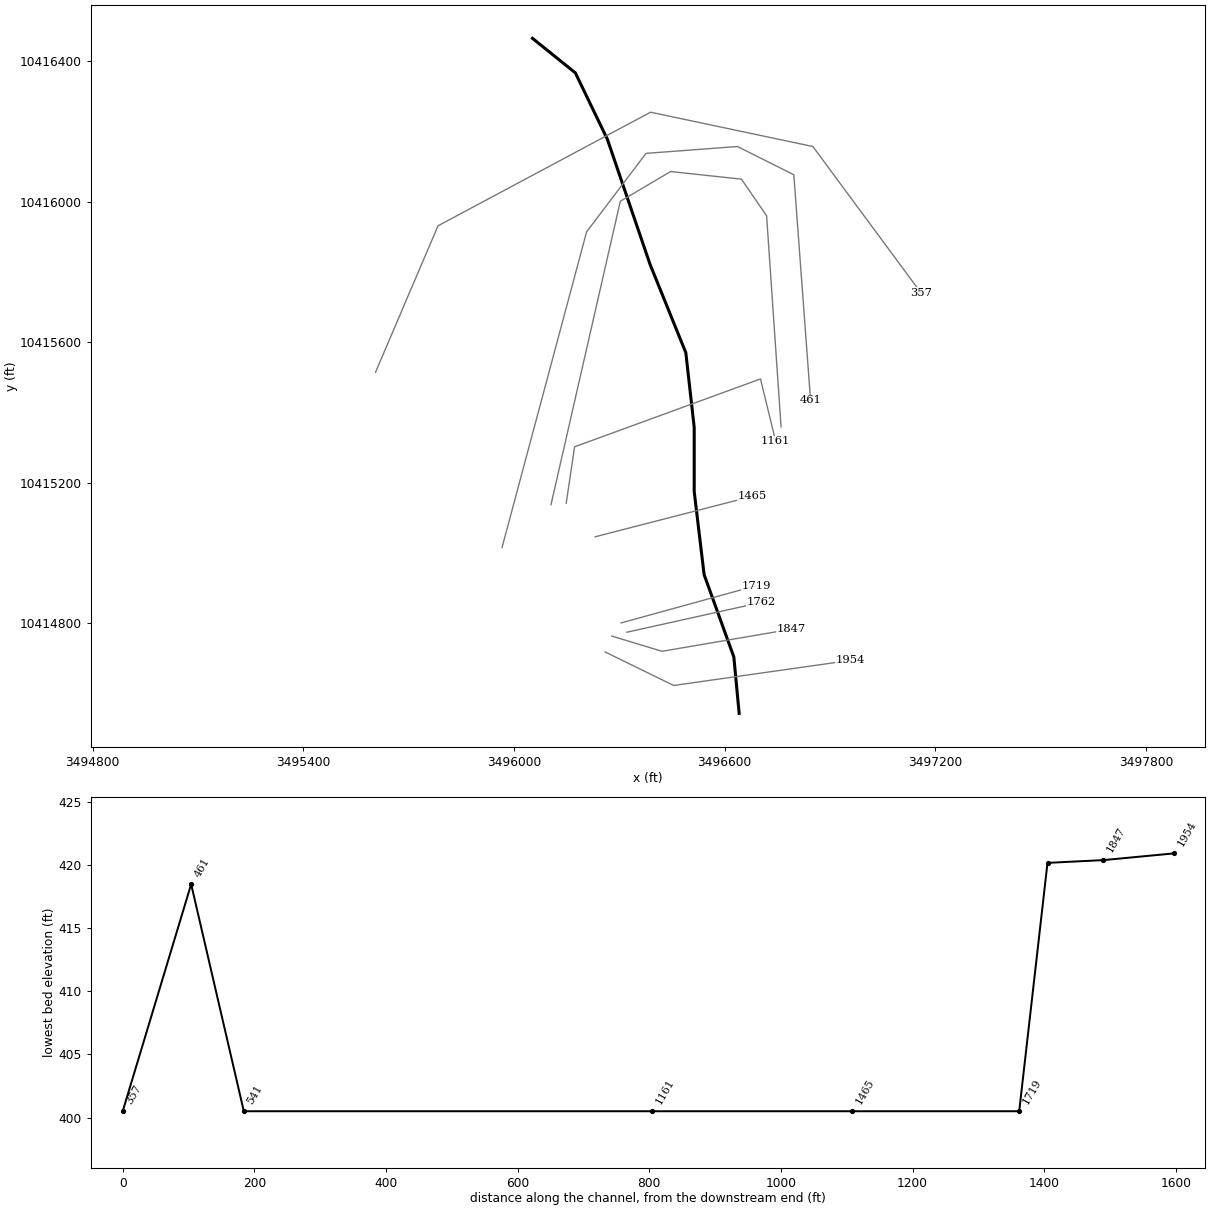
--- UNT1061 IN DUCK CR.prj (project) ---

Proj Title=UNT1061 IN DUCK CR Base Level Engineering
Current Plan=p01
Default Exp/Contr=0.3,0.1
English Units
Geom File=g01
Flow File=f01
Plan File=p01
BEGIN DESCRIPTION:
UNT1061 IN DUCK CR
END DESCRIPTION:

--- UNT1061 IN DUCK CR.p01 (plan) ---

Plan Title=Multiple Run
Short Identifier=Multiple
Geom File=g01
Flow File=f01
Subcritical Flow
K Sum by GR= 0
Std Step Tol= 0.01
Critical Tol= 0.01
Num of Std Step Trials= 20
Max Error Tol= 0.3
Flow Tol Ratio= 0.001
Split Flow NTrial= 30
Split Flow Tol= 0.02
Split Flow Ratio= 0.02
Log Output Level= 0
Friction Slope Method= 1
Unsteady Friction Slope Method= 2
Unsteady Bridges Friction Slope Method= 1
Parabolic Critical Depth
Global Vel Dist=  1 , 1 , 1
Global Log Level= 0
CheckData=True
Encroach Param= -1, 0, 0, 0
BEGIN DESCRIPTION:
Multiple Run
END DESCRIPTION:

--- UNT1061 IN DUCK CR.f01 (steady flow) ---

Flow Title=Multiple
Number of Profiles=7
Profile Names=10-year,25-year,50-year,1pct_min,100-year,1pct_plu,500-year
River Rch & RM= UNT1061 IN DUCK ,Reach-1,1954
     279     354     411     350     474     641     625
Boundary for River Rch & Prof#=UNT1061 IN DUCK ,Reach-1,1
Up Type=0
Dn Type=3
Dn Slope=0.005
Boundary for River Rch & Prof#=UNT1061 IN DUCK ,Reach-1,2
Up Type=0
Dn Type=3
Dn Slope=0.005
Boundary for River Rch & Prof#=UNT1061 IN DUCK ,Reach-1,3
Up Type=0
Dn Type=3
Dn Slope=0.005
Boundary for River Rch & Prof#=UNT1061 IN DUCK ,Reach-1,4
Up Type=0
Dn Type=3
Dn Slope=0.005
Boundary for River Rch & Prof#=UNT1061 IN DUCK ,Reach-1,5
Up Type=0
Dn Type=3
Dn Slope=0.005
Boundary for River Rch & Prof#=UNT1061 IN DUCK ,Reach-1,6
Up Type=0
Dn Type=3
Dn Slope=0.005
Boundary for River Rch & Prof#=UNT1061 IN DUCK ,Reach-1,7
Up Type=0
Dn Type=3
Dn Slope=0.005

--- UNT1061 IN DUCK CR.g01 (geometry) ---

Geom Title=Existing Conditions

River Reach=UNT1061 IN DUCK ,Reach-1
Reach XY= 10
      3496641.60     10414543.99      3496626.41     10414704.58
      3496541.77     10414938.95      3496513.56     10415175.50
      3496513.56     10415357.79      3496489.69     10415570.46
      3496387.69     10415822.20      3496266.16     10416178.10
      3496175.02     10416366.90      3496052.86     10416465.17

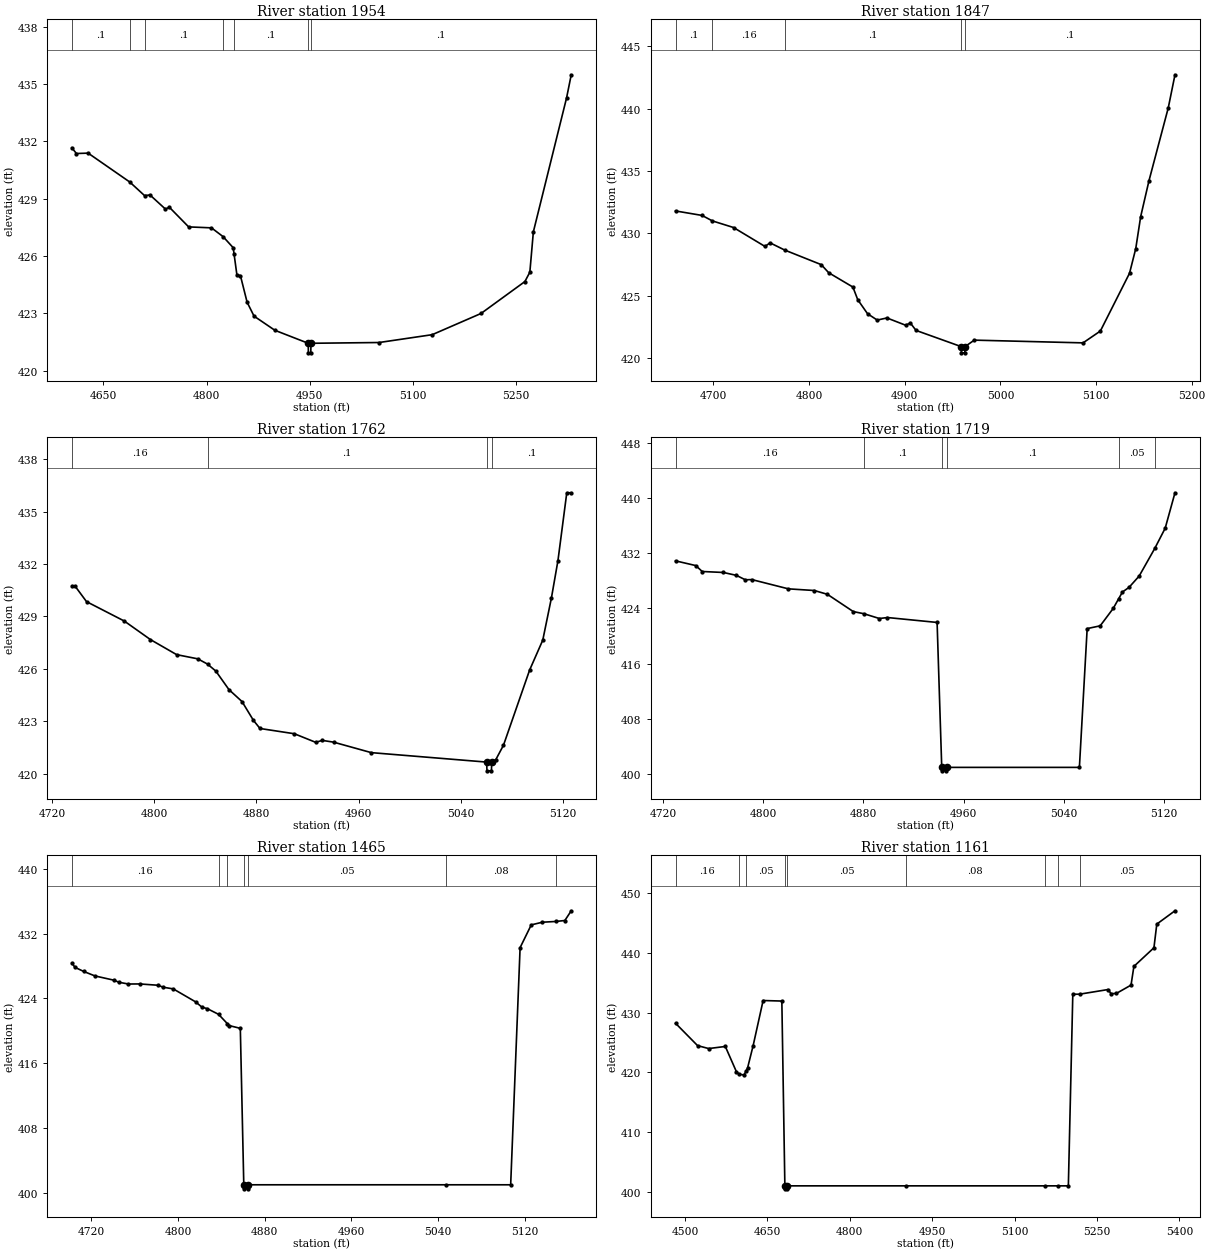
Type RM Length L Ch R = 1,1954,107,107,107
BEGIN DESCRIPTION:
UNT1061 IN DUCK CR 4 1
END DESCRIPTION:
XS GIS Cut Line= 3
      3496259.67     10414718.90      3496455.00     10414623.41
      3496958.85     10414694.77
#Sta/Elev= 30
  4604.1  431.66  4610.8  431.36  4627.8  431.38  4688.3  429.87  4709.8  429.16
  4717.8  429.19  4740.3  428.45  4745.9  428.55  4774.0  427.52  4807.2  427.47
  4824.1  427.01  4838.8  426.43  4840.1  426.09  4844.2  425.00  4849.3  424.97
  4859.0  423.58  4869.1  422.85  4899.4  422.11  4947.9  421.43  4948.1  420.93
  4951.6  420.93  4951.9  421.43  5050.9  421.47  5128.2  421.88  5199.2  422.99
  5263.0  424.66  5270.2  425.15  5275.3  427.26  5323.6  434.27  5330.4  435.48
#Mann=7,-1,0
  4604.1     0.1       0  4688.3    0.16       0  4709.8     0.1       0
  4824.1    0.16       0  4840.1     0.1       0  4947.9    0.07       0
  4951.9     0.1       0
Bank Sta=4947.9,4951.9
Exp/Cntr=0.3,0.1

Type RM Length L Ch R = 1,1847,85,85,85
BEGIN DESCRIPTION:
Mapping XS fcef1f6b
END DESCRIPTION:
XS GIS Cut Line= 3
      3496278.60     10414764.07      3496421.86     10414720.66
      3496788.97     10414783.29
#Sta/Elev= 30
  4660.4  431.79  4688.1  431.43  4698.9  430.99  4721.0  430.46  4753.9  428.94
  4759.2  429.23  4774.5  428.65  4812.7  427.48  4820.5  426.83  4845.8  425.68
  4850.9  424.66  4861.1  423.54  4871.2  423.03  4881.4  423.20  4900.8  422.62
  4905.9  422.79  4911.8  422.20  4959.0  420.90  4959.3  420.40  4962.8  420.40
  4963.0  420.90  4972.7  421.42  5086.4  421.20  5104.5  422.15  5135.0  426.79
  5141.5  428.77  5146.6  431.32  5155.3  434.21  5175.5  440.07  5182.5  442.72
#Mann=5,-1,0
  4660.4     0.1       0  4698.9    0.16       0  4774.5     0.1       0
  4959.0    0.07       0  4963.0     0.1       0
Bank Sta=4959,4963
Exp/Cntr=0.3,0.1

Type RM Length L Ch R = 1,1762,43,43,43
BEGIN DESCRIPTION:
Mapping XS a040e630
END DESCRIPTION:
XS GIS Cut Line= 2
      3496321.97     10414775.01      3496703.90     10414859.64
#Sta/Elev= 30
  4735.4  430.73  4738.0  430.73  4746.9  429.85  4776.5  428.74  4797.0  427.68
  4817.5  426.82  4834.1  426.58  4841.7  426.28  4848.2  425.88  4858.5  424.82
  4868.7  424.14  4877.7  423.06  4882.8  422.60  4909.7  422.30  4926.4  421.81
  4931.6  421.92  4940.4  421.82  4970.0  421.22  5060.3  420.68  5060.6  420.18
  5064.1  420.18  5064.3  420.68  5067.5  420.82  5073.5  421.64  5094.0  425.94
  5104.3  427.65  5111.1  430.07  5116.2  432.20  5123.1  436.07  5126.6  436.07
#Mann=4,-1,0
  4735.4    0.16       0  4841.7     0.1       0  5060.3    0.07       0
  5064.3     0.1       0
Bank Sta=5060.3,5064.3
Exp/Cntr=0.3,0.1

Type RM Length L Ch R = 1,1719,254,254,254
BEGIN DESCRIPTION:
UNT1061 IN DUCK CR 3 1
END DESCRIPTION:
XS GIS Cut Line= 2
      3496305.26     10414801.36      3496689.66     10414907.18
#Sta/Elev= 30
  4730.0  430.88  4746.1  430.20  4751.3  429.34  4768.2  429.20  4778.6  428.78
  4785.7  428.14  4790.9  428.17  4820.1  426.83  4840.8  426.59  4851.2  426.04
  4871.9  423.54  4880.4  423.23  4892.7  422.54  4899.2  422.68  4938.8  421.97
  4942.5  401.00  4942.8  400.50  4946.3  400.50  4946.5  401.00  5052.4  401.00
  5058.6  421.08  5069.0  421.48  5079.4  424.00  5083.8  425.42  5086.8  426.38
  5092.0  427.04  5100.1  428.68  5112.6  432.69  5120.9  435.61  5128.7  440.73
#Mann=6,-1,0
  4730.0    0.16       0  4880.4     0.1       0  4942.5    0.07       0
  4946.5     0.1       0  5083.8    0.05       0  5112.6     0.1       0
Bank Sta=4942.5,4946.5
Exp/Cntr=0.3,0.1

Type RM Length L Ch R = 1,1465,304,304,304
BEGIN DESCRIPTION:
UNT1061 IN DUCK CR 6 1
END DESCRIPTION:
XS GIS Cut Line= 2
      3496231.48     10415046.59      3496677.84     10415161.43
#Sta/Elev= 30
  4702.0  428.36  4705.0  427.83  4713.0  427.33  4723.3  426.78  4740.6  426.26
  4745.7  425.99  4754.3  425.78  4764.6  425.79  4781.3  425.63  4786.5  425.38
  4795.6  425.18  4816.2  423.58  4822.0  422.93  4827.2  422.73  4837.4  422.04
  4845.6  420.88  4847.2  420.65  4857.5  420.31  4860.7  401.00  4861.0  400.50
  4864.5  400.50  4864.7  401.00  5047.6  401.00  5107.0  401.00  5115.7  430.27
  5126.0  433.08  5136.3  433.41  5148.6  433.50  5157.0  433.62  5162.9  434.82
#Mann=7,-1,0
  4702.0    0.16       0  4837.4     0.1       0  4845.6    0.05       0
  4860.7   0.033       0  4864.7    0.05       0  5047.6    0.08       0
  5148.6    0.05       0
Bank Sta=4860.7,4864.7
Exp/Cntr=0.3,0.1

Type RM Length L Ch R = 1,1161,620,620,620
BEGIN DESCRIPTION:
UNT1061 IN DUCK CR 5 1
END DESCRIPTION:
XS GIS Cut Line= 4
      3496149.00     10415142.03      3496172.88     10415302.66
      3496702.40     10415495.81      3496745.80     10415317.87
#Sta/Elev= 30
  4482.9  428.21  4523.0  424.47  4543.2  423.98  4573.5  424.33  4593.7  420.10
  4598.3  419.70  4607.5  419.55  4611.2  420.21  4613.9  420.69  4624.1  424.45
  4642.3  432.02  4676.4  431.93  4681.9  401.00  4682.2  400.50  4685.7  400.50
  4685.9  401.00  4902.8  401.00  5154.6  401.00  5178.3  401.00  5198.0  401.00
  5206.1  433.07  5218.5  433.08  5270.4  433.86  5275.6  433.17  5285.3  433.20
  5312.1  434.60  5317.3  437.73  5353.8  440.85  5359.0  444.81  5392.1  447.04
#Mann=9,-1,0
  4482.9    0.16       0  4598.3     0.1       0  4611.2    0.05       0
  4681.9    0.07       0  4685.9    0.05       0  4902.8    0.08       0
  5154.6    0.05       0  5178.3    0.08       0  5218.5    0.05       0
Bank Sta=4681.9,4685.9
Exp/Cntr=0.3,0.1

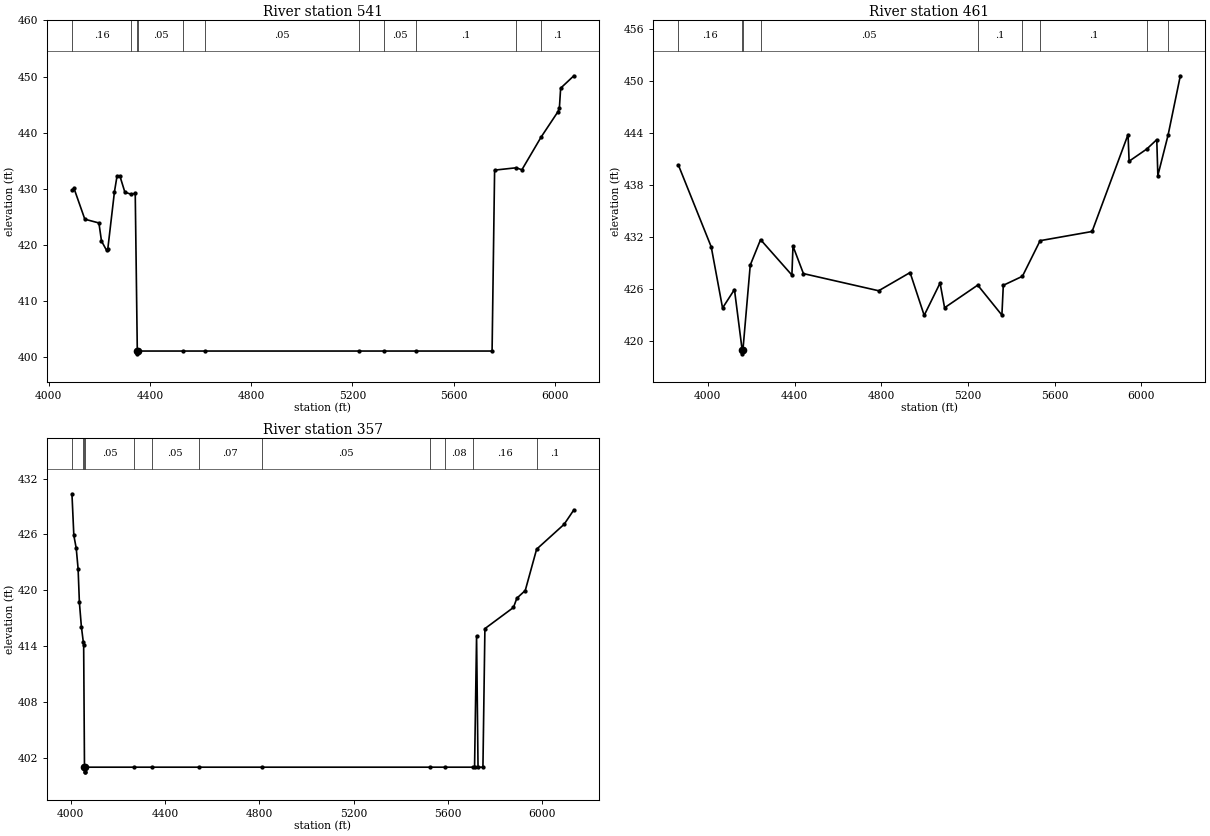
Type RM Length L Ch R = 1,541,80,80,80
BEGIN DESCRIPTION:
UNT1061 IN DUCK CR 3 0
END DESCRIPTION:
XS GIS Cut Line= 6
      3496105.61     10415137.75      3496303.09     10416001.45
      3496446.32     10416086.08      3496648.14     10416064.38
      3496719.76     10415960.22      3496760.99     10415359.08
#Sta/Elev= 30
  4091.4  429.74  4099.3  430.06  4142.3  424.53  4198.0  423.86  4208.2  420.63
  4228.2  418.98  4233.3  419.28  4259.5  429.45  4269.8  432.27  4281.4  432.17
  4300.6  429.36  4326.2  428.97  4341.6  429.15  4349.8  401.00  4350.1  400.50
  4353.8  401.00  4529.5  401.00  4617.2  401.00  5226.5  401.00  5326.4  401.00
  5452.2  401.00  5752.4  401.00  5762.4  433.29  5847.9  433.71  5870.2  433.35
  5946.1  439.18  6013.0  443.73  6018.5  444.37  6023.5  447.92  6075.7  450.13
#Mann=11,-1,0
  4091.4    0.16       0  4326.2    0.05       0  4349.8   0.033       0
  4353.8    0.05       0  4529.5    0.15       0  4617.2    0.05       0
  5226.5     0.1       0  5326.4    0.05       0  5452.2     0.1       0
  5847.9    0.08       0  5946.1     0.1       0
Bank Sta=4349.8,4353.8
Exp/Cntr=0.3,0.1

Type RM Length L Ch R = 1,461,104,104,104
BEGIN DESCRIPTION:
UNT1061 IN DUCK CR 4 0
END DESCRIPTION:
XS GIS Cut Line= 6
      3495966.15     10415015.84      3496207.01     10415914.24
      3496376.28     10416137.76      3496636.70     10416157.29
      3496797.29     10416077.00      3496844.96     10415435.60
#Sta/Elev= 30
  3864.2  440.27  4015.7  430.83  4067.9  423.78  4122.8  425.91  4158.1  418.99
  4158.3  418.49  4162.1  418.99  4195.7  428.73  4243.3  431.67  4387.9  427.58
  4392.9  430.92  4441.1  427.75  4788.3  425.77  4933.3  427.87  4998.4  422.93
  5071.7  426.66  5092.5  423.81  5245.4  426.42  5357.0  422.96  5363.5  426.40
  5451.7  427.44  5533.4  431.55  5773.2  432.61  5939.1  443.79  5944.1  440.72
  6025.8  442.13  6071.7  443.21  6076.7  439.07  6123.9  443.73  6180.4  450.58
#Mann=9,-1,0
  3864.2    0.16       0  4158.1   0.033       0  4162.1    0.16       0
  4243.3    0.05       0  5245.4     0.1       0  5451.7    0.16       0
  5533.4     0.1       0  6025.8    0.08       0  6123.9     0.1       0
Bank Sta=4158.1,4162.1
Exp/Cntr=0.3,0.1

Type RM Length L Ch R = 1,357,0,0,0
BEGIN DESCRIPTION:
UNT1061 IN DUCK CR 1 0
END DESCRIPTION:
XS GIS Cut Line= 5
      3495605.87     10415514.89      3495783.84     10415931.60
      3496389.30     10416254.95      3496851.54     10416157.29
      3497159.70     10415740.63
#Sta/Elev= 30
  4004.9  430.36  4012.9  425.89  4023.1  424.50  4031.0  422.31  4036.5  418.69
  4044.9  416.10  4053.0  414.46  4054.6  414.14  4058.1  401.00  4058.3  400.50
  4061.8  400.50  4062.1  401.00  4268.8  401.00  4344.0  401.00  4543.4  401.00
  4810.5  401.00  5526.5  401.00  5586.3  401.00  5708.7  401.00  5713.7  401.00
  5722.2  415.11  5728.4  401.00  5749.2  401.00  5757.6  415.88  5878.7  418.15
  5893.3  419.15  5928.8  419.97  5977.1  424.41  6093.7  427.08  6135.1  428.63
#Mann=12,-1,0
  4004.9     0.1       0  4053.0    0.05       0  4058.1   0.033       0
  4062.1    0.05       0  4268.8    0.07       0  4344.0    0.05       0
  4543.4    0.07       0  4810.5    0.05       0  5526.5    0.16       0
  5586.3    0.08       0  5708.7    0.16       0  5977.1     0.1       0
Bank Sta=4058.1,4062.1
Exp/Cntr=0.3,0.1

Chan Stop Cuts=-1