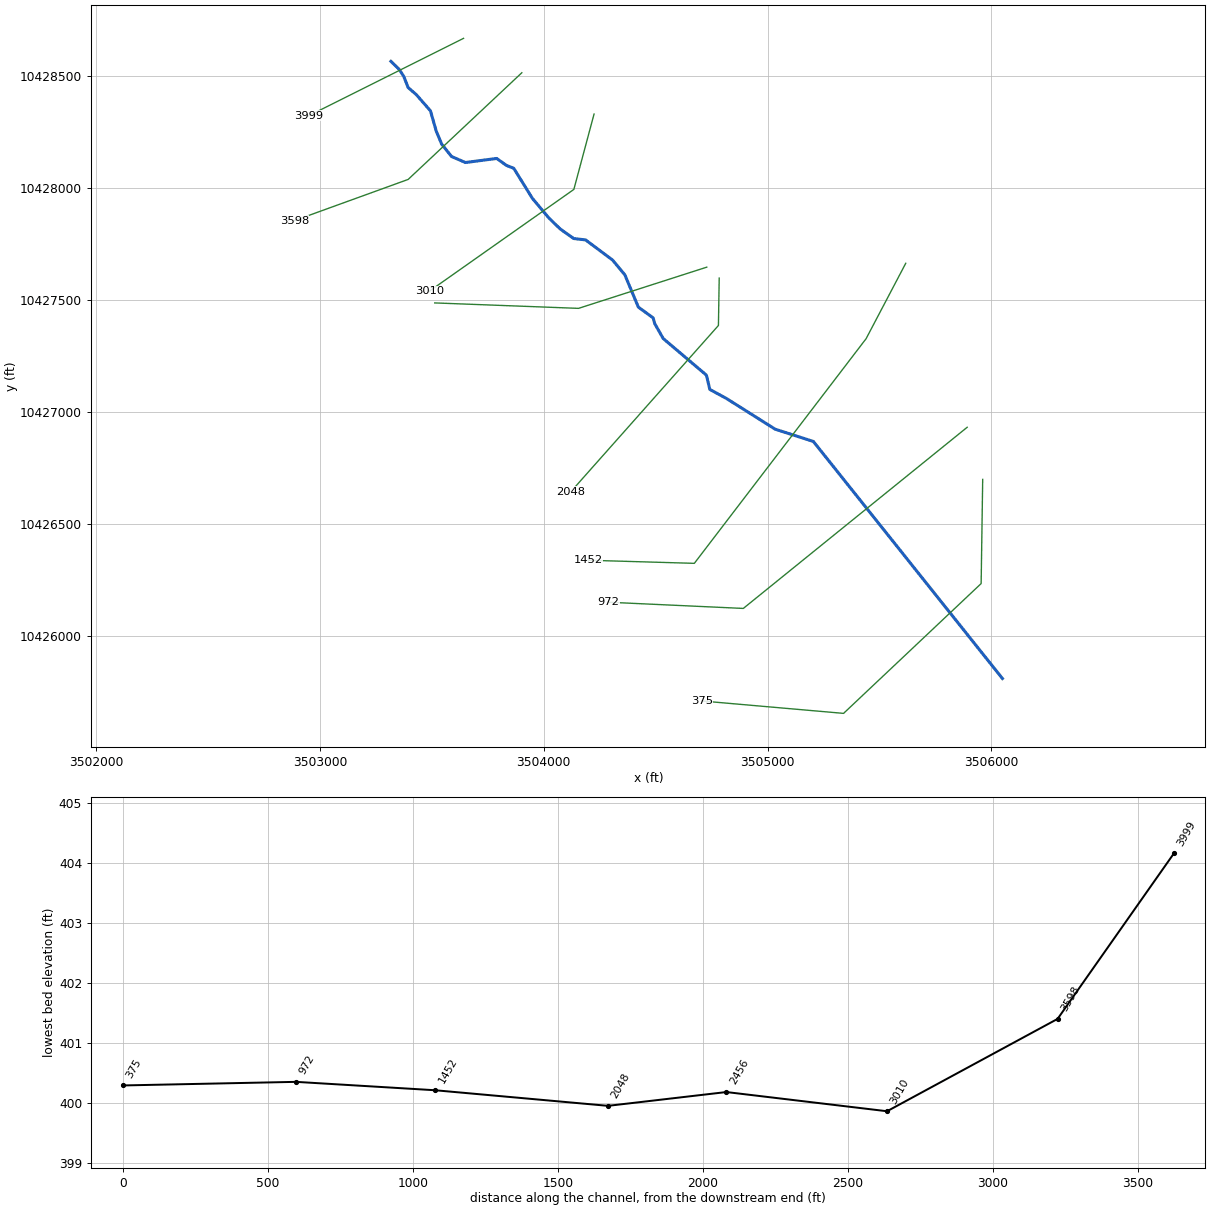
--- UNT1065 IN DUCK CR.prj (project) ---

Proj Title=UNT1065 IN DUCK CR Base Level Engineering
Current Plan=p01
Default Exp/Contr=0.3,0.1
English Units
Geom File=g01
Flow File=f01
Plan File=p01
BEGIN DESCRIPTION:
UNT1065 IN DUCK CR
END DESCRIPTION:

--- UNT1065 IN DUCK CR.p01 (plan) ---

Plan Title=Multiple Run
Short Identifier=Multiple
Geom File=g01
Flow File=f01
Subcritical Flow
K Sum by GR= 0
Std Step Tol= 0.01
Critical Tol= 0.01
Num of Std Step Trials= 20
Max Error Tol= 0.3
Flow Tol Ratio= 0.001
Split Flow NTrial= 30
Split Flow Tol= 0.02
Split Flow Ratio= 0.02
Log Output Level= 0
Friction Slope Method= 1
Unsteady Friction Slope Method= 2
Unsteady Bridges Friction Slope Method= 1
Parabolic Critical Depth
Global Vel Dist=  1 , 1 , 1
Global Log Level= 0
CheckData=True
Encroach Param= -1, 0, 0, 0
BEGIN DESCRIPTION:
Multiple Run
END DESCRIPTION:

--- UNT1065 IN DUCK CR.f01 (steady flow) ---

Flow Title=Multiple
Number of Profiles=7
Profile Names=10-year,25-year,50-year,1pct_min,100-year,1pct_plu,500-year
River Rch & RM= UNT1065 IN DUCK ,Reach-1,3999
     543     719     859     750    1014    1372    1408
Boundary for River Rch & Prof#=UNT1065 IN DUCK ,Reach-1,1
Up Type=0
Dn Type=3
Dn Slope=0.005
Boundary for River Rch & Prof#=UNT1065 IN DUCK ,Reach-1,2
Up Type=0
Dn Type=3
Dn Slope=0.005
Boundary for River Rch & Prof#=UNT1065 IN DUCK ,Reach-1,3
Up Type=0
Dn Type=3
Dn Slope=0.005
Boundary for River Rch & Prof#=UNT1065 IN DUCK ,Reach-1,4
Up Type=0
Dn Type=3
Dn Slope=0.005
Boundary for River Rch & Prof#=UNT1065 IN DUCK ,Reach-1,5
Up Type=0
Dn Type=3
Dn Slope=0.005
Boundary for River Rch & Prof#=UNT1065 IN DUCK ,Reach-1,6
Up Type=0
Dn Type=3
Dn Slope=0.005
Boundary for River Rch & Prof#=UNT1065 IN DUCK ,Reach-1,7
Up Type=0
Dn Type=3
Dn Slope=0.005

--- UNT1065 IN DUCK CR.g01 (geometry) ---

Geom Title=Existing Conditions

River Reach=UNT1065 IN DUCK ,Reach-1
Reach XY= 30
      3503317.11     10428566.64      3503353.97     10428530.90
      3503374.37     10428499.65      3503393.90     10428449.73
      3503430.80     10428417.62      3503493.73     10428345.57
      3503519.77     10428254.42      3503544.08     10428196.70
      3503587.91     10428141.57      3503649.98     10428114.66
      3503789.74     10428132.89      3503833.14     10428101.64
      3503865.69     10428089.06      3503949.46     10427954.07
      3504023.24     10427866.40      3504074.03     10427817.35
      3504133.49     10427775.25      3504186.79     10427769.00
      3504307.27     10427679.07      3504362.13     10427613.10
      3504422.55     10427468.66      3504488.52     10427420.74
      3504495.81     10427394.70      3504533.66     10427328.38
      3504726.58     10427164.91      3504741.77     10427101.10
      3504815.99     10427060.74      3505033.55     10426923.63
      3505204.31     10426868.75      3506048.94     10425809.86

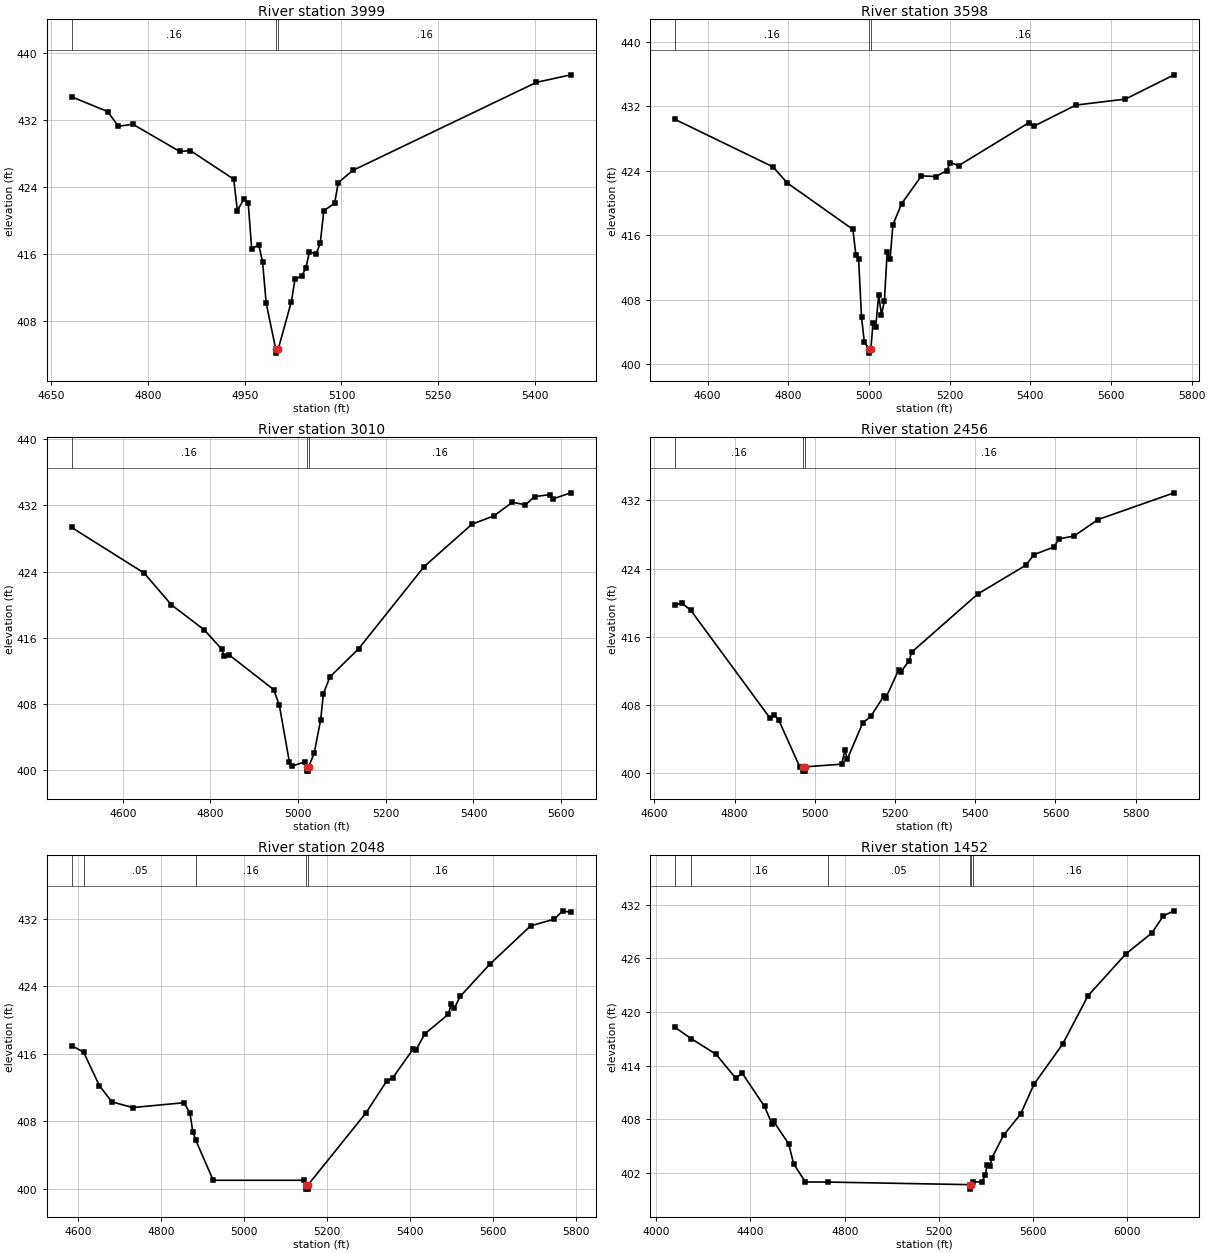
Type RM Length L Ch R = 1,3999,401,401,401
BEGIN DESCRIPTION:
UNT1065 IN DUCK CR 11 0
END DESCRIPTION:
XS GIS Cut Line= 2
      3503641.57     10428669.35      3502948.92     10428323.03
#Sta/Elev= 30
  4681.4  434.81  4737.2  433.05  4754.0  431.29  4776.4  431.53  4849.0  428.28
  4865.8  428.37  4932.9  424.96  4938.5  421.20  4949.1  422.64  4955.3  422.16
  4960.8  416.57  4971.5  417.15  4977.6  415.09  4983.2  410.14  4998.0  404.66
  4998.2  404.16  5002.0  404.66  5022.3  410.32  5027.9  412.98  5038.6  413.43
  5044.7  414.32  5050.3  416.24  5060.9  416.07  5067.1  417.29  5072.6  421.18
  5089.4  422.08  5095.0  424.54  5117.4  426.00  5402.5  436.54  5455.8  437.44
#Mann=3,-1,0
  4681.4    0.16       0  4998.0    0.07       0  5002.0    0.16       0
Bank Sta=4998,5002
Exp/Cntr=0.3,0.1

Type RM Length L Ch R = 1,3598,588,588,588
BEGIN DESCRIPTION:
UNT1065 IN DUCK CR 10 0
END DESCRIPTION:
XS GIS Cut Line= 3
      3503901.98     10428515.70      3503394.19     10428039.16
      3502885.42     10427854.86
#Sta/Elev= 30
  4518.9  430.39  4762.3  424.49  4797.5  422.50  4960.2  416.74  4967.5  413.59
  4974.3  413.11  4981.6  405.85  4988.5  402.77  5000.7  401.90  5000.9  401.40
  5004.7  401.90  5010.0  405.13  5016.8  404.67  5024.1  408.60  5031.0  406.18
  5038.3  407.85  5045.1  413.92  5052.5  413.13  5059.3  417.30  5080.8  419.92
  5130.1  423.38  5165.3  423.30  5193.6  424.03  5200.9  425.03  5222.7  424.66
  5395.9  429.95  5408.9  429.54  5513.1  432.16  5635.7  432.90  5756.4  435.91
#Mann=3,-1,0
  4518.9    0.16       0  5000.7    0.07       0  5004.7    0.16       0
Bank Sta=5000.7,5004.7
Exp/Cntr=0.3,0.1

Type RM Length L Ch R = 1,3010,554,554,554
BEGIN DESCRIPTION:
UNT1065 IN DUCK CR 9 0
END DESCRIPTION:
XS GIS Cut Line= 3
      3504224.67     10428331.31      3504134.39     10427994.51
      3503488.58     10427539.66
#Sta/Elev= 30
  4483.4  429.34  4648.7  423.83  4710.9  419.98  4785.7  416.96  4825.7  414.62
  4831.0  413.82  4843.4  413.89  4944.4  409.72  4957.2  407.83  4980.1  400.96
  4986.2  400.46  5015.8  401.00  5019.9  400.36  5020.2  399.86  5023.7  399.86
  5023.9  400.36  5036.7  402.04  5051.5  406.07  5057.7  409.22  5072.5  411.26
  5137.8  414.65  5287.4  424.60  5396.4  429.73  5446.5  430.74  5488.8  432.39
  5518.4  432.08  5539.3  433.07  5575.0  433.32  5581.1  432.79  5622.0  433.53
#Mann=3,-1,0
  4483.4    0.16       0  5019.9    0.07       0  5023.9    0.16       0
Bank Sta=5019.9,5023.9
Exp/Cntr=0.3,0.1

Type RM Length L Ch R = 1,2456,408,408,408
BEGIN DESCRIPTION:
UNT1065 IN DUCK CR 7 0
END DESCRIPTION:
XS GIS Cut Line= 3
      3504728.18     10427647.30      3504155.23     10427463.26
      3503512.87     10427487.56
#Sta/Elev= 30
  4651.1  419.75  4668.0  419.92  4690.1  419.13  4888.5  406.40  4899.1  406.81
  4909.6  406.23  4962.1  400.71  4970.6  400.68  4970.8  400.18  4974.3  400.18
  4974.6  400.68  5067.1  401.00  5075.3  402.70  5080.6  401.55  5119.6  405.86
  5139.5  406.61  5171.7  408.98  5176.9  408.77  5209.0  412.08  5214.3  411.85
  5235.2  413.15  5241.1  414.15  5406.1  421.00  5526.2  424.39  5546.2  425.63
  5596.2  426.53  5609.1  427.49  5646.3  427.82  5706.3  429.76  5895.7  432.90
#Mann=3,-1,0
  4651.1    0.16       0  4970.6    0.07       0  4974.6    0.16       0
Bank Sta=4970.6,4974.6
Exp/Cntr=0.3,0.1

Type RM Length L Ch R = 1,2048,596,596,596
BEGIN DESCRIPTION:
UNT1065 IN DUCK CR 6 0
END DESCRIPTION:
XS GIS Cut Line= 3
      3504783.70     10427598.66      3504780.23     10427386.87
      3504121.76     10426645.22
#Sta/Elev= 30
  4584.1  416.99  4612.9  416.21  4651.1  412.23  4681.1  410.31  4731.1  409.63
  4855.3  410.21  4869.5  408.96  4876.2  406.77  4883.6  405.73  4925.5  401.00
  5145.5  401.00  5150.2  400.45  5150.4  399.95  5153.9  399.95  5154.2  400.45
  5294.3  409.03  5343.7  412.78  5357.9  413.13  5407.2  416.55  5414.8  416.49
  5435.7  418.38  5492.5  420.70  5499.2  421.89  5506.8  421.42  5521.0  422.82
  5591.9  426.62  5690.7  431.19  5747.6  431.99  5768.5  432.98  5787.7  432.79
#Mann=5,-1,0
  4584.1    0.16       0  4612.9    0.05       0  4883.6    0.16       0
  5150.2    0.07       0  5154.2    0.16       0
Bank Sta=5150.2,5154.2
Exp/Cntr=0.3,0.1

Type RM Length L Ch R = 1,1452,480,480,480
BEGIN DESCRIPTION:
UNT1065 IN DUCK CR 5 0
END DESCRIPTION:
XS GIS Cut Line= 4
      3505617.05     10427664.67      3505439.95     10427327.84
      3504672.59     10426324.37      3504196.99     10426338.26
#Sta/Elev= 30
  4079.0  418.31  4148.7  417.03  4254.2  415.28  4336.7  412.63  4364.9  413.17
  4459.5  409.46  4491.7  407.49  4498.0  407.79  4562.4  405.26  4583.2  403.03
  4633.1  401.01  4728.0  401.00  5331.2  400.71  5331.5  400.21  5335.2  400.71
  5345.1  401.04  5383.1  401.00  5397.6  401.82  5403.9  402.87  5418.4  402.83
  5424.7  403.69  5474.6  406.24  5547.2  408.61  5603.4  411.92  5725.5  416.43
  5833.3  421.84  5993.4  426.50  6103.4  428.83  6153.5  430.77  6198.6  431.33
#Mann=6,-1,0
  4079.0    0.05       0  4148.7    0.16       0  4728.0    0.05       0
  5331.2   0.033       0  5335.2    0.05       0  5345.1    0.16       0
Bank Sta=5331.2,5335.2
Exp/Cntr=0.3,0.1

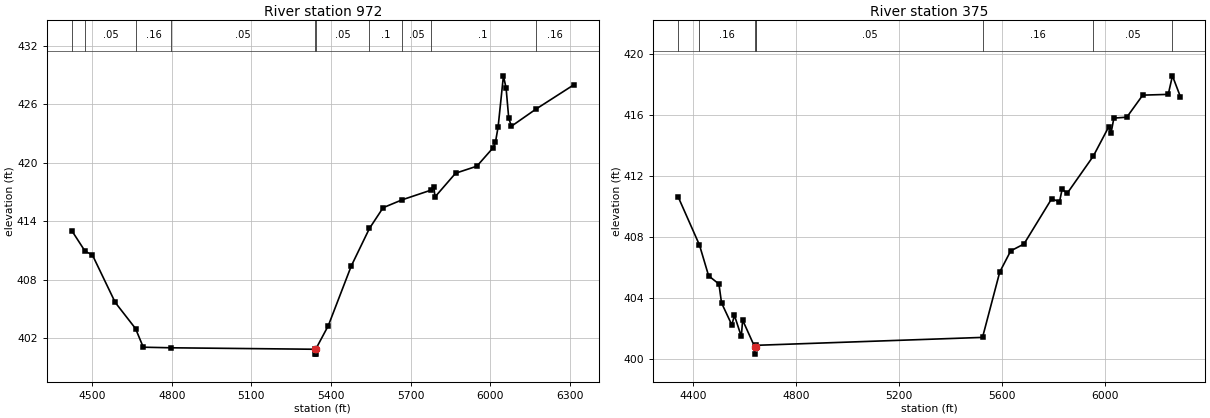
Type RM Length L Ch R = 1,972,597,597,597
BEGIN DESCRIPTION:
UNT1065 IN DUCK CR 4 0
END DESCRIPTION:
XS GIS Cut Line= 3
      3505891.38     10426932.04      3504891.34     10426122.98
      3504287.21     10426150.76
#Sta/Elev= 30
  4423.4  413.02  4473.9  410.89  4500.8  410.54  4587.1  405.65  4663.6  402.97
  4692.7  401.06  4799.0  401.00  5338.2  400.85  5338.4  400.35  5341.9  400.35
  5342.2  400.85  5389.8  403.28  5476.1  409.39  5544.5  413.24  5596.0  415.37
  5667.7  416.18  5775.0  417.16  5786.7  417.54  5791.7  416.48  5869.1  418.91
  5949.2  419.63  6010.7  421.53  6019.3  422.10  6029.3  423.67  6049.3  428.90
  6059.3  427.64  6069.3  424.55  6079.4  423.73  6171.5  425.48  6314.5  427.98
#Mann=10,-1,0
  4423.4    0.16       0  4473.9    0.05       0  4663.6    0.16       0
  4799.0    0.05       0  5338.2   0.033       0  5342.2    0.05       0
  5544.5     0.1       0  5667.7    0.05       0  5775.0     0.1       0
  6171.5    0.16       0
Bank Sta=5338.2,5342.2
Exp/Cntr=0.3,0.1

Type RM Length L Ch R = 1,375,0,0,0
BEGIN DESCRIPTION:
UNT1065 IN DUCK CR 1 0
END DESCRIPTION:
XS GIS Cut Line= 4
      3505960.78     10426699.39      3505953.84     10426234.09
      3505339.26     10425654.23      3504705.48     10425709.64
#Sta/Elev= 30
  4343.8  410.62  4426.2  407.46  4461.6  405.44  4501.6  404.90  4511.6  403.66
  4551.6  402.21  4561.6  402.84  4588.4  401.45  4593.4  402.53  4639.6  400.79
  4639.8  400.29  4643.6  400.79  4646.8  400.87  5523.5  401.39  5590.3  405.69
  5632.8  407.08  5684.1  407.53  5791.7  410.51  5821.9  410.30  5831.9  411.12
  5852.0  410.87  5953.0  413.31  6012.6  415.23  6021.9  414.84  6032.7  415.81
  6082.9  415.87  6144.6  417.32  6243.5  417.37  6259.8  418.59  6290.3  417.23
#Mann=8,-1,0
  4343.8    0.05       0  4426.2    0.16       0  4639.6   0.033       0
  4643.6    0.16       0  4646.8    0.05       0  5523.5    0.16       0
  5953.0    0.05       0  6259.8     0.1       0
Bank Sta=4639.6,4643.6
Exp/Cntr=0.3,0.1

Chan Stop Cuts=-1