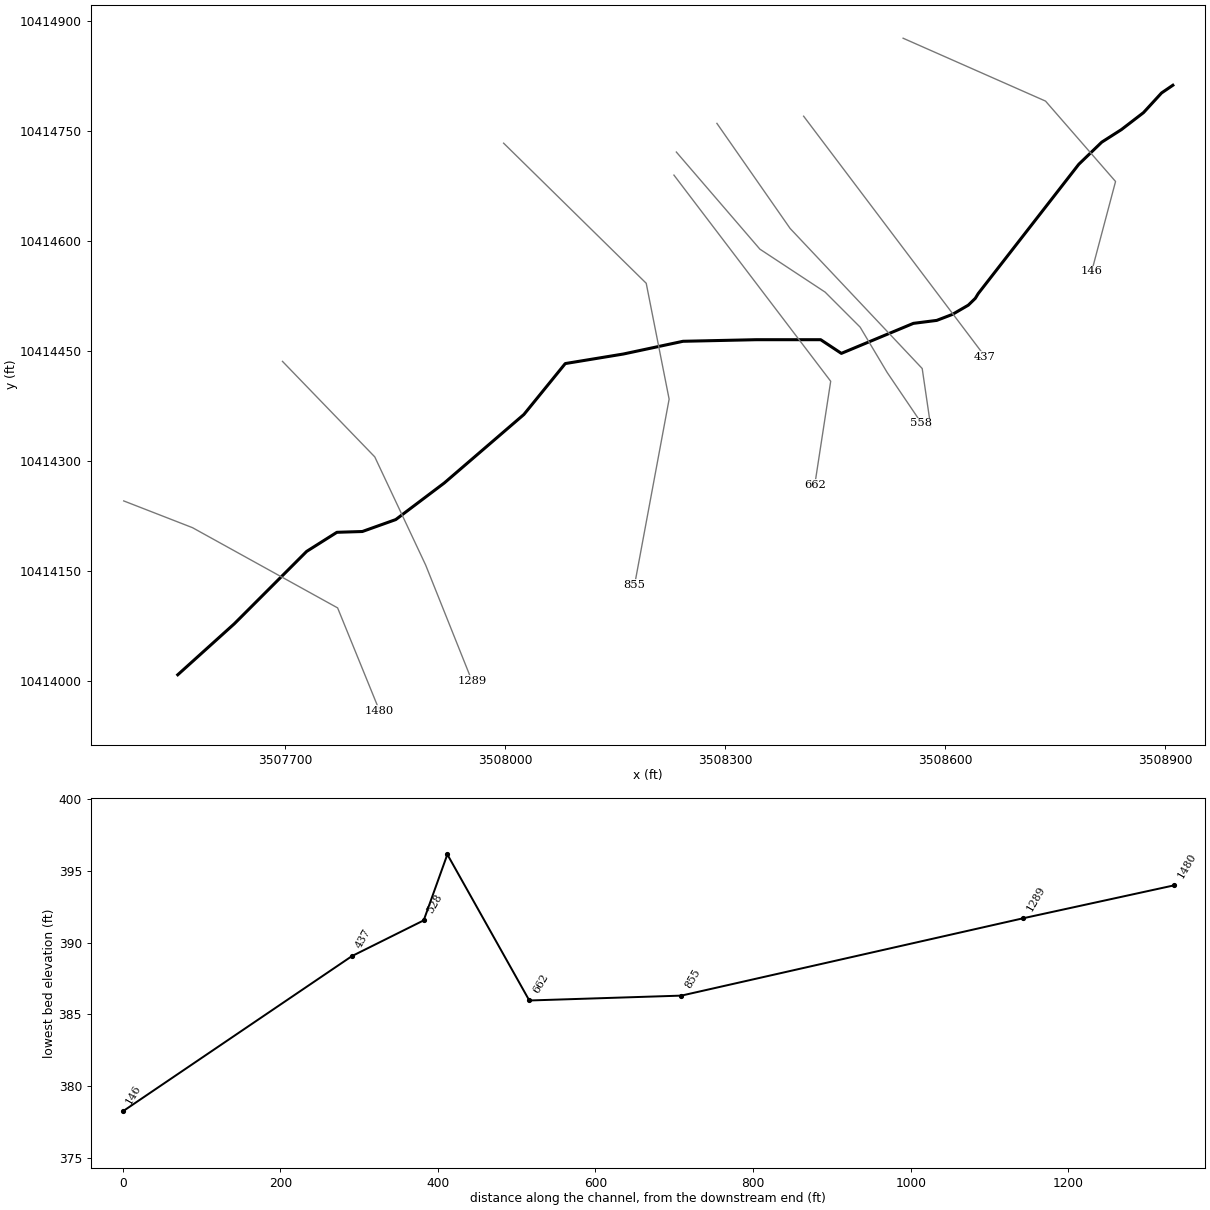
--- UNT5862 IN DUCK CR.prj (project) ---

Proj Title=UNT5862 IN DUCK CR Base Level Engineering
Current Plan=p01
Default Exp/Contr=0.3,0.1
English Units
Geom File=g01
Flow File=f01
Plan File=p01
Y Axis Title=Elevation
X Axis Title(PF)=Main Channel Distance
X Axis Title(XS)=Station
BEGIN DESCRIPTION:
UNT5862 IN DUCK CR
END DESCRIPTION:
DSS Export Rating Curves= 0
DSS Export Rating Curve Sorted= 0
DSS Export Volume Flow Curves= 0
DXF OffsetX= 0
DXF OffsetY= 0
DXF ScaleX= 1
DXF ScaleY= 10

--- UNT5862 IN DUCK CR.p01 (plan) ---

Plan Title=Multiple Run
Short Identifier=Multiple
Geom File=g01
Flow File=f01
Subcritical Flow
K Sum by GR= 0
Std Step Tol= 0.01
Critical Tol= 0.01
Num of Std Step Trials= 20
Max Error Tol= 0.3
Flow Tol Ratio= 0.001
Split Flow NTrial= 30
Split Flow Tol= 0.02
Split Flow Ratio= 0.02
Log Output Level= 0
Friction Slope Method= 1
Unsteady Friction Slope Method= 2
Unsteady Bridges Friction Slope Method= 1
Parabolic Critical Depth
Global Vel Dist=  1 , 1 , 1
Global Log Level= 0
CheckData=True
Encroach Param= -1, 0, 0, 0
BEGIN DESCRIPTION:
Multiple Run
END DESCRIPTION:

--- UNT5862 IN DUCK CR.f01 (steady flow) ---

Flow Title=Multiple
Program Version=4.10
Number of Profiles= 7
Profile Names=10-year,25-year,50-year,1pct_min,100-year,1pct_plu,500-year
River Rch & RM=UNT5862 IN DUCK,Reach-1         ,1480
     127     152     171     141     190     258     235
Boundary for River Rch & Prof#=UNT5862 IN DUCK,Reach-1         , 1
Up Type= 0
Dn Type= 3
Dn Slope=0.035
Boundary for River Rch & Prof#=UNT5862 IN DUCK,Reach-1         , 2
Up Type= 0
Dn Type= 3
Dn Slope=0.035
Boundary for River Rch & Prof#=UNT5862 IN DUCK,Reach-1         , 3
Up Type= 0
Dn Type= 3
Dn Slope=0.035
Boundary for River Rch & Prof#=UNT5862 IN DUCK,Reach-1         , 4
Up Type= 0
Dn Type= 3
Dn Slope=0.035
Boundary for River Rch & Prof#=UNT5862 IN DUCK,Reach-1         , 5
Up Type= 0
Dn Type= 3
Dn Slope=0.035
Boundary for River Rch & Prof#=UNT5862 IN DUCK,Reach-1         , 6
Up Type= 0
Dn Type= 3
Dn Slope=0.035
Boundary for River Rch & Prof#=UNT5862 IN DUCK,Reach-1         , 7
Up Type= 0
Dn Type= 3
Dn Slope=0.035
DSS Import GetInterval= 0
DSS Import GetPeak= 0
DSS Import FillOption= 0

--- UNT5862 IN DUCK CR.g01 (geometry) ---

Geom Title=Existing Conditions
Program Version=4.10

River Reach=UNT5862 IN DUCK ,Reach-1
Reach XY= 26
      3507553.87     10414008.77      3507630.91     10414078.21
      3507729.65     10414176.96      3507770.89       10414203.
      3507805.61     10414204.08      3507851.18     10414220.36
      3507917.37     10414270.27      3508025.88     10414363.59
       3508082.3     10414433.03      3508161.51     10414446.05
      3508242.89     10414463.41      3508342.72     10414465.58
      3508430.61     10414465.58      3508458.82     10414446.92
      3508557.04     10414487.85      3508588.89     10414491.89
      3508610.27     10414500.07      3508631.92     10414512.66
      3508641.51     10414521.98      3508645.47     10414528.48
       3508782.6     10414704.73      3508813.89     10414734.87
      3508840.76     10414752.04      3508870.84     10414775.15
      3508895.45     10414801.96      3508910.88     10414812.47

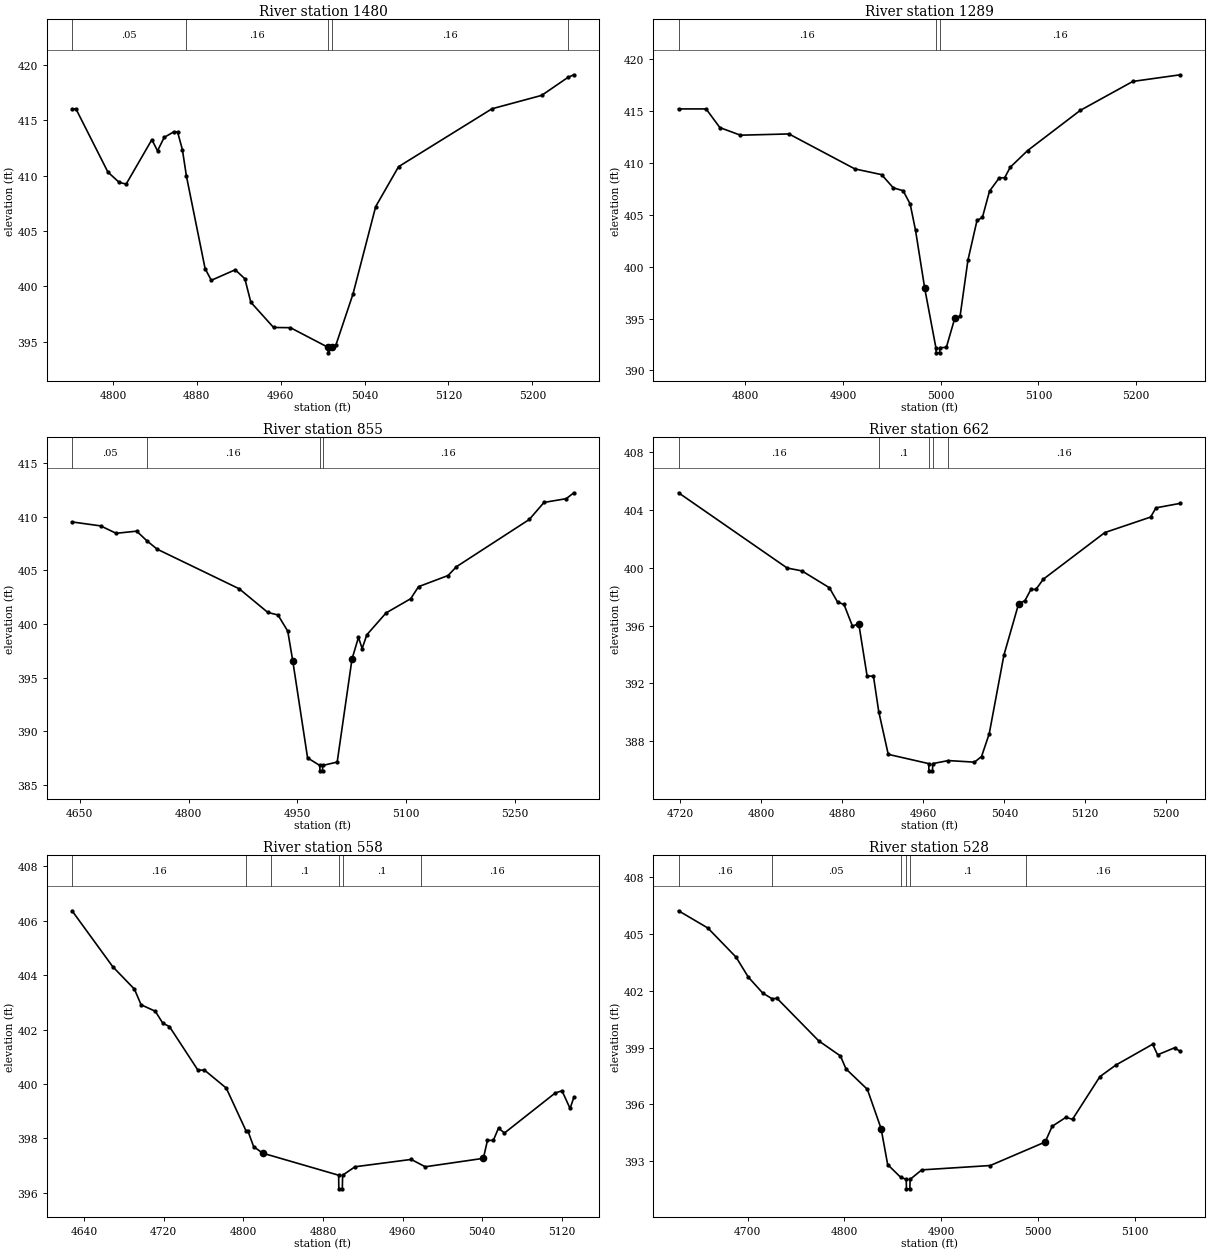
Type RM Length L Ch R = 1 ,1480    ,191,191,191
BEGIN DESCRIPTION:
UNT5862 IN DUCK CR 4 0
END DESCRIPTION:
XS GIS Cut Line= 4
      3507480.19     10414245.79      3507573.96     10414209.32
      3507771.88     10414099.94      3507829.17     10413959.31
#Sta/Elev= 30
    4761  416.02  4764.7  416.02  4795.2  410.31    4806  409.38  4812.6  409.23
  4837.1  413.24  4842.5  412.23  4848.9  413.45  4857.9  413.94  4861.6  413.94
  4866.2  412.35  4870.1  409.93  4887.9  401.59  4893.8  400.54  4916.6  401.49
  4925.8  400.68  4931.5  398.56  4953.2  396.28  4969.3  396.26  5005.1  394.49
  5005.3  393.99  5009.1  394.49  5012.8  394.74  5028.9  399.29  5050.6   407.2
  5072.4   410.8  5161.5  416.03  5208.9  417.24  5233.9  418.86  5239.6   419.1
#Mann= 5 ,-1 , 0
    4761     .05       0  4870.1     .16       0  5005.1     .07       0
  5009.1     .16       0  5233.9     .08       0
Bank Sta=5005.1,5009.1
XS Rating Curve= 0 ,0
Exp/Cntr=0.3,0.1

Type RM Length L Ch R = 1 ,1289    ,434,434,434
BEGIN DESCRIPTION:
UNT5862 IN DUCK CR 4 0
END DESCRIPTION:
XS GIS Cut Line= 4
      3507696.69     10414436.01      3507822.53     10414305.83
      3507891.97     10414158.26      3507954.91     10414000.93
#Sta/Elev= 30
  4731.6   415.2  4759.8   415.2  4773.9   413.4    4795  412.67  4844.6  412.79
  4912.1  409.42  4939.4  408.87  4951.4   407.6  4961.5  407.32  4968.7  406.03
  4974.2  403.49  4983.6   397.9    4995   392.2  4995.3   391.7  4998.8   391.7
    4999   392.2  5005.7  392.22  5014.3  395.02  5019.8  395.25  5027.8  400.62
  5037.1  404.46  5042.6  404.74  5049.9  407.28  5059.9  408.56  5065.4  408.57
  5071.1  409.58  5088.9  411.19  5142.8  415.06  5196.6  417.85  5245.2  418.49
#Mann= 3 ,-1 , 0
  4731.6     .16       0    4995     .07       0    4999     .16       0
Bank Sta=4983.6,5014.3
XS Rating Curve= 0 ,0
Exp/Cntr=0.3,0.1

Type RM Length L Ch R = 1 ,855     ,193,193,193
BEGIN DESCRIPTION:
UNT5862 IN DUCK CR 2 0
END DESCRIPTION:
XS GIS Cut Line= 4
      3507998.25      10414733.5       3508192.7     10414542.51
      3508223.95     10414384.53      3508176.83     10414131.28
#Sta/Elev= 30
  4639.6  409.52    4679  409.15  4700.3  408.46  4728.6  408.66  4742.5  407.77
  4756.8  406.98  4869.9  403.28  4909.2  401.08  4923.2  400.84  4936.7  399.33
  4943.6  396.56    4964  387.51  4980.8   386.8  4981.1   386.3  4984.6   386.3
  4984.8   386.8  5004.8  387.12  5025.2  396.73  5034.1  398.75  5039.2  397.71
  5045.6  398.99  5072.1  401.03  5106.1  402.36  5116.8  403.48  5157.5  404.52
    5169  405.34  5269.4  409.75  5289.7  411.34  5320.3  411.69  5330.8  412.24
#Mann= 4 ,-1 , 0
  4639.6     .05       0  4742.5     .16       0  4980.8     .07       0
  4984.8     .16       0
Bank Sta=4943.6,5025.2
XS Rating Curve= 0 ,0
Exp/Cntr=0.3,0.1

Type RM Length L Ch R = 1 ,662     ,104,104,104
BEGIN DESCRIPTION:
Mapping XS e43375b3
END DESCRIPTION:
XS GIS Cut Line= 3
      3508230.51     10414689.96      3508444.27     10414408.91
      3508422.58     10414267.87
#Sta/Elev= 30
  4718.1  405.18  4825.4  399.98    4840  399.78  4867.1  398.62  4875.3  397.62
  4881.6  397.46  4889.9  395.97  4896.2  396.12  4904.4  392.52  4910.7   392.5
  4915.9  390.06  4925.3   387.1  4965.3  386.46  4965.5  385.96    4969  385.96
  4969.3  386.46  4984.7  386.67  5010.5  386.56  5017.5  386.95  5025.1  388.53
  5039.6  393.96  5054.1   397.5  5060.4  397.73  5066.3   398.5  5071.2   398.5
  5078.6  399.21  5139.3  402.43  5184.5   403.5  5189.9  404.14  5213.9  404.45
#Mann= 5 ,-1 , 0
  4718.1     .16       0  4915.9      .1       0  4965.3     .07       0
  4969.3      .1       0  4984.7     .16       0
Bank Sta=4896.2,5054.1
XS Rating Curve= 0 ,0
Exp/Cntr=0.3,0.1

Type RM Length L Ch R = 1 ,558     ,30,30,30
BEGIN DESCRIPTION:
UNT5862 IN DUCK CR 3 0
END DESCRIPTION:
XS GIS Cut Line= 6
      3508233.79     10414721.39       3508347.7     10414589.03
      3508436.68     10414530.44      3508484.42      10414482.7
      3508521.31     10414420.85      3508568.06     10414351.78
#Sta/Elev= 30
  4627.9  406.36  4668.7  404.31  4690.6  403.48  4697.2  402.91  4711.5  402.67
  4719.1  402.23  4725.7  402.11  4754.3  400.51  4760.9  400.51  4782.8  399.85
  4802.9  398.26  4804.7  398.26  4810.3   397.7  4819.4  397.46  4895.7  396.65
  4895.9  396.15  4899.4  396.15  4899.7  396.65  4912.1  396.96  4968.6  397.23
  4982.7  396.96  5041.1  397.27  5045.2  397.93  5051.1  397.93  5056.3  398.38
  5062.3   398.2  5113.3  399.67  5120.1  399.75  5128.2   399.1    5132  399.51
#Mann= 6 ,-1 , 0
  4627.9     .16       0  4802.9     .05       0    4828      .1       0
  4895.7     .07       0  4899.7      .1       0    4978     .16       0
Bank Sta=4819.4,5041.1
XS Rating Curve= 0 ,0
Exp/Cntr=0.3,0.1

Type RM Length L Ch R = 1 ,528     ,91,91,91
BEGIN DESCRIPTION:
Mapping XS 183399f0
END DESCRIPTION:
XS GIS Cut Line= 4
      3508289.11     10414760.48      3508388.94     10414617.24
      3508569.06     10414426.27      3508580.87     10414345.74
#Sta/Elev= 30
  4628.6  406.22  4658.9  405.31  4688.1  403.77  4700.7  402.72  4715.6  401.88
  4725.2  401.58  4730.4   401.6  4773.4  399.36  4795.9  398.56  4801.6  397.88
  4823.7   396.8  4837.9  394.73  4844.7  392.83  4858.1  392.16  4863.9  392.05
  4864.1  391.55  4867.6  391.55  4867.9  392.05  4879.9  392.55  4950.7  392.78
  5007.4  394.02  5014.7  394.85  5028.8  395.32  5035.7  395.22    5064  397.47
  5080.5  398.08  5118.5  399.18  5123.6  398.62  5141.1  398.99  5147.1   398.8
#Mann= 6 ,-1 , 0
  4628.6     .16       0  4725.2     .05       0  4858.1      .1       0
  4863.9     .07       0  4867.9      .1       0  4988.1     .16       0
Bank Sta=4837.9,5007.4
XS Rating Curve= 0 ,0
Exp/Cntr=0.3,0.1

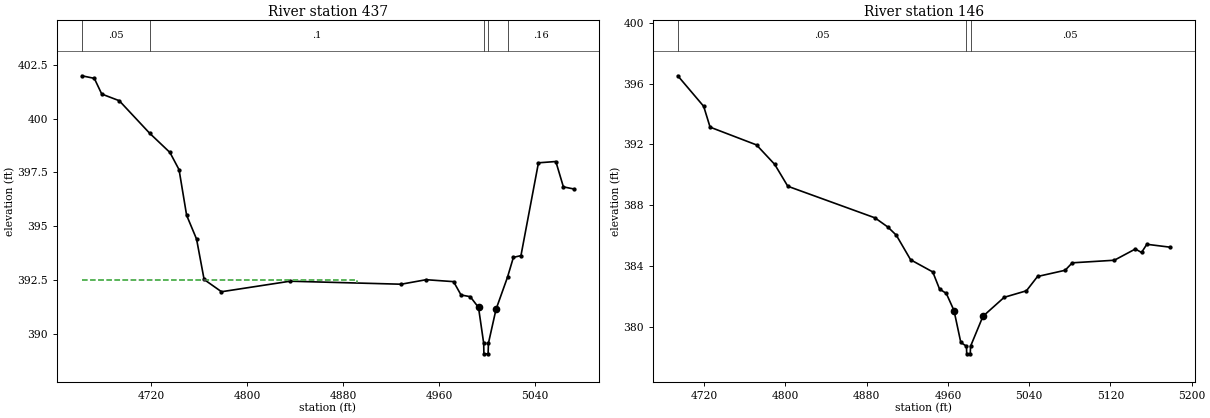
Type RM Length L Ch R = 1 ,437     ,291,291,291
BEGIN DESCRIPTION:
UNT5862 IN DUCK CR 5 0
END DESCRIPTION:
XS GIS Cut Line= 2
      3508407.36     10414770.26      3508654.76     10414442.57
#Sta/Elev= 30
    4662     402  4672.4  401.88  4678.6  401.15  4693.2  400.84  4718.5  399.33
  4735.5  398.43  4743.1  397.63  4749.4  395.51  4757.7   394.4    4764  392.52
  4778.5  391.95  4835.7  392.44  4928.4   392.3  4949.2  392.51  4972.1  392.42
  4978.3   391.8    4986  391.72  4992.9  391.22  4997.2  389.56  4997.4  389.06
  5000.9  389.06  5001.2  389.56  5007.5  391.13  5017.1  392.63    5022  393.55
  5028.3  393.63  5042.9  397.95  5057.4  398.01  5063.7  396.83  5072.6  396.73
#Mann= 5 ,-1 , 0
    4662     .05       0  4718.5      .1       0  4997.2     .07       0
  5001.2      .1       0  5017.1     .16       0
#XS Ineff= 2 , 0
         4891.36  392.49
Permanent Ineff=
       F       F
Bank Sta=4992.9,5007.5
XS Rating Curve= 0 ,0
Exp/Cntr=0.3,0.1

Type RM Length L Ch R = 1 ,146     ,0,0,0
BEGIN DESCRIPTION:
UNT5862 IN DUCK CR 1 0
END DESCRIPTION:
XS GIS Cut Line= 4
      3508543.03     10414876.57      3508737.24     10414790.86
      3508832.73     10414681.26      3508800.18     10414558.65
#Sta/Elev= 30
  4694.1  396.52  4719.6  394.51  4725.9  393.14  4771.6  391.97  4789.5  390.69
  4802.4  389.25  4888.2  387.17  4900.8  386.57  4909.2  386.03  4923.3  384.41
  4945.1  383.61  4951.8  382.48  4958.4   382.2    4966  381.07  4972.7  378.97
  4978.3  378.72  4978.5  378.22    4982  378.22  4982.3  378.72  4994.5  380.69
  5015.4  381.94  5037.3  382.37  5048.2  383.31  5075.4  383.72  5082.4  384.21
  5123.8  384.38  5144.5  385.12  5150.6  384.89  5155.8  385.43  5178.6  385.24
#Mann= 3 ,-1 , 0
  4694.1     .05       0  4978.3     .04       0  4982.3     .05       0
Bank Sta=4966,4994.5
XS Rating Curve= 0 ,0
Exp/Cntr=0.3,0.1

Chan Stop Cuts=-1
Use User Specified Reach Order=0
Composite Channel Slope=5