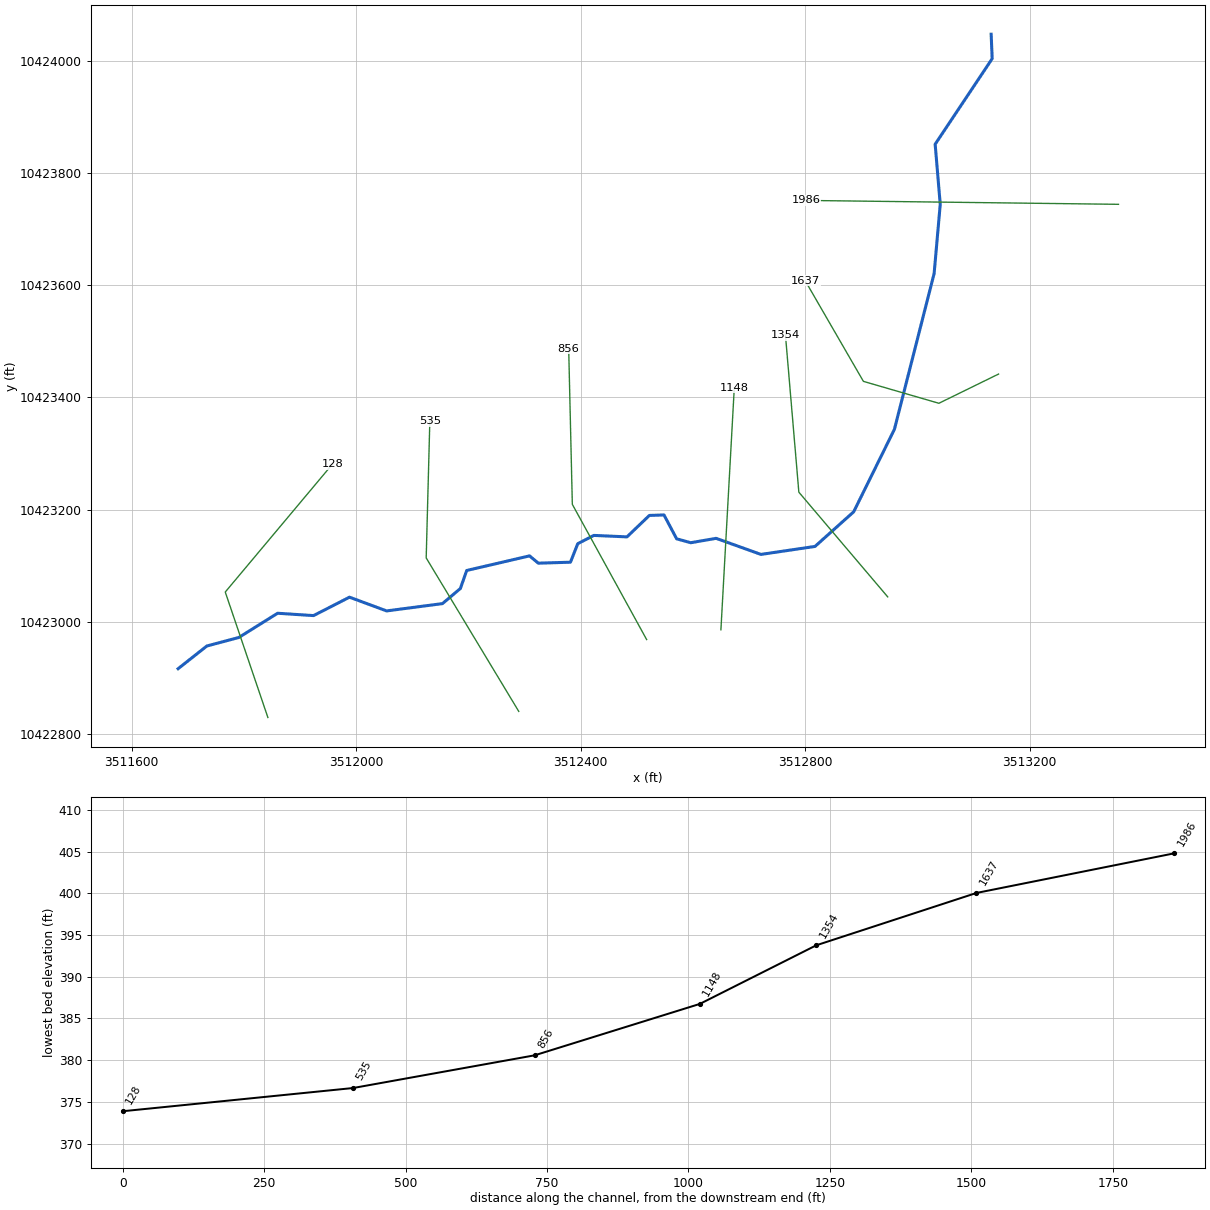
--- UNT6083 IN DUCK CR.prj (project) ---

Proj Title=UNT6083 IN DUCK CR Base Level Engineering
Current Plan=p01
Default Exp/Contr=0.3,0.1
English Units
Geom File=g01
Flow File=f01
Plan File=p01
Y Axis Title=Elevation
X Axis Title(PF)=Main Channel Distance
X Axis Title(XS)=Station
BEGIN DESCRIPTION:
UNT6083 IN DUCK CR
END DESCRIPTION:
DSS Export Rating Curves= 0
DSS Export Rating Curve Sorted= 0
DSS Export Volume Flow Curves= 0
DXF OffsetX= 0
DXF OffsetY= 0
DXF ScaleX= 1
DXF ScaleY= 10

--- UNT6083 IN DUCK CR.p01 (plan) ---

Plan Title=Multiple Run
Short Identifier=Multiple
Geom File=g01
Flow File=f01
Subcritical Flow
K Sum by GR= 0
Std Step Tol= 0.01
Critical Tol= 0.01
Num of Std Step Trials= 20
Max Error Tol= 0.3
Flow Tol Ratio= 0.001
Split Flow NTrial= 30
Split Flow Tol= 0.02
Split Flow Ratio= 0.02
Log Output Level= 0
Friction Slope Method= 1
Unsteady Friction Slope Method= 2
Unsteady Bridges Friction Slope Method= 1
Parabolic Critical Depth
Global Vel Dist=  1 , 1 , 1
Global Log Level= 0
CheckData=True
Encroach Param= -1, 0, 0, 0
BEGIN DESCRIPTION:
Multiple Run
END DESCRIPTION:

--- UNT6083 IN DUCK CR.f01 (steady flow) ---

Flow Title=Multiple
Number of Profiles=7
Profile Names=10-year,25-year,50-year,1pct_min,100-year,1pct_plu,500-year
River Rch & RM= UNT6083 IN DUCK ,Reach-1,1986
     139     168     189     157     212     287     263
Boundary for River Rch & Prof#=UNT6083 IN DUCK ,Reach-1,1
Up Type=0
Dn Type=3
Dn Slope=0.005
Boundary for River Rch & Prof#=UNT6083 IN DUCK ,Reach-1,2
Up Type=0
Dn Type=3
Dn Slope=0.005
Boundary for River Rch & Prof#=UNT6083 IN DUCK ,Reach-1,3
Up Type=0
Dn Type=3
Dn Slope=0.005
Boundary for River Rch & Prof#=UNT6083 IN DUCK ,Reach-1,4
Up Type=0
Dn Type=3
Dn Slope=0.005
Boundary for River Rch & Prof#=UNT6083 IN DUCK ,Reach-1,5
Up Type=0
Dn Type=3
Dn Slope=0.005
Boundary for River Rch & Prof#=UNT6083 IN DUCK ,Reach-1,6
Up Type=0
Dn Type=3
Dn Slope=0.005
Boundary for River Rch & Prof#=UNT6083 IN DUCK ,Reach-1,7
Up Type=0
Dn Type=3
Dn Slope=0.005

--- UNT6083 IN DUCK CR.g01 (geometry) ---

Geom Title=Existing Conditions
Program Version=4.10

River Reach=UNT6083 IN DUCK ,Reach-1
Reach XY= 30
      3513131.49      10424047.3      3513133.31     10424003.75
      3513031.69     10423851.32      3513040.76     10423744.25
      3513029.87     10423620.86       3512959.1     10423343.21
      3512886.51     10423196.22      3512817.56     10423134.52
      3512721.23     10423120.33      3512641.37     10423148.97
      3512596.23     10423141.16      3512571.06      10423148.1
      3512548.49     10423190.64      3512522.45     10423189.77
      3512482.52     10423151.58      3512423.49     10423154.18
      3512394.84     10423139.42      3512381.82     10423106.44
      3512324.53      10423104.7      3512308.91     10423117.72
      3512196.93     10423091.68      3512185.64     10423059.56
       3512153.7     10423032.65      3512054.22     10423019.63
      3511988.07     10423044.11      3511924.01      10423011.3
      3511859.95     10423015.47      3511790.68     10422972.24
      3511733.91     10422957.13      3511682.64     10422916.64

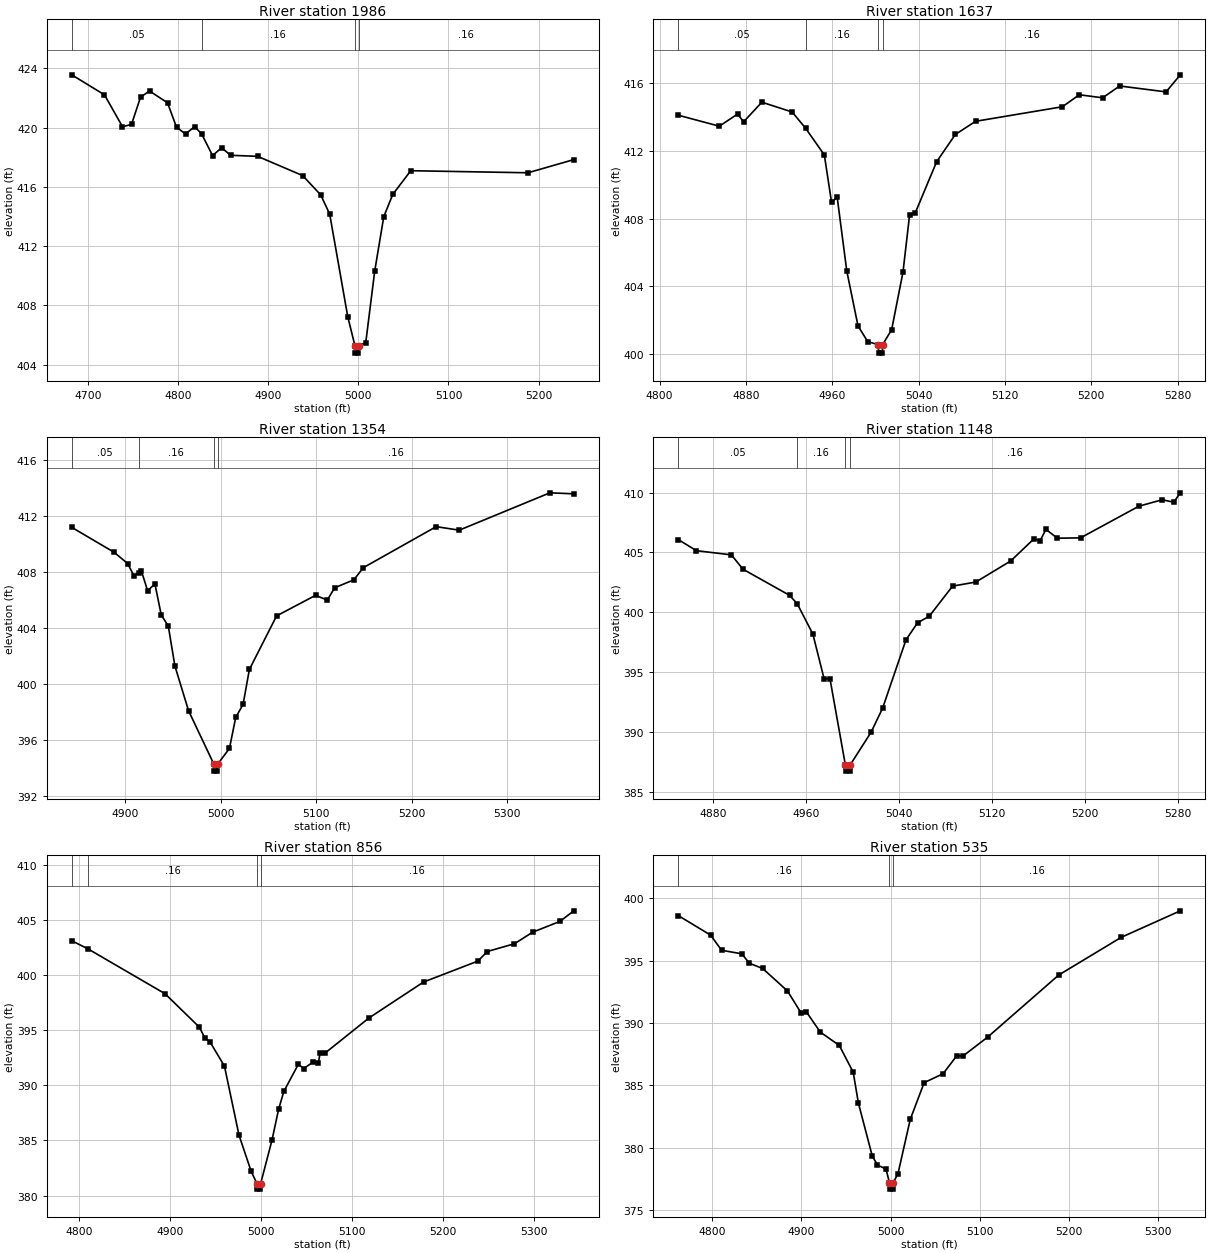
Type RM Length L Ch R = 1 ,1986    ,349,349,349
BEGIN DESCRIPTION:
UNT6083 IN DUCK CR 6 0
END DESCRIPTION:
XS GIS Cut Line= 2
      3513358.39     10423744.18      3512801.14     10423751.12
#Sta/Elev= 30
  4681.9  423.56  4718.2  422.21  4738.2  420.06  4748.2  420.21  4758.2  422.05
  4768.2  422.47  4788.2  421.67  4798.2  420.02  4808.2  419.57  4818.2  420.06
    4826  419.58  4838.2  418.11  4848.2  418.64  4858.2  418.13  4888.2  418.06
  4938.2  416.76  4958.2  415.46  4968.2  414.16  4988.2  407.25  4996.2  405.28
  4996.5  404.78    5000  404.78  5000.2  405.28  5008.2  405.48  5018.2  410.33
  5028.2  413.98  5038.2  415.49  5058.2  417.09  5188.2  416.95  5239.2  417.84
#Mann= 4 ,-1 , 0
  4681.9     .05       0    4826     .16       0  4996.2     .07       0
  5000.2     .16       0
Bank Sta=4996.2,5000.2
XS Rating Curve= 0 ,0
Exp/Cntr=0.3,0.1

Type RM Length L Ch R = 1 ,1637    ,283,283,283
BEGIN DESCRIPTION:
UNT6083 IN DUCK CR 5 0
END DESCRIPTION:
XS GIS Cut Line= 4
      3513144.73     10423441.74      3513038.37     10423389.64
      3512903.82     10423428.71      3512800.31     10423607.69
#Sta/Elev= 30
  4817.2  414.12  4855.3  413.47  4872.2  414.19  4877.8  413.73  4894.7  414.89
  4922.8  414.31  4935.2  413.35  4952.6  411.77  4959.3  408.96  4964.5  409.27
  4973.4   404.9  4983.8  401.65  4992.8  400.72  5002.6  400.54  5002.9  400.04
  5006.4  400.04  5006.6  400.54    5015  401.43  5025.5  404.84  5031.6  408.21
  5036.8  408.33  5056.7  411.37    5074  412.98  5092.8  413.76  5173.2  414.62
  5188.9  415.33  5210.5  415.15  5226.3  415.85  5269.3   415.5  5282.5  416.51
#Mann= 4 ,-1 , 0
  4817.2     .05       0  4935.2     .16       0  5002.6     .07       0
  5006.6     .16       0
Bank Sta=5002.6,5006.6
XS Rating Curve= 0 ,0
Exp/Cntr=0.3,0.1

Type RM Length L Ch R = 1 ,1354    ,206,206,206
BEGIN DESCRIPTION:
UNT6083 IN DUCK CR 3 0
END DESCRIPTION:
XS GIS Cut Line= 3
      3512947.22     10423044.59      3512788.81     10423231.22
      3512764.93     10423511.21
#Sta/Elev= 30
  4844.2   411.2  4888.5  409.42  4902.8  408.61  4909.3  407.73  4914.3  407.96
  4917.1  408.09  4923.6  406.67  4931.3  407.15  4937.9  404.94  4945.3  404.14
  4952.2  401.29  4966.5  398.09    4993  394.27  4993.3  393.77  4996.8  393.77
    4997  394.27  5009.3  395.39  5015.9  397.61  5023.6  398.54  5030.2  401.04
  5058.7  404.87  5099.5  406.34  5111.8     406  5119.5  406.88  5139.6  407.45
  5149.6  408.32  5225.8  411.25    5250     411  5344.9  413.67    5370   413.6
#Mann= 4 ,-1 , 0
  4844.2     .05       0  4914.3     .16       0    4993     .07       0
    4997     .16       0
Bank Sta=4993,4997
XS Rating Curve= 0 ,0
Exp/Cntr=0.3,0.1

Type RM Length L Ch R = 1 ,1148    ,292,292,292
BEGIN DESCRIPTION:
UNT6083 IN DUCK CR 4 0
END DESCRIPTION:
XS GIS Cut Line= 2
      3512649.92     10422986.03      3512673.76     10423417.27
#Sta/Elev= 30
  4849.9  406.08  4865.5  405.15  4895.6   404.8  4905.6   403.6  4945.7  401.42
  4952.3  400.71  4965.7  398.19  4975.4  394.44  4980.4  394.47  4993.7  387.24
    4994  386.74  4997.5  386.74  4997.7  387.24  5015.8  389.99  5025.8  392.02
  5045.8   397.7  5055.8  399.13  5065.8  399.67  5085.9  402.19  5105.9  402.53
  5135.9  404.29    5156  406.15  5161.1  405.96  5166.2  406.93    5176  406.19
    5196  406.22  5246.1  408.86  5266.1   409.4  5276.2   409.2  5281.8  409.98
#Mann= 4 ,-1 , 0
  4849.9     .05       0  4952.3     .16       0  4993.7     .07       0
  4997.7     .16       0
Bank Sta=4993.7,4997.7
XS Rating Curve= 0 ,0
Exp/Cntr=0.3,0.1

Type RM Length L Ch R = 1 ,856     ,321,321,321
BEGIN DESCRIPTION:
UNT6083 IN DUCK CR 2 1
END DESCRIPTION:
XS GIS Cut Line= 3
      3512517.54     10422968.63      3512385.16     10423209.52
      3512378.66     10423486.97
#Sta/Elev= 30
  4791.9  403.14  4809.8   402.4  4894.5  398.33  4932.3  395.29  4938.1  394.35
  4943.8  393.98  4959.9  391.75  4975.9  385.48  4989.3  382.19  4995.7  381.08
    4996  380.58  4999.5  380.58  4999.7  381.08  5012.1     385  5019.5  387.84
  5025.2  389.45  5041.3  391.94    5047  391.52  5057.4  392.13  5063.1  392.02
  5065.1  392.92  5070.3  392.92  5118.9  396.13  5178.9  399.39  5238.9   401.3
  5248.9  402.16    5279  402.87    5299  403.92    5329   404.9  5344.3  405.86
#Mann= 4 ,-1 , 0
  4791.9     .05       0  4809.8     .16       0  4995.7     .07       0
  4999.7     .16       0
Bank Sta=4995.7,4999.7
XS Rating Curve= 0 ,0
Exp/Cntr=0.3,0.1

Type RM Length L Ch R = 1 ,535     ,407,407,407
BEGIN DESCRIPTION:
UNT6083 IN DUCK CR 7 0
END DESCRIPTION:
XS GIS Cut Line= 3
      3512289.68     10422840.59      3512124.74     10423114.04
      3512131.22     10423357.91
#Sta/Elev= 30
  4761.8  398.63  4798.1  397.06  4810.5  395.84  4833.1  395.56  4841.6   394.8
  4856.5  394.38  4884.3  392.58  4899.8  390.79  4905.7  390.88  4921.2  389.27
  4942.5   388.2  4958.1  386.05  4963.9  383.58  4979.4  379.34  4985.3  378.59
  4994.9  378.28  4998.8  377.16    4999  376.66  5002.5  376.66  5002.8  377.16
  5008.3  377.89  5022.1  382.26  5037.7  385.21    5059  385.93  5074.5  387.39
  5081.1  387.34  5108.8  388.86  5188.8  393.86  5258.8  396.88  5325.1  399.01
#Mann= 3 ,-1 , 0
  4761.8     .16       0  4998.8     .07       0  5002.8     .16       0
Bank Sta=4998.8,5002.8
XS Rating Curve= 0 ,0
Exp/Cntr=0.3,0.1

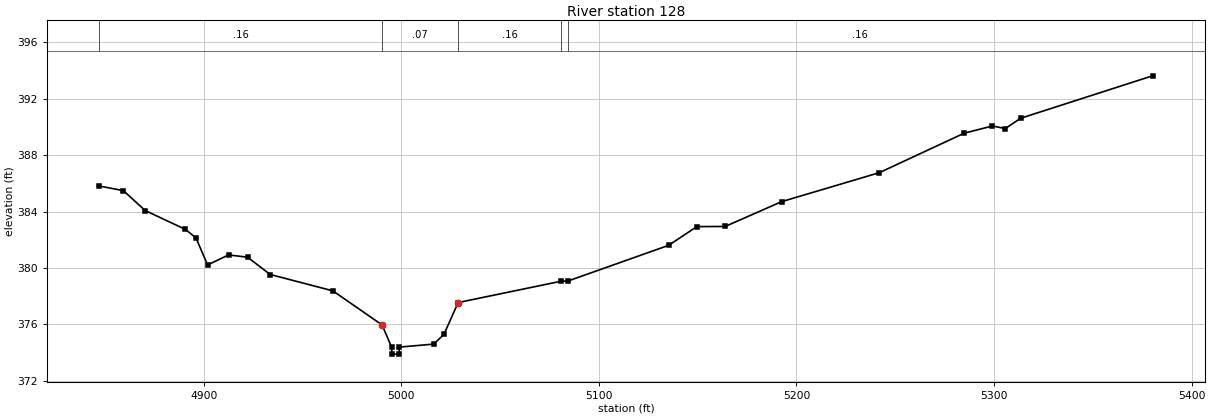
Type RM Length L Ch R = 1 ,128     ,0,0,0
BEGIN DESCRIPTION:
UNT6083 IN DUCK CR 1 0
END DESCRIPTION:
XS GIS Cut Line= 3
      3511842.63     10422829.72      3511766.67     10423053.27
      3511957.37     10423280.82
#Sta/Elev= 30
  4847.2  385.81  4859.4  385.48  4870.4  384.07  4890.8  382.73  4896.1  382.13
    4902  380.21  4912.6  380.92  4922.2  380.76  4933.7  379.53  4965.4  378.37
  4990.3  375.95  4995.1  374.38  4995.3  373.88  4998.8  373.88  4999.1  374.38
  5016.4  374.59  5021.6  375.28  5028.8  377.54  5080.8  379.05  5084.4  379.07
  5135.3   381.6  5149.6  382.93  5163.9  382.94  5192.5   384.7    5242  386.76
  5284.9  389.56  5299.2  390.07  5305.7  389.89  5313.5  390.62  5380.2  393.63
#Mann= 5 ,-1 , 0
  4847.2     .16       0  4990.3     .07       0  5028.8     .16       0
  5080.8     .12       0  5084.4     .16       0
Bank Sta=4990.3,5028.8
XS Rating Curve= 0 ,0
Exp/Cntr=0.3,0.1

Chan Stop Cuts=-1
Use User Specified Reach Order=0
Composite Channel Slope=5