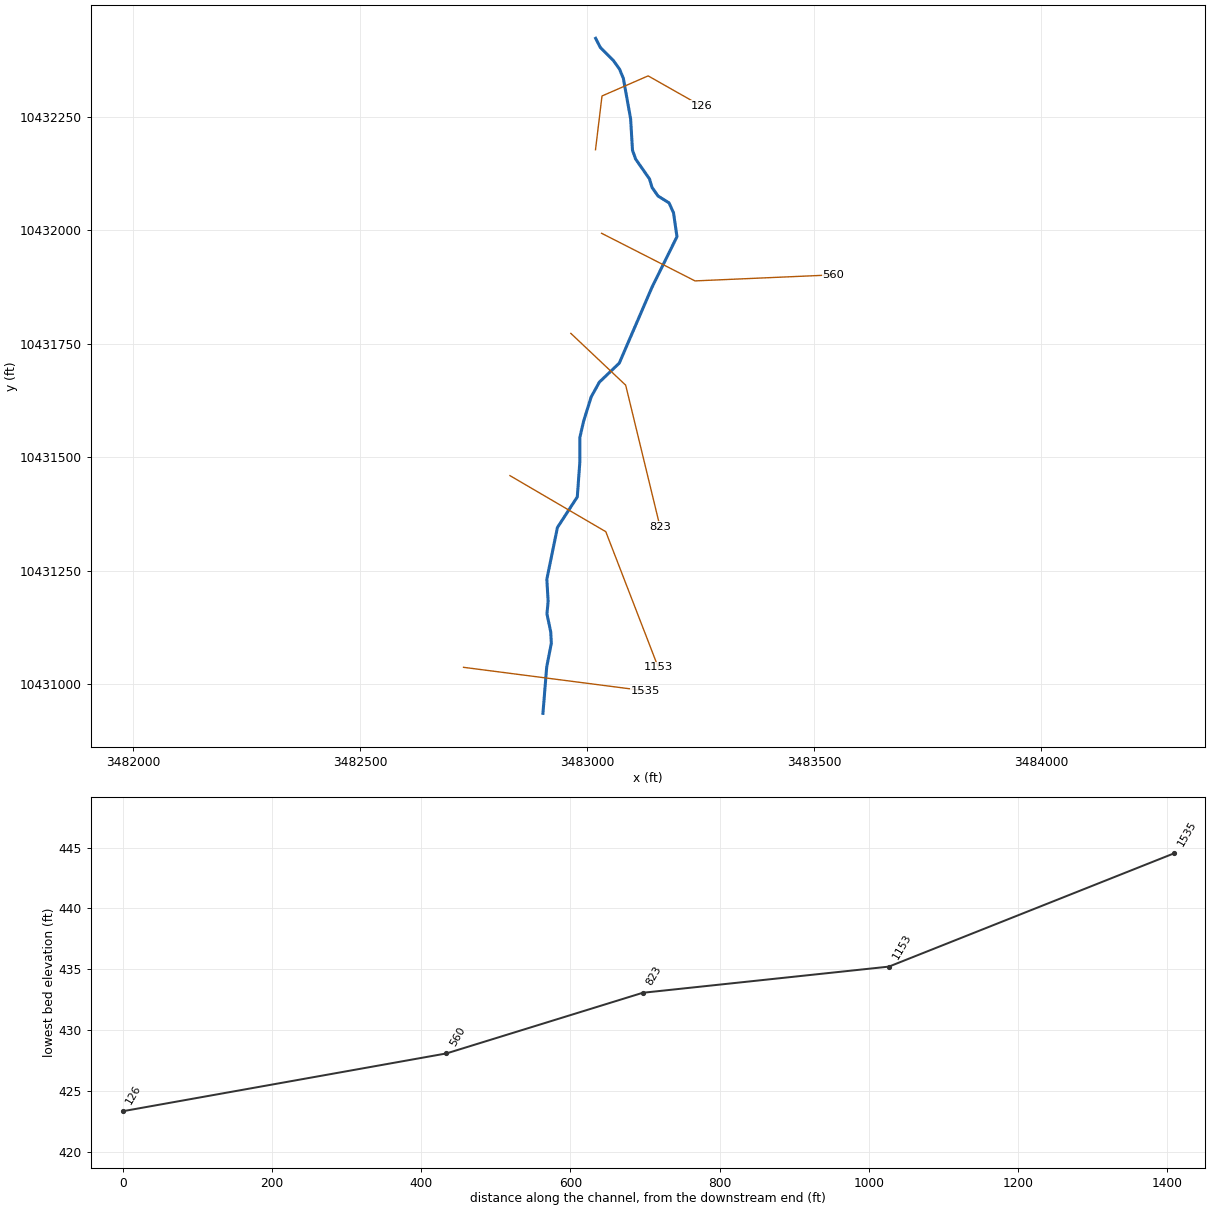
--- UNT6325 IN DUCK CR.prj (project) ---

Proj Title=UNT6325 IN DUCK CR Base Level Engineering
Current Plan=p01
Default Exp/Contr=0.3,0.1
English Units
Geom File=g01
Flow File=f01
Plan File=p01
BEGIN DESCRIPTION:
UNT6325 IN DUCK CR
END DESCRIPTION:

--- UNT6325 IN DUCK CR.p01 (plan) ---

Plan Title=Multiple Run
Short Identifier=Multiple
Geom File=g01
Flow File=f01
Subcritical Flow
K Sum by GR= 0
Std Step Tol= 0.01
Critical Tol= 0.01
Num of Std Step Trials= 20
Max Error Tol= 0.3
Flow Tol Ratio= 0.001
Split Flow NTrial= 30
Split Flow Tol= 0.02
Split Flow Ratio= 0.02
Log Output Level= 0
Friction Slope Method= 1
Unsteady Friction Slope Method= 2
Unsteady Bridges Friction Slope Method= 1
Parabolic Critical Depth
Global Vel Dist=  1 , 1 , 1
Global Log Level= 0
CheckData=True
Encroach Param= -1, 0, 0, 0
BEGIN DESCRIPTION:
Multiple Run
END DESCRIPTION:

--- UNT6325 IN DUCK CR.f01 (steady flow) ---

Flow Title=Multiple
Number of Profiles=7
Profile Names=10-year,25-year,50-year,1pct_min,100-year,1pct_plu,500-year
River Rch & RM= UNT6325 IN DUCK ,Reach-1,1535
     176     218     248     209     282     382     361
Boundary for River Rch & Prof#=UNT6325 IN DUCK ,Reach-1,1
Up Type=0
Dn Type=3
Dn Slope=0.005
Boundary for River Rch & Prof#=UNT6325 IN DUCK ,Reach-1,2
Up Type=0
Dn Type=3
Dn Slope=0.005
Boundary for River Rch & Prof#=UNT6325 IN DUCK ,Reach-1,3
Up Type=0
Dn Type=3
Dn Slope=0.005
Boundary for River Rch & Prof#=UNT6325 IN DUCK ,Reach-1,4
Up Type=0
Dn Type=3
Dn Slope=0.005
Boundary for River Rch & Prof#=UNT6325 IN DUCK ,Reach-1,5
Up Type=0
Dn Type=3
Dn Slope=0.005
Boundary for River Rch & Prof#=UNT6325 IN DUCK ,Reach-1,6
Up Type=0
Dn Type=3
Dn Slope=0.005
Boundary for River Rch & Prof#=UNT6325 IN DUCK ,Reach-1,7
Up Type=0
Dn Type=3
Dn Slope=0.005

--- UNT6325 IN DUCK CR.g01 (geometry) ---

Geom Title=Existing Conditions

River Reach=UNT6325 IN DUCK ,Reach-1
Reach XY= 30
      3482902.50     10430936.40      3482910.83     10431038.74
      3482920.99     10431090.57      3482919.68     10431115.83
      3482911.35     10431155.41      3482913.96     10431183.01
      3482911.09     10431231.71      3482934.43     10431345.61
      3482978.18     10431412.97      3482983.73     10431489.36
      3482983.73     10431543.53      3482992.06     10431579.64
      3483008.73     10431633.11      3483026.79     10431665.75
      3483070.54     10431707.41      3483142.76     10431874.78
      3483197.62     10431985.89      3483189.98     10432038.66
      3483180.26     10432060.19      3483155.95     10432075.47
      3483142.76     10432094.22      3483137.20     10432112.97
      3483106.65     10432156.72      3483099.70     10432176.16
      3483095.54     10432245.61      3483079.57     10432334.50
      3483071.23     10432354.64      3483057.34     10432374.08
      3483028.87     10432402.55      3483018.52     10432422.62

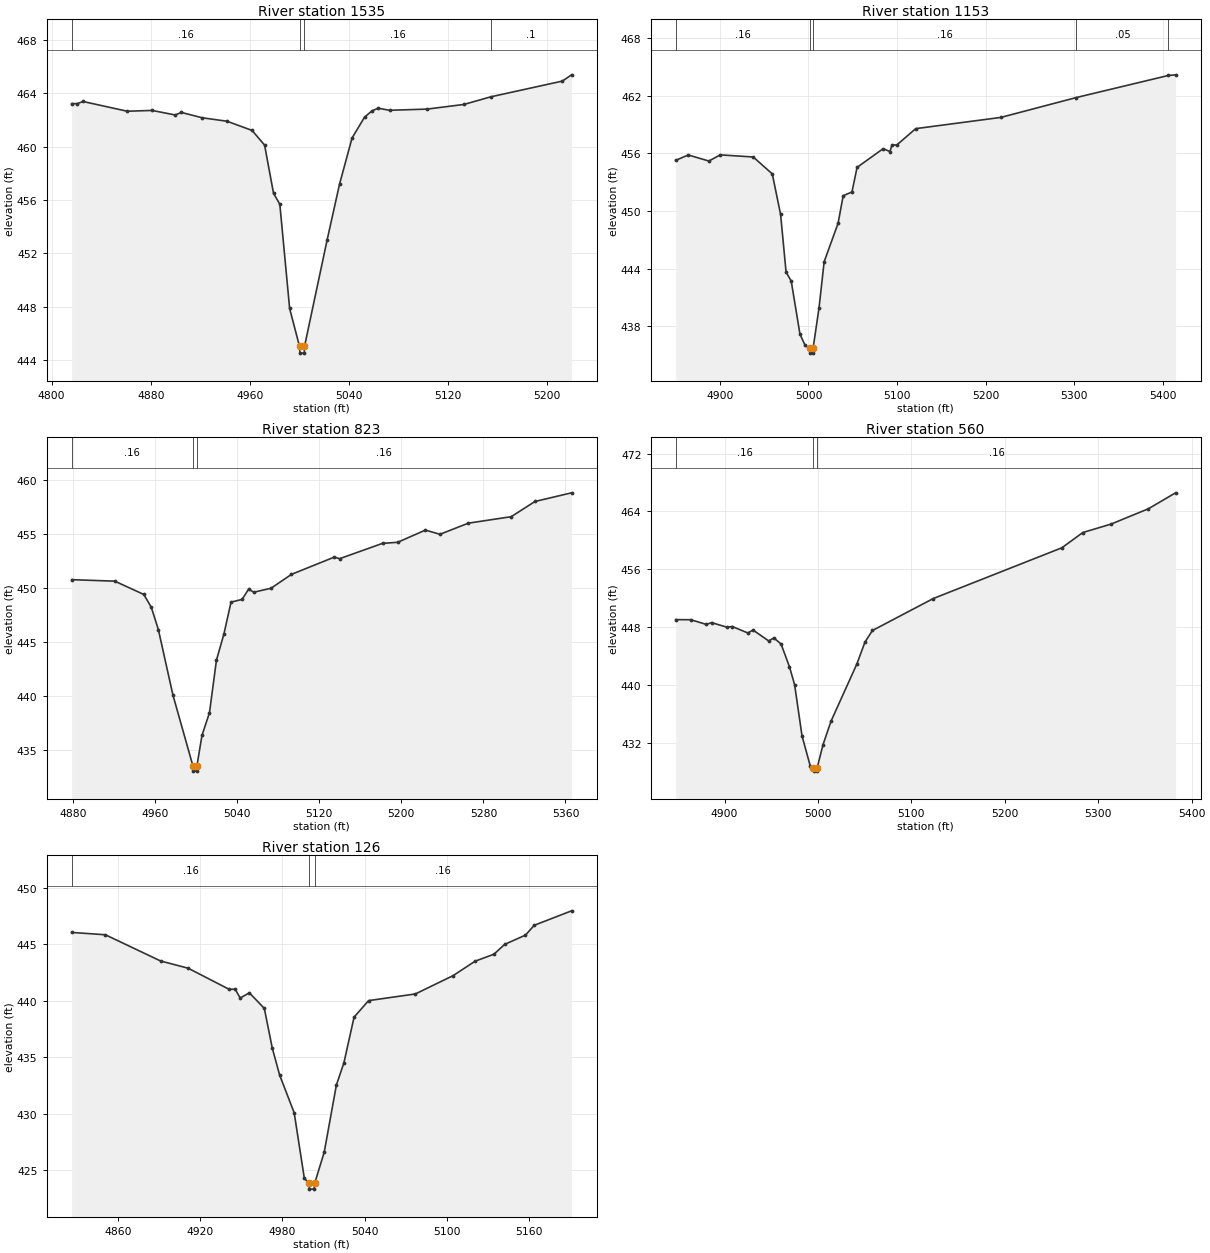
Type RM Length L Ch R = 1,1535,382,382,382
BEGIN DESCRIPTION:
UNT6325 IN DUCK CR 4 0
END DESCRIPTION:
XS GIS Cut Line= 2
      3482727.69     10431037.79      3483127.77     10430986.12
#Sta/Elev= 30
  4816.2  463.23  4820.7  463.23  4825.4  463.39  4861.0  462.66  4881.1  462.72
  4899.7  462.38  4904.8  462.57  4921.5  462.17  4941.6  461.91  4961.8  461.22
  4971.9  460.12  4979.1  456.51  4984.2  455.68  4992.1  447.87  5000.1  445.02
  5000.4  444.52  5003.9  444.52  5004.1  445.02  5022.3  452.98  5032.4  457.20
  5042.5  460.66  5052.6  462.22  5058.5  462.68  5063.5  462.89  5072.7  462.73
  5103.0  462.82  5132.8  463.17  5154.4  463.74  5212.2  464.92  5219.6  465.39
#Mann=4,-1,0
  4816.2    0.16       0  5000.1    0.07       0  5004.1    0.16       0
  5154.4     0.1       0
Bank Sta=5000.1,5004.1
Exp/Cntr=0.3,0.1

Type RM Length L Ch R = 1,1153,330,330,330
BEGIN DESCRIPTION:
UNT6325 IN DUCK CR 5 0
END DESCRIPTION:
XS GIS Cut Line= 3
      3482829.86     10431459.88      3483040.92     10431336.42
      3483156.40     10431037.79
#Sta/Elev= 30
  4850.0  455.28  4864.2  455.84  4887.4  455.21  4900.4  455.85  4937.6  455.63
  4959.1  453.87  4968.5  449.65  4974.7  443.64  4980.5  442.72  4990.4  437.18
  4996.2  436.03  5001.2  435.72  5001.5  435.22  5005.0  435.22  5005.2  435.72
  5011.9  439.92  5017.7  444.73  5033.4  448.72  5039.2  451.60  5049.1  451.99
  5054.9  454.55  5084.3  456.49  5092.1  456.20  5094.3  456.88  5099.8  456.88
  5121.1  458.58  5217.4  459.75  5302.7  461.82  5406.4  464.11  5414.7  464.18
#Mann=5,-1,0
  4850.0    0.16       0  5001.2    0.07       0  5005.2    0.16       0
  5302.7    0.05       0  5406.4     0.1       0
Bank Sta=5001.2,5005.2
Exp/Cntr=0.3,0.1

Type RM Length L Ch R = 1,823,263,263,263
BEGIN DESCRIPTION:
UNT6325 IN DUCK CR 2 1
END DESCRIPTION:
XS GIS Cut Line= 3
      3482963.97     10431773.06      3483084.72     10431658.95
      3483160.38     10431347.03
#Sta/Elev= 30
  4878.8  450.80  4920.8  450.66  4949.1  449.43  4956.4  448.24  4963.3  446.17
  4977.5  440.11  4996.9  433.57  4997.2  433.07  5000.7  433.07  5000.9  433.57
  5005.8  436.38  5013.1  438.48  5019.9  443.35  5027.2  445.78  5034.1  448.72
  5044.9  448.97  5051.2  449.92  5056.3  449.64  5073.0  450.00  5093.0  451.29
  5134.8  452.89  5139.9  452.74  5181.7  454.16  5196.5  454.26  5223.5  455.39
  5237.7  455.00  5265.3  456.03  5307.1  456.63  5330.3  458.04  5365.9  458.84
#Mann=3,-1,0
  4878.8    0.16       0  4996.9    0.07       0  5000.9    0.16       0
Bank Sta=4996.9,5000.9
Exp/Cntr=0.3,0.1

Type RM Length L Ch R = 1,560,434,434,434
BEGIN DESCRIPTION:
UNT6325 IN DUCK CR 3 0
END DESCRIPTION:
XS GIS Cut Line= 3
      3483031.64     10431993.42      3483237.36     10431888.57
      3483541.27     10431901.84
#Sta/Elev= 30
  4847.7  449.04  4863.8  449.03  4880.5  448.38  4886.1  448.63  4902.7  447.99
  4908.3  448.09  4924.9  447.20  4930.5  447.60  4947.2  446.10  4952.8  446.51
  4960.5  445.67  4969.4  442.55  4975.0  440.04  4982.9  432.97  4991.6  428.86
  4995.2  428.59  4995.5  428.09  4999.0  428.09  4999.2  428.59  5005.4  431.74
  5013.9  434.98  5041.7  442.93  5050.3  445.94  5058.3  447.54  5123.4  451.96
  5261.1  458.98  5283.5  461.09  5313.6  462.25  5353.6  464.37  5382.8  466.58
#Mann=3,-1,0
  4847.7    0.16       0  4995.2    0.07       0  4999.2    0.16       0
Bank Sta=4995.2,4999.2
Exp/Cntr=0.3,0.1

Type RM Length L Ch R = 1,126,0,0,0
BEGIN DESCRIPTION:
UNT6325 IN DUCK CR 1 0
END DESCRIPTION:
XS GIS Cut Line= 4
      3483018.25     10432177.25      3483032.57     10432295.70
      3483134.13     10432339.97      3483251.31     10432273.57
#Sta/Elev= 30
  4826.2  446.07  4850.8  445.86  4891.1  443.54  4911.2  442.90  4941.0  441.04
  4945.5  441.04  4949.2  440.26  4955.9  440.72  4966.8  439.34  4972.6  435.83
  4978.0  433.43  4988.6  430.10  4996.0  424.30  4999.5  423.84  4999.7  423.34
  5003.2  423.34  5003.5  423.84  5010.5  426.60  5019.4  432.56  5024.9  434.53
  5032.3  438.57  5042.9  440.03  5077.0  440.62  5104.7  442.25  5120.6  443.52
  5134.4  444.14  5142.2  445.01  5157.4  445.83  5163.8  446.70  5191.0  447.98
#Mann=3,-1,0
  4826.2    0.16       0  4999.5    0.07       0  5003.5    0.16       0
Bank Sta=4999.5,5003.5
Exp/Cntr=0.3,0.1

Chan Stop Cuts=-1