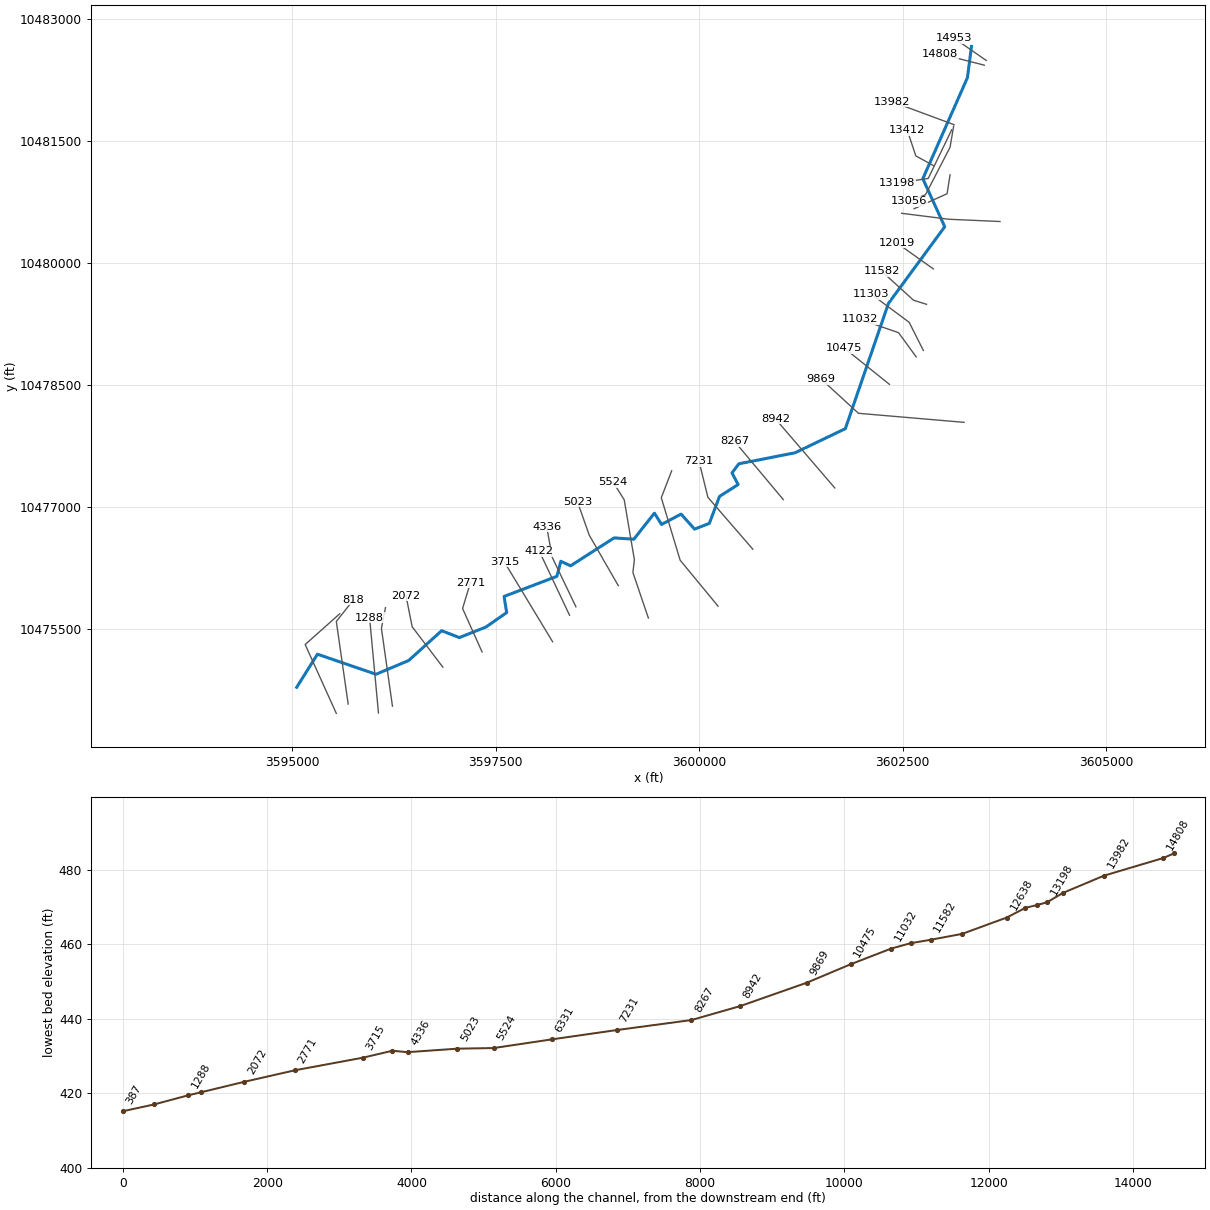
--- YELLOW BRANCH.prj (project) ---

Proj Title=YELLOW BRANCH Base Level Engineering
Current Plan=p01
Default Exp/Contr=0.3,0.1
English Units
Geom File=g01
Flow File=f01
Plan File=p01
Y Axis Title=Elevation
X Axis Title(PF)=Main Channel Distance
X Axis Title(XS)=Station
BEGIN DESCRIPTION:
YELLOW BRANCH
END DESCRIPTION:
DSS Export Rating Curves= 0
DSS Export Rating Curve Sorted= 0
DSS Export Volume Flow Curves= 0
DXF OffsetX= 0
DXF OffsetY= 0
DXF ScaleX= 1
DXF ScaleY= 10

--- YELLOW BRANCH.p01 (plan) ---

Plan Title=Multiple Run
Short Identifier=Multiple
Geom File=g01
Flow File=f01
Subcritical Flow
K Sum by GR= 0
Std Step Tol= 0.01
Critical Tol= 0.01
Num of Std Step Trials= 20
Max Error Tol= 0.3
Flow Tol Ratio= 0.001
Split Flow NTrial= 30
Split Flow Tol= 0.02
Split Flow Ratio= 0.02
Log Output Level= 0
Friction Slope Method= 1
Unsteady Friction Slope Method= 2
Unsteady Bridges Friction Slope Method= 1
Parabolic Critical Depth
Global Vel Dist=  1 , 1 , 1
Global Log Level= 0
CheckData=True
Encroach Param= -1, 0, 0, 0
BEGIN DESCRIPTION:
Multiple Run
END DESCRIPTION:

--- YELLOW BRANCH.f01 (steady flow) ---

Flow Title=Multiple
Program Version=4.10
Number of Profiles= 7
Profile Names=10-year,25-year,50-year,1pct_min,100-year,1pct_plu,500-year
River Rch & RM=YELLOW BRANCH,Reach-1         ,14953
     628     841    1013     892    1206    1631    1703
River Rch & RM=YELLOW BRANCH,Reach-1         ,14808
     628     841    1013     892    1206    1631    1703
River Rch & RM=YELLOW BRANCH,Reach-1         ,11303
    1619    2292    2863    2607    3525    4768    5331
River Rch & RM=YELLOW BRANCH,Reach-1         ,2771
    1781    2529    3165    2885    3902    5277    5919
Boundary for River Rch & Prof#=YELLOW BRANCH,Reach-1         , 1
Up Type= 0
Dn Type= 3
Dn Slope=0.005
Boundary for River Rch & Prof#=YELLOW BRANCH,Reach-1         , 2
Up Type= 0
Dn Type= 3
Dn Slope=0.005
Boundary for River Rch & Prof#=YELLOW BRANCH,Reach-1         , 3
Up Type= 0
Dn Type= 3
Dn Slope=0.005
Boundary for River Rch & Prof#=YELLOW BRANCH,Reach-1         , 4
Up Type= 0
Dn Type= 3
Dn Slope=0.005
Boundary for River Rch & Prof#=YELLOW BRANCH,Reach-1         , 5
Up Type= 0
Dn Type= 3
Dn Slope=0.005
Boundary for River Rch & Prof#=YELLOW BRANCH,Reach-1         , 6
Up Type= 0
Dn Type= 3
Dn Slope=0.005
Boundary for River Rch & Prof#=YELLOW BRANCH,Reach-1         , 7
Up Type= 0
Dn Type= 3
Dn Slope=0.005
DSS Import GetInterval= 0
DSS Import GetPeak= 0
DSS Import FillOption= 0

--- YELLOW BRANCH.g01 (geometry) ---

Geom Title=Existing Conditions
Program Version=4.10

River Reach=YELLOW BRANCH   ,Reach-1
Reach XY= 30
      3603346.76     10482659.26       3603297.4     10482276.06
      3602748.83     10481033.18       3603018.2     10480442.97
      3602325.91     10479500.43      3601796.75     10477960.98
      3601176.41     10477663.77       3600486.5     10477528.86
      3600402.96     10477416.55      3600478.66     10477273.86
        3600250.     10477128.74      3600124.61     10476796.93
       3599943.3     10476725.87      3599777.17     10476910.75
      3599536.88     10476783.37      3599449.69     10476922.26
      3599195.87     10476601.78      3598953.74     10476618.18
       3598418.7     10476275.04      3598298.91     10476330.77
      3598249.95     10476145.35      3597601.51     10475898.48
      3597633.81     10475700.04      3597377.03     10475521.81
      3597051.75     10475392.78      3596833.62     10475477.39
      3596428.99     10475111.03      3596027.27     10474941.97
      3595307.14     10475188.51      3595052.11     10474781.64

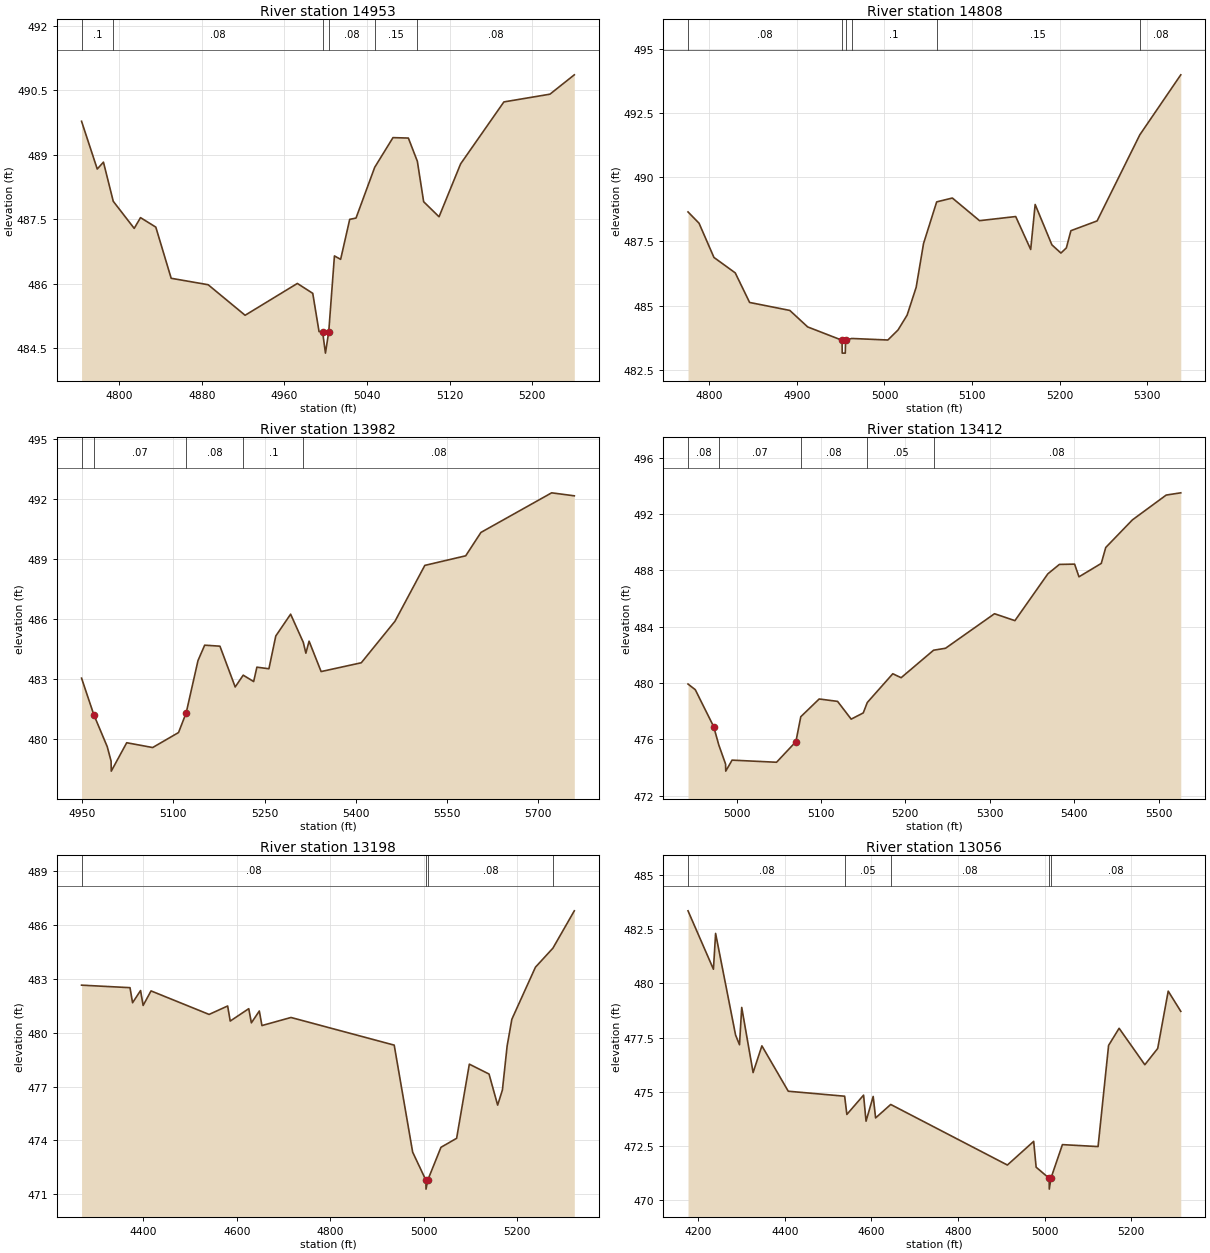
Type RM Length L Ch R = 1 ,14953   ,145,145,145
BEGIN DESCRIPTION:
YELLOW BRANCH 7 0
END DESCRIPTION:
XS GIS Cut Line= 2
      3603528.25     10482487.09      3603136.05     10482758.94
#Sta/Elev= 30
  4763.6  489.78  4778.8  488.67  4784.8  488.83  4794.3  487.92  4814.6  487.29
  4820.7  487.54  4835.5  487.32  4850.4  486.13  4886.2  485.98    4922  485.27
  4972.6  486.01  4987.5  485.78  4993.6  484.89    4997  484.89  4999.8  484.39
    5003  484.89  5008.5  486.65  5014.5  486.57  5023.3   487.5  5029.4  487.53
  5047.5  488.71  5065.2   489.4  5080.1  489.39  5088.8  488.85  5094.9  487.91
  5109.8  487.56  5130.7  488.79  5172.6  490.23  5217.2  490.41  5240.8  490.86
#Mann= 6 ,-1 , 0
  4763.6      .1       0  4794.3     .08       0    4997     .07       0
    5003     .08       0  5047.5     .15       0  5088.8     .08       0
Bank Sta=4997,5003
XS Rating Curve= 0 ,0
Exp/Cntr=0.3,0.1

Type RM Length L Ch R = 1 ,14808   ,826,826,826
BEGIN DESCRIPTION:
YELLOW BRANCH 7 0
END DESCRIPTION:
XS GIS Cut Line= 2
      3603504.31     10482428.91       3602959.6     10482568.89
#Sta/Elev= 30
  4775.8  488.65  4788.4  488.21  4805.4  486.88  4829.7  486.28  4846.1  485.13
    4892  484.82  4912.3  484.18  4951.6  483.66  4951.8  483.16  4955.3  483.16
  4955.6  483.66  4962.7  483.73  5003.9  483.67  5015.5  484.06  5025.9  484.64
  5036.2  485.72  5044.6  487.42  5059.6  489.04  5077.5  489.19  5108.5  488.31
  5149.8  488.47  5166.9  487.19    5172  488.94  5191.1  487.37  5201.4  487.05
  5207.6  487.25  5212.8  487.92  5242.7   488.3  5291.5  491.65  5338.2  493.98
#Mann= 6 ,-1 , 0
  4775.8     .08       0  4951.6     .07       0  4955.6     .08       0
  4962.7      .1       0  5059.6     .15       0  5291.5     .08       0
Bank Sta=4951.6,4955.6
XS Rating Curve= 0 ,0
Exp/Cntr=0.3,0.1

Type RM Length L Ch R = 1 ,13982   ,570,570,570
BEGIN DESCRIPTION:
YELLOW BRANCH 4 0
END DESCRIPTION:
XS GIS Cut Line= 2
      3603131.82     10481698.07      3602371.36     10481979.33
#Sta/Elev= 30
  4948.9  483.05  4969.1  481.22  4991.2  479.62  4997.5   478.9  4997.8   478.4
  5023.2  479.82  5065.9  479.58  5108.5  480.33  5121.1  481.32  5140.5  483.93
  5151.5   484.7  5176.6  484.65  5201.7  482.61  5214.9   483.2  5232.1  482.88
  5237.4   483.6  5257.2  483.52  5268.5  485.16  5292.9  486.25  5313.8  484.84
    5318   484.3  5323.3   484.9  5343.1  483.38  5409.2  483.82  5464.7   485.9
  5513.7  488.69    5581  489.17  5606.1  490.34  5722.4  492.32  5759.7  492.17
#Mann= 5 ,-1 , 0
  4948.9     .08       0  4969.1     .07       0  5121.1     .08       0
  5214.9      .1       0  5313.8     .08       0
Bank Sta=4969.1,5121.1
XS Rating Curve= 0 ,0
Exp/Cntr=0.3,0.1

Type RM Length L Ch R = 1 ,13412   ,214,214,214
BEGIN DESCRIPTION:
YELLOW BRANCH 2 0
END DESCRIPTION:
XS GIS Cut Line= 3
      3602884.09     10481192.24      3602662.77     10481313.75
        3602558.     10481628.06
#Sta/Elev= 30
  4942.5  479.93  4951.1  479.53  4972.9  476.91    4979   475.6    4987  474.25
  4987.2  473.75  4994.7  474.53  5047.4  474.38  5070.3  475.84  5076.1  477.61
  5097.9  478.87  5119.7   478.7  5135.8  477.44  5150.1  477.88  5154.9  478.62
  5185.1  480.66    5195  480.38  5233.4  482.33  5247.6  482.47  5305.6  484.92
  5329.8  484.43  5368.8  487.75  5382.5  488.42  5400.5  488.44  5405.7  487.54
  5432.1  488.49  5437.4  489.62    5469  491.58    5509  493.34  5526.3   493.5
#Mann= 5 ,-1 , 0
  4942.5     .08       0    4979     .07       0  5076.1     .08       0
  5154.9     .05       0  5233.4     .08       0
Bank Sta=4972.9,5070.3
XS Rating Curve= 0 ,0
Exp/Cntr=0.3,0.1

Type RM Length L Ch R = 1 ,13198   ,142,142,142
BEGIN DESCRIPTION:
YELLOW BRANCH 31 0
END DESCRIPTION:
XS GIS Cut Line= 3
      3603104.29      10481635.6      3602815.22     10481036.62
      3602429.84     10480979.33
#Sta/Elev= 30
  4267.8  482.65  4371.5  482.51    4377  481.67  4394.1  482.35  4399.6  481.52
  4416.5  482.33  4540.8  481.02  4580.5  481.49    4586  480.65  4625.7  481.34
  4631.3  480.55  4648.3  481.21  4653.9   480.4  4716.1  480.85    4937  479.31
  4976.5  473.35  5004.8  471.79  5005.1  471.29  5008.8  471.79  5037.1  473.62
  5070.6  474.12  5097.8  478.25    5140   477.7  5158.4  475.97  5168.6  476.81
  5178.7  479.26  5188.8  480.75  5239.3  483.65  5276.7  484.71  5322.5  486.79
#Mann= 4 ,-1 , 0
  4267.8     .08       0  5004.8     .07       0  5008.8     .08       0
  5276.7     .05       0
Bank Sta=5004.8,5008.8
XS Rating Curve= 0 ,0
Exp/Cntr=0.3,0.1

Type RM Length L Ch R = 1 ,13056   ,160,160,160
BEGIN DESCRIPTION:
Mapping XS b3e8a437
END DESCRIPTION:
XS GIS Cut Line= 4
      3603127.72     10481679.86      3603083.45     10481419.43
      3602781.37      10480836.1      3602579.87     10480756.02
#Sta/Elev= 30
  4176.6  483.34  4235.3  480.65  4240.3   482.3  4286.4  477.62  4295.5  477.17
  4300.6  478.89  4326.9  475.89  4347.2  477.12  4408.1  475.03  4538.3   474.8
  4543.4  473.96    4582  474.85  4587.7  473.65  4604.2  474.79  4609.8   473.8
  4644.7  474.42  4914.1  471.63  4974.8  472.72  4980.5  471.53  5010.6  471.02
  5010.9  470.52  5014.6  471.02  5041.2  472.57  5123.5  472.48  5147.8  477.14
  5172.1  477.93  5231.5  476.25  5261.2     477  5285.5  479.64  5314.5  478.71
#Mann= 5 ,-1 , 0
  4176.6     .08       0  4538.3     .05       0  4644.7     .08       0
  5010.6     .07       0  5014.6     .08       0
Bank Sta=5010.6,5014.6
XS Rating Curve= 0 ,0
Exp/Cntr=0.3,0.1

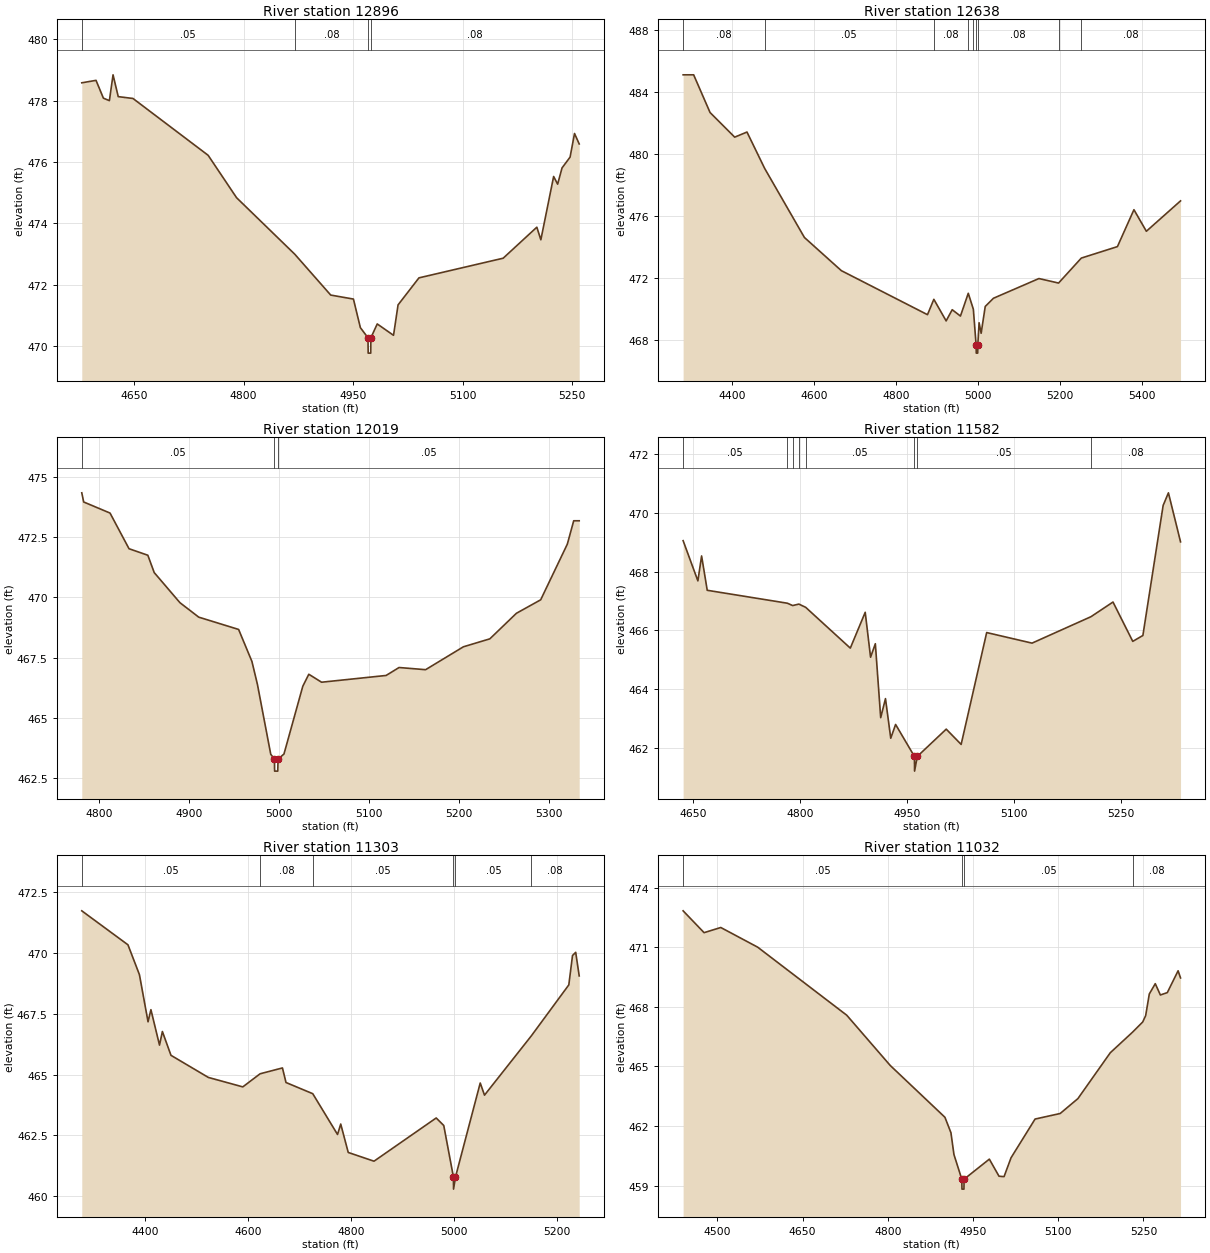
Type RM Length L Ch R = 1 ,12896   ,258,258,258
BEGIN DESCRIPTION:
YELLOW BRANCH 5 0
END DESCRIPTION:
XS GIS Cut Line= 3
      3603083.45     10481080.92      3603046.99     10480849.12
      3602640.74     10480664.22
#Sta/Elev= 30
  4578.4  478.58  4597.9  478.66    4608  478.08  4616.2     478  4621.2  478.84
  4628.3  478.13  4648.5  478.07  4751.4  476.22  4790.3  474.84    4870     473
  4919.2  471.67  4950.3  471.54  4959.8  470.61  4970.2  470.28  4970.5  469.78
    4974  469.78  4974.2  470.28  4982.9  470.73  5005.2  470.36  5011.4  471.35
    5040  472.23  5155.3  472.87  5201.4  473.88  5206.9  473.47  5224.4  475.53
  5229.9  475.28  5235.9  475.81  5246.9  476.16    5253  476.93  5259.4  476.59
#Mann= 4 ,-1 , 0
  4578.4     .05       0    4870     .08       0  4970.2     .07       0
  4974.2     .08       0
Bank Sta=4970.2,4974.2
XS Rating Curve= 0 ,0
Exp/Cntr=0.3,0.1

Type RM Length L Ch R = 1 ,12638   ,619,619,619
BEGIN DESCRIPTION:
YELLOW BRANCH 3 0
END DESCRIPTION:
XS GIS Cut Line= 3
      3603697.74     10480507.24      3603069.23     10480535.02
      3602489.32     10480607.95
#Sta/Elev= 30
  4280.4  485.13  4306.1  485.13  4346.1   482.7  4406.2  481.11  4436.2  481.44
  4479.4  479.09  4576.3  474.64  4666.4   472.5  4876.6  469.66  4892.1  470.65
  4922.1  469.26  4936.9  469.98    4957  469.57  4976.1  471.04  4988.5  470.01
  4995.3  467.68  4995.6  467.18  4999.1  467.18  4999.3  467.68  5002.5  469.14
  5007.5  468.46  5017.5  470.19  5037.6  470.72  5148.5  471.99  5196.4   471.7
  5251.9  473.31    5340  474.05  5380.3  476.43  5410.6  475.04    5494     477
#Mann= 9 ,-1 , 0
  4280.4     .08       0  4479.4     .05       0  4892.1     .08       0
  4976.1     .05       0  4988.5     .08       0  4995.3     .07       0
  4999.3     .08       0  5196.4     .05       0  5251.9     .08       0
Bank Sta=4995.3,4999.3
XS Rating Curve= 0 ,0
Exp/Cntr=0.3,0.1

Type RM Length L Ch R = 1 ,12019   ,437,437,437
BEGIN DESCRIPTION:
YELLOW BRANCH 25 1
END DESCRIPTION:
XS GIS Cut Line= 2
      3602877.73     10479924.63       3602427.2     10480244.95
#Sta/Elev= 30
  4780.4  474.34  4782.5  473.96  4811.8   473.5  4832.9  472.02  4853.8  471.75
  4860.9  471.03  4889.5  469.78  4910.4  469.18  4954.7  468.67  4969.5  467.34
  4975.6  466.39  4990.4  463.49  4994.5  463.29  4994.7  462.79  4998.2  462.79
  4998.5  463.29  5005.1   463.5    5026  466.31  5032.7  466.81  5046.9  466.48
  5118.6  466.76    5133  467.09  5162.5     467  5204.5  467.95  5233.9  468.28
  5263.4  469.34  5290.4   469.9    5320  472.21  5327.1  473.18  5333.2  473.18
#Mann= 3 ,-1 , 0
  4780.4     .05       0  4994.5     .03       0  4998.5     .05       0
Bank Sta=4994.5,4998.5
XS Rating Curve= 0 ,0
Exp/Cntr=0.3,0.1

Type RM Length L Ch R = 1 ,11582   ,279,279,279
BEGIN DESCRIPTION:
YELLOW BRANCH 28 0
END DESCRIPTION:
XS GIS Cut Line= 3
      3602794.41     10479489.74      3602635.53     10479539.22
      3602242.27     10479896.02
#Sta/Elev= 30
  4636.4  469.05  4657.1  467.68  4662.3  468.53  4670.2  467.36  4782.5  466.92
    4790  466.84  4798.7  466.89  4808.2  466.78  4870.8  465.39  4891.7  466.61
  4899.2  465.08  4905.9  465.54  4913.4  463.02  4920.1  463.67  4927.5  462.32
  4934.3  462.79  4960.7   461.7  4960.9   461.2  4964.7   461.7  5005.3  462.63
  5026.2  462.11    5062  465.92  5125.6  465.56  5208.2  466.46  5239.1  466.96
  5266.8  465.62    5281  465.82  5309.4  470.25  5316.8  470.68  5333.8  469.01
#Mann= 8 ,-1 , 0
  4636.4     .05       0  4782.5     .08       0    4790     .05       0
  4798.7     .08       0  4808.2     .05       0  4960.7     .03       0
  4964.7     .05       0  5208.2     .08       0
Bank Sta=4960.7,4964.7
XS Rating Curve= 0 ,0
Exp/Cntr=0.3,0.1

Type RM Length L Ch R = 1 ,11303   ,271,271,271
BEGIN DESCRIPTION:
YELLOW BRANCH 25 0
END DESCRIPTION:
XS GIS Cut Line= 3
       3602755.3     10478922.08      3602580.84     10479268.39
      3602115.91     10479613.84
#Sta/Elev= 30
  4276.4  471.74  4366.2  470.34  4388.5  469.11  4405.2  467.17  4410.8  467.67
  4427.5  466.21  4433.1  466.77  4449.8  465.79  4522.4  464.88  4589.4  464.49
  4623.1  465.03  4666.5  465.27  4673.4  464.67  4725.4  464.21  4773.6  462.53
  4779.8  462.96  4794.4  461.79  4844.5  461.43  4965.4  463.21  4980.1   462.9
  4998.9  460.78  4999.1  460.28  5002.9  460.78    5051  464.65  5059.3  464.15
  5150.3  466.59  5223.2  468.69  5230.4   469.9  5236.6  470.03  5243.4  469.06
#Mann= 6 ,-1 , 0
  4276.4     .05       0  4623.1     .08       0  4725.4     .05       0
  4998.9     .03       0  5002.9     .05       0  5150.3     .08       0
Bank Sta=4998.9,5002.9
XS Rating Curve= 0 ,0
Exp/Cntr=0.3,0.1

Type RM Length L Ch R = 1 ,11032   ,557,557,557
BEGIN DESCRIPTION:
YELLOW BRANCH 27 0
END DESCRIPTION:
XS GIS Cut Line= 3
      3602666.77     10478843.93      3602450.64     10479140.79
      3601970.08     10479307.03
#Sta/Elev= 30
  4439.6  472.84  4476.5  471.74  4505.9     472  4570.8  471.01  4727.7  467.58
  4804.2  465.05  4900.5  462.44  4911.1  461.66  4916.4  460.56  4930.2  459.32
  4930.5  458.82    4934  458.82  4934.2  459.32  4978.7  460.33  4995.7  459.47
  5004.6  459.45  5016.9   460.4  5059.2  462.35  5103.4  462.63  5134.6  463.38
  5191.6  465.69  5230.9  466.73  5248.7  467.24  5253.9  467.56  5260.3  468.65
  5270.8  469.17  5279.8   468.6    5292  468.72    5311  469.82  5315.3  469.46
#Mann= 4 ,-1 , 0
  4439.6     .05       0  4930.2     .03       0  4934.2     .05       0
  5230.9     .08       0
Bank Sta=4930.2,4934.2
XS Rating Curve= 0 ,0
Exp/Cntr=0.3,0.1

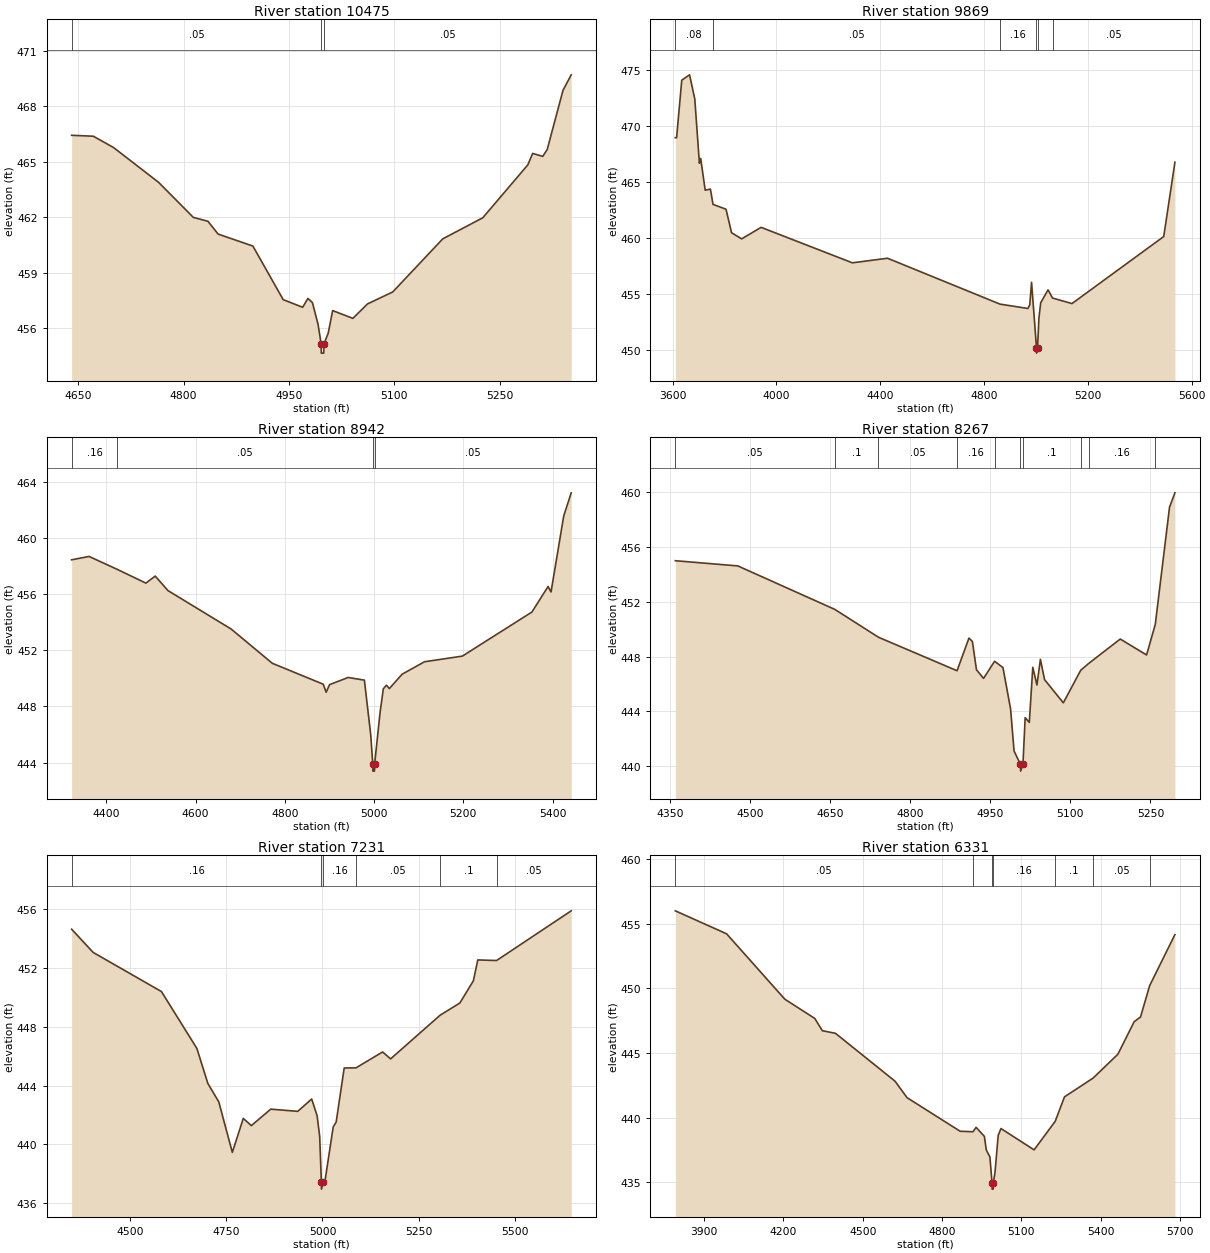
Type RM Length L Ch R = 1 ,10475   ,606,606,606
BEGIN DESCRIPTION:
YELLOW BRANCH 24 1
END DESCRIPTION:
XS GIS Cut Line= 2
      3602338.69     10478505.34      3601783.94      10478950.7
#Sta/Elev= 30
  4640.5  466.42  4671.4  466.37  4700.1  465.76  4764.2  463.88  4813.8  461.98
  4834.6  461.77    4849  461.08  4898.6  460.43  4941.8  457.53  4969.5  457.12
    4977   457.6  4983.4  457.37  4991.4   456.2  4995.8  455.14    4996  454.64
  4999.5  454.64  4999.8  455.14  5005.8  455.71  5012.2  456.94    5041  456.52
  5061.8   457.3  5097.8  457.95    5169  460.82    5226  461.96  5290.1  464.82
    5297  465.44  5311.4  465.28  5317.8  465.66  5340.2  468.85  5351.9  469.69
#Mann= 3 ,-1 , 0
  4640.5     .05       0  4995.8     .03       0  4999.8     .05       0
Bank Sta=4995.8,4999.8
XS Rating Curve= 0 ,0
Exp/Cntr=0.3,0.1

Type RM Length L Ch R = 1 ,9869    ,927,927,927
BEGIN DESCRIPTION:
YELLOW BRANCH 24 0
END DESCRIPTION:
XS GIS Cut Line= 3
       3603256.7      10478038.5      3601958.12     10478149.61
      3601499.77     10478569.75
#Sta/Elev= 30
  3610.4  468.95  3615.2  468.95  3635.1  474.09  3665.2  474.57  3685.3  472.41
  3703.1  466.67  3708.1   467.1  3725.4  464.26  3745.5  464.36  3755.6  462.99
  3805.7  462.56    3827  460.46  3865.9  459.91  3940.9  460.94  4292.5  457.77
    4428  458.18  4861.4  454.08  4968.9  453.69  4976.1  454.01  4983.1  456.03
  5002.1   450.2  5002.3   449.7  5006.1   450.2  5011.5  452.84  5018.3   454.2
  5046.6  455.35    5064  454.62  5138.9  454.13  5492.5  460.12  5535.5  466.76
#Mann= 6 ,-1 , 0
  3610.4     .08       0  3755.6     .05       0  4861.4     .16       0
  5002.1     .07       0  5006.1     .16       0    5064     .05       0
Bank Sta=5002.1,5006.1
XS Rating Curve= 0 ,0
Exp/Cntr=0.3,0.1

Type RM Length L Ch R = 1 ,8942    ,675,675,675
BEGIN DESCRIPTION:
YELLOW BRANCH 22 0
END DESCRIPTION:
XS GIS Cut Line= 2
      3601666.75     10477231.97      3600937.59     10478080.91
#Sta/Elev= 30
  4322.5  458.44  4361.5  458.68  4424.6  457.76  4488.8  456.78  4509.7  457.28
  4538.2  456.25  4679.8  453.51    4772  451.07  4886.1  449.58  4892.7  449.01
  4900.3  449.55    4942  450.06  4978.3  449.87  4992.5  445.98  4997.1  443.89
  4997.3  443.39  5000.9  443.39  5001.2  443.89  5013.4  447.56  5020.7  449.25
  5027.6  449.51  5034.2  449.27  5062.8  450.29    5113  451.18  5197.7  451.58
  5353.6  454.72  5389.8  456.54  5396.4  456.15  5424.9  461.57  5441.6  463.21
#Mann= 4 ,-1 , 0
  4322.5     .16       0  4424.6     .05       0  4997.1     .03       0
  5001.2     .05       0
Bank Sta=4997.1,5001.2
XS Rating Curve= 0 ,0
Exp/Cntr=0.3,0.1

Type RM Length L Ch R = 1 ,8267    ,1036,1036,1036
BEGIN DESCRIPTION:
YELLOW BRANCH 21 0
END DESCRIPTION:
XS GIS Cut Line= 2
      3601033.96     10477088.71      3600432.77     10477807.02
#Sta/Elev= 30
  4359.3  454.99  4476.5  454.61  4658.4  451.44  4740.2  449.41  4887.5  446.97
  4909.8  449.35  4916.3   449.1  4923.9  447.04  4937.2  446.41  4957.9  447.66
  4973.6   447.2  4987.9  444.18  4994.4  441.12  5006.3  440.15  5006.7  439.65
  5011.1  440.15  5015.2  443.55    5023   443.2  5029.5  447.22  5037.3  445.93
  5043.8   447.8  5051.6  446.32  5086.8  444.63  5119.5  447.01  5135.3  447.53
  5193.5  449.28  5242.9  448.12  5259.2  450.35  5285.9  458.89    5296  459.94
#Mann= 10 ,-1 , 0
  4359.3     .05       0  4658.4      .1       0  4740.2     .05       0
  4887.5     .16       0  4957.9      .1       0  5006.3     .07       0
  5011.1      .1       0  5119.5     .05       0  5135.3     .16       0
  5259.2      .1       0
Bank Sta=5006.3,5011.1
XS Rating Curve= 0 ,0
Exp/Cntr=0.3,0.1

Type RM Length L Ch R = 1 ,7231    ,900,900,900
BEGIN DESCRIPTION:
YELLOW BRANCH 19 0
END DESCRIPTION:
XS GIS Cut Line= 3
      3600658.96     10476479.34      3600106.89     10477117.35
      3599997.92     10477558.39
#Sta/Elev= 30
  4348.3  454.64  4404.2  453.06  4581.6   450.4  4673.7  446.53  4702.2  444.15
  4730.7  442.89  4765.8  439.46  4794.3  441.77  4815.2  441.28  4865.6   442.4
  4935.8  442.25    4972  443.09  4986.1  441.95  4992.8  440.54  4997.1  437.46
  4997.4  436.96  5001.9  437.46  5007.1  437.61    5028   441.2  5035.6  441.52
  5056.5   445.2  5087.2  445.21  5156.2  446.29  5177.1  445.82  5305.7  448.79
    5357  449.62  5392.1  451.13  5403.6  452.55  5452.4  452.51  5646.3  455.89
#Mann= 6 ,-1 , 0
  4348.3     .16       0  4997.1     .07       0  5001.9     .16       0
  5087.2     .05       0  5305.7      .1       0  5452.4     .05       0
Bank Sta=4997.1,5001.9
XS Rating Curve= 0 ,0
Exp/Cntr=0.3,0.1

Type RM Length L Ch R = 1 ,6331    ,807,807,807
BEGIN DESCRIPTION:
YELLOW BRANCH 17 0
END DESCRIPTION:
XS GIS Cut Line= 4
       3600231.9     10475778.78      3599765.74     10476343.91
      3599533.97     10477112.14      3599661.57     10477442.87
#Sta/Elev= 30
  3791.3     456  3985.2  454.22  4205.4  449.16  4318.7  447.67  4347.4  446.72
  4396.9  446.52  4621.9  442.82  4667.7  441.54  4868.4  438.94  4916.9   438.9
  4928.9  439.24  4960.2  438.54  4967.3   437.5  4981.1  436.95    4989  434.96
  4989.4  434.46  4993.6  434.46    4994  434.96  5000.3  435.75  5012.4  438.62
  5022.9  439.15  5148.2   437.5  5228.1  439.71  5263.1   441.6  5371.7  443.06
  5465.1   444.9  5526.8  447.42  5550.9  447.79  5585.3  450.21  5680.8  454.16
#Mann= 7 ,-1 , 0
  3791.3     .05       0  4916.9     .16       0    4989     .07       0
    4994     .16       0  5228.1      .1       0  5371.7     .05       0
  5585.3      .1       0
Bank Sta=4989,4994
XS Rating Curve= 0 ,0
Exp/Cntr=0.3,0.1

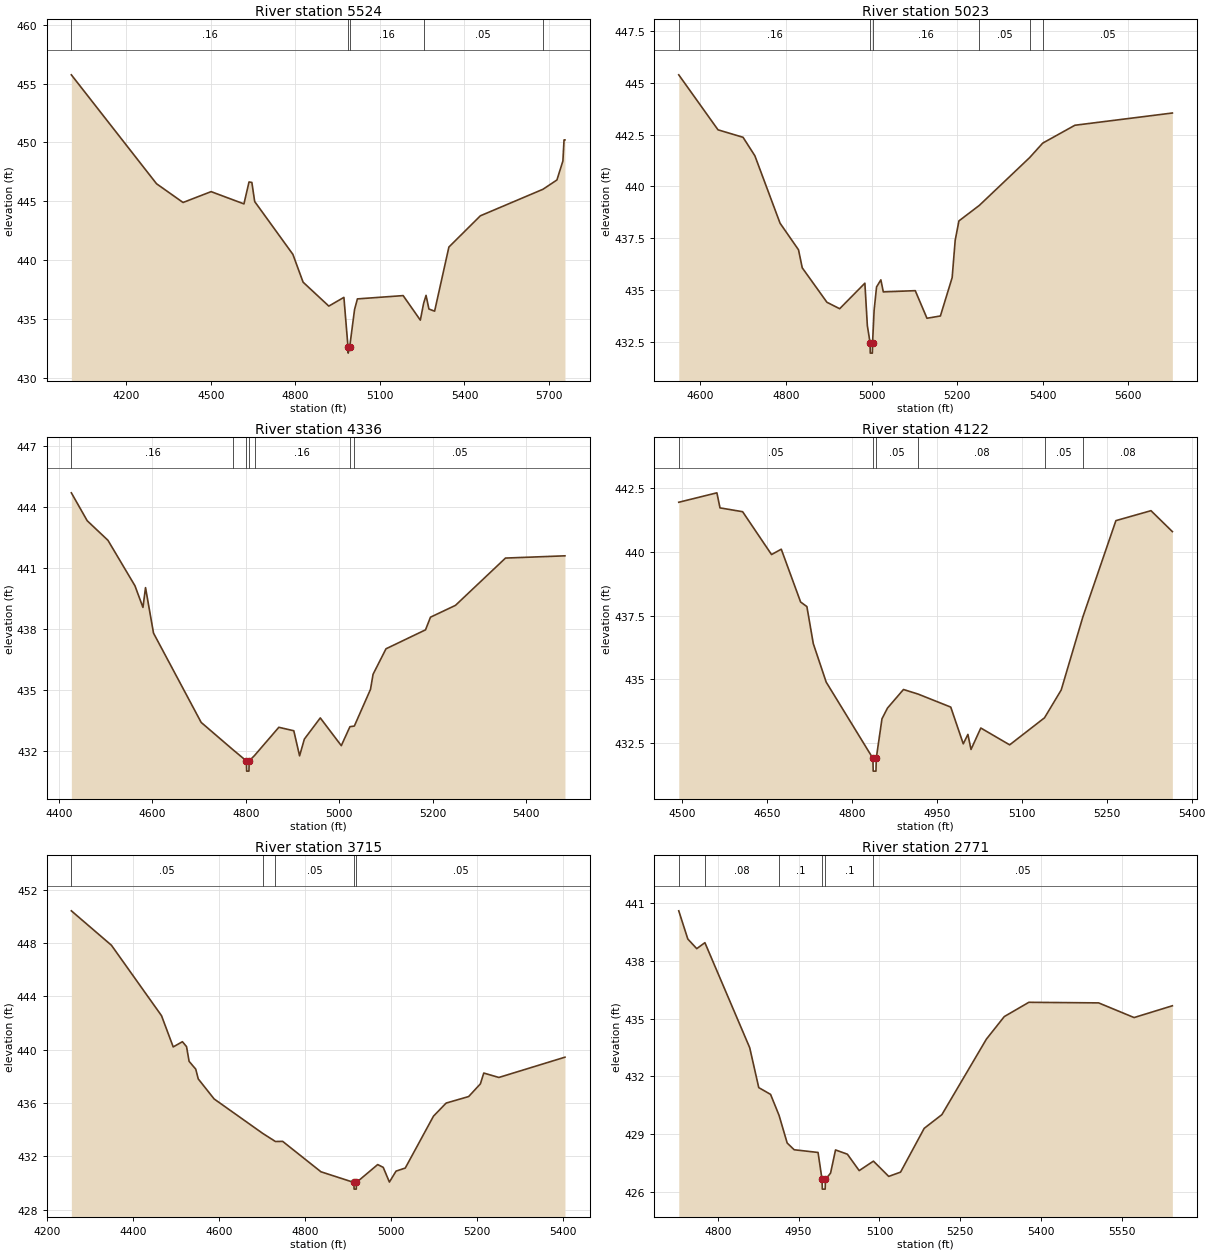
Type RM Length L Ch R = 1 ,5524    ,501,501,501
BEGIN DESCRIPTION:
YELLOW BRANCH 15 0
END DESCRIPTION:
XS GIS Cut Line= 5
       3599375.1     10475633.01      3599185.01     10476192.87
      3599203.24     10476349.12      3599078.24      10477086.1
      3598942.84     10477302.22
#Sta/Elev= 30
  4005.4  455.74  4307.6   446.5  4401.7  444.91  4501.2  445.83  4617.7  444.79
  4635.7  446.65  4645.8  446.61  4655.8  444.99  4791.3  440.51  4827.5  438.15
  4918.8  436.12  4972.3  436.86  4986.9  432.63  4987.4  432.13  4992.7  432.63
  5010.1  435.83  5020.2  436.73  5182.5  437.01  5243.4  434.93  5255.1  436.35
  5263.7  437.03    5274  435.87  5294.1  435.69  5344.8  441.13  5456.4  443.78
  5678.4  446.03    5728  446.82  5749.2  448.43  5753.2  450.22  5756.5  450.22
#Mann= 5 ,-1 , 0
  4005.4     .16       0  4986.9     .07       0  4992.7     .16       0
  5255.1     .05       0  5678.4     .08       0
Bank Sta=4986.9,4992.7
XS Rating Curve= 0 ,0
Exp/Cntr=0.3,0.1

Type RM Length L Ch R = 1 ,5023    ,687,687,687
BEGIN DESCRIPTION:
YELLOW BRANCH 14 0
END DESCRIPTION:
XS GIS Cut Line= 3
      3599005.34     10476031.38      3598648.55      10476651.2
      3598502.71      10477065.3
#Sta/Elev= 30
  4549.3  445.38  4641.1  442.73  4699.6  442.37  4727.3  441.48  4786.2  438.23
  4829.3  436.95  4838.1  436.08  4895.8  434.42  4925.6  434.11  4984.5  435.34
  4990.3  433.29  4996.7  432.47  4997.1  431.97    5002  431.97  5002.5  432.47
  5006.1  434.03  5011.8  435.16  5021.9   435.5  5027.6  434.92  5102.3  434.98
  5129.7  433.65  5161.1  433.76  5188.6  435.61  5195.7  437.41  5204.4  438.34
  5252.2  439.09  5369.7  441.39  5400.4  442.09  5475.6  442.95  5703.5  443.54
#Mann= 6 ,-1 , 0
  4549.3     .16       0  4996.7     .07       0  5002.5     .16       0
  5252.2     .05       0  5369.7     .16       0  5400.4     .05       0
Bank Sta=4996.7,5002.5
XS Rating Curve= 0 ,0
Exp/Cntr=0.3,0.1

Type RM Length L Ch R = 1 ,4336    ,214,214,214
BEGIN DESCRIPTION:
YELLOW BRANCH 12 0
END DESCRIPTION:
XS GIS Cut Line= 3
      3598484.51     10475770.95      3598192.82     10476380.37
      3598125.11     10476755.38
#Sta/Elev= 30
  4426.6  444.68  4460.6  443.31    4505  442.35  4562.8  440.12  4579.9  439.06
  4585.4  440.03  4602.5   437.8  4704.5  433.42  4773.6  432.06  4801.4  431.53
  4801.9  431.03  4806.8  431.03  4807.3  431.53  4818.9   431.8  4870.8  433.18
  4902.8  433.01  4915.2  431.78  4925.4   432.6  4959.5  433.64  5004.5  432.28
    5023  433.21  5032.4  433.24    5067  435.04  5072.5  435.78  5100.2  437.03
  5184.8  437.96  5195.4  438.58  5248.9  439.16    5356  441.48  5483.3  441.59
#Mann= 7 ,-1 , 0
  4426.6     .16       0  4773.6     .05       0  4801.4     .07       0
  4807.3     .05       0  4818.9     .16       0    5023     .08       0
  5032.4     .05       0
Bank Sta=4801.4,4807.3
XS Rating Curve= 0 ,0
Exp/Cntr=0.3,0.1

Type RM Length L Ch R = 1 ,4122    ,407,407,407
BEGIN DESCRIPTION:
YELLOW BRANCH 9 2
END DESCRIPTION:
XS GIS Cut Line= 2
      3598406.37     10475666.82      3598033.98     10476455.86
#Sta/Elev= 30
  4493.4  441.94  4560.8  442.31  4566.3  441.72  4606.3  441.57  4657.4  439.89
  4674.6   440.1  4708.8  438.03  4719.9  437.85  4731.2   436.4    4754  434.89
  4836.6   431.9  4837.1   431.4    4842   431.4  4842.5   431.9  4852.6  433.45
  4862.3  433.87  4890.6   434.6  4916.5  434.42  4974.2  433.91  4996.3  432.47
  5004.5  432.84    5010  432.25  5027.3  433.09  5078.3  432.43  5139.9  433.49
  5169.4  434.58  5207.6  437.44  5266.1  441.22  5328.1  441.61  5365.9  440.79
#Mann= 6 ,-1 , 0
  4493.4     .05       0  4836.6     .07       0  4842.5     .05       0
  4916.5     .08       0  5139.9     .05       0  5207.6     .08       0
Bank Sta=4836.6,4842.5
XS Rating Curve= 0 ,0
Exp/Cntr=0.3,0.1

Type RM Length L Ch R = 1 ,3715    ,944,944,944
BEGIN DESCRIPTION:
YELLOW BRANCH 9 1
END DESCRIPTION:
XS GIS Cut Line= 2
      3598198.04     10475341.29      3597604.26     10476323.11
#Sta/Elev= 30
  4256.4  450.41  4349.6  447.83    4466  442.55  4493.2  440.21  4514.6   440.6
  4524.2  440.23  4530.1  439.13  4545.6  438.54  4551.4  437.81  4588.3  436.31
  4701.6  433.72  4730.8  433.12  4747.6  433.13  4836.6  430.85  4913.2  430.05
  4913.7  429.55  4918.7  429.55  4919.1  430.05  4968.5  431.39  4981.4  431.18
  4995.7  430.08  5011.2   430.9  5032.6  431.13  5098.2  435.02  5127.6     436
    5180  436.49  5207.2  437.44  5215.1  438.25  5250.2  437.92  5403.8  439.44
#Mann= 5 ,-1 , 0
  4256.4     .05       0  4701.6     .08       0  4730.8     .05       0
  4913.2     .03       0  4919.1     .05       0
Bank Sta=4913.2,4919.1
XS Rating Curve= 0 ,0
Exp/Cntr=0.3,0.1

Type RM Length L Ch R = 1 ,2771    ,699,699,699
BEGIN DESCRIPTION:
YELLOW BRANCH 9 0
END DESCRIPTION:
XS GIS Cut Line= 3
      3597330.85     10475216.29      3597091.26     10475750.16
      3597187.16     10476066.37
#Sta/Elev= 30
  4727.7  440.58  4744.5  439.12  4761.1  438.62  4776.2  438.93  4859.3  433.49
  4876.1  431.42    4898  431.07  4913.8  429.98  4928.8  428.55  4941.8   428.2
  4986.1  428.06  4993.5  426.66    4994  426.16  4999.3  426.16  4999.8  426.66
  5009.3  426.99  5018.5  428.19  5040.5  427.97  5062.4  427.12  5088.8  427.61
  5117.2  426.82  5139.1  427.04    5183  429.31  5215.8  430.02  5298.3  433.93
  5331.5   435.1  5377.1  435.84  5506.5  435.81  5572.3  435.05  5643.3  435.66
#Mann= 6 ,-1 , 0
  4727.7     .05       0  4776.2     .08       0  4913.8      .1       0
  4993.5     .07       0  4999.8      .1       0  5088.8     .05       0
Bank Sta=4993.5,4999.8
XS Rating Curve= 0 ,0
Exp/Cntr=0.3,0.1

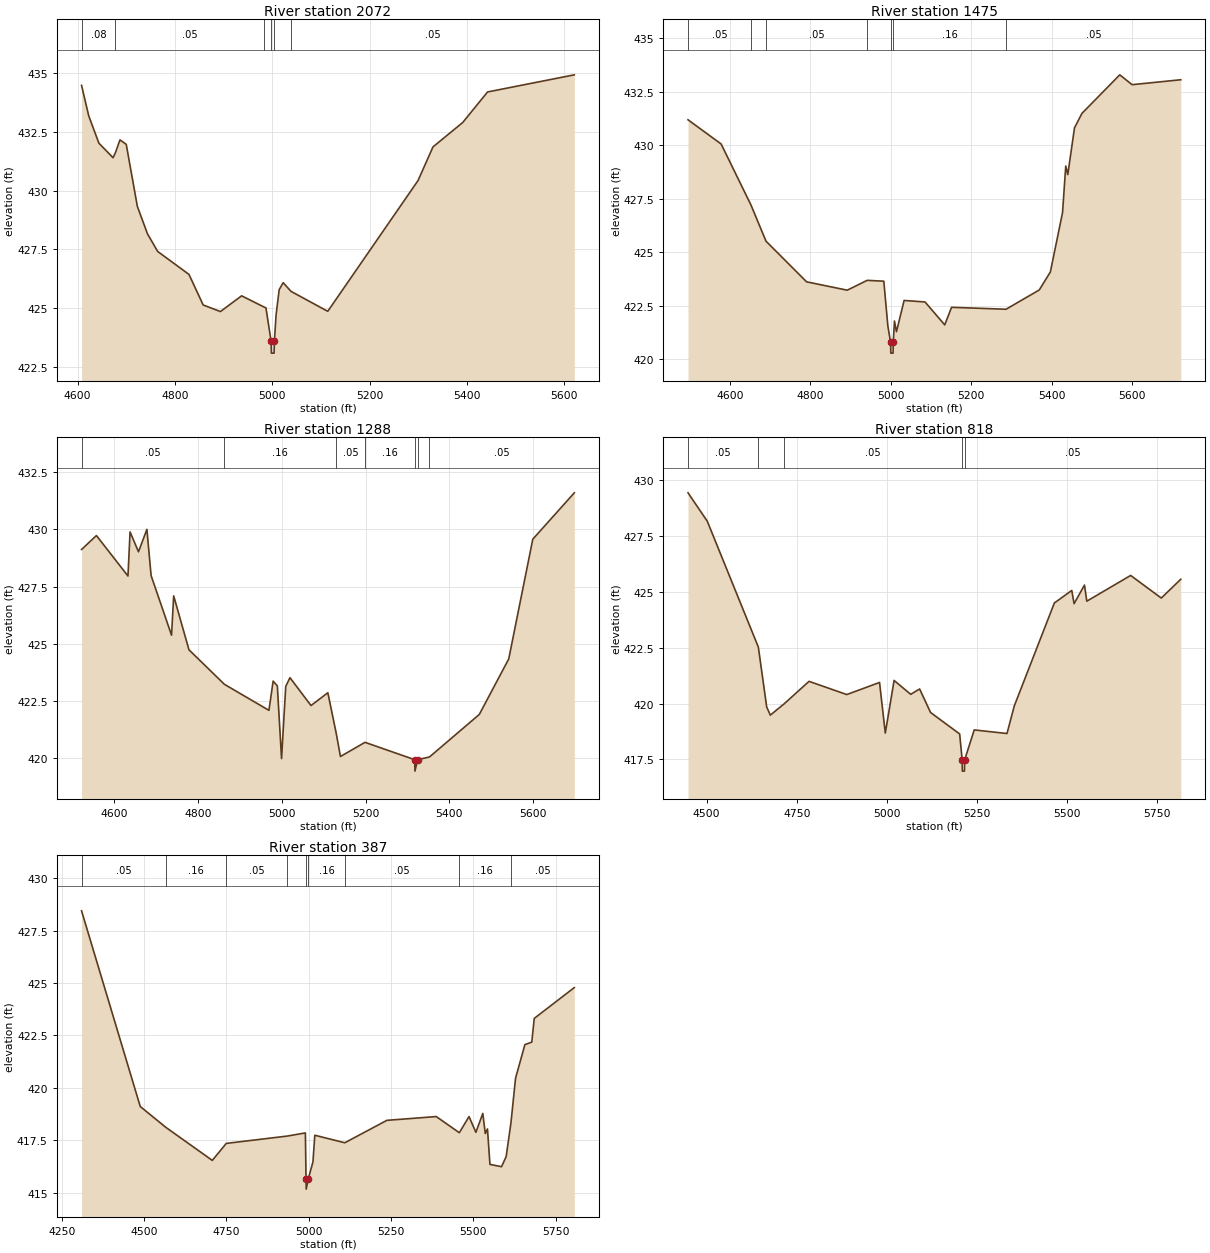
Type RM Length L Ch R = 1 ,2072    ,597,597,597
BEGIN DESCRIPTION:
YELLOW BRANCH 5 1
END DESCRIPTION:
XS GIS Cut Line= 3
      3596849.05     10475028.84      3596471.47      10475526.2
      3596395.95     10475906.42
#Sta/Elev= 30
  4608.3  434.48  4623.1  433.18  4643.9  432.02    4673   431.4    4678  431.62
  4687.2  432.16  4700.1  431.97  4722.9  429.33  4743.7  428.16  4764.6  427.41
    4829  426.43  4858.1  425.13  4893.5  424.85  4937.1  425.52  4983.4  425.04
    4987  425.01  4997.7  423.58  4998.2  423.08  5003.8  423.08  5004.3  423.58
  5007.9  424.71  5014.2  425.78  5022.4  426.08  5038.5  425.71    5114  424.86
  5299.5  430.43  5330.1  431.86  5391.2   432.9  5442.2   434.2  5620.4  434.93
#Mann= 6 ,-1 , 0
  4608.3     .08       0    4678     .05       0  4983.4     .16       0
  4997.7     .07       0  5004.3     .16       0  5038.5     .05       0
Bank Sta=4997.7,5004.3
XS Rating Curve= 0 ,0
Exp/Cntr=0.3,0.1

Type RM Length L Ch R = 1 ,1475    ,187,187,187
BEGIN DESCRIPTION:
YELLOW BRANCH 8 0
END DESCRIPTION:
XS GIS Cut Line= 3
      3596229.28     10474549.63      3596093.87     10475505.37
      3596143.34     10475760.54
#Sta/Elev= 30
  4495.7  431.18    4578  430.05  4652.2   427.2  4689.6  425.51  4790.6  423.61
  4891.6  423.22  4941.2  423.68  4982.5  423.64  4992.6  421.55  4999.4  420.78
  4999.9  420.28  5005.5  420.28    5006  420.78    5009  421.78    5014  421.28
    5033  422.74    5085  422.67    5134   421.6    5151  422.42  5286.5  422.33
    5369  423.23  5396.6  424.07  5426.9  426.84  5434.9  429.02    5440  428.62
  5456.6   430.8  5475.2  431.48  5569.2  433.28  5599.8  432.82  5720.9  433.05
#Mann= 7 ,-1 , 0
  4495.7     .05       0  4652.2     .16       0  4689.6     .05       0
  4941.2     .16       0  4999.4     .07       0    5006     .16       0
  5286.5     .05       0
Bank Sta=4999.4,5006
XS Rating Curve= 0 ,0
Exp/Cntr=0.3,0.1

Type RM Length L Ch R = 1 ,1288    ,470,470,470
BEGIN DESCRIPTION:
YELLOW BRANCH 10 0
END DESCRIPTION:
XS GIS Cut Line= 2
      3596057.41     10474466.32       3595948.1     10475637.43
#Sta/Elev= 30
  4522.2  429.12  4557.7  429.73    4633  427.96    4638  429.89  4658.1  429.02
  4678.2     430  4688.2  427.98    4737  425.37  4742.1  427.09  4778.6  424.73
  4863.2  423.22  4969.5  422.08  4979.5  423.36  4989.5  423.15  4999.6  419.97
  5009.6  423.13  5019.7  423.51  5069.9  422.29  5110.1  422.85  5129.6  421.12
  5140.2  420.06  5198.8  420.68  5317.5  419.92    5318  419.42  5324.4  419.92
  5352.7  420.04  5471.6   421.9  5541.9  424.33  5599.3  429.57  5698.4   431.6
#Mann= 7 ,-1 , 0
  4522.2     .05       0  4863.2     .16       0  5129.6     .05       0
  5198.8     .16       0  5317.5     .07       0  5324.4     .16       0
  5352.7     .05       0
Bank Sta=5317.5,5324.4
XS Rating Curve= 0 ,0
Exp/Cntr=0.3,0.1

Type RM Length L Ch R = 1 ,818     ,431,431,431
BEGIN DESCRIPTION:
YELLOW BRANCH 1 1
END DESCRIPTION:
XS GIS Cut Line= 3
      3595685.01      10474575.7      3595539.18     10475591.31
      3595751.55     10475858.07
#Sta/Elev= 30
  4448.4  429.41  4501.9  428.14  4643.5  422.52  4666.6  419.85  4676.7  419.48
  4715.4  419.99  4784.1  420.99  4888.8   420.4  4979.7  420.94  4995.7  418.68
  5020.1  421.03  5066.2  420.41  5090.9  420.65  5121.2   419.6    5202  418.64
  5208.9  417.48  5209.4  416.98  5215.3  416.98  5215.8  417.48  5242.4  418.82
  5333.3  418.66  5353.5  419.89  5464.7  424.49    5513  425.05  5519.4  424.46
  5548.3  425.29  5554.7  424.57  5676.4  425.72  5761.3  424.71  5815.4  425.55
#Mann= 5 ,-1 , 0
  4448.4     .05       0  4643.5     .16       0  4715.4     .05       0
  5208.9     .03       0  5215.8     .05       0
Bank Sta=5208.9,5215.8
XS Rating Curve= 0 ,0
Exp/Cntr=0.3,0.1

Type RM Length L Ch R = 1 ,387     ,0,0,0
BEGIN DESCRIPTION:
YELLOW BRANCH 1 0
END DESCRIPTION:
XS GIS Cut Line= 3
      3595539.18     10474461.09      3595156.37     10475307.45
      3595580.82     10475685.03
#Sta/Elev= 30
  4309.9  428.44  4488.2  419.11  4565.6  418.12  4707.1  416.54  4749.6  417.35
  4934.9   417.7  4989.9  417.85  4991.9  415.67  4992.4  415.17  4998.9  415.67
  5012.9  416.47  5018.5  417.74  5109.6  417.38  5237.5  418.45  5387.5  418.63
  5457.6  417.86    5487  418.63  5507.9  417.88  5528.9  418.78  5536.4  417.82
  5543.1  418.04  5550.6  416.35  5585.7  416.24  5599.9  416.72  5614.5  418.34
  5628.4  420.46  5656.8  422.06  5677.7  422.18  5685.2  423.31  5806.9  424.78
#Mann= 9 ,-1 , 0
  4309.9     .05       0  4565.6     .16       0  4749.6     .05       0
  4934.9     .16       0  4991.9     .07       0  4998.9     .16       0
  5109.6     .05       0  5457.6     .16       0  5614.5     .05       0
Bank Sta=4991.9,4998.9
XS Rating Curve= 0 ,0
Exp/Cntr=0.3,0.1

Chan Stop Cuts=-1
Use User Specified Reach Order=0
Composite Channel Slope=5