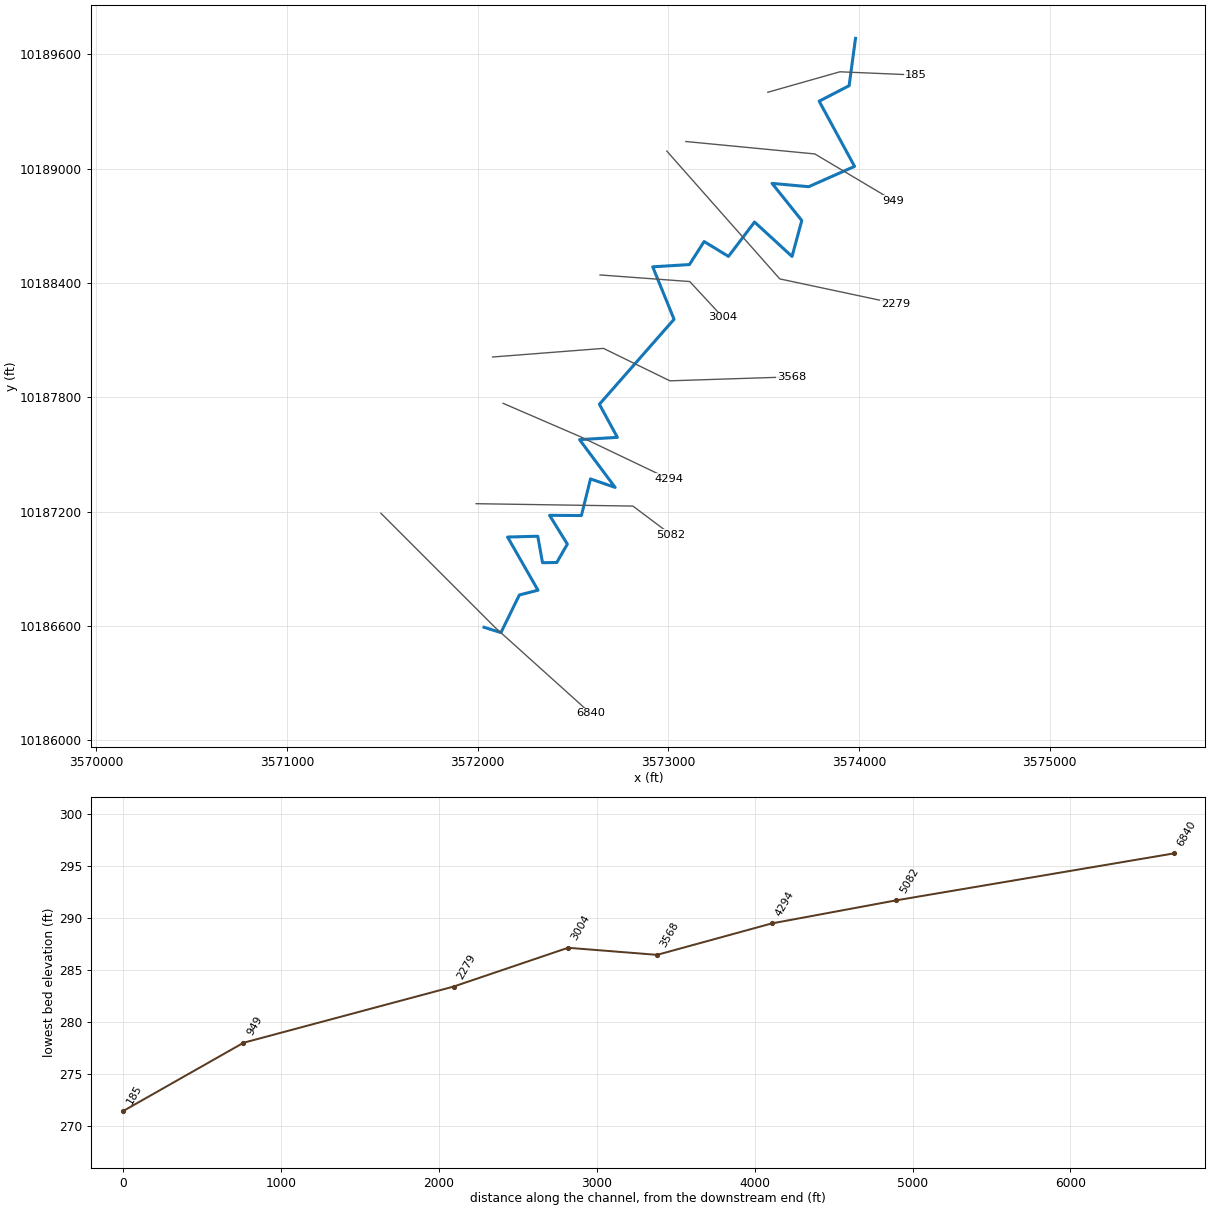
--- A-2 LOWER.prj (project) ---

Proj Title=A-2 LOWER Base Level Engineering
Current Plan=p01
Default Exp/Contr=0.3,0.1
English Units
Geom File=g01
Flow File=f01
Plan File=p01
BEGIN DESCRIPTION:
A-2 LOWER
END DESCRIPTION:

--- A-2 LOWER.p01 (plan) ---

Plan Title=Multiple Run
Short Identifier=Multiple
Geom File=g01
Flow File=f01
Subcritical Flow
K Sum by GR= 0
Std Step Tol= 0.01
Critical Tol= 0.01
Num of Std Step Trials= 20
Max Error Tol= 0.3
Flow Tol Ratio= 0.001
Split Flow NTrial= 30
Split Flow Tol= 0.02
Split Flow Ratio= 0.02
Log Output Level= 0
Friction Slope Method= 1
Unsteady Friction Slope Method= 2
Unsteady Bridges Friction Slope Method= 1
Parabolic Critical Depth
Global Vel Dist=  1 , 1 , 1
Global Log Level= 0
CheckData=True
Encroach Param= -1, 0, 0, 0
BEGIN DESCRIPTION:
Multiple Run
END DESCRIPTION:

--- A-2 LOWER.f01 (steady flow) ---

Flow Title=Multiple
Number of Profiles=7
Profile Names=10-year,25-year,50-year,1pct_min,100-year,1pct_plu,500-year
River Rch & RM= A-2 LOWER,Reach-1,6840
     434     572     683     598     809    1094    1136
Boundary for River Rch & Prof#=A-2 LOWER,Reach-1,1
Up Type=0
Dn Type=3
Dn Slope=0.005
Boundary for River Rch & Prof#=A-2 LOWER,Reach-1,2
Up Type=0
Dn Type=3
Dn Slope=0.005
Boundary for River Rch & Prof#=A-2 LOWER,Reach-1,3
Up Type=0
Dn Type=3
Dn Slope=0.005
Boundary for River Rch & Prof#=A-2 LOWER,Reach-1,4
Up Type=0
Dn Type=3
Dn Slope=0.005
Boundary for River Rch & Prof#=A-2 LOWER,Reach-1,5
Up Type=0
Dn Type=3
Dn Slope=0.005
Boundary for River Rch & Prof#=A-2 LOWER,Reach-1,6
Up Type=0
Dn Type=3
Dn Slope=0.005
Boundary for River Rch & Prof#=A-2 LOWER,Reach-1,7
Up Type=0
Dn Type=3
Dn Slope=0.005

--- A-2 LOWER.g01 (geometry) ---

Geom Title=Existing Conditions

River Reach=A-2 LOWER,Reach-1
Reach XY= 30
      3572033.49     10186593.23      3572122.04     10186565.31
      3572218.61     10186762.79      3572316.27     10186787.75
      3572156.76     10187066.61      3572315.19     10187070.95
      3572340.14     10186932.06      3572415.01     10186933.15
      3572470.35     10187029.72      3572377.03     10187180.54
      3572544.13     10187179.46      3572591.88     10187371.51
      3572721.00     10187327.03      3572534.37     10187577.68
      3572732.94     10187589.61      3572638.54     10187763.22
      3573030.10     10188209.07      3572918.25     10188484.26
      3573110.71     10188496.10      3573187.94     10188616.87
      3573315.67     10188539.11      3573452.48     10188719.21
      3573649.17     10188538.66      3573700.25     10188727.30
      3573544.33     10188921.99      3573736.34     10188904.59
      3573977.18     10189011.17      3573791.42     10189353.17
      3573948.70     10189434.56      3573982.11     10189682.96

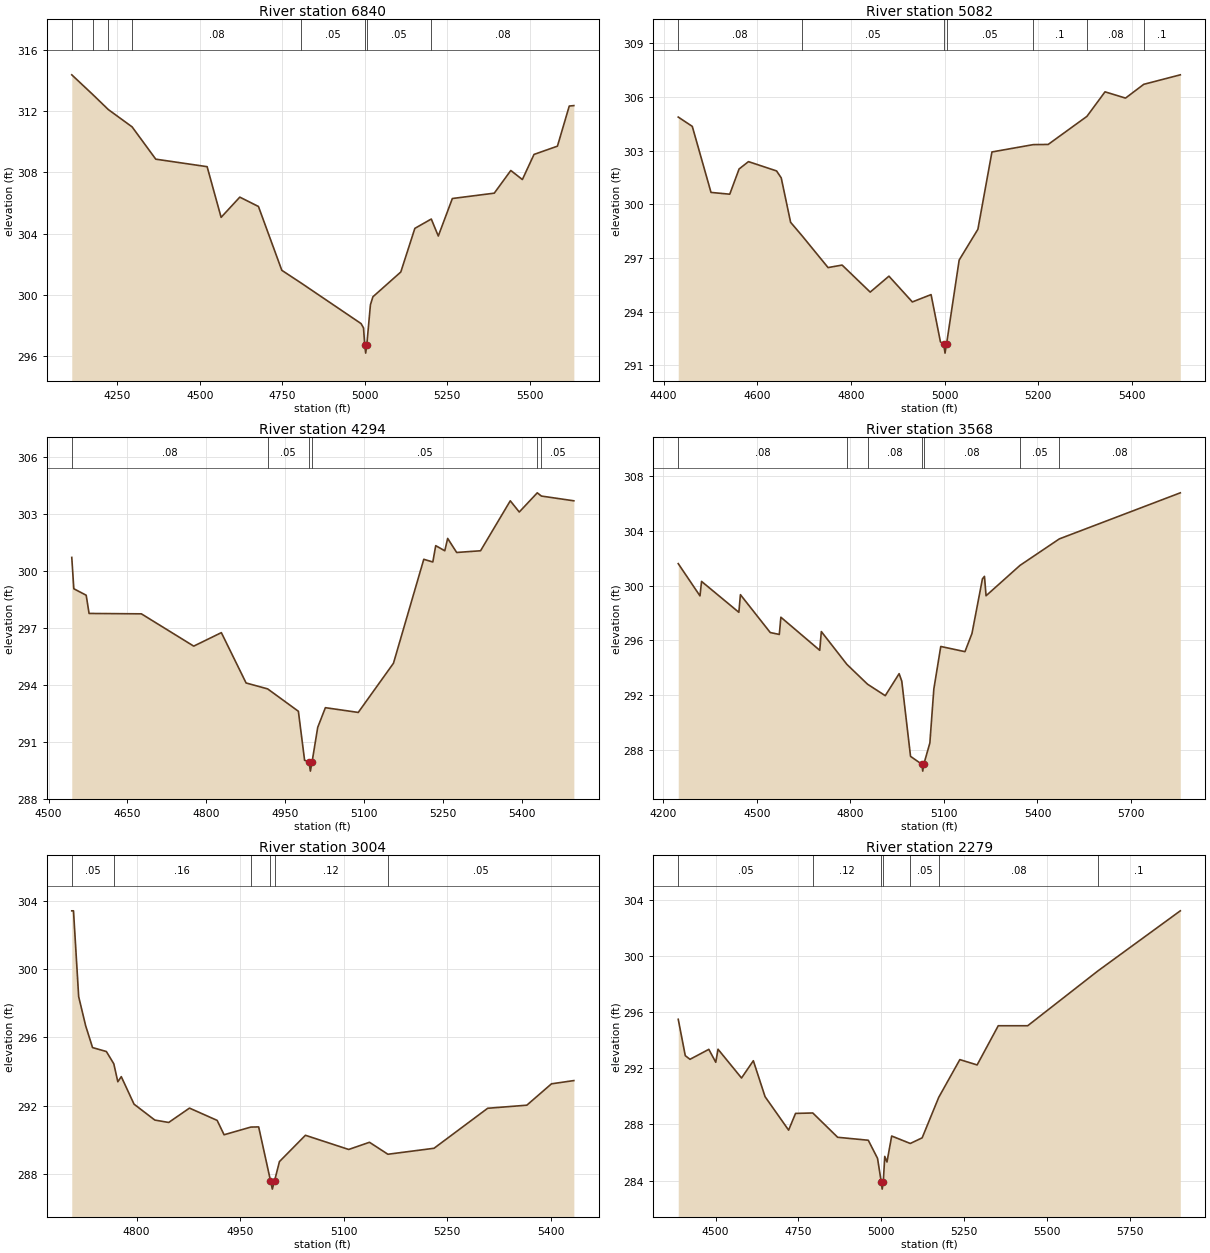
Type RM Length L Ch R = 1,6840,1758,1758,1758
BEGIN DESCRIPTION:
A-2 LOWER 11.0
END DESCRIPTION:
XS GIS Cut Line= 3
      3571492.13     10187191.62      3572092.11     10186591.64
      3572592.13     10186141.62
#Sta/Elev= 30
  4112.2  314.37  4175.5  313.09  4223.0  312.10  4295.0  310.97  4366.7  308.86
  4522.3  308.37  4564.7  305.06  4621.3  306.38  4677.8  305.77  4748.6  301.60
  4807.8  300.76  4988.7  298.12  4996.2  297.84  4999.9  296.69  5002.7  296.19
  5005.9  296.69  5017.1  299.35  5024.6  299.87  5109.1  301.49  5151.7  304.34
  5201.5  304.95  5222.7  303.84  5265.3  306.29  5392.3  306.64  5442.4  308.12
  5477.5  307.53  5512.7  309.17  5583.7  309.71  5619.5  312.33  5633.4  312.36
#Mann=8,-1,0
  4112.2     0.1       0  4175.5    0.08       0  4223.0     0.1       0
  4295.0    0.08       0  4807.8    0.05       0  4999.9    0.03       0
  5005.9    0.05       0  5201.5    0.08       0
Bank Sta=4999.9,5005.9
Exp/Cntr=0.3,0.1

Type RM Length L Ch R = 1,5082,788,788,788
BEGIN DESCRIPTION:
A-2 LOWER 9.0
END DESCRIPTION:
XS GIS Cut Line= 3
      3571992.14     10187241.64      3572814.33     10187229.14
      3573014.34     10187079.13
#Sta/Elev= 30
  4431.2  304.87  4461.2  304.35  4501.2  300.66  4541.2  300.56  4561.2  301.97
  4581.2  302.38  4641.2  301.86  4651.2  301.47  4671.2  298.99  4695.6  298.24
  4751.2  296.46  4781.2  296.60  4841.2  295.09  4881.2  295.98  4931.2  294.54
  4971.2  294.95  4991.2  292.31  4998.2  292.18  5001.0  291.68  5004.2  292.18
  5031.2  296.88  5071.2  298.60  5101.2  302.92  5189.5  303.33  5221.3  303.34
  5304.1  304.91  5342.7  306.28  5386.5  305.93  5425.5  306.70  5503.5  307.23
#Mann=7,-1,0
  4431.2    0.08       0  4695.6    0.05       0  4998.2    0.04       0
  5004.2    0.05       0  5189.5     0.1       0  5304.1    0.08       0
  5425.5     0.1       0
Bank Sta=4998.2,5004.2
Exp/Cntr=0.3,0.1

Type RM Length L Ch R = 1,4294,726,726,726
BEGIN DESCRIPTION:
A-2 LOWER 8.0
END DESCRIPTION:
XS GIS Cut Line= 3
      3572133.38     10187768.15      3572542.11     10187591.64
      3573001.42     10187372.32
#Sta/Elev= 30
  4544.1  300.71  4548.0  299.06  4571.5  298.72  4577.0  297.76  4676.4  297.74
  4775.9  296.04  4828.4  296.75  4875.4  294.10  4916.3  293.79  4974.8  292.61
  4986.6  290.03  4994.9  289.96  4997.6  289.46  5000.9  289.96  5011.5  291.76
  5026.1  292.80  5088.6  292.55  5155.5  295.14  5213.1  300.61  5230.3  300.47
  5235.8  301.33  5253.0  301.06  5258.5  301.71  5275.6  300.97  5321.0  301.06
  5377.5  303.69  5394.6  303.10  5428.8  304.11  5436.6  303.94  5498.3  303.69
#Mann=6,-1,0
  4544.1    0.08       0  4916.3    0.05       0  4994.9    0.04       0
  5000.9    0.05       0  5428.8    0.08       0  5436.6    0.05       0
Bank Sta=4994.9,5000.9
Exp/Cntr=0.3,0.1

Type RM Length L Ch R = 1,3568,564,564,564
BEGIN DESCRIPTION:
A-2 LOWER 6.0
END DESCRIPTION:
XS GIS Cut Line= 4
      3572077.81     10188011.22      3572660.00     10188056.44
      3573008.35     10187886.22      3573647.15     10187907.05
#Sta/Elev= 30
  4247.4  301.62  4317.2  299.26  4322.2  300.32  4441.9  298.06  4446.9  299.35
  4542.6  296.58  4571.7  296.44  4576.7  297.70  4701.4  295.28  4706.5  296.65
  4788.5  294.25  4854.7  292.80  4911.6  291.96  4956.1  293.57  4964.6  293.02
  4992.7  287.52  5029.2  286.94  5031.9  286.44  5035.2  286.94  5054.7  288.50
  5067.4  292.44  5089.7  295.56  5167.3  295.18  5189.8  296.51  5223.4  300.51
  5229.9  300.69  5235.0  299.27  5343.8  301.49  5470.1  303.43  5858.2  306.80
#Mann=7,-1,0
  4247.4    0.08       0  4788.5    0.05       0  4854.7    0.08       0
  5029.2    0.07       0  5035.2    0.08       0  5343.8    0.05       0
  5470.1    0.08       0
Bank Sta=5029.2,5035.2
Exp/Cntr=0.3,0.1

Type RM Length L Ch R = 1,3004,725,725,725
BEGIN DESCRIPTION:
A-2 LOWER 5.0
END DESCRIPTION:
XS GIS Cut Line= 3
      3572642.10     10188441.64      3573112.52     10188407.05
      3573286.11     10188219.57
#Sta/Elev= 30
  4706.2  303.40  4708.7  303.40  4716.2  298.38  4726.3  296.68  4736.3  295.40
  4756.3  295.17  4767.1  294.45  4772.9  293.40  4777.9  293.70  4796.4  292.09
  4826.5  291.16  4846.6  291.02  4876.7  291.86  4916.8  291.14  4926.8  290.30
  4965.6  290.75  4976.9  290.76  4994.0  287.62  4996.7  287.12  5000.0  287.62
  5007.0  288.73  5044.6  290.27  5107.3  289.44  5137.4  289.86  5164.1  289.16
  5230.9  289.51  5308.6  291.85  5365.3  292.03  5401.0  293.28  5433.4  293.47
#Mann=6,-1,0
  4706.2    0.05       0  4767.1    0.16       0  4965.6    0.12       0
  4994.0    0.07       0  5000.0    0.12       0  5164.1    0.05       0
Bank Sta=4994,5000
Exp/Cntr=0.3,0.1

Type RM Length L Ch R = 1,2279,1330,1330,1330
BEGIN DESCRIPTION:
A-2 LOWER 3.0
END DESCRIPTION:
XS GIS Cut Line= 3
      3572992.12     10189091.62      3573584.74     10188420.94
      3574192.14     10188291.64
#Sta/Elev= 30
  4387.3  295.48  4408.6  292.89  4422.8  292.63  4479.7  293.34  4500.6  292.42
  4507.4  293.35  4578.4  291.30  4614.1  292.53  4649.5  289.97  4720.6  287.59
  4741.5  288.78  4793.6  288.81  4868.7  287.08  4961.1  286.87  4989.1  285.58
  5000.4  283.89  5003.1  283.39  5006.4  283.89  5010.9  285.72  5017.6  285.32
  5031.8  287.17  5088.0  286.64  5123.8  287.04  5173.8  289.92  5237.6  292.61
  5289.8  292.23  5353.6  295.02  5442.5  295.02  5654.9  298.93  5903.3  303.20
#Mann=7,-1,0
  4387.3    0.05       0  4793.6    0.12       0  5000.4    0.07       0
  5006.4    0.12       0  5088.0    0.05       0  5173.8    0.08       0
  5654.9     0.1       0
Bank Sta=5000.4,5006.4
Exp/Cntr=0.3,0.1

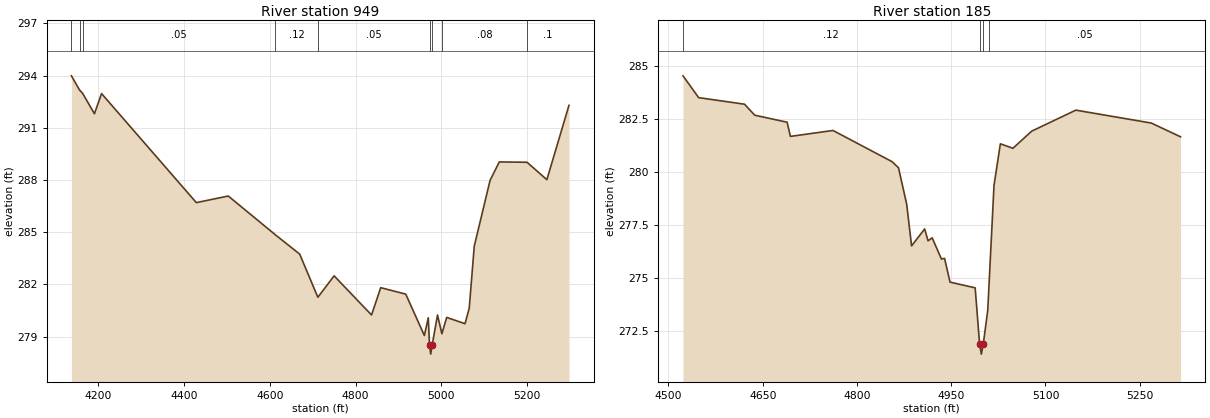
Type RM Length L Ch R = 1,949,764,764,764
BEGIN DESCRIPTION:
A-2 LOWER 2.0
END DESCRIPTION:
XS GIS Cut Line= 3
      3573092.09     10189141.64      3573768.73     10189076.49
      3574181.96     10188830.66
#Sta/Elev= 30
  4137.0  293.99  4156.1  293.17  4163.2  292.98  4190.7  291.81  4207.3  292.97
  4428.4  286.70  4502.9  287.08  4612.3  284.86  4669.5  283.74  4711.9  281.26
  4749.8  282.49  4837.1  280.24  4858.5  281.81  4916.9  281.44  4960.3  279.06
  4969.5  280.08  4972.4  278.49  4975.1  277.99  4978.4  278.49  4991.0  280.24
  5001.2  279.16  5012.4  280.10  5055.2  279.74  5065.0  280.63  5076.7  284.19
  5113.6  287.98  5135.1  289.04  5199.9  289.02  5246.1  288.02  5297.6  292.29
#Mann=9,-1,0
  4137.0    0.05       0  4156.1     0.1       0  4163.2    0.05       0
  4612.3    0.12       0  4711.9    0.05       0  4972.4    0.04       0
  4978.4    0.05       0  5001.2    0.08       0  5199.9     0.1       0
Bank Sta=4972.4,4978.4
Exp/Cntr=0.3,0.1

Type RM Length L Ch R = 1,185,0,0,0
BEGIN DESCRIPTION:
A-2 LOWER 1.0
END DESCRIPTION:
XS GIS Cut Line= 3
      3573522.20     10189400.10      3573900.40     10189507.47
      3574298.59     10189490.45
#Sta/Elev= 30
  4523.2  284.55  4548.1  283.52  4621.1  283.21  4637.4  282.69  4688.9  282.36
  4694.1  281.69  4761.9  281.97  4855.7  280.50  4866.1  280.21  4879.2  278.48
  4886.9  276.52  4907.7  277.32  4913.1  276.76  4919.7  276.90  4934.4  275.90
  4939.4  275.93  4948.1  274.81  4988.1  274.54  4995.1  271.91  4997.9  271.41
  5001.1  271.91  5008.1  273.47  5009.7  274.42  5018.1  279.38  5028.2  281.34
  5048.2  281.13  5078.2  281.94  5148.3  282.93  5268.4  282.32  5314.9  281.67
#Mann=4,-1,0
  4523.2    0.12       0  4995.1    0.07       0  5001.1    0.12       0
  5009.7    0.05       0
Bank Sta=4995.1,5001.1
Exp/Cntr=0.3,0.1

Chan Stop Cuts=-1