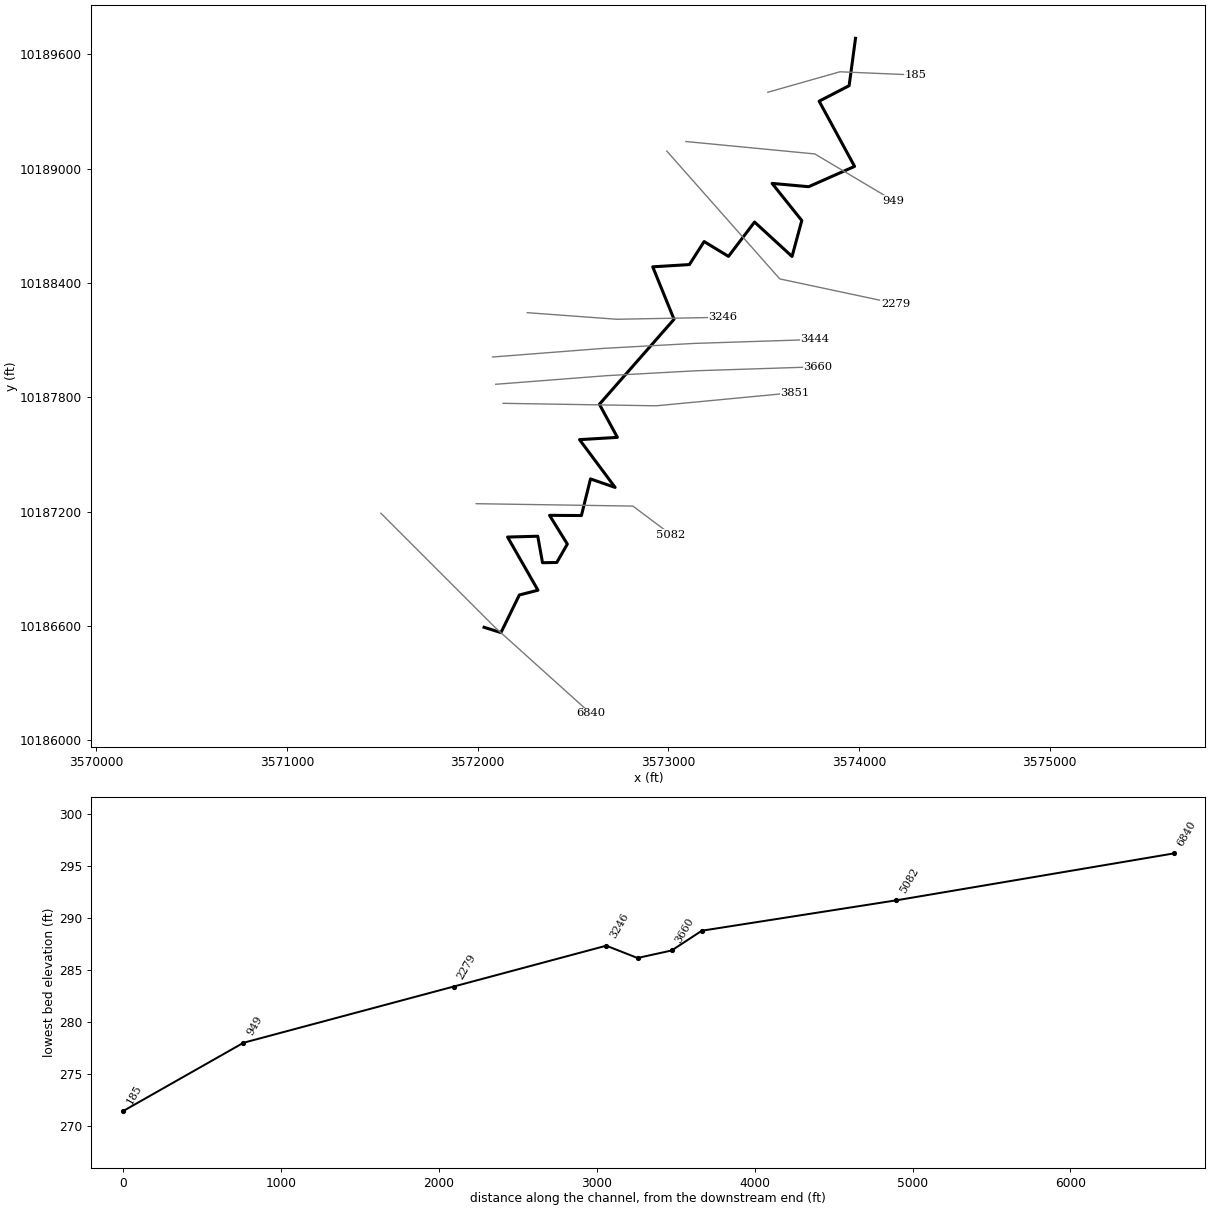
--- A2 LOWER.prj (project) ---

Proj Title=A2 LOWER Base Level Engineering
Current Plan=p01
Default Exp/Contr=0.3,0.1
English Units
Geom File=g01
Flow File=f01
Plan File=p01
BEGIN DESCRIPTION:
A2 LOWER
END DESCRIPTION:

--- A2 LOWER.p01 (plan) ---

Plan Title=Multiple Run
Short Identifier=Multiple
Geom File=g01
Flow File=f01
Subcritical Flow
K Sum by GR= 0
Std Step Tol= 0.01
Critical Tol= 0.01
Num of Std Step Trials= 20
Max Error Tol= 0.3
Flow Tol Ratio= 0.001
Split Flow NTrial= 30
Split Flow Tol= 0.02
Split Flow Ratio= 0.02
Log Output Level= 0
Friction Slope Method= 1
Unsteady Friction Slope Method= 2
Unsteady Bridges Friction Slope Method= 1
Parabolic Critical Depth
Global Vel Dist=  1 , 1 , 1
Global Log Level= 0
CheckData=True
Encroach Param= -1, 0, 0, 0
BEGIN DESCRIPTION:
Multiple Run
END DESCRIPTION:

--- A2 LOWER.f01 (steady flow) ---

Flow Title=Multiple
Number of Profiles=7
Profile Names=10-year,25-year,50-year,1pct_min,100-year,1pct_plu,500-year
River Rch & RM= A2 LOWER,Reach-1,6840
     434     572     683     598     809    1094    1136
Boundary for River Rch & Prof#=A2 LOWER,Reach-1,1
Up Type=0
Dn Type=3
Dn Slope=0.005
Boundary for River Rch & Prof#=A2 LOWER,Reach-1,2
Up Type=0
Dn Type=3
Dn Slope=0.005
Boundary for River Rch & Prof#=A2 LOWER,Reach-1,3
Up Type=0
Dn Type=3
Dn Slope=0.005
Boundary for River Rch & Prof#=A2 LOWER,Reach-1,4
Up Type=0
Dn Type=3
Dn Slope=0.005
Boundary for River Rch & Prof#=A2 LOWER,Reach-1,5
Up Type=0
Dn Type=3
Dn Slope=0.005
Boundary for River Rch & Prof#=A2 LOWER,Reach-1,6
Up Type=0
Dn Type=3
Dn Slope=0.005
Boundary for River Rch & Prof#=A2 LOWER,Reach-1,7
Up Type=0
Dn Type=3
Dn Slope=0.005

--- A2 LOWER.g01 (geometry) ---

Geom Title=Existing Conditions

River Reach=A2 LOWER,Reach-1
Reach XY= 30
      3572033.49     10186593.23      3572122.04     10186565.31
      3572218.61     10186762.79      3572316.27     10186787.75
      3572156.76     10187066.61      3572315.19     10187070.95
      3572340.14     10186932.06      3572415.01     10186933.15
      3572470.35     10187029.72      3572377.03     10187180.54
      3572544.13     10187179.46      3572591.88     10187371.51
      3572721.00     10187327.03      3572534.37     10187577.68
      3572732.94     10187589.61      3572638.54     10187763.22
      3573030.10     10188209.07      3572918.25     10188484.26
      3573110.71     10188496.10      3573187.94     10188616.87
      3573315.67     10188539.11      3573452.48     10188719.21
      3573649.17     10188538.66      3573700.25     10188727.30
      3573544.33     10188921.99      3573736.34     10188904.59
      3573977.18     10189011.17      3573791.42     10189353.17
      3573948.70     10189434.56      3573982.11     10189682.96

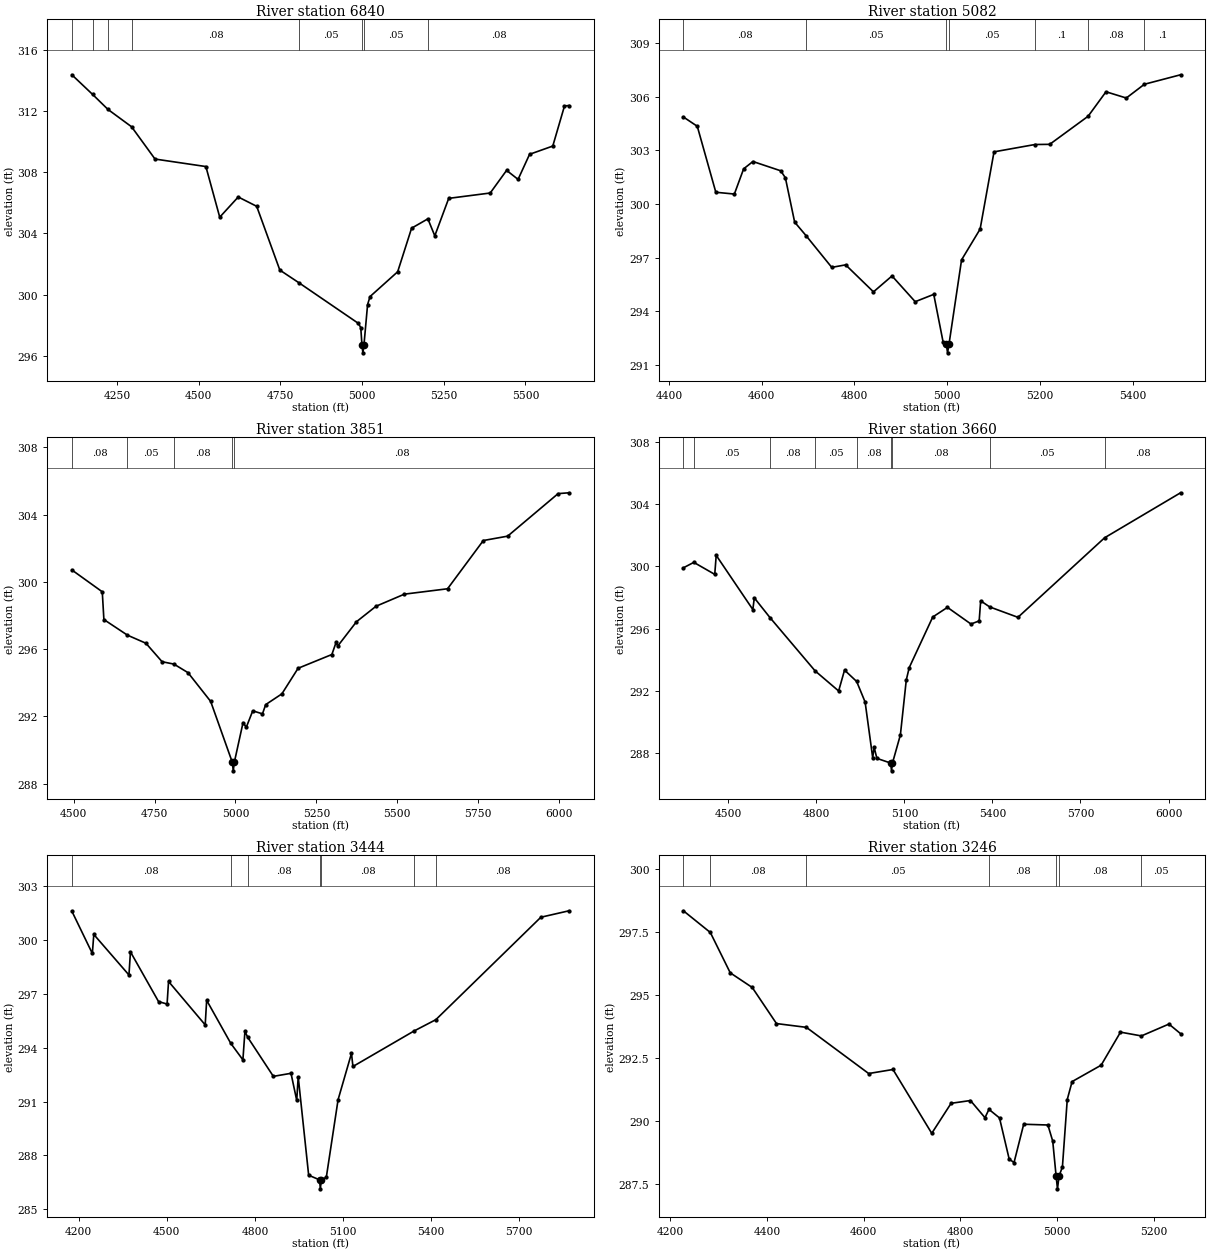
Type RM Length L Ch R = 1,6840,1758,1758,1758
BEGIN DESCRIPTION:
A-2 LOWER 11.0
END DESCRIPTION:
XS GIS Cut Line= 3
      3571492.13     10187191.62      3572092.11     10186591.64
      3572592.13     10186141.62
#Sta/Elev= 30
  4112.2  314.37  4175.5  313.09  4223.0  312.10  4295.0  310.97  4366.7  308.86
  4522.3  308.37  4564.7  305.06  4621.3  306.38  4677.8  305.77  4748.6  301.60
  4807.8  300.76  4988.7  298.12  4996.2  297.84  4999.9  296.69  5002.7  296.19
  5005.9  296.69  5017.1  299.35  5024.6  299.87  5109.1  301.49  5151.7  304.34
  5201.5  304.95  5222.7  303.84  5265.3  306.29  5392.3  306.64  5442.4  308.12
  5477.5  307.53  5512.7  309.17  5583.7  309.71  5619.5  312.33  5633.4  312.36
#Mann=8,-1,0
  4112.2     0.1       0  4175.5    0.08       0  4223.0     0.1       0
  4295.0    0.08       0  4807.8    0.05       0  4999.9    0.03       0
  5005.9    0.05       0  5201.5    0.08       0
Bank Sta=4999.9,5005.9
Exp/Cntr=0.3,0.1

Type RM Length L Ch R = 1,5082,1231,1231,1231
BEGIN DESCRIPTION:
A-2 LOWER 9.0
END DESCRIPTION:
XS GIS Cut Line= 3
      3571992.14     10187241.64      3572814.33     10187229.14
      3573014.34     10187079.13
#Sta/Elev= 30
  4431.2  304.87  4461.2  304.35  4501.2  300.66  4541.2  300.56  4561.2  301.97
  4581.2  302.38  4641.2  301.86  4651.2  301.47  4671.2  298.99  4695.6  298.24
  4751.2  296.46  4781.2  296.60  4841.2  295.09  4881.2  295.98  4931.2  294.54
  4971.2  294.95  4991.2  292.31  4998.2  292.18  5001.0  291.68  5004.2  292.18
  5031.2  296.88  5071.2  298.60  5101.2  302.92  5189.5  303.33  5221.3  303.34
  5304.1  304.91  5342.7  306.28  5386.5  305.93  5425.5  306.70  5503.5  307.23
#Mann=7,-1,0
  4431.2    0.08       0  4695.6    0.05       0  4998.2    0.04       0
  5004.2    0.05       0  5189.5     0.1       0  5304.1    0.08       0
  5425.5     0.1       0
Bank Sta=4998.2,5004.2
Exp/Cntr=0.3,0.1

Type RM Length L Ch R = 1,3851,191,191,191
BEGIN DESCRIPTION:
A-2 LOWER 8.0
END DESCRIPTION:
XS GIS Cut Line= 3
      3572133.36     10187768.16      3572936.47     10187755.19
      3573665.65     10187824.64
#Sta/Elev= 30
  4494.5  300.71  4588.5  299.41  4593.5  297.76  4666.3  296.83  4723.3  296.35
  4773.3  295.25  4809.7  295.11  4853.3  294.60  4923.3  292.89  4990.3  289.26
  4993.1  288.76  4996.3  289.26  5023.3  291.63  5033.3  291.35  5053.3  292.33
  5083.3  292.15  5093.3  292.70  5143.3  293.34  5193.3  294.86  5297.7  295.68
  5310.7  296.40  5315.7  296.18  5373.7  297.63  5434.0  298.55  5521.7  299.27
  5655.0  299.59  5765.5  302.46  5840.6  302.72  5996.5  305.25  6030.2  305.30
#Mann=5,-1,0
  4494.5    0.08       0  4666.3    0.05       0  4809.7    0.08       0
  4990.3    0.07       0  4996.3    0.08       0
Bank Sta=4990.3,4996.3
Exp/Cntr=0.3,0.1

Type RM Length L Ch R = 1,3660,216,216,216
BEGIN DESCRIPTION:
A-2 LOWER 7.0
END DESCRIPTION:
XS GIS Cut Line= 4
      3572094.67     10187868.04      3572676.84     10187913.26
      3573146.88     10187939.04      3573785.77     10187959.87
#Sta/Elev= 30
  4347.0  299.90  4382.6  300.25  4453.9  299.48  4458.9  300.70  4583.7  297.22
  4588.7  297.97  4642.2  296.70  4795.8  293.28  4876.0  291.99  4896.1  293.33
  4937.4  292.60  4966.2  291.28  4992.0  287.71  4997.0  288.37  5006.3  287.66
  5053.4  287.36  5056.1  286.86  5059.4  287.36  5086.4  289.17  5106.5  292.70
  5116.5  293.49  5196.6  296.74  5246.7  297.36  5326.8  296.29  5354.8  296.49
  5359.9  297.78  5390.5  297.39  5486.9  296.72  5782.2  301.83  6040.9  304.72
#Mann=9,-1,0
  4347.0    0.08       0  4382.6    0.05       0  4642.2    0.08       0
  4795.8    0.05       0  4937.4    0.08       0  5053.4    0.07       0
  5059.4    0.08       0  5390.5    0.05       0  5782.2    0.08       0
Bank Sta=5053.4,5059.4
Exp/Cntr=0.3,0.1

Type RM Length L Ch R = 1,3444,198,198,198
BEGIN DESCRIPTION:
A-2 LOWER 6.0
END DESCRIPTION:
XS GIS Cut Line= 4
      3572077.78     10188011.22      3572660.00     10188056.44
      3573130.03     10188082.22      3573767.98     10188103.03
#Sta/Elev= 30
  4176.6  301.62  4246.4  299.26  4251.4  300.32  4371.1  298.06  4376.2  299.35
  4471.8  296.58  4500.9  296.44  4505.9  297.70  4630.7  295.28  4635.7  296.65
  4717.8  294.25  4759.1  293.33  4766.0  294.92  4775.4  294.59  4862.8  292.41
  4922.9  292.58  4942.4  291.07  4947.4  292.39  4983.0  286.90  5020.1  286.64
  5022.8  286.14  5026.1  286.64  5043.1  286.78  5083.2  291.11  5128.8  293.69
  5133.8  292.96  5340.9  294.93  5416.1  295.57  5773.7  301.28  5869.6  301.64
#Mann=7,-1,0
  4176.6    0.08       0  4717.8    0.05       0  4775.4    0.08       0
  5020.1    0.07       0  5026.1    0.08       0  5340.9    0.05       0
  5416.1    0.08       0
Bank Sta=5020.1,5026.1
Exp/Cntr=0.3,0.1

Type RM Length L Ch R = 1,3246,967,967,967
BEGIN DESCRIPTION:
A-2 LOWER 5.0
END DESCRIPTION:
XS GIS Cut Line= 3
      3572260.20     10188243.72      3572730.57     10188209.14
      3573286.14     10188219.55
#Sta/Elev= 30
  4227.5  298.34  4283.2  297.48  4324.4  295.88  4369.8  295.30  4419.9  293.87
  4481.7  293.72  4610.4  291.89  4660.6  292.05  4740.7  289.52  4780.7  290.71
  4820.7  290.82  4850.7  290.14  4858.9  290.47  4880.7  290.13  4900.7  288.50
  4910.7  288.36  4930.7  289.88  4980.7  289.85  4990.7  289.21  4997.7  287.82
  5000.5  287.32  5003.7  287.82  5010.7  288.19  5020.7  290.86  5030.7  291.57
  5090.7  292.22  5130.7  293.53  5173.9  293.38  5230.8  293.85  5254.8  293.47
#Mann=7,-1,0
  4227.5    0.05       0  4283.2    0.08       0  4481.7    0.05       0
  4858.9    0.08       0  4997.7    0.07       0  5003.7    0.08       0
  5173.9    0.05       0
Bank Sta=4997.7,5003.7
Exp/Cntr=0.3,0.1

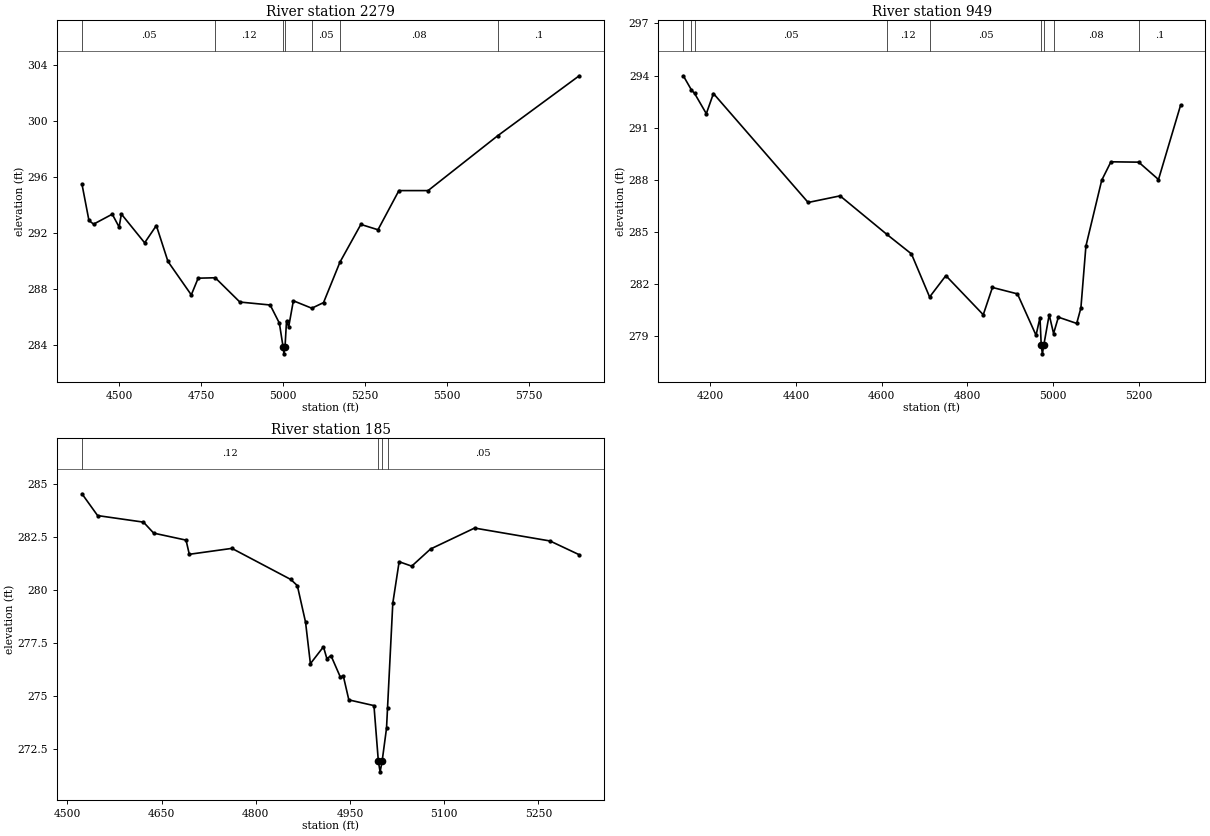
Type RM Length L Ch R = 1,2279,1330,1330,1330
BEGIN DESCRIPTION:
A-2 LOWER 3.0
END DESCRIPTION:
XS GIS Cut Line= 3
      3572992.12     10189091.62      3573584.74     10188420.94
      3574192.14     10188291.64
#Sta/Elev= 30
  4387.3  295.48  4408.6  292.89  4422.8  292.63  4479.7  293.34  4500.6  292.42
  4507.4  293.35  4578.4  291.30  4614.1  292.53  4649.5  289.97  4720.6  287.59
  4741.5  288.78  4793.6  288.81  4868.7  287.08  4961.1  286.87  4989.1  285.58
  5000.4  283.89  5003.1  283.39  5006.4  283.89  5010.9  285.72  5017.6  285.32
  5031.8  287.17  5088.0  286.64  5123.8  287.04  5173.8  289.92  5237.6  292.61
  5289.8  292.23  5353.6  295.02  5442.5  295.02  5654.9  298.93  5903.3  303.20
#Mann=7,-1,0
  4387.3    0.05       0  4793.6    0.12       0  5000.4    0.07       0
  5006.4    0.12       0  5088.0    0.05       0  5173.8    0.08       0
  5654.9     0.1       0
Bank Sta=5000.4,5006.4
Exp/Cntr=0.3,0.1

Type RM Length L Ch R = 1,949,764,764,764
BEGIN DESCRIPTION:
A-2 LOWER 2.0
END DESCRIPTION:
XS GIS Cut Line= 3
      3573092.09     10189141.64      3573768.73     10189076.49
      3574181.96     10188830.66
#Sta/Elev= 30
  4137.0  293.99  4156.1  293.17  4163.2  292.98  4190.7  291.81  4207.3  292.97
  4428.4  286.70  4502.9  287.08  4612.3  284.86  4669.5  283.74  4711.9  281.26
  4749.8  282.49  4837.1  280.24  4858.5  281.81  4916.9  281.44  4960.3  279.06
  4969.5  280.08  4972.4  278.49  4975.1  277.99  4978.4  278.49  4991.0  280.24
  5001.2  279.16  5012.4  280.10  5055.2  279.74  5065.0  280.63  5076.7  284.19
  5113.6  287.98  5135.1  289.04  5199.9  289.02  5246.1  288.02  5297.6  292.29
#Mann=9,-1,0
  4137.0    0.05       0  4156.1     0.1       0  4163.2    0.05       0
  4612.3    0.12       0  4711.9    0.05       0  4972.4    0.04       0
  4978.4    0.05       0  5001.2    0.08       0  5199.9     0.1       0
Bank Sta=4972.4,4978.4
Exp/Cntr=0.3,0.1

Type RM Length L Ch R = 1,185,0,0,0
BEGIN DESCRIPTION:
A-2 LOWER 1.0
END DESCRIPTION:
XS GIS Cut Line= 3
      3573522.20     10189400.10      3573900.40     10189507.47
      3574298.59     10189490.45
#Sta/Elev= 30
  4523.2  284.55  4548.1  283.52  4621.1  283.21  4637.4  282.69  4688.9  282.36
  4694.1  281.69  4761.9  281.97  4855.7  280.50  4866.1  280.21  4879.2  278.48
  4886.9  276.52  4907.7  277.32  4913.1  276.76  4919.7  276.90  4934.4  275.90
  4939.4  275.93  4948.1  274.81  4988.1  274.54  4995.1  271.91  4997.9  271.41
  5001.1  271.91  5008.1  273.47  5009.7  274.42  5018.1  279.38  5028.2  281.34
  5048.2  281.13  5078.2  281.94  5148.3  282.93  5268.4  282.32  5314.9  281.67
#Mann=4,-1,0
  4523.2    0.12       0  4995.1    0.07       0  5001.1    0.12       0
  5009.7    0.05       0
Bank Sta=4995.1,5001.1
Exp/Cntr=0.3,0.1

Chan Stop Cuts=-1