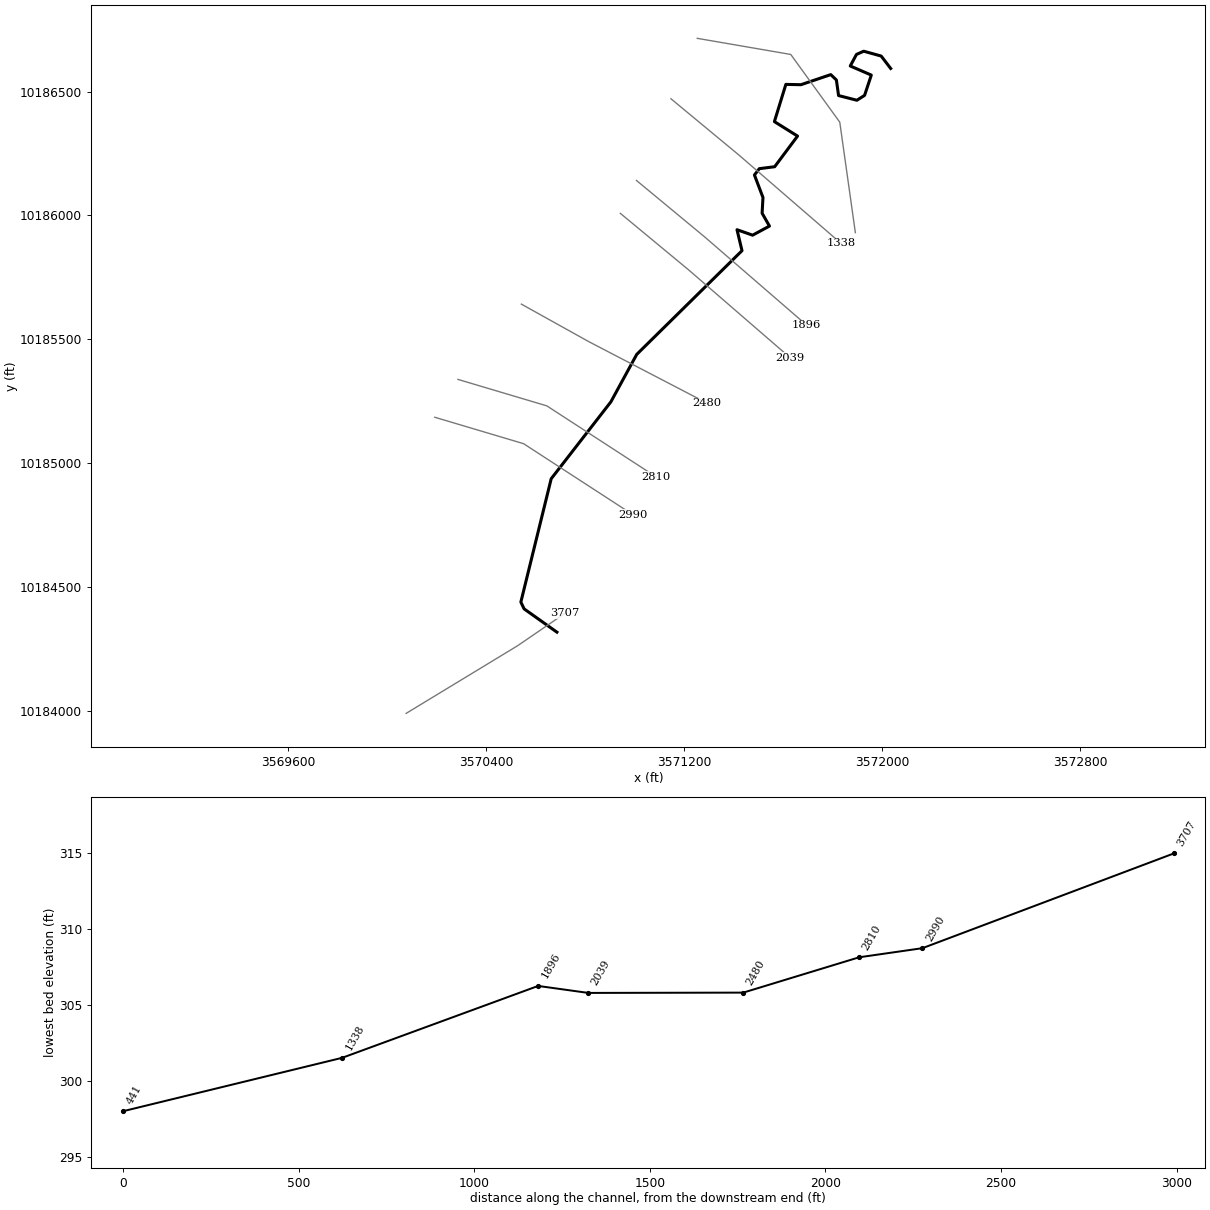
--- A2A.prj (project) ---

Proj Title=A2A Base Level Engineering
Current Plan=p01
Default Exp/Contr=0.3,0.1
English Units
Geom File=g01
Flow File=f01
Plan File=p01
Y Axis Title=Elevation
X Axis Title(PF)=Main Channel Distance
X Axis Title(XS)=Station
BEGIN DESCRIPTION:
A2A
END DESCRIPTION:
DSS Export Rating Curves= 0
DSS Export Rating Curve Sorted= 0
DSS Export Volume Flow Curves= 0
DXF OffsetX= 0
DXF OffsetY= 0
DXF ScaleX= 1
DXF ScaleY= 10

--- A2A.p01 (plan) ---

Plan Title=Multiple Run
Short Identifier=Multiple
Geom File=g01
Flow File=f01
Subcritical Flow
K Sum by GR= 0
Std Step Tol= 0.01
Critical Tol= 0.01
Num of Std Step Trials= 20
Max Error Tol= 0.3
Flow Tol Ratio= 0.001
Split Flow NTrial= 30
Split Flow Tol= 0.02
Split Flow Ratio= 0.02
Log Output Level= 0
Friction Slope Method= 1
Unsteady Friction Slope Method= 2
Unsteady Bridges Friction Slope Method= 1
Parabolic Critical Depth
Global Vel Dist=  1 , 1 , 1
Global Log Level= 0
CheckData=True
Encroach Param= -1, 0, 0, 0
BEGIN DESCRIPTION:
Multiple Run
END DESCRIPTION:

--- A2A.f01 (steady flow) ---

Flow Title=Multiple
Program Version=4.10
Number of Profiles= 7
Profile Names=10-year,25-year,50-year,1pct_min,100-year,1pct_plu,500-year
River Rch & RM=A2A,Reach-1         ,3707
     233     296     345     295     399     540     535
Boundary for River Rch & Prof#=A2A,Reach-1         , 1
Up Type= 0
Dn Type= 1
Dn Known WS=299.71
Boundary for River Rch & Prof#=A2A,Reach-1         , 2
Up Type= 0
Dn Type= 1
Dn Known WS=300.05
Boundary for River Rch & Prof#=A2A,Reach-1         , 3
Up Type= 0
Dn Type= 1
Dn Known WS=300.3
Boundary for River Rch & Prof#=A2A,Reach-1         , 4
Up Type= 0
Dn Type= 1
Dn Known WS=300.13
Boundary for River Rch & Prof#=A2A,Reach-1         , 5
Up Type= 0
Dn Type= 1
Dn Known WS=300.52
Boundary for River Rch & Prof#=A2A,Reach-1         , 6
Up Type= 0
Dn Type= 1
Dn Known WS=300.96
Boundary for River Rch & Prof#=A2A,Reach-1         , 7
Up Type= 0
Dn Type= 1
Dn Known WS=301.01
DSS Import GetInterval= 0
DSS Import GetPeak= 0
DSS Import FillOption= 0

--- A2A.g01 (geometry) ---

Geom Title=Existing Conditions
Program Version=4.10

River Reach=A2A             ,Reach-1
Reach XY= 30
      3570685.68     10184316.99       3570553.2       10184411.
      3570540.06     10184438.55      3570662.62     10184936.62
      3570903.51     10185246.95      3571008.03     10185438.71
      3571433.08     10185857.49       3571412.9     10185942.18
      3571475.94     10185920.07      3571543.91      10185956.8
      3571514.32     10186008.77      3571517.78     10186072.25
       3571483.3     10186163.13      3571502.93     10186188.61
      3571565.06     10186196.55      3571657.37     10186320.21
      3571563.89     10186378.66      3571610.18     10186528.97
      3571671.12     10186527.73      3571791.59     10186568.45
      3571814.26     10186546.74      3571823.04     10186483.89
      3571896.99     10186464.92      3571928.04     10186484.62
      3571955.25     10186566.52      3571870.31     10186603.28
      3571895.26     10186649.94      3571924.56     10186662.96
      3571995.09     10186643.43      3572033.49     10186593.23

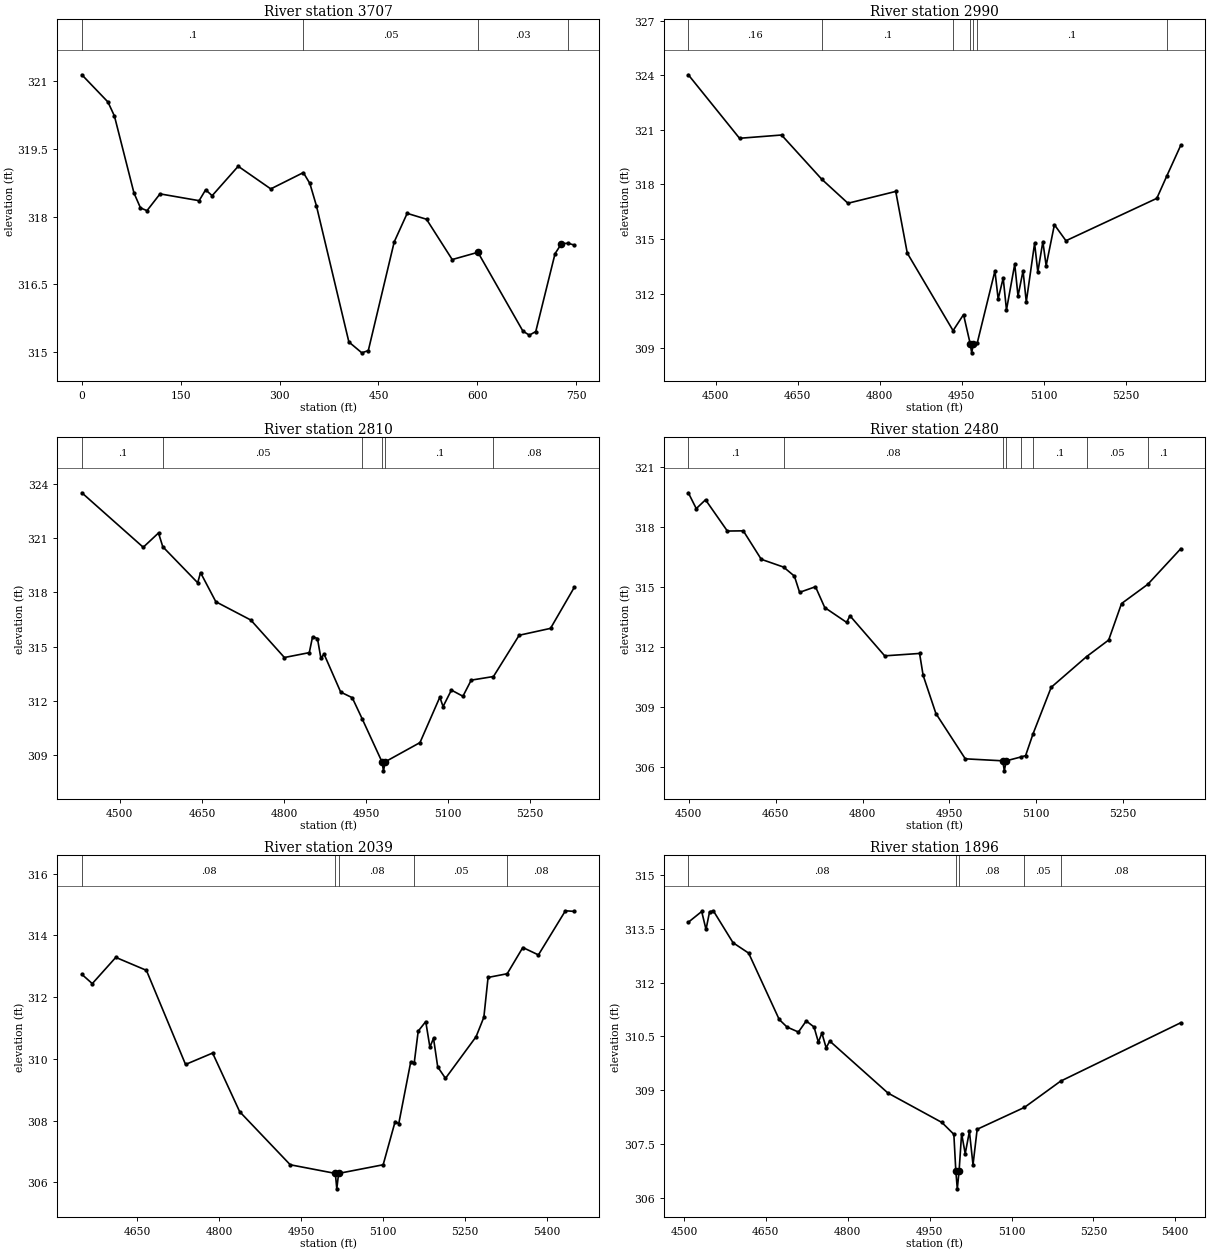
Type RM Length L Ch R = 1 ,3707    ,716,716,716
BEGIN DESCRIPTION:
A2-A 6.0
END DESCRIPTION:
XS GIS Cut Line= 3
     3570076.856    10183989.022     3570527.377     10184262.46
     3570717.481    10184392.668
#Sta/Elev= 30
       0  321.13   39.53  320.53   49.41  320.22   79.06  318.52   88.94  318.19
   98.83  318.13  118.59   318.5  177.89  318.35  187.77  318.59  197.65  318.46
  237.18  319.11   286.6  318.61  336.01  318.97  345.89  318.73  355.78  318.24
  405.08  315.23  424.73  314.99  434.55  315.04  473.86  317.44  493.51  318.07
  522.83  317.94  561.83  317.05  600.83  317.21  669.08  315.47  678.83  315.38
  688.58  315.46  717.83  317.18  727.58   317.4  737.33  317.41  747.08  317.37
#Mann= 4 ,-1 , 0
       0      .1       0  336.01     .05       0  600.83     .03       0
  737.33     .05       0
Bank Sta=600.83,727.58
XS Rating Curve= 0 ,0
Exp/Cntr=0.3,0.1

Type RM Length L Ch R = 1 ,2990    ,180,180,180
BEGIN DESCRIPTION:
A2-A 5.1
END DESCRIPTION:
XS GIS Cut Line= 3
      3570192.41     10185184.82      3570551.05     10185078.11
       3570992.1     10184791.64
#Sta/Elev= 30
  4450.3  324.02  4543.9  320.53  4620.7  320.71  4694.2  318.28  4742.1  316.96
  4829.4  317.61  4850.5  314.22  4934.2  309.96  4953.3  310.84  4965.5  309.24
  4968.2  308.74  4971.5  309.24  4978.2  309.26  5010.7  313.24  5016.6   311.7
  5025.8  312.85  5031.8   311.1  5046.9  313.61  5052.9  311.86  5062.1  313.25
    5068  311.54  5083.2  314.76  5089.1  313.18  5098.3  314.85  5104.3  313.53
  5119.4  315.78  5140.5   314.9  5306.6  317.23  5324.7  318.45  5350.4  320.15
#Mann= 7 ,-1 , 0
  4450.3     .16       0  4694.2      .1       0  4934.2     .05       0
  4965.5     .07       0  4971.5     .05       0  4978.2      .1       0
  5324.7     .05       0
Bank Sta=4965.5,4971.5
XS Rating Curve= 0 ,0
Exp/Cntr=0.3,0.1

Type RM Length L Ch R = 1 ,2810    ,330,330,330
BEGIN DESCRIPTION:
A2-A 5.0
END DESCRIPTION:
XS GIS Cut Line= 3
      3570286.15      10185337.6       3570644.8     10185230.89
      3571085.84     10184944.43
#Sta/Elev= 30
  4430.6   323.5  4542.8  320.49  4570.7  321.28  4578.5  320.52  4642.3  318.53
  4647.5  319.09  4675.5  317.48  4739.4  316.47  4800.8   314.4  4846.3  314.67
  4852.3  315.55  4861.2  315.45  4867.4  314.38  4873.4  314.58  4903.7  312.49
  4924.8  312.18  4942.7  311.03  4979.1  308.64  4981.9  308.14  4985.1  308.64
  5048.6   309.7  5084.9  312.21  5090.8  311.69    5106   312.6  5127.1  312.26
  5142.2  313.15  5182.9  313.35  5229.9  315.63  5287.2  316.01  5330.7  318.28
#Mann= 6 ,-1 , 0
  4430.6      .1       0  4578.5     .05       0  4942.7      .1       0
  4979.1     .07       0  4985.1      .1       0  5182.9     .08       0
Bank Sta=4979.1,4985.1
XS Rating Curve= 0 ,0
Exp/Cntr=0.3,0.1

Type RM Length L Ch R = 1 ,2480    ,441,441,441
BEGIN DESCRIPTION:
A2-A 3.0
END DESCRIPTION:
XS GIS Cut Line= 3
      3570542.13     10185641.63      3570813.91     10185490.39
      3571292.15     10185241.62
#Sta/Elev= 30
  4499.3  319.69    4513   318.9    4529  319.34  4566.7  317.78  4594.2  317.79
  4625.2  316.37  4663.8  315.98  4682.4  315.53  4691.4  314.72  4718.8     315
  4734.8  313.96  4772.6  313.22  4778.3  313.55  4838.3  311.55  4898.5  311.67
  4904.6  310.58  4926.7  308.67  4977.4  306.41    5042  306.31  5044.8  305.81
    5048  306.31  5073.1   306.5  5081.5  306.57  5094.4  307.66  5125.7  309.98
  5186.7  311.51  5224.9  312.34  5247.1  314.16  5292.4  315.12  5349.4   316.9
#Mann= 8 ,-1 , 0
  4499.3      .1       0  4663.8     .08       0    5042     .07       0
    5048     .08       0  5073.1     .05       0  5094.4      .1       0
  5186.7     .05       0  5292.4      .1       0
Bank Sta=5042,5048
XS Rating Curve= 0 ,0
Exp/Cntr=0.3,0.1

Type RM Length L Ch R = 1 ,2039    ,143,143,143
BEGIN DESCRIPTION:
A2-A 1.2
END DESCRIPTION:
XS GIS Cut Line= 3
      3570941.71     10186008.27      3571216.99     10185780.37
      3571628.08      10185424.8
#Sta/Elev= 30
  4548.6  312.74  4567.7  312.44  4610.7  313.29  4666.7  312.87  4738.3  309.82
  4787.8  310.19  4837.3  308.29  4929.8  306.57  5012.3  306.29    5015  305.79
  5018.3  306.29  5099.8  306.57  5121.7  307.97  5128.3   307.9  5150.2   309.9
  5156.7  309.88  5163.9   310.9  5177.7  311.21  5185.3  310.38  5191.9  310.67
  5199.6  309.74  5213.8  309.37  5269.8  310.72    5284  311.35  5291.7  312.64
  5326.7  312.76  5355.3  313.61  5383.8  313.37  5433.2   314.8  5449.5  314.78
#Mann= 5 ,-1 , 0
  4548.6     .08       0  5012.3     .07       0  5018.3     .08       0
  5156.7     .05       0  5326.7     .08       0
Bank Sta=5012.3,5018.3
XS Rating Curve= 0 ,0
Exp/Cntr=0.3,0.1

Type RM Length L Ch R = 1 ,1896    ,558,558,558
BEGIN DESCRIPTION:
A2-A 1.1
END DESCRIPTION:
XS GIS Cut Line= 3
      3571006.81     10186141.13      3571282.05     10185913.27
      3571694.08     10185556.88
#Sta/Elev= 30
    4508  313.68  4532.5  313.98  4540.4  313.48  4546.9  313.97  4553.8     314
  4589.9  313.11  4618.5  312.82  4674.5  310.97  4688.8  310.76  4709.7  310.62
    4724  310.93  4738.3  310.76  4746.2  310.34  4752.7  310.59  4760.5  310.18
    4767  310.37  4873.7  308.92  4972.5   308.1  4994.4  307.77    4998  306.75
  5000.7  306.25    5004  306.75  5008.6  307.79  5015.2  307.23  5022.9  307.85
  5029.5  306.92  5037.1  307.91  5123.7  308.52  5189.8  309.25  5410.1  310.88
#Mann= 5 ,-1 , 0
    4508     .08       0    4998     .07       0    5004     .08       0
  5123.7     .05       0  5189.8     .08       0
Bank Sta=4998,5004
XS Rating Curve= 0 ,0
Exp/Cntr=0.3,0.1

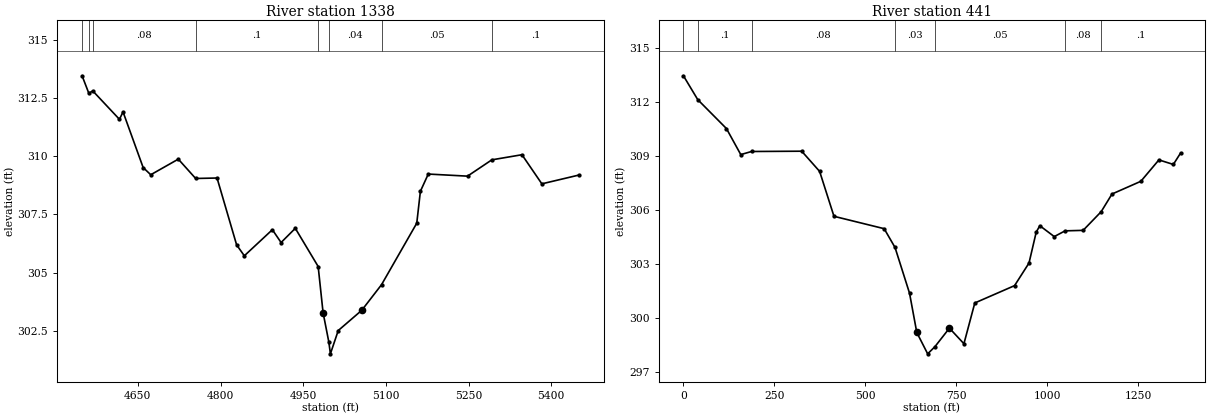
Type RM Length L Ch R = 1 ,1338    ,624,624,624
BEGIN DESCRIPTION:
A2-A 1.3
END DESCRIPTION:
XS GIS Cut Line= 3
      3571146.13     10186470.94      3571421.38     10186243.08
       3571833.4     10185886.69
#Sta/Elev= 30
  4548.8  313.45    4561   312.7  4568.2   312.8  4616.6  311.58  4623.1   311.9
  4659.6  309.51  4673.4   309.2  4723.4  309.87  4754.9  309.04  4793.7  309.06
  4829.2  306.19  4843.2  305.72  4894.1  306.84  4909.9  306.29  4935.7   306.9
  4977.2  305.26  4986.1  303.28  4996.6  302.01  4999.4  301.51  5013.6  302.51
  5056.3  303.38  5092.2  304.48  5156.1  307.12  5162.7  308.49    5177  309.23
  5248.2  309.14  5292.3  309.84    5347  310.06  5383.1  308.81  5450.9  309.19
#Mann= 8 ,-1 , 0
  4548.8     .08       0    4561      .1       0  4568.2     .08       0
  4754.9      .1       0  4977.2     .05       0  4996.6     .04       0
  5092.2     .05       0  5292.3      .1       0
Bank Sta=4986.1,5056.3
XS Rating Curve= 0 ,0
Exp/Cntr=0.3,0.1

Type RM Length L Ch R = 1 ,441     ,0,0,0
BEGIN DESCRIPTION:
A2-A 1.0
END DESCRIPTION:
XS GIS Cut Line= 4
      3571252.42     10186714.96      3571629.98     10186649.86
       3571827.9     10186376.42      3571890.82     10185930.42
#Sta/Elev= 30
       0313.430939.39723312.1049118.1917310.4994157.5889309.0531187.1368309.2257
325.0271309.2421374.2737  308.12413.6709305.6258551.5612304.9388581.4497303.8947
 621.301301.3543641.2266299.1739671.1151297.9877691.0408298.3848730.8921 299.414
770.7434298.5501800.6319300.8134 909.892301.7759949.5541303.0302969.3851304.7472
979.3007305.10341018.963304.49931048.709304.81851098.287304.84581147.865305.8817
1177.611 306.8641256.936307.57091306.513308.75881346.175308.50631366.006 309.137
#Mann= 7 ,-1 , 0
       0     .08       039.39723      .1       0187.1368     .08       0
581.4497     .03       0691.0408     .05       01048.709     .08       0
1147.865      .1       0
Bank Sta=641.2266,730.8921
XS Rating Curve= 0 ,0
Exp/Cntr=0.3,0.1
Stream Node=A2A             ,Reach-1         , 0 , 0 ,Upstream end
Stream Node=A2A             ,Reach-1         , 0 , 1 ,Downstream end

Chan Stop Cuts=-1
Use User Specified Reach Order=0
Composite Channel Slope=5