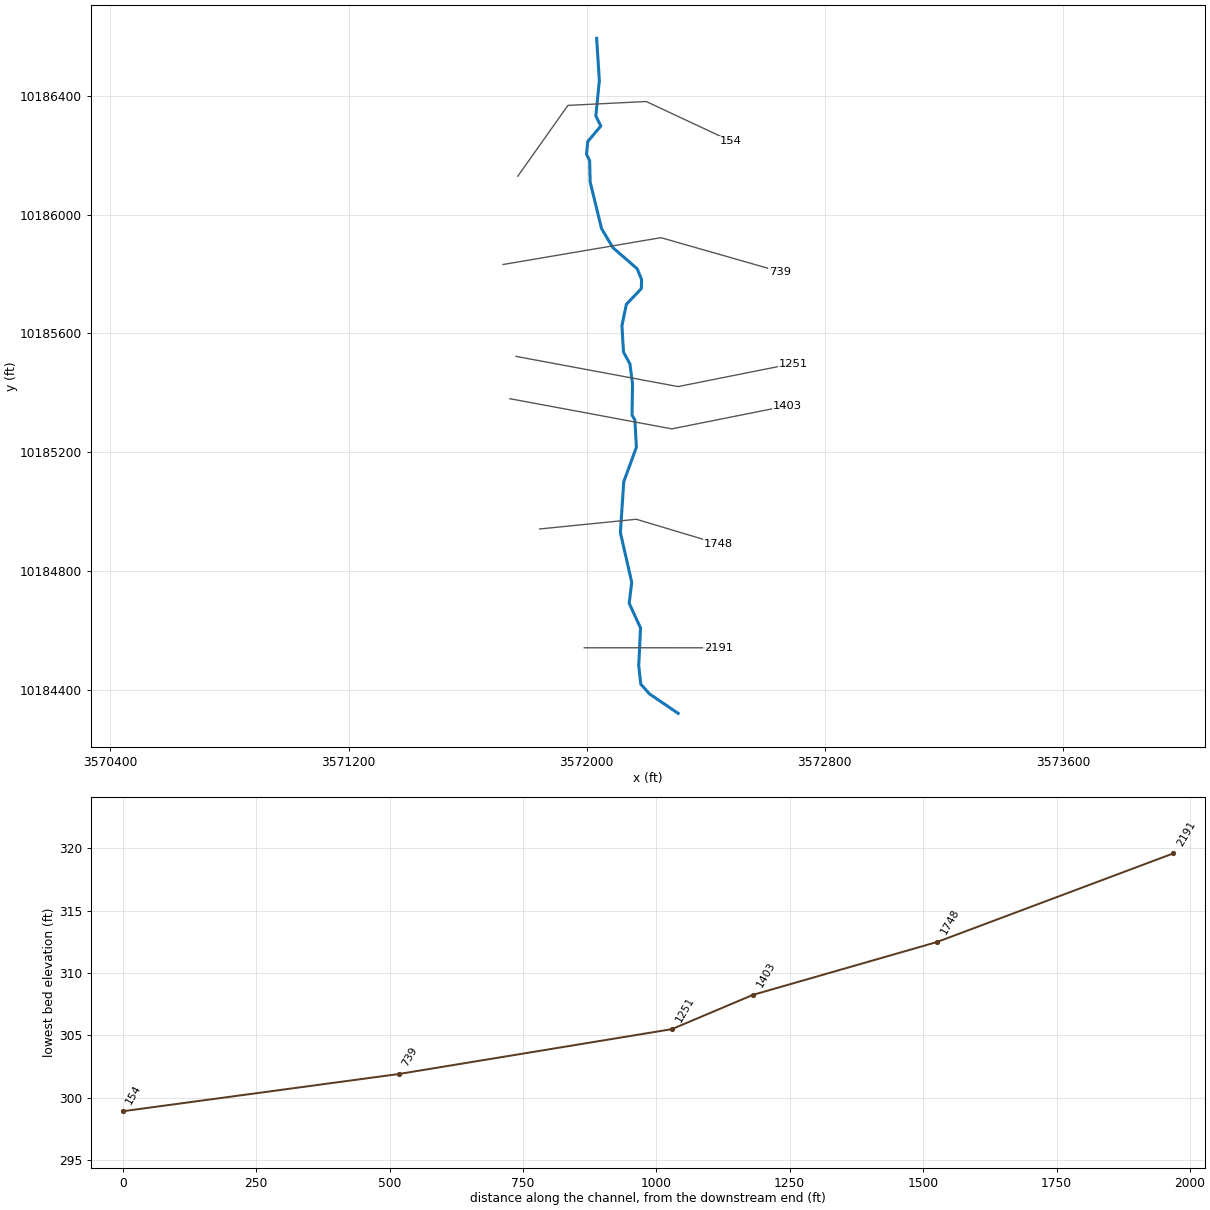
--- A2B.prj (project) ---

Proj Title=A2B Base Level Engineering
Current Plan=p01
Default Exp/Contr=0.3,0.1
English Units
Geom File=g01
Flow File=f01
Plan File=p01
Y Axis Title=Elevation
X Axis Title(PF)=Main Channel Distance
X Axis Title(XS)=Station
BEGIN DESCRIPTION:
A2B
END DESCRIPTION:
DSS Export Rating Curves= 0
DSS Export Rating Curve Sorted= 0
DSS Export Volume Flow Curves= 0
DXF OffsetX= 0
DXF OffsetY= 0
DXF ScaleX= 1
DXF ScaleY= 10

--- A2B.p01 (plan) ---

Plan Title=Multiple Run
Short Identifier=Multiple
Geom File=g01
Flow File=f01
Subcritical Flow
K Sum by GR= 0
Std Step Tol= 0.01
Critical Tol= 0.01
Num of Std Step Trials= 20
Max Error Tol= 0.3
Flow Tol Ratio= 0.001
Split Flow NTrial= 30
Split Flow Tol= 0.02
Split Flow Ratio= 0.02
Log Output Level= 0
Friction Slope Method= 1
Unsteady Friction Slope Method= 2
Unsteady Bridges Friction Slope Method= 1
Parabolic Critical Depth
Global Vel Dist=  1 , 1 , 1
Global Log Level= 0
CheckData=True
Encroach Param= -1, 0, 0, 0
BEGIN DESCRIPTION:
Multiple Run
END DESCRIPTION:

--- A2B.f01 (steady flow) ---

Flow Title=Multiple
Program Version=4.10
Number of Profiles= 7
Profile Names=10-year,25-year,50-year,1pct_min,100-year,1pct_plu,500-year
River Rch & RM=A2B,Reach-1         ,2191
      81      96     106      86     117     158     142
Boundary for River Rch & Prof#=A2B,Reach-1         , 1
Up Type= 0
Dn Type= 1
Dn Known WS=299.71
Boundary for River Rch & Prof#=A2B,Reach-1         , 2
Up Type= 0
Dn Type= 1
Dn Known WS=300.05
Boundary for River Rch & Prof#=A2B,Reach-1         , 3
Up Type= 0
Dn Type= 1
Dn Known WS=300.3
Boundary for River Rch & Prof#=A2B,Reach-1         , 4
Up Type= 0
Dn Type= 1
Dn Known WS=300.13
Boundary for River Rch & Prof#=A2B,Reach-1         , 5
Up Type= 0
Dn Type= 1
Dn Known WS=300.52
Boundary for River Rch & Prof#=A2B,Reach-1         , 6
Up Type= 0
Dn Type= 1
Dn Known WS=300.96
Boundary for River Rch & Prof#=A2B,Reach-1         , 7
Up Type= 0
Dn Type= 1
Dn Known WS=301.01
DSS Import GetInterval= 0
DSS Import GetPeak= 0
DSS Import FillOption= 0

--- A2B.g01 (geometry) ---

Geom Title=Existing Conditions
Program Version=4.10

River Reach=A2B             ,Reach-1
Reach XY= 30
      3572307.42     10184320.88      3572211.35     10184386.12
      3572181.84     10184419.11       3572174.9     10184481.61
      3572180.97     10184608.35      3572142.78     10184691.68
      3572151.46     10184761.99      3572113.26     10184929.53
      3572124.55     10185100.53      3572167.08     10185216.85
      3572161.88     10185308.87      3572152.33     10185325.36
      3572154.06     10185428.66      3572145.38     10185497.23
      3572123.68     10185537.16      3572118.47     10185625.71
      3572133.23     10185697.75      3572183.58     10185750.71
      3572184.45     10185781.09      3572169.69     10185817.55
      3572088.09     10185888.73       3572049.9     10185952.96
       3572011.7     10186110.08      3572009.97     10186181.44
      3571999.55     10186202.96      3572003.72     10186246.02
      3572047.47      10186298.1       3572030.8     10186332.13
       3572042.6     10186450.88      3572033.49     10186593.23

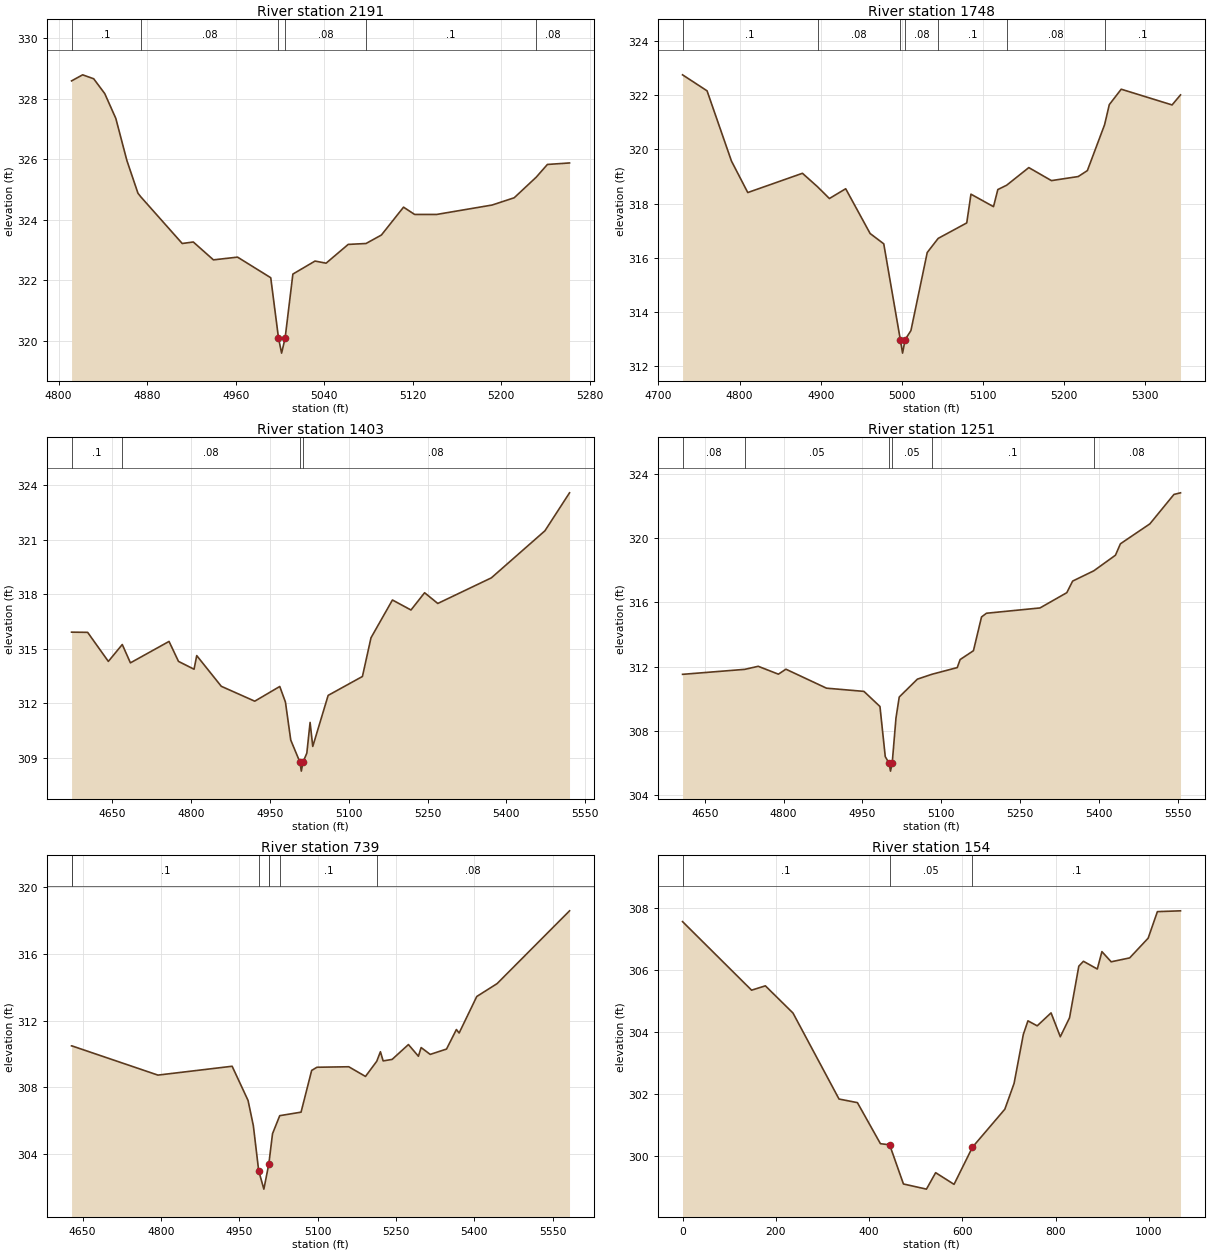
Type RM Length L Ch R = 1 ,2191    ,443,443,443
BEGIN DESCRIPTION:
A2-B 4.0
END DESCRIPTION:
XS GIS Cut Line= 3
      3571992.08     10184541.64      3572123.45     10184541.71
      3572442.08     10184541.64
#Sta/Elev= 30
  4811.7  328.59  4821.7  328.79  4831.7  328.66  4841.7  328.17  4851.7  327.35
  4861.7  325.96  4871.7  324.88  4874.3  324.76  4911.7  323.22  4921.7  323.27
  4939.9  322.68  4961.7  322.77  4991.7  322.09  4998.7   320.1  5001.5   319.6
  5004.7   320.1  5011.7  322.21  5031.7  322.64  5041.7  322.57  5061.7  323.19
  5077.8  323.22  5091.7   323.5  5111.7  324.42  5121.7  324.18  5141.7  324.18
  5191.7  324.49  5211.7  324.73  5231.6  325.41  5241.7  325.83  5261.7  325.88
#Mann= 6 ,-1 , 0
  4811.7      .1       0  4874.3     .08       0  4998.7     .07       0
  5004.7     .08       0  5077.8      .1       0  5231.6     .08       0
Bank Sta=4998.7,5004.7
XS Rating Curve= 0 ,0
Exp/Cntr=0.3,0.1

Type RM Length L Ch R = 1 ,1748    ,345,345,345
BEGIN DESCRIPTION:
A2-B 3.0
END DESCRIPTION:
XS GIS Cut Line= 3
      3571842.06     10184941.64      3572166.72     10184974.32
      3572442.08     10184891.65
#Sta/Elev= 30
  4729.7  322.75  4759.9  322.16    4790  319.57  4810.1  318.41  4877.5  319.12
  4896.2  318.62  4910.7  318.19  4930.8  318.55  4960.9   316.9  4977.7  316.52
  4998.1  312.99  5000.9  312.49  5004.1  312.99  5011.2  313.32  5031.3   316.2
  5044.8  316.72    5080  317.29  5085.2  318.35    5113  317.89  5118.3  318.52
  5129.2  318.68  5156.5  319.33  5184.4  318.85  5217.4     319  5228.7  319.22
  5249.9  320.91  5255.7  321.65  5270.4  322.22  5333.1  321.64  5343.5  322.01
#Mann= 7 ,-1 , 0
  4729.7      .1       0  4896.2     .08       0  4998.1     .07       0
  5004.1     .08       0  5044.8      .1       0  5129.2     .08       0
  5249.9      .1       0
Bank Sta=4998.1,5004.1
XS Rating Curve= 0 ,0
Exp/Cntr=0.3,0.1

Type RM Length L Ch R = 1 ,1403    ,152,152,152
BEGIN DESCRIPTION:
A2-B 2.1
END DESCRIPTION:
XS GIS Cut Line= 3
      3571742.06     10185380.19      3572286.13     10185278.58
      3572672.59     10185355.89
#Sta/Elev= 30
  4572.5   315.9  4603.1  315.89  4642.5  314.29    4669  315.22  4684.5  314.21
    4758  315.39    4776  314.29  4805.6  313.86  4810.7  314.61  4857.4  312.92
  4921.1   312.1  4968.7  312.91  4979.5  312.05  4989.6  309.96    5007  308.75
  5009.7  308.25    5013  308.75  5020.2  309.24  5026.4  310.93  5031.5  309.61
  5060.8  312.42    5126  313.46  5142.3  315.59  5183.1  317.67  5218.4  317.12
  5244.3  318.07  5269.4  317.48  5371.4  318.89  5473.3  321.48  5520.1  323.57
#Mann= 4 ,-1 , 0
  4572.5      .1       0    4669     .08       0    5007     .07       0
    5013     .08       0
Bank Sta=5007,5013
XS Rating Curve= 0 ,0
Exp/Cntr=0.3,0.1

Type RM Length L Ch R = 1 ,1251    ,512,512,512
BEGIN DESCRIPTION:
A2-B 2.0
END DESCRIPTION:
XS GIS Cut Line= 3
      3571762.82     10185522.56      3572306.96     10185420.94
      3572693.45     10185498.26
#Sta/Elev= 30
  4607.7  311.52  4726.1  311.83  4751.7  312.02  4790.1  311.53  4804.4  311.84
  4881.6  310.66  4952.9  310.46  4983.4  309.52  4993.5   306.4  5000.7     306
  5003.5   305.5  5006.7     306  5013.9  308.81  5020.1  310.11  5054.6  311.22
  5081.8  311.52  5130.5  311.94    5136  312.44  5161.3  312.99  5176.7  315.09
  5186.1  315.32    5288  315.65    5339   316.6  5350.1  317.32  5390.4  317.96
  5431.6  318.93    5441  319.64  5497.1  320.88  5542.9  322.71  5555.4  322.81
#Mann= 6 ,-1 , 0
  4607.7     .08       0  4726.1     .05       0  5000.7     .04       0
  5006.7     .05       0  5081.8      .1       0  5390.4     .08       0
Bank Sta=5000.7,5006.7
XS Rating Curve= 0 ,0
Exp/Cntr=0.3,0.1

Type RM Length L Ch R = 1 ,739     ,517,517,517
BEGIN DESCRIPTION:
A2-B 1.1
END DESCRIPTION:
XS GIS Cut Line= 3
      3571719.12     10185831.89      3572249.56     10185922.21
      3572648.44     10185807.96
#Sta/Elev= 30
    4629  310.48  4629.6  310.48  4794.3  308.73  4936.3  309.26  4966.8  307.21
  4976.9   305.7  4987.1  303.01    4997   301.9  5006.5   303.4  5013.6  305.22
  5027.4   306.3  5068.2  306.51  5088.5  309.01  5098.6   309.2  5159.5  309.23
  5191.5  308.65  5213.1  309.56  5220.1  310.13  5225.3  309.58  5242.5  309.67
  5273.7  310.56  5292.8  309.86    5298  310.38  5315.4  309.97  5346.6  310.29
  5365.5  311.46  5370.7  311.25  5404.5  313.44  5443.4  314.21    5582  318.57
#Mann= 7 ,-1 , 0
    4629     .08       0  4629.6      .1       0  4987.1     .07       0
  5006.5      .1       0  5006.5     .05       0  5027.4      .1       0
  5213.1     .08       0
Bank Sta=4987.1,5006.5
XS Rating Curve= 0 ,0
Exp/Cntr=0.3,0.1

Type RM Length L Ch R = 1 ,154     ,0,0,0
BEGIN DESCRIPTION:
A2-B 1.0
END DESCRIPTION:
XS GIS Cut Line= 4
      3571768.74     10186129.24      3571937.06     10186367.52
      3572200.08     10186380.55      3572484.01     10186247.35
#Sta/Elev= 30
       0307.5637148.0021305.3472177.6026 305.488236.8034304.6081335.4715301.8283
374.9387301.7111424.2728300.3839444.0064 300.348473.6068299.0813522.9209298.9151
542.6445299.4467582.0918299.0699621.5895300.2713690.9758301.4982710.8005302.3333
730.6251303.9157740.5374304.3563760.3621304.1948 790.099304.6132809.9236303.8418
829.7483304.4567849.5729306.1226859.4853306.2819889.2222306.0317899.1346306.5941
918.9592306.2653958.6085306.3908998.2578307.02861018.082307.88691067.644 307.913
#Mann= 3 , 0 , 0
       0      .1       0444.0064     .05       0621.5895      .1       0
Bank Sta=444.0064,621.5895
XS Rating Curve= 0 ,0
Exp/Cntr=0.3,0.1
Stream Node=A2B             ,Reach-1         , 0 , 0 ,Upstream end
Stream Node=A2B             ,Reach-1         , 0 , 1 ,Downstream end

Chan Stop Cuts=-1
Use User Specified Reach Order=0
Composite Channel Slope=5