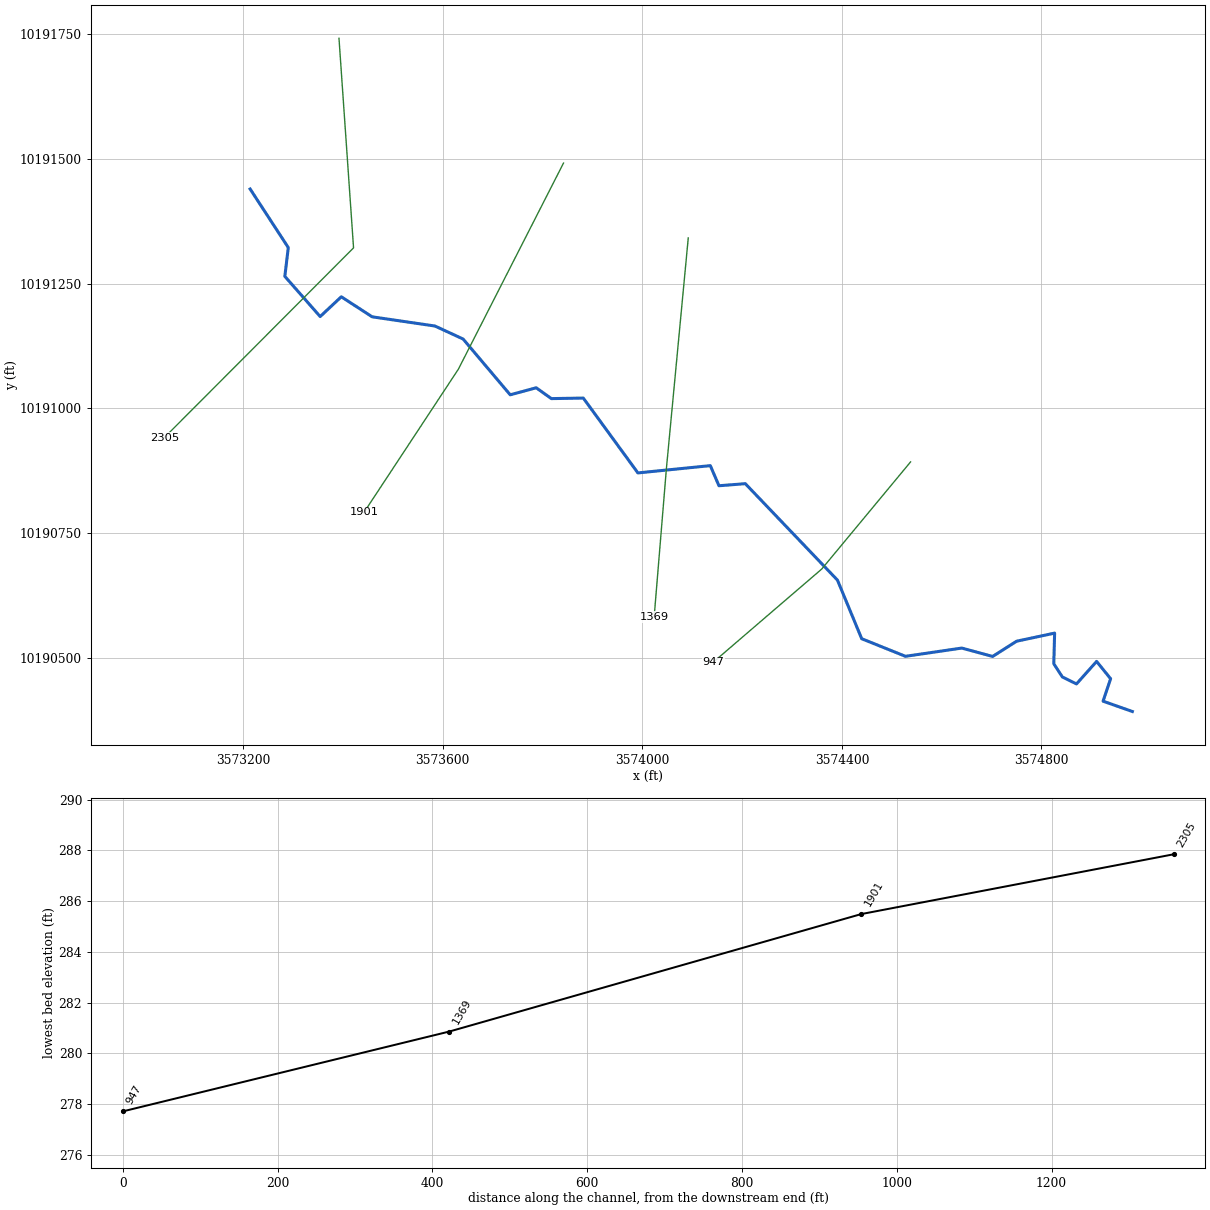
--- A-3 TRIB.prj (project) ---

Proj Title=A-3 TRIB Base Level Engineering
Current Plan=p01
Default Exp/Contr=0.3,0.1
English Units
Geom File=g01
Flow File=f01
Plan File=p01
BEGIN DESCRIPTION:
A-3 TRIB
END DESCRIPTION:

--- A-3 TRIB.p01 (plan) ---

Plan Title=Multiple Run
Short Identifier=Multiple
Geom File=g01
Flow File=f01
Subcritical Flow
K Sum by GR= 0
Std Step Tol= 0.01
Critical Tol= 0.01
Num of Std Step Trials= 20
Max Error Tol= 0.3
Flow Tol Ratio= 0.001
Split Flow NTrial= 30
Split Flow Tol= 0.02
Split Flow Ratio= 0.02
Log Output Level= 0
Friction Slope Method= 1
Unsteady Friction Slope Method= 2
Unsteady Bridges Friction Slope Method= 1
Parabolic Critical Depth
Global Vel Dist=  1 , 1 , 1
Global Log Level= 0
CheckData=True
Encroach Param= -1, 0, 0, 0
BEGIN DESCRIPTION:
Multiple Run
END DESCRIPTION:

--- A-3 TRIB.f01 (steady flow) ---

Flow Title=Multiple
Number of Profiles=7
Profile Names=10-year,25-year,50-year,1pct_min,100-year,1pct_plu,500-year
River Rch & RM= A-3 TRIB,Reach-1,2305
     134     163     185     155     209     283     267
Boundary for River Rch & Prof#=A-3 TRIB,Reach-1,1
Up Type=0
Dn Type=3
Dn Slope=0.005
Boundary for River Rch & Prof#=A-3 TRIB,Reach-1,2
Up Type=0
Dn Type=3
Dn Slope=0.005
Boundary for River Rch & Prof#=A-3 TRIB,Reach-1,3
Up Type=0
Dn Type=3
Dn Slope=0.005
Boundary for River Rch & Prof#=A-3 TRIB,Reach-1,4
Up Type=0
Dn Type=3
Dn Slope=0.005
Boundary for River Rch & Prof#=A-3 TRIB,Reach-1,5
Up Type=0
Dn Type=3
Dn Slope=0.005
Boundary for River Rch & Prof#=A-3 TRIB,Reach-1,6
Up Type=0
Dn Type=3
Dn Slope=0.005
Boundary for River Rch & Prof#=A-3 TRIB,Reach-1,7
Up Type=0
Dn Type=3
Dn Slope=0.005

--- A-3 TRIB.g01 (geometry) ---

Geom Title=Existing Conditions

River Reach=A-3 TRIB,Reach-1
Reach XY= 30
      3573214.03     10191439.64      3573290.52     10191322.30
      3573283.57     10191264.66      3573354.41     10191184.11
      3573396.74     10191223.74      3573458.59     10191183.60
      3573584.46     10191165.15      3573640.88     10191139.11
      3573735.28     10191027.35      3573787.36     10191041.45
      3573817.75     10191019.75      3573881.77     10191020.83
      3573991.16     10190870.88      3574136.29     10190885.47
      3574153.66     10190845.19      3574206.43     10190849.35
      3574391.14     10190656.09      3574439.72     10190538.73
      3574527.42     10190503.50      3574640.30     10190520.02
      3574702.13     10190503.25      3574750.06     10190533.74
      3574826.33     10190549.98      3574824.67     10190488.58
      3574841.83     10190462.12      3574870.18     10190448.18
      3574910.49     10190493.30      3574938.56     10190458.57
      3574923.41     10190413.62      3574982.11     10190392.96

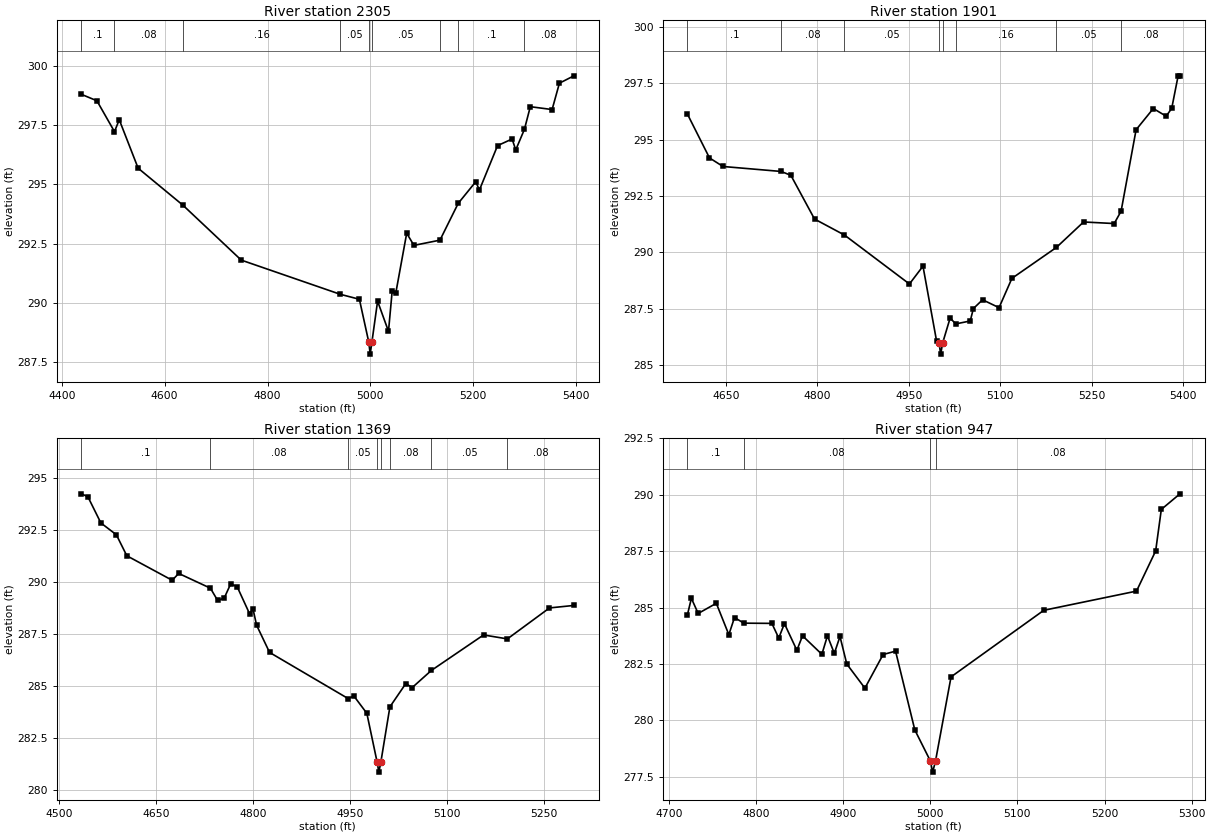
Type RM Length L Ch R = 1,2305,404,404,404
BEGIN DESCRIPTION:
A-3 TRIB 4.0
END DESCRIPTION:
XS GIS Cut Line= 3
      3573392.10     10191741.65      3573421.30     10191321.74
      3573042.13     10190941.66
#Sta/Elev= 30
  4438.1  298.79  4468.2  298.52  4502.4  297.22  4511.7  297.72  4548.4  295.68
  4635.6  294.12  4748.9  291.81  4941.5  290.37  4978.7  290.16  4997.0  288.35
  4999.7  287.85  5003.0  288.35  5014.1  290.08  5035.3  288.81  5042.4  290.49
  5049.4  290.41  5070.7  292.94  5084.8  292.43  5135.4  292.65  5170.9  294.20
  5205.0  295.11  5212.1  294.76  5247.4  296.63  5275.7  296.91  5282.8  296.45
  5299.7  297.32  5311.1  298.27  5353.5  298.15  5367.7  299.26  5395.9  299.57
#Mann=9,-1,0
  4438.1     0.1       0  4502.4    0.08       0  4635.6    0.16       0
  4941.5    0.05       0  4997.0    0.04       0  5003.0    0.05       0
  5135.4    0.08       0  5170.9     0.1       0  5299.7    0.08       0
Bank Sta=4997,5003
Exp/Cntr=0.3,0.1

Type RM Length L Ch R = 1,1901,532,532,532
BEGIN DESCRIPTION:
A-3 TRIB 3.0
END DESCRIPTION:
XS GIS Cut Line= 3
      3573842.09     10191491.61      3573631.37     10191078.68
      3573442.11     10190791.65
#Sta/Elev= 30
  4587.3  296.13  4623.4  294.19  4645.6  293.81  4740.7  293.59  4756.8  293.42
  4795.6  291.48  4844.7  290.77  4951.2  288.60  4973.4  289.39  4995.7  286.07
  4999.7  285.99  5002.4  285.49  5005.7  285.99  5017.9  287.09  5027.1  286.83
  5050.9  286.96  5056.0  287.51  5071.1  287.90  5098.1  287.55  5119.2  288.85
  5192.1  290.22  5236.7  291.35  5286.9  291.28  5298.2  291.83  5322.8  295.44
  5351.0  296.38  5372.1  296.04  5381.2  296.39  5391.7  297.83  5394.7  297.83
#Mann=8,-1,0
  4587.3     0.1       0  4740.7    0.08       0  4844.7    0.05       0
  4999.7    0.04       0  5005.7    0.05       0  5027.1    0.16       0
  5192.1    0.05       0  5298.2    0.08       0
Bank Sta=4999.7,5005.7
Exp/Cntr=0.3,0.1

Type RM Length L Ch R = 1,1369,422,422,422
BEGIN DESCRIPTION:
A-3 TRIB 2.0
END DESCRIPTION:
XS GIS Cut Line= 3
      3574092.10     10191341.61      3574048.26     10190879.28
      3574023.73     10190582.19
#Sta/Elev= 30
  4534.4  294.25  4544.4  294.11  4564.5  292.85  4588.5  292.28  4604.7  291.27
  4675.0  290.09  4685.0  290.42  4734.1  289.71  4745.3  289.12  4755.4  289.23
  4765.4  289.91  4775.4  289.79  4794.9  288.47  4799.9  288.73  4805.6  287.93
  4825.7  286.62  4947.3  284.40  4956.3  284.52  4976.3  283.69  4992.1  281.36
  4994.9  280.86  4998.1  281.36  5012.0  284.00  5036.6  285.12  5046.6  284.93
  5076.1  285.75  5157.0  287.46  5193.9  287.27  5259.1  288.76  5296.9  288.88
#Mann=8,-1,0
  4534.4     0.1       0  4734.1    0.08       0  4947.3    0.05       0
  4992.1    0.04       0  4998.1    0.05       0  5012.0    0.08       0
  5076.1    0.05       0  5193.9    0.08       0
Bank Sta=4992.1,4998.1
Exp/Cntr=0.3,0.1

Type RM Length L Ch R = 1,947,0,0,0
BEGIN DESCRIPTION:
A-3 TRIB 1.0
END DESCRIPTION:
XS GIS Cut Line= 3
      3574537.62     10190892.92      3574359.60     10190678.35
      3574142.14     10190491.67
#Sta/Elev= 30
  4721.2  284.69  4725.7  285.41  4733.5  284.74  4754.3  285.19  4768.7  283.80
  4775.2  284.56  4785.9  284.31  4818.1  284.30  4826.0  283.65  4832.5  284.29
  4846.8  283.11  4853.3  283.75  4875.5  282.93  4881.9  283.75  4889.8  282.97
  4896.3  283.72  4904.1  282.50  4924.9  281.43  4945.8  282.92  4960.1  283.07
  4982.2  279.58  5000.0  278.21  5002.7  277.71  5006.0  278.21  5023.8  281.93
  5130.3  284.88  5236.7  285.73  5258.7  287.51  5265.2  289.35  5286.6  290.04
#Mann=4,-1,0
  4721.2     0.1       0  4785.9    0.08       0  5000.0    0.07       0
  5006.0    0.08       0
Bank Sta=5000,5006
Exp/Cntr=0.3,0.1

Chan Stop Cuts=-1