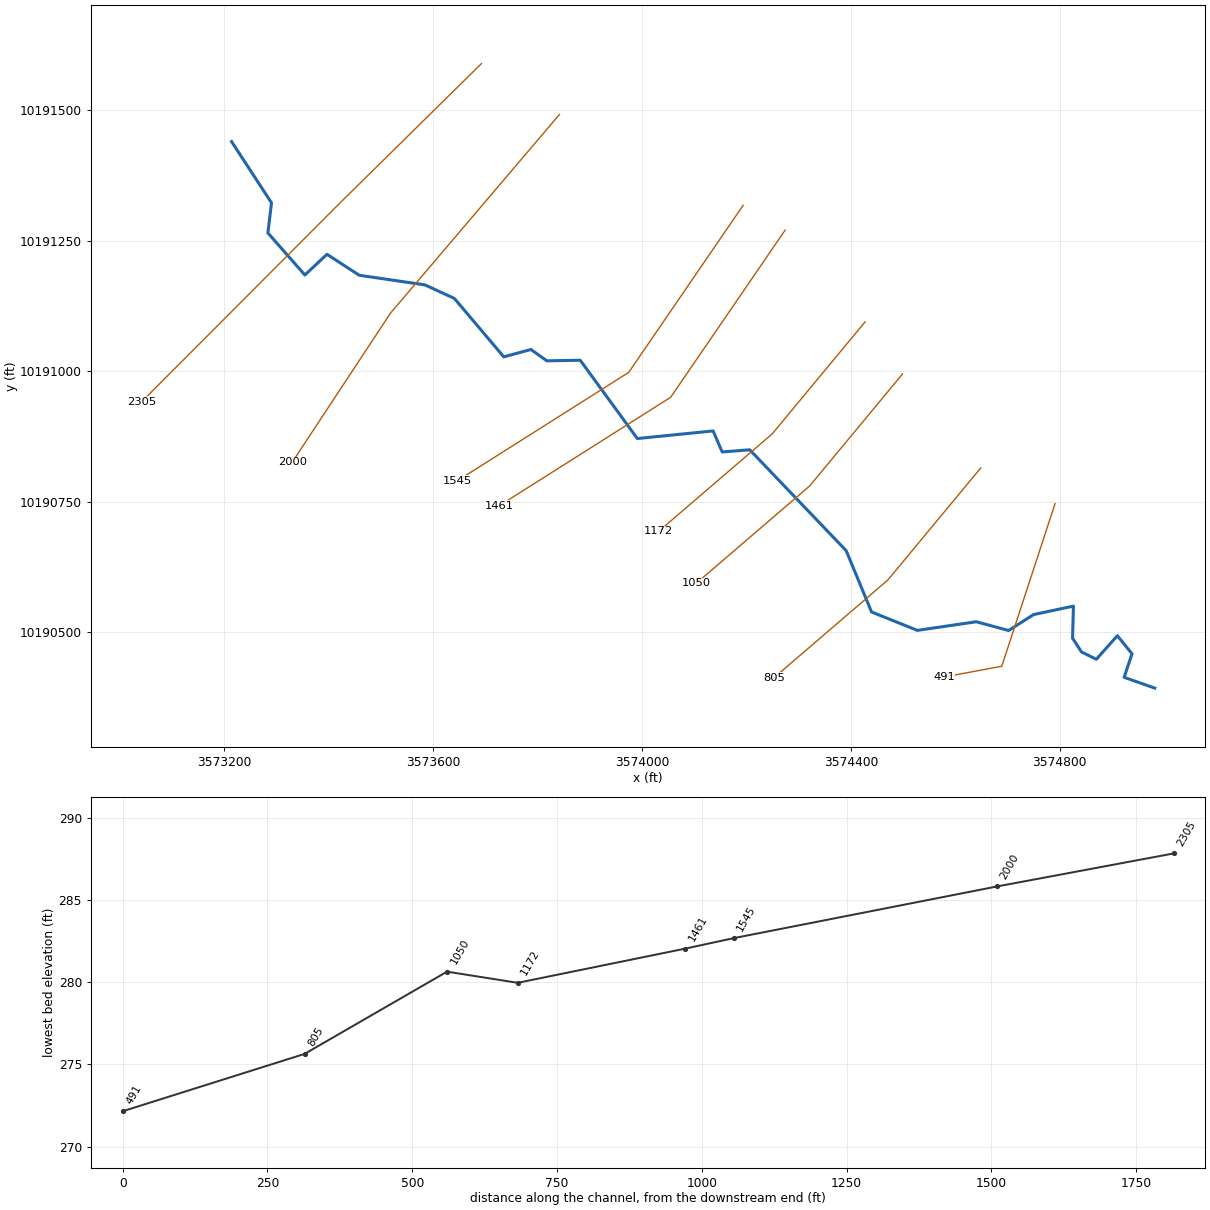
--- A3 TRIB.prj (project) ---

Proj Title=A3 TRIB Base Level Engineering
Current Plan=p01
Default Exp/Contr=0.3,0.1
English Units
Geom File=g01
Flow File=f01
Plan File=p01
Y Axis Title=Elevation
X Axis Title(PF)=Main Channel Distance
X Axis Title(XS)=Station
BEGIN DESCRIPTION:
A3 TRIB
END DESCRIPTION:
DSS Export Rating Curves= 0
DSS Export Rating Curve Sorted= 0
DSS Export Volume Flow Curves= 0
DXF OffsetX= 0
DXF OffsetY= 0
DXF ScaleX= 1
DXF ScaleY= 10

--- A3 TRIB.p01 (plan) ---

Plan Title=Multiple Run
Short Identifier=Multiple
Geom File=g01
Flow File=f01
Subcritical Flow
K Sum by GR= 0
Std Step Tol= 0.01
Critical Tol= 0.01
Num of Std Step Trials= 20
Max Error Tol= 0.3
Flow Tol Ratio= 0.001
Split Flow NTrial= 30
Split Flow Tol= 0.02
Split Flow Ratio= 0.02
Log Output Level= 0
Friction Slope Method= 1
Unsteady Friction Slope Method= 2
Unsteady Bridges Friction Slope Method= 1
Parabolic Critical Depth
Global Vel Dist=  1 , 1 , 1
Global Log Level= 0
CheckData=True
Encroach Param= -1, 0, 0, 0
BEGIN DESCRIPTION:
Multiple Run
END DESCRIPTION:

--- A3 TRIB.f01 (steady flow) ---

Flow Title=Multiple
Number of Profiles=7
Profile Names=10-year,25-year,50-year,1pct_min,100-year,1pct_plu,500-year
River Rch & RM= A3 TRIB,Reach-1,2305
     134     163     185     155     209     283     267
Boundary for River Rch & Prof#=A3 TRIB,Reach-1,1
Up Type=0
Dn Type=3
Dn Slope=0.005
Boundary for River Rch & Prof#=A3 TRIB,Reach-1,2
Up Type=0
Dn Type=3
Dn Slope=0.005
Boundary for River Rch & Prof#=A3 TRIB,Reach-1,3
Up Type=0
Dn Type=3
Dn Slope=0.005
Boundary for River Rch & Prof#=A3 TRIB,Reach-1,4
Up Type=0
Dn Type=3
Dn Slope=0.005
Boundary for River Rch & Prof#=A3 TRIB,Reach-1,5
Up Type=0
Dn Type=3
Dn Slope=0.005
Boundary for River Rch & Prof#=A3 TRIB,Reach-1,6
Up Type=0
Dn Type=3
Dn Slope=0.005
Boundary for River Rch & Prof#=A3 TRIB,Reach-1,7
Up Type=0
Dn Type=3
Dn Slope=0.005

--- A3 TRIB.g01 (geometry) ---

Geom Title=Existing Conditions
Program Version=4.10

River Reach=A3 TRIB         ,Reach-1
Reach XY= 30
      3573214.03     10191439.64      3573290.52      10191322.3
      3573283.57     10191264.66      3573354.41     10191184.11
      3573396.74     10191223.74      3573458.59      10191183.6
      3573584.46     10191165.15      3573640.88     10191139.11
      3573735.28     10191027.35      3573787.36     10191041.45
      3573817.75     10191019.75      3573881.77     10191020.83
      3573991.16     10190870.88      3574136.29     10190885.47
      3574153.66     10190845.19      3574206.43     10190849.35
      3574391.14     10190656.09      3574439.72     10190538.73
      3574527.42      10190503.5       3574640.3     10190520.02
      3574702.13     10190503.25      3574750.06     10190533.74
      3574826.33     10190549.98      3574824.67     10190488.58
      3574841.83     10190462.12      3574870.18     10190448.18
      3574910.49      10190493.3      3574938.56     10190458.57
      3574923.41     10190413.62      3574982.11     10190392.96

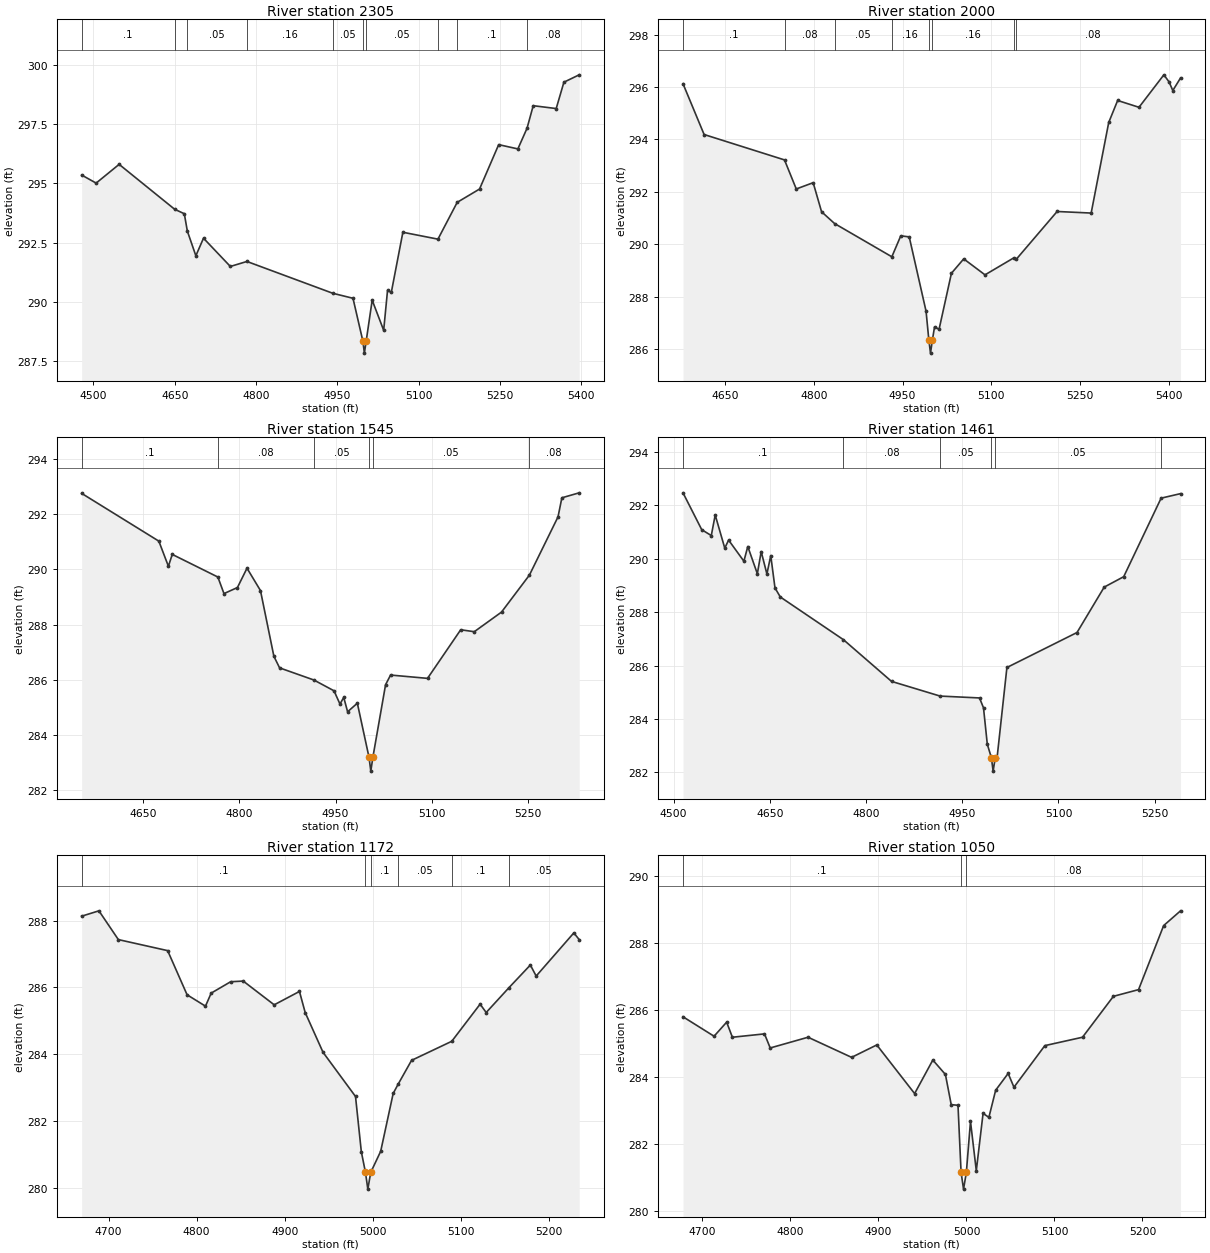
Type RM Length L Ch R = 1 ,2305    ,305,305,305
BEGIN DESCRIPTION:
A-3 TRIB 4.0
END DESCRIPTION:
XS GIS Cut Line= 3
      3573692.52     10191588.94       3573421.3     10191321.74
      3573042.13     10190941.66
#Sta/Elev= 30
  4478.3  295.35    4505  295.01  4547.4   295.8  4649.7  293.91  4667.6  293.72
  4673.2  292.99  4688.9  291.95    4703  292.69  4752.5   291.5  4783.1  291.71
  4941.5  290.37  4978.7  290.16    4997  288.35  4999.7  287.85    5003  288.35
  5014.1  290.08  5035.3  288.81  5042.4  290.49  5049.4  290.41  5070.7  292.94
  5135.4  292.65  5170.9   294.2  5212.1  294.76  5247.4  296.63  5282.8  296.45
  5299.7  297.32  5311.1  298.27  5353.5  298.15  5367.7  299.26  5395.9  299.57
#Mann= 10 ,-1 , 0
  4478.3      .1       0  4649.7     .08       0  4673.2     .05       0
  4783.1     .16       0  4941.5     .05       0    4997     .04       0
    5003     .05       0  5135.4     .08       0  5170.9      .1       0
  5299.7     .08       0
Bank Sta=4997,5003
XS Rating Curve= 0 ,0
Exp/Cntr=0.3,0.1

Type RM Length L Ch R = 1 ,2000    ,455,455,455
BEGIN DESCRIPTION:
A-3 TRIB 3.0
END DESCRIPTION:
XS GIS Cut Line= 3
      3573842.08     10191491.61      3573518.52     10191111.23
      3573330.08     10190825.44
#Sta/Elev= 30
  4578.6  296.13  4614.3  294.19  4750.3  293.22  4770.2  292.11  4798.8  292.35
    4813  291.24    4835  290.79  4931.9  289.52    4947  290.32  4961.3  290.28
  4989.8  287.44  4994.5  286.34  4997.3  285.84  5000.5  286.34  5004.1  286.84
  5011.8  286.75  5032.7  288.89  5053.5  289.44  5089.5  288.83  5138.3  289.48
  5142.6  289.43  5211.5  291.25  5269.1  291.19  5298.8  294.65  5313.9  295.49
    5350  295.23  5392.1  296.47  5400.9   296.2  5407.2  295.87  5420.3  296.35
#Mann= 9 ,-1 , 0
  4578.6      .1       0  4750.3     .08       0    4835     .05       0
  4931.9     .16       0  4994.5     .07       0  5000.5     .16       0
  5138.3     .05       0  5142.6     .08       0  5400.9      .1       0
Bank Sta=4994.5,5000.5
XS Rating Curve= 0 ,0
Exp/Cntr=0.3,0.1

Type RM Length L Ch R = 1 ,1545    ,84,84,84
BEGIN DESCRIPTION:
A-3 TRIB 2.1
END DESCRIPTION:
XS GIS Cut Line= 3
      3574193.82     10191317.66      3573974.67     10190997.65
      3573647.07     10190790.41
#Sta/Elev= 30
  4554.2  292.75  4674.5  291.02  4689.4  290.11  4695.4  290.54  4766.5  289.72
    4776  289.12    4797  289.34  4811.9  290.04  4832.9  289.23  4853.8  286.85
  4862.7  286.43  4916.2  285.99  4947.5   285.6  4956.8  285.12  4962.7  285.36
  4968.7  284.84  4983.9  285.15  5002.1  283.19  5004.9  282.69  5008.1  283.19
  5027.9  285.82  5035.7  286.17  5093.3  286.05    5145  287.81  5166.2  287.74
  5208.6  288.45  5252.1  289.79  5296.7   291.9  5302.7  292.59  5329.7  292.77
#Mann= 6 ,-1 , 0
  4554.2      .1       0  4766.5     .08       0  4916.2     .05       0
  5002.1     .04       0  5008.1     .05       0  5252.1     .08       0
Bank Sta=5002.1,5008.1
XS Rating Curve= 0 ,0
Exp/Cntr=0.3,0.1

Type RM Length L Ch R = 1 ,1461    ,289,289,289
BEGIN DESCRIPTION:
A-3 TRIB 2.0
END DESCRIPTION:
XS GIS Cut Line= 3
      3574274.14     10191269.95      3574054.96     10190949.91
      3573727.23     10190742.59
#Sta/Elev= 30
  4514.6  292.47  4543.8  291.09  4558.7  290.87  4564.8  291.64  4579.7   290.4
  4585.7   290.7  4609.5  289.91  4615.6  290.46  4630.5  289.44  4636.5  290.27
  4645.4  289.43  4651.4  290.12    4658  288.91  4666.3  288.57  4764.8  286.97
  4839.7  285.41  4915.4  284.86  4976.9  284.79  4983.1  284.42    4989  283.06
  4995.4  282.55  4998.1  282.05  5001.4  282.55  5004.3  282.56  5019.6  285.93
  5128.9  287.24  5171.3  288.94  5201.7  289.33    5260  292.27  5290.3  292.44
#Mann= 6 ,-1 , 0
  4514.6      .1       0  4764.8     .08       0  4915.4     .05       0
  4995.4     .04       0  5001.4     .05       0    5260     .08       0
Bank Sta=4995.4,5001.4
XS Rating Curve= 0 ,0
Exp/Cntr=0.3,0.1

Type RM Length L Ch R = 1 ,1172    ,122,122,122
BEGIN DESCRIPTION:
A-3 TRIB 1.2
END DESCRIPTION:
XS GIS Cut Line= 3
      3574427.39     10191094.34       3574249.4     10190879.79
      3574031.91     10190693.09
#Sta/Elev= 30
  4669.3  288.13  4688.9  288.29    4711  287.43    4767   287.1  4789.1  285.78
    4810  285.44  4816.5  285.83  4838.6  286.17  4852.9  286.19  4888.1  285.48
  4916.8  285.88  4923.3  285.25  4943.6  284.06  4980.5  282.74  4987.1  281.09
  4991.8  280.47  4994.5  279.97  4997.8  280.47  5009.1   281.1  5023.3  282.83
    5029  283.11  5044.2  283.82  5089.9  284.39  5122.1   285.5    5129  285.25
  5154.8  285.99  5179.2  286.67  5185.8  286.34  5228.6  287.63  5234.7  287.43
#Mann= 6 ,-1 , 0
  4669.3      .1       0  4991.8     .07       0  4997.8      .1       0
    5029     .05       0  5089.9      .1       0  5154.8     .05       0
Bank Sta=4991.8,4997.8
XS Rating Curve= 0 ,0
Exp/Cntr=0.3,0.1

Type RM Length L Ch R = 1 ,1050    ,246,246,246
BEGIN DESCRIPTION:
A-3 TRIB 1.1
END DESCRIPTION:
XS GIS Cut Line= 3
      3574499.03     10190994.53      3574321.01     10190779.96
      3574103.55     10190593.28
#Sta/Elev= 30
  4677.9  285.79  4713.2  285.21  4727.5  285.63    4734  285.18  4770.5  285.28
    4777  284.86    4820  285.18  4869.5  284.58  4898.1  284.95  4941.1   283.5
  4961.8   284.5  4976.1  284.07  4982.7  283.17  4990.4  283.15  4993.9  281.15
  4996.7  280.65  4999.9  281.15  5004.6  282.67  5011.2   281.2  5018.9  282.91
  5025.5  282.79  5033.2   283.6  5047.4   284.1    5054  283.69  5089.1  284.93
  5131.9  285.18    5167   286.4  5195.6   286.6  5224.1  288.51  5243.3  288.95
#Mann= 3 ,-1 , 0
  4677.9      .1       0  4993.9     .07       0  4999.9     .08       0
Bank Sta=4993.9,4999.9
XS Rating Curve= 0 ,0
Exp/Cntr=0.3,0.1

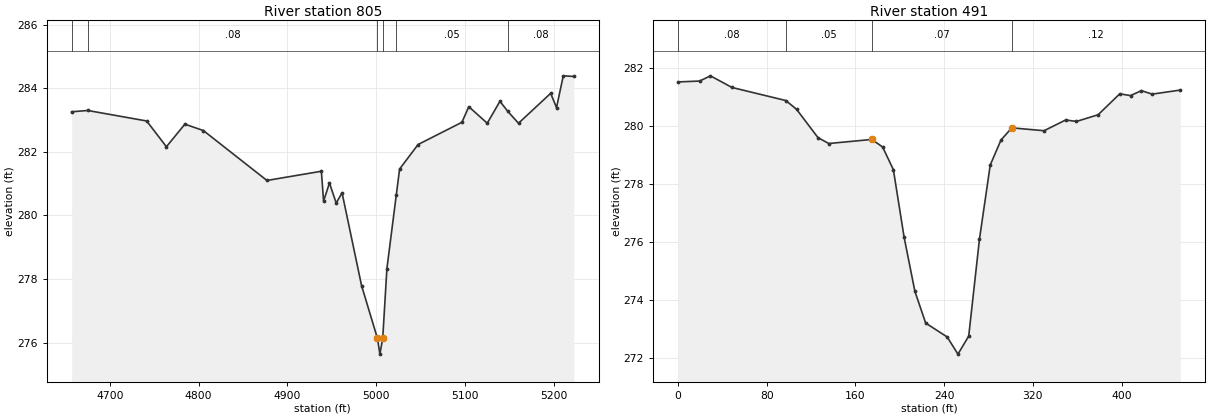
Type RM Length L Ch R = 1 ,805     ,314,314,314
BEGIN DESCRIPTION:
A-3 TRIB 1.0
END DESCRIPTION:
XS GIS Cut Line= 3
      3574648.77     10190814.42      3574470.75     10190599.84
      3574253.22     10190413.11
#Sta/Elev= 30
    4657  283.26  4675.2   283.3  4741.5  282.97  4763.7  282.16  4784.5  282.87
  4805.3  282.67  4876.9   281.1  4938.2  281.39  4940.7  280.45  4947.3  281.02
  4954.9  280.39  4961.5  280.71  4983.5  277.79  5001.3  276.14  5004.1  275.64
  5007.3  276.14    5012  278.33  5022.5  280.63  5026.3  281.46  5047.1  282.23
  5096.5  282.93  5104.2  283.42    5125   282.9  5139.3  283.59  5148.2  283.27
  5160.2   282.9  5196.4  283.84    5203  283.39  5210.6  284.39  5222.5  284.37
#Mann= 6 ,-1 , 0
    4657      .1       0  4675.2     .08       0  5001.3     .07       0
  5007.3     .08       0  5022.5     .05       0  5148.2     .08       0
Bank Sta=5001.3,5007.3
XS Rating Curve= 0 ,0
Exp/Cntr=0.3,0.1

Type RM Length L Ch R = 1 ,491     ,,,
XS GIS Cut Line= 3
     3574791.116    10190746.213      3574689.12    10190434.798
     3574578.443    10190414.182
#Sta/Elev= 30
       0  281.52   19.42  281.55   29.13  281.73   48.54  281.33   97.09  280.88
  106.79  280.58  126.21   279.6  135.92   279.4  174.76  279.54  184.46  279.28
  194.17   278.5  203.88  276.17  213.59  274.31   223.3  273.22  242.72  272.74
  252.42  272.15  262.13  272.77  271.84  276.11  281.55  278.66  291.26  279.52
  300.97  279.94  330.09  279.84   349.6  280.21  359.35  280.16  378.86  280.39
  398.37  281.11  408.12  281.05  417.88  281.22  427.63   281.1     453  281.24
#Mann= 4 ,-1 , 0
       0     .08       0   97.09     .05       0  174.76     .07       0
  300.97     .12       0
Bank Sta=174.76,300.97
XS Rating Curve= 0 ,0
Exp/Cntr=0.3,0.1

Chan Stop Cuts=-1
Use User Specified Reach Order=0
Composite Channel Slope=5