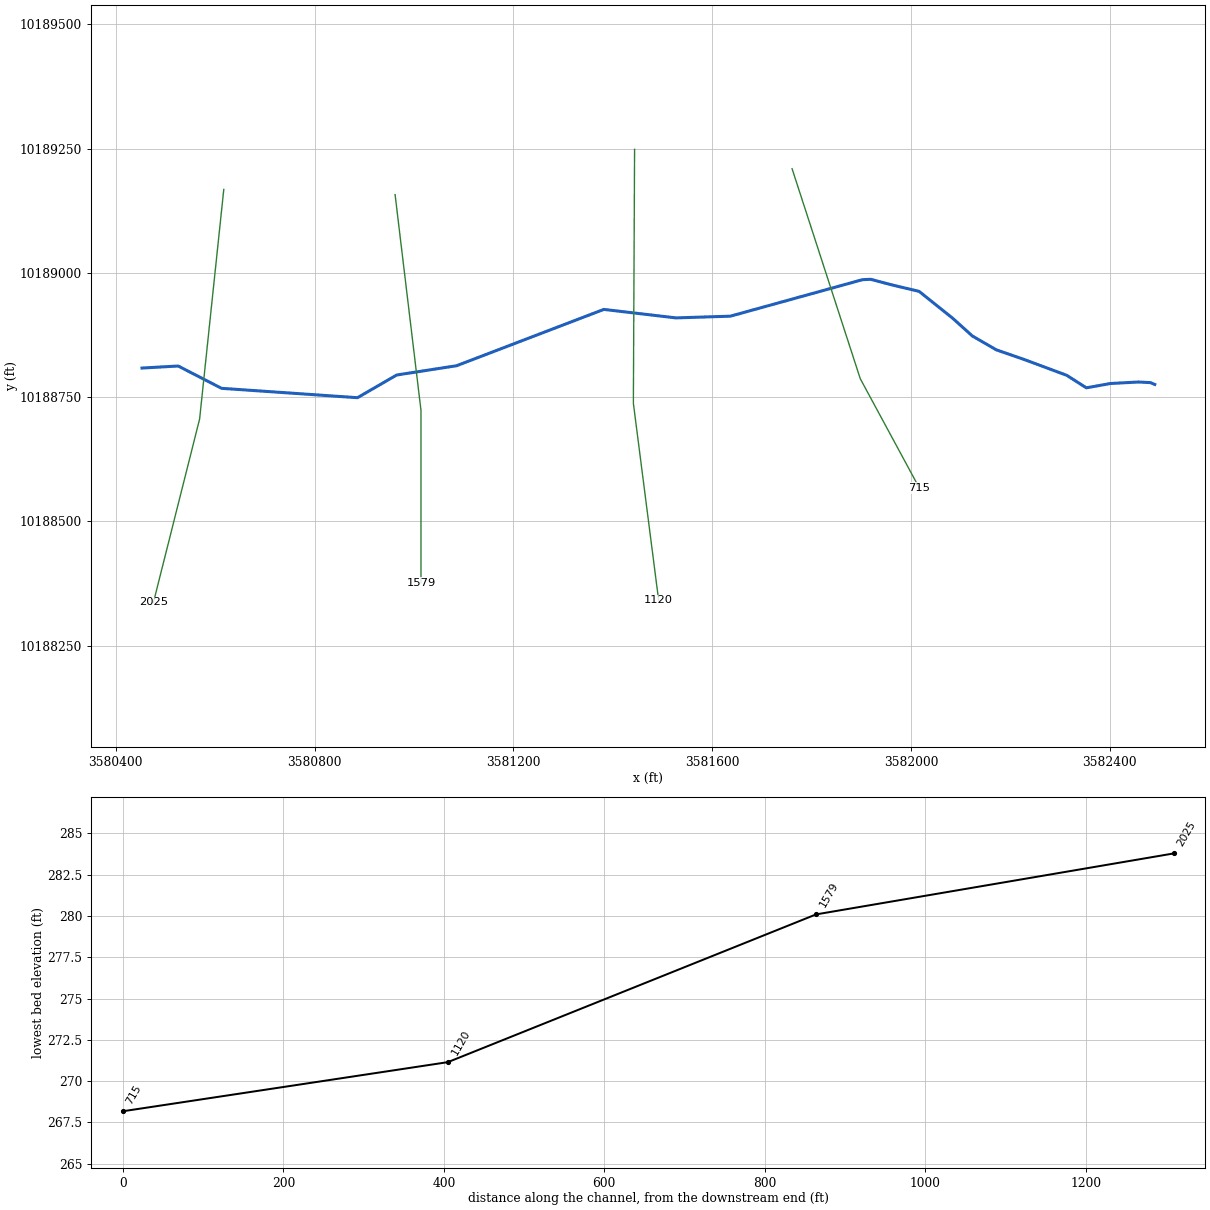
--- AC-1 TRIBUTARY 1.prj (project) ---

Proj Title=AC-1 TRIBUTARY 1 Base Level Engineering
Current Plan=p01
Default Exp/Contr=0.3,0.1
English Units
Geom File=g01
Flow File=f01
Plan File=p01
BEGIN DESCRIPTION:
AC-1 TRIBUTARY 1
END DESCRIPTION:

--- AC-1 TRIBUTARY 1.p01 (plan) ---

Plan Title=Multiple Run
Short Identifier=Multiple
Geom File=g01
Flow File=f01
Subcritical Flow
K Sum by GR= 0
Std Step Tol= 0.01
Critical Tol= 0.01
Num of Std Step Trials= 20
Max Error Tol= 0.3
Flow Tol Ratio= 0.001
Split Flow NTrial= 30
Split Flow Tol= 0.02
Split Flow Ratio= 0.02
Log Output Level= 0
Friction Slope Method= 1
Unsteady Friction Slope Method= 2
Unsteady Bridges Friction Slope Method= 1
Parabolic Critical Depth
Global Vel Dist=  1 , 1 , 1
Global Log Level= 0
CheckData=True
Encroach Param= -1, 0, 0, 0
BEGIN DESCRIPTION:
Multiple Run
END DESCRIPTION:

--- AC-1 TRIBUTARY 1.f01 (steady flow) ---

Flow Title=Multiple
Number of Profiles=7
Profile Names=10-year,25-year,50-year,1pct_min,100-year,1pct_plu,500-year
River Rch & RM= AC-1 TRIBUTARY 1,Reach-1,2025
      73      86      94      76     103     140     124
River Rch & RM= AC-1 TRIBUTARY 1,Reach-1,1120
     133     163     185     155     209     283     268
Boundary for River Rch & Prof#=AC-1 TRIBUTARY 1,Reach-1,1
Up Type=0
Dn Type=3
Dn Slope=0.005
Boundary for River Rch & Prof#=AC-1 TRIBUTARY 1,Reach-1,2
Up Type=0
Dn Type=3
Dn Slope=0.005
Boundary for River Rch & Prof#=AC-1 TRIBUTARY 1,Reach-1,3
Up Type=0
Dn Type=3
Dn Slope=0.005
Boundary for River Rch & Prof#=AC-1 TRIBUTARY 1,Reach-1,4
Up Type=0
Dn Type=3
Dn Slope=0.005
Boundary for River Rch & Prof#=AC-1 TRIBUTARY 1,Reach-1,5
Up Type=0
Dn Type=3
Dn Slope=0.005
Boundary for River Rch & Prof#=AC-1 TRIBUTARY 1,Reach-1,6
Up Type=0
Dn Type=3
Dn Slope=0.005
Boundary for River Rch & Prof#=AC-1 TRIBUTARY 1,Reach-1,7
Up Type=0
Dn Type=3
Dn Slope=0.005

--- AC-1 TRIBUTARY 1.g01 (geometry) ---

Geom Title=Existing Conditions

River Reach=AC-1 TRIBUTARY 1,Reach-1
Reach XY= 23
      3580452.95     10188808.42      3580525.60     10188812.54
      3580612.89     10188767.63      3580886.34     10188748.78
      3580965.15     10188794.41      3581085.69     10188813.09
      3581381.82     10188926.38      3581527.11     10188909.31
      3581636.49     10188912.78      3581902.18     10188986.21
      3581918.54     10188986.96      3581963.24     10188975.24
      3582016.19     10188962.66      3582083.90     10188908.40
      3582123.40     10188872.81      3582171.57     10188845.04
      3582226.70     10188825.94      3582313.07     10188793.82
      3582352.56     10188768.65      3582401.18     10188777.33
      3582457.60     10188780.37      3582481.60     10188779.09
      3582490.24     10188775.43

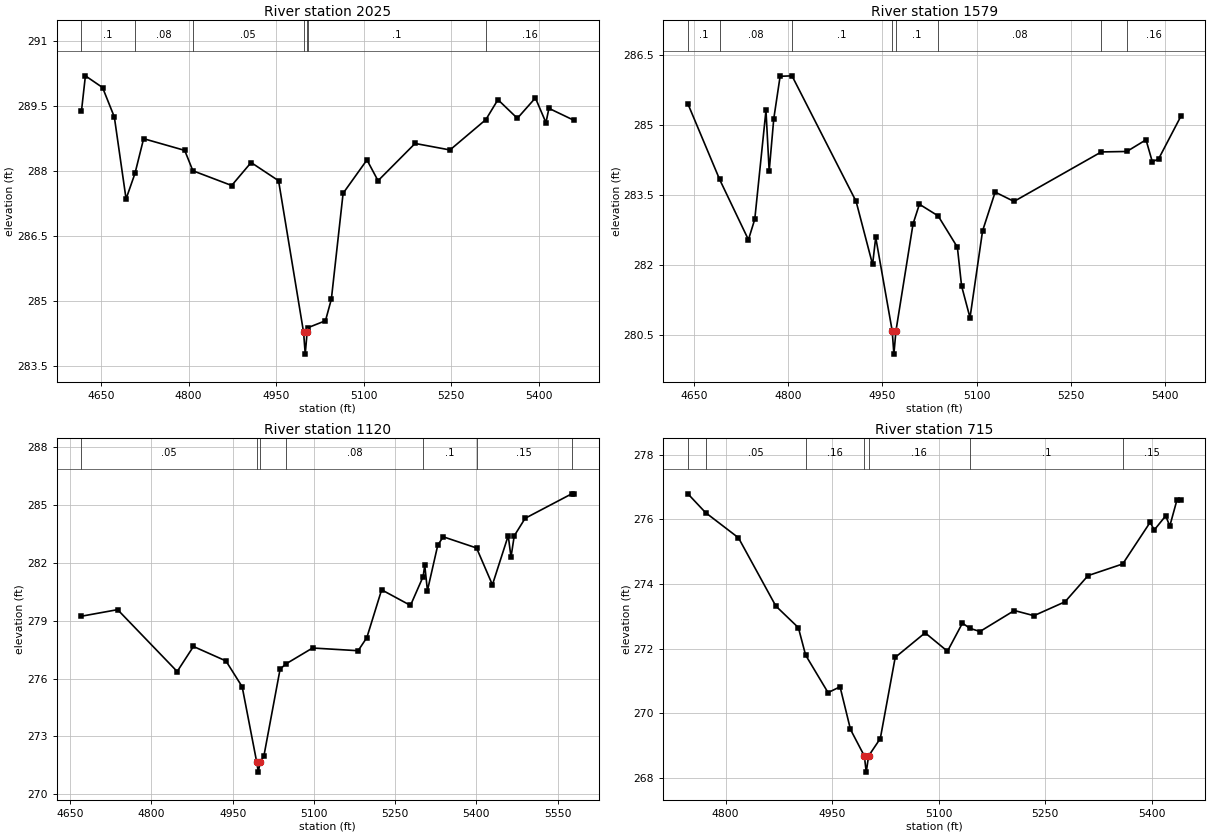
Type RM Length L Ch R = 1,2025,446,446,446
BEGIN DESCRIPTION:
AC-1 TRIBUTARY 1 4.0
END DESCRIPTION:
XS GIS Cut Line= 3
      3580617.36     10189167.69      3580568.75     10188705.92
      3580475.86     10188336.96
#Sta/Elev= 30
  4616.2  289.38  4623.0  290.20  4652.4  289.93  4672.6  289.25  4692.7  287.36
  4708.0  287.95  4722.8  288.75  4793.2  288.48  4807.2  288.01  4873.7  287.67
  4907.0  288.20  4954.1  287.78  4997.0  284.28  4999.8  283.78  5003.0  284.28
  5004.4  284.39  5034.5  284.55  5044.6  285.05  5064.7  287.49  5105.6  288.26
  5124.6  287.78  5188.1  288.64  5247.9  288.49  5309.4  289.19  5330.1  289.65
  5363.4  289.22  5394.3  289.69  5412.4  289.12  5417.5  289.45  5461.0  289.17
#Mann=7,-1,0
  4616.2     0.1       0  4708.0    0.08       0  4807.2    0.05       0
  4997.0    0.04       0  5003.0    0.05       0  5004.4     0.1       0
  5309.4    0.16       0
Bank Sta=4997,5003
Exp/Cntr=0.3,0.1

Type RM Length L Ch R = 1,1579,459,459,459
BEGIN DESCRIPTION:
AC-1 TRIBUTARY 1 3.0
END DESCRIPTION:
XS GIS Cut Line= 3
      3580961.98     10189157.29      3581014.06     10188723.28
      3581014.06     10188376.31
#Sta/Elev= 30
  4640.7  285.45  4691.2  283.83  4737.0  282.54  4747.1  282.98  4764.9  285.31
  4770.0  284.01  4777.3  285.13  4787.4  286.04  4806.3  286.05  4908.3  283.36
  4934.5  282.01  4939.5  282.59  4965.7  280.59  4968.4  280.09  4971.7  280.59
  4998.9  282.88  5009.0  283.30  5038.8  283.05  5069.4  282.38  5076.1  281.55
  5089.5  280.87  5109.5  282.73  5129.5  283.56  5159.5  283.36  5298.4  284.42
  5339.0  284.43  5369.5  284.68  5379.5  284.21  5389.5  284.27  5424.8  285.18
#Mann=8,-1,0
  4640.7     0.1       0  4691.2    0.08       0  4806.3     0.1       0
  4965.7    0.07       0  4971.7     0.1       0  5038.8    0.08       0
  5298.4    0.05       0  5339.0    0.16       0
Bank Sta=4965.7,4971.7
Exp/Cntr=0.3,0.1

Type RM Length L Ch R = 1,1120,405,405,405
BEGIN DESCRIPTION:
AC-1 TRIBUTARY 1 2.0
END DESCRIPTION:
XS GIS Cut Line= 3
      3581443.75     10189248.48      3581441.33     10188737.55
      3581492.11     10188341.63
#Sta/Elev= 30
  4670.8  279.24  4737.6  279.58  4847.6  276.37  4877.6  277.67  4937.6  276.92
  4967.6  275.58  4994.6  271.65  4997.4  271.15  5000.6  271.65  5007.6  271.97
  5037.6  276.49  5048.1  276.76  5097.6  277.59  5181.7  277.45  5197.8  278.13
  5225.1  280.61  5278.4  279.80  5301.8  281.30  5304.7  281.89  5309.7  280.57
  5328.8  282.93  5338.9  283.36  5400.4  282.78  5429.7  280.87  5458.9  283.42
  5464.0  282.30  5470.0  283.41  5490.1  284.32  5576.1  285.59  5580.9  285.56
#Mann=7,-1,0
  4670.8    0.05       0  4994.6    0.04       0  5000.6    0.05       0
  5048.1    0.08       0  5301.8     0.1       0  5400.4    0.15       0
  5576.1     0.1       0
Bank Sta=4994.6,5000.6
Exp/Cntr=0.3,0.1

Type RM Length L Ch R = 1,715,0,0,0
BEGIN DESCRIPTION:
AC-1 TRIBUTARY 1 1.0
END DESCRIPTION:
XS GIS Cut Line= 3
      3581760.59     10189209.41      3581897.74     10188787.04
      3582016.68     10188567.01
#Sta/Elev= 30
  4746.9  276.79  4771.7  276.21  4818.1  275.43  4870.7  273.32  4902.5  272.65
  4912.7  271.80  4944.3  270.64  4961.2  270.82  4975.9  269.50  4995.4  268.68
  4998.1  268.18  5001.4  268.68  5017.9  269.22  5038.9  271.73  5081.0  272.49
  5112.5  271.92  5133.6  272.79  5144.0  272.63  5158.2  272.53  5206.7  273.18
  5234.3  273.02  5278.1  273.45  5310.5  274.26  5359.3  274.62  5398.0  275.91
  5403.7  275.67  5419.9  276.11  5425.6  275.79  5435.6  276.59  5441.1  276.59
#Mann=7,-1,0
  4746.9     0.1       0  4771.7    0.05       0  4912.7    0.16       0
  4995.4    0.07       0  5001.4    0.16       0  5144.0     0.1       0
  5359.3    0.15       0
Bank Sta=4995.4,5001.4
Exp/Cntr=0.3,0.1

Chan Stop Cuts=-1