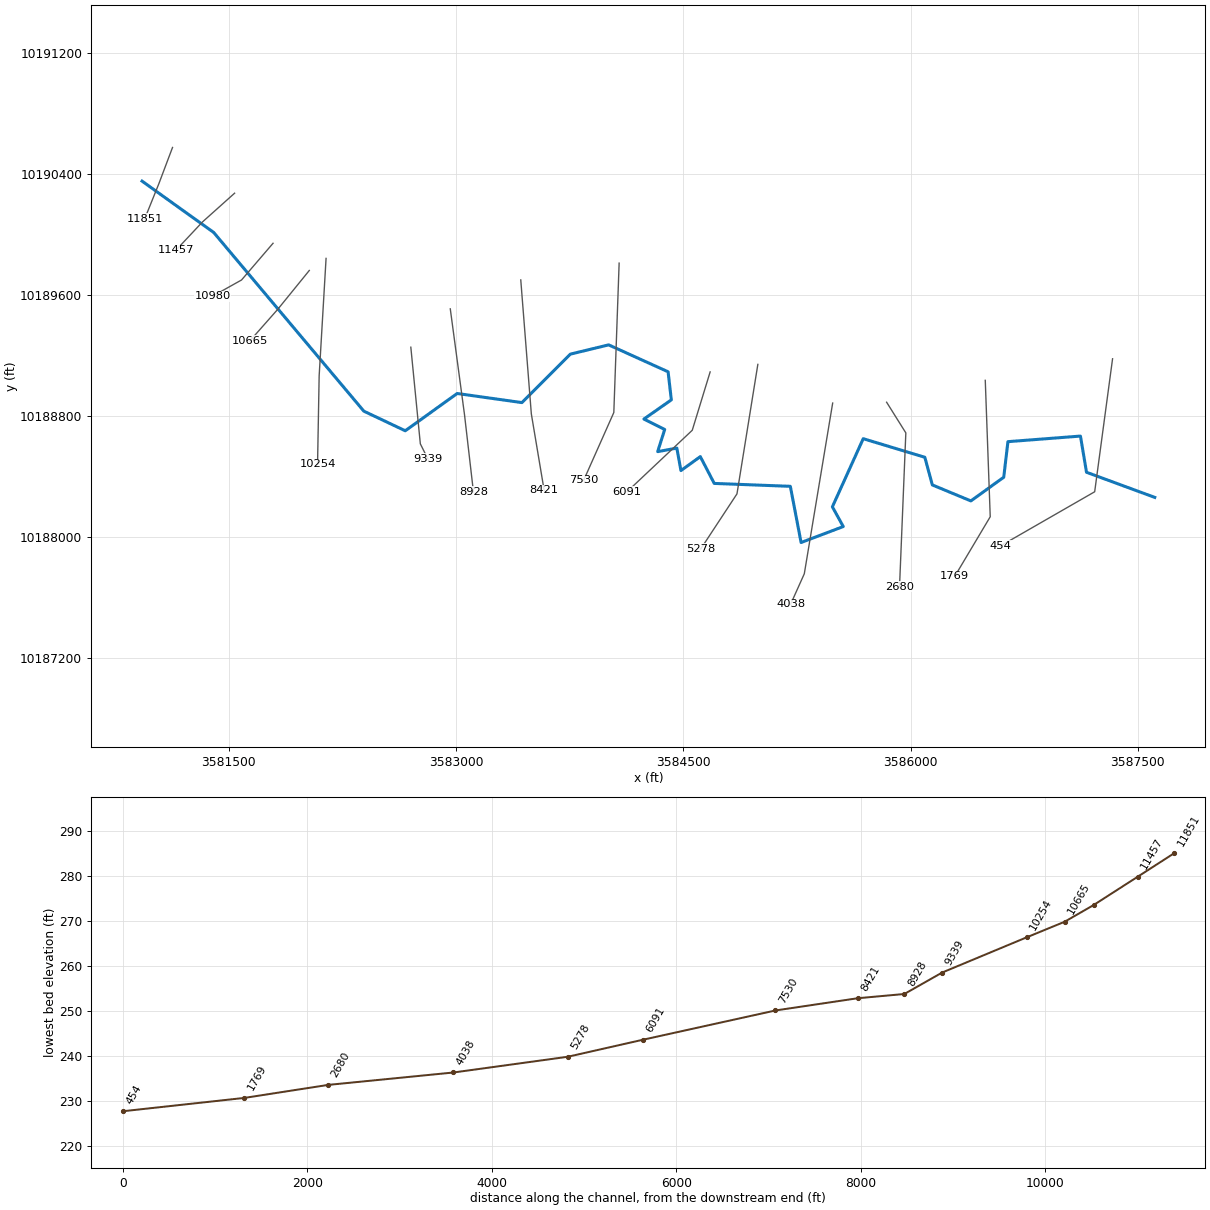
--- AC-1.prj (project) ---

Proj Title=AC-1 Base Level Engineering
Current Plan=p01
Default Exp/Contr=0.3,0.1
English Units
Geom File=g01
Flow File=f01
Plan File=p01
BEGIN DESCRIPTION:
AC-1
END DESCRIPTION:

--- AC-1.p01 (plan) ---

Plan Title=Multiple Run
Short Identifier=Multiple
Geom File=g01
Flow File=f01
Subcritical Flow
K Sum by GR= 0
Std Step Tol= 0.01
Critical Tol= 0.01
Num of Std Step Trials= 20
Max Error Tol= 0.3
Flow Tol Ratio= 0.001
Split Flow NTrial= 30
Split Flow Tol= 0.02
Split Flow Ratio= 0.02
Log Output Level= 0
Friction Slope Method= 1
Unsteady Friction Slope Method= 2
Unsteady Bridges Friction Slope Method= 1
Parabolic Critical Depth
Global Vel Dist=  1 , 1 , 1
Global Log Level= 0
CheckData=True
Encroach Param= -1, 0, 0, 0
BEGIN DESCRIPTION:
Multiple Run
END DESCRIPTION:

--- AC-1.f01 (steady flow) ---

Flow Title=Multiple
Number of Profiles=7
Profile Names=10-year,25-year,50-year,1pct_min,100-year,1pct_plu,500-year
River Rch & RM= AC-1,Reach-1,11851
     124     150     170     142     192     259     243
River Rch & RM= AC-1,Reach-1,9339
     510     682     821     725     980    1326    1399
Boundary for River Rch & Prof#=AC-1,Reach-1,1
Up Type=0
Dn Type=3
Dn Slope=0.005
Boundary for River Rch & Prof#=AC-1,Reach-1,2
Up Type=0
Dn Type=3
Dn Slope=0.005
Boundary for River Rch & Prof#=AC-1,Reach-1,3
Up Type=0
Dn Type=3
Dn Slope=0.005
Boundary for River Rch & Prof#=AC-1,Reach-1,4
Up Type=0
Dn Type=3
Dn Slope=0.005
Boundary for River Rch & Prof#=AC-1,Reach-1,5
Up Type=0
Dn Type=3
Dn Slope=0.005
Boundary for River Rch & Prof#=AC-1,Reach-1,6
Up Type=0
Dn Type=3
Dn Slope=0.005
Boundary for River Rch & Prof#=AC-1,Reach-1,7
Up Type=0
Dn Type=3
Dn Slope=0.005

--- AC-1.g01 (geometry) ---

Geom Title=Existing Conditions

River Reach=AC-1,Reach-1
Reach XY= 30
      3580927.49     10190352.07      3581400.44     10190012.96
      3582391.28     10188832.72      3582664.91     10188703.04
      3583007.42     10188949.27      3583434.91     10188889.21
      3583754.31     10189209.21      3584007.25     10189270.48
      3584399.61     10189092.70      3584421.14     10188907.28
      3584239.90     10188780.28      3584377.31     10188711.68
      3584330.82     10188565.14      3584457.38     10188588.57
      3584484.46     10188440.14      3584612.33     10188532.32
      3584704.34     10188355.24      3585206.51     10188336.14
      3585277.53     10187964.87      3585555.96     10188070.32
      3585484.10     10188200.65      3585687.74     10188650.72
      3586094.33     10188527.97      3586143.85     10188345.40
      3586398.21     10188239.70      3586615.13     10188396.12
      3586642.86     10188631.10      3587121.52     10188668.03
      3587161.58     10188428.83      3587612.11     10188262.96

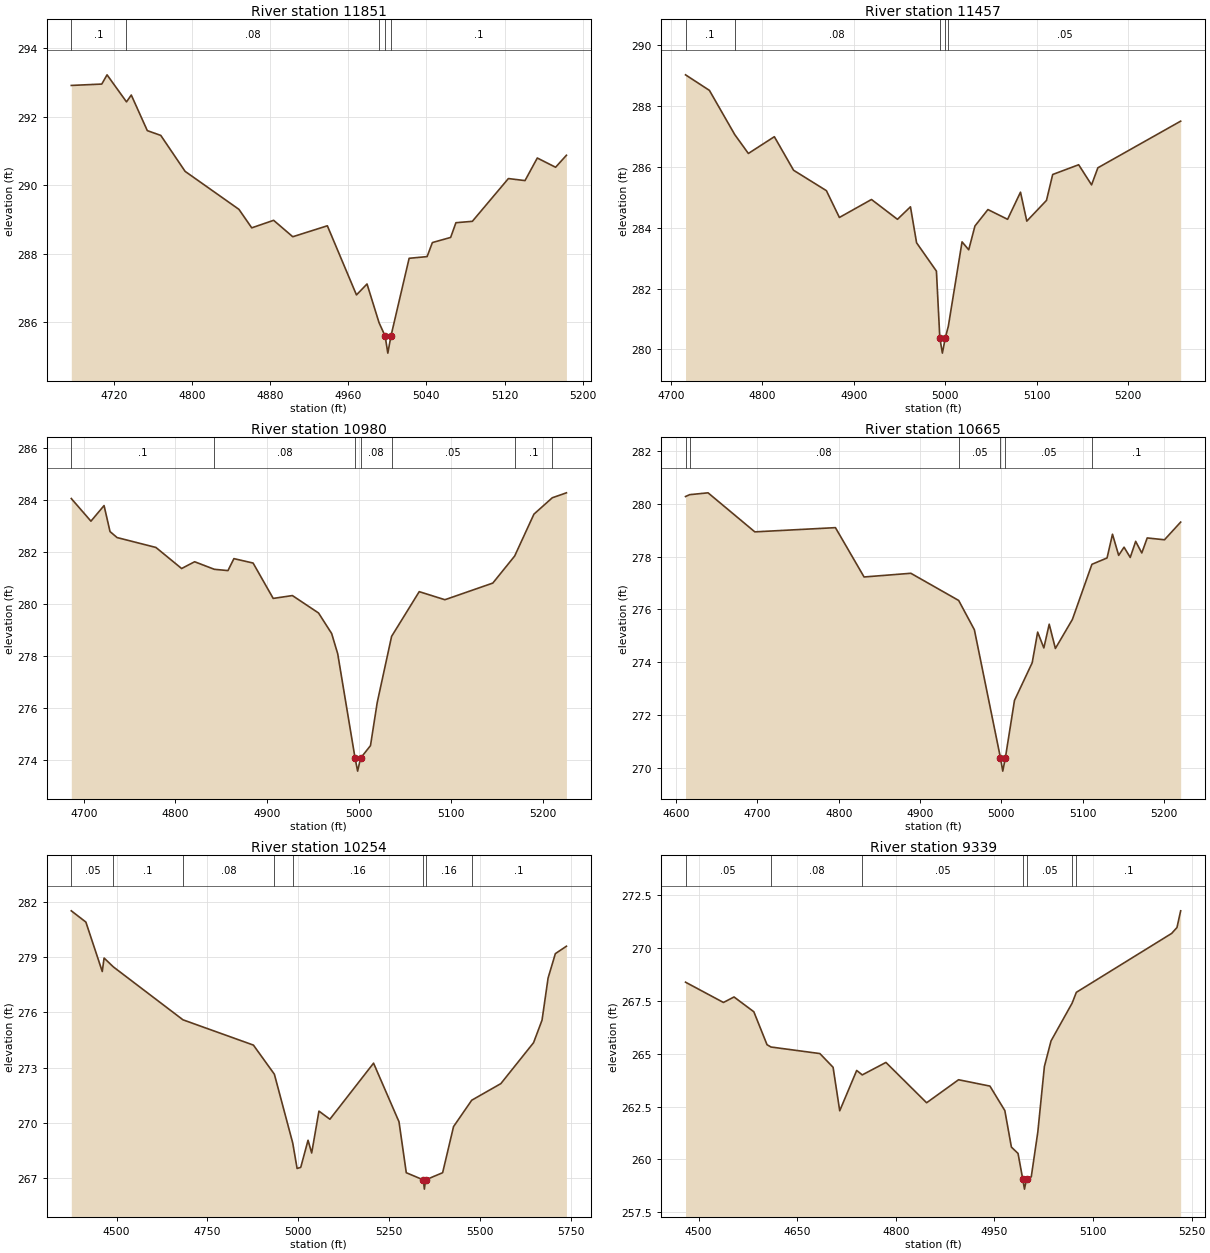
Type RM Length L Ch R = 1,11851,394,394,394
BEGIN DESCRIPTION:
AC-1 17.0
END DESCRIPTION:
XS GIS Cut Line= 3
      3581128.63     10190574.48      3581038.36     10190334.91
      3580944.62     10190102.30
#Sta/Elev= 30
  4676.5  292.91  4707.7  292.95  4713.1  293.22  4733.0  292.43  4737.9  292.63
  4754.3  291.59  4768.1  291.45  4793.0  290.40  4848.1  289.29  4861.2  288.75
  4883.6  288.97  4903.2  288.49  4938.6  288.81  4968.4  286.79  4979.2  287.11
  4991.5  285.98  4997.7  285.59  5000.5  285.09  5003.7  285.59  5022.3  287.86
  5040.7  287.91  5046.1  288.32  5064.8  288.47  5070.2  288.90  5087.0  288.94
  5123.9  290.19  5140.9  290.13  5153.5  290.79  5172.2  290.52  5183.3  290.87
#Mann=5,-1,0
  4676.5     0.1       0  4733.0    0.08       0  4991.5    0.05       0
  4997.7    0.04       0  5003.7     0.1       0
Bank Sta=4997.7,5003.7
Exp/Cntr=0.3,0.1

Type RM Length L Ch R = 1,11457,477,477,477
BEGIN DESCRIPTION:
AC-1 16.0
END DESCRIPTION:
XS GIS Cut Line= 3
      3581538.37     10190272.42      3581326.80     10190082.98
      3581150.76     10189895.32
#Sta/Elev= 30
  4716.0  289.01  4742.1  288.50  4769.8  287.05  4784.7  286.43  4813.1  286.98
  4834.1  285.88  4870.0  285.21  4884.2  284.33  4919.3  284.92  4947.7  284.27
  4961.9  284.68  4968.6  283.50  4990.3  282.57  4994.0  280.38  4996.8  279.88
  5000.0  280.38  5003.3  280.76  5018.3  283.53  5025.6  283.27  5032.4  284.05
  5046.6  284.59  5068.1  284.27  5082.2  285.16  5089.1  284.21  5110.6  284.89
  5117.4  285.74  5145.8  286.06  5159.9  285.40  5166.8  285.96  5257.3  287.49
#Mann=5,-1,0
  4716.0     0.1       0  4769.8    0.08       0  4994.0    0.07       0
  5000.0    0.08       0  5003.3    0.05       0
Bank Sta=4994,5000
Exp/Cntr=0.3,0.1

Type RM Length L Ch R = 1,10980,315,315,315
BEGIN DESCRIPTION:
AC-1 15.0
END DESCRIPTION:
XS GIS Cut Line= 3
      3581792.09     10189941.63      3581584.25     10189699.16
      3581392.14     10189591.66
#Sta/Elev= 30
  4686.5  284.07  4707.9  283.20  4722.2  283.80  4728.7  282.80  4736.4  282.57
  4778.7  282.19  4806.7  281.38  4820.9  281.64  4842.3  281.35  4857.2  281.30
  4863.7  281.76  4884.6  281.59  4906.5  280.23  4927.4  280.34  4955.9  279.67
  4970.2  278.88  4976.8  278.10  4995.7  274.09  4998.5  273.59  5001.7  274.09
  5012.5  274.57  5019.8  276.22  5035.5  278.77  5065.6  280.49  5093.6  280.18
  5145.8  280.82  5169.6  281.86  5190.6  283.47  5210.6  284.10  5226.0  284.29
#Mann=7,-1,0
  4686.5     0.1       0  4842.3    0.08       0  4995.7    0.07       0
  5001.7    0.08       0  5035.5    0.05       0  5169.6     0.1       0
  5210.6    0.08       0
Bank Sta=4995.7,5001.7
Exp/Cntr=0.3,0.1

Type RM Length L Ch R = 1,10665,411,411,411
BEGIN DESCRIPTION:
AC-1 14.0
END DESCRIPTION:
XS GIS Cut Line= 3
      3582031.41     10189761.98      3581824.06     10189506.38
      3581639.08     10189296.75
#Sta/Elev= 30
  4611.7  280.28  4616.8  280.35  4639.4  280.42  4696.9  278.94  4796.0  279.10
  4831.2  277.23  4888.7  277.37  4947.5  276.34  4966.8  275.23  4998.9  270.37
  5001.7  269.87  5004.9  270.37  5016.1  272.55  5037.9  273.98  5044.6  275.14
  5052.2  274.54  5058.8  275.44  5066.4  274.52  5087.3  275.62  5111.3  277.71
  5129.9  277.95  5136.6  278.85  5144.2  278.05  5150.8  278.36  5158.4  277.97
  5165.1  278.58  5172.6  278.14  5179.3  278.71  5200.5  278.64  5220.4  279.31
#Mann=6,-1,0
  4611.7    0.05       0  4616.8    0.08       0  4947.5    0.05       0
  4998.9    0.04       0  5004.9    0.05       0  5111.3     0.1       0
Bank Sta=4998.9,5004.9
Exp/Cntr=0.3,0.1

Type RM Length L Ch R = 1,10254,915,915,915
BEGIN DESCRIPTION:
AC-1 13.0
END DESCRIPTION:
XS GIS Cut Line= 3
      3582142.11     10189841.69      3582096.45     10189065.16
      3582085.86     10188481.23
#Sta/Elev= 30
  4375.6  281.50  4415.7  280.89  4460.8  278.21  4465.8  278.94  4491.3  278.46
  4682.8  275.59  4876.5  274.22  4934.2  272.64  4984.7  268.91  4996.7  267.53
  5006.7  267.59  5026.8  269.06  5036.8  268.37  5056.8  270.64  5086.9  270.20
  5207.0  273.24  5277.0  270.06  5297.0  267.30  5344.0  266.91  5346.8  266.41
  5350.0  266.91  5397.0  267.30  5427.0  269.80  5477.0  271.23  5557.1  272.13
  5647.1  274.35  5670.4  275.57  5687.1  277.86  5707.1  279.18  5737.5  279.58
#Mann=8,-1,0
  4375.6    0.05       0  4491.3     0.1       0  4682.8    0.08       0
  4934.2    0.05       0  4984.7    0.16       0  5344.0    0.07       0
  5350.0    0.16       0  5477.0     0.1       0
Bank Sta=5344,5350
Exp/Cntr=0.3,0.1

Type RM Length L Ch R = 1,9339,411,411,411
BEGIN DESCRIPTION:
AC-1 12.0
END DESCRIPTION:
XS GIS Cut Line= 3
      3582701.55     10189255.07      3582764.33     10188616.64
      3582814.32     10188516.65
#Sta/Elev= 30
  4480.1  268.39  4537.8  267.43  4553.9  267.69  4584.0  266.99  4604.1  265.43
  4610.2  265.32  4684.5  265.01  4704.6  264.36  4714.7  262.30  4740.5  264.21
  4749.0  264.00  4785.0  264.59  4846.9  262.68  4895.5  263.77  4943.2  263.47
  4965.9  262.31  4975.9  260.58  4986.0  260.28  4993.0  259.09  4995.8  258.59
  4999.0  259.09  5006.1  259.17  5016.1  261.30  5026.1  264.40  5036.2  265.61
  5068.3  267.40  5074.7  267.91  5219.7  270.70  5227.8  270.98  5233.4  271.77
#Mann=7,-1,0
  4480.1    0.05       0  4610.2    0.08       0  4749.0    0.05       0
  4993.0    0.04       0  4999.0    0.05       0  5068.3    0.08       0
  5074.7     0.1       0
Bank Sta=4993,4999
Exp/Cntr=0.3,0.1

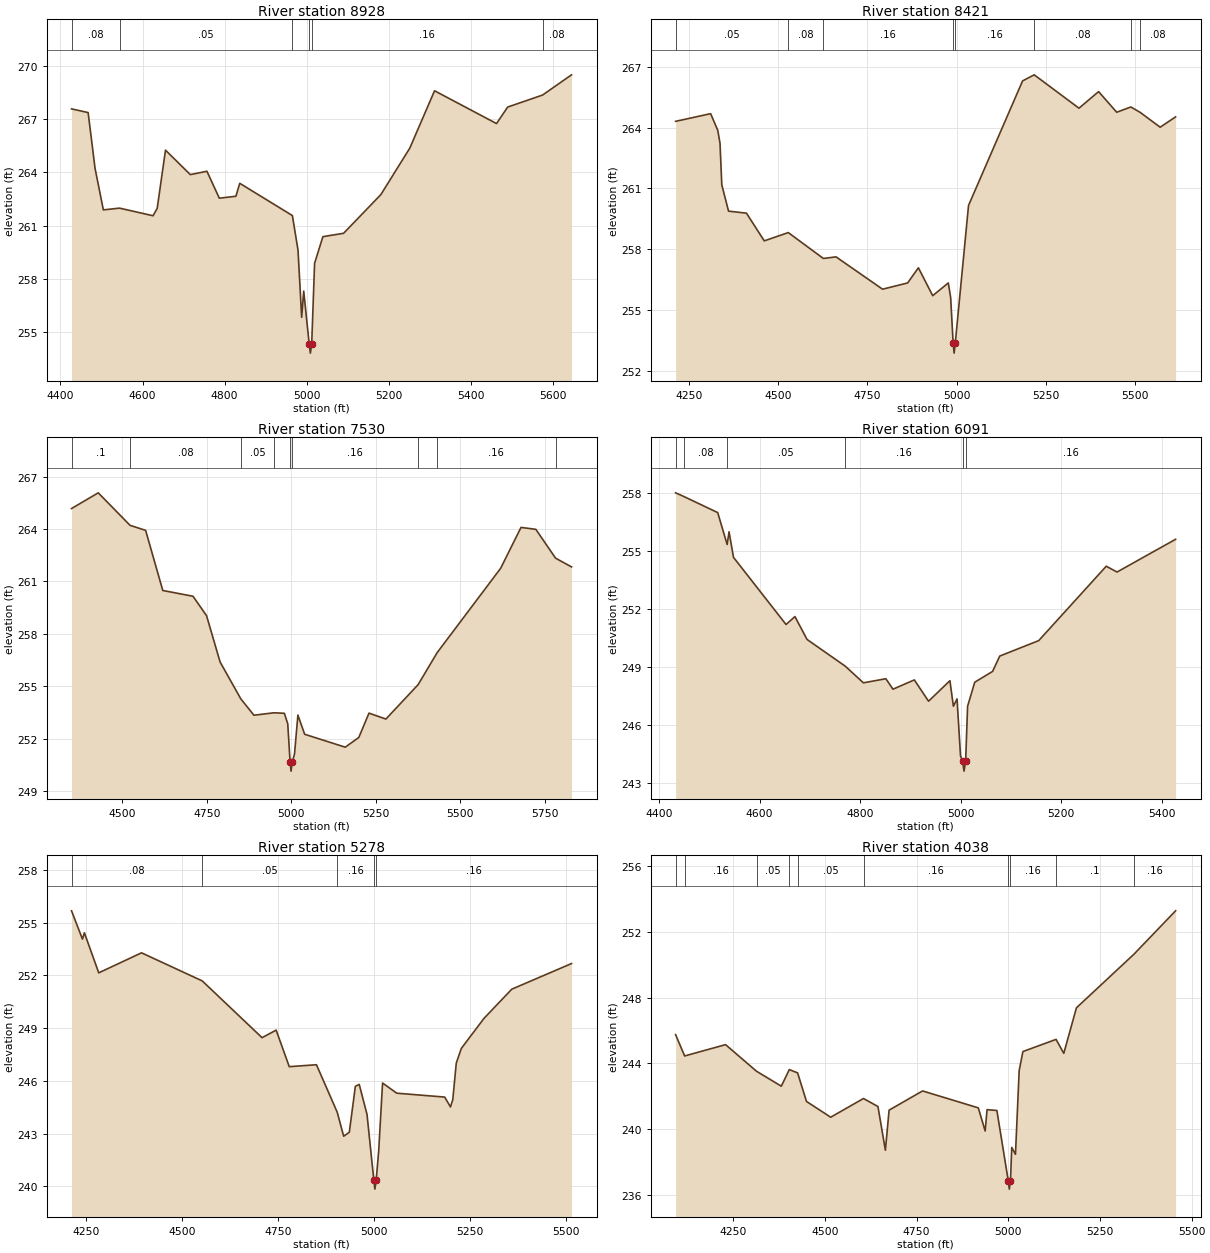
Type RM Length L Ch R = 1,8928,507,507,507
BEGIN DESCRIPTION:
AC-1 11.0
END DESCRIPTION:
XS GIS Cut Line= 3
      3582961.97     10189508.48      3583055.72     10188810.60
      3583114.75     10188300.15
#Sta/Elev= 30
  4427.1  267.59  4467.5  267.38  4484.4  264.23  4504.6  261.89  4544.0  261.99
  4625.7  261.56  4635.8  261.98  4656.0  265.26  4716.5  263.88  4756.9  264.07
  4787.1  262.55  4827.5  262.66  4836.9  263.39  4965.1  261.57  4978.8  259.62
  4987.7  255.83  4992.7  257.31  5006.1  254.31  5008.9  253.81  5012.1  254.31
  5019.2  258.88  5039.4  260.38  5089.8  260.57  5180.5  262.75  5251.0  265.37
  5311.4  268.61  5462.4  266.76  5489.5  267.69  5574.6  268.37  5645.1  269.51
#Mann=6,-1,0
  4427.1    0.08       0  4544.0    0.05       0  4965.1    0.16       0
  5006.1    0.07       0  5012.1    0.16       0  5574.6    0.08       0
Bank Sta=5006.1,5012.1
Exp/Cntr=0.3,0.1

Type RM Length L Ch R = 1,8421,891,891,891
BEGIN DESCRIPTION:
AC-1 10.0
END DESCRIPTION:
XS GIS Cut Line= 3
      3583427.24     10189699.52      3583496.97     10188814.56
      3583581.69     10188309.01
#Sta/Elev= 30
  4212.6  264.32  4310.8  264.70  4330.8  263.87  4337.0  263.24  4342.0  261.18
  4360.9  259.88  4411.1  259.78  4460.9  258.41  4528.2  258.82  4626.5  257.54
  4661.9  257.62  4792.3  256.02  4862.5  256.33  4892.6  257.08  4932.7  255.70
  4976.3  256.33  4982.9  255.62  4989.9  253.36  4992.6  252.86  4995.9  253.36
  5033.0  260.16  5184.4  266.32  5217.0  266.62  5342.3  264.97  5397.3  265.79
  5448.0  264.77  5487.7  265.03  5514.0  264.76  5569.7  264.03  5612.9  264.54
#Mann=8,-1,0
  4212.6    0.05       0  4528.2    0.08       0  4626.5    0.16       0
  4989.9    0.07       0  4995.9    0.16       0  5217.0    0.08       0
  5487.7    0.16       0  5514.0    0.08       0
Bank Sta=4989.9,4995.9
Exp/Cntr=0.3,0.1

Type RM Length L Ch R = 1,7530,1439,1439,1439
BEGIN DESCRIPTION:
AC-1 9.0
END DESCRIPTION:
XS GIS Cut Line= 3
      3584076.55     10189810.56      3584041.41     10188823.59
      3583842.08     10188375.08
#Sta/Elev= 30
  4350.3  265.17  4429.3  266.07  4523.3  264.21  4569.4  263.92  4620.1  260.48
  4709.4  260.15  4749.5  259.04  4789.5  256.39  4850.7  254.28  4889.6  253.34
  4949.2  253.48  4979.6  253.45  4989.6  252.85  4996.6  250.64  4999.4  250.14
  5002.6  250.64  5009.6  251.12  5019.6  253.35  5039.6  252.25  5159.7  251.51
  5199.8  252.07  5229.8  253.46  5279.8  253.12  5375.1  255.09  5431.3  256.92
  5619.1  261.75  5679.3  264.09  5723.2  263.98  5781.5  262.33  5828.7  261.83
#Mann=9,-1,0
  4350.3     0.1       0  4523.3    0.08       0  4850.7    0.05       0
  4949.2    0.16       0  4996.6    0.07       0  5002.6    0.16       0
  5375.1    0.05       0  5431.3    0.16       0  5781.5    0.05       0
Bank Sta=4996.6,5002.6
Exp/Cntr=0.3,0.1

Type RM Length L Ch R = 1,6091,813,813,813
BEGIN DESCRIPTION:
AC-1 7.0
END DESCRIPTION:
XS GIS Cut Line= 3
      3584677.23     10189091.81      3584559.19     10188706.44
      3584128.64     10188300.19
#Sta/Elev= 30
  4433.0  257.99  4449.4  257.80  4516.8  256.97  4535.6  255.32  4539.4  255.98
  4548.2  254.66  4652.8  251.19  4670.5  251.60  4694.6  250.42  4770.6  249.04
  4806.7  248.18  4851.5  248.39  4865.6  247.85  4908.1  248.33  4936.4  247.23
  4978.9  248.29  4985.8  246.97  4993.1  247.35  5000.0  244.41  5004.2  244.12
  5007.0  243.62  5010.2  244.12  5014.1  246.97  5028.3  248.21  5063.9  248.77
  5078.0  249.56  5155.7  250.36  5290.0  254.20  5311.5  253.90  5428.0  255.59
#Mann=6,-1,0
  4433.0    0.05       0  4449.4    0.08       0  4535.6    0.05       0
  4770.6    0.16       0  5004.2    0.07       0  5010.2    0.16       0
Bank Sta=5004.2,5010.2
Exp/Cntr=0.3,0.1

Type RM Length L Ch R = 1,5278,1240,1240,1240
BEGIN DESCRIPTION:
AC-1 5.0
END DESCRIPTION:
XS GIS Cut Line= 3
      3584992.11     10189141.65      3584854.33     10188286.30
      3584614.77     10187921.75
#Sta/Elev= 30
  4211.9  255.68  4240.3  254.07  4245.4  254.43  4282.8  252.15  4394.2  253.29
  4552.5  251.69  4708.2  248.46  4745.0  248.89  4779.1  246.81  4850.0  246.92
  4904.0  244.22  4920.9  242.85  4935.6  243.08  4951.3  245.69  4961.4  245.80
  4981.7  244.09  4999.5  240.34  5002.2  239.84  5005.5  240.34  5012.1  242.01
  5022.2  245.88  5059.2  245.30  5184.0  245.08  5199.1  244.52  5205.1  244.93
  5214.2  247.01  5227.4  247.85  5286.5  249.56  5358.8  251.22  5514.5  252.68
#Mann=5,-1,0
  4211.9    0.08       0  4552.5    0.05       0  4904.0    0.16       0
  4999.5    0.07       0  5005.5    0.16       0
Bank Sta=4999.5,5005.5
Exp/Cntr=0.3,0.1

Type RM Length L Ch R = 1,4038,1358,1358,1358
BEGIN DESCRIPTION:
AC-1 4.0
END DESCRIPTION:
XS GIS Cut Line= 3
      3585486.05     10188886.10      3585298.77     10187758.52
      3585208.51     10187557.15
#Sta/Elev= 30
  4092.5  245.75  4117.2  244.45  4228.8  245.14  4313.2  243.52  4380.9  242.61
  4402.6  243.62  4425.3  243.42  4449.5  241.68  4515.5  240.72  4605.0  241.86
  4644.4  241.37  4664.7  238.71  4674.8  241.15  4766.1  242.32  4918.1  241.29
  4936.9  239.88  4942.0  241.18  4968.8  241.13  4999.9  236.84  5002.7  236.34
  5005.9  236.84  5009.3  238.88  5019.5  238.46  5029.6  243.56  5039.8  244.72
  5130.2  245.46  5151.3  244.61  5185.7  247.38  5342.7  250.65  5456.2  253.29
#Mann=10,-1,0
  4092.5    0.08       0  4117.2    0.16       0  4313.2    0.05       0
  4402.6    0.16       0  4425.3    0.05       0  4605.0    0.16       0
  4999.9    0.07       0  5005.9    0.16       0  5130.2     0.1       0
  5342.7    0.16       0
Bank Sta=4999.9,5005.9
Exp/Cntr=0.3,0.1

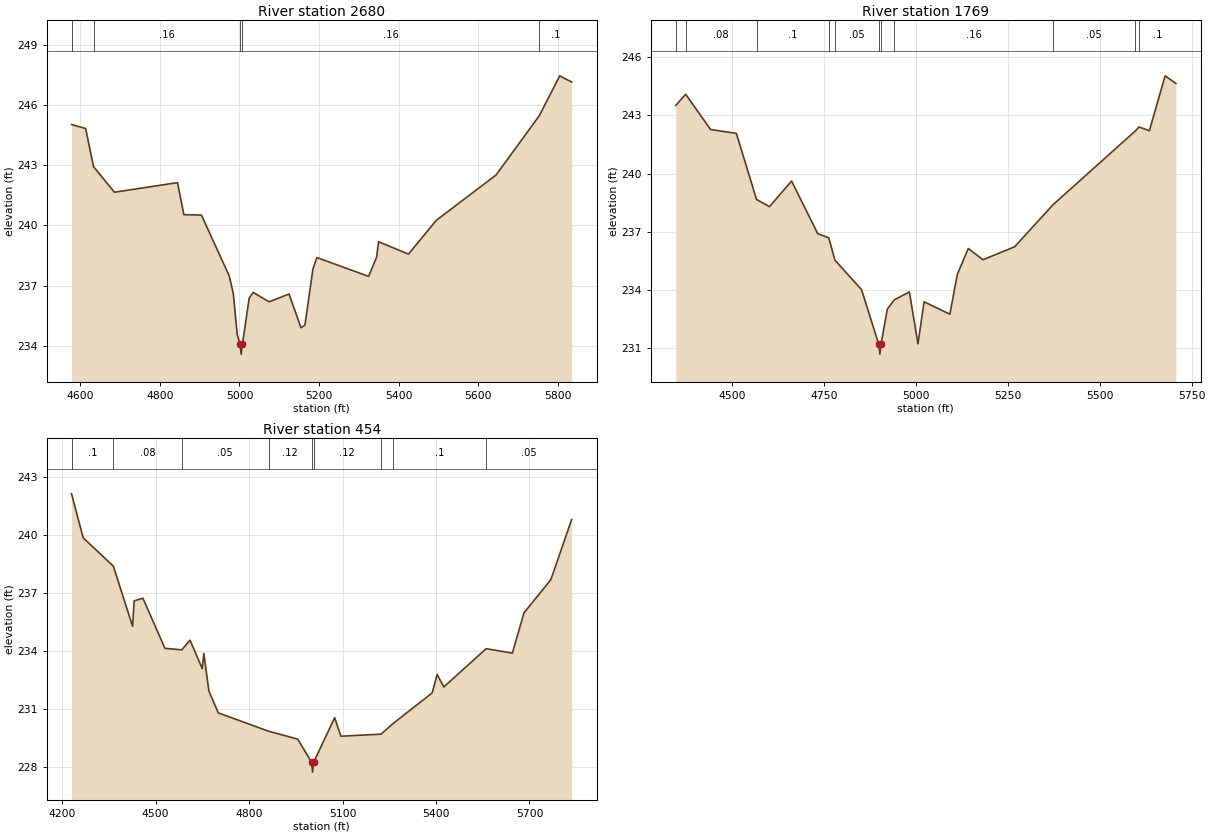
Type RM Length L Ch R = 1,2680,911,911,911
BEGIN DESCRIPTION:
AC-1 3.0
END DESCRIPTION:
XS GIS Cut Line= 3
      3585842.11     10188891.63      3585968.91     10188689.08
      3585927.25     10187671.70
#Sta/Elev= 30
  4577.9  245.04  4613.3  244.84  4633.1  242.94  4685.8  241.66  4844.3  242.14
  4860.2  240.54  4904.4  240.52  4974.4  237.48  4984.4  236.61  4994.5  234.55
  5001.5  234.08  5004.2  233.58  5007.5  234.08  5024.5  236.38  5034.5  236.66
  5074.5  236.19  5124.6  236.58  5154.6  234.90  5164.6  235.03  5184.6  237.82
  5194.6  238.40  5324.7  237.46  5344.7  238.42  5349.8  239.19  5424.8  238.57
  5494.9  240.26  5645.0  242.52  5753.4  245.47  5805.1  247.47  5835.1  247.16
#Mann=5,-1,0
  4577.9    0.08       0  4633.1    0.16       0  5001.5    0.07       0
  5007.5    0.16       0  5753.4     0.1       0
Bank Sta=5001.5,5007.5
Exp/Cntr=0.3,0.1

Type RM Length L Ch R = 1,1769,1315,1315,1315
BEGIN DESCRIPTION:
AC-1 2.0
END DESCRIPTION:
XS GIS Cut Line= 3
      3586493.22     10189036.32      3586526.02     10188135.16
      3586292.13     10187741.68
#Sta/Elev= 30
  4347.6  243.51  4374.6  244.09  4442.3  242.27  4512.4  242.07  4567.2  238.66
  4602.4  238.29  4662.5  239.61  4733.5  236.90  4763.6  236.68  4780.3  235.53
  4852.6  234.01  4899.6  231.18  4902.4  230.68  4905.6  231.18  4922.7  233.00
  4941.6  233.48  4982.7  233.89  5006.0  231.21  5022.7  233.38  5092.8  232.74
  5112.8  234.78  5142.8  236.13  5182.8  235.55  5268.9  236.22  5372.7  238.38
  5597.2  242.20  5606.8  242.40  5635.1  242.21  5677.9  245.04  5707.1  244.65
#Mann=11,-1,0
  4347.6     0.1       0  4374.6    0.08       0  4567.2     0.1       0
  4763.6    0.08       0  4780.3    0.05       0  4899.6    0.07       0
  4905.6    0.05       0  4941.6    0.16       0  5372.7    0.05       0
  5597.2    0.16       0  5606.8     0.1       0
Bank Sta=4899.6,4905.6
Exp/Cntr=0.3,0.1

Type RM Length L Ch R = 1,454,0,0,0
BEGIN DESCRIPTION:
AC-1 1.0
END DESCRIPTION:
XS GIS Cut Line= 3
      3587333.49     10189178.62      3587215.44     10188300.19
      3586592.13     10187941.66
#Sta/Elev= 30
  4230.0  242.15  4267.3  239.87  4364.2  238.40  4425.9  235.28  4431.0  236.60
  4459.0  236.74  4529.7  234.14  4583.7  234.06  4610.4  234.56  4649.5  233.09
  4654.6  233.88  4670.9  231.92  4701.2  230.79  4862.8  229.84  4956.1  229.43
  5000.9  228.22  5003.6  227.72  5006.9  228.22  5074.5  230.54  5094.7  229.58
  5223.6  229.69  5260.6  230.22  5387.7  231.83  5403.5  232.78  5425.1  232.14
  5561.0  234.12  5645.0  233.89  5682.4  235.98  5768.6  237.70  5835.4  240.82
#Mann=9,-1,0
  4230.0     0.1       0  4364.2    0.08       0  4583.7    0.05       0
  4862.8    0.12       0  5000.9    0.07       0  5006.9    0.12       0
  5223.6    0.05       0  5260.6     0.1       0  5561.0    0.05       0
Bank Sta=5000.9,5006.9
Exp/Cntr=0.3,0.1

Chan Stop Cuts=-1