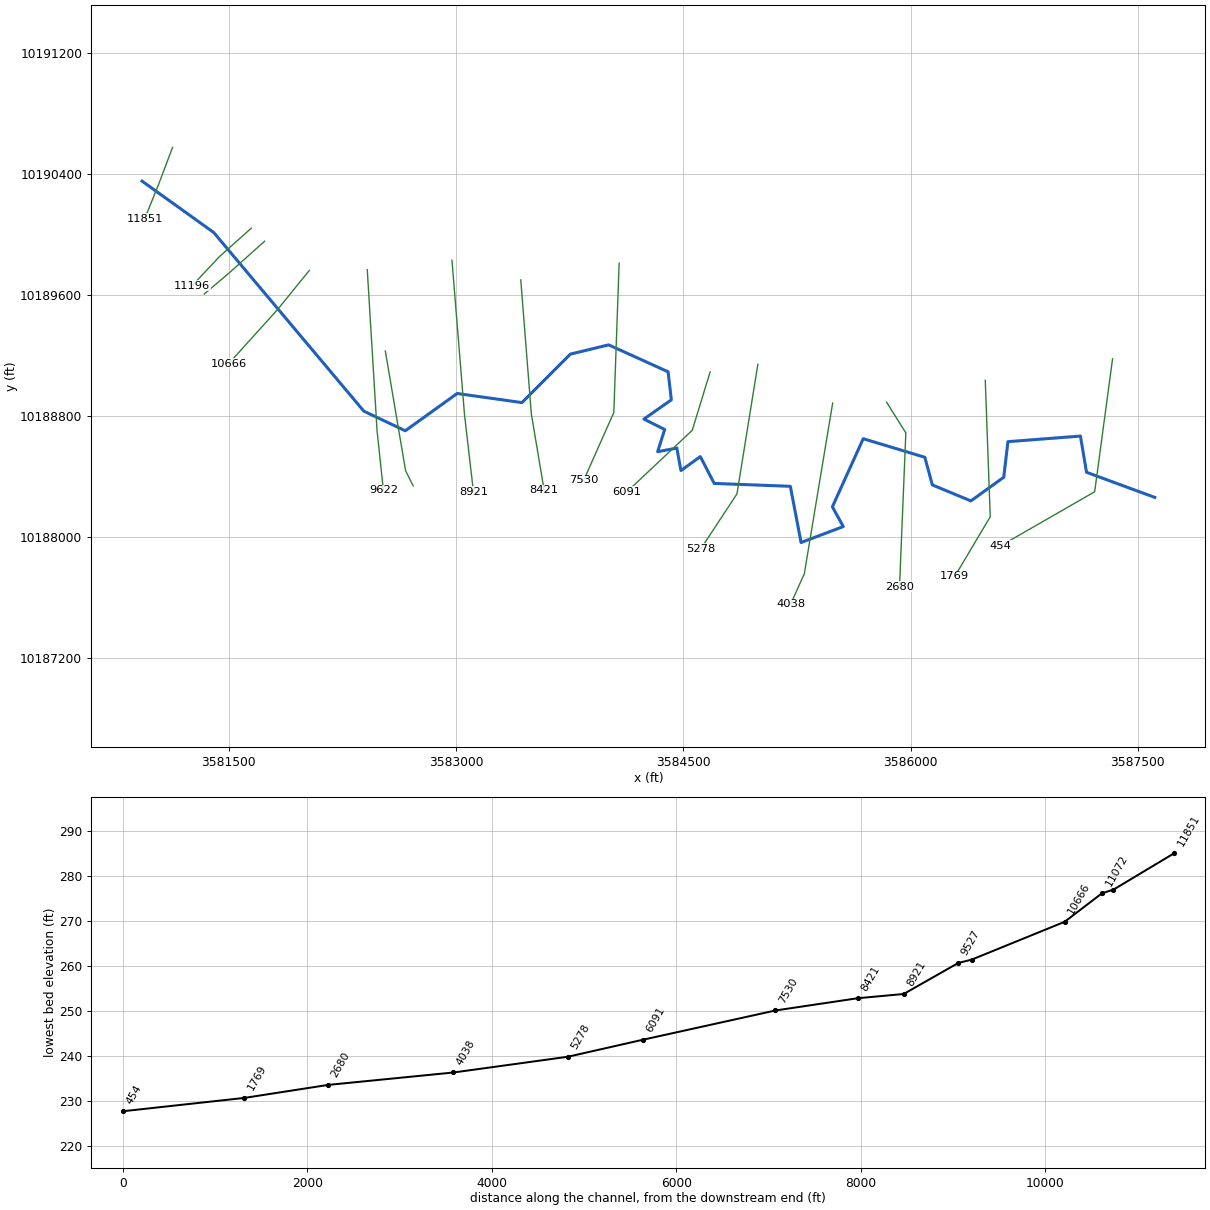
--- AC1.prj (project) ---

Proj Title=AC1 Base Level Engineering
Current Plan=p01
Default Exp/Contr=0.3,0.1
English Units
Geom File=g01
Flow File=f01
Plan File=p01
Y Axis Title=Elevation
X Axis Title(PF)=Main Channel Distance
X Axis Title(XS)=Station
BEGIN DESCRIPTION:
AC1
END DESCRIPTION:
DSS Export Rating Curves= 0
DSS Export Rating Curve Sorted= 0
DSS Export Volume Flow Curves= 0
DXF OffsetX= 0
DXF OffsetY= 0
DXF ScaleX= 1
DXF ScaleY= 10

--- AC1.p01 (plan) ---

Plan Title=Multiple Run
Short Identifier=Multiple
Geom File=g01
Flow File=f01
Subcritical Flow
K Sum by GR= 0
Std Step Tol= 0.01
Critical Tol= 0.01
Num of Std Step Trials= 20
Max Error Tol= 0.3
Flow Tol Ratio= 0.001
Split Flow NTrial= 30
Split Flow Tol= 0.02
Split Flow Ratio= 0.02
Log Output Level= 0
Friction Slope Method= 1
Unsteady Friction Slope Method= 2
Unsteady Bridges Friction Slope Method= 1
Parabolic Critical Depth
Global Vel Dist=  1 , 1 , 1
Global Log Level= 0
CheckData=True
Encroach Param= -1, 0, 0, 0
BEGIN DESCRIPTION:
Multiple Run
END DESCRIPTION:

--- AC1.f01 (steady flow) ---

Flow Title=Multiple
Program Version=4.10
Number of Profiles= 7
Profile Names=10-year,25-year,50-year,1pct_min,100-year,1pct_plu,500-year
River Rch & RM=AC1,Reach-1         ,11851
     124     150     170     142     192     259     243
River Rch & RM=AC1,Reach-1         ,9622
     510     682     821     725     980    1326    1399
Boundary for River Rch & Prof#=AC1,Reach-1         , 1
Up Type= 0
Dn Type= 3
Dn Slope=0.005
Boundary for River Rch & Prof#=AC1,Reach-1         , 2
Up Type= 0
Dn Type= 3
Dn Slope=0.005
Boundary for River Rch & Prof#=AC1,Reach-1         , 3
Up Type= 0
Dn Type= 3
Dn Slope=0.005
Boundary for River Rch & Prof#=AC1,Reach-1         , 4
Up Type= 0
Dn Type= 3
Dn Slope=0.005
Boundary for River Rch & Prof#=AC1,Reach-1         , 5
Up Type= 0
Dn Type= 3
Dn Slope=0.005
Boundary for River Rch & Prof#=AC1,Reach-1         , 6
Up Type= 0
Dn Type= 3
Dn Slope=0.005
Boundary for River Rch & Prof#=AC1,Reach-1         , 7
Up Type= 0
Dn Type= 3
Dn Slope=0.005
DSS Import GetInterval= 0
DSS Import GetPeak= 0
DSS Import FillOption= 0

--- AC1.g01 (geometry) ---

Geom Title=Existing Conditions
Program Version=4.10

River Reach=AC1             ,Reach-1
Reach XY= 30
      3580927.49     10190352.07      3581400.44     10190012.96
      3582391.28     10188832.72      3582664.91     10188703.04
      3583007.42     10188949.27      3583434.91     10188889.21
      3583754.31     10189209.21      3584007.25     10189270.48
      3584399.61      10189092.7      3584421.14     10188907.28
       3584239.9     10188780.28      3584377.31     10188711.68
      3584330.82     10188565.14      3584457.38     10188588.57
      3584484.46     10188440.14      3584612.33     10188532.32
      3584704.34     10188355.24      3585206.51     10188336.14
      3585277.53     10187964.87      3585555.96     10188070.32
       3585484.1     10188200.65      3585687.74     10188650.72
      3586094.33     10188527.97      3586143.85      10188345.4
      3586398.21      10188239.7      3586615.13     10188396.12
      3586642.86      10188631.1      3587121.52     10188668.03
      3587161.58     10188428.83      3587612.11     10188262.96

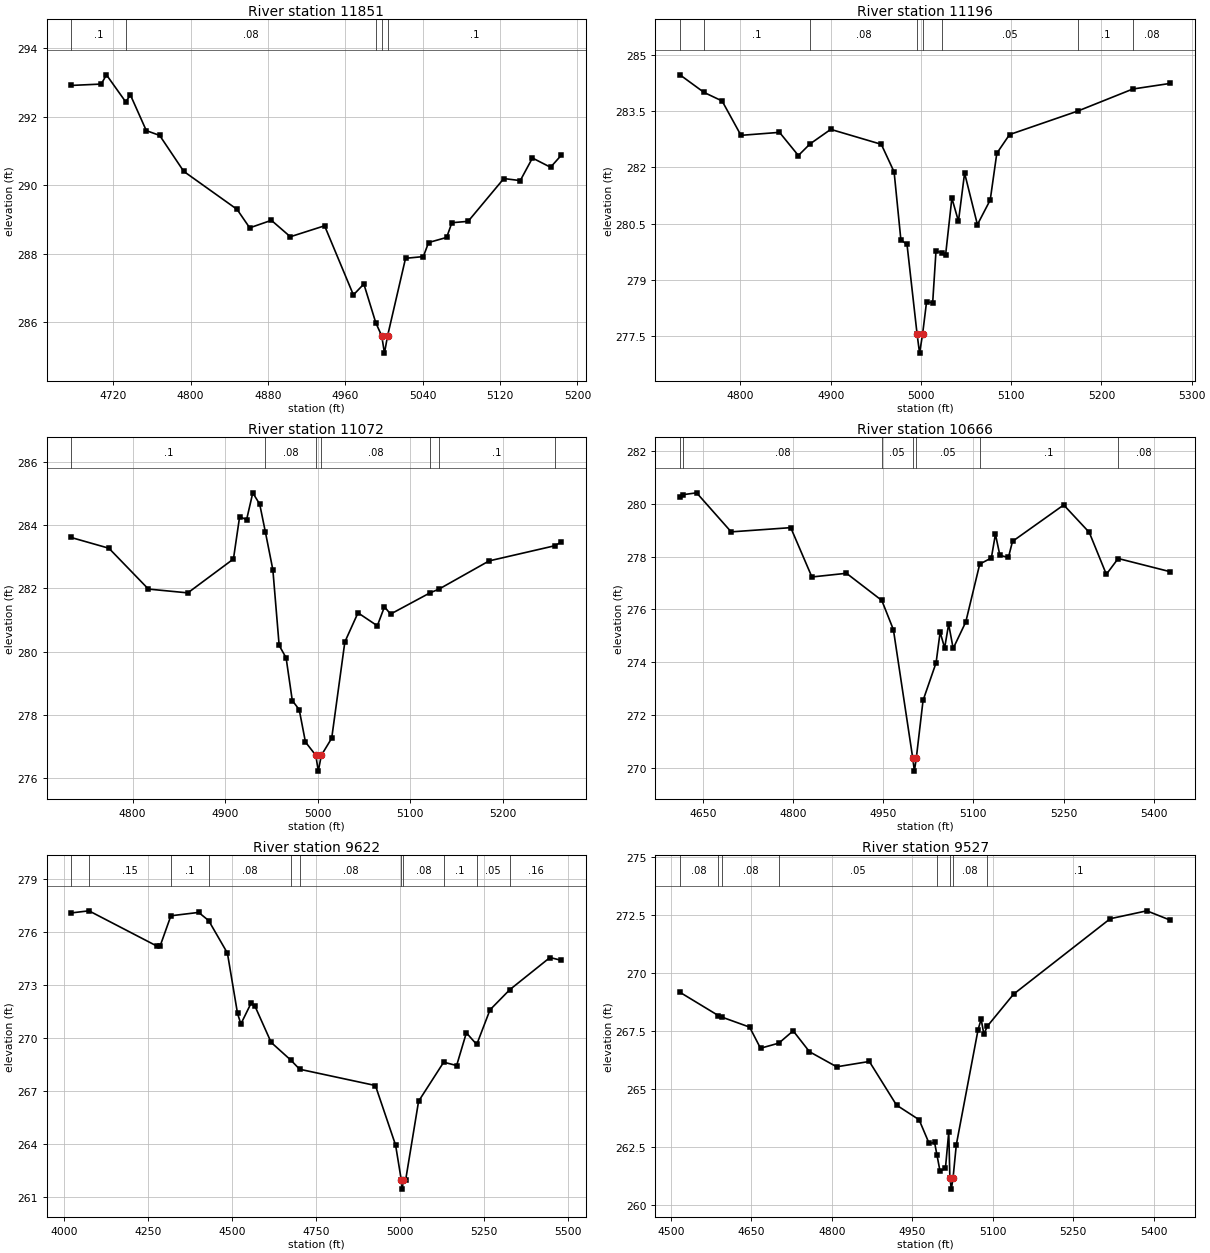
Type RM Length L Ch R = 1 ,11851   ,655,655,655
BEGIN DESCRIPTION:
AC-1 17.0
END DESCRIPTION:
XS GIS Cut Line= 3
      3581128.63     10190574.48      3581038.36     10190334.91
      3580944.62      10190102.3
#Sta/Elev= 30
  4676.5  292.91  4707.7  292.95  4713.1  293.22    4733  292.43  4737.9  292.63
  4754.3  291.59  4768.1  291.45    4793   290.4  4848.1  289.29  4861.2  288.75
  4883.6  288.97  4903.2  288.49  4938.6  288.81  4968.4  286.79  4979.2  287.11
  4991.5  285.98  4997.7  285.59  5000.5  285.09  5003.7  285.59  5022.3  287.86
  5040.7  287.91  5046.1  288.32  5064.8  288.47  5070.2   288.9    5087  288.94
  5123.9  290.19  5140.9  290.13  5153.5  290.79  5172.2  290.52  5183.3  290.87
#Mann= 5 ,-1 , 0
  4676.5      .1       0    4733     .08       0  4991.5     .05       0
  4997.7     .04       0  5003.7      .1       0
Bank Sta=4997.7,5003.7
XS Rating Curve= 0 ,0
Exp/Cntr=0.3,0.1

Type RM Length L Ch R = 1 ,11196   ,124,124,124
BEGIN DESCRIPTION:
AC-1 16.0
END DESCRIPTION:
XS GIS Cut Line= 3
      3581648.22     10190041.12      3581436.63     10189851.66
      3581259.31     10189662.63
#Sta/Elev= 30
    4733  284.48  4759.6  284.01  4779.7  283.78  4800.6  282.86  4843.3  282.94
  4864.2  282.32  4877.1  282.63  4900.1  283.02  4956.1  282.62  4970.3  281.88
  4977.8  280.06  4984.6  279.94  4995.8  277.53  4998.5  277.03  5001.8  277.53
  5006.3  278.41    5013  278.37  5016.7  279.76  5023.2  279.72  5027.4  279.67
  5034.3  281.18  5041.6  280.56  5048.4  281.85  5062.6  280.47  5076.8  281.13
  5084.1  282.38  5098.2  282.88  5173.8  283.51  5234.8   284.1  5276.2  284.25
#Mann= 8 ,-1 , 0
    4733     .08       0  4759.6      .1       0  4877.1     .08       0
  4995.8     .07       0  5001.8     .08       0  5023.2     .05       0
  5173.8      .1       0  5234.8     .08       0
Bank Sta=4995.8,5001.8
XS Rating Curve= 0 ,0
Exp/Cntr=0.3,0.1

Type RM Length L Ch R = 1 ,11072   ,406,406,406
BEGIN DESCRIPTION:
AC-1 15.0
END DESCRIPTION:
XS GIS Cut Line= 3
      3581736.48     10189954.95      3581502.14      10189745.4
      3581337.81     10189606.08
#Sta/Elev= 30
  4733.4  283.61  4774.3  283.27    4817  281.98  4859.6  281.86  4908.9  282.93
  4915.6  284.27  4923.1  284.17  4929.8  285.02  4937.3  284.66  4943.5  283.77
  4951.5  282.59  4958.3   280.2  4965.8  279.81  4972.5  278.46    4980  278.17
  4986.7  277.15  4997.9  276.73  5000.6  276.23  5003.9  276.73  5015.1  277.27
  5029.3  280.31  5043.5  281.23  5064.4  280.82  5072.1  281.42  5078.7  281.19
  5121.3  281.86  5131.1  281.98  5185.2  282.87  5256.4  283.35  5263.2  283.47
#Mann= 7 ,-1 , 0
  4733.4      .1       0  4943.5     .08       0  4997.9     .07       0
  5003.9     .08       0  5121.3     .05       0  5131.1      .1       0
  5256.4     .08       0
Bank Sta=4997.9,5003.9
XS Rating Curve= 0 ,0
Exp/Cntr=0.3,0.1

Type RM Length L Ch R = 1 ,10666   ,1007,1007,1007
BEGIN DESCRIPTION:
AC-1 14.0
END DESCRIPTION:
XS GIS Cut Line= 3
      3582031.43     10189762.02      3581824.06     10189506.38
      3581498.26     10189145.32
#Sta/Elev= 30
  4611.9  280.28  4617.1  280.35  4639.6  280.42  4697.1  278.94  4796.2   279.1
  4831.4  277.23  4888.9  277.37  4947.7  276.34    4967  275.23  4999.1  270.37
  5001.9  269.87  5005.1  270.37  5016.3  272.55    5038  273.98  5044.7  275.14
  5052.2  274.54  5058.9  275.44  5066.4  274.52  5087.3  275.52  5110.6  277.72
  5129.9  277.95  5136.7  278.85  5144.1  278.05  5158.3  277.97  5165.1  278.58
  5250.3  279.96  5292.8  278.92  5321.2  277.33  5340.9  277.93  5427.4  277.43
#Mann= 7 ,-1 , 0
  4611.9     .05       0  4617.1     .08       0  4947.7     .05       0
  4999.1     .04       0  5005.1     .05       0  5110.6      .1       0
  5340.9     .08       0
Bank Sta=4999.1,5005.1
XS Rating Curve= 0 ,0
Exp/Cntr=0.3,0.1

Type RM Length L Ch R = 1 ,9622    ,147,147,147
BEGIN DESCRIPTION:
AC-1 13.0
END DESCRIPTION:
XS GIS Cut Line= 3
      3582414.08     10189766.48       3582478.7     10188703.74
      3582520.36     10188310.54
#Sta/Elev= 30
    4020  277.08  4073.3   277.2  4275.3  275.21  4285.3  275.21  4317.4  276.92
    4400  277.11  4429.8  276.65  4485.7  274.81  4515.8   271.4  4525.8   270.8
  4555.8  271.96  4567.5  271.82  4615.9  269.76  4674.9  268.75  4700.9  268.24
  4926.5  267.32  4986.6  263.95  5003.7  261.96  5006.4  261.46  5009.7  261.96
  5016.7  261.99  5055.1  266.43  5129.9  268.64  5168.4  268.45  5197.4   270.3
  5228.3  269.64  5267.8   271.6  5326.7  272.74  5446.5  274.56  5480.1   274.4
#Mann= 11 ,-1 , 0
    4020      .1       0  4073.3     .15       0  4317.4      .1       0
  4429.8     .08       0  4674.9     .05       0  4700.9     .08       0
  5003.7     .07       0  5009.7     .08       0  5129.9      .1       0
  5228.3     .05       0  5326.7     .16       0
Bank Sta=5003.7,5009.7
XS Rating Curve= 0 ,0
Exp/Cntr=0.3,0.1

Type RM Length L Ch R = 1 ,9527    ,591,591,591
BEGIN DESCRIPTION:
AC-1 12.0
END DESCRIPTION:
XS GIS Cut Line= 3
      3582533.39     10189229.76      3582667.11     10188438.69
      3582717.11     10188338.69
#Sta/Elev= 30
  4516.6  269.18    4588  268.18  4594.9  268.11  4646.5  267.68  4666.8  266.77
    4701  266.99  4727.7  267.52  4758.1  266.62  4808.8  265.97  4869.7   266.2
  4920.4  264.32  4962.5  263.69  4981.2  262.67  4991.4  262.71  4995.9  262.16
  5001.5  261.48  5011.6  261.59  5017.8  263.16  5019.9   261.2  5022.6   260.7
  5025.9   261.2  5031.9  262.61  5072.5  267.57  5078.2  268.02  5083.3  267.38
  5089.8  267.72  5138.7   269.1  5318.9  272.35  5387.1  272.69  5430.7  272.29
#Mann= 8 ,-1 , 0
  4516.6     .08       0    4588     .05       0  4594.9     .08       0
    4701     .05       0  4995.9     .08       0  5019.9     .07       0
  5025.9     .08       0  5089.8      .1       0
Bank Sta=5019.9,5025.9
XS Rating Curve= 0 ,0
Exp/Cntr=0.3,0.1

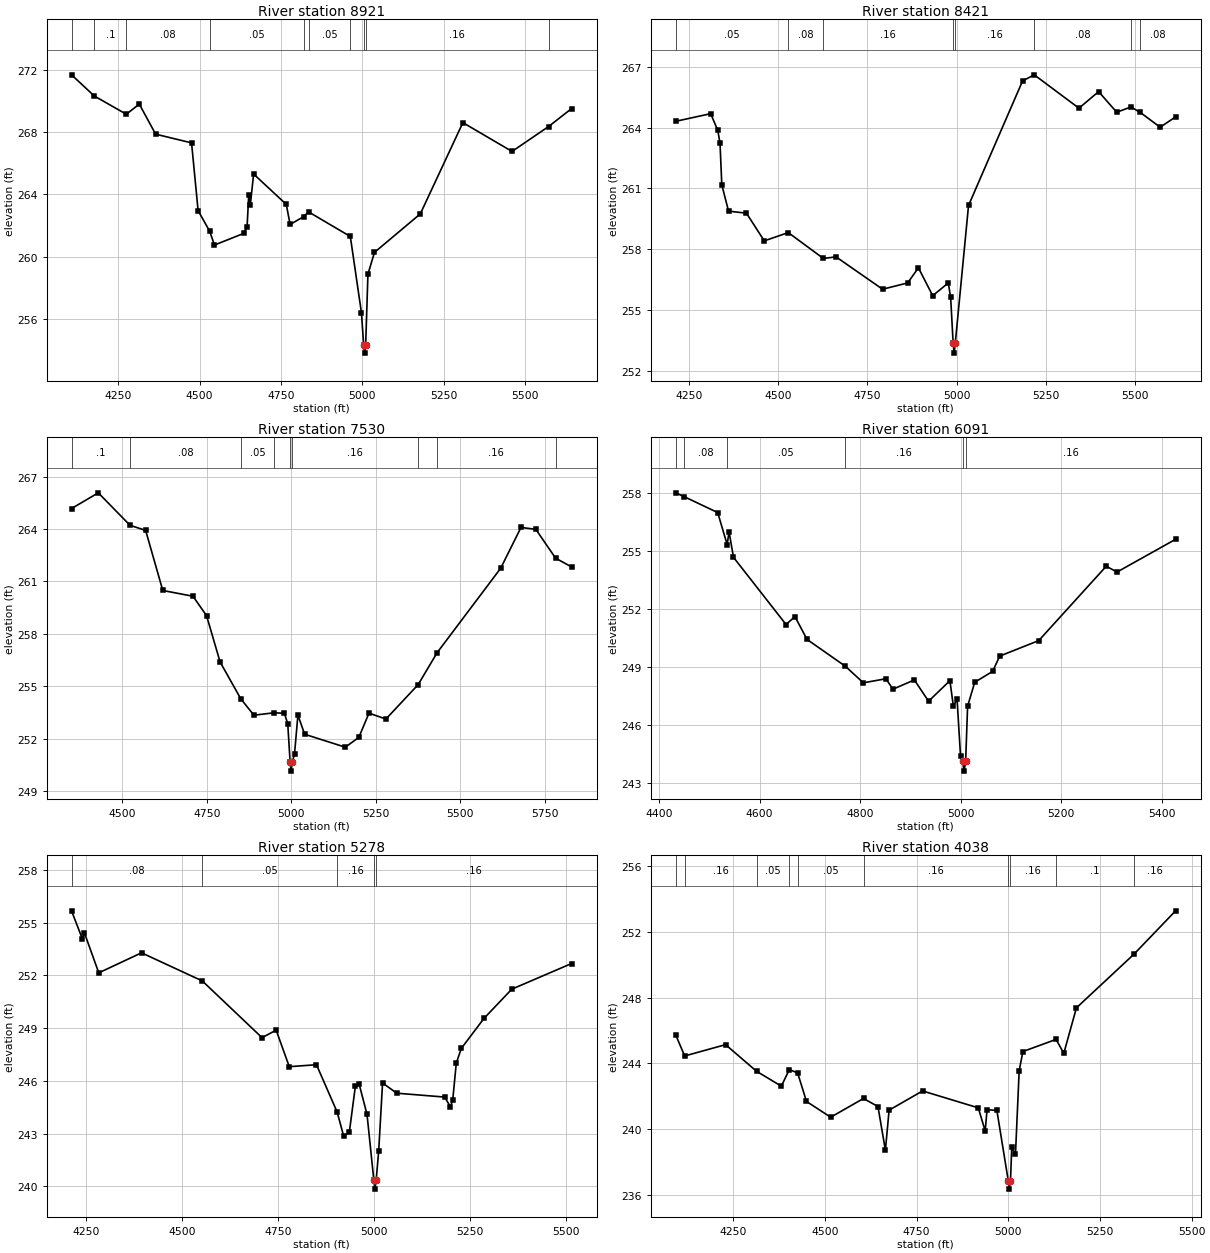
Type RM Length L Ch R = 1 ,8921    ,500,500,500
BEGIN DESCRIPTION:
AC-1 11.0
END DESCRIPTION:
XS GIS Cut Line= 3
       3582973.1     10189829.03      3583055.72      10188810.6
      3583114.75     10188300.18
#Sta/Elev= 30
    4107  271.68  4176.9  270.32  4275.2  269.15  4315.1   269.8  4365.2  267.87
  4475.6  267.31  4495.7  262.96  4531.5  261.63  4545.8  260.75  4636.1   261.5
  4646.2  261.94  4651.2  263.97  4656.2  263.35  4666.2  265.31  4766.5  263.36
  4778.3  262.07  4819.4  262.57  4834.8  262.88  4963.2   261.3  4997.3  256.41
  5004.3  254.31  5007.1  253.81  5010.3  254.31  5017.3  258.88  5037.4  260.28
  5178.1  262.75  5308.9  268.61  5459.9  266.76  5572.1  268.36  5642.6  269.51
#Mann= 10 ,-1 , 0
    4107     .08       0  4176.9      .1       0  4275.2     .08       0
  4531.5     .05       0  4819.4     .08       0  4834.8     .05       0
  4963.2     .16       0  5004.3     .07       0  5010.3     .16       0
  5572.1     .08       0
Bank Sta=5004.3,5010.3
XS Rating Curve= 0 ,0
Exp/Cntr=0.3,0.1

Type RM Length L Ch R = 1 ,8421    ,891,891,891
BEGIN DESCRIPTION:
AC-1 10.0
END DESCRIPTION:
XS GIS Cut Line= 3
      3583427.24     10189699.52      3583496.97     10188814.56
      3583581.69     10188309.01
#Sta/Elev= 30
  4212.6  264.32  4310.8   264.7  4330.8  263.87    4337  263.24    4342  261.18
  4360.9  259.88  4411.1  259.78  4460.9  258.41  4528.2  258.82  4626.5  257.54
  4661.9  257.62  4792.3  256.02  4862.5  256.33  4892.6  257.08  4932.7   255.7
  4976.3  256.33  4982.9  255.62  4989.9  253.36  4992.6  252.86  4995.9  253.36
    5033  260.16  5184.4  266.32    5217  266.62  5342.3  264.97  5397.3  265.79
    5448  264.77  5487.7  265.03    5514  264.76  5569.7  264.03  5612.9  264.54
#Mann= 8 ,-1 , 0
  4212.6     .05       0  4528.2     .08       0  4626.5     .16       0
  4989.9     .07       0  4995.9     .16       0    5217     .08       0
  5487.7     .16       0    5514     .08       0
Bank Sta=4989.9,4995.9
XS Rating Curve= 0 ,0
Exp/Cntr=0.3,0.1

Type RM Length L Ch R = 1 ,7530    ,1439,1439,1439
BEGIN DESCRIPTION:
AC-1 9.0
END DESCRIPTION:
XS GIS Cut Line= 3
      3584076.55     10189810.56      3584041.41     10188823.59
      3583842.08     10188375.08
#Sta/Elev= 30
  4350.3  265.17  4429.3  266.07  4523.3  264.21  4569.4  263.92  4620.1  260.48
  4709.4  260.15  4749.5  259.04  4789.5  256.39  4850.7  254.28  4889.6  253.34
  4949.2  253.48  4979.6  253.45  4989.6  252.85  4996.6  250.64  4999.4  250.14
  5002.6  250.64  5009.6  251.12  5019.6  253.35  5039.6  252.25  5159.7  251.51
  5199.8  252.07  5229.8  253.46  5279.8  253.12  5375.1  255.09  5431.3  256.92
  5619.1  261.75  5679.3  264.09  5723.2  263.98  5781.5  262.33  5828.7  261.83
#Mann= 9 ,-1 , 0
  4350.3      .1       0  4523.3     .08       0  4850.7     .05       0
  4949.2     .16       0  4996.6     .07       0  5002.6     .16       0
  5375.1     .05       0  5431.3     .16       0  5781.5     .05       0
Bank Sta=4996.6,5002.6
XS Rating Curve= 0 ,0
Exp/Cntr=0.3,0.1

Type RM Length L Ch R = 1 ,6091    ,813,813,813
BEGIN DESCRIPTION:
AC-1 7.0
END DESCRIPTION:
XS GIS Cut Line= 3
      3584677.23     10189091.81      3584559.19     10188706.44
      3584128.64     10188300.19
#Sta/Elev= 30
    4433  257.99  4449.4   257.8  4516.8  256.97  4535.6  255.32  4539.4  255.98
  4548.2  254.66  4652.8  251.19  4670.5   251.6  4694.6  250.42  4770.6  249.04
  4806.7  248.18  4851.5  248.39  4865.6  247.85  4908.1  248.33  4936.4  247.23
  4978.9  248.29  4985.8  246.97  4993.1  247.35    5000  244.41  5004.2  244.12
    5007  243.62  5010.2  244.12  5014.1  246.97  5028.3  248.21  5063.9  248.77
    5078  249.56  5155.7  250.36    5290   254.2  5311.5   253.9    5428  255.59
#Mann= 6 ,-1 , 0
    4433     .05       0  4449.4     .08       0  4535.6     .05       0
  4770.6     .16       0  5004.2     .07       0  5010.2     .16       0
Bank Sta=5004.2,5010.2
XS Rating Curve= 0 ,0
Exp/Cntr=0.3,0.1

Type RM Length L Ch R = 1 ,5278    ,1240,1240,1240
BEGIN DESCRIPTION:
AC-1 5.0
END DESCRIPTION:
XS GIS Cut Line= 3
      3584992.11     10189141.65      3584854.33      10188286.3
      3584614.77     10187921.75
#Sta/Elev= 30
  4211.9  255.68  4240.3  254.07  4245.4  254.43  4282.8  252.15  4394.2  253.29
  4552.5  251.69  4708.2  248.46    4745  248.89  4779.1  246.81    4850  246.92
    4904  244.22  4920.9  242.85  4935.6  243.08  4951.3  245.69  4961.4   245.8
  4981.7  244.09  4999.5  240.34  5002.2  239.84  5005.5  240.34  5012.1  242.01
  5022.2  245.88  5059.2   245.3    5184  245.08  5199.1  244.52  5205.1  244.93
  5214.2  247.01  5227.4  247.85  5286.5  249.56  5358.8  251.22  5514.5  252.68
#Mann= 5 ,-1 , 0
  4211.9     .08       0  4552.5     .05       0    4904     .16       0
  4999.5     .07       0  5005.5     .16       0
Bank Sta=4999.5,5005.5
XS Rating Curve= 0 ,0
Exp/Cntr=0.3,0.1

Type RM Length L Ch R = 1 ,4038    ,1358,1358,1358
BEGIN DESCRIPTION:
AC-1 4.0
END DESCRIPTION:
XS GIS Cut Line= 3
      3585486.05      10188886.1      3585298.77     10187758.52
      3585208.51     10187557.15
#Sta/Elev= 30
  4092.5  245.75  4117.2  244.45  4228.8  245.14  4313.2  243.52  4380.9  242.61
  4402.6  243.62  4425.3  243.42  4449.5  241.68  4515.5  240.72    4605  241.86
  4644.4  241.37  4664.7  238.71  4674.8  241.15  4766.1  242.32  4918.1  241.29
  4936.9  239.88    4942  241.18  4968.8  241.13  4999.9  236.84  5002.7  236.34
  5005.9  236.84  5009.3  238.88  5019.5  238.46  5029.6  243.56  5039.8  244.72
  5130.2  245.46  5151.3  244.61  5185.7  247.38  5342.7  250.65  5456.2  253.29
#Mann= 10 ,-1 , 0
  4092.5     .08       0  4117.2     .16       0  4313.2     .05       0
  4402.6     .16       0  4425.3     .05       0    4605     .16       0
  4999.9     .07       0  5005.9     .16       0  5130.2      .1       0
  5342.7     .16       0
Bank Sta=4999.9,5005.9
XS Rating Curve= 0 ,0
Exp/Cntr=0.3,0.1

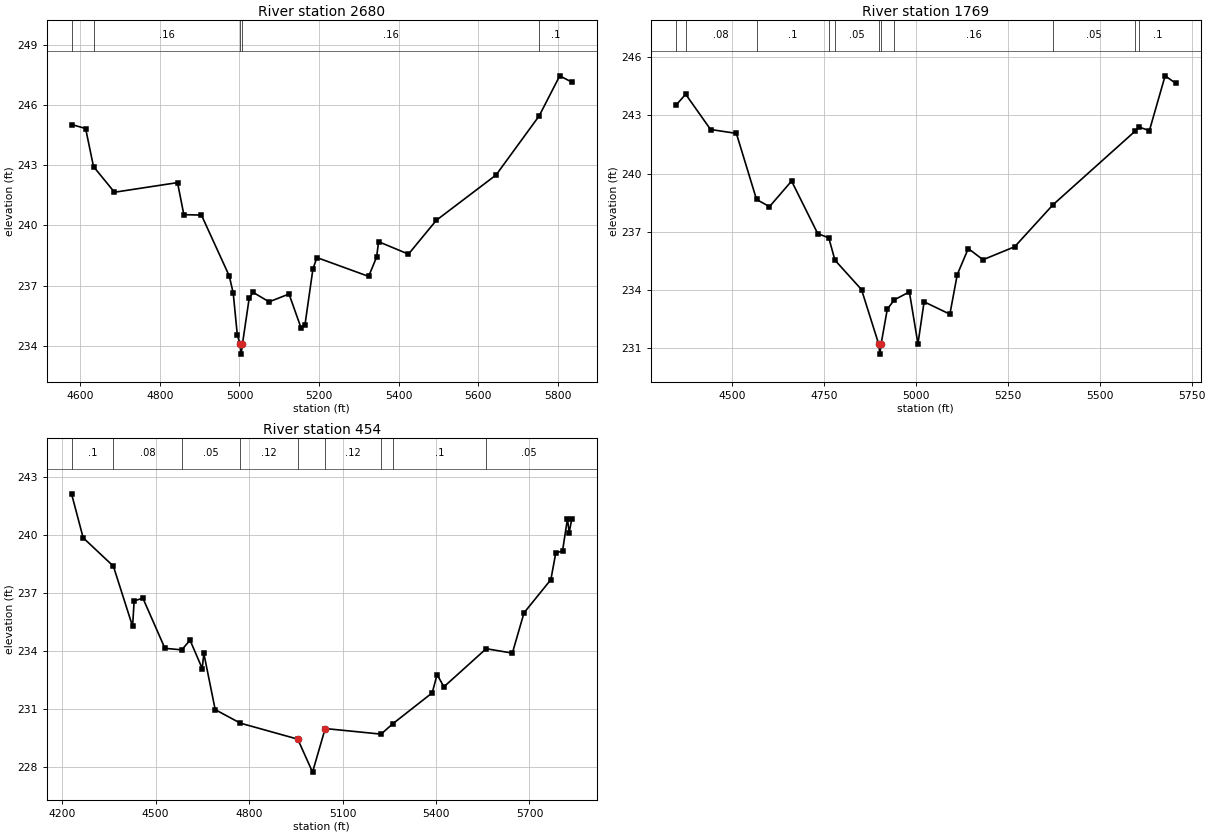
Type RM Length L Ch R = 1 ,2680    ,911,911,911
BEGIN DESCRIPTION:
AC-1 3.0
END DESCRIPTION:
XS GIS Cut Line= 3
      3585842.11     10188891.63      3585968.91     10188689.08
      3585927.25      10187671.7
#Sta/Elev= 30
  4577.9  245.04  4613.3  244.84  4633.1  242.94  4685.8  241.66  4844.3  242.14
  4860.2  240.54  4904.4  240.52  4974.4  237.48  4984.4  236.61  4994.5  234.55
  5001.5  234.08  5004.2  233.58  5007.5  234.08  5024.5  236.38  5034.5  236.66
  5074.5  236.19  5124.6  236.58  5154.6   234.9  5164.6  235.03  5184.6  237.82
  5194.6   238.4  5324.7  237.46  5344.7  238.42  5349.8  239.19  5424.8  238.57
  5494.9  240.26    5645  242.52  5753.4  245.47  5805.1  247.47  5835.1  247.16
#Mann= 5 ,-1 , 0
  4577.9     .08       0  4633.1     .16       0  5001.5     .07       0
  5007.5     .16       0  5753.4      .1       0
Bank Sta=5001.5,5007.5
XS Rating Curve= 0 ,0
Exp/Cntr=0.3,0.1

Type RM Length L Ch R = 1 ,1769    ,1315,1315,1315
BEGIN DESCRIPTION:
AC-1 2.0
END DESCRIPTION:
XS GIS Cut Line= 3
      3586493.22     10189036.32      3586526.02     10188135.16
      3586292.13     10187741.68
#Sta/Elev= 30
  4347.6  243.51  4374.6  244.09  4442.3  242.27  4512.4  242.07  4567.2  238.66
  4602.4  238.29  4662.5  239.61  4733.5   236.9  4763.6  236.68  4780.3  235.53
  4852.6  234.01  4899.6  231.18  4902.4  230.68  4905.6  231.18  4922.7     233
  4941.6  233.48  4982.7  233.89    5006  231.21  5022.7  233.38  5092.8  232.74
  5112.8  234.78  5142.8  236.13  5182.8  235.55  5268.9  236.22  5372.7  238.38
  5597.2   242.2  5606.8   242.4  5635.1  242.21  5677.9  245.04  5707.1  244.65
#Mann= 11 ,-1 , 0
  4347.6      .1       0  4374.6     .08       0  4567.2      .1       0
  4763.6     .08       0  4780.3     .05       0  4899.6     .07       0
  4905.6     .05       0  4941.6     .16       0  5372.7     .05       0
  5597.2     .16       0  5606.8      .1       0
Bank Sta=4899.6,4905.6
XS Rating Curve= 0 ,0
Exp/Cntr=0.3,0.1

Type RM Length L Ch R = 1 ,454     ,0,0,0
BEGIN DESCRIPTION:
AC-1 1.0
END DESCRIPTION:
XS GIS Cut Line= 3
      3587333.49     10189178.62      3587215.44     10188300.19
      3586592.13     10187941.66
#Sta/Elev= 30
    4230  242.15  4267.3  239.87  4364.2   238.4  4425.9  235.28    4431   236.6
    4459  236.74  4529.7  234.14  4583.7  234.06  4610.4  234.56  4649.5  233.09
  4654.6  233.88  4691.1  230.96  4771.8  230.26  4956.1  229.43  5003.6  227.72
  5044.2  229.98  5223.6  229.69  5260.6  230.22  5387.7  231.83  5403.5  232.78
  5425.1  232.14    5561  234.12    5645  233.89  5682.4  235.98  5768.6   237.7
  5784.4  239.09    5806  239.18  5821.8  240.85  5827.5  240.14  5835.4  240.82
#Mann= 9 ,-1 , 0
    4230      .1       0  4364.2     .08       0  4583.7     .05       0
  4771.8     .12       0  4956.1    .055       0  5044.2     .12       0
  5223.6     .05       0  5260.6      .1       0    5561     .05       0
Bank Sta=4956.1,5044.2
XS Rating Curve= 0 ,0
Exp/Cntr=0.3,0.1
Stream Node=AC1             ,Reach-1         , 0 , 0 ,Upstream end
Stream Node=AC1             ,Reach-1         , 0 , 1 ,Downstream end

Chan Stop Cuts=-1
Use User Specified Reach Order=0
Composite Channel Slope=5