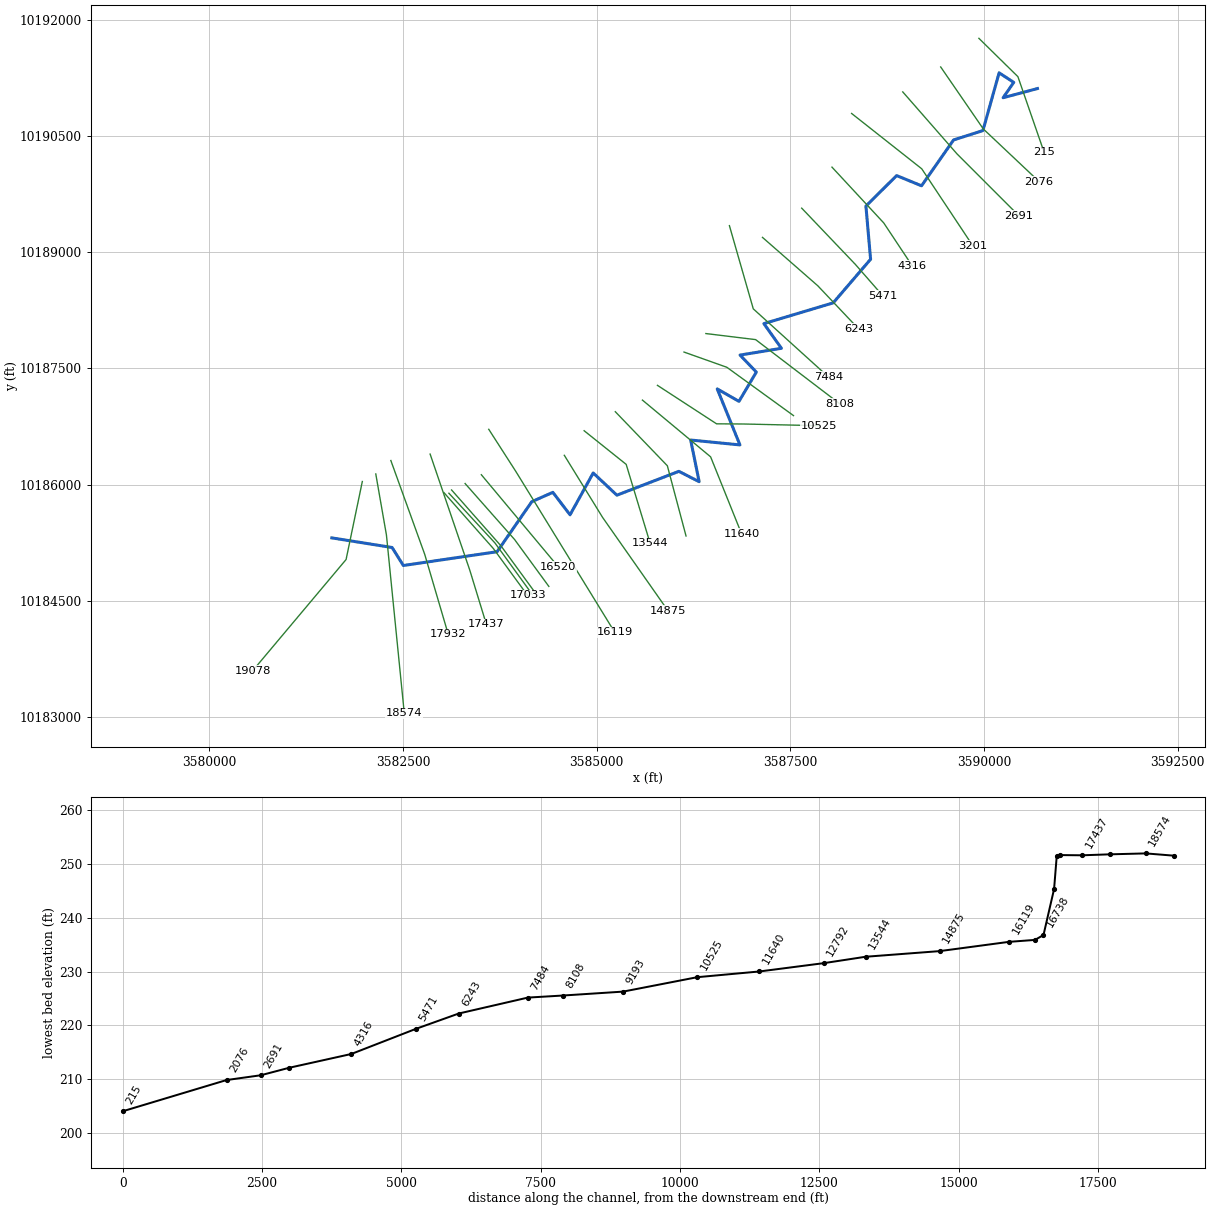
--- ALUM CREEK 2.prj (project) ---

Proj Title=ALUM CREEK 2 Base Level Engineering
Current Plan=p01
Default Exp/Contr=0.3,0.1
English Units
Geom File=g01
Flow File=f01
Plan File=p01
Y Axis Title=Elevation
X Axis Title(PF)=Main Channel Distance
X Axis Title(XS)=Station
BEGIN DESCRIPTION:
ALUM CREEK 2
END DESCRIPTION:
DSS Export Rating Curves= 0
DSS Export Rating Curve Sorted= 0
DSS Export Volume Flow Curves= 0
DXF OffsetX= 0
DXF OffsetY= 0
DXF ScaleX= 1
DXF ScaleY= 10

--- ALUM CREEK 2.p01 (plan) ---

Plan Title=Multiple Run
Short Identifier=Multiple
Geom File=g01
Flow File=f01
Subcritical Flow
K Sum by GR= 0
Std Step Tol= 0.01
Critical Tol= 0.01
Num of Std Step Trials= 20
Max Error Tol= 0.3
Flow Tol Ratio= 0.001
Split Flow NTrial= 30
Split Flow Tol= 0.02
Split Flow Ratio= 0.02
Log Output Level= 0
Friction Slope Method= 1
Unsteady Friction Slope Method= 2
Unsteady Bridges Friction Slope Method= 1
Parabolic Critical Depth
Global Vel Dist=  1 , 1 , 1
Global Log Level= 0
CheckData=True
Encroach Param= -1, 0, 0, 0
BEGIN DESCRIPTION:
Multiple Run
END DESCRIPTION:

--- ALUM CREEK 2.f01 (steady flow) ---

Flow Title=Multiple
Program Version=4.10
Number of Profiles= 7
Profile Names=10-year,25-year,50-year,1pct_min,100-year,1pct_plu,500-year
River Rch & RM=ALUM CREEK 2,Reach-1         ,19078
     497     661     793     698     943    1276    1337
River Rch & RM=ALUM CREEK 2,Reach-1         ,18574
     846    1160    1419    1271    1719    2325    2530
River Rch & RM=ALUM CREEK 2,Reach-1         ,17932
     928    1281    1575    1418    1917    2593    2847
River Rch & RM=ALUM CREEK 2,Reach-1         ,16520
     967    1330    1630    1460    1975    2671    2909
River Rch & RM=ALUM CREEK 2,Reach-1         ,10525
    1051    1448    1777    1595    2157    2917    3184
River Rch & RM=ALUM CREEK 2,Reach-1         ,9193
    1051    1448    1777    1595    2157    2917    3184
River Rch & RM=ALUM CREEK 2,Reach-1         ,7484
    1333    1854    2289    2064    2791    3774    4162
River Rch & RM=ALUM CREEK 2,Reach-1         ,6243
    1333    1854    2289    2064    2791    3774    4162
Boundary for River Rch & Prof#=ALUM CREEK 2,Reach-1         , 1
Up Type= 0
Dn Type= 3
Dn Slope=0.005
Boundary for River Rch & Prof#=ALUM CREEK 2,Reach-1         , 2
Up Type= 0
Dn Type= 3
Dn Slope=0.005
Boundary for River Rch & Prof#=ALUM CREEK 2,Reach-1         , 3
Up Type= 0
Dn Type= 3
Dn Slope=0.005
Boundary for River Rch & Prof#=ALUM CREEK 2,Reach-1         , 4
Up Type= 0
Dn Type= 3
Dn Slope=0.005
Boundary for River Rch & Prof#=ALUM CREEK 2,Reach-1         , 5
Up Type= 0
Dn Type= 3
Dn Slope=0.005
Boundary for River Rch & Prof#=ALUM CREEK 2,Reach-1         , 6
Up Type= 0
Dn Type= 3
Dn Slope=0.005
Boundary for River Rch & Prof#=ALUM CREEK 2,Reach-1         , 7
Up Type= 0
Dn Type= 3
Dn Slope=0.005
DSS Import GetInterval= 0
DSS Import GetPeak= 0
DSS Import FillOption= 0

--- ALUM CREEK 2.g01 (geometry) ---

Geom Title=Existing Conditions
Program Version=4.10

River Reach=ALUM CREEK 2    ,Reach-1
Reach XY= 30
      3581582.48     10185313.05       3582360.5     10185189.08
      3582505.78     10184956.58      3583716.57     10185134.59
      3584163.41     10185779.87      3584435.78      10185901.1
      3584657.62     10185610.77      3584956.81     10186151.04
      3585262.22     10185864.22      3586062.35     10186172.07
       3586324.4     10186038.23      3586214.75     10186576.21
      3586850.93     10186513.05      3586557.61     10187235.77
      3586838.34     10187075.27      3587062.31      10187453.3
      3586852.01     10187672.77      3587386.26     10187760.25
      3587159.64     10188078.82      3588054.46     10188346.68
      3588537.21     10188909.61      3588476.93     10189595.84
      3588873.57     10189989.57      3589194.58     10189857.75
      3589608.26     10190449.41       3589987.1     10190570.75
      3590196.13     10191316.02       3590385.1     10191192.78
      3590247.94     10190994.73      3590691.18     10191113.09

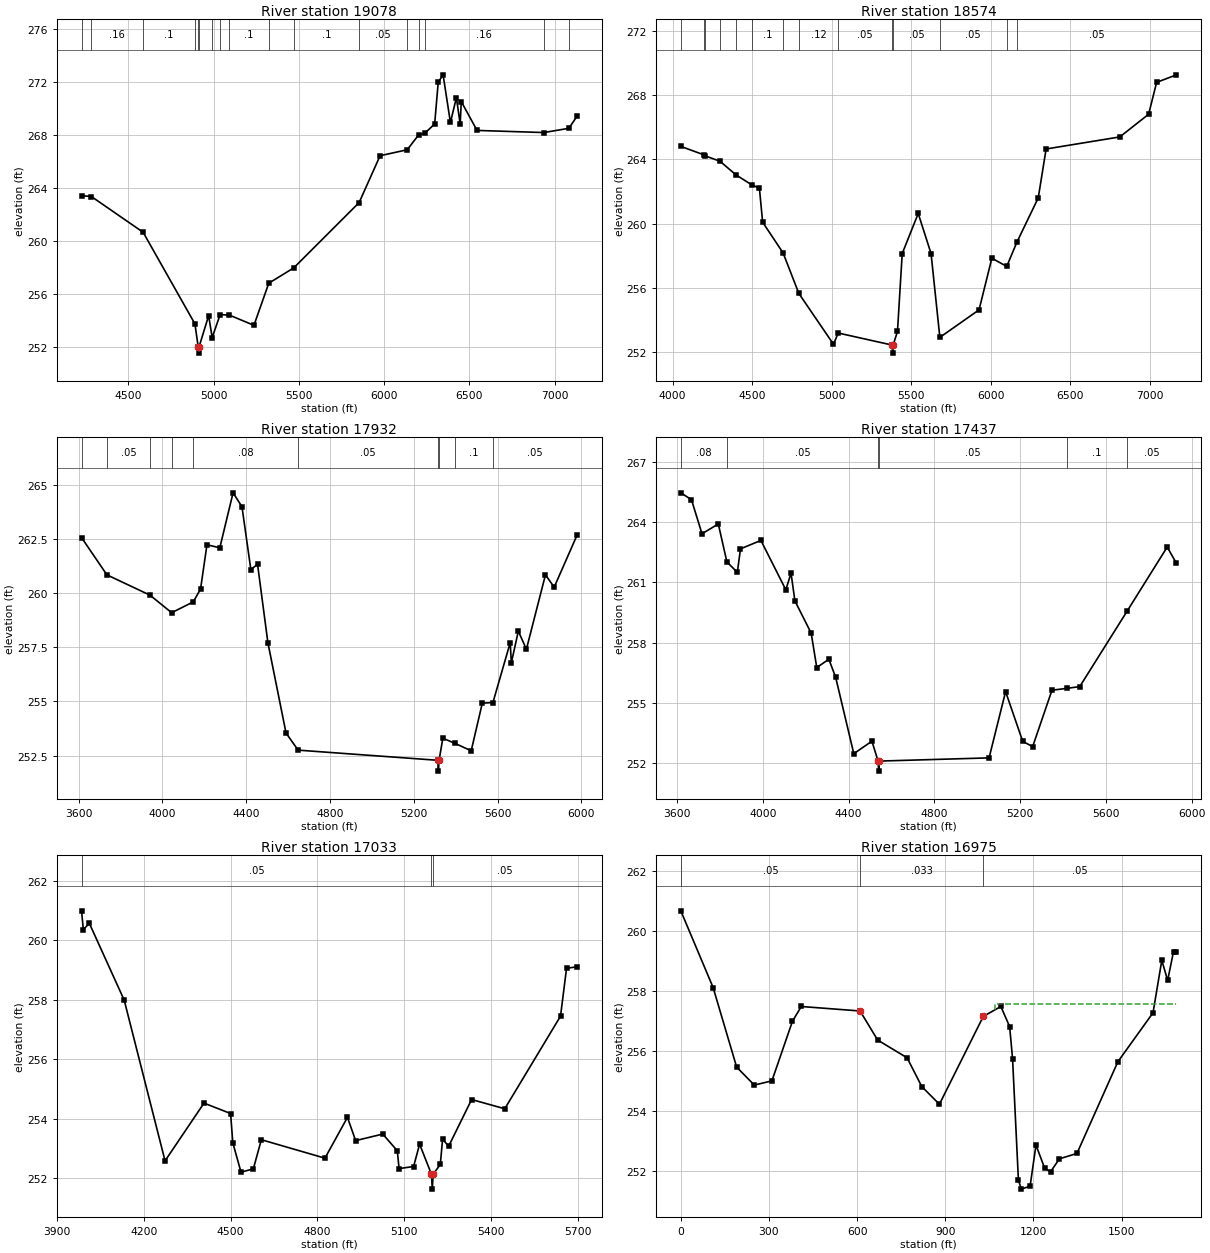
Type RM Length L Ch R = 1 ,19078   ,504,504,504
BEGIN DESCRIPTION:
ALUM CREEK 2 29.0
END DESCRIPTION:
XS GIS Cut Line= 3
      3581976.56     10186040.92      3581766.87     10185033.81
      3580559.95     10183596.56
#Sta/Elev= 30
  4226.2  263.42  4283.4  263.36    4587  260.66  4890.7  253.74  4909.6  252.03
  4912.4  251.53  4915.6  252.03  4971.1  254.36  4991.9  252.71  5038.5  254.44
  5093.1   254.4  5236.7  253.63  5323.6  256.81  5470.2  257.97  5853.3   262.9
  5976.2  266.44  6135.2  266.89  6203.3  268.03  6237.2  268.12  6296.1  268.84
    6317  271.99  6345.6  272.55  6388.5  268.95  6423.6  270.83  6445.7  268.83
  6452.2  270.53  6544.6  268.35  6936.4  268.19    7083  268.51  7131.7  269.44
#Mann= 17 ,-1 , 0
  4226.2      .1       0  4283.4     .16       0    4587      .1       0
  4890.7     .05       0  4909.6     .07       0  4915.6     .05       0
  4991.9     .12       0  5038.5     .16       0  5093.1      .1       0
  5323.6     .05       0  5470.2      .1       0  5853.3     .05       0
  6135.2     .16       0  6203.3     .05       0  6237.2     .16       0
  6936.4     .05       0    7083      .1       0
Bank Sta=4909.6,4915.6
XS Rating Curve= 0 ,0
Exp/Cntr=0.3,0.1

Type RM Length L Ch R = 1 ,18574   ,642,642,642
BEGIN DESCRIPTION:
ALUM CREEK 2 28.0
END DESCRIPTION:
XS GIS Cut Line= 3
      3582150.19     10186138.12       3582287.7     10185350.65
      3582518.24     10183047.85
#Sta/Elev= 30
  4051.9   264.8    4199  264.27  4205.7  264.21  4298.1  263.88  4397.2  263.04
  4496.2  262.42  4545.7   262.2    4566  260.09  4694.4  258.18  4793.5  255.66
  5011.1   252.5  5040.7   253.2  5379.9  252.45  5382.7  251.95  5385.9  252.45
  5413.1   253.3  5442.9  258.14  5543.4  260.63  5624.1  258.14  5679.3  252.93
  5925.6  254.64    6006  257.85  6099.6  257.34    6163  258.84  6297.5   261.6
  6346.9  264.64    6810  265.39  6990.9   266.8  7041.2  268.78  7165.6  269.25
#Mann= 14 ,-1 , 0
  4051.9     .05       0    4199     .16       0  4205.7     .08       0
  4298.1      .1       0  4397.2     .16       0  4496.2      .1       0
  4694.4     .08       0  4793.5     .12       0  5040.7     .05       0
  5379.9     .07       0  5385.9     .05       0  5679.3     .05       0
  6099.6     .08       0    6163     .05       0
Bank Sta=5379.9,5385.9
XS Rating Curve= 0 ,0
Exp/Cntr=0.3,0.1

Type RM Length L Ch R = 1 ,17932   ,495,495,495
BEGIN DESCRIPTION:
ALUM CREEK 2 27.0
END DESCRIPTION:
XS GIS Cut Line= 3
      3582344.63     10186311.76       3582782.5     10185098.92
       3583086.2     10184066.32
#Sta/Elev= 30
  3614.2  262.57  3735.1  260.85  3941.1  259.91  4044.2   259.1  4147.2   259.6
  4182.1  260.19  4212.7  262.24  4274.1   262.1  4337.3  264.64  4379.8     264
  4422.3  261.09  4454.2  261.34  4503.5  257.72  4590.2  253.54  4647.9  252.75
  5314.8  252.28  5317.5  251.78  5320.8  252.28  5338.6   253.3  5394.9  253.07
  5474.1  252.72    5527  254.92  5577.8  254.95  5660.4  257.72  5665.6  256.78
    5699  258.25  5737.5  257.41  5828.5  260.85  5870.2  260.28    5980   262.7
#Mann= 10 ,-1 , 0
  3614.2     .08       0  3735.1     .05       0  3941.1     .08       0
  4044.2     .05       0  4147.2     .08       0  4647.9     .05       0
  5314.8    .033       0  5320.8     .05       0  5394.9      .1       0
  5577.8     .05       0
Bank Sta=5314.8,5320.8
XS Rating Curve= 0 ,0
Exp/Cntr=0.3,0.1

Type RM Length L Ch R = 1 ,17437   ,404,404,404
BEGIN DESCRIPTION:
ALUM CREEK 2 25.0
END DESCRIPTION:
XS GIS Cut Line= 3
      3582851.56     10186395.14      3583364.09     10184894.92
      3583576.76     10184200.51
#Sta/Elev= 30
  3617.4  265.46  3667.1  265.12  3716.2  263.42  3792.3  263.91  3832.3  262.02
    3881   261.5  3895.8  262.67    3991  263.09  4107.2  260.63  4131.5  261.46
  4149.5  260.08  4225.5  258.47  4251.5  256.76    4308  257.17  4339.7  256.27
  4424.2  252.47  4508.8  253.09  4537.5   252.1  4540.2   251.6  4543.5   252.1
  5055.2  252.26  5132.2  255.56  5212.2  253.08  5258.5  252.82  5348.5  255.63
  5416.8  255.72  5478.1  255.81    5698  259.55    5886  262.76    5929  261.95
#Mann= 6 ,-1 , 0
  3617.4     .08       0  3832.3     .05       0  4537.5    .033       0
  4543.5     .05       0  5416.8      .1       0    5698     .05       0
Bank Sta=4537.5,4543.5
XS Rating Curve= 0 ,0
Exp/Cntr=0.3,0.1

Type RM Length L Ch R = 1 ,17033   ,58,58,58
BEGIN DESCRIPTION:
ALUM CREEK 2 24.2
END DESCRIPTION:
XS GIS Cut Line= 3
       3583029.9     10185897.52      3583668.67     10185174.45
      3584110.63     10184569.39
#Sta/Elev= 30
  3984.8  260.99  3990.8  260.36  4011.7  260.57  4132.2  257.99  4273.5  252.59
  4408.2  254.53  4500.2  254.18  4507.8   253.2  4536.2  252.21  4578.9  252.32
  4606.5   253.3  4826.5  252.68  4904.3  254.05  4932.7  253.27  5026.5  253.49
  5076.7  252.93  5082.9  252.33  5133.1   252.4  5153.9  253.15  5194.9  252.14
  5197.7  251.64  5200.9  252.14  5225.5  252.47  5233.4  253.32  5254.3  253.08
  5333.8  254.65  5448.4  254.34  5641.2  257.45  5662.1  259.06  5698.9  259.11
#Mann= 3 ,-1 , 0
  3984.8     .05       0  5194.9    .033       0  5200.9     .05       0
Bank Sta=5194.9,5200.9
XS Rating Curve= 0 ,0
Exp/Cntr=0.3,0.1

Type RM Length L Ch R = 1 ,16975   ,47,47,47
XS GIS Cut Line= 3
     3583094.022    10185889.583      3583688.62    10185247.222
     3584170.391    10184583.159
#Sta/Elev= 30
       0  260.66     110   258.1     190  255.45     250  254.85     310  254.99
  379.99  256.98  409.99  257.47  609.99  257.32  669.99  256.35  769.99  255.76
  819.99   254.8  879.99  254.21 1029.35  257.14 1089.09  257.47 1118.96   256.8
 1128.92  255.73 1148.83  251.68 1158.79  251.38 1188.66  251.48 1208.58  252.85
 1238.45  252.07 1258.36  251.96 1288.23  252.39 1347.98  252.57 1487.38  255.63
 1606.87  257.26 1636.74  259.01 1656.65  258.34 1676.57   259.3 1686.52   259.3
#Mann= 3 ,-1 , 0
       0     .05       0  609.99    .033       0 1029.35     .05       0
#XS Ineff= 2 , 0
                         1067.73          257.54
Permanent Ineff=
       F       F
Bank Sta=609.99,1029.35
XS Rating Curve= 0 ,0
Exp/Cntr=0.3,0.1

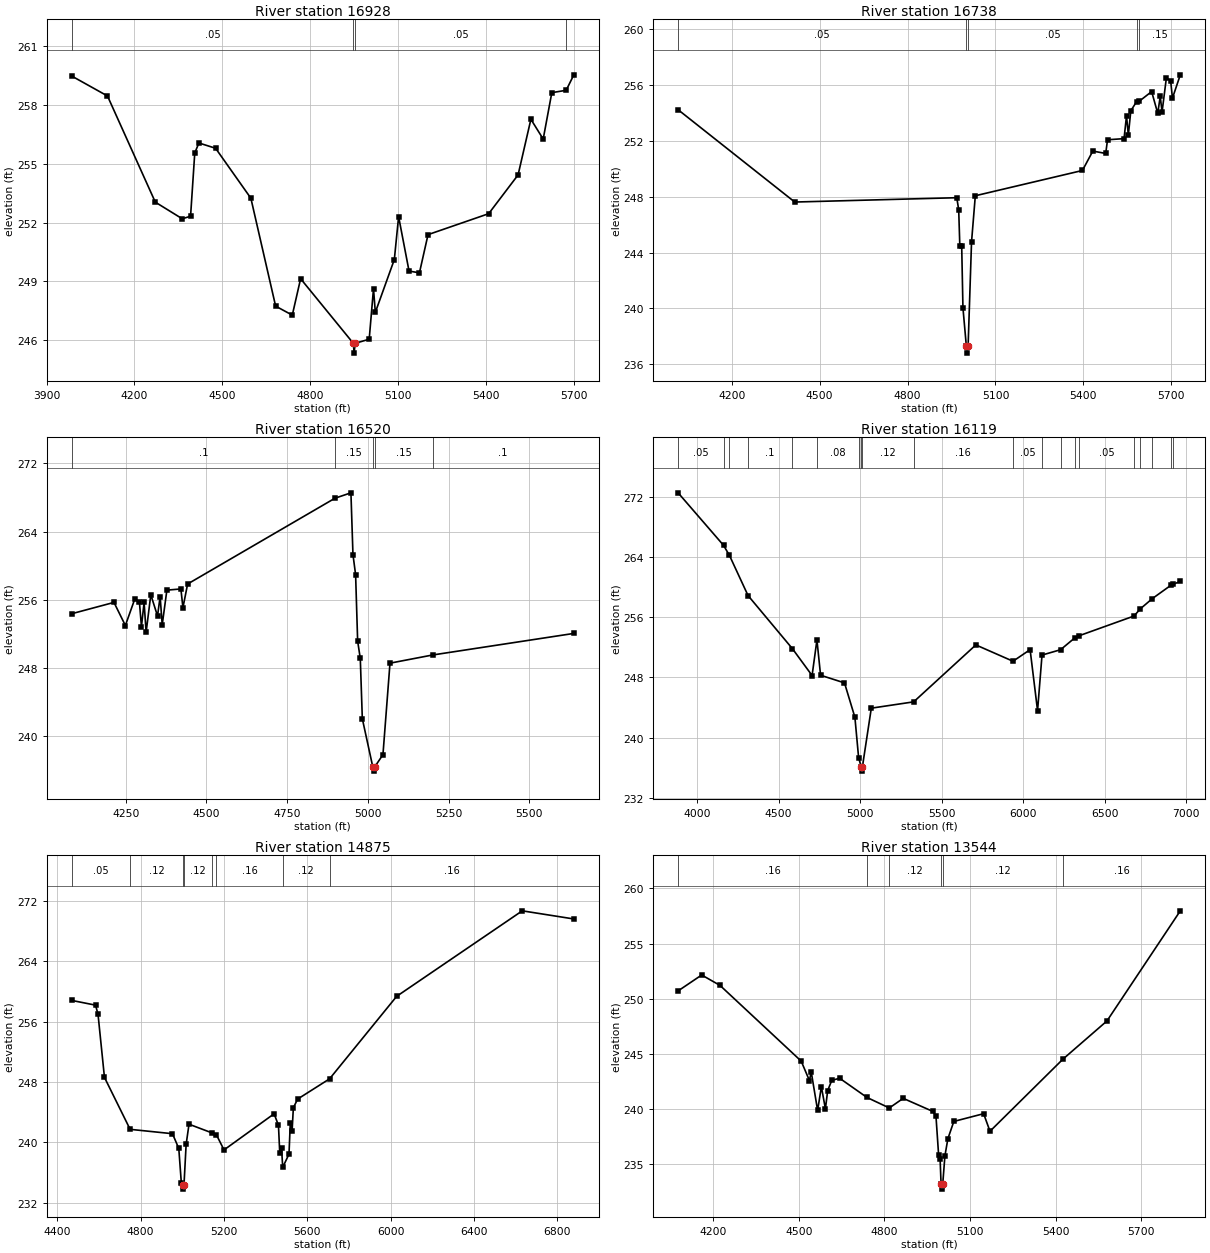
Type RM Length L Ch R = 1 ,16928   ,190,190,190
BEGIN DESCRIPTION:
ALUM CREEK 2 24.1
END DESCRIPTION:
XS GIS Cut Line= 3
      3583128.83     10185931.41      3583767.63     10185208.31
      3584209.56     10184603.28
#Sta/Elev= 30
  3985.5  259.49  4107.8  258.47    4271  253.05    4363   252.2  4391.4  252.33
  4405.7  255.56  4419.9  256.07  4476.8   255.8  4597.2  253.25  4681.7  247.74
  4738.6  247.28    4767  249.14    4947  245.84  4949.7  245.34    4953  245.84
  5001.1  246.05  5015.8  248.63    5022  247.42  5086.9  250.12  5101.5  252.31
  5137.1  249.53  5172.6  249.44  5201.9  251.39  5408.9  252.46  5509.3  254.44
    5553  257.28    5595  256.27  5624.4  258.64  5673.4  258.76  5699.6  259.55
#Mann= 4 ,-1 , 0
  3985.5     .05       0    4947     .03       0    4953     .05       0
  5673.4     .08       0
Bank Sta=4947,4953
XS Rating Curve= 0 ,0
Exp/Cntr=0.3,0.1

Type RM Length L Ch R = 1 ,16738   ,153,153,153
BEGIN DESCRIPTION:
ALUM CREEK 2 24.0
END DESCRIPTION:
XS GIS Cut Line= 3
      3583303.31     10186014.74      3583942.11     10185291.64
      3584384.05      10184686.6
#Sta/Elev= 30
  4016.8  254.23  4414.9  247.62  4967.9  247.93  4974.5  247.07  4978.3   244.5
  4984.7   244.5    4989  240.04  5000.6   237.3  5003.4   236.8  5006.6   237.3
  5018.3  244.76  5031.2  248.07  5396.8  249.88  5432.3  251.27  5476.3   251.1
  5482.5  252.08  5538.9  252.16  5547.3   253.8  5553.5  252.41    5562  254.16
  5581.5   254.8  5591.4  254.85  5633.1  255.53  5653.9  253.97  5662.4  255.19
  5668.6  254.07  5683.3   256.5  5697.9  256.31  5704.1  255.06  5730.9  256.73
#Mann= 5 ,-1 , 0
  4016.8     .05       0  5000.6    .035       0  5006.6     .05       0
  5581.5      .1       0  5591.4     .15       0
Bank Sta=5000.6,5006.6
XS Rating Curve= 0 ,0
Exp/Cntr=0.3,0.1

Type RM Length L Ch R = 1 ,16520   ,466,466,466
BEGIN DESCRIPTION:
ALUM CREEK 2 23.0
END DESCRIPTION:
XS GIS Cut Line= 2
     3583512.839    10186128.298     3584504.592    10184941.232
#Sta/Elev= 30
  4082.4  254.36  4213.5  255.69  4248.8  252.98  4277.8  256.07  4292.3  255.75
  4298.6  252.84  4306.8  255.69  4313.1   252.2  4327.6  256.59  4348.4   254.1
  4356.5  256.38  4362.9  253.06  4377.4  257.13  4420.8  257.27  4427.1  255.07
  4441.6  257.85  4898.2  267.92  4947.5  268.55  4953.8  261.31    4962  258.94
  4968.3  251.15  4976.5  249.11  4982.8  242.04  5015.2  236.39  5017.9  235.89
  5021.2  236.39  5046.7  237.82  5068.5  248.56  5200.6  249.52    5638  252.05
#Mann= 5 ,-1 , 0
  4082.4      .1       0  4898.2     .15       0  5015.2     .07       0
  5021.2     .15       0  5200.6      .1       0
Bank Sta=5015.2,5021.2
XS Rating Curve= 0 ,0
Exp/Cntr=0.3,0.1

Type RM Length L Ch R = 1 ,16119   ,1244,1244,1244
BEGIN DESCRIPTION:
ALUM CREEK 2 22.0
END DESCRIPTION:
XS GIS Cut Line= 3
      3583608.51     10186714.56      3583957.29     10186171.84
      3585233.47     10184096.56
#Sta/Elev= 30
    3883  272.53  4161.7  265.55  4198.2   264.2  4312.1  258.87  4584.3  251.81
    4705  248.24  4734.8  252.97  4757.1  248.28  4903.9  247.26  4967.7  242.69
  4990.5  237.33  5007.3  236.03    5010  235.53  5013.3  236.03  5068.4   243.9
  5328.4  244.74  5709.8  252.31  5937.9  250.14  6042.8  251.68  6088.5  243.57
  6115.9  250.96  6229.6  251.67  6317.2  253.25  6342.3  253.52  6680.2  256.15
  6719.8  257.12  6792.9  258.47  6905.5  260.22  6921.1  260.38  6964.4  260.75
#Mann= 20 ,-1 , 0
    3883     .05       0  4161.7      .1       0  4198.2     .05       0
  4312.1      .1       0  4584.3     .05       0  4734.8     .08       0
  4990.5     .12       0  5007.3     .07       0  5013.3     .12       0
  5328.4     .16       0  5937.9     .05       0  6115.9     .16       0
  6229.6     .05       0  6317.2     .16       0  6342.3     .05       0
  6680.2      .1       0  6719.8     .05       0  6792.9      .1       0
  6905.5     .15       0  6921.1     .05       0
Bank Sta=5007.3,5013.3
XS Rating Curve= 0 ,0
Exp/Cntr=0.3,0.1

Type RM Length L Ch R = 1 ,14875   ,1331,1331,1331
BEGIN DESCRIPTION:
ALUM CREEK 2 21.0
END DESCRIPTION:
XS GIS Cut Line= 3
      3584583.72     10186379.28       3585078.5     10185576.35
      3585920.17     10184375.47
#Sta/Elev= 30
  4469.2  258.84  4583.9  258.21  4595.8  256.98  4626.6  248.63  4749.7  241.74
    4953  241.16  4983.3   239.2  4995.6  234.58  5002.1  234.31  5004.9  233.81
  5008.1  234.31  5018.5  239.74  5032.3  242.42  5141.4  241.28  5164.1     241
  5200.3  239.01  5440.6   243.8  5461.5  242.28  5467.6  238.66  5476.3  239.24
    5482   236.7  5512.1  238.46  5518.2  242.53  5526.9   241.5    5533  244.61
  5553.9  245.76  5706.9  248.44  6028.7  259.38  6631.3  270.72  6878.8  269.64
#Mann= 8 ,-1 , 0
  4469.2     .05       0  4749.7     .12       0  5002.1     .07       0
  5008.1     .12       0  5141.4      .1       0  5164.1     .16       0
    5482     .12       0  5706.9     .16       0
Bank Sta=5002.1,5008.1
XS Rating Curve= 0 ,0
Exp/Cntr=0.3,0.1

Type RM Length L Ch R = 1 ,13544   ,752,752,752
BEGIN DESCRIPTION:
ALUM CREEK 2 19.0
END DESCRIPTION:
XS GIS Cut Line= 3
      3584839.77     10186696.15      3585382.32     10186262.11
      3585692.12      10185241.6
#Sta/Elev= 30
  4076.3  250.71    4159  252.15  4223.1  251.21    4508  244.35  4536.8  242.59
  4543.2  243.37  4565.6  239.88  4578.7  242.03  4592.9  240.03  4600.9  241.69
  4615.3  242.61  4642.8   242.8  4738.7  241.06    4817  240.11  4865.7  240.98
  4970.2  239.79  4980.6  239.38    4990  235.83  4995.2  235.45  4998.5  233.26
  5001.3  232.76  5004.5  233.26    5012  235.77  5022.4  237.32  5043.3  238.89
  5147.8  239.59  5170.1     238    5426  244.53  5580.4  247.99  5837.6  257.96
#Mann= 6 ,-1 , 0
  4076.3     .16       0  4738.7     .05       0    4817     .12       0
  4998.5     .07       0  5004.5     .12       0    5426     .16       0
Bank Sta=4998.5,5004.5
XS Rating Curve= 0 ,0
Exp/Cntr=0.3,0.1

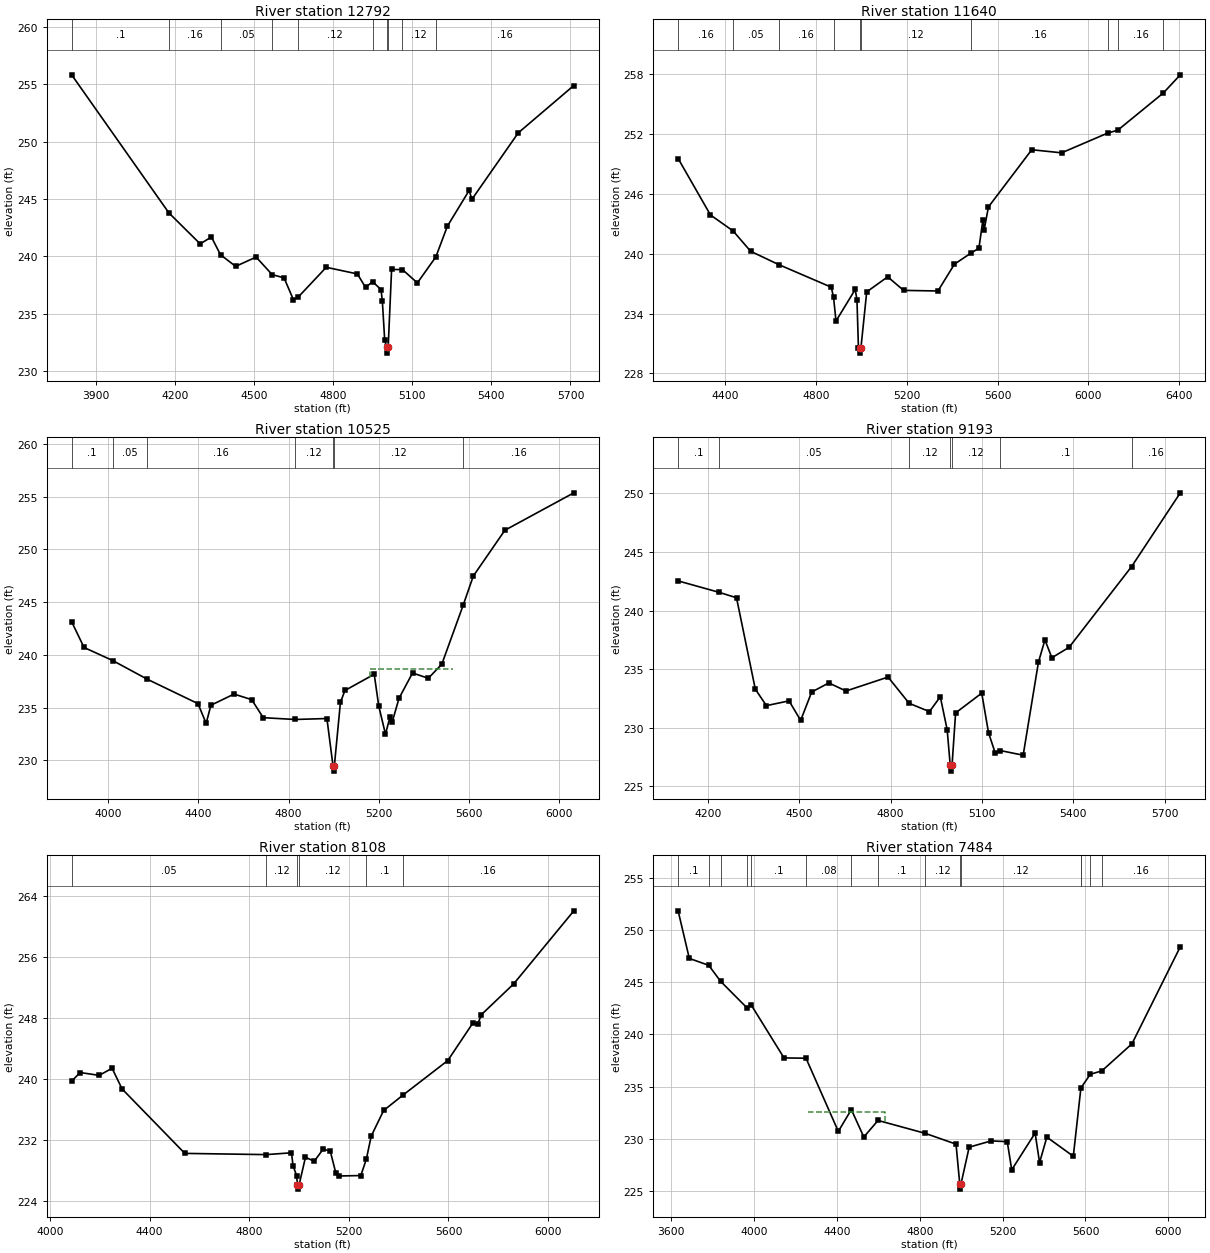
Type RM Length L Ch R = 1 ,12792   ,1152,1152,1152
BEGIN DESCRIPTION:
ALUM CREEK 2 17.0
END DESCRIPTION:
XS GIS Cut Line= 3
      3585242.09     10186941.66      3585913.68     10186244.17
      3586154.88     10185337.67
#Sta/Elev= 30
  3806.6  255.82  4175.7  243.79  4294.5  241.09    4337  241.69  4371.7  240.14
  4429.1  239.13  4506.8  239.94  4567.8  238.41  4612.8  238.13  4648.3  236.23
  4666.1  236.44  4773.1  239.05  4891.3  238.47  4922.3  237.29  4948.7   237.8
  4980.9  237.11  4986.1  236.08  4994.8  232.74  5002.1  232.07  5004.9  231.57
  5008.1  232.07  5021.1  238.86  5062.2  238.85    5119  237.69  5189.2  239.96
  5232.8  242.63  5315.6  245.75  5325.9  244.97  5501.8  250.76  5712.9  254.89
#Mann= 10 ,-1 , 0
  3806.6      .1       0  4175.7     .16       0  4371.7     .05       0
  4567.8     .16       0  4666.1     .12       0  4948.7     .16       0
  5002.1     .07       0  5008.1     .16       0  5062.2     .12       0
  5189.2     .16       0
Bank Sta=5002.1,5008.1
XS Rating Curve= 0 ,0
Exp/Cntr=0.3,0.1

Type RM Length L Ch R = 1 ,11640   ,1115,1115,1115
BEGIN DESCRIPTION:
ALUM CREEK 2 15.0
END DESCRIPTION:
XS GIS Cut Line= 3
      3585592.07     10187091.67      3586472.36     10186359.19
      3586871.03     10185368.04
#Sta/Elev= 30
  4191.9  249.54  4334.5  243.88  4434.2  242.28  4511.6  240.24  4635.9   238.9
    4867  236.64    4877  235.63  4887.8  233.25  4972.5  236.41  4980.2  235.36
  4986.7  230.58  4991.6  230.53  4994.3  230.03  4997.6  230.53  5023.2  236.17
  5115.6  237.68  5185.9  236.32  5337.1  236.26  5409.9  238.95    5482  240.05
  5517.7  240.55  5535.6  243.42    5541  242.42  5559.8  244.69  5750.6  250.42
  5882.3  250.11  6086.4   252.1  6129.9  252.38  6330.5  256.11  6405.4  257.93
#Mann= 10 ,-1 , 0
  4191.9     .16       0  4434.2     .05       0  4635.9     .16       0
    4877     .12       0  4991.6     .07       0  4997.6     .12       0
    5482     .16       0  6086.4      .1       0  6129.9     .16       0
  6330.5      .1       0
Bank Sta=4991.6,4997.6
XS Rating Curve= 0 ,0
Exp/Cntr=0.3,0.1

Type RM Length L Ch R = 1 ,10525   ,1332,1332,1332
BEGIN DESCRIPTION:
ALUM CREEK 2 14.0
END DESCRIPTION:
XS GIS Cut Line= 4
        3585786.     10187282.05      3586548.93     10186785.43
      3586905.76     10186782.94      3587868.25     10186761.27
#Sta/Elev= 30
    3837  243.14    3892   240.7  4019.3  239.46  4171.7   237.7    4398  235.37
  4434.2   233.5  4455.3  235.22    4558  236.28  4636.4  235.75  4687.8  234.04
  4828.8  233.87  4970.5  233.96  4997.5  229.47  5000.3  228.97  5003.5  229.47
  5030.5  235.49  5050.5  236.62  5180.5  238.16  5200.5  235.16  5230.5  232.47
  5250.5  234.11  5260.6  233.64  5290.6  235.88  5350.6  238.28  5420.6  237.78
  5480.6  239.11  5575.8  244.73  5620.6  247.48  5760.7  251.82  6066.9  255.37
#Mann= 7 ,-1 , 0
    3837      .1       0  4019.3     .05       0  4171.7     .16       0
  4828.8     .12       0  4997.5     .07       0  5003.5     .12       0
  5575.8     .16       0
#XS Ineff= 1 ,-1
 5161.93 5530.11  238.62
Permanent Ineff=
       F
Bank Sta=4997.5,5003.5
XS Rating Curve= 0 ,0
Exp/Cntr=0.3,0.1

Type RM Length L Ch R = 1 ,9193    ,1085,1085,1085
BEGIN DESCRIPTION:
ALUM CREEK 2 13.0
END DESCRIPTION:
XS GIS Cut Line= 3
      3586128.82     10187711.77      3586681.87     10187515.19
       3587542.1     10186891.64
#Sta/Elev= 30
  4102.3  242.53  4237.6  241.55  4294.1  241.09  4355.8  233.29  4392.3  231.88
  4466.6  232.29  4504.8  230.62  4540.9  233.04  4597.3  233.82  4653.7  233.13
  4791.8  234.32  4861.1  232.08  4927.8  231.37  4963.4  232.64    4986  229.82
    4996  226.79  4998.7  226.29    5002  226.79  5013.7  231.26  5099.5  232.95
  5121.8  229.57  5143.6  227.85  5159.7  228.05  5235.6  227.65  5285.8   235.6
  5307.1  237.49  5329.9  235.97  5386.4  236.86  5591.9  243.76  5751.7  250.05
#Mann= 7 ,-1 , 0
  4102.3      .1       0  4237.6     .05       0  4861.1     .12       0
    4996     .07       0    5002     .12       0  5159.7      .1       0
  5591.9     .16       0
Bank Sta=4996,5002
XS Rating Curve= 0 ,0
Exp/Cntr=0.3,0.1

Type RM Length L Ch R = 1 ,8108    ,624,624,624
BEGIN DESCRIPTION:
ALUM CREEK 2 11.0
END DESCRIPTION:
XS GIS Cut Line= 3
      3586410.99     10187950.48      3587053.33     10187872.35
      3588142.13     10187041.62
#Sta/Elev= 30
  4086.8   239.7  4120.9  240.83  4197.5  240.46  4249.1  241.39  4289.4  238.68
  4541.2  230.24  4868.1  230.08  4969.6  230.32  4975.8  228.63  4990.4  227.31
  4993.7  226.06  4996.4  225.56  4999.7  226.06  5025.7  229.73  5061.1  229.21
  5097.1  230.82  5125.5  230.51  5147.4   227.7  5160.9  227.28    5248  227.34
  5270.3   229.5  5289.7   232.5  5339.6  235.86  5416.7  237.86  5597.2   242.4
    5697  247.27  5717.8  247.22  5732.4  248.42  5861.2  252.42  6103.4  262.01
#Mann= 6 ,-1 , 0
  4086.8     .05       0  4868.1     .12       0  4993.7     .07       0
  4999.7     .12       0  5270.3      .1       0  5416.7     .16       0
Bank Sta=4993.7,4999.7
XS Rating Curve= 0 ,0
Exp/Cntr=0.3,0.1

Type RM Length L Ch R = 1 ,7484    ,1241,1241,1241
BEGIN DESCRIPTION:
ALUM CREEK 2 10.0
END DESCRIPTION:
XS GIS Cut Line= 3
       3586714.8     10189343.68      3587022.83     10188269.59
      3587992.14     10187391.61
#Sta/Elev= 30
  3632.9  251.84    3687  247.28  3780.8  246.62    3838  245.09  3965.2  242.55
  3987.2  242.78  4144.3  237.75  4250.6  237.72  4406.5  230.71  4469.5   232.8
  4529.7  230.17  4598.3  231.76  4825.2  230.53    4975  229.49    4993  225.68
  4995.7  225.18    4999  225.68  5038.5   229.2  5144.6   229.8  5222.4  229.73
    5244  227.03  5356.9  230.55  5378.5  227.72  5413.6  230.16  5541.4  228.33
    5578  234.87  5623.3  236.18  5679.4  236.51  5824.6   239.1  6058.1   248.4
#Mann= 15 ,-1 , 0
  3632.9      .1       0  3780.8     .08       0    3838      .1       0
  3965.2     .08       0  3987.2      .1       0  4250.6     .08       0
  4469.5     .05       0  4598.3      .1       0  4825.2     .12       0
    4993     .07       0    4999     .12       0    5578     .05       0
    5578     .16       0  5623.3      .1       0  5679.4     .16       0
#XS Ineff= 1 ,-1
 4258.52 4631.82  232.55
Permanent Ineff=
       F
Bank Sta=4993,4999
XS Rating Curve= 0 ,0
Exp/Cntr=0.3,0.1

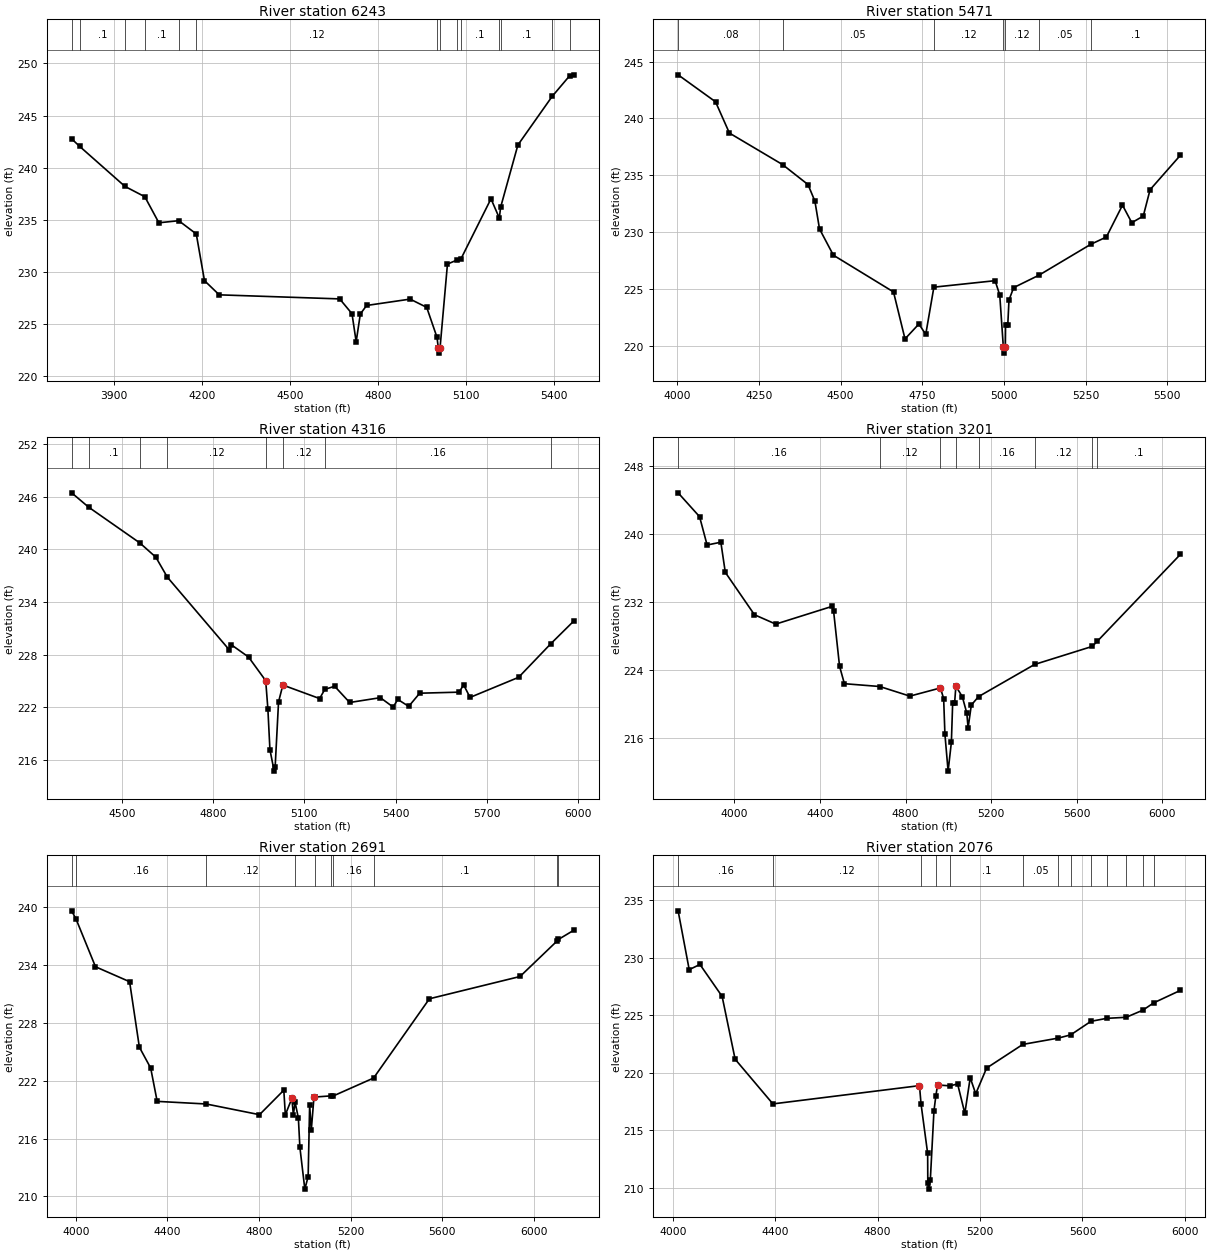
Type RM Length L Ch R = 1 ,6243    ,772,772,772
BEGIN DESCRIPTION:
ALUM CREEK 2 9.0
END DESCRIPTION:
XS GIS Cut Line= 3
      3587142.09     10189191.66      3587856.28      10188566.8
      3588381.42     10188011.28
#Sta/Elev= 30
  3755.8  242.77    3783  242.05  3937.6  238.21  4005.4  237.22  4053.4  234.72
  4121.1  234.92    4181  233.65    4209  229.17  4259.3  227.81  4670.3  227.42
  4712.3     226  4726.5  223.31  4740.7  225.97  4762.1  226.79  4910.6   227.4
  4967.2  226.61  5002.4  223.73  5006.7  222.72  5009.4  222.22  5012.7  222.72
    5038  230.76  5071.5  231.16  5084.6  231.29  5186.5  237.02    5215  235.17
  5219.3   236.2  5278.3  242.18  5395.2  246.84  5454.9  248.82  5469.2  248.91
#Mann= 14 ,-1 , 0
  3755.8     .08       0    3783      .1       0  3937.6     .08       0
  4005.4      .1       0  4121.1     .08       0    4181     .12       0
  5002.4     .07       0  5012.7     .12       0  5071.5     .05       0
  5084.6      .1       0    5215     .05       0  5219.3      .1       0
  5395.2     .16       0  5454.9      .1       0
Bank Sta=5006.7,5012.7
XS Rating Curve= 0 ,0
Exp/Cntr=0.3,0.1

Type RM Length L Ch R = 1 ,5471    ,1155,1155,1155
BEGIN DESCRIPTION:
ALUM CREEK 2 7.0
END DESCRIPTION:
XS GIS Cut Line= 3
      3587647.96     10189569.39      3588342.11     10188841.64
      3588692.09     10188441.66
#Sta/Elev= 30
  4002.8  243.83  4117.3  241.46  4159.8  238.71  4322.4  235.94  4400.4  234.18
  4421.5  232.72  4435.6  230.28  4478.1  227.97  4662.1  224.74  4697.3  220.61
  4739.8  221.92  4760.8  221.01  4785.7  225.16  4973.1  225.73  4987.3  224.47
  4998.4  219.86  5001.2  219.36  5004.4  219.86  5005.1  221.79  5011.8  221.79
  5015.6  224.03  5029.9  225.12  5107.2  226.21  5266.1  228.93  5313.7  229.57
    5363  232.37  5391.5  230.83  5426.6  231.41  5447.5  233.73    5540  236.75
#Mann= 7 ,-1 , 0
  4002.8     .08       0  4322.4     .05       0  4785.7     .12       0
  4998.4     .07       0  5004.4     .12       0  5107.2     .05       0
  5266.1      .1       0
Bank Sta=4998.4,5004.4
XS Rating Curve= 0 ,0
Exp/Cntr=0.3,0.1

Type RM Length L Ch R = 1 ,4316    ,1115,1115,1115
BEGIN DESCRIPTION:
ALUM CREEK 2 6.0
END DESCRIPTION:
XS GIS Cut Line= 3
      3588038.59      10190098.9      3588706.98     10189378.43
      3589075.87     10188822.92
#Sta/Elev= 30
  4335.6  246.46  4391.2  244.83  4559.3  240.75  4612.1  239.12  4649.9  236.84
  4852.5  228.58  4859.9  229.13  4916.6  227.73    4973  225.03  4980.1  221.85
  4986.9  217.16  5000.8  214.71  5004.1  215.21  5015.2  222.61  5029.4  224.53
  5150.1  222.99  5167.3  224.04  5199.5  224.39  5248.8  222.54  5349.6  223.09
  5391.7  222.02  5406.8  222.89  5442.8   222.1  5478.9   223.6  5608.2  223.72
  5623.2  224.55  5644.3  223.12  5803.7  225.41  5909.7  229.25  5985.2  231.84
#Mann= 8 ,-1 , 0
  4335.6     .16       0  4391.2      .1       0  4559.3     .05       0
  4649.9     .12       0    4973     .07       0  5029.4     .12       0
  5167.3     .16       0  5909.7     .05       0
Bank Sta=4973,5029.4
XS Rating Curve= 0 ,0
Exp/Cntr=0.3,0.1

Type RM Length L Ch R = 1 ,3201    ,510,510,510
BEGIN DESCRIPTION:
ALUM CREEK 2 5.0
END DESCRIPTION:
XS GIS Cut Line= 3
      3588292.14     10190791.61      3589197.43     10190077.22
      3589857.12     10189083.34
#Sta/Elev= 30
  3737.5  244.84  3837.7  242.04  3872.9  238.71  3937.1  239.04  3957.9   235.5
  4094.1  230.52  4193.6  229.42  4456.5   231.5  4463.6     231  4491.7  224.47
  4514.3  222.42  4679.4  222.09  4820.2  220.96  4962.9  221.92    4978  220.67
    4984  216.46  4998.8  212.15  5014.1  215.53  5020.1  220.14  5029.1  220.12
  5035.1  222.13  5065.2  220.89  5086.2  218.96  5092.2  217.22  5107.3  219.91
  5140.9   220.9  5402.8  224.68  5672.2   226.8  5695.7   227.4  6083.6   237.6
#Mann= 8 ,-1 , 0
  3737.5     .16       0  4679.4     .12       0  4962.9     .07       0
  5035.1     .12       0  5140.9     .16       0  5402.8     .12       0
  5672.2     .16       0  5695.7      .1       0
Bank Sta=4962.9,5035.1
XS Rating Curve= 0 ,0
Exp/Cntr=0.3,0.1

Type RM Length L Ch R = 1 ,2691    ,615,615,615
BEGIN DESCRIPTION:
ALUM CREEK 2 4.0
END DESCRIPTION:
XS GIS Cut Line= 3
      3588952.51     10191069.61      3589652.52     10190269.59
      3590452.52      10189469.6
#Sta/Elev= 30
  3981.2  239.62  4000.9  238.74  4085.4  233.82  4234.4  232.27  4277.1  225.48
  4326.5  223.32  4354.9  219.86  4568.9  219.59    4802  218.48  4908.3  221.02
  4914.9  218.47  4943.4  220.16    4950  218.49  4957.6  219.76  4971.9  218.13
  4978.5   215.1  5000.1  210.76  5014.6  212.06  5021.2  219.52  5028.2  216.85
  5040.1  220.31  5044.2  220.31    5114  220.43    5125  220.43  5300.6  222.28
  5544.5   230.5  5940.5  232.81    6101  236.46    6108  236.65  6175.6  237.61
#Mann= 10 ,-1 , 0
  3981.2      .1       0  4000.9     .16       0  4568.9     .12       0
  4957.6     .07       0  5044.2     .12       0    5114      .1       0
    5125     .16       0  5300.6      .1       0    6101     .16       0
    6108      .1       0
Bank Sta=4943.4,5040.1
XS Rating Curve= 0 ,0
Exp/Cntr=0.3,0.1

Type RM Length L Ch R = 1 ,2076    ,1861,1861,1861
BEGIN DESCRIPTION:
ALUM CREEK 2 3.0
END DESCRIPTION:
XS GIS Cut Line= 3
       3589442.1     10191391.64      3589992.11     10190591.64
      3590712.19     10189912.28
#Sta/Elev= 30
  4021.1   234.1  4064.4  228.98  4106.3  229.43  4192.9  226.65  4243.7  221.18
  4391.2  217.29  4963.5  218.88  4969.6  217.28  4995.4  212.98    4996  210.37
  4998.8  209.87  5005.9   210.7    5020  216.68  5027.3  217.97  5034.2  218.94
    5083  218.86  5112.3  219.03  5140.6  216.47  5161.6  219.57  5183.1  218.17
  5225.6  220.41    5367  222.47  5505.6  223.02  5553.9   223.3    5633  224.48
  5694.8  224.74  5770.4  224.83  5835.7  225.45  5878.2  226.09  5981.9  227.17
#Mann= 13 ,-1 , 0
  4021.1     .16       0  4391.2     .12       0  4969.6     .07       0
  5027.3     .12       0    5083      .1       0    5367     .05       0
  5505.6      .1       0  5553.9     .05       0    5633      .1       0
  5694.8     .05       0  5770.4      .1       0  5835.7     .16       0
  5878.2      .1       0
Bank Sta=4963.5,5034.2
XS Rating Curve= 0 ,0
Exp/Cntr=0.3,0.1

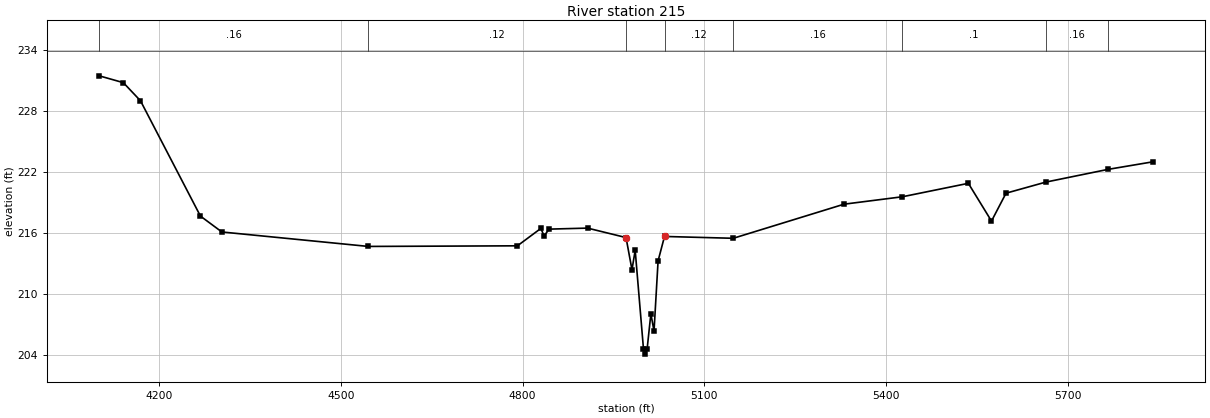
Type RM Length L Ch R = 1 ,215     ,0,0,0
BEGIN DESCRIPTION:
ALUM CREEK 2 1.0
END DESCRIPTION:
XS GIS Cut Line= 3
      3589935.31     10191761.21      3590438.75     10191266.45
      3590777.21     10190290.11
#Sta/Elev= 30
    4101  231.42  4140.8  230.75  4169.1  228.97  4268.1  217.64  4303.5  216.08
  4545.3  214.66  4791.4  214.72  4830.1  216.43  4835.4  215.69  4843.7  216.36
  4907.2  216.46  4970.7  215.53  4980.5  212.37  4985.8  214.28  4999.5  204.58
  5002.2  204.08  5005.5  204.58  5011.7  208.05  5016.9  206.34  5023.6  213.24
  5034.2  215.64  5147.7  215.46  5330.6  218.81    5427  219.54  5535.8  220.86
    5574  217.15    5598  219.89  5663.7  220.98  5766.4  222.23  5840.2  222.97
#Mann= 8 ,-1 , 0
    4101     .16       0  4545.3     .12       0  4970.7     .07       0
  5034.2     .12       0  5147.7     .16       0    5427      .1       0
  5663.7     .16       0  5766.4      .1       0
Bank Sta=4970.7,5034.2
XS Rating Curve= 0 ,0
Exp/Cntr=0.3,0.1
Stream Node=ALUM CREEK 2    ,Reach-1         , 0 , 0 ,Upstream end
Stream Node=ALUM CREEK 2    ,Reach-1         , 0 , 1 ,Downstream end

Chan Stop Cuts=-1
Use User Specified Reach Order=0
Composite Channel Slope=5