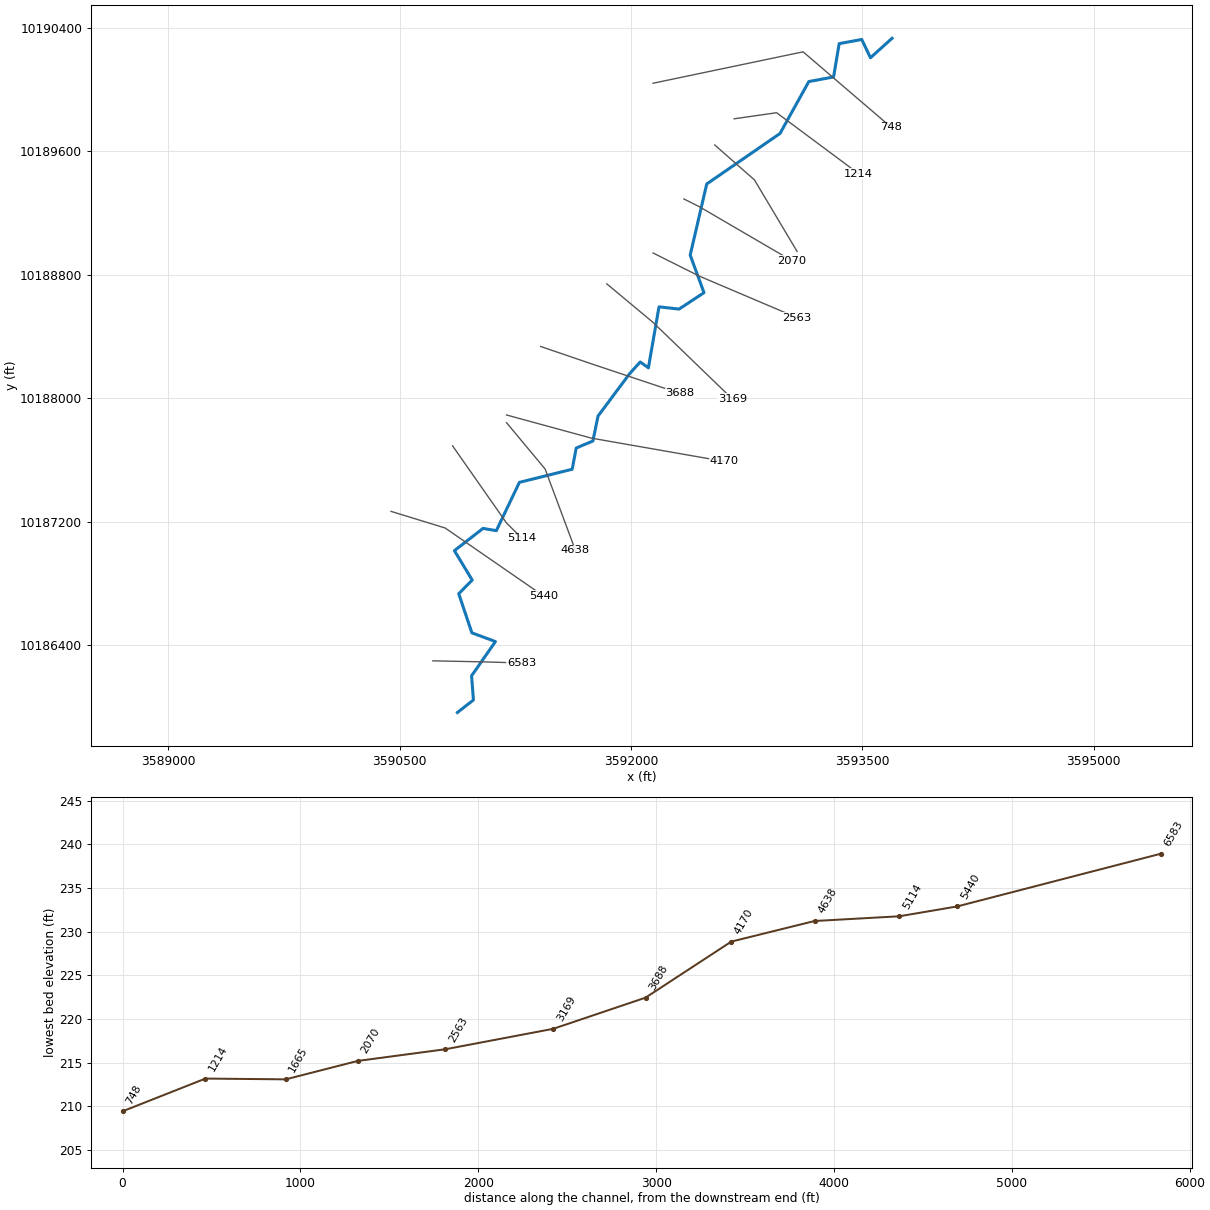
--- ALUM CREEK TRIBUTARY 2.prj (project) ---

Proj Title=ALUM CREEK TRIBUTARY 2 Base Level Engineering
Current Plan=p01
Default Exp/Contr=0.3,0.1
English Units
Geom File=g01
Flow File=f01
Plan File=p01
BEGIN DESCRIPTION:
ALUM CREEK TRIBUTARY 2
END DESCRIPTION:

--- ALUM CREEK TRIBUTARY 2.p01 (plan) ---

Plan Title=Multiple Run
Short Identifier=Multiple
Geom File=g01
Flow File=f01
Subcritical Flow
K Sum by GR= 0
Std Step Tol= 0.01
Critical Tol= 0.01
Num of Std Step Trials= 20
Max Error Tol= 0.3
Flow Tol Ratio= 0.001
Split Flow NTrial= 30
Split Flow Tol= 0.02
Split Flow Ratio= 0.02
Log Output Level= 0
Friction Slope Method= 1
Unsteady Friction Slope Method= 2
Unsteady Bridges Friction Slope Method= 1
Parabolic Critical Depth
Global Vel Dist=  1 , 1 , 1
Global Log Level= 0
CheckData=True
Encroach Param= -1, 0, 0, 0
BEGIN DESCRIPTION:
Multiple Run
END DESCRIPTION:

--- ALUM CREEK TRIBUTARY 2.f01 (steady flow) ---

Flow Title=Multiple
Number of Profiles=7
Profile Names=10-year,25-year,50-year,1pct_min,100-year,1pct_plu,500-year
River Rch & RM= ALUM CREEK TRIBU,Reach-1,6583
     457     603     719     629     851    1151    1192
Boundary for River Rch & Prof#=ALUM CREEK TRIBU,Reach-1,1
Up Type=0
Dn Type=3
Dn Slope=0.005
Boundary for River Rch & Prof#=ALUM CREEK TRIBU,Reach-1,2
Up Type=0
Dn Type=3
Dn Slope=0.005
Boundary for River Rch & Prof#=ALUM CREEK TRIBU,Reach-1,3
Up Type=0
Dn Type=3
Dn Slope=0.005
Boundary for River Rch & Prof#=ALUM CREEK TRIBU,Reach-1,4
Up Type=0
Dn Type=3
Dn Slope=0.005
Boundary for River Rch & Prof#=ALUM CREEK TRIBU,Reach-1,5
Up Type=0
Dn Type=3
Dn Slope=0.005
Boundary for River Rch & Prof#=ALUM CREEK TRIBU,Reach-1,6
Up Type=0
Dn Type=3
Dn Slope=0.005
Boundary for River Rch & Prof#=ALUM CREEK TRIBU,Reach-1,7
Up Type=0
Dn Type=3
Dn Slope=0.005

--- ALUM CREEK TRIBUTARY 2.g01 (geometry) ---

Geom Title=Existing Conditions

River Reach=ALUM CREEK TRIBU,Reach-1
Reach XY= 30
      3590873.48     10185963.30      3590977.29     10186044.50
      3590965.41     10186201.40      3591120.16     10186423.15
      3590967.34     10186479.80      3590882.18     10186733.44
      3590969.57     10186821.74      3590853.93     10187012.29
      3591039.77     10187156.63      3591125.79     10187141.71
      3591275.46     10187455.05      3591617.78     10187539.95
      3591643.83     10187677.45      3591752.11     10187722.96
      3591785.40     10187884.66      3591989.94     10188159.24
      3592058.89     10188235.30      3592111.85     10188197.05
      3592180.71     10188592.45      3592311.08     10188578.03
      3592472.41     10188684.22      3592383.01     10188928.11
      3592490.14     10189388.62      3592965.41     10189716.09
      3593152.27     10190052.58      3593312.59     10190082.25
      3593349.18     10190298.34      3593495.43     10190325.42
      3593551.90     10190206.76      3593692.11     10190332.96

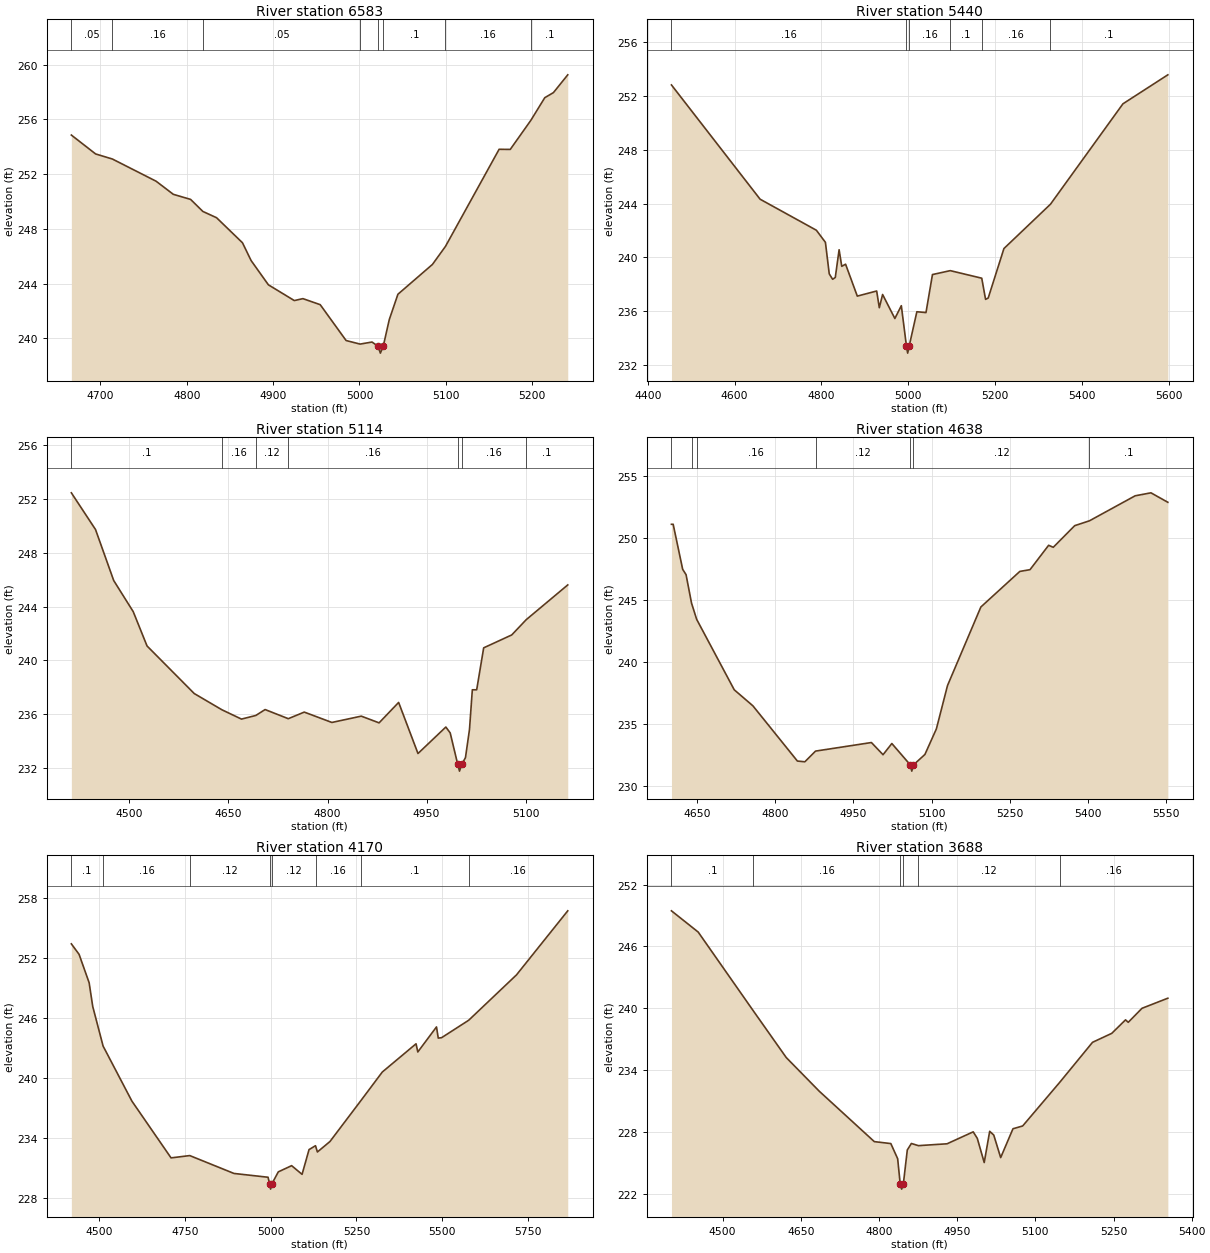
Type RM Length L Ch R = 1,6583,1143,1143,1143
BEGIN DESCRIPTION:
ALUM CREEK TRIBUTARY 2 12.0
END DESCRIPTION:
XS GIS Cut Line= 3
      3590713.99     10186298.20      3591042.11     10186291.64
      3591288.71     10186284.36
#Sta/Elev= 30
  4666.3  254.86  4694.4  253.48  4713.8  253.11  4764.4  251.49  4784.4  250.53
  4804.4  250.16  4818.6  249.28  4834.5  248.82  4864.5  246.99  4874.5  245.69
  4894.5  243.92  4924.5  242.77  4934.5  242.91  4954.5  242.47  4984.5  239.85
  5000.7  239.59  5014.5  239.74  5021.5  239.43  5024.2  238.93  5027.5  239.43
  5034.5  241.38  5044.5  243.23  5084.5  245.41  5099.6  246.73  5161.7  253.82
  5174.6  253.81  5198.4  255.93  5214.6  257.59  5224.6  257.96  5241.2  259.26
#Mann=8,-1,0
  4666.3    0.05       0  4713.8    0.16       0  4818.6    0.05       0
  5000.7     0.1       0  5021.5    0.03       0  5027.5     0.1       0
  5099.6    0.16       0  5198.4     0.1       0
Bank Sta=5021.5,5027.5
Exp/Cntr=0.3,0.1

Type RM Length L Ch R = 1,5440,326,326,326
BEGIN DESCRIPTION:
ALUM CREEK TRIBUTARY 2 11.0
END DESCRIPTION:
XS GIS Cut Line= 3
      3590443.11     10187266.96      3590793.84     10187159.31
      3591432.75     10186718.32
#Sta/Elev= 30
  4454.5  252.80  4658.7  244.32  4788.2  242.02  4809.1  241.12  4817.9  238.78
  4825.7  238.38  4831.8  238.51  4840.6  240.57  4846.7  239.34  4855.5  239.50
  4882.5  237.13  4927.1  237.51  4933.2  236.27  4940.8  237.25  4969.0  235.47
  4983.9  236.42  4995.8  233.40  4998.5  232.90  5001.8  233.40  5019.7  235.97
  5040.7  235.91  5055.6  238.73  5096.6  239.02  5169.1  238.46  5177.9  236.89
  5184.0  236.99  5220.2  240.66  5327.4  243.95  5494.3  251.40  5597.7  253.55
#Mann=6,-1,0
  4454.5    0.16       0  4995.8    0.07       0  5001.8    0.16       0
  5096.6     0.1       0  5169.1    0.16       0  5327.4     0.1       0
Bank Sta=4995.8,5001.8
Exp/Cntr=0.3,0.1

Type RM Length L Ch R = 1,5114,476,476,476
BEGIN DESCRIPTION:
ALUM CREEK TRIBUTARY 2 10.0
END DESCRIPTION:
XS GIS Cut Line= 3
      3590842.12     10187691.62      3591192.11     10187191.64
      3591292.09     10187091.66
#Sta/Elev= 30
  4412.1  252.47  4448.7  249.74  4476.2  245.95  4505.8  243.63  4526.7  241.08
  4598.2  237.54  4640.2  236.33  4669.7  235.64  4691.4  235.91  4705.5  236.35
  4740.6  235.67  4764.8  236.16  4806.6  235.39  4851.1  235.86  4878.1  235.36
  4907.7  236.88  4937.0  233.08  4979.2  235.05  4985.8  234.61  4997.2  232.27
  4999.9  231.77  5003.2  232.27  5008.9  232.77  5015.0  234.87  5019.3  237.82
  5025.9  237.82  5036.5  240.94  5079.0  241.90  5100.8  243.03  5163.8  245.62
#Mann=7,-1,0
  4412.1     0.1       0  4640.2    0.16       0  4691.4    0.12       0
  4740.6    0.16       0  4997.2    0.07       0  5003.2    0.16       0
  5100.8     0.1       0
Bank Sta=4997.2,5003.2
Exp/Cntr=0.3,0.1

Type RM Length L Ch R = 1,4638,468,468,468
BEGIN DESCRIPTION:
ALUM CREEK TRIBUTARY 2 9.0
END DESCRIPTION:
XS GIS Cut Line= 3
      3591192.08     10187841.67      3591442.11     10187541.64
      3591638.24     10187015.78
#Sta/Elev= 30
  4601.1  251.08  4604.4  251.08  4622.6  247.46  4629.1  247.03  4639.6  244.74
  4649.4  243.44  4721.5  237.77  4757.3  236.48  4842.6  232.04  4856.9  231.98
  4877.4  232.84  4984.5  233.53  5006.8  232.55  5023.7  233.45  5059.1  231.73
  5061.9  231.23  5065.1  231.73  5087.1  232.57  5109.1  234.63  5130.4  238.11
  5194.4  244.43  5269.1  247.29  5288.6  247.43  5324.3  249.39  5333.2  249.23
  5374.3  250.97  5402.6  251.36  5490.2  253.37  5520.5  253.61  5552.9  252.85
#Mann=7,-1,0
  4601.1    0.16       0  4639.6     0.1       0  4649.4    0.16       0
  4877.4    0.12       0  5059.1    0.07       0  5065.1    0.12       0
  5402.6     0.1       0
Bank Sta=5059.1,5065.1
Exp/Cntr=0.3,0.1

Type RM Length L Ch R = 1,4170,482,482,482
BEGIN DESCRIPTION:
ALUM CREEK TRIBUTARY 2 8.0
END DESCRIPTION:
XS GIS Cut Line= 3
      3591192.09     10187891.65      3591742.11     10187741.64
      3592603.91     10187590.86
#Sta/Elev= 30
  4420.0  253.44  4442.5  252.39  4471.8  249.54  4482.2  247.17  4512.4  243.20
  4596.2  237.69  4710.2  232.00  4764.7  232.23  4893.4  230.44  4992.6  230.06
  4997.3  229.37  5000.0  228.87  5003.3  229.37  5022.4  230.60  5061.2  231.22
  5091.6  230.35  5111.9  232.83  5130.7  233.22  5136.2  232.59  5172.8  233.64
  5263.1  237.75  5325.1  240.60  5423.4  243.43  5428.5  242.61  5482.9  245.12
  5488.0  244.00  5497.7  244.04  5576.7  245.79  5715.7  250.33  5865.0  256.75
#Mann=8,-1,0
  4420.0     0.1       0  4512.4    0.16       0  4764.7    0.12       0
  4997.3    0.07       0  5003.3    0.12       0  5130.7    0.16       0
  5263.1     0.1       0  5576.7    0.16       0
Bank Sta=4997.3,5003.3
Exp/Cntr=0.3,0.1

Type RM Length L Ch R = 1,3688,519,519,519
BEGIN DESCRIPTION:
ALUM CREEK TRIBUTARY 2 7.0
END DESCRIPTION:
XS GIS Cut Line= 3
      3591413.59     10188335.54      3591756.81     10188218.37
      3592316.43     10188031.70
#Sta/Elev= 30
  4401.7  249.46  4453.0  247.40  4558.7  239.76  4622.0  235.22  4685.4  231.95
  4791.0  227.06  4822.7  226.87  4835.8  225.40  4840.7  222.95  4843.5  222.45
  4846.7  222.95  4854.3  226.25  4862.1  226.88  4875.6  226.67  4930.6  226.85
  4980.8  228.01  4988.6  227.38  5001.9  225.03  5012.4  228.06  5020.2  227.70
  5033.5  225.51  5057.1  228.31  5075.7  228.58  5146.4  232.79  5209.8  236.70
  5246.7  237.57  5273.1  238.88  5278.3  238.64  5304.7  240.00  5354.3  240.98
#Mann=6,-1,0
  4401.7     0.1       0  4558.7    0.16       0  4840.7    0.07       0
  4846.7    0.16       0  4875.6    0.12       0  5146.4    0.16       0
Bank Sta=4840.7,4846.7
Exp/Cntr=0.3,0.1

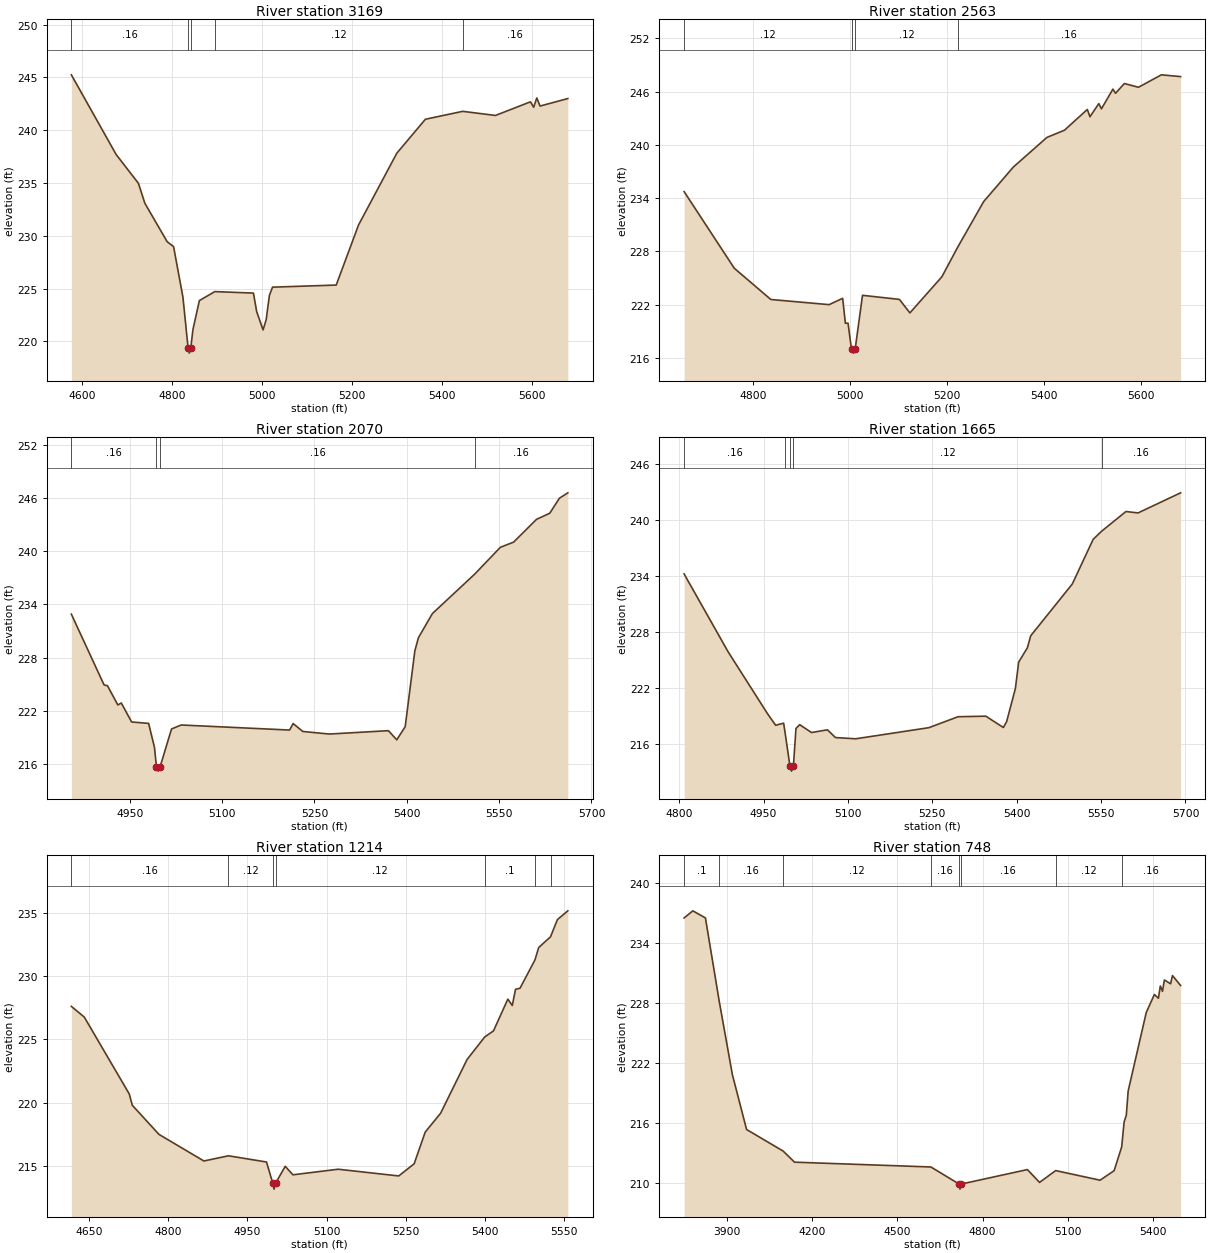
Type RM Length L Ch R = 1,3169,606,606,606
BEGIN DESCRIPTION:
ALUM CREEK TRIBUTARY 2 6.0
END DESCRIPTION:
XS GIS Cut Line= 3
      3591842.13     10188741.62      3592142.11     10188491.64
      3592654.94     10187996.99
#Sta/Elev= 30
  4575.8  245.25  4675.3  237.70  4724.8  234.97  4739.1  233.08  4788.6  229.44
  4802.9  228.97  4823.7  224.18  4835.1  219.38  4837.8  218.88  4841.1  219.38
  4845.9  221.11  4860.2  223.86  4894.6  224.71  4980.3  224.57  4987.5  222.82
  5001.7  221.08  5008.6  222.04  5015.8  224.36  5022.7  225.13  5164.2  225.33
  5213.9  231.03  5298.8  237.82  5362.3  241.04  5445.3  241.79  5518.0  241.40
  5595.7  242.69  5602.9  242.18  5609.8  243.06  5617.0  242.29  5678.8  243.00
#Mann=5,-1,0
  4575.8    0.16       0  4835.1    0.07       0  4841.1    0.16       0
  4894.6    0.12       0  5445.3    0.16       0
Bank Sta=4835.1,4841.1
Exp/Cntr=0.3,0.1

Type RM Length L Ch R = 1,2563,493,493,493
BEGIN DESCRIPTION:
ALUM CREEK TRIBUTARY 2 5.0
END DESCRIPTION:
XS GIS Cut Line= 3
      3592142.07     10188941.66      3592442.11     10188791.64
      3593075.95     10188522.16
#Sta/Elev= 30
  4657.0  234.73  4760.5  226.10  4835.9  222.58  4956.1  222.00  4984.1  222.71
  4989.7  219.91  4995.2  219.91  5001.6  217.26  5004.0  217.04  5006.7  216.54
  5010.0  217.04  5025.0  223.05  5101.1  222.59  5122.8  221.07  5188.8  225.14
  5221.4  228.47  5275.0  233.61  5336.1  237.49  5405.4  240.83  5441.6  241.64
  5488.8  243.98  5494.3  243.16  5512.5  244.64  5517.9  244.05  5541.6  246.27
  5547.0  245.80  5565.2  246.90  5594.3  246.48  5641.6  247.88  5681.2  247.68
#Mann=4,-1,0
  4657.0    0.12       0  5004.0    0.07       0  5010.0    0.12       0
  5221.4    0.16       0
Bank Sta=5004,5010
Exp/Cntr=0.3,0.1

Type RM Length L Ch R = 1,2070,405,405,405
BEGIN DESCRIPTION:
ALUM CREEK TRIBUTARY 2 4.0
END DESCRIPTION:
XS GIS Cut Line= 3
      3592342.07     10189291.66      3592442.11     10189241.64
      3593042.13     10188891.63
#Sta/Elev= 30
  4855.1  232.89  4908.2  224.92  4913.8  224.82  4930.6  222.66  4936.2  222.88
  4953.0  220.74  4980.6  220.58  4990.1  217.88  4993.3  215.70  4996.1  215.20
  4999.3  215.70  5017.8  219.95  5033.5  220.40  5209.6  219.83  5215.4  220.56
  5231.1  219.67  5274.1  219.38  5370.1  219.76  5383.7  218.73  5397.4  220.21
  5413.1  228.77  5418.9  230.24  5441.6  232.96  5510.5  237.42  5552.0  240.43
  5573.5  241.01  5610.7  243.58  5632.2  244.27  5647.9  245.96  5661.6  246.57
#Mann=4,-1,0
  4855.1    0.16       0  4993.3    0.07       0  4999.3    0.16       0
  5510.5    0.16       0
Bank Sta=4993.3,4999.3
Exp/Cntr=0.3,0.1

Type RM Length L Ch R = 1,1665,451,451,451
BEGIN DESCRIPTION:
ALUM CREEK TRIBUTARY 2 3.0
END DESCRIPTION:
XS GIS Cut Line= 3
      3592542.11     10189641.64      3592799.54     10189415.29
      3593075.96     10188951.85
#Sta/Elev= 30
  4808.9  234.19  4887.2  225.85  4957.4  219.21  4971.6  218.00  4985.8  218.22
  4988.0  217.35  4997.1  213.59  4999.8  213.09  5003.1  213.59  5007.7  217.65
  5014.3  218.06  5035.3  217.22  5063.7  217.51  5077.9  216.68  5113.9  216.55
  5243.9  217.74  5295.7  218.91  5345.1  218.97  5376.3  217.76  5382.1  218.38
  5397.7  221.93  5403.5  224.75  5419.1  226.30  5424.9  227.57  5498.9  233.12
  5535.9  237.89  5550.9  238.76  5594.2  240.87  5615.7  240.72  5691.3  242.87
#Mann=5,-1,0
  4808.9    0.16       0  4988.0    0.12       0  4997.1    0.07       0
  5003.1    0.12       0  5550.9    0.16       0
Bank Sta=4997.1,5003.1
Exp/Cntr=0.3,0.1

Type RM Length L Ch R = 1,1214,466,466,466
BEGIN DESCRIPTION:
ALUM CREEK TRIBUTARY 2 2.0
END DESCRIPTION:
XS GIS Cut Line= 3
      3592667.99     10189811.22      3592943.41     10189850.61
      3593474.39     10189455.97
#Sta/Elev= 30
  4616.8  227.60  4641.2  226.76  4726.4  220.69  4732.1  219.80  4782.6  217.50
  4867.7  215.40  4914.1  215.81  4986.2  215.32  4997.8  213.68  5000.5  213.18
  5003.8  213.68  5021.6  214.98  5036.2  214.31  5121.8  214.75  5236.5  214.22
  5265.7  215.18  5286.6  217.68  5315.8  219.17  5365.9  223.41  5399.1  225.18
  5415.9  225.67  5443.0  228.17  5451.4  227.67  5457.6  228.95  5466.0  229.03
  5494.3  231.26  5501.4  232.24  5523.8  233.09  5536.9  234.45  5556.6  235.14
#Mann=7,-1,0
  4616.8    0.16       0  4914.1    0.12       0  4997.8    0.07       0
  5003.8    0.12       0  5399.1     0.1       0  5494.3    0.16       0
  5523.8     0.1       0
Bank Sta=4997.8,5003.8
Exp/Cntr=0.3,0.1

Type RM Length L Ch R = 1,748,0,0,0
BEGIN DESCRIPTION:
ALUM CREEK TRIBUTARY 2 1.0
END DESCRIPTION:
XS GIS Cut Line= 3
      3592142.06     10190041.63      3593115.02     10190245.25
      3593686.41     10189756.10
#Sta/Elev= 30
  3750.2  236.49  3780.9  237.20  3825.2  236.49  3873.8  228.16  3920.0  220.85
  3969.9  215.38  4098.4  213.23  4138.5  212.12  4618.2  211.64  4717.8  209.93
  4720.6  209.43  4723.8  209.93  4957.5  211.38  5000.3  210.10  5057.1  211.28
  5213.2  210.32  5262.6  211.27  5289.2  213.64  5297.8  216.13  5305.5  216.81
  5312.0  219.22  5375.7  227.06  5404.2  228.85  5418.5  228.48  5425.1  229.70
  5432.8  229.17  5439.4  230.30  5461.3  229.92  5467.9  230.74  5496.4  229.75
#Mann=8,-1,0
  3750.2     0.1       0  3873.8    0.16       0  4098.4    0.12       0
  4618.2    0.16       0  4717.8    0.07       0  4723.8    0.16       0
  5057.1    0.12       0  5289.2    0.16       0
Bank Sta=4717.8,4723.8
Exp/Cntr=0.3,0.1

Chan Stop Cuts=-1