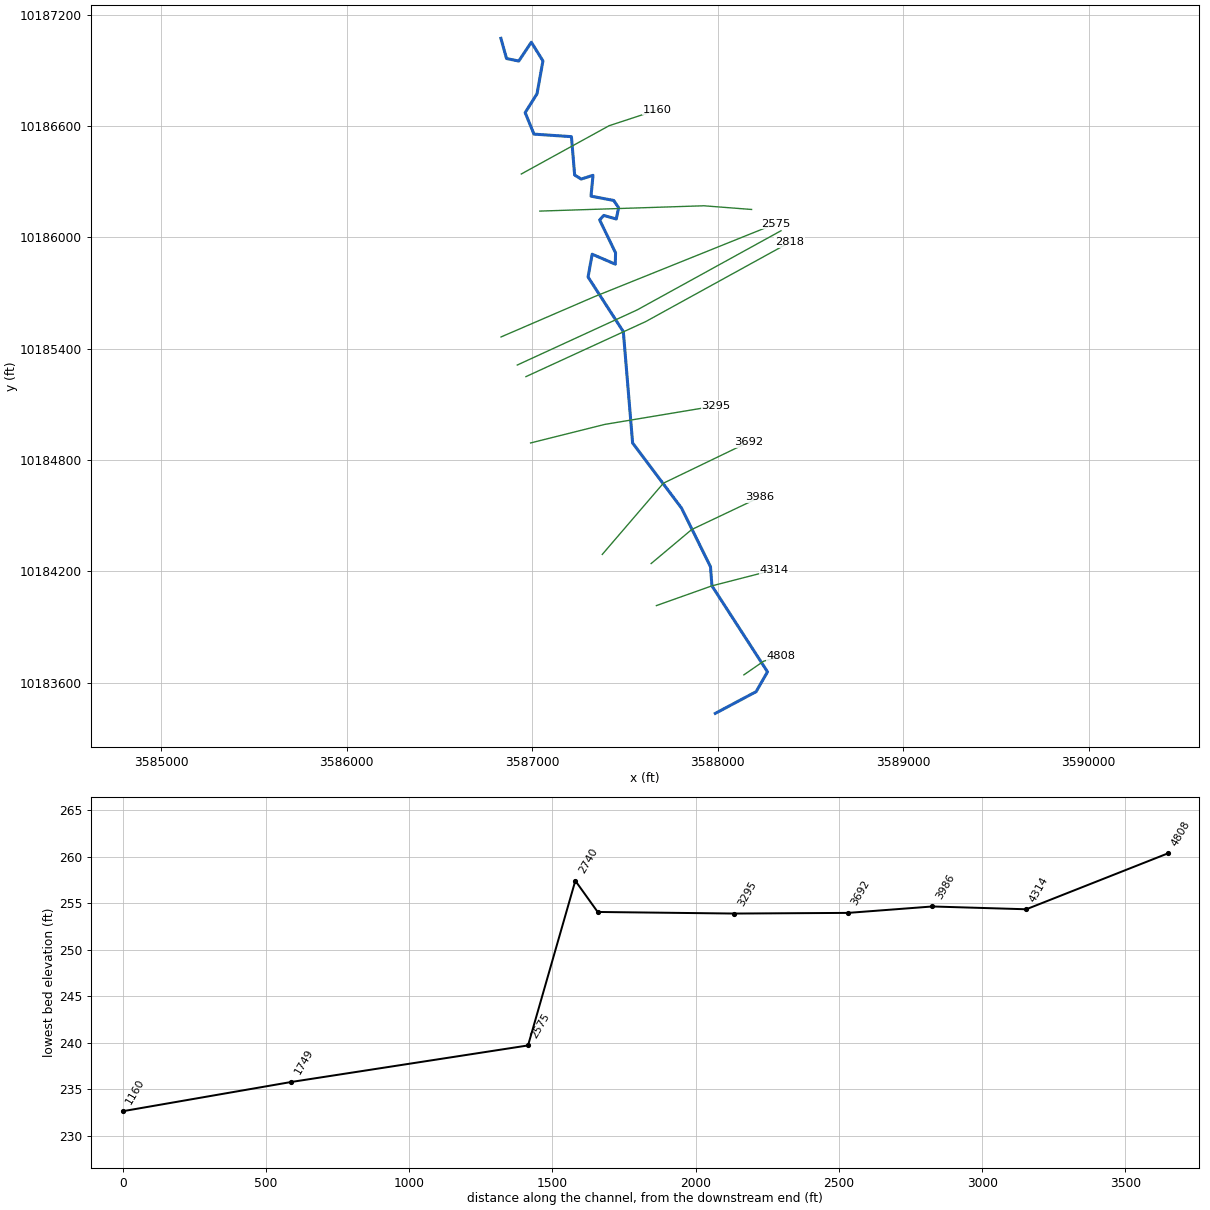
--- ALUM CREEK TRIBUTARY 4.prj (project) ---

Proj Title=ALUM CREEK TRIBUTARY 4 Base Level Engineering
Current Plan=p01
Default Exp/Contr=0.3,0.1
English Units
Geom File=g01
Flow File=f01
Plan File=p01
Y Axis Title=Elevation
X Axis Title(PF)=Main Channel Distance
X Axis Title(XS)=Station
BEGIN DESCRIPTION:
ALUM CREEK TRIBUTARY 4
END DESCRIPTION:
DSS Export Rating Curves= 0
DSS Export Rating Curve Sorted= 0
DSS Export Volume Flow Curves= 0
DXF OffsetX= 0
DXF OffsetY= 0
DXF ScaleX= 1
DXF ScaleY= 10

--- ALUM CREEK TRIBUTARY 4.p01 (plan) ---

Plan Title=Multiple Run
Short Identifier=Multiple
Geom File=g01
Flow File=f01
Subcritical Flow
K Sum by GR= 0
Std Step Tol= 0.01
Critical Tol= 0.01
Num of Std Step Trials= 20
Max Error Tol= 0.3
Flow Tol Ratio= 0.001
Split Flow NTrial= 30
Split Flow Tol= 0.02
Split Flow Ratio= 0.02
Log Output Level= 0
Friction Slope Method= 1
Unsteady Friction Slope Method= 2
Unsteady Bridges Friction Slope Method= 1
Parabolic Critical Depth
Global Vel Dist=  1 , 1 , 1
Global Log Level= 0
CheckData=True
Encroach Param= -1, 0, 0, 0
BEGIN DESCRIPTION:
Multiple Run
END DESCRIPTION:

--- ALUM CREEK TRIBUTARY 4.f01 (steady flow) ---

Flow Title=Multiple
Program Version=4.10
Number of Profiles= 7
Profile Names=10-year,25-year,50-year,1pct_min,100-year,1pct_plu,500-year
River Rch & RM=ALUM CREEK TRIBU,Reach-1         ,4808
     264     339     397     343     463     627     630
Boundary for River Rch & Prof#=ALUM CREEK TRIBU,Reach-1         , 1
Up Type= 0
Dn Type= 3
Dn Slope=0.009
Boundary for River Rch & Prof#=ALUM CREEK TRIBU,Reach-1         , 2
Up Type= 0
Dn Type= 3
Dn Slope=0.009
Boundary for River Rch & Prof#=ALUM CREEK TRIBU,Reach-1         , 3
Up Type= 0
Dn Type= 3
Dn Slope=0.009
Boundary for River Rch & Prof#=ALUM CREEK TRIBU,Reach-1         , 4
Up Type= 0
Dn Type= 3
Dn Slope=0.009
Boundary for River Rch & Prof#=ALUM CREEK TRIBU,Reach-1         , 5
Up Type= 0
Dn Type= 3
Dn Slope=0.009
Boundary for River Rch & Prof#=ALUM CREEK TRIBU,Reach-1         , 6
Up Type= 0
Dn Type= 3
Dn Slope=0.009
Boundary for River Rch & Prof#=ALUM CREEK TRIBU,Reach-1         , 7
Up Type= 0
Dn Type= 3
Dn Slope=0.009
DSS Import GetInterval= 0
DSS Import GetPeak= 0
DSS Import FillOption= 0

--- ALUM CREEK TRIBUTARY 4.g01 (geometry) ---

Geom Title=Existing Conditions
Program Version=4.10

River Reach=ALUM CREEK TRIBU,Reach-1
Reach XY= 30
      3587988.03     10183433.88      3588208.08     10183551.07
      3588269.28     10183657.84       3587969.8     10184121.38
      3587961.98     10184224.25      3587805.73     10184540.66
      3587542.11     10184891.64      3587492.11     10185491.64
       3587301.9     10185786.36      3587324.14     10185909.18
       3587448.8     10185855.47      3587450.15     10185916.58
      3587364.49     10186093.88      3587386.32     10186118.33
        3587454.     10186098.92      3587466.71     10186159.87
      3587440.24     10186199.01      3587317.86     10186222.13
      3587328.61     10186334.55      3587264.75     10186314.27
      3587229.65     10186336.17       3587212.3      10186542.9
      3587010.44     10186556.57      3586962.83     10186672.47
      3587026.81     10186774.11      3587058.63     10186951.33
      3586996.09     10187051.93      3586928.52     10186950.49
      3586862.46     10186964.02      3586832.11     10187072.96

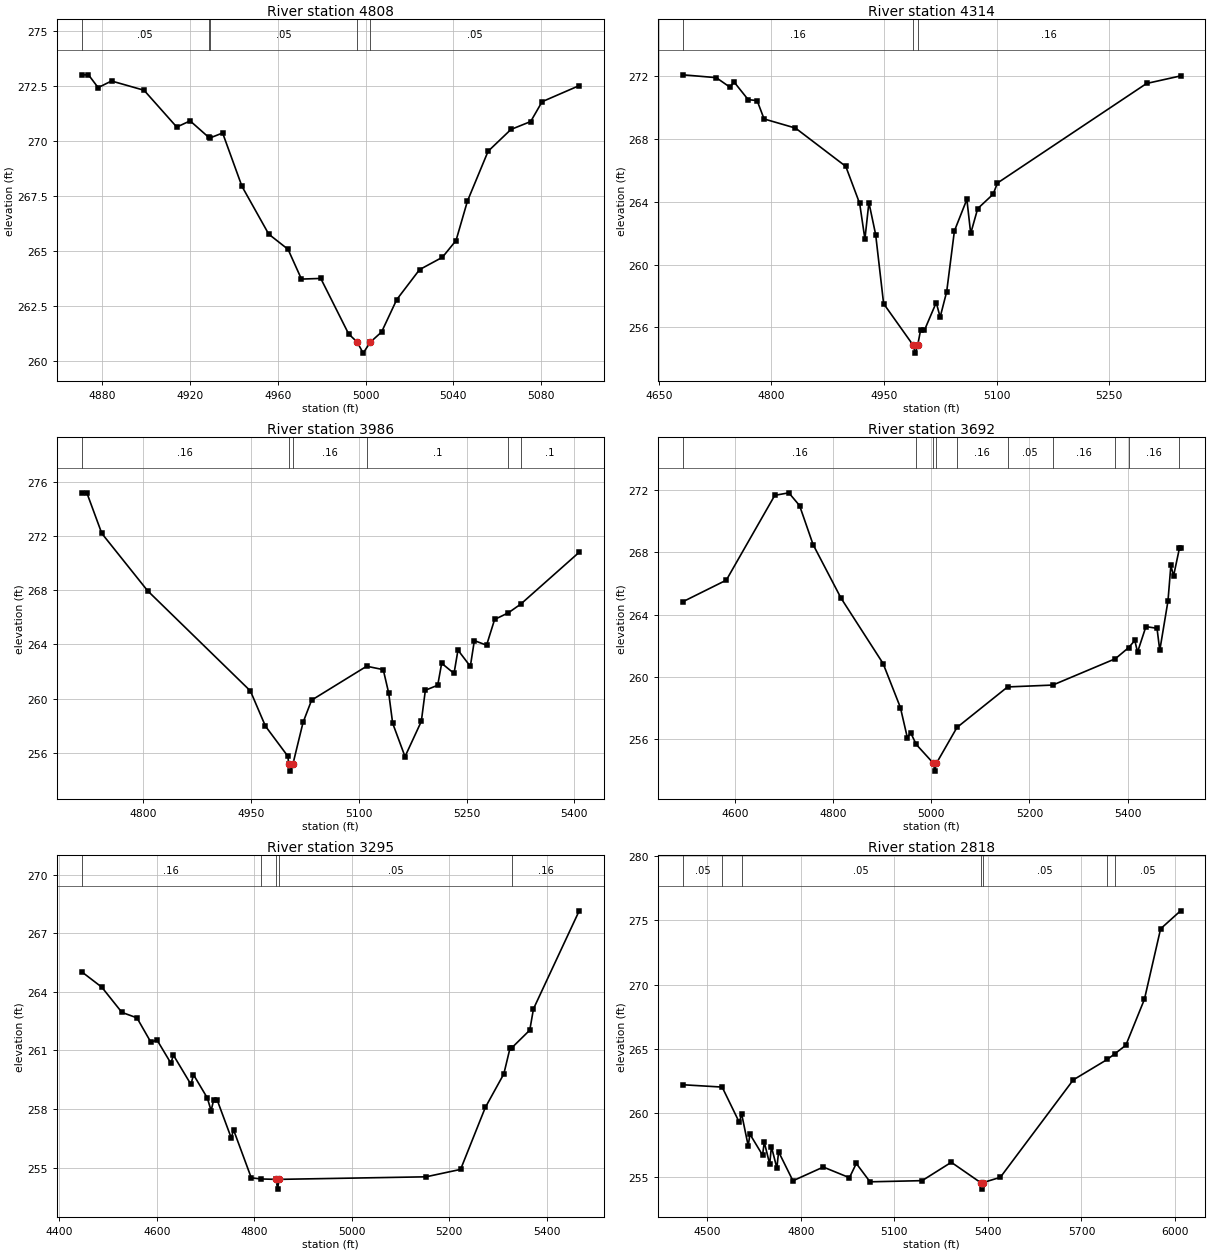
Type RM Length L Ch R = 1 ,4808    ,494,494,494
BEGIN DESCRIPTION:
ALUM CREEK TRIBUTARY 4 10.0
END DESCRIPTION:
XS GIS Cut Line= 3
      3588142.07     10183641.62      3588248.44     10183715.13
      3588342.07     10183741.63
#Sta/Elev= 30
  4870.7     273  4873.8     273  4878.2  272.42  4884.3  272.72  4899.1   272.3
    4914  270.63  4920.1  270.91  4928.6  270.16    4929  270.13  4934.9  270.36
  4943.7  267.94  4955.9  265.77  4964.7  265.08  4970.8  263.73  4979.6  263.76
  4992.3  261.24  4996.2  260.87  4998.9  260.37  5002.2  260.87  5007.3  261.33
  5014.2   262.8  5024.6  264.16    5035  264.72  5041.2  265.48  5046.4  267.27
  5055.8  269.53  5066.2  270.52  5075.2  270.88  5080.4  271.78  5097.3  272.51
#Mann= 5 ,-1 , 0
  4870.7     .05       0  4928.6      .1       0    4929     .05       0
  4996.2     .03       0  5002.2     .05       0
Bank Sta=4996.2,5002.2
XS Rating Curve= 0 ,0
Exp/Cntr=0.3,0.1

Type RM Length L Ch R = 1 ,4314    ,328,328,328
BEGIN DESCRIPTION:
ALUM CREEK TRIBUTARY 4 9.0
END DESCRIPTION:
XS GIS Cut Line= 3
      3587670.37      10184014.9       3587969.8     10184121.38
      3588303.87     10184207.12
#Sta/Elev= 30
  4682.2  272.08  4726.5   271.9  4744.8  271.29  4750.1  271.63    4769   270.5
  4780.9  270.44  4790.2  269.27    4832  268.69    4899  266.25  4917.5  263.89
  4924.5  261.62  4929.8  263.95  4938.8  261.91  4949.4  257.51  4988.8  254.86
  4991.6  254.36  4994.8  254.86  4998.6  255.82  5003.8  255.82  5019.5  257.58
  5024.7  256.65  5033.4  258.27  5043.7  262.14  5060.3  264.15  5065.4  261.98
  5074.7  263.56  5095.3  264.48    5101  265.19  5299.7  271.53  5344.9  272.01
#Mann= 3 ,-1 , 0
  4682.2     .16       0  4988.8     .07       0  4994.8     .16       0
Bank Sta=4988.8,4994.8
XS Rating Curve= 0 ,0
Exp/Cntr=0.3,0.1

Type RM Length L Ch R = 1 ,3986    ,294,294,294
BEGIN DESCRIPTION:
ALUM CREEK TRIBUTARY 4 8.0
END DESCRIPTION:
XS GIS Cut Line= 3
      3587642.09     10184241.63      3587860.42     10184424.77
      3588228.53     10184599.38
#Sta/Elev= 30
  4714.4  275.17  4721.6  275.17  4742.4  272.18  4806.2  267.95  4949.2  260.57
  4970.1  257.98  5001.6  255.74  5002.3  255.16    5005  254.66  5008.3  255.16
  5022.5  258.25  5034.4  259.89    5111  262.39  5134.1  262.14  5141.7  260.41
  5147.2  258.19  5164.4  255.73  5187.1  258.33  5192.7  260.62  5209.9  260.99
  5215.4  262.61  5232.6  261.86  5238.1  263.58  5255.3  262.38  5260.9  264.28
  5277.9  263.94  5289.1  265.84    5308  266.32  5325.5  266.97  5406.8  270.79
#Mann= 6 ,-1 , 0
  4714.4     .16       0  5002.3     .07       0  5008.3     .16       0
    5111      .1       0    5308     .16       0  5325.5      .1       0
Bank Sta=5002.3,5008.3
XS Rating Curve= 0 ,0
Exp/Cntr=0.3,0.1

Type RM Length L Ch R = 1 ,3692    ,397,397,397
BEGIN DESCRIPTION:
ALUM CREEK TRIBUTARY 4 7.0
END DESCRIPTION:
XS GIS Cut Line= 3
      3587378.67     10184290.91      3587708.08     10184674.77
      3588165.12     10184895.09
#Sta/Elev= 30
  4494.5  264.84  4582.7  266.22  4681.4  271.66    4710  271.82  4731.9     271
  4759.4   268.5  4816.4  265.06    4902  260.87  4937.2  258.05  4951.4  256.11
    4958  256.44  4969.5  255.68  5004.5  254.47  5007.2  253.97  5010.5  254.47
  5052.4  256.77  5155.5  259.37  5247.5  259.49    5375  261.18  5401.9  261.89
  5414.6  262.35  5420.1   261.6  5437.2  263.24  5459.8  263.13  5465.4  261.71
  5482.1  264.88    5488  267.16  5493.5  266.49  5505.4  268.26  5507.7  268.26
#Mann= 10 ,-1 , 0
  4494.5     .16       0  4969.5     .05       0  5004.5    .033       0
  5010.5     .05       0  5052.4     .16       0  5155.5     .05       0
  5247.5     .16       0    5375      .1       0  5401.9     .16       0
  5505.4     .05       0
Bank Sta=5004.5,5010.5
XS Rating Curve= 0 ,0
Exp/Cntr=0.3,0.1

Type RM Length L Ch R = 1 ,3295    ,477,477,477
BEGIN DESCRIPTION:
ALUM CREEK TRIBUTARY 4 6.0
END DESCRIPTION:
XS GIS Cut Line= 3
      3586992.07     10184891.63      3587392.11     10184991.64
      3587992.08     10185091.64
#Sta/Elev= 30
    4446  265.03  4487.3  264.24  4528.5  262.95  4559.4  262.67  4587.8  261.43
  4600.7  261.53    4629  260.35  4634.2  260.76  4670.2  259.26  4675.4  259.76
  4703.7  258.57  4711.5  257.92  4716.6  258.44  4724.3  258.44  4752.7  256.53
  4757.8  256.92  4793.9  254.48  4813.9  254.42    4845   254.4  4847.8   253.9
    4851   254.4  5152.3  254.53  5223.3  254.91    5274  258.08    5312   259.8
  5324.7  261.12  5328.1  261.13  5365.2  262.04  5372.8  263.13  5466.6  268.15
#Mann= 5 ,-1 , 0
    4446     .16       0  4813.9     .05       0    4845    .033       0
    4851     .05       0  5328.1     .16       0
Bank Sta=4845,4851
XS Rating Curve= 0 ,0
Exp/Cntr=0.3,0.1

Type RM Length L Ch R = 1 ,2818    ,78,78,78
BEGIN DESCRIPTION:
ALUM CREEK TRIBUTARY 4 5.0
END DESCRIPTION:
XS GIS Cut Line= 3
       3586967.2     10185249.26      3587613.07     10185546.15
      3588388.12     10185972.69
#Sta/Elev= 30
  4422.2   262.2  4547.7  262.02  4602.8  259.27  4610.1  259.94  4631.3  257.44
  4636.8  258.35  4677.3  256.72  4682.8  257.73  4700.2  256.02  4705.7  257.38
  4723.2  255.71  4728.7  256.98  4774.7  254.72  4872.1  255.79  4955.9  254.96
  4977.9  256.07  5021.9  254.64    5189  254.73  5282.6  256.16  5377.1  254.57
  5379.9  254.07  5383.1  254.57  5439.8  254.99  5673.7  262.58  5782.5  264.17
  5806.3   264.6  5842.3  265.28  5901.9  268.86  5953.8  274.35  6017.7  275.75
#Mann= 7 ,-1 , 0
  4422.2     .05       0  4547.7      .1       0  4610.1     .05       0
  5377.1     .03       0  5383.1     .05       0  5782.5      .1       0
  5806.3     .05       0
Bank Sta=5377.1,5383.1
XS Rating Curve= 0 ,0
Exp/Cntr=0.3,0.1

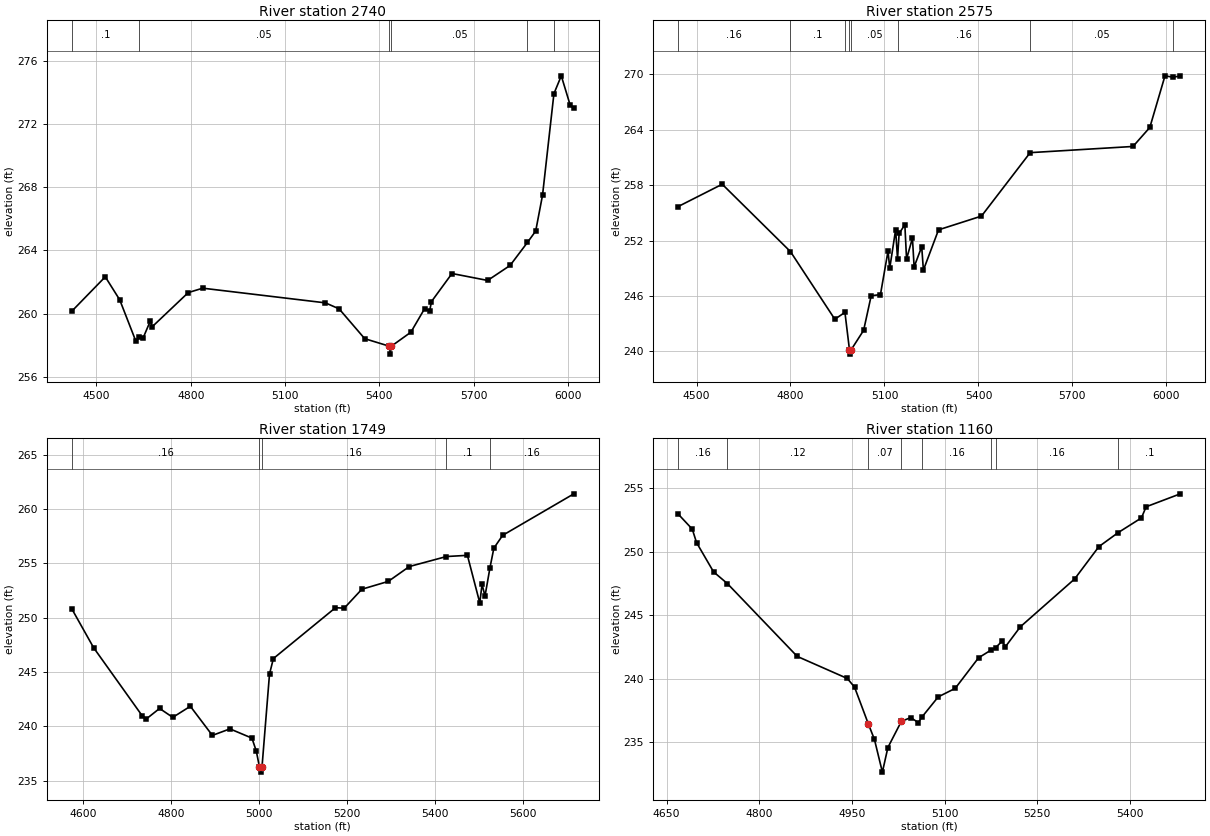
Type RM Length L Ch R = 1 ,2740    ,165,165,165
BEGIN DESCRIPTION:
ALUM CREEK TRIBUTARY 4 5.1
END DESCRIPTION:
XS GIS Cut Line= 3
      3586920.39     10185311.79      3587566.19     10185608.65
      3588342.26     10186035.75
#Sta/Elev= 30
  4421.5  260.14  4528.4  262.33  4574.4  260.87  4625.8  258.24  4635.8  258.49
  4648.8  258.46  4671.8  259.54  4677.3  259.16  4792.2  261.33  4838.1  261.61
  5228.2  260.68  5271.8   260.3  5353.2  258.41  5431.7  257.93  5434.4  257.43
  5437.7  257.93    5500  258.82  5543.6  260.31  5559.7  260.16  5565.4  260.76
  5630.7  262.54    5744   262.1  5815.4  263.05  5870.6  264.51  5896.8  265.23
  5918.6  267.51  5954.8  273.94  5978.2  275.07  6006.5  273.21  6018.1  273.02
#Mann= 6 ,-1 , 0
  4421.5      .1       0  4635.8     .05       0  5431.7     .03       0
  5437.7     .05       0  5870.6     .16       0  5954.8     .05       0
Bank Sta=5431.7,5437.7
XS Rating Curve= 0 ,0
Exp/Cntr=0.3,0.1

Type RM Length L Ch R = 1 ,2575    ,826,826,826
BEGIN DESCRIPTION:
ALUM CREEK TRIBUTARY 4 4.0
END DESCRIPTION:
XS GIS Cut Line= 3
      3586832.78     10185463.14      3587338.41     10185681.23
      3588314.82     10186073.97
#Sta/Elev= 30
  4441.3  255.69  4582.1  258.11    4800  250.81  4941.5  243.49  4973.8  244.23
  4988.2  240.21    4991  239.71  4994.2  240.21  5033.5  242.29  5057.6  246.03
  5087.2  246.16  5111.4  250.88  5116.8     249  5135.6  253.18  5141.7  250.03
  5146.8  252.78  5165.1  253.72  5170.5  250.01  5189.3  252.27  5194.7  249.16
  5218.9  251.34  5224.3  248.81  5272.6  253.17  5409.7  254.66  5565.1  261.53
  5893.4   262.2  5947.1  264.26  5995.5  269.85  6021.3   269.7  6044.4  269.84
#Mann= 8 ,-1 , 0
  4441.3     .16       0    4800      .1       0  4973.8     .05       0
  4988.2     .03       0  4994.2     .05       0  5141.7     .16       0
  5565.1     .05       0  6021.3     .16       0
Bank Sta=4988.2,4994.2
XS Rating Curve= 0 ,0
Exp/Cntr=0.3,0.1

Type RM Length L Ch R = 1 ,1749    ,589,589,589
BEGIN DESCRIPTION:
ALUM CREEK TRIBUTARY 4 2.0
END DESCRIPTION:
XS GIS Cut Line= 3
      3587042.12     10186141.64      3587926.08     10186170.31
      3588183.58     10186150.38
#Sta/Elev= 30
  4573.4  250.83  4623.4  247.23  4733.5  240.99  4743.5  240.68  4773.5  241.64
  4803.5  240.82  4843.5  241.84  4893.6  239.16  4933.6  239.76  4983.6  238.91
  4993.6  237.71  5000.6  236.28  5003.4  235.78  5006.6  236.28  5023.6   244.8
  5032.4  246.23  5173.7  250.91  5193.7  250.87  5233.7  252.61  5293.8  253.33
  5341.8   254.7  5426.2  255.62  5473.9  255.73  5502.1  251.35  5507.2  253.05
    5514  251.99  5525.3   254.6  5534.1  256.39  5554.1  257.57  5716.1  261.39
#Mann= 5 ,-1 , 0
  4573.4     .16       0  5000.6     .07       0  5006.6     .16       0
  5426.2      .1       0  5525.3     .16       0
Bank Sta=5000.6,5006.6
XS Rating Curve= 0 ,0
Exp/Cntr=0.3,0.1

Type RM Length L Ch R = 1 ,1160    ,0,0,0
BEGIN DESCRIPTION:
ALUM CREEK TRIBUTARY 4 1.0
END DESCRIPTION:
XS GIS Cut Line= 3
      3586942.08     10186341.63      3587415.47     10186601.87
      3587674.62     10186687.05
#Sta/Elev= 30
  4668.6  252.97  4691.5  251.78  4698.5  250.71    4726  248.41  4748.3  247.49
  4861.4  241.75  4942.5  240.01  4954.2  239.33  4976.7  236.41  4986.4  235.21
  4999.3  232.63  5008.2  234.57    5030  236.63  5045.2  236.93  5057.5  236.53
  5063.3  236.97  5089.7  238.56  5117.2  239.23    5155  241.64  5175.3  242.25
  5182.6  242.44  5192.9  242.94  5198.6  242.52  5222.6  244.08  5310.5  247.85
  5349.8   250.4  5381.2  251.51  5418.6  252.66  5426.3  253.54  5481.6  254.56
#Mann= 8 ,-1 , 0
  4668.6     .16       0  4748.3     .12       0  4976.7     .07       0
    5030     .12       0  5063.3     .16       0  5175.3     .12       0
  5182.6     .16       0  5381.2      .1       0
Bank Sta=4976.7,5030
XS Rating Curve= 0 ,0
Exp/Cntr=0.3,0.1

Chan Stop Cuts=-1
Use User Specified Reach Order=0
Composite Channel Slope=5