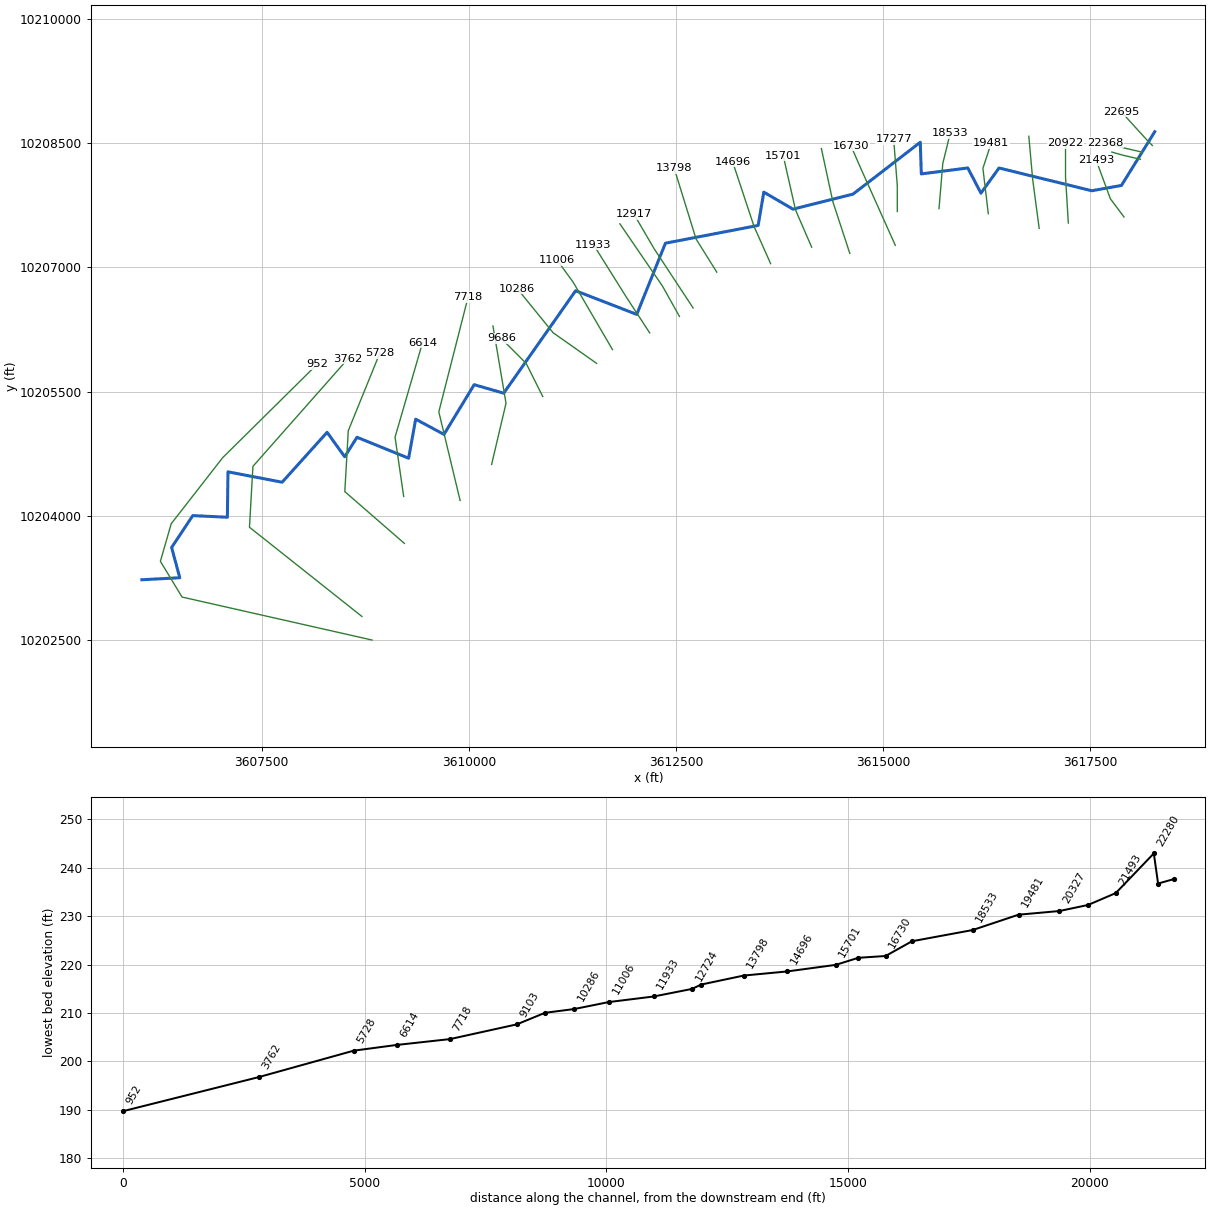
--- ALUM CREEK.prj (project) ---

Proj Title=ALUM CREEK Base Level Engineering
Current Plan=p01
Default Exp/Contr=0.3,0.1
English Units
Geom File=g01
Flow File=f01
Plan File=p01
Y Axis Title=Elevation
X Axis Title(PF)=Main Channel Distance
X Axis Title(XS)=Station
BEGIN DESCRIPTION:
ALUM CREEK
END DESCRIPTION:
DSS Export Rating Curves= 0
DSS Export Rating Curve Sorted= 0
DSS Export Volume Flow Curves= 0
DXF OffsetX= 0
DXF OffsetY= 0
DXF ScaleX= 1
DXF ScaleY= 10

--- ALUM CREEK.p01 (plan) ---

Plan Title=Multiple Run
Short Identifier=Multiple
Geom File=g01
Flow File=f01
Subcritical Flow
K Sum by GR= 0
Std Step Tol= 0.01
Critical Tol= 0.01
Num of Std Step Trials= 20
Max Error Tol= 0.3
Flow Tol Ratio= 0.001
Split Flow NTrial= 30
Split Flow Tol= 0.02
Split Flow Ratio= 0.02
Log Output Level= 0
Friction Slope Method= 1
Unsteady Friction Slope Method= 2
Unsteady Bridges Friction Slope Method= 1
Parabolic Critical Depth
Global Vel Dist=  1 , 1 , 1
Global Log Level= 0
CheckData=True
Encroach Param= -1, 0, 0, 0
BEGIN DESCRIPTION:
Multiple Run
END DESCRIPTION:

--- ALUM CREEK.f01 (steady flow) ---

Flow Title=Multiple
Program Version=4.10
Number of Profiles= 7
Profile Names=10-year,25-year,50-year,1pct_min,100-year,1pct_plu,500-year
River Rch & RM=ALUM CREEK,Reach-1         ,22695
     406     535     637     557     754    1020    1056
River Rch & RM=ALUM CREEK,Reach-1         ,22280
     748    1022    1248    1117    1510    2043    2216
River Rch & RM=ALUM CREEK,Reach-1         ,17277
     882    1206    1473    1316    1779    2406    2604
River Rch & RM=ALUM CREEK,Reach-1         ,9103
     979    1339    1637    1462    1978    2675    2894
River Rch & RM=ALUM CREEK,Reach-1         ,7718
     979    1339    1637    1462    1978    2675    2894
Boundary for River Rch & Prof#=ALUM CREEK,Reach-1         , 1
Up Type= 0
Dn Type= 3
Dn Slope=0.005
Boundary for River Rch & Prof#=ALUM CREEK,Reach-1         , 2
Up Type= 0
Dn Type= 3
Dn Slope=0.005
Boundary for River Rch & Prof#=ALUM CREEK,Reach-1         , 3
Up Type= 0
Dn Type= 3
Dn Slope=0.005
Boundary for River Rch & Prof#=ALUM CREEK,Reach-1         , 4
Up Type= 0
Dn Type= 3
Dn Slope=0.005
Boundary for River Rch & Prof#=ALUM CREEK,Reach-1         , 5
Up Type= 0
Dn Type= 3
Dn Slope=0.005
Boundary for River Rch & Prof#=ALUM CREEK,Reach-1         , 6
Up Type= 0
Dn Type= 3
Dn Slope=0.005
Boundary for River Rch & Prof#=ALUM CREEK,Reach-1         , 7
Up Type= 0
Dn Type= 3
Dn Slope=0.005
DSS Import GetInterval= 0
DSS Import GetPeak= 0
DSS Import FillOption= 0

--- ALUM CREEK.g01 (geometry) ---

Geom Title=Existing Conditions
Program Version=4.10

River Reach=ALUM CREEK      ,Reach-1
Reach XY= 30
      3618275.69     10208636.37      3617873.52     10207987.88
      3617516.33      10207923.9      3616396.73     10208198.34
      3616178.67     10207894.91      3616020.04     10208198.81
      3615459.35     10208126.93      3615446.93     10208508.47
      3614636.04     10207883.78      3613911.78     10207701.55
      3613559.38     10207906.94      3613491.02     10207505.45
      3612372.55     10207291.16      3612026.65     10206432.06
      3611288.89     10206717.44      3610421.53     10205481.78
      3610065.28     10205584.27      3609700.73     10204984.38
      3609359.66     10205168.41      3609274.41     10204697.11
      3608651.51       10204950.      3608503.04     10204714.83
      3608291.04     10205009.77      3607748.88     10204407.78
      3607095.26     10204532.89      3607087.83     10203984.96
      3606670.69       10204005.      3606415.29     10203620.48
      3606513.74     10203255.38      3606057.21      10203231.2

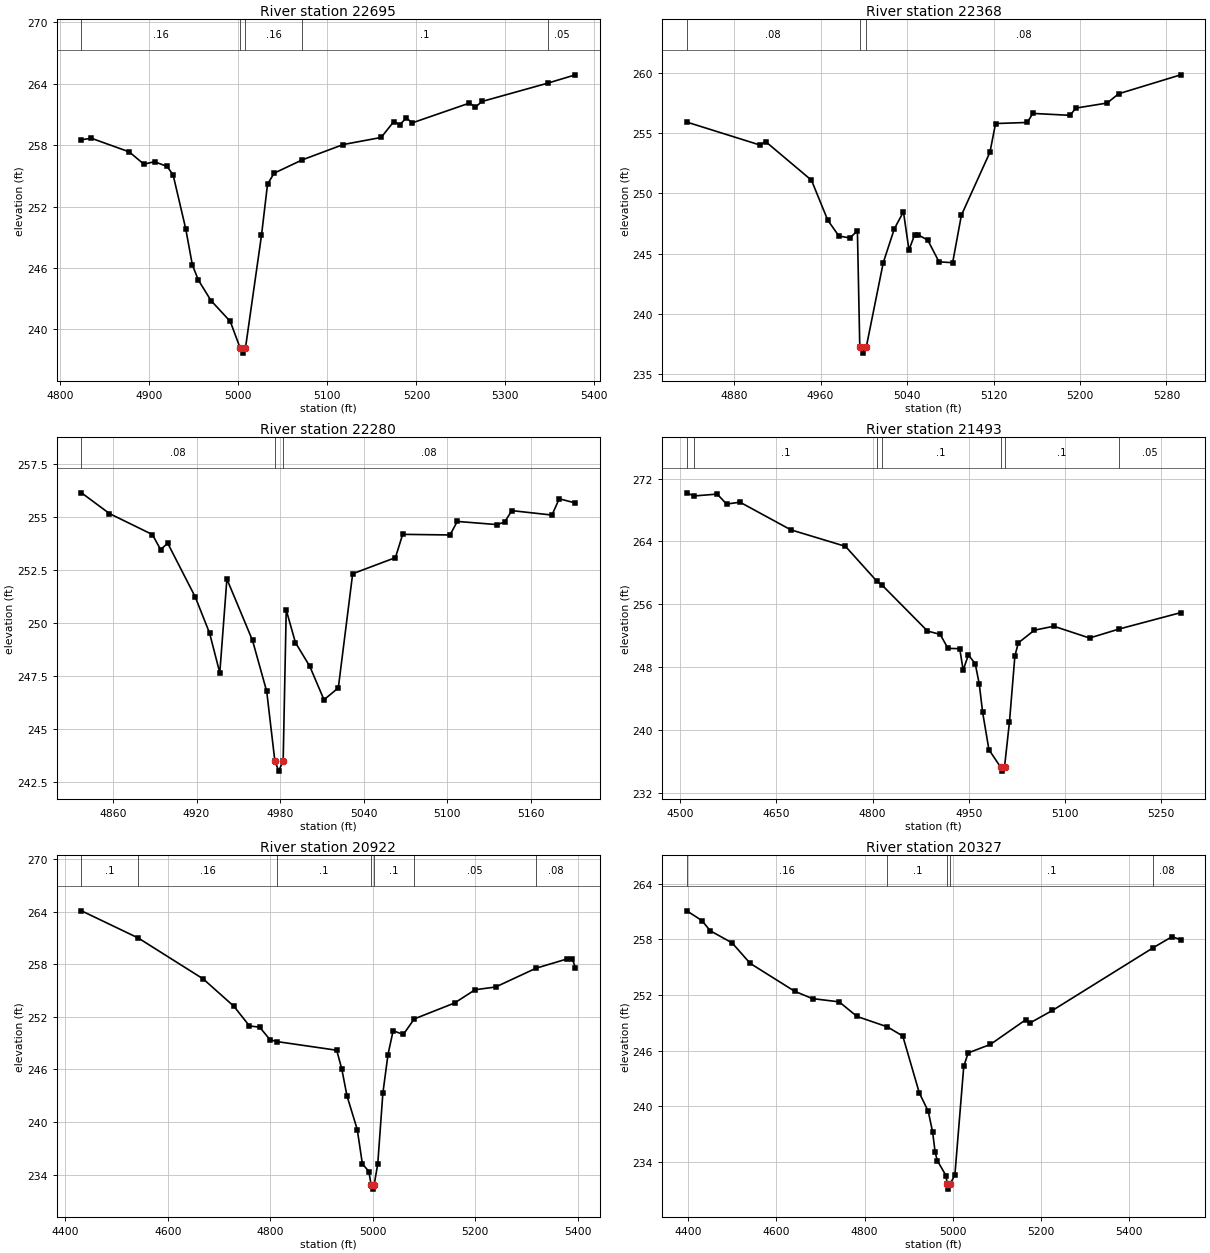
Type RM Length L Ch R = 1 ,22695   ,327,327,327
BEGIN DESCRIPTION:
ALUM CREEK 30.0
END DESCRIPTION:
XS GIS Cut Line= 3
      3618246.28     10208469.93      3618196.27     10208519.94
      3617869.74      10208877.7
#Sta/Elev= 30
  4823.6  258.53  4834.8  258.67  4877.3  257.34  4893.7  256.14  4905.7  256.38
  4919.8  255.92  4926.6  255.09  4940.8  249.81  4948.2   246.3    4955  244.81
  4969.2  242.81  4990.8  240.78  5001.9  238.18  5004.7  237.68  5007.9  238.18
  5025.9  249.18  5032.7  254.18  5040.1  255.26  5071.7  256.56  5117.8  258.06
  5160.4  258.75  5174.6   260.3  5181.3     260  5188.7  260.65  5195.5  260.18
  5259.7  262.11  5266.4  261.73  5273.9  262.27  5347.4  264.05  5378.7  264.87
#Mann= 5 ,-1 , 0
  4823.6     .16       0  5001.9     .07       0  5007.9     .16       0
  5071.7      .1       0  5347.4     .05       0
Bank Sta=5001.9,5007.9
XS Rating Curve= 0 ,0
Exp/Cntr=0.3,0.1

Type RM Length L Ch R = 1 ,22368   ,88,88,88
BEGIN DESCRIPTION:
ALUM CREEK 29.0
END DESCRIPTION:
XS GIS Cut Line= 3
      3618119.09     10208390.37      3617910.72     10208438.99
      3617676.39     10208503.07
#Sta/Elev= 30
  4836.3  255.92  4903.9  254.02  4909.1  254.31  4951.6   251.1  4966.7  247.78
    4977  246.47  4987.2  246.31  4994.1  246.91  4996.3  237.26    4999  236.76
  5002.3  237.26    5018  244.26  5028.3  247.08  5036.7  248.48  5041.8  245.31
    5047  246.57  5050.3  246.57  5059.2  246.13  5069.6  244.33  5082.2  244.26
  5090.3   248.2  5116.7  253.42  5121.9   255.8  5151.2  255.89  5156.4  256.64
  5190.9  256.48  5196.1  257.08  5225.1   257.5  5235.8  258.27  5293.2  259.84
#Mann= 3 ,-1 , 0
  4836.3     .08       0  4996.3     .07       0  5002.3     .08       0
Bank Sta=4996.3,5002.3
XS Rating Curve= 0 ,0
Exp/Cntr=0.3,0.1

Type RM Length L Ch R = 1 ,22280   ,787,787,787
BEGIN DESCRIPTION:
ALUM CREEK 29.1
END DESCRIPTION:
XS GIS Cut Line= 3
      3618101.67     10208303.58      3617893.36     10208352.19
      3617757.95     10208390.38
#Sta/Elev= 30
  4837.4  256.13  4857.5  255.15  4888.3  254.16  4894.2  253.45  4899.3  253.75
  4919.1  251.21  4929.4   249.5  4936.7  247.63  4941.8  252.06  4960.2  249.16
  4970.4  246.75  4976.2  243.49    4979  242.99  4982.2  243.49  4984.4   250.6
    4991  249.06  5001.3  247.94  5011.5  246.36  5021.8  246.92  5032.1  252.31
  5062.8  253.07    5068  254.17    5102  254.14  5107.2  254.78  5135.7  254.63
  5141.2  254.75  5146.4  255.29  5175.2  255.08  5180.4  255.85    5192  255.65
#Mann= 3 ,-1 , 0
  4837.4     .08       0  4976.2     .07       0  4982.2     .08       0
Bank Sta=4976.2,4982.2
XS Rating Curve= 0 ,0
Exp/Cntr=0.3,0.1

Type RM Length L Ch R = 1 ,21493   ,571,571,571
BEGIN DESCRIPTION:
ALUM CREEK 28.0
END DESCRIPTION:
XS GIS Cut Line= 3
      3617904.63     10207607.42      3617740.58     10207826.14
      3617568.72     10208292.26
#Sta/Elev= 30
  4510.2  270.19  4521.2  269.79  4557.6  270.03  4572.2  268.76  4593.1     269
  4672.2  265.49  4757.6  263.38  4806.6  258.94  4814.3  258.48  4885.5  252.61
  4905.3  252.18  4917.4  250.41  4935.8  250.36  4941.1  247.64  4949.3  249.58
    4960  248.43  4966.2  245.88  4971.5  242.26  4981.3  237.52  4999.6  235.29
  5002.4  234.79  5005.6  235.29  5013.3  241.03  5021.8  249.44  5027.1   251.1
  5052.2  252.72  5082.6  253.22  5138.2  251.72  5184.9  252.88  5280.4  254.95
#Mann= 7 ,-1 , 0
  4510.2     .05       0  4521.2      .1       0  4806.6     .16       0
  4814.3      .1       0  4999.6     .07       0  5005.6      .1       0
  5184.9     .05       0
Bank Sta=4999.6,5005.6
XS Rating Curve= 0 ,0
Exp/Cntr=0.3,0.1

Type RM Length L Ch R = 1 ,20922   ,595,595,595
BEGIN DESCRIPTION:
ALUM CREEK 27.0
END DESCRIPTION:
XS GIS Cut Line= 3
      3617232.77     10207534.46      3617198.92     10208094.37
      3617198.92     10208497.34
#Sta/Elev= 30
  4431.7  264.08  4542.5  260.98  4669.3  256.31  4729.4  253.18  4759.5  250.95
  4779.5  250.81  4799.6  249.38  4812.9  249.17  4929.8  248.18  4939.8  246.02
  4949.8  242.99  4969.9  239.14  4979.9  235.23  4992.6  234.35  4996.9  232.84
  4999.7  232.34  5002.9  232.84  5009.9  235.21  5019.9  243.29  5029.9  247.69
  5039.9   250.4  5059.9  249.98  5081.1  251.75  5159.9  253.57  5199.9  255.08
  5239.9  255.39  5318.6  257.53  5379.9   258.6  5389.9  258.56  5395.6  257.59
#Mann= 7 ,-1 , 0
  4431.7      .1       0  4542.5     .16       0  4812.9      .1       0
  4996.9     .07       0  5002.9      .1       0  5081.1     .05       0
  5318.6     .08       0
Bank Sta=4996.9,5002.9
XS Rating Curve= 0 ,0
Exp/Cntr=0.3,0.1

Type RM Length L Ch R = 1 ,20327   ,846,846,846
BEGIN DESCRIPTION:
ALUM CREEK 25.0
END DESCRIPTION:
XS GIS Cut Line= 3
      3616881.21     10207469.35      3616803.08     10208057.91
       3616756.2     10208581.39
#Sta/Elev= 30
  4397.3  261.07  4431.7  260.01  4450.1  258.93    4500  257.61  4540.8  255.41
  4641.7   252.4  4682.1  251.61  4742.6  251.26  4782.9  249.69  4851.6  248.57
  4886.7  247.58  4924.2  241.44  4944.4  239.47  4954.4  237.21    4960  235.07
    4965  234.15  4984.7  232.53  4987.4  231.58  4990.1  231.08  4993.4  231.58
  5004.8  232.62  5024.9  244.31  5034.9  245.76  5085.1  246.67  5165.3  249.33
  5175.5     249  5225.7  250.33  5454.8  257.11  5496.8  258.28  5516.6  257.96
#Mann= 5 ,-1 , 0
  4397.3     .16       0  4851.6      .1       0  4987.4     .07       0
  4993.4      .1       0  5454.8     .08       0
Bank Sta=4987.4,4993.4
XS Rating Curve= 0 ,0
Exp/Cntr=0.3,0.1

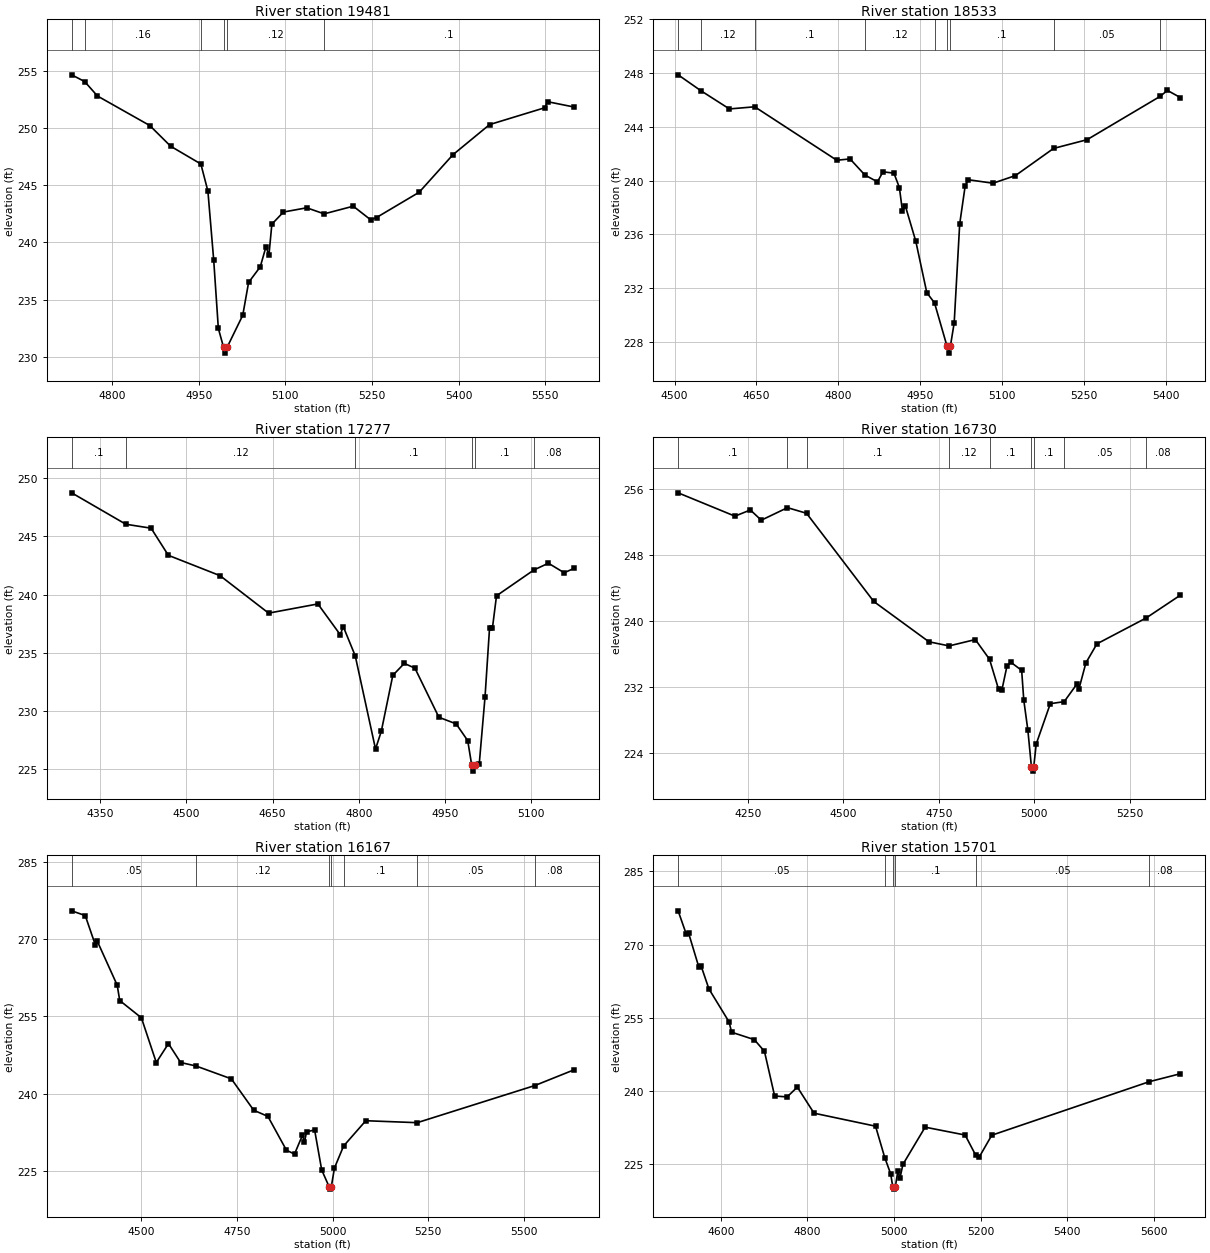
Type RM Length L Ch R = 1 ,19481   ,948,948,948
BEGIN DESCRIPTION:
ALUM CREEK 24.0
END DESCRIPTION:
XS GIS Cut Line= 3
       3616267.5     10207647.28      3616202.39      10208194.2
        3616302.     10208497.37
#Sta/Elev= 30
  4729.8  254.64  4752.4  254.05  4774.5  252.79  4865.1  250.21  4901.3   248.4
  4953.6  246.85  4965.8  244.48  4975.9  238.43  4983.9  232.48    4993  230.82
  4995.8  230.32    4999  230.82  5026.2  233.63  5036.3   236.5  5056.5  237.86
  5066.5  239.63  5071.5  238.87  5076.6  241.59  5096.7  242.65    5137  243.02
  5167.2  242.49  5217.6  243.16  5247.8  241.97  5257.9  242.17  5331.8  244.38
  5390.1  247.65  5453.7  250.29  5549.1  251.76  5554.4  252.29  5599.7  251.83
#Mann= 6 ,-1 , 0
  4729.8      .1       0  4752.4     .16       0  4953.6     .12       0
    4993     .07       0    4999     .12       0  5167.2      .1       0
Bank Sta=4993,4999
XS Rating Curve= 0 ,0
Exp/Cntr=0.3,0.1

Type RM Length L Ch R = 1 ,18533   ,1256,1256,1256
BEGIN DESCRIPTION:
ALUM CREEK 22.0
END DESCRIPTION:
XS GIS Cut Line= 3
      3615672.87     10207708.05      3615718.32     10208252.23
      3615807.27      10208614.6
#Sta/Elev= 30
  4506.6  247.87  4547.8   246.7  4600.5  245.33  4646.8  245.49    4797  241.51
  4821.3  241.61  4848.5  240.41  4871.5   239.9  4881.5  240.65  4901.6  240.55
  4911.6  239.48  4917.3   237.7  4922.3  238.14  4941.7  235.47  4961.8  231.65
  4975.9  230.89  4998.9  227.65  5001.7  227.15  5004.9  227.65  5011.9   229.4
    5022  236.77    5032  239.59  5037.6  240.06    5083   239.8  5124.1  240.37
  5193.8  242.39  5255.1  243.04  5388.6  246.26  5402.2  246.71  5425.8  246.18
#Mann= 9 ,-1 , 0
  4506.6      .1       0  4547.8     .12       0  4646.8      .1       0
  4848.5     .12       0  4975.9      .1       0  4998.9     .07       0
  5004.9      .1       0  5193.8     .05       0  5388.6     .08       0
Bank Sta=4998.9,5004.9
XS Rating Curve= 0 ,0
Exp/Cntr=0.3,0.1

Type RM Length L Ch R = 1 ,17277   ,547,547,547
BEGIN DESCRIPTION:
ALUM CREEK 20.0
END DESCRIPTION:
XS GIS Cut Line= 3
       3615169.4     10207673.39       3615169.4     10207985.87
        3615126.     10208545.81
#Sta/Elev= 30
  4300.3  248.75  4394.6  246.05  4438.6  245.71  4468.6  243.38  4558.6  241.63
  4643.1  238.41  4728.9   239.2  4767.9  236.55    4773  237.26  4793.9  234.74
  4829.2  226.73  4839.2  228.24  4859.3  233.06  4879.3  234.09  4897.8  233.68
  4939.5  229.46  4969.6  228.89  4989.7  227.45  4996.7  225.33  4999.5  224.83
  5002.7  225.33  5009.7  225.42  5019.8   231.2  5027.7  237.14  5032.7  237.13
  5039.8   239.9  5104.9  242.12  5130.1   242.7  5157.6  241.88  5174.4  242.25
#Mann= 6 ,-1 , 0
  4300.3      .1       0  4394.6     .12       0  4793.9      .1       0
  4996.7     .07       0  5002.7      .1       0  5104.9     .08       0
Bank Sta=4996.7,5002.7
XS Rating Curve= 0 ,0
Exp/Cntr=0.3,0.1

Type RM Length L Ch R = 1 ,16730   ,563,563,563
BEGIN DESCRIPTION:
ALUM CREEK 19.0
END DESCRIPTION:
XS GIS Cut Line= 3
      3615145.31     10207265.83      3614731.03     10208189.86
      3614609.72     10208467.14
#Sta/Elev= 30
  4067.2  255.54    4216  252.71  4256.4  253.46    4285  252.22  4353.6  253.74
  4403.5  253.06  4579.6  242.36  4724.2  237.47    4777  236.97  4845.6  237.74
  4882.8  235.35  4906.5  231.71  4915.1   231.6  4928.4   234.5  4938.3     235
    4967     234  4972.5  230.41  4983.2  226.76  4992.6  222.28  4995.4  221.78
  4998.6  222.28  5005.1  225.07    5042  229.96  5078.4  230.21  5111.8  232.35
  5117.3   231.8  5135.2  234.91  5164.1  237.22  5292.8  240.35  5382.5  243.12
#Mann= 9 ,-1 , 0
  4067.2      .1       0  4353.6     .16       0  4403.5      .1       0
    4777     .12       0  4882.8      .1       0  4992.6     .07       0
  4998.6      .1       0  5078.4     .05       0  5292.8     .08       0
Bank Sta=4992.6,4998.6
XS Rating Curve= 0 ,0
Exp/Cntr=0.3,0.1

Type RM Length L Ch R = 1 ,16167   ,466,466,466
BEGIN DESCRIPTION:
ALUM CREEK 18.0
END DESCRIPTION:
XS GIS Cut Line= 3
      3614596.72     10207168.53      3614392.11     10207791.64
       3614253.6     10208432.91
#Sta/Elev= 30
  4318.5  275.52    4354   274.6  4380.5  268.86  4385.8  269.56  4437.5  261.06
  4444.1  258.08  4500.7  254.72  4539.6  246.03  4571.4   249.7  4603.2  246.03
  4643.4  245.35  4735.7  242.85  4794.1  236.75  4831.2  235.55  4879.6  228.98
  4900.7  228.22  4921.4  231.89  4926.6  230.55  4932.2  232.55  4953.2  232.92
  4971.7  225.14  4990.9  221.91  4993.6  221.41  4996.9  221.91    5005  225.51
  5028.9  229.79  5086.9  234.71  5221.2  234.33  5528.5  241.55  5630.4  244.59
#Mann= 7 ,-1 , 0
  4318.5     .05       0  4643.4     .12       0  4990.9     .07       0
  4996.9     .12       0  5028.9      .1       0  5221.2     .05       0
  5528.5     .08       0
Bank Sta=4990.9,4996.9
XS Rating Curve= 0 ,0
Exp/Cntr=0.3,0.1

Type RM Length L Ch R = 1 ,15701   ,1005,1005,1005
BEGIN DESCRIPTION:
ALUM CREEK 17.0
END DESCRIPTION:
XS GIS Cut Line= 3
       3614136.4     10207243.71      3613942.11     10207691.64
      3613793.53     10208346.14
#Sta/Elev= 30
  4501.6   276.9  4520.3  272.16  4525.8  272.33  4549.2  265.45  4554.7  265.61
  4572.7  260.92  4619.2  254.17  4625.1  252.06  4677.5  250.54  4700.9  248.15
  4724.4  239.01  4753.3  238.82  4776.8  240.83  4815.4  235.49  4957.4  232.83
  4978.6  226.42  4992.4  223.06  4997.1  220.45  4999.9  219.95  5003.1  220.45
  5008.8   223.6    5014   222.3  5020.6  225.01  5071.9  232.63  5164.2  231.02
  5188.4  226.93  5196.6  226.49  5225.7  230.98  5589.5  241.94    5661  243.56
#Mann= 6 ,-1 , 0
  4501.6     .05       0  4978.6      .1       0  4997.1     .07       0
  5003.1      .1       0  5188.4     .05       0  5589.5     .08       0
Bank Sta=4997.1,5003.1
XS Rating Curve= 0 ,0
Exp/Cntr=0.3,0.1

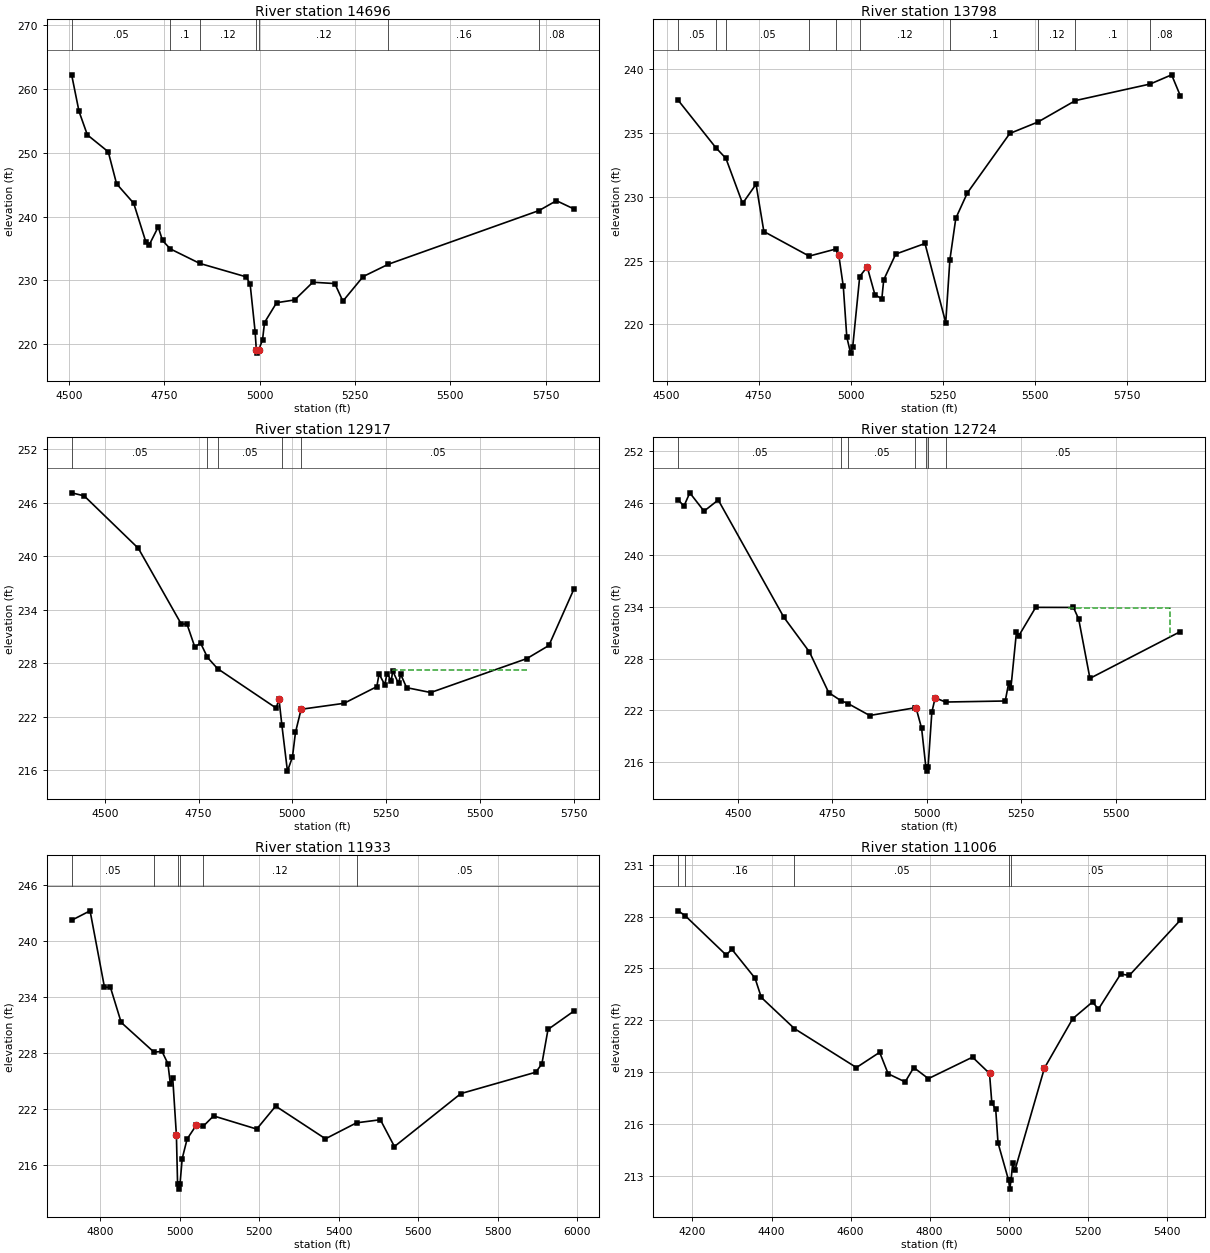
Type RM Length L Ch R = 1 ,14696   ,898,898,898
BEGIN DESCRIPTION:
ALUM CREEK 15.0
END DESCRIPTION:
XS GIS Cut Line= 3
      3613641.63       10207044.      3613442.11     10207491.64
      3613181.56     10208276.64
#Sta/Elev= 30
    4507  262.24  4526.3  256.51  4548.2  252.82    4603  250.17  4624.8  245.15
  4669.8  242.09  4701.5  236.05  4710.8  235.61    4734  238.38  4745.3  236.26
  4765.7  234.94  4843.1  232.66    4965  230.55  4975.2  229.38  4988.2  221.97
  4991.4  219.09  4994.1  218.59  4997.4  219.09  5007.6  220.64  5012.9  223.39
  5044.6   226.5  5091.9  226.93  5139.6  229.71  5197.3   229.5  5218.4  226.74
  5271.6   230.6    5338  232.54  5733.2  240.96  5778.5   242.5  5824.2  241.21
#Mann= 7 ,-1 , 0
    4507     .05       0  4765.7      .1       0  4843.1     .12       0
  4991.4     .07       0  4997.4     .12       0    5338     .16       0
  5733.2     .08       0
Bank Sta=4991.4,4997.4
XS Rating Curve= 0 ,0
Exp/Cntr=0.3,0.1

Type RM Length L Ch R = 1 ,13798   ,881,881,881
BEGIN DESCRIPTION:
ALUM CREEK 13.0
END DESCRIPTION:
XS GIS Cut Line= 3
      3612992.12     10206941.62      3612742.11     10207341.64
      3612478.44     10208194.18
#Sta/Elev= 30
  4531.4  237.58  4633.7  233.86  4661.2  233.02  4706.5  229.48  4743.1  230.99
  4764.3  227.28  4887.4  225.35  4958.9   225.9  4967.7  225.45  4980.1  222.97
  4989.6     219  4999.9  217.74  5005.7  218.24  5024.7  223.75    5045  224.51
  5065.9  222.33  5084.7  221.99  5089.9  223.49  5122.5  225.51    5202  226.34
  5258.3  220.13  5269.6  225.06  5285.7  228.32  5317.1  230.31  5432.3  234.97
  5508.9  235.87  5610.5  237.55  5813.8  238.85  5871.9  239.57  5895.5  237.93
#Mann= 10 ,-1 , 0
  4531.4     .05       0  4633.7     .12       0  4661.2     .05       0
  4887.4     .12       0  4958.9     .07       0  5024.7     .12       0
  5269.6      .1       0  5508.9     .12       0  5610.5      .1       0
  5813.8     .08       0
Bank Sta=4967.7,5045
XS Rating Curve= 0 ,0
Exp/Cntr=0.3,0.1

Type RM Length L Ch R = 1 ,12917   ,193,193,193
BEGIN DESCRIPTION:
ALUM CREEK 12.0
END DESCRIPTION:
XS GIS Cut Line= 3
      3612706.27      10206510.2      3612237.54     10207221.98
      3611992.11     10207641.63
#Sta/Elev= 30
  4411.9  247.11  4445.2  246.77  4589.7  240.88  4704.1  232.38  4719.2  232.39
  4740.3  229.79  4755.4  230.26  4773.9  228.64  4800.8  227.38  4957.1  222.95
  4964.4  223.99  4972.2  221.04    4987  215.88  5000.3  217.45  5008.4  220.22
  5023.4  222.82  5137.8  223.49  5225.2  225.36  5231.2   226.8  5246.3  225.57
  5252.3   226.8  5264.1  226.04  5267.3  227.15    5283  225.72  5288.8  226.75
  5304.5  225.25  5368.9   224.7  5625.1  228.51  5683.8  229.98  5750.3  236.29
#Mann= 5 ,-1 , 0
  4411.9     .05       0  4773.9     .12       0  4800.8     .05       0
  4972.2     .03       0  5023.4     .05       0
#XS Ineff= 1 ,-1
 5267.05  5624.2  227.27
Permanent Ineff=
       F
Bank Sta=4964.4,5023.4
XS Rating Curve= 0 ,0
Exp/Cntr=0.3,0.1

Type RM Length L Ch R = 1 ,12724   ,791,791,791
BEGIN DESCRIPTION:
ALUM CREEK 10.0
END DESCRIPTION:
XS GIS Cut Line= 3
      3612541.35     10206408.19      3612337.37     10206772.76
      3611822.84      10207525.2
#Sta/Elev= 30
  4341.8  246.39  4357.2  245.65  4372.7  247.19  4410.4  245.07    4448  246.36
  4621.6  232.79  4689.5  228.76  4740.4  224.06  4772.3  223.14  4792.1  222.78
  4848.8  221.41  4968.1   222.3  4971.4  222.33  4986.3  219.94  4997.5  215.47
  5000.2  214.97  5003.5  215.47  5013.4  221.78  5022.2  223.46  5049.6  222.97
  5207.7  223.09  5216.6  225.12  5222.6  224.57  5237.5  231.13  5243.6  230.64
  5288.3  233.93  5388.2  233.92  5402.1  232.58  5431.9  225.71  5671.1  231.12
#Mann= 7 ,-1 , 0
  4341.8     .05       0  4772.3     .12       0  4792.1     .05       0
  4968.1     .12       0  4997.5     .07       0  5003.5     .12       0
  5049.6     .05       0
#XS Ineff= 1 ,-1
 5373.64 5644.55  233.83
Permanent Ineff=
       F
Bank Sta=4971.4,5022.2
XS Rating Curve= 0 ,0
Exp/Cntr=0.3,0.1

Type RM Length L Ch R = 1 ,11933   ,927,927,927
BEGIN DESCRIPTION:
ALUM CREEK 9.0
END DESCRIPTION:
XS GIS Cut Line= 3
        3612183.     10206208.82      3611901.17     10206640.38
      3611504.02     10207274.08
#Sta/Elev= 30
    4728   242.2  4774.3  243.21  4810.5  235.04  4825.6  235.01  4852.6  231.26
  4935.1  228.08  4955.3  228.15  4970.2  226.84  4976.4  224.63  4982.3   225.3
  4991.5   219.2  4994.5  213.91  4997.2  213.41  5000.5  213.91  5006.1  216.68
  5018.5  218.78  5041.9  220.28  5058.5  220.12    5085  221.25  5193.6  219.84
  5241.2   222.3  5366.5   218.8  5444.6  220.51  5504.6  220.84    5540  217.97
  5707.1  223.64  5895.6  225.93  5910.9  226.82  5926.3  230.51  5991.3  232.47
#Mann= 6 ,-1 , 0
    4728     .05       0  4935.1     .16       0  4994.5     .07       0
  5000.5     .16       0  5058.5     .12       0  5444.6     .05       0
Bank Sta=4991.5,5041.9
XS Rating Curve= 0 ,0
Exp/Cntr=0.3,0.1

Type RM Length L Ch R = 1 ,11006   ,720,720,720
BEGIN DESCRIPTION:
ALUM CREEK 8.0
END DESCRIPTION:
XS GIS Cut Line= 3
      3611734.08     10206006.68      3611260.98     10206818.33
      3611066.65     10207086.08
#Sta/Elev= 30
  4163.7  228.33  4181.5  228.05  4285.2  225.78  4299.6  226.11  4358.3  224.44
  4374.1  223.33  4457.9  221.53  4614.7  219.28  4673.5  220.16    4695  218.92
    4738  218.45  4759.8  219.28  4796.7  218.64  4908.4  219.88  4951.4  218.94
  4957.2  217.25  4967.1  216.86  4972.9  214.93  4999.8  212.76  5002.6  212.26
  5005.8  212.76  5010.1  213.77  5015.9  213.37  5090.3  219.25  5161.8   222.1
  5212.1  223.07  5226.8  222.65  5283.2  224.68    5305   224.6    5434  227.79
#Mann= 5 ,-1 , 0
  4163.7      .1       0  4181.5     .16       0  4457.9     .05       0
  4999.8    .035       0  5005.8     .05       0
Bank Sta=4951.4,5090.3
XS Rating Curve= 0 ,0
Exp/Cntr=0.3,0.1

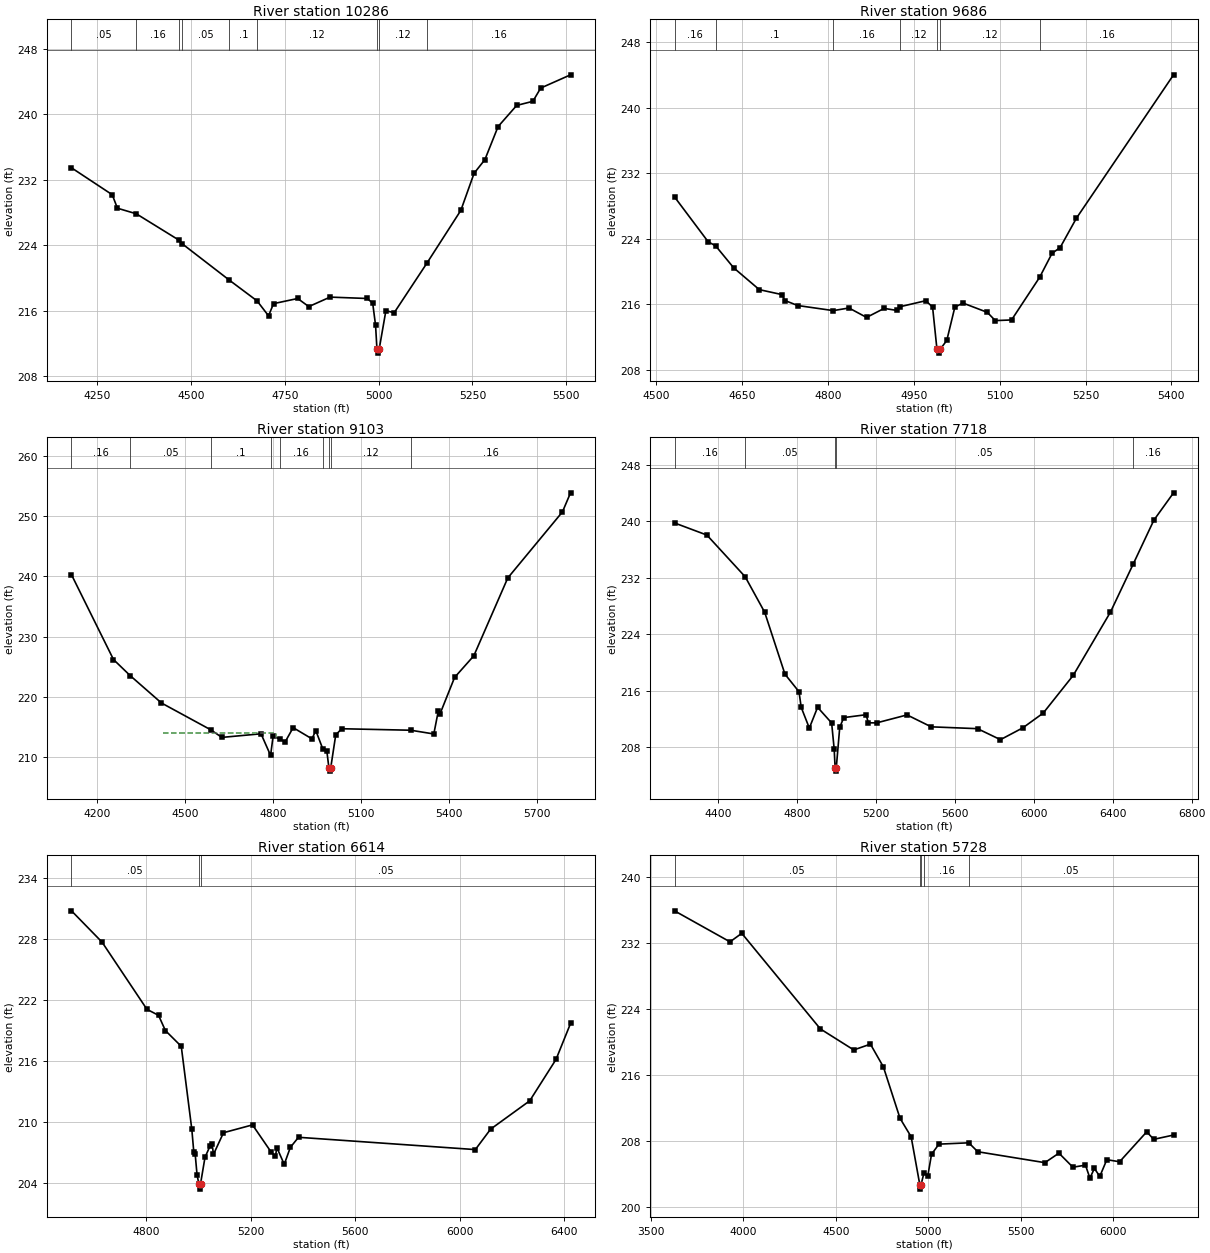
Type RM Length L Ch R = 1 ,10286   ,600,600,600
BEGIN DESCRIPTION:
ALUM CREEK 7.0
END DESCRIPTION:
XS GIS Cut Line= 3
      3611542.12     10205841.63      3611017.93     10206210.69
       3610583.9     10206744.54
#Sta/Elev= 30
  4182.2  233.47  4290.7  230.18  4304.5  228.53  4354.7  227.85  4467.2  224.66
  4476.2  224.21    4603  219.72  4676.4   217.2    4707  215.37  4720.3  216.86
  4784.6  217.49  4814.2   216.5  4870.9  217.66    4970  217.49  4984.4  216.91
    4992  214.23  4995.7  211.31  4998.5  210.81  5001.7  211.31  5019.5  215.99
  5041.8  215.76  5128.3  221.78  5219.2  228.27  5254.4   232.8  5283.2  234.47
  5318.3  238.51  5367.9   241.1    5411   241.6  5431.8  243.22  5511.3  244.84
#Mann= 9 ,-1 , 0
  4182.2     .05       0  4354.7     .16       0  4467.2      .1       0
  4476.2     .05       0    4603      .1       0  4676.4     .12       0
  4995.7     .07       0  5001.7     .12       0  5128.3     .16       0
Bank Sta=4995.7,5001.7
XS Rating Curve= 0 ,0
Exp/Cntr=0.3,0.1

Type RM Length L Ch R = 1 ,9686    ,583,583,583
BEGIN DESCRIPTION:
ALUM CREEK 6.0
END DESCRIPTION:
XS GIS Cut Line= 3
       3610892.1     10205441.65      3610692.11     10205841.64
      3610392.08     10206141.67
#Sta/Elev= 30
  4532.2  229.11  4590.9  223.64  4604.1  223.13  4635.6  220.45  4680.3  217.79
  4719.5  217.19  4725.1  216.46  4747.4  215.85  4809.5  215.23  4836.9  215.55
  4867.6   214.4  4898.3   215.5  4920.7  215.25  4926.4  215.71    4971  216.44
  4982.9  215.66  4990.5  210.54  4993.3  210.04  4996.5  210.54  5007.7  211.59
  5021.8  215.66    5036  216.15  5078.4  215.02  5092.5  214.01  5120.8  214.09
  5169.8  219.29  5191.5  222.22  5205.7  222.93    5234   226.5  5403.7  244.01
#Mann= 7 ,-1 , 0
  4532.2     .16       0  4604.1      .1       0  4809.5     .16       0
  4926.4     .12       0  4990.5     .07       0  4996.5     .12       0
  5169.8     .16       0
Bank Sta=4990.5,4996.5
XS Rating Curve= 0 ,0
Exp/Cntr=0.3,0.1

Type RM Length L Ch R = 1 ,9103    ,1385,1385,1385
BEGIN DESCRIPTION:
ALUM CREEK 5.0
END DESCRIPTION:
XS GIS Cut Line= 3
      3610275.74     10204622.15      3610449.35       10205360.
      3610292.11     10206291.63
#Sta/Elev= 30
  4112.5  240.26  4255.8  226.18  4312.5  223.52  4419.6  218.96  4588.1   214.5
  4625.6  213.25  4759.2  213.85  4791.8  210.26  4800.3   213.4  4823.1     213
  4841.4  212.49  4868.8  214.87    4933  213.01  4946.1  214.38  4969.7  211.37
  4983.7  211.02  4990.9  208.15  4993.6  207.65  4996.9  208.15  5014.1  213.66
  5034.4  214.69  5270.4  214.44  5348.8  213.82  5364.3  217.69  5369.4  217.09
  5419.7  223.21  5485.3   226.8  5601.1  239.72  5787.6  250.69  5815.3  253.86
#Mann= 9 ,-1 , 0
  4112.5     .16       0  4312.5     .05       0  4588.1      .1       0
  4791.8     .12       0  4823.1     .16       0  4969.7     .12       0
  4990.9     .07       0  4996.9     .12       0  5270.4     .16       0
#XS Ineff= 1 ,-1
    4425 4810.23  213.97
Permanent Ineff=
       F
Bank Sta=4990.9,4996.9
XS Rating Curve= 0 ,0
Exp/Cntr=0.3,0.1

Type RM Length L Ch R = 1 ,7718    ,1104,1104,1104
BEGIN DESCRIPTION:
ALUM CREEK 4.0
END DESCRIPTION:
XS GIS Cut Line= 3
      3609895.53     10204187.27      3609638.59      10205256.7
       3609992.1     10206641.63
#Sta/Elev= 30
    4179  239.79  4343.2  238.07  4537.2  232.16    4636  227.13  4738.9  218.34
    4810  215.86  4821.1  213.65  4862.3   210.7  4904.2  213.65  4975.4  211.43
  4988.2  207.75    4993   205.1  4995.7   204.6    4999   205.1  5016.5  210.83
  5037.1  212.19  5150.2   212.6  5161.2  211.45  5203.2  211.44  5357.6  212.57
  5480.1  210.88  5714.9  210.62    5831  209.06  5944.5  210.74  6047.7  212.83
  6200.1  218.19  6388.3  227.14  6503.6  233.95  6608.6  240.19  6708.2  244.06
#Mann= 5 ,-1 , 0
    4179     .16       0  4537.2     .05       0    4993    .035       0
    4999     .05       0  6503.6     .16       0
Bank Sta=4993,4999
XS Rating Curve= 0 ,0
Exp/Cntr=0.3,0.1

Type RM Length L Ch R = 1 ,6614    ,886,886,886
BEGIN DESCRIPTION:
ALUM CREEK 3.0
END DESCRIPTION:
XS GIS Cut Line= 3
      3609214.98     10204235.86      3609110.81     10204951.14
      3609442.11     10206091.67
#Sta/Elev= 30
  4513.2  230.77  4630.2  227.69    4802  221.08  4846.4  220.49  4872.7  218.99
  4933.4  217.44  4973.8  209.28  4981.5  207.02  4986.5  206.89    4994  204.76
  5001.1  203.89  5003.9  203.39  5007.1  203.89  5024.3  206.52  5044.5  207.68
  5051.6  207.86  5056.6   206.8  5095.1  208.94  5206.2  209.71  5278.2  207.01
  5294.1  206.63  5299.3  207.48  5327.7  205.83  5351.1   207.5  5382.3  208.49
  6059.2  207.28  6117.7  209.29  6267.5  212.08  6368.1  216.15  6423.7  219.69
#Mann= 3 ,-1 , 0
  4513.2     .05       0  5001.1     .03       0  5007.1     .05       0
Bank Sta=5001.1,5007.1
XS Rating Curve= 0 ,0
Exp/Cntr=0.3,0.1

Type RM Length L Ch R = 1 ,5728    ,1966,1966,1966
BEGIN DESCRIPTION:
ALUM CREEK 2.1
END DESCRIPTION:
XS GIS Cut Line= 4
      3609223.44     10203669.31       3608504.7     10204294.31
      3608546.36     10205028.68      3608927.29     10205966.11
#Sta/Elev= 30
  3626.8  235.86  3927.1  232.11  3990.7  233.14  4416.1  221.58  4596.6  219.04
  4686.8  219.74  4756.9  216.99    4847  210.77  4907.1  208.54  4954.2  202.71
    4957  202.21  4960.2  202.71  4976.8   204.2  4997.3  203.81  5017.3  206.42
  5057.4  207.65  5218.9  207.81  5267.7  206.73  5630.6  205.41  5706.6  206.56
  5782.2  204.86  5850.2  205.11  5874.3  203.54  5898.4  204.71  5927.8  203.75
  5965.7  205.77  6034.9  205.52  6181.6  209.14  6219.6  208.23  6326.7  208.75
#Mann= 5 ,-1 , 0
  3626.8     .05       0  4954.2     .07       0  4960.2     .05       0
  4976.8     .16       0  5218.9     .05       0
Bank Sta=4954.2,4960.2
XS Rating Curve= 0 ,0
Exp/Cntr=0.3,0.1

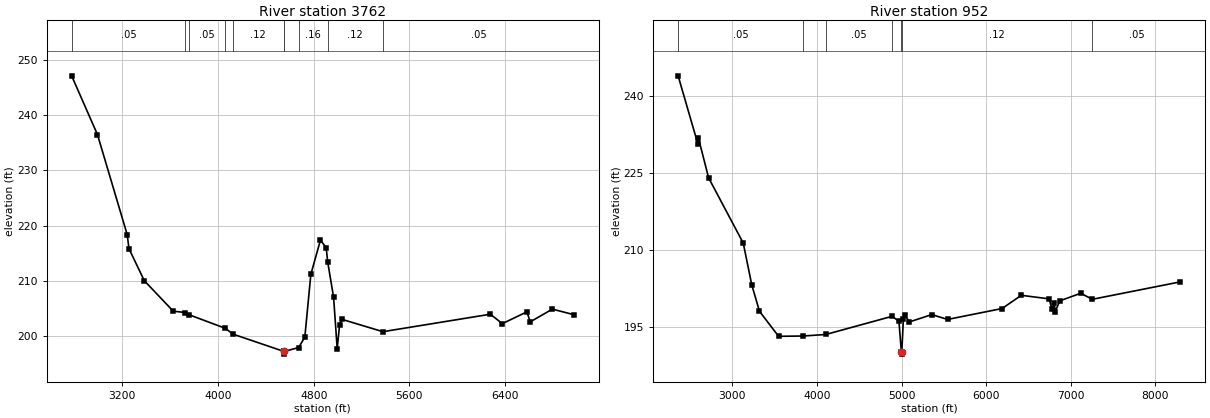
Type RM Length L Ch R = 1 ,3762    ,2810,2810,2810
BEGIN DESCRIPTION:
ALUM CREEK 2.0
END DESCRIPTION:
XS GIS Cut Line= 4
      3608711.24     10202788.11      3607354.52     10203864.62
      3607396.19     10204598.99      3608541.96     10205895.75
#Sta/Elev= 30
  2776.4  247.09  2992.3  236.45  3240.9  218.35  3255.3  215.83  3383.5  210.03
  3625.5  204.51  3726.7  204.27  3757.3  203.87  4061.4  201.41  4124.6  200.36
  4549.2  197.24  4551.9  196.74  4555.2  197.24  4674.1  197.93  4725.6  199.81
  4775.8  211.16  4855.9  217.36    4904  216.02  4916.5  213.47  4966.1  207.01
  4996.1  197.74  5016.2  202.04  5036.2  203.03  5378.2   200.8  6276.9  203.96
  6376.5  202.25  6581.8  204.39  6609.9  202.58  6794.8  204.88  6974.3  203.88
#Mann= 10 ,-1 , 0
  2776.4     .05       0  3726.7     .16       0  3757.3     .05       0
  4061.4     .16       0  4124.6     .12       0  4549.2     .07       0
  4555.2     .12       0  4674.1     .16       0  4916.5     .12       0
  5378.2     .05       0
Bank Sta=4549.2,4555.2
XS Rating Curve= 0 ,0
Exp/Cntr=0.3,0.1

Type RM Length L Ch R = 1 ,952     ,0,0,0
BEGIN DESCRIPTION:
ALUM CREEK 1.0
END DESCRIPTION:
XS GIS Cut Line= 6
      3608833.07     10202503.87       3606541.1     10203022.49
      3606279.76     10203453.53      3606410.77     10203907.49
      3607031.84      10204704.4      3608168.98     10205828.53
#Sta/Elev= 30
  2359.5  243.91  2594.9  230.54    2600  231.78  2719.3  224.06  3129.4  211.32
  3229.9  203.18  3321.4  198.03  3547.4  193.16  3839.7  193.22  4105.4  193.52
  4889.2  197.06  4969.7  196.08  4997.7  190.19  5000.4  189.69  5003.7  190.19
    5022  196.47  5035.9  197.33  5094.3  195.97  5357.2  197.39  5544.6  196.45
  6188.2  198.57  6416.1  201.15    6744  200.46  6779.4  198.45  6807.7  199.62
  6814.8  197.93  6871.3  200.07  7118.8  201.55  7255.3  200.37  8295.3  203.77
#Mann= 7 ,-1 , 0
  2359.5     .05       0  3839.7     .16       0  4105.4     .05       0
  4889.2     .12       0  4997.7     .07       0  5003.7     .12       0
  7255.3     .05       0
Bank Sta=4997.7,5003.7
XS Rating Curve= 0 ,0
Exp/Cntr=0.3,0.1

Chan Stop Cuts=-1
Use User Specified Reach Order=0
Composite Channel Slope=5