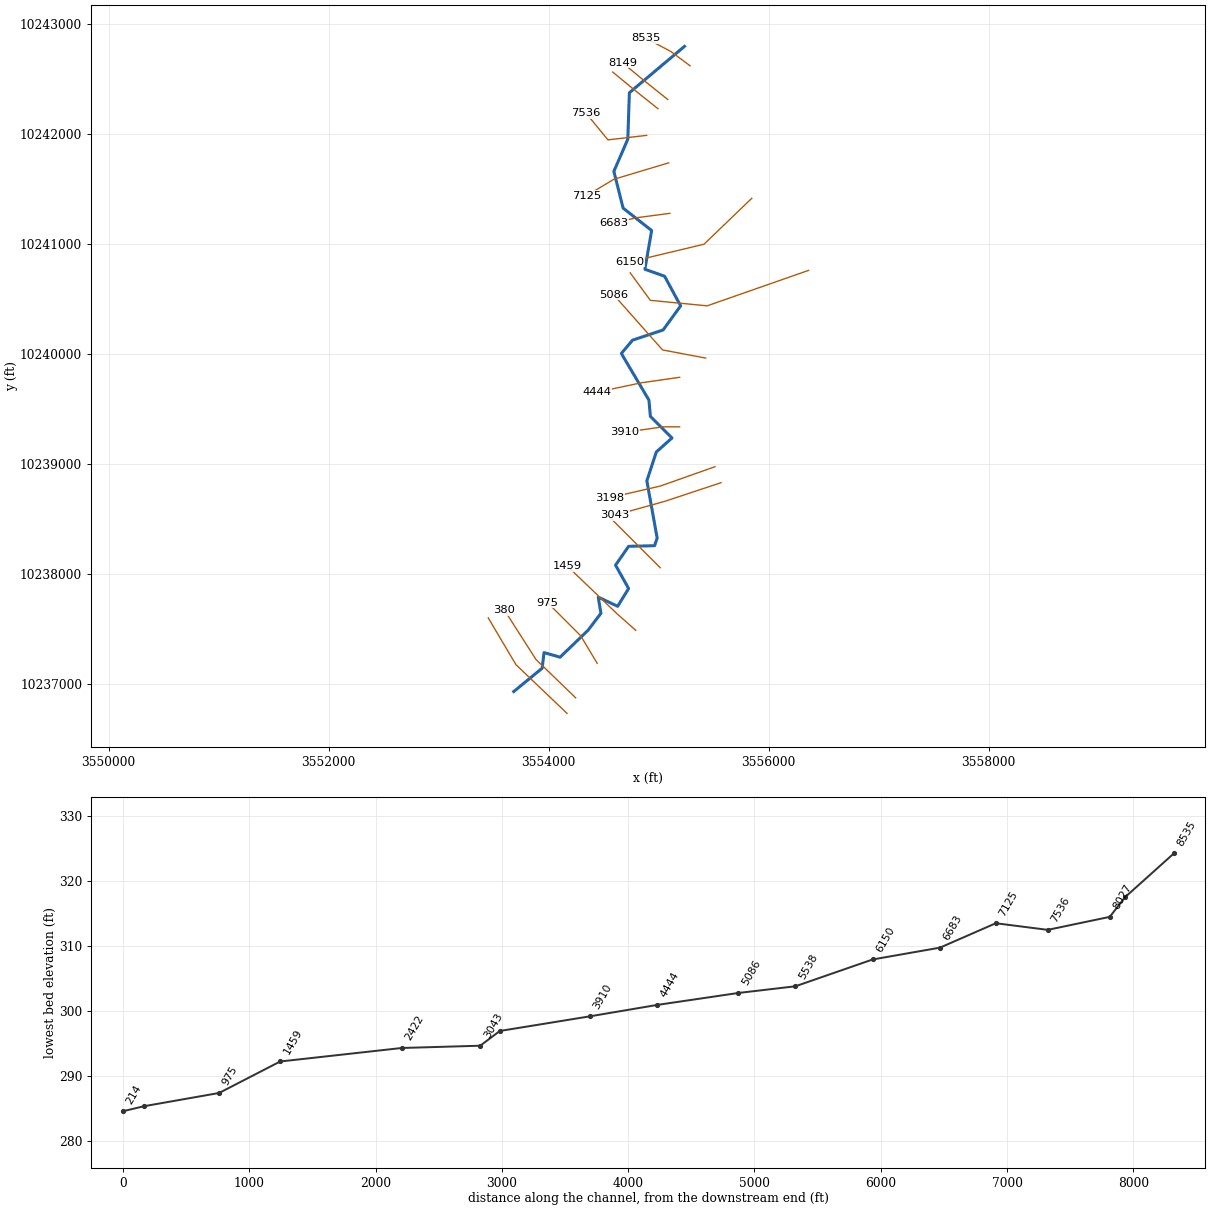
--- AUSTINS CREEK.prj (project) ---

Proj Title=AUSTINS CREEK Base Level Engineering
Current Plan=p01
Default Exp/Contr=0.3,0.1
English Units
Geom File=g01
Flow File=f01
Plan File=p01
Y Axis Title=Elevation
X Axis Title(PF)=Main Channel Distance
X Axis Title(XS)=Station
BEGIN DESCRIPTION:
AUSTINS CREEK
END DESCRIPTION:
DSS Export Rating Curves= 0
DSS Export Rating Curve Sorted= 0
DSS Export Volume Flow Curves= 0
DXF OffsetX= 0
DXF OffsetY= 0
DXF ScaleX= 1
DXF ScaleY= 10

--- AUSTINS CREEK.p01 (plan) ---

Plan Title=Multiple Run
Short Identifier=Multiple
Geom File=g01
Flow File=f01
Subcritical Flow
K Sum by GR= 0
Std Step Tol= 0.01
Critical Tol= 0.01
Num of Std Step Trials= 20
Max Error Tol= 0.3
Flow Tol Ratio= 0.001
Split Flow NTrial= 30
Split Flow Tol= 0.02
Split Flow Ratio= 0.02
Log Output Level= 0
Friction Slope Method= 1
Unsteady Friction Slope Method= 2
Unsteady Bridges Friction Slope Method= 1
Parabolic Critical Depth
Global Vel Dist=  1 , 1 , 1
Global Log Level= 0
CheckData=True
Encroach Param= -1, 0, 0, 0
BEGIN DESCRIPTION:
Multiple Run
END DESCRIPTION:

--- AUSTINS CREEK.f01 (steady flow) ---

Flow Title=Multiple
Number of Profiles=7
Profile Names=10-year,25-year,50-year,1pct_min,100-year,1pct_plu,500-year
River Rch & RM= AUSTINS CREEK,Reach-1,8535
     459     610     731     642     869    1175    1229
Boundary for River Rch & Prof#=AUSTINS CREEK,Reach-1,1
Up Type=0
Dn Type=3
Dn Slope=0.005
Boundary for River Rch & Prof#=AUSTINS CREEK,Reach-1,2
Up Type=0
Dn Type=3
Dn Slope=0.005
Boundary for River Rch & Prof#=AUSTINS CREEK,Reach-1,3
Up Type=0
Dn Type=3
Dn Slope=0.005
Boundary for River Rch & Prof#=AUSTINS CREEK,Reach-1,4
Up Type=0
Dn Type=3
Dn Slope=0.005
Boundary for River Rch & Prof#=AUSTINS CREEK,Reach-1,5
Up Type=0
Dn Type=3
Dn Slope=0.005
Boundary for River Rch & Prof#=AUSTINS CREEK,Reach-1,6
Up Type=0
Dn Type=3
Dn Slope=0.005
Boundary for River Rch & Prof#=AUSTINS CREEK,Reach-1,7
Up Type=0
Dn Type=3
Dn Slope=0.005

--- AUSTINS CREEK.g01 (geometry) ---

Geom Title=Existing Conditions
Program Version=4.10

River Reach=AUSTINS CREEK   ,Reach-1
Reach XY= 30
      3555235.65     10242800.48      3554734.61     10242379.06
       3554720.5     10241956.97      3554593.55       10241664.
      3554677.75     10241330.01      3554937.19     10241126.39
      3554875.55     10240774.06      3555054.67     10240711.02
       3555200.8     10240441.25      3555041.75     10240222.46
      3554763.03     10240129.21      3554661.77     10240008.29
      3554912.64     10239583.82      3554925.66     10239436.25
      3555121.84     10239240.07      3554979.48     10239112.46
      3554893.54     10238850.31      3554987.29     10238330.34
      3554963.86      10238260.9      3554727.75     10238254.82
      3554608.82     10238083.82      3554727.75     10237871.14
      3554627.92     10237709.68       3554451.7     10237793.02
      3554476.01     10237646.31      3554358.82      10237491.8
      3554104.48     10237247.01      3553958.65     10237288.68
      3553941.29     10237146.31       3553683.4     10236934.76

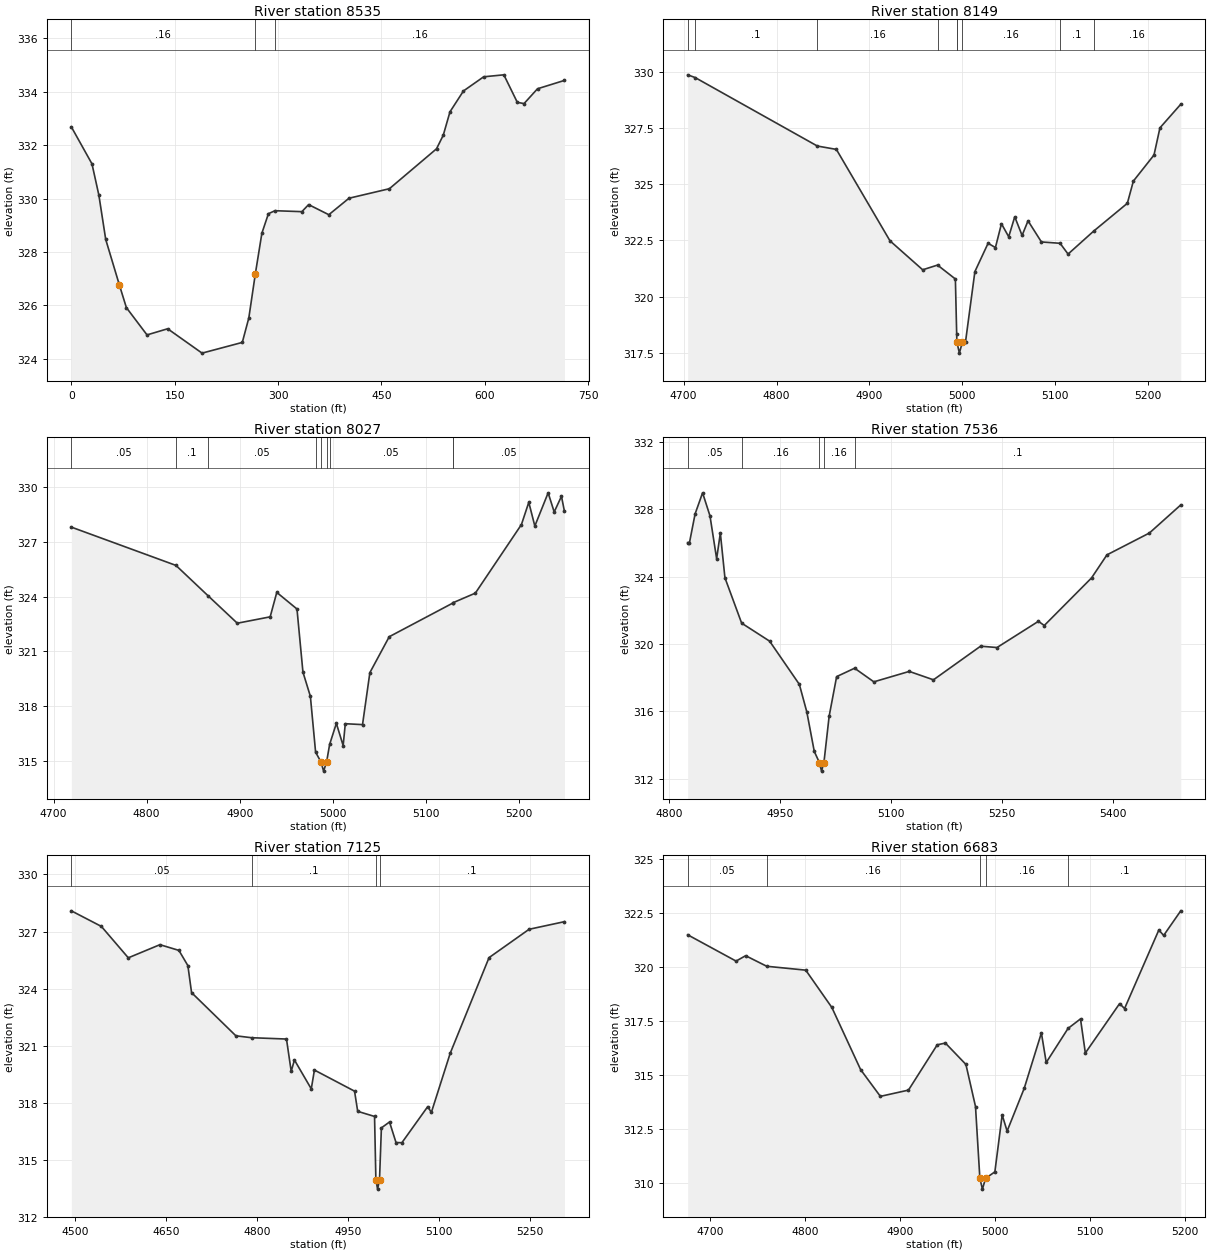
Type RM Length L Ch R = 1 ,8535    ,386,386,386
BEGIN DESCRIPTION:
UNT072 IN GIBB 18.0
END DESCRIPTION:
XS GIS Cut Line= 3
      3555286.74     10242623.84      3555114.99     10242752.16
      3554886.87     10242873.78
#Sta/Elev= 30
       0332.684329.95166331.299739.93555330.131949.91943328.467569.88721326.7505
79.87109 325.917109.8228 324.895139.7744325.1249189.6938324.2128248.0704324.6138
257.5453325.5312267.0203327.1858276.4953 328.703285.9702329.4324295.4452329.5447
 334.517 329.509344.2849329.7731373.5887 329.395402.8925330.0118461.5002 330.368
529.8757331.8628539.6437332.3702549.4116333.2479568.9475334.0277598.2513334.5576
627.5551334.6319 647.091333.6015656.8589333.5556676.3948334.1099715.4666 334.423
#Mann= 3 ,-1 , 0
       0     .16       0267.0203     .07       0295.4452     .16       0
Bank Sta=69.88721,267.0203
XS Rating Curve= 0 ,0
Exp/Cntr=0.3,0.1

Type RM Length L Ch R = 1 ,8149    ,122,122,122
BEGIN DESCRIPTION:
UNT072 IN GIBB 17.1
END DESCRIPTION:
XS GIS Cut Line= 3
      3555083.54     10242317.76      3554852.51     10242502.31
       3554671.2     10242651.97
#Sta/Elev= 30
  4704.3  329.87  4712.3  329.75  4843.9   326.7  4864.4  326.55  4922.1  322.48
  4957.3  321.19  4973.3   321.4  4992.5  320.78  4993.9  318.33  4994.1  317.98
  4996.8  317.48  5000.1  317.98  5003.4  317.98  5013.5  321.11  5027.7  322.37
  5035.6  322.18  5042.1  323.24  5049.9  322.66  5056.4  323.55  5064.3  322.72
  5070.7  323.37  5085.1  322.43  5105.2  322.37  5113.8  321.89  5141.3  322.91
  5177.6  324.15  5184.1  325.14  5206.3   326.3  5212.7  327.51  5235.1  328.56
#Mann= 9 ,-1 , 0
  4704.3     .08       0  4712.3      .1       0  4843.9     .16       0
  4973.3      .1       0  4993.9     .16       0  4994.1     .07       0
  5000.1     .16       0  5105.2      .1       0  5141.3     .16       0
Bank Sta=4994.1,5000.1
XS Rating Curve= 0 ,0
Exp/Cntr=0.3,0.1

Type RM Length L Ch R = 1 ,8027    ,491,491,491
BEGIN DESCRIPTION:
UNT072 IN GIBB 17.0
END DESCRIPTION:
XS GIS Cut Line= 3
      3554994.57     10242233.83       3554763.5     10242418.42
      3554583.08     10242567.34
#Sta/Elev= 30
  4719.1  327.82  4831.5  325.72  4866.1  324.05  4897.4  322.55  4932.7   322.9
  4939.8  324.24  4961.5  323.33  4967.9  319.87  4975.9  318.54  4981.5  315.48
  4987.3  314.94  4990.1  314.44  4993.3  314.94  4996.6  315.91  5003.8  317.06
  5011.1  315.84  5013.4  317.04  5031.9  316.99  5039.8  319.84  5060.6  321.81
  5128.7  323.65  5129.4  323.68  5153.1   324.2  5202.6  327.96  5210.5  329.18
    5217  327.88  5231.3   329.7  5237.8  328.65  5245.6  329.51  5248.8  328.69
#Mann= 9 ,-1 , 0
  4719.1     .05       0  4831.5      .1       0  4866.1     .05       0
  4981.5      .1       0  4987.3     .04       0  4993.3      .1       0
  4996.6     .05       0  5128.7      .1       0  5129.4     .05       0
Bank Sta=4987.3,4993.3
XS Rating Curve= 0 ,0
Exp/Cntr=0.3,0.1

Type RM Length L Ch R = 1 ,7536    ,411,411,411
BEGIN DESCRIPTION:
UNT072 IN GIBB 16.0
END DESCRIPTION:
XS GIS Cut Line= 3
      3554892.12     10241991.64      3554539.65     10241950.53
      3554342.08     10242191.67
#Sta/Elev= 30
  4825.4  326.03  4827.9  326.03  4835.5  327.74  4845.6  328.99  4855.6  327.62
  4864.6  325.07  4869.6   326.6  4875.8  323.94  4898.4  321.24  4936.2  320.17
  4976.4   317.6  4986.5  315.96  4996.6  313.61  5003.6  312.94  5006.4  312.44
  5009.6  312.94  5016.7  315.71  5026.8  318.06  5051.1  318.56  5077.1  317.75
    5125  318.37  5157.7  317.87  5221.4  319.87  5243.6  319.79  5299.6  321.35
  5307.5   321.1  5371.4  323.93  5392.2   325.3  5449.6   326.6    5492  328.27
#Mann= 5 ,-1 , 0
  4825.4     .05       0  4898.4     .16       0  5003.6     .07       0
  5009.6     .16       0  5051.1      .1       0
Bank Sta=5003.6,5009.6
XS Rating Curve= 0 ,0
Exp/Cntr=0.3,0.1

Type RM Length L Ch R = 1 ,7125    ,442,442,442
BEGIN DESCRIPTION:
UNT072 IN GIBB 15.0
END DESCRIPTION:
XS GIS Cut Line= 3
      3555092.15     10241741.66      3554592.11     10241591.64
      3554342.11     10241441.65
#Sta/Elev= 30
  4493.5  328.09  4543.1  327.27  4587.5  325.62  4639.7  326.31    4671  326.01
  4685.8  325.21  4691.9  323.79    4765  321.52  4790.8  321.42  4848.5  321.35
  4856.3  319.65  4861.6  320.25  4889.4  318.73  4894.6  319.72  4960.8  318.61
    4966  317.55  4993.8  317.28    4996  313.96  4998.8  313.46    5002  313.96
  5005.1  316.68  5018.5  316.99  5029.2  315.91  5038.9   315.9  5081.6   317.8
  5087.5  317.49  5118.6   320.6  5182.7  325.63  5248.8  327.12  5307.1  327.52
#Mann= 4 ,-1 , 0
  4493.5     .05       0  4790.8      .1       0    4996     .07       0
    5002      .1       0
Bank Sta=4996,5002
XS Rating Curve= 0 ,0
Exp/Cntr=0.3,0.1

Type RM Length L Ch R = 1 ,6683    ,533,533,533
BEGIN DESCRIPTION:
UNT072 IN GIBB 14.0
END DESCRIPTION:
XS GIS Cut Line= 3
       3555102.7     10241282.63      3554792.11     10241241.64
      3554592.15     10241191.65
#Sta/Elev= 30
  4676.1  321.49  4727.1  320.27  4737.2  320.52  4759.4  320.03  4800.5  319.85
    4828  318.12  4858.3  315.24  4879.1     314  4908.7  314.29    4939  316.39
  4947.6  316.47  4969.2  315.48  4979.3  313.53  4983.9   310.2  4986.6   309.7
  4989.9   310.2  4999.7   310.5  5007.4  313.14  5012.6  312.39  5030.6  314.37
  5048.7  316.94  5053.8  315.57  5076.8  317.15  5089.9  317.59    5095  316.01
  5131.1   318.3  5136.3  318.07  5172.4  321.71  5177.5  321.46  5195.5   322.6
#Mann= 5 ,-1 , 0
  4676.1     .05       0  4759.4     .16       0  4983.9     .07       0
  4989.9     .16       0  5076.8      .1       0
Bank Sta=4983.9,4989.9
XS Rating Curve= 0 ,0
Exp/Cntr=0.3,0.1

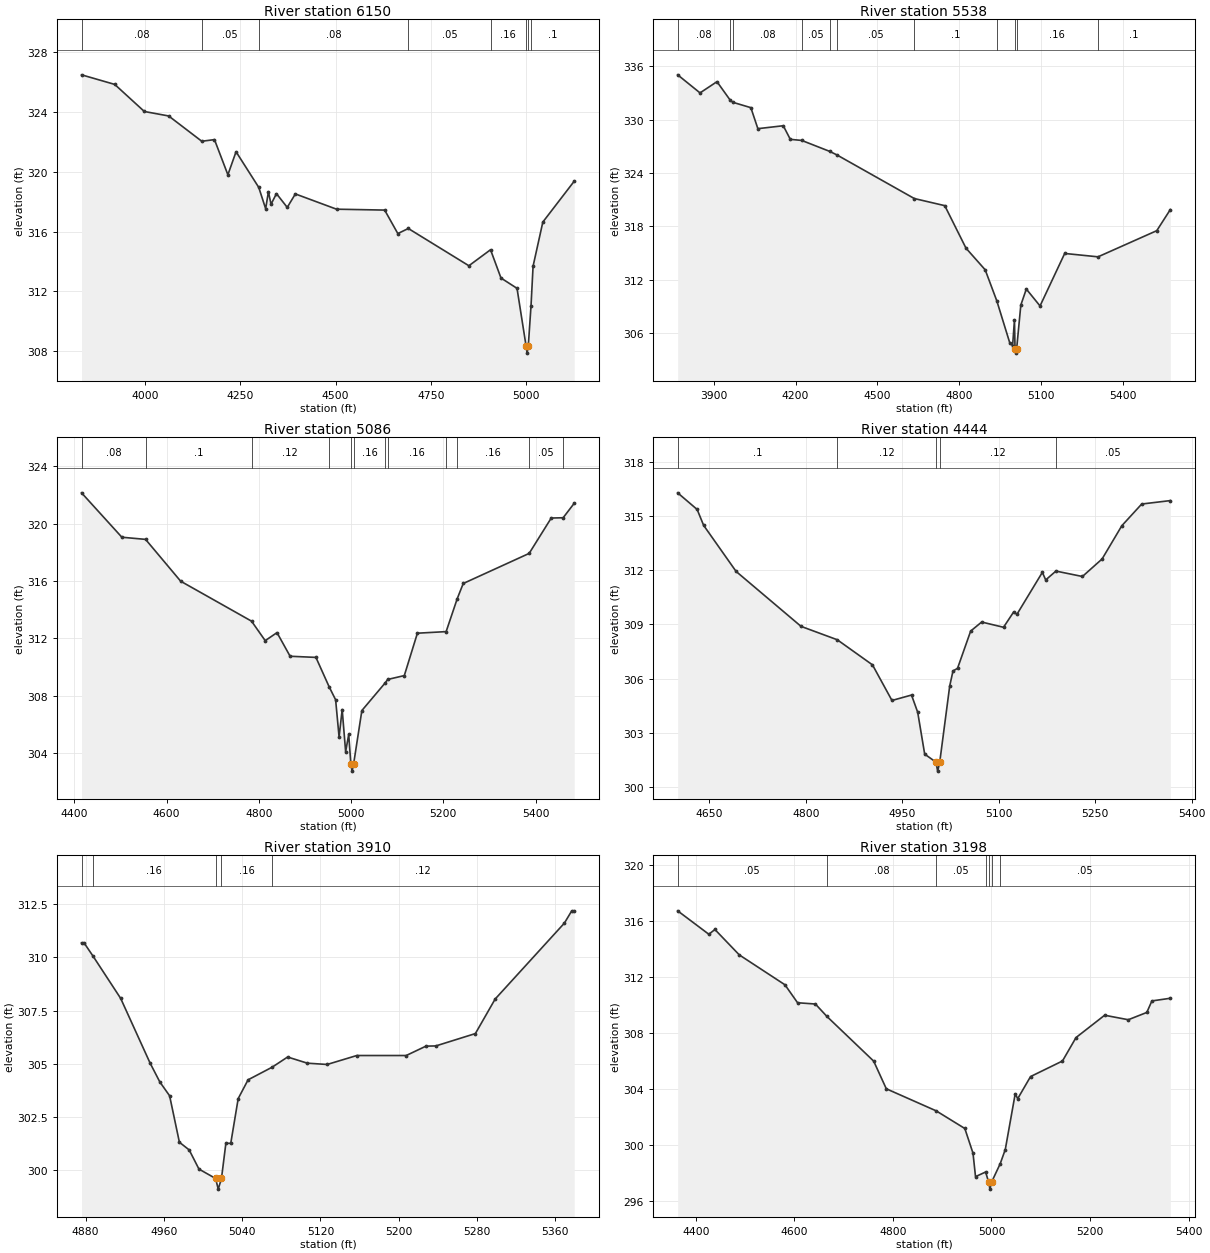
Type RM Length L Ch R = 1 ,6150    ,612,612,612
BEGIN DESCRIPTION:
UNT072 IN GIBB 13.0
END DESCRIPTION:
XS GIS Cut Line= 3
      3555847.44      10241419.3      3555413.18      10241001.7
      3554742.07     10240841.63
#Sta/Elev= 30
  3833.6  326.48  3920.6  325.84  3998.3  324.03  4062.2  323.73    4149  322.04
  4182.3  322.15  4217.5   319.8  4238.9  321.34  4298.4  318.96  4316.6  317.53
  4323.8  318.67  4330.7  317.83  4344.9  318.54  4373.2  317.62  4394.5  318.52
  4502.5   317.5  4628.8  317.44  4663.3  315.87  4690.8  316.21  4849.7  313.72
  4906.5  314.79  4933.9   312.9    4976  312.21  4999.6  308.38  5002.4  307.88
  5005.6  308.38  5012.7  311.04  5018.1  313.69  5043.7  316.64    5126  319.37
#Mann= 8 ,-1 , 0
  3833.6     .08       0    4149     .05       0  4298.4     .08       0
  4690.8     .05       0  4906.5     .16       0  4999.6     .07       0
  5005.6     .16       0  5012.7      .1       0
Bank Sta=4999.6,5005.6
XS Rating Curve= 0 ,0
Exp/Cntr=0.3,0.1

Type RM Length L Ch R = 1 ,5538    ,452,452,452
BEGIN DESCRIPTION:
UNT072 IN GIBB 12.0
END DESCRIPTION:
XS GIS Cut Line= 4
      3556363.92     10240763.92      3555442.11     10240441.64
      3554925.26     10240491.61      3554742.12     10240741.63
#Sta/Elev= 30
  3767.8  335.02  3849.8  332.99  3911.9  334.25    3960  332.19  3970.4  331.93
  4036.1  331.33  4061.8  328.97  4154.9   329.3  4180.7  327.77  4222.5  327.65
  4325.7  326.41  4351.6  326.02  4635.2  321.12  4746.8  320.32  4824.7  315.54
    4895  313.11  4937.7  309.61  4985.4  304.87  4995.5  304.59  5002.3  307.51
  5004.3  304.25  5007.1  303.75  5010.3  304.25  5025.6  309.15  5045.7  310.95
    5096  309.05  5186.4  314.95  5308.5  314.57  5523.9  317.51  5573.5  319.88
#Mann= 11 ,-1 , 0
  3767.8     .08       0    3960     .05       0  3970.4     .08       0
  4222.5     .05       0  4325.7     .08       0  4351.6     .05       0
  4635.2      .1       0  4937.7     .16       0  5004.3     .07       0
  5010.3     .16       0  5308.5      .1       0
Bank Sta=5004.3,5010.3
XS Rating Curve= 0 ,0
Exp/Cntr=0.3,0.1

Type RM Length L Ch R = 1 ,5086    ,642,642,642
BEGIN DESCRIPTION:
UNT072 IN GIBB 11.0
END DESCRIPTION:
XS GIS Cut Line= 3
      3555427.96     10239966.73      3555036.15     10240040.65
      3554592.09     10240541.66
#Sta/Elev= 30
  4415.6  322.15    4503  319.05  4554.4   318.9  4630.5  315.98  4784.2  313.19
  4813.8  311.83  4839.4  312.39  4867.8  310.74  4923.8  310.66  4952.4  308.61
  4966.5   307.7    4974   305.1  4980.7  307.02  4988.2  304.08  4994.9  305.28
  4999.5  303.22  5002.2  302.72  5005.5  303.22  5023.4  306.95  5074.5   308.9
  5079.3  309.12  5115.4  309.39  5143.8  312.35  5206.1  312.46  5230.3  314.77
  5243.2  315.82  5386.1  317.92    5434  320.39  5459.8  320.41  5483.8  321.42
#Mann= 12 ,-1 , 0
  4415.6     .08       0  4554.4      .1       0  4784.2     .12       0
  4952.4     .16       0  4999.5     .07       0  5005.5     .16       0
  5074.5     .12       0  5079.3     .16       0  5206.1      .1       0
  5230.3     .16       0  5386.1     .05       0  5459.8      .1       0
Bank Sta=4999.5,5005.5
XS Rating Curve= 0 ,0
Exp/Cntr=0.3,0.1

Type RM Length L Ch R = 1 ,4444    ,534,534,534
BEGIN DESCRIPTION:
UNT072 IN GIBB 9.0
END DESCRIPTION:
XS GIS Cut Line= 3
      3555192.06     10239791.64      3554842.11     10239741.64
      3554438.31     10239656.44
#Sta/Elev= 30
  4600.6  316.28  4630.9  315.36    4641  314.48  4691.5  311.93  4792.5  308.89
  4848.8  308.15  4903.6  306.76  4933.9  304.79  4964.3  305.09  4973.9  304.14
  4984.8  301.82  5002.2  301.38    5005  300.88  5008.2  301.38  5023.7  305.59
  5028.8  306.42  5035.9  306.57  5056.3  308.63  5073.4  309.13  5107.4  308.84
  5123.2  309.69  5128.3  309.56  5167.8  311.88    5173  311.46  5188.9  311.95
  5230.1  311.65  5260.7  312.62  5291.4  314.46  5322.3  315.66  5366.8  315.85
#Mann= 5 ,-1 , 0
  4600.6      .1       0  4848.8     .12       0  5002.2     .07       0
  5008.2     .12       0  5188.9     .05       0
Bank Sta=5002.2,5008.2
XS Rating Curve= 0 ,0
Exp/Cntr=0.3,0.1

Type RM Length L Ch R = 1 ,3910    ,712,712,712
BEGIN DESCRIPTION:
UNT072 IN GIBB 8.0
END DESCRIPTION:
XS GIS Cut Line= 3
      3555192.09     10239341.64      3555042.11     10239341.64
      3554692.15     10239291.65
#Sta/Elev= 30
  4875.9  310.68  4878.4  310.68  4887.7  310.05  4915.9  308.07  4945.9  305.04
  4955.9  304.15  4965.9   303.5  4975.9  301.32  4985.9  300.96  4995.9  300.06
  5012.9  299.62  5015.6  299.12  5018.9  299.62  5023.4  301.27  5028.4  301.27
    5036  303.37  5046.1  304.25  5070.6  304.84  5086.5  305.32  5106.7  305.03
  5126.9  304.97  5157.2  305.39  5207.7  305.39  5227.9  305.83    5238  305.84
  5278.4  306.42  5298.6  308.04  5369.3   311.6  5376.9  312.18  5379.4  312.18
#Mann= 5 ,-1 , 0
  4875.9      .1       0  4887.7     .16       0  5012.9     .07       0
  5018.9     .16       0  5070.6     .12       0
Bank Sta=5012.9,5018.9
XS Rating Curve= 0 ,0
Exp/Cntr=0.3,0.1

Type RM Length L Ch R = 1 ,3198    ,155,155,155
BEGIN DESCRIPTION:
UNT072 IN GIBB 7.0
END DESCRIPTION:
XS GIS Cut Line= 3
      3555513.38     10238978.93      3555016.39     10238803.14
      3554555.59     10238697.13
#Sta/Elev= 30
    4363   316.7  4426.3  315.03  4438.6  315.37  4488.1  313.56  4580.8  311.43
  4606.4  310.15  4642.6  310.06  4665.8  309.18  4760.9  305.99  4786.5  304.02
  4887.6  302.45  4945.9  301.19  4962.5  299.43  4967.6  297.76  4988.1  298.09
  4994.2  297.37  4996.9  296.87  5000.2  297.37  5017.7  298.68    5028  299.69
  5048.1  303.65  5053.3  303.32  5079.3  304.89  5144.1     306  5171.6  307.67
  5229.7  309.26  5277.7  308.94  5315.3  309.46  5325.6  310.28    5363  310.47
#Mann= 7 ,-1 , 0
    4363     .05       0  4665.8     .08       0  4887.6     .05       0
  4988.1     .12       0  4994.2     .07       0  5000.2     .12       0
  5017.7     .05       0
Bank Sta=4994.2,5000.2
XS Rating Curve= 0 ,0
Exp/Cntr=0.3,0.1

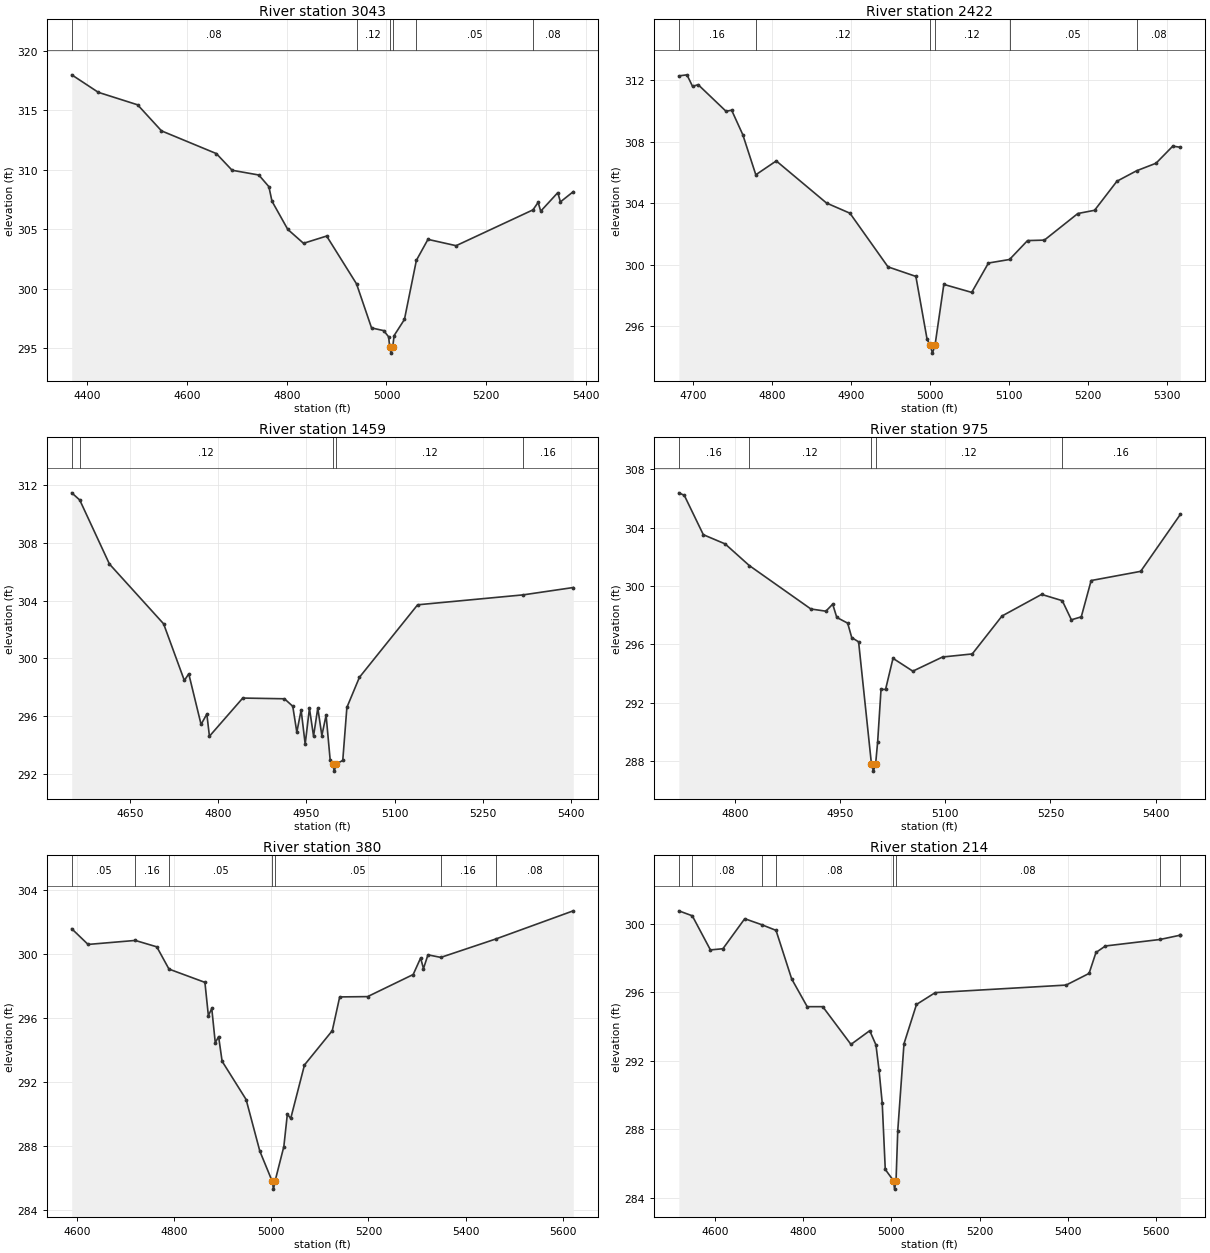
Type RM Length L Ch R = 1 ,3043    ,621,621,621
BEGIN DESCRIPTION:
UNT072 IN GIBB 6.0
END DESCRIPTION:
XS GIS Cut Line= 3
      3555567.57      10238833.5      3555057.62     10238664.25
       3554605.6     10238538.81
#Sta/Elev= 30
  4368.5  317.99  4421.8  316.52  4500.7  315.47  4548.6  313.28  4658.7  311.37
  4690.3  309.97  4743.9  309.57  4764.1  308.59  4770.3  307.37    4802     305
  4833.6  303.83    4880  304.44    4940  300.42  4970.1  296.72  4994.5  296.49
  5004.4  295.97  5006.6   295.1  5009.3   294.6  5012.6   295.1  5015.3  296.07
  5036.1  297.43  5060.1   302.4  5083.3  304.16  5139.8  303.63    5294  306.64
  5304.4  307.27  5309.6  306.53  5343.9  308.09  5349.1  307.31  5374.9  308.17
#Mann= 6 ,-1 , 0
  4368.5     .08       0    4940     .12       0  5006.6     .07       0
  5012.6     .12       0  5060.1     .05       0    5294     .08       0
Bank Sta=5006.6,5012.6
XS Rating Curve= 0 ,0
Exp/Cntr=0.3,0.1

Type RM Length L Ch R = 1 ,2422    ,963,963,963
BEGIN DESCRIPTION:
UNT072 IN GIBB 5.0
END DESCRIPTION:
XS GIS Cut Line= 3
      3555015.25      10238060.2      3554865.25      10238210.2
      3554566.16     10238509.29
#Sta/Elev= 30
  4681.8  312.28  4692.1  312.35  4699.2   311.6  4706.3  311.71  4741.6  309.98
  4748.7  310.05  4762.8  308.46  4779.3  305.85  4805.2  306.75  4868.9  304.01
  4898.5  303.35  4946.7  299.86    4982  299.24  4996.2  295.15  5000.2  294.75
    5003  294.25  5006.2  294.75  5017.4  298.72  5052.7   298.2  5073.9  300.11
  5100.6  300.34  5123.4  301.57  5144.7   301.6  5187.1  303.33  5208.3  303.54
  5236.6  305.43  5261.5  306.11  5286.1   306.6  5307.3  307.71  5316.9  307.64
#Mann= 6 ,-1 , 0
  4681.8     .16       0  4779.3     .12       0  5000.2     .07       0
  5006.2     .12       0  5100.6     .05       0  5261.5     .08       0
Bank Sta=5000.2,5006.2
XS Rating Curve= 0 ,0
Exp/Cntr=0.3,0.1

Type RM Length L Ch R = 1 ,1459    ,484,484,484
BEGIN DESCRIPTION:
UNT072 IN GIBB 3.0
END DESCRIPTION:
XS GIS Cut Line= 3
      3554792.14     10237491.62      3554623.43     10237640.84
      3554171.19     10238074.22
#Sta/Elev= 30
  4551.6  311.48  4565.2  310.98  4615.6  306.54  4707.6  302.39  4742.8  298.46
  4750.3  298.92  4771.2  295.41    4781  296.13  4785.4  294.59    4842  297.24
  4912.8  297.19  4926.9  296.67  4933.8  294.87  4941.1  296.41    4948  294.04
  4955.2  296.53  4962.2   294.6  4969.4  296.55  4976.3  294.64  4983.5  296.05
  4990.5  292.91  4994.7  292.67  4997.4  292.17  5000.7  292.67  5011.8  292.91
  5018.8  296.59  5040.1  298.68  5138.9  303.71  5318.2   304.4  5403.2  304.91
#Mann= 5 ,-1 , 0
  4551.6     .16       0  4565.2     .12       0  4994.7     .07       0
  5000.7     .12       0  5318.2     .16       0
Bank Sta=4994.7,5000.7
XS Rating Curve= 0 ,0
Exp/Cntr=0.3,0.1

Type RM Length L Ch R = 1 ,975     ,595,595,595
BEGIN DESCRIPTION:
UNT072 IN GIBB 2.0
END DESCRIPTION:
XS GIS Cut Line= 3
      3554442.11     10237191.64      3554292.11     10237441.64
      3553992.12     10237741.63
#Sta/Elev= 30
  4719.6  306.39  4727.4  306.22  4754.6  303.52  4785.7  302.89  4820.1  301.41
  4908.1  298.43  4929.5  298.28  4939.2  298.76  4945.1  297.85  4960.6  297.46
  4966.4  296.47  4976.2  296.18  4994.5  287.82  4997.3  287.32  5000.5  287.82
  5003.4  289.33  5008.2  292.92  5014.7  292.92  5025.3  295.05  5053.6  294.17
    5096  295.14  5138.4  295.35  5180.9  297.95  5237.4  299.43  5266.9     299
  5279.9  297.69    5294  297.89  5308.1  300.38  5378.8  301.01  5435.4  304.91
#Mann= 5 ,-1 , 0
  4719.6     .16       0  4820.1     .12       0  4994.5     .07       0
  5000.5     .12       0  5266.9     .16       0
Bank Sta=4994.5,5000.5
XS Rating Curve= 0 ,0
Exp/Cntr=0.3,0.1

Type RM Length L Ch R = 1 ,380     ,166,166,166
BEGIN DESCRIPTION:
UNT072 IN GIBB 2.1
END DESCRIPTION:
XS GIS Cut Line= 3
      3554246.04     10236877.87      3553885.46     10237226.17
      3553599.15     10237673.69
#Sta/Elev= 30
    4589  301.55  4622.6  300.57  4719.8  300.82  4764.1  300.42  4789.2  299.03
  4863.2   298.2  4870.3  296.12  4877.3  296.57  4884.5  294.43  4891.4  294.81
  4898.6  293.27    4948  290.88  4976.3  287.65  5001.6  285.78  5004.4  285.28
  5007.6  285.78  5025.7  287.94  5032.9  289.96  5039.9   289.7  5068.2  293.04
  5125.4  295.18  5140.7  297.29  5198.2  297.31    5292  298.69  5307.3  299.72
  5313.2  299.06  5322.4  299.92  5348.9  299.76  5462.1  300.91  5621.6  302.67
#Mann= 7 ,-1 , 0
    4589     .05       0  4719.8     .16       0  4789.2     .05       0
  5001.6     .04       0  5007.6     .05       0  5348.9     .16       0
  5462.1     .08       0
Bank Sta=5001.6,5007.6
XS Rating Curve= 0 ,0
Exp/Cntr=0.3,0.1

Type RM Length L Ch R = 1 ,214     ,0,0,0
BEGIN DESCRIPTION:
UNT072 IN GIBB 1.0
END DESCRIPTION:
XS GIS Cut Line= 3
      3554167.77     10236736.14      3553703.35     10237178.86
       3553451.6     10237604.22
#Sta/Elev= 30
  4518.5  300.74    4549  300.45  4590.1  298.46  4618.4  298.53  4667.8  300.28
  4706.4  299.93  4738.7   299.6  4774.1  296.77  4809.3  295.15  4844.5  295.15
  4908.4  292.95  4950.9  293.75    4965  292.92  4971.9  291.47  4979.2  289.53
  4986.1  285.66  5004.5  285.01  5007.2  284.51  5010.5  285.01  5014.4  287.92
  5028.5  292.99  5056.8  295.28  5099.3  295.97  5395.8  296.41  5447.7  297.09
  5463.3  298.31  5484.7  298.69  5608.6  299.07  5654.2  299.32  5654.4  299.32
#Mann= 8 ,-1 , 0
  4518.5      .1       0    4549     .08       0  4706.4     .16       0
  4738.7     .08       0  5004.5     .07       0  5010.5     .08       0
  5608.6     .05       0  5654.2     .08       0
Bank Sta=5004.5,5010.5
XS Rating Curve= 0 ,0
Exp/Cntr=0.3,0.1

Chan Stop Cuts=-1
Use User Specified Reach Order=0
Composite Channel Slope=5