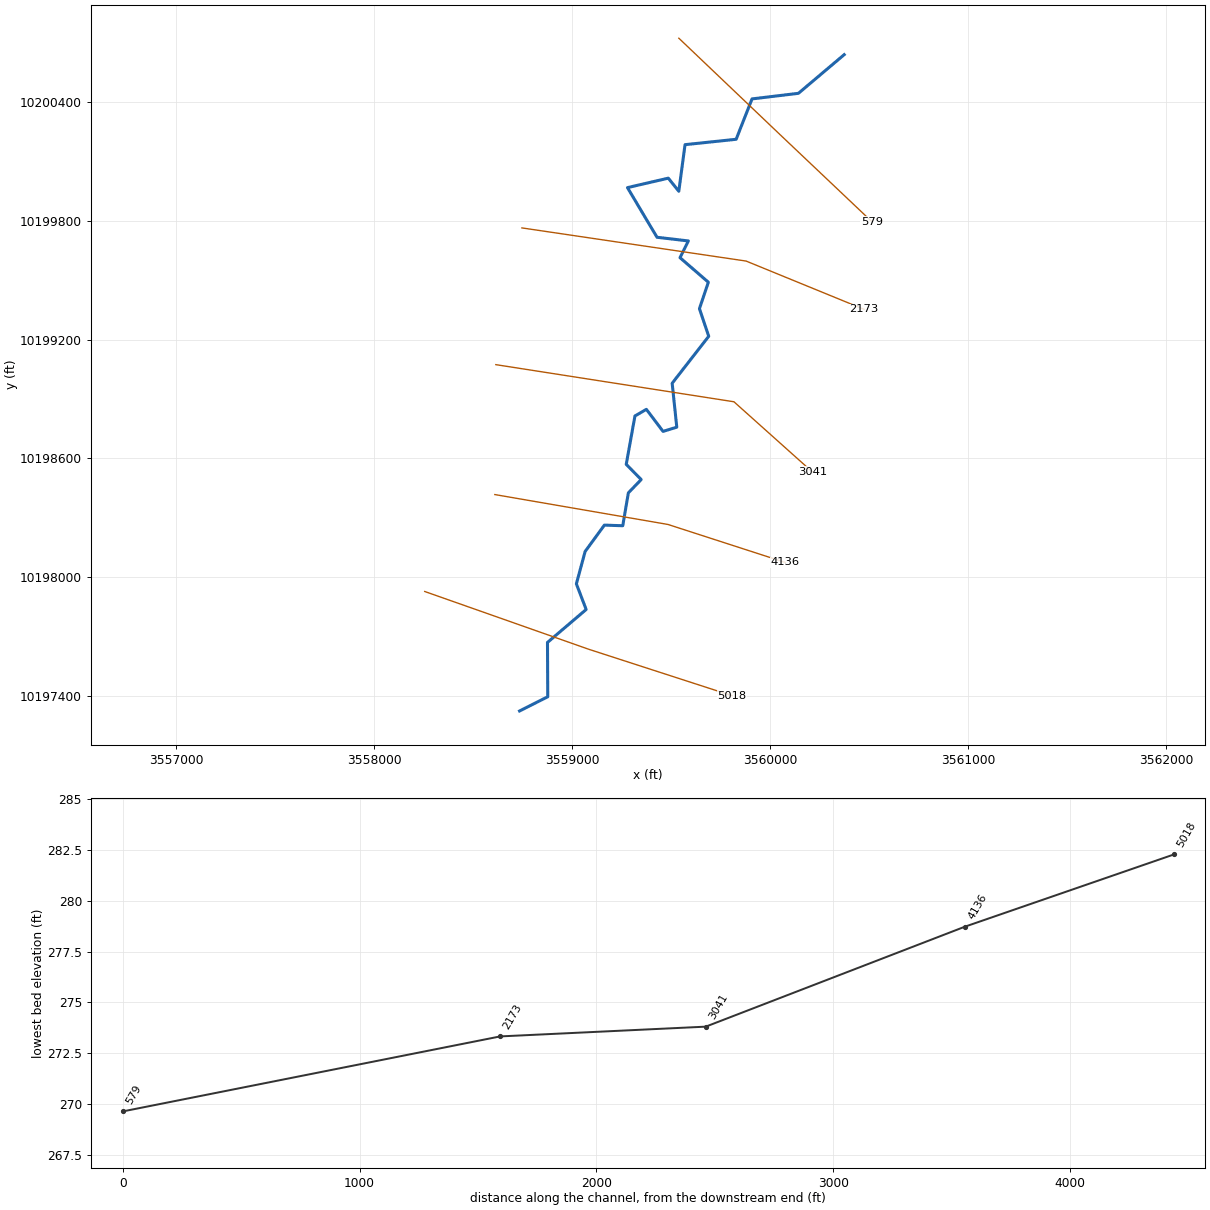
--- BEE CREEK TRIB 3.prj (project) ---

Proj Title=BEE CREEK TRIB 3 Base Level Engineering
Current Plan=p01
Default Exp/Contr=0.3,0.1
English Units
Geom File=g01
Flow File=f01
Plan File=p01
Y Axis Title=Elevation
X Axis Title(PF)=Main Channel Distance
X Axis Title(XS)=Station
BEGIN DESCRIPTION:
BEE CREEK TRIB 3
END DESCRIPTION:
DSS Export Rating Curves= 0
DSS Export Rating Curve Sorted= 0
DSS Export Volume Flow Curves= 0
DXF OffsetX= 0
DXF OffsetY= 0
DXF ScaleX= 1
DXF ScaleY= 10

--- BEE CREEK TRIB 3.p01 (plan) ---

Plan Title=Multiple Run
Short Identifier=Multiple
Geom File=g01
Flow File=f01
Subcritical Flow
K Sum by GR= 0
Std Step Tol= 0.01
Critical Tol= 0.01
Num of Std Step Trials= 20
Max Error Tol= 0.3
Flow Tol Ratio= 0.001
Split Flow NTrial= 30
Split Flow Tol= 0.02
Split Flow Ratio= 0.02
Log Output Level= 0
Friction Slope Method= 1
Unsteady Friction Slope Method= 2
Unsteady Bridges Friction Slope Method= 1
Parabolic Critical Depth
Global Vel Dist=  1 , 1 , 1
Global Log Level= 0
CheckData=True
Encroach Param= -1, 0, 0, 0
BEGIN DESCRIPTION:
Multiple Run
END DESCRIPTION:

--- BEE CREEK TRIB 3.f01 (steady flow) ---

Flow Title=Multiple
Number of Profiles=7
Profile Names=10-year,25-year,50-year,1pct_min,100-year,1pct_plu,500-year
River Rch & RM= BEE CREEK TRIB 3,Reach-1,5018
     587     785     945     832    1126    1522    1601
Boundary for River Rch & Prof#=BEE CREEK TRIB 3,Reach-1,1
Up Type=0
Dn Type=3
Dn Slope=0.005
Boundary for River Rch & Prof#=BEE CREEK TRIB 3,Reach-1,2
Up Type=0
Dn Type=3
Dn Slope=0.005
Boundary for River Rch & Prof#=BEE CREEK TRIB 3,Reach-1,3
Up Type=0
Dn Type=3
Dn Slope=0.005
Boundary for River Rch & Prof#=BEE CREEK TRIB 3,Reach-1,4
Up Type=0
Dn Type=3
Dn Slope=0.005
Boundary for River Rch & Prof#=BEE CREEK TRIB 3,Reach-1,5
Up Type=0
Dn Type=3
Dn Slope=0.005
Boundary for River Rch & Prof#=BEE CREEK TRIB 3,Reach-1,6
Up Type=0
Dn Type=3
Dn Slope=0.005
Boundary for River Rch & Prof#=BEE CREEK TRIB 3,Reach-1,7
Up Type=0
Dn Type=3
Dn Slope=0.005

--- BEE CREEK TRIB 3.g01 (geometry) ---

Geom Title=Existing Conditions
Program Version=4.10

River Reach=BEE CREEK TRIB 3,Reach-1
Reach XY= 30
      3558734.54     10197324.48      3558876.91      10197396.3
      3558875.59     10197670.83      3559070.98     10197837.16
      3559021.52     10197966.63      3559065.76      10198130.2
      3559163.17     10198263.36      3559255.87     10198260.21
      3559284.29     10198426.45      3559349.07     10198493.55
      3559273.46     10198570.27      3559317.47     10198814.65
      3559375.21     10198848.22      3559459.46     10198736.81
      3559528.85     10198758.08      3559505.56     10198980.06
      3559690.36     10199217.33       3559643.3      10199356.7
      3559688.36     10199490.38       3559545.1     10199614.27
      3559587.42     10199698.91        3559429.     10199717.36
      3559279.76     10199968.18      3559485.92     10200015.93
      3559539.09     10199949.74      3559570.55      10200185.2
       3559828.8     10200212.33       3559909.1     10200416.32
      3560143.47     10200444.53      3560374.81     10200639.88

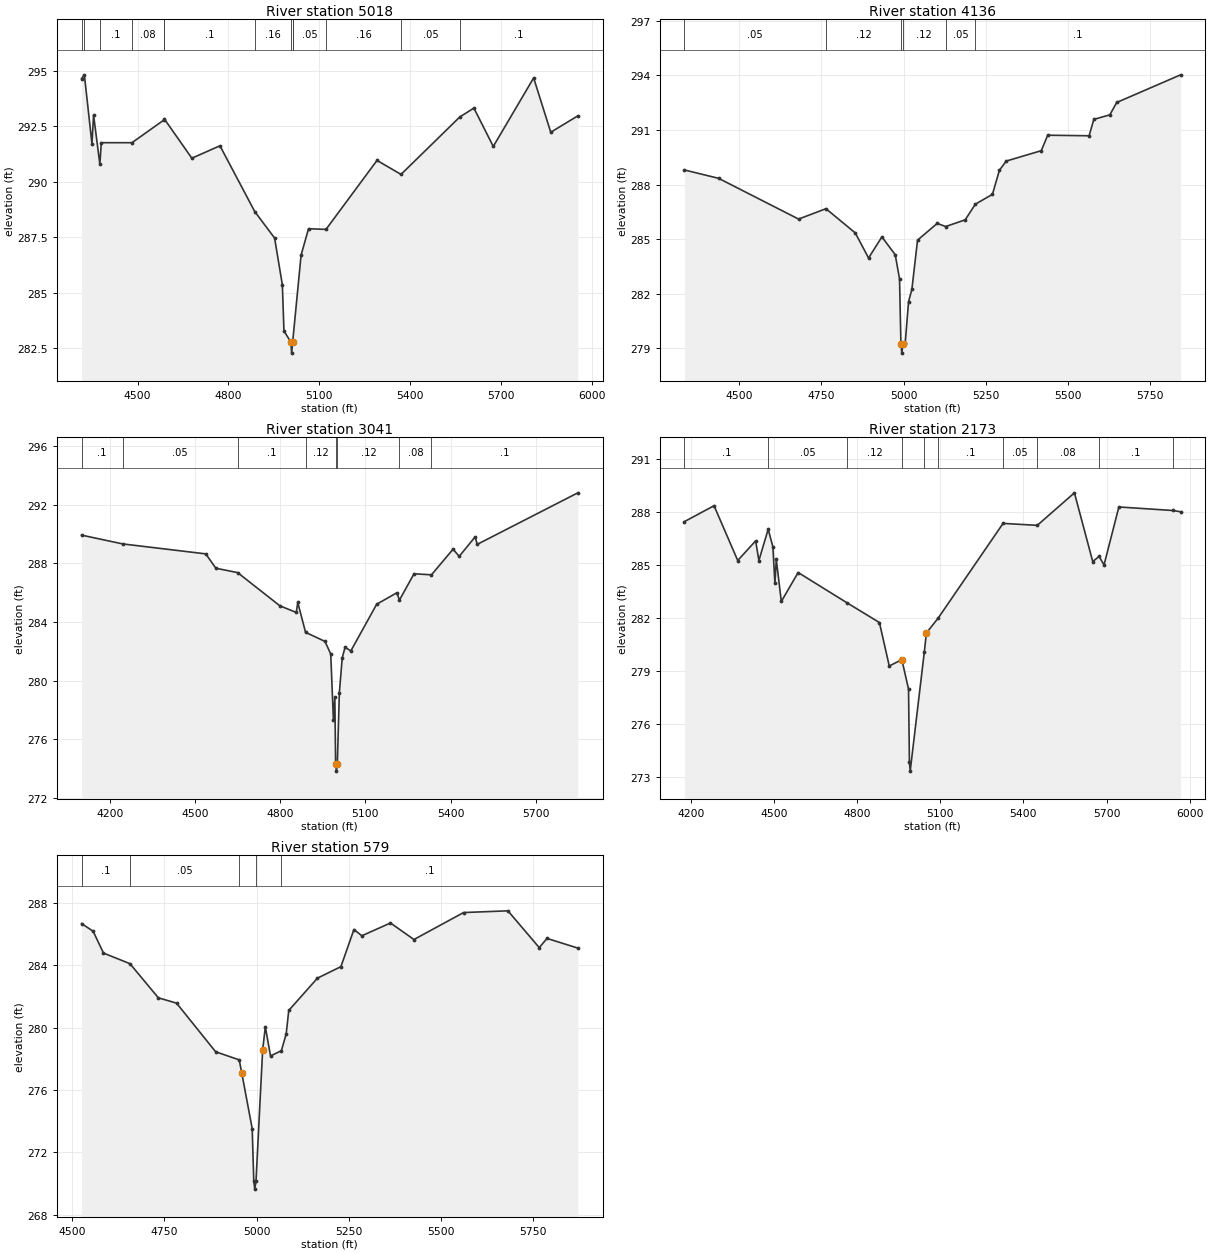
Type RM Length L Ch R = 1 ,5018    ,882,882,882
BEGIN DESCRIPTION:
BEE CREEK TRIB 3 6.0
END DESCRIPTION:
XS GIS Cut Line= 3
      3558255.25     10197928.12      3559083.35     10197636.46
       3559807.2     10197402.13
#Sta/Elev= 30
  4315.3  294.66  4324.4  294.83  4349.5  291.72  4354.8  293.02  4375.6   290.8
  4380.4  291.77  4481.7  291.77  4587.9   292.8    4589  292.83  4679.4  291.07
  4772.2  291.63  4887.3  288.66  4952.7  287.47  4978.3  285.36  4983.6  283.28
  5006.3  282.78    5009  282.28  5012.3  282.78  5012.4  282.79  5040.2   286.7
  5064.7  287.89  5122.4  287.86  5290.9  290.97  5370.2  290.34  5564.3  292.93
  5610.9  293.33  5674.9   291.6  5808.2  294.69  5864.7  292.24  5954.1  292.98
#Mann= 13 ,-1 , 0
  4315.3      .1       0  4324.4     .08       0  4375.6      .1       0
  4481.7     .08       0  4587.9     .05       0    4589      .1       0
  4887.3     .16       0  5006.3     .07       0  5012.3     .16       0
  5012.4     .05       0  5122.4     .16       0  5370.2     .05       0
  5564.3      .1       0
Bank Sta=5006.3,5012.3
XS Rating Curve= 0 ,0
Exp/Cntr=0.3,0.1

Type RM Length L Ch R = 1 ,4136    ,1095,1095,1095
BEGIN DESCRIPTION:
BEE CREEK TRIB 3 5.0
END DESCRIPTION:
XS GIS Cut Line= 3
      3558609.43     10198417.71       3559484.4     10198266.67
      3560077.14     10198074.88
#Sta/Elev= 30
  4332.7   288.8  4436.9  288.34  4680.4   286.1  4763.7  286.67    4853  285.34
  4893.5  283.96  4934.1  285.12  4974.7  284.14  4987.8  282.81    4992  279.23
  4994.8  278.73    4998  279.23  5005.2  279.31  5015.3  281.56  5025.5  282.25
  5042.6  284.94  5102.4  285.86  5128.4  285.69  5187.8  286.06  5218.7  286.92
  5270.7  287.46  5291.8  288.78  5312.8  289.29  5419.4  289.86  5438.9  290.71
    5565  290.68  5579.4  291.58  5628.1  291.83  5649.1  292.51  5843.6  294.03
#Mann= 6 ,-1 , 0
  4332.7     .05       0  4763.7     .12       0    4992     .07       0
    4998     .12       0  5128.4     .05       0  5218.7      .1       0
Bank Sta=4992,4998
XS Rating Curve= 0 ,0
Exp/Cntr=0.3,0.1

Type RM Length L Ch R = 1 ,3041    ,868,868,868
BEGIN DESCRIPTION:
BEE CREEK TRIB 3 3.0
END DESCRIPTION:
XS GIS Cut Line= 3
      3558614.57     10199073.97      3559817.73     10198886.46
      3560213.54     10198532.32
#Sta/Elev= 30
  4099.8  289.93  4244.8  289.33  4537.3  288.65    4573  287.67  4649.7  287.37
  4798.7   285.1  4856.4  284.65  4861.6  285.33  4889.1  283.29  4957.6  282.67
  4977.8  281.81  4987.2  277.33  4992.3  278.84    4995  274.31  4997.8  273.81
    5001  274.31  5008.2  279.17  5018.3  281.55  5028.4  282.27  5048.6  282.02
  5139.7  285.21  5210.6  285.99  5220.1   285.5  5271.3  287.29  5332.9  287.22
  5408.9  288.97  5430.6  288.48  5486.6  289.81  5494.1   289.3  5848.6  292.82
#Mann= 8 ,-1 , 0
  4099.8      .1       0  4244.8     .05       0  4649.7      .1       0
  4889.1     .12       0    4995     .07       0    5001     .12       0
  5220.1     .08       0  5332.9      .1       0
Bank Sta=4995,5001
XS Rating Curve= 0 ,0
Exp/Cntr=0.3,0.1

Type RM Length L Ch R = 1 ,2173    ,1594,1594,1594
BEGIN DESCRIPTION:
BEE CREEK TRIB 3 2.0
END DESCRIPTION:
XS GIS Cut Line= 3
      3558746.33     10199764.71      3559879.29     10199597.19
      3560475.44     10199353.26
#Sta/Elev= 30
  4177.4  287.45  4284.3  288.35  4369.8  285.25  4434.3  286.36  4446.1  285.25
  4479.6  287.02  4496.6  286.02  4503.8  283.95  4508.9  285.31  4526.9  282.93
  4587.6  284.57  4765.5  282.84  4880.7  281.74  4916.2  279.28  4961.6  279.64
  4985.7  277.97  4988.9  273.83  4991.7  273.33  5042.5  280.06  5050.2  281.15
    5093     282  5326.6  287.35    5450  287.24  5583.9  289.08  5649.9  285.19
  5672.8  285.48  5690.7     285  5744.2  288.28  5937.9  288.08  5966.8  288.01
#Mann= 10 ,-1 , 0
  4177.4      .1       0  4479.6     .05       0  4765.5     .12       0
  4961.6     .07       0  5042.5     .12       0    5093      .1       0
  5326.6     .05       0    5450     .08       0  5672.8      .1       0
  5937.9     .08       0
Bank Sta=4961.6,5050.2
XS Rating Curve= 0 ,0
Exp/Cntr=0.3,0.1

Type RM Length L Ch R = 1 ,579     ,0,0,0
BEGIN DESCRIPTION:
BEE CREEK TRIB 3 1.0
END DESCRIPTION:
XS GIS Cut Line= 3
      3559539.33     10200722.88      3560049.73     10200236.78
      3560514.58     10199796.21
#Sta/Elev= 30
  4525.3  286.67  4556.6  286.18  4584.6  284.78  4656.4   284.1  4733.4  281.91
  4782.7  281.57  4888.7  278.45  4952.6  277.93  4959.5  277.09  4987.8  273.52
  4992.1  270.14  4994.8  269.64  4998.1  270.14  5016.1  278.56  5023.4  280.05
  5037.5  278.18  5066.9  278.52    5080   279.6  5086.9   281.1  5164.6  283.17
  5228.3  283.91  5263.6  286.29  5285.1  285.89  5362.7  286.71  5426.3  285.65
  5560.9  287.38  5681.1  287.49    5766  285.13  5787.1  285.72  5870.6   285.1
#Mann= 5 ,-1 , 0
  4525.3      .1       0  4656.4     .05       0  4952.6     .04       0
  4998.1     .05       0  5066.9      .1       0
Bank Sta=4959.5,5016.1
XS Rating Curve= 0 ,0
Exp/Cntr=0.3,0.1

Chan Stop Cuts=-1
Use User Specified Reach Order=0
Composite Channel Slope=5