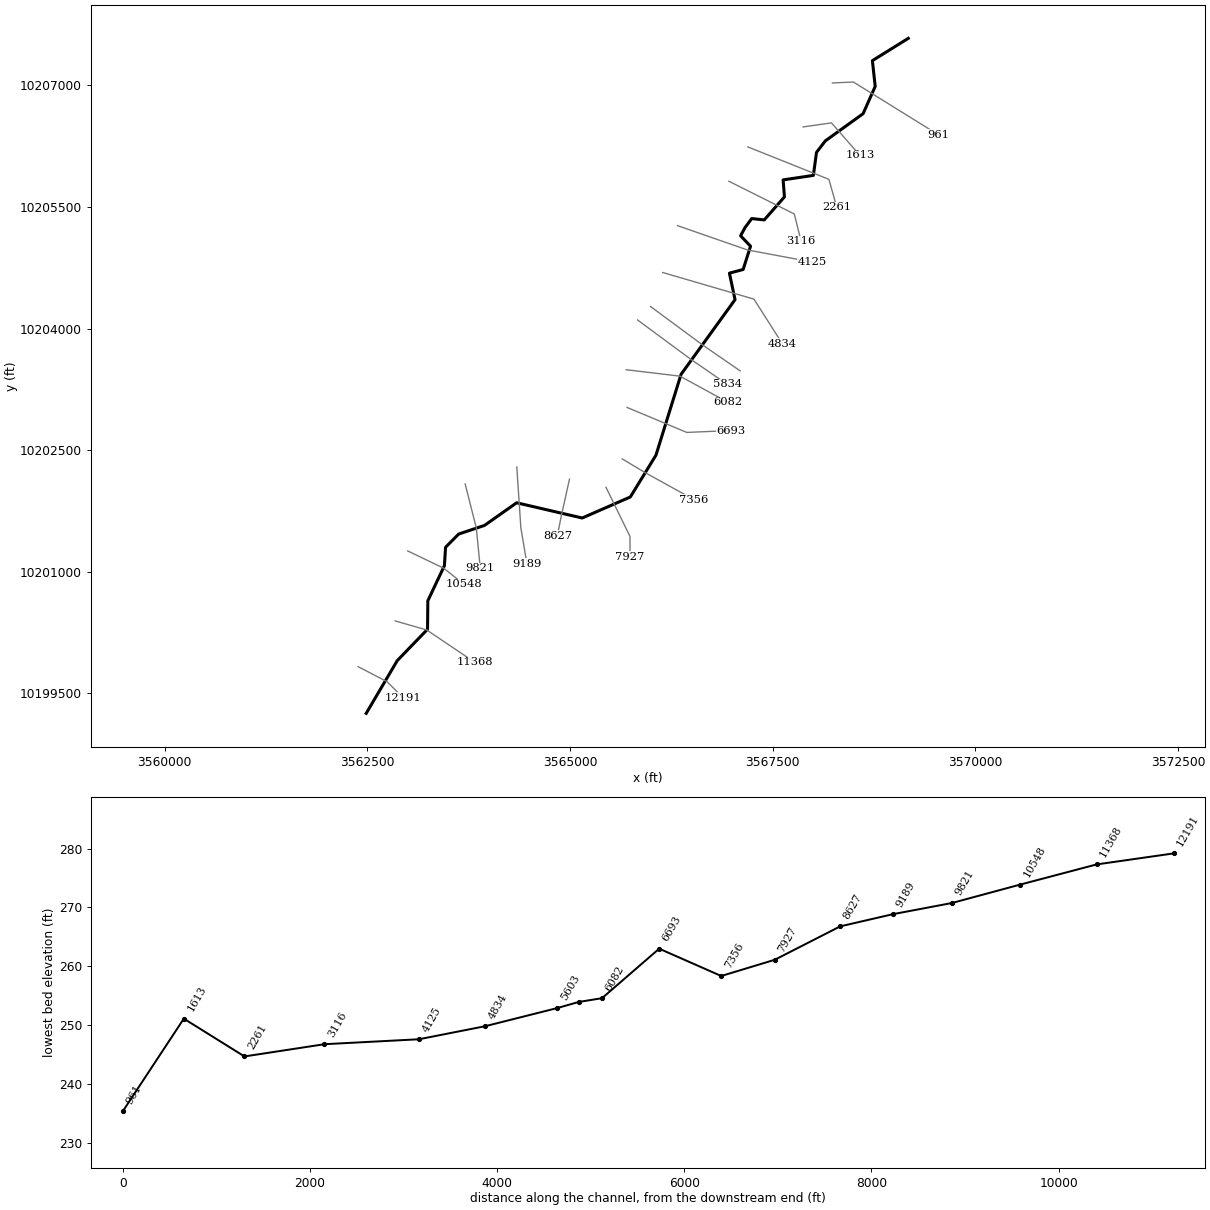
--- BEE CREEK TRIB A.prj (project) ---

Proj Title=BEE CREEK TRIB A Base Level Engineering
Current Plan=p01
Default Exp/Contr=0.3,0.1
English Units
Geom File=g01
Flow File=f01
Plan File=p01
Y Axis Title=Elevation
X Axis Title(PF)=Main Channel Distance
X Axis Title(XS)=Station
BEGIN DESCRIPTION:
BEE CREEK TRIB A
END DESCRIPTION:
DSS Export Rating Curves= 0
DSS Export Rating Curve Sorted= 0
DSS Export Volume Flow Curves= 0
DXF OffsetX= 0
DXF OffsetY= 0
DXF ScaleX= 1
DXF ScaleY= 10

--- BEE CREEK TRIB A.p01 (plan) ---

Plan Title=Multiple Run
Short Identifier=Multiple
Geom File=g01
Flow File=f01
Subcritical Flow
K Sum by GR= 0
Std Step Tol= 0.01
Critical Tol= 0.01
Num of Std Step Trials= 20
Max Error Tol= 0.3
Flow Tol Ratio= 0.001
Split Flow NTrial= 30
Split Flow Tol= 0.02
Split Flow Ratio= 0.02
Log Output Level= 0
Friction Slope Method= 1
Unsteady Friction Slope Method= 2
Unsteady Bridges Friction Slope Method= 1
Parabolic Critical Depth
Global Vel Dist=  1 , 1 , 1
Global Log Level= 0
CheckData=True
Encroach Param= -1, 0, 0, 0
BEGIN DESCRIPTION:
Multiple Run
END DESCRIPTION:

--- BEE CREEK TRIB A.f01 (steady flow) ---

Flow Title=Multiple
Number of Profiles=7
Profile Names=10-year,25-year,50-year,1pct_min,100-year,1pct_plu,500-year
River Rch & RM= BEE CREEK TRIB A,Reach-1,12191
     504     673     810     714     966    1306    1376
River Rch & RM= BEE CREEK TRIB A,Reach-1,7356
     726     988    1203    1072    1449    1960    2111
River Rch & RM= BEE CREEK TRIB A,Reach-1,5603
     841    1152    1408    1259    1703    2303    2498
Boundary for River Rch & Prof#=BEE CREEK TRIB A,Reach-1,1
Up Type=0
Dn Type=3
Dn Slope=0.005
Boundary for River Rch & Prof#=BEE CREEK TRIB A,Reach-1,2
Up Type=0
Dn Type=3
Dn Slope=0.005
Boundary for River Rch & Prof#=BEE CREEK TRIB A,Reach-1,3
Up Type=0
Dn Type=3
Dn Slope=0.005
Boundary for River Rch & Prof#=BEE CREEK TRIB A,Reach-1,4
Up Type=0
Dn Type=3
Dn Slope=0.005
Boundary for River Rch & Prof#=BEE CREEK TRIB A,Reach-1,5
Up Type=0
Dn Type=3
Dn Slope=0.005
Boundary for River Rch & Prof#=BEE CREEK TRIB A,Reach-1,6
Up Type=0
Dn Type=3
Dn Slope=0.005
Boundary for River Rch & Prof#=BEE CREEK TRIB A,Reach-1,7
Up Type=0
Dn Type=3
Dn Slope=0.005

--- BEE CREEK TRIB A.g01 (geometry) ---

Geom Title=Existing Conditions
Program Version=4.10

River Reach=BEE CREEK TRIB A,Reach-1
Reach XY= 30
      3562484.48     10199250.66       3562867.5     10199901.71
      3563241.39     10200288.96      3563244.77     10200640.51
      3563449.14     10201072.95      3563463.69     10201301.03
      3563625.61     10201463.86       3563944.4     10201570.65
      3564340.27      10201849.7      3565148.86     10201661.84
      3565742.62     10201921.31      3566058.59     10202436.94
      3566368.48      10203435.2      3567034.27     10204356.26
      3566964.82     10204683.52      3567134.09     10204728.66
      3567225.24     10205015.98      3567102.84     10205144.46
       3567158.4     10205247.76      3567239.99     10205357.13
      3567394.51     10205340.64      3567643.64     10205624.49
      3567627.15     10205834.56      3568000.41     10205890.12
      3568039.18     10206174.12      3568148.56     10206316.48
      3568613.84     10206651.55      3568763.14     10206988.35
      3568728.42     10207306.06      3569171.25      10207581.5

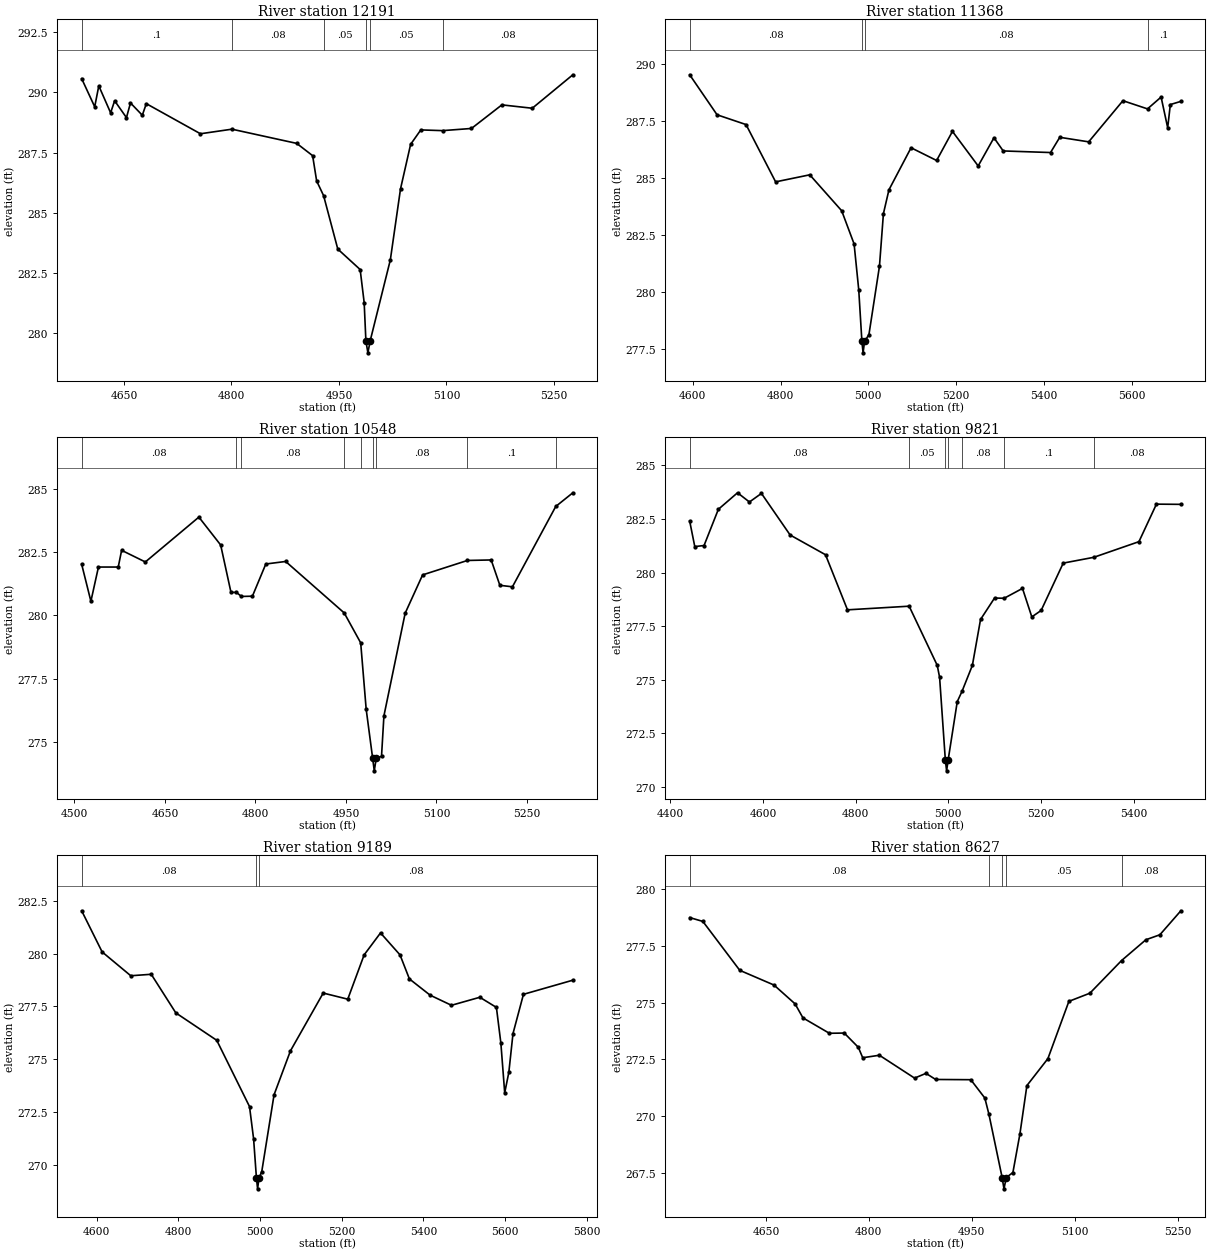
Type RM Length L Ch R = 1 ,12191   ,823,823,823
BEGIN DESCRIPTION:
BEE CREEK TRIB A 28.0
END DESCRIPTION:
XS GIS Cut Line= 3
      3562385.11     10199827.24      3562742.11     10199641.64
      3562942.11     10199441.64
#Sta/Elev= 30
  4591.1  290.57  4609.3   289.4    4615  290.27  4631.5  289.15  4637.1  289.65
  4653.6  288.95  4659.2  289.56  4675.7  289.05  4681.3  289.53  4756.8  288.28
  4800.7  288.47  4891.1  287.88  4913.3  287.37  4918.9  286.32  4928.6  285.71
  4948.4  283.49  4979.6  282.64  4985.2  281.27  4987.6  279.68  4990.4  279.18
  4993.6  279.68  5021.7  283.04  5035.9  285.99    5050  287.84  5064.2  288.44
  5094.5  288.41  5134.9   288.5  5177.3  289.48  5219.7  289.34  5276.3  290.73
#Mann= 6 ,-1 , 0
  4591.1      .1       0  4800.7     .08       0  4928.6     .05       0
  4987.6     .04       0  4993.6     .05       0  5094.5     .08       0
Bank Sta=4987.6,4993.6
XS Rating Curve= 0 ,0
Exp/Cntr=0.3,0.1

Type RM Length L Ch R = 1 ,11368   ,820,820,820
BEGIN DESCRIPTION:
BEE CREEK TRIB A 26.0
END DESCRIPTION:
XS GIS Cut Line= 3
       3562842.1     10200391.64      3563232.14     10200279.55
      3563823.62     10199880.92
#Sta/Elev= 30
    4593  289.54  4655.4  287.78  4721.4  287.35  4788.8  284.83  4866.6  285.14
  4939.3  283.56  4967.6   282.1  4978.2  280.08  4985.4  277.81  4988.1  277.31
  4991.4  277.81  5001.4  278.11  5025.4  281.12  5034.4  283.43    5047  284.48
  5097.4  286.33  5155.6  285.77  5191.7  287.05  5250.3  285.53  5286.3  286.77
  5307.3  286.19  5415.2  286.12  5436.2  286.79  5502.1  286.59  5580.1   288.4
  5636.1  288.04  5667.1  288.56  5682.1  287.21  5688.1  288.23  5712.1  288.37
#Mann= 4 ,-1 , 0
    4593     .08       0  4985.4     .07       0  4991.4     .08       0
  5636.1      .1       0
Bank Sta=4985.4,4991.4
XS Rating Curve= 0 ,0
Exp/Cntr=0.3,0.1

Type RM Length L Ch R = 1 ,10548   ,727,727,727
BEGIN DESCRIPTION:
BEE CREEK TRIB A 24.0
END DESCRIPTION:
XS GIS Cut Line= 3
        3562997.     10201255.04      3563442.11     10201041.64
      3563692.13     10200841.63
#Sta/Elev= 30
  4512.1  282.02  4527.4  280.56  4539.9  281.91  4572.7  281.91  4578.3  282.57
  4617.6  282.11  4706.3  283.88  4742.4  282.78  4759.5  280.91  4768.5  280.91
  4776.8  280.75    4795  280.76  4817.2  282.03  4850.1  282.13  4947.1   280.1
  4974.4  278.92  4983.5   276.3  4994.2  274.37  4996.9  273.87  5000.2  274.37
  5008.9  274.44  5012.9  276.04  5048.1  280.09    5077   281.6  5151.3  282.17
  5190.6  282.19    5205  281.19  5225.8  281.13  5297.6   284.3  5325.9  284.84
#Mann= 9 ,-1 , 0
  4512.1     .08       0  4768.5      .1       0  4776.8     .08       0
  4947.1     .05       0  4974.4     .08       0  4994.2     .07       0
  5000.2     .08       0  5151.3      .1       0  5297.6     .08       0
Bank Sta=4994.2,5000.2
XS Rating Curve= 0 ,0
Exp/Cntr=0.3,0.1

Type RM Length L Ch R = 1 ,9821    ,632,632,632
BEGIN DESCRIPTION:
BEE CREEK TRIB A 22.0
END DESCRIPTION:
XS GIS Cut Line= 3
      3563705.51     10202081.69      3563842.11     10201541.64
       3563892.1     10201041.69
#Sta/Elev= 30
    4442   282.4    4453  281.21    4473  281.26  4503.9  282.95  4545.2  283.72
  4570.9  283.29  4596.8  283.69  4658.7  281.75    4735  280.83  4782.4  278.26
  4915.4  278.43    4976  275.67  4981.1  275.11  4993.5  271.25  4996.2  270.75
  4999.5  271.25  5019.2  273.98  5029.5  274.46  5051.8  275.67  5069.4  277.81
  5099.6  278.81  5120.4   278.8  5159.9  279.26    5180  277.93  5200.1  278.23
  5247.8  280.44  5313.7  280.71  5411.1  281.44  5448.8  283.19  5501.5  283.18
#Mann= 7 ,-1 , 0
    4442     .08       0  4915.4     .05       0  4993.5     .04       0
  4999.5     .05       0  5029.5     .08       0  5120.4      .1       0
  5313.7     .08       0
Bank Sta=4993.5,4999.5
XS Rating Curve= 0 ,0
Exp/Cntr=0.3,0.1

Type RM Length L Ch R = 1 ,9189    ,562,562,562
BEGIN DESCRIPTION:
BEE CREEK TRIB A 20.0
END DESCRIPTION:
XS GIS Cut Line= 3
      3564342.11     10202291.61      3564392.11     10201541.64
      3564467.18     10201097.17
#Sta/Elev= 30
  4563.6  282.03  4613.7  280.08  4683.8  278.95  4733.9  279.02  4794.1  277.19
  4894.3  275.89  4974.5  272.75  4984.5  271.22  4991.5  269.35  4994.3  268.85
  4997.5  269.35  5004.5  269.67  5034.6  273.31  5074.7  275.39  5154.9  278.13
    5215  277.84  5255.1  279.94  5295.2  280.98  5342.9  279.94  5365.9   278.8
  5416.6  278.03  5468.9  277.55  5538.3  277.93  5578.9  277.45  5589.8  275.76
  5599.2   273.4  5609.3  274.37  5619.5  276.21  5645.1  278.07    5766  278.74
#Mann= 3 ,-1 , 0
  4563.6     .08       0  4991.5     .07       0  4997.5     .08       0
Bank Sta=4991.5,4997.5
XS Rating Curve= 0 ,0
Exp/Cntr=0.3,0.1

Type RM Length L Ch R = 1 ,8627    ,700,700,700
BEGIN DESCRIPTION:
BEE CREEK TRIB A 19.0
END DESCRIPTION:
XS GIS Cut Line= 3
       3564992.1     10202141.61      3564892.11     10201691.64
       3564842.1     10201441.63
#Sta/Elev= 30
  4538.9  278.76  4558.1  278.59  4611.9  276.43  4661.8  275.78  4692.5  274.95
    4704  274.33  4742.5  273.65  4764.2  273.66  4784.7  273.03  4791.1  272.57
  4815.4  272.68  4866.7  271.67  4883.3  271.88  4897.4  271.61  4948.6   271.6
  4969.1  270.79    4975  270.08  4994.3  267.28    4997  266.78  5000.3  267.28
    5010   267.5  5020.2   269.2  5030.4  271.34    5061  272.53  5091.6  275.06
  5122.2  275.42  5168.3  276.86  5203.8  277.78  5224.2     278  5254.8  279.06
#Mann= 5 ,-1 , 0
  4538.9     .08       0    4975     .05       0  4994.3     .04       0
  5000.3     .05       0  5168.3     .08       0
Bank Sta=4994.3,5000.3
XS Rating Curve= 0 ,0
Exp/Cntr=0.3,0.1

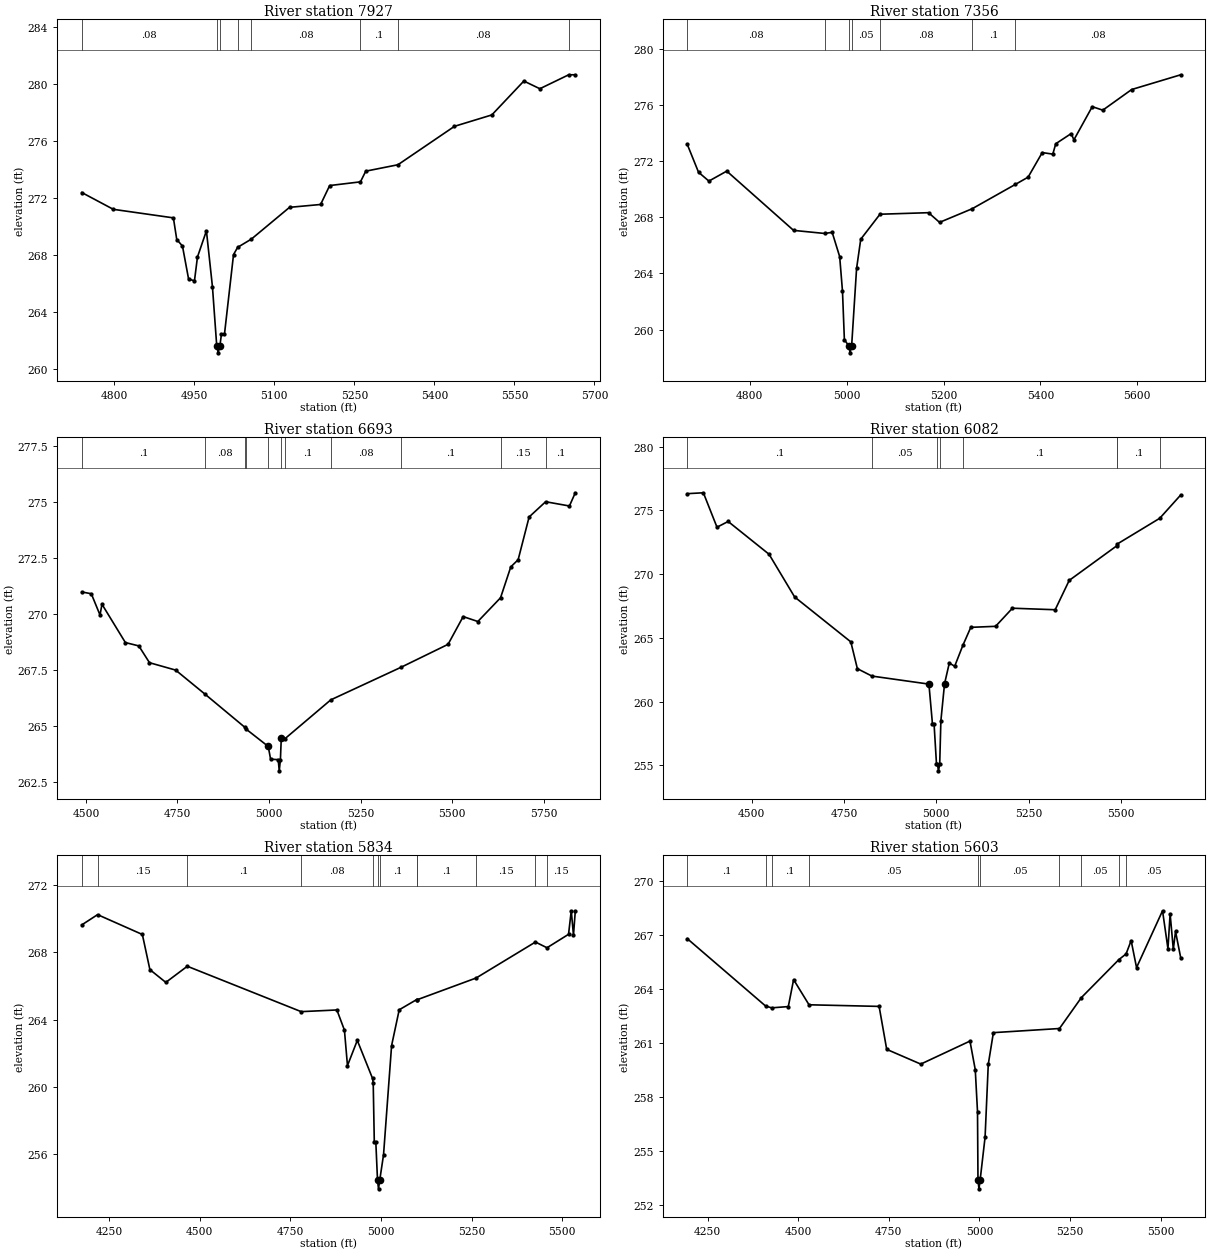
Type RM Length L Ch R = 1 ,7927    ,571,571,571
BEGIN DESCRIPTION:
BEE CREEK TRIB A 17.0
END DESCRIPTION:
XS GIS Cut Line= 3
      3565442.12      10202041.6      3565738.72      10201433.7
      3565738.72      10201185.2
#Sta/Elev= 30
  4739.2  272.36  4798.3  271.18  4910.9  270.58  4917.2  269.06  4927.9   268.6
  4939.4  266.28  4950.4  266.16    4956  267.83  4972.8  269.67  4984.1  265.74
  4992.1   261.6  4994.8   261.1  4998.1   261.6    5001  262.43  5006.6   262.4
  5023.6     268  5031.3  268.51  5057.1  269.09  5128.6  271.32  5186.8  271.52
  5203.8  272.85  5261.5  273.11  5271.4  273.86  5331.7  274.31  5437.7  277.01
  5507.7  277.81  5567.7  280.19  5597.7  279.65  5651.8  280.63  5664.1  280.63
#Mann= 8 ,-1 , 0
  4739.2     .08       0  4992.1     .07       0  4998.1     .08       0
  5031.3     .05       0  5057.1     .08       0  5261.5      .1       0
  5331.7     .08       0  5651.8      .1       0
Bank Sta=4992.1,4998.1
XS Rating Curve= 0 ,0
Exp/Cntr=0.3,0.1

Type RM Length L Ch R = 1 ,7356    ,663,663,663
BEGIN DESCRIPTION:
BEE CREEK TRIB A 16.0
END DESCRIPTION:
XS GIS Cut Line= 3
      3565642.09     10202391.65      3565923.08     10202222.62
      3566528.02     10201888.89
#Sta/Elev= 30
  4670.9   273.2  4694.2  271.21  4715.6  270.58  4752.5  271.29  4890.4  267.07
  4954.6  266.85  4970.1  266.93  4985.6   265.2  4991.4  262.74  4995.3  259.29
  5004.3  258.85  5007.1  258.35  5010.3  258.85  5020.5  264.36  5029.1  266.44
  5068.8  268.22    5169  268.33  5191.8  267.64  5259.1  268.61  5348.1  270.34
  5374.6  270.86  5403.8  272.61  5425.6   272.5  5431.7  273.24  5463.4  273.96
  5469.2  273.52    5507  275.88  5528.8  275.63  5588.4   277.1  5689.7  278.15
#Mann= 7 ,-1 , 0
  4670.9     .08       0  4954.6     .05       0  5004.3     .04       0
  5010.3     .05       0  5068.8     .08       0  5259.1      .1       0
  5348.1     .08       0
Bank Sta=5004.3,5010.3
XS Rating Curve= 0 ,0
Exp/Cntr=0.3,0.1

Type RM Length L Ch R = 1 ,6693    ,611,611,611
BEGIN DESCRIPTION:
BEE CREEK TRIB A 14.0
END DESCRIPTION:
XS GIS Cut Line= 3
      3565702.28     10203026.35      3566439.02     10202717.86
       3566988.1     10202741.31
#Sta/Elev= 30
  4488.5  270.98  4514.5   270.9  4538.3  269.95  4543.7  270.43  4607.6  268.72
  4644.3  268.57  4673.5  267.82  4744.9  267.49  4824.8  266.42  4933.6  264.94
  4936.2  264.87  4997.9  264.08  5004.4  263.51  5025.2  263.49    5028  262.99
  5031.2  263.49  5033.6  264.47  5042.5  264.41  5168.8  266.16  5361.3  267.62
  5489.2  268.64  5530.5  269.88  5570.6  269.66  5632.6  270.72  5660.6   272.1
  5680.7  272.42  5710.7  274.33  5755.8  275.01  5820.8  274.82  5836.8  275.41
#Mann= 11 ,-1 , 0
  4488.5      .1       0  4824.8     .08       0  4933.6     .05       0
  4936.2     .08       0  4997.9     .07       0  5033.6     .08       0
  5042.5      .1       0  5168.8     .08       0  5361.3      .1       0
  5632.6     .15       0  5755.8      .1       0
Bank Sta=4997.9,5033.6
XS Rating Curve= 0 ,0
Exp/Cntr=0.3,0.1

Type RM Length L Ch R = 1 ,6082    ,248,248,248
BEGIN DESCRIPTION:
BEE CREEK TRIB A 12.0
END DESCRIPTION:
XS GIS Cut Line= 3
      3565692.11     10203491.64      3566355.87     10203412.29
      3566942.12     10203091.63
#Sta/Elev= 30
  4325.2  276.31  4368.9  276.38  4405.8  273.68    4436  274.13  4546.8  271.56
  4616.1  268.21  4768.3  264.69    4786  262.59  4825.4  262.01  4979.8  261.38
  4989.3  258.29  4993.7  258.29  5000.3  255.12    5003  255.08  5005.7  254.58
    5009  255.08  5012.2   258.5  5022.1   261.4    5035  263.03  5049.6  262.78
  5071.8  264.42  5093.2  265.83  5160.4  265.91    5206  267.33  5321.8  267.21
  5359.8  269.51    5489  272.23  5489.8  272.36    5605  274.38  5661.9  276.21
#Mann= 8 ,-1 , 0
  4325.2      .1       0  4825.4     .05       0    5003     .04       0
    5009     .05       0  5071.8      .1       0    5489     .15       0
  5489.8      .1       0    5605     .15       0
Bank Sta=4979.8,5022.1
XS Rating Curve= 0 ,0
Exp/Cntr=0.3,0.1

Type RM Length L Ch R = 1 ,5834    ,231,231,231
BEGIN DESCRIPTION:
BEE CREEK TRIB A 11.0
END DESCRIPTION:
XS GIS Cut Line= 3
      3565832.04     10204105.38      3566482.02     10203625.39
      3566937.45     10203311.19
#Sta/Elev= 30
  4174.7  269.64  4218.3  270.25  4341.8  269.07  4362.6  266.98  4406.5  266.22
  4465.8  267.18  4779.9  264.48  4878.4  264.58  4899.2  263.38  4907.6  261.27
  4934.7  262.77  4976.7  260.51  4978.6  260.24  4981.6  256.72  4985.8  256.72
  4990.5  254.44  4993.2  253.94  4996.5  254.44  5007.1  255.97  5029.3  262.46
  5050.3  264.59  5098.7   265.2  5100.1  265.19  5262.4  266.48  5426.1  268.62
    5458  268.28  5517.4  269.08  5524.9  270.48    5531  269.03    5536  270.45
#Mann= 12 ,-1 , 0
  4174.7      .1       0  4218.3     .15       0  4465.8      .1       0
  4779.9     .08       0  4976.7      .1       0  4990.5     .07       0
  4996.5      .1       0  5098.7     .05       0  5100.1      .1       0
  5262.4     .15       0  5426.1      .1       0    5458     .15       0
Bank Sta=4990.5,4996.5
XS Rating Curve= 0 ,0
Exp/Cntr=0.3,0.1

Type RM Length L Ch R = 1 ,5603    ,769,769,769
BEGIN DESCRIPTION:
BEE CREEK TRIB A 11.1
END DESCRIPTION:
XS GIS Cut Line= 3
      3565992.08     10204271.67      3566642.11     10203791.64
      3567097.49     10203477.48
#Sta/Elev= 30
  4193.9  266.82  4410.1  263.07  4426.6  262.97  4472.7  263.04  4487.3  264.54
  4529.8  263.14  4723.2  263.05  4744.1  260.66  4838.1  259.84  4973.8  261.12
  4988.4  259.53  4994.6  257.19  4995.9   253.4  4998.6   252.9  5001.9   253.4
  5015.5  255.78  5024.3  259.83  5038.4  261.59  5220.7  261.82  5281.1  263.54
  5384.4  265.65  5404.4  265.97  5418.4  266.71  5433.3  265.21    5505  268.37
  5519.9  266.26  5525.9   268.2  5534.7  266.23  5540.8  267.22  5555.2  265.75
#Mann= 10 ,-1 , 0
  4193.9      .1       0  4410.1     .05       0  4426.6      .1       0
  4529.8     .05       0  4995.9     .04       0  5001.9     .05       0
  5220.7     .08       0  5281.1     .05       0  5384.4     .08       0
  5404.4     .05       0
Bank Sta=4995.9,5001.9
XS Rating Curve= 0 ,0
Exp/Cntr=0.3,0.1

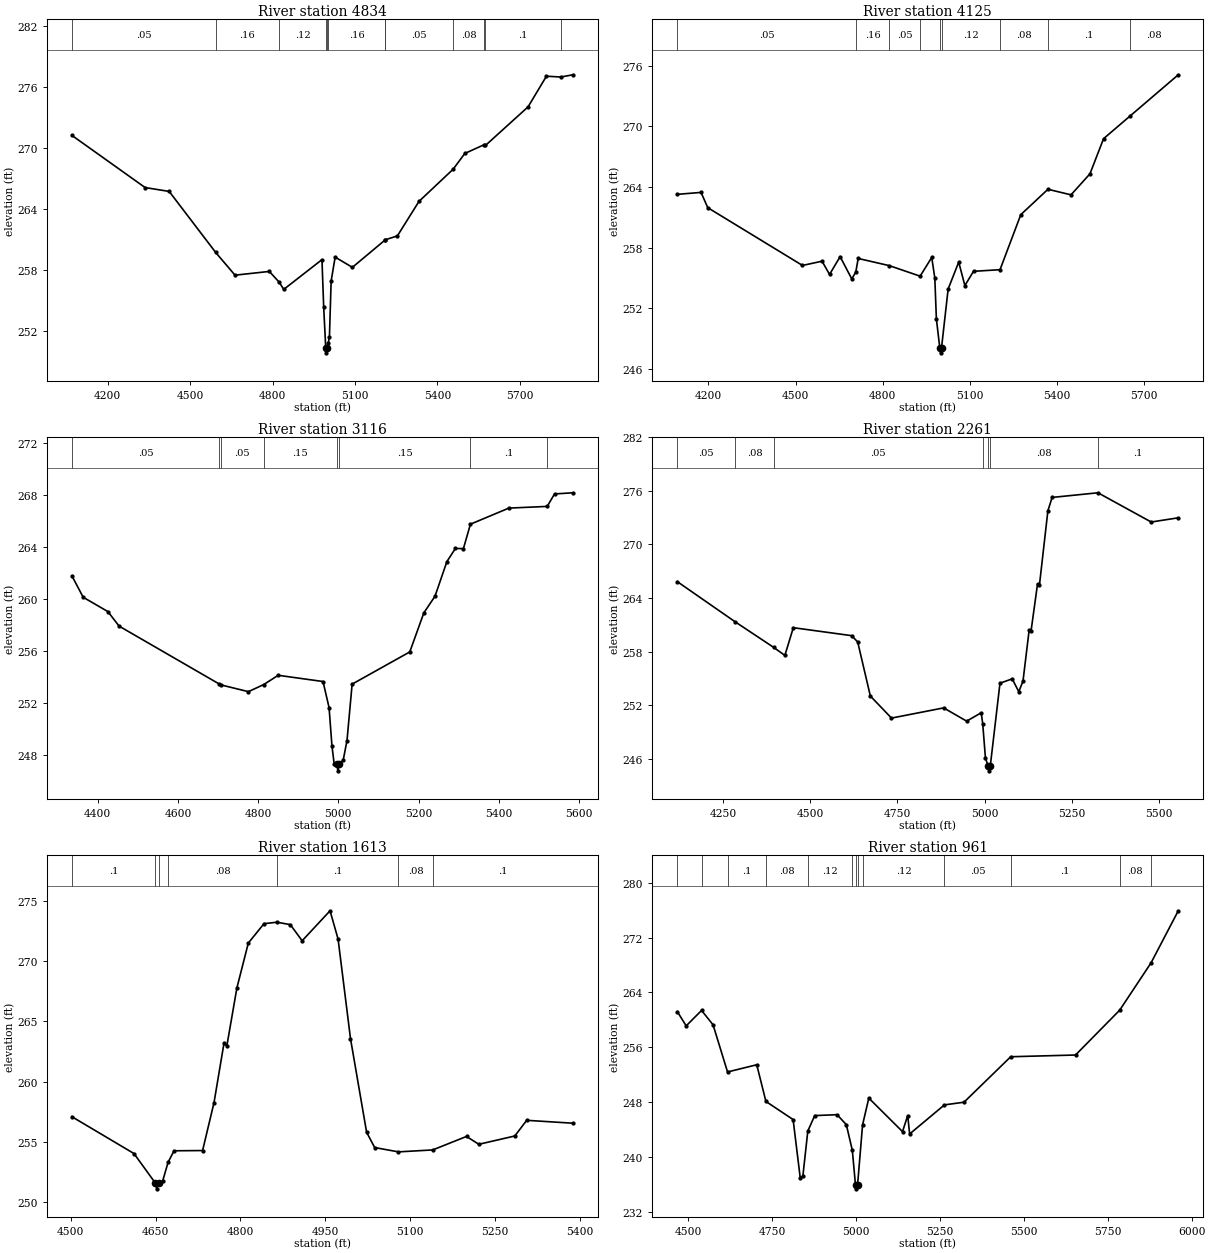
Type RM Length L Ch R = 1 ,4834    ,709,709,709
BEGIN DESCRIPTION:
BEE CREEK TRIB A 9.0
END DESCRIPTION:
XS GIS Cut Line= 3
      3566142.08     10204691.65      3567267.55     10204362.82
      3567617.31     10203813.19
#Sta/Elev= 30
  4069.3  271.24  4335.9   266.1  4423.5  265.72  4592.8  259.71  4663.2  257.47
  4788.2  257.84  4823.9  256.78  4840.7  256.07  4979.8     259  4986.1   254.3
  4993.5  250.32  4996.3  249.82  4999.5  250.32  5002.6  250.77    5007  251.41
  5013.2  256.89  5027.8  259.25  5090.5  258.24  5210.3  260.95  5210.7  260.96
  5254.4  261.34  5333.1  264.74  5457.5  267.91  5499.9  269.46  5571.1  270.33
  5575.2  270.25  5730.2  274.05  5797.1  277.07  5849.5  276.99  5893.3  277.21
#Mann= 12 ,-1 , 0
  4069.3     .05       0  4592.8     .16       0  4823.9     .12       0
  4993.5     .07       0  4999.5     .12       0  5002.6     .16       0
  5210.3      .1       0  5210.7     .05       0  5457.5     .08       0
  5571.1     .05       0  5575.2      .1       0  5849.5     .08       0
Bank Sta=4993.5,4999.5
XS Rating Curve= 0 ,0
Exp/Cntr=0.3,0.1

Type RM Length L Ch R = 1 ,4125    ,1009,1009,1009
BEGIN DESCRIPTION:
BEE CREEK TRIB A 8.0
END DESCRIPTION:
XS GIS Cut Line= 3
      3566324.94       10205270.      3567185.05     10204970.46
      3567985.03     10204820.47
#Sta/Elev= 30
  4092.8  263.27  4174.5  263.46  4197.6  261.95  4523.7  256.24  4591.1  256.66
  4616.9  255.35  4653.3  257.11  4693.4  254.91  4707.2  255.58  4715.5  256.93
  4822.7  256.22  4928.7  255.18  4968.7  257.03  4979.3  254.99  4984.7  250.96
  4996.4   248.1  4999.1   247.6  5002.4   248.1  5025.2  253.91  5061.6  256.57
  5082.8  254.25  5112.5  255.66  5203.8  255.82  5275.3  261.26  5368.8  263.77
  5448.2  263.22  5513.5   265.3  5560.2  268.77  5650.2  270.98  5817.5  275.09
#Mann= 9 ,-1 , 0
  4092.8     .05       0  4707.2     .16       0  4822.7     .05       0
  4928.7     .12       0  4996.4     .07       0  5002.4     .12       0
  5203.8     .08       0  5368.8      .1       0  5650.2     .08       0
Bank Sta=4996.4,5002.4
XS Rating Curve= 0 ,0
Exp/Cntr=0.3,0.1

Type RM Length L Ch R = 1 ,3116    ,855,855,855
BEGIN DESCRIPTION:
BEE CREEK TRIB A 6.0
END DESCRIPTION:
XS GIS Cut Line= 3
      3566958.32     10205817.49      3567764.91      10205414.2
      3567849.31     10205076.78
#Sta/Elev= 30
  4335.4  261.78  4363.6  260.13  4425.1  259.03  4453.1  257.91  4702.3  253.46
  4707.1  253.38  4775.7  252.86  4814.1  253.41    4850  254.12  4961.8  253.64
  4976.9  251.63  4984.1  248.68  4989.7  247.28  4996.3  247.26    4999  246.76
  5002.3  247.26  5012.1  247.58  5021.6  249.09  5034.4  253.44  5178.2  255.92
  5213.3  258.93  5241.1  260.21  5270.8  262.88    5292  263.89    5312  263.88
  5329.5  265.76  5425.4     267    5521  267.13  5539.3  268.09    5585  268.18
#Mann= 8 ,-1 , 0
  4335.4     .05       0  4702.3     .16       0  4707.1     .05       0
  4814.1     .15       0  4996.3     .07       0  5002.3     .15       0
  5329.5      .1       0    5521     .08       0
Bank Sta=4996.3,5002.3
XS Rating Curve= 0 ,0
Exp/Cntr=0.3,0.1

Type RM Length L Ch R = 1 ,2261    ,648,648,648
BEGIN DESCRIPTION:
BEE CREEK TRIB A 5.0
END DESCRIPTION:
XS GIS Cut Line= 3
      3567192.09     10206241.65      3568192.11     10205841.64
      3568289.27     10205496.09
#Sta/Elev= 30
  4119.1  265.84  4285.2  261.34  4394.8   258.5  4427.4  257.59  4451.6  260.69
  4618.6   259.8  4636.1   259.1  4672.4  253.05    4733  250.58  4882.5  251.72
  4948.4  250.24  4990.2  251.17  4994.5  249.96  5002.3  246.13  5010.1  245.18
  5012.8  244.68  5016.1  245.18    5044  254.48    5079  254.97  5097.9  253.53
    5110  254.72  5127.5  260.38  5132.9  260.27  5151.7   265.6  5157.1  265.44
  5181.3  273.76  5193.5  275.26  5324.8  275.78  5477.5  272.51  5555.1  272.98
#Mann= 7 ,-1 , 0
  4119.1     .05       0  4285.2     .08       0  4394.8     .05       0
  4994.5     .08       0  5010.1     .07       0  5016.1     .08       0
  5324.8      .1       0
Bank Sta=5010.1,5016.1
XS Rating Curve= 0 ,0
Exp/Cntr=0.3,0.1

Type RM Length L Ch R = 1 ,1613    ,652,652,652
BEGIN DESCRIPTION:
BEE CREEK TRIB A 2.0
END DESCRIPTION:
XS GIS Cut Line= 3
       3567873.5      10206488.3      3568223.53      10206538.3
      3568573.53     10206138.29
#Sta/Elev= 30
  4502.2  257.09  4611.9  254.03  4649.3   251.6  4652.1   251.1  4655.3   251.6
  4662.4  251.72  4672.1   253.3  4682.6  254.26  4733.1  254.28  4753.3  258.26
  4770.9  263.19    4776  262.98  4793.7  267.78  4813.9  271.51  4841.6  273.12
  4864.4  273.24  4888.1  273.04    4909   271.7  4958.3  274.19  4972.5  271.84
  4994.4  263.58  5022.9   255.8  5037.1  254.53    5079  254.17  5139.6  254.33
  5199.4  255.45  5221.2   254.8  5284.8  255.49  5305.7  256.79  5387.3  256.55
#Mann= 7 ,-1 , 0
  4502.2      .1       0  4649.3     .07       0  4655.3      .1       0
  4672.1     .08       0  4864.4      .1       0    5079     .08       0
  5139.6      .1       0
Bank Sta=4649.3,4655.3
XS Rating Curve= 0 ,0
Exp/Cntr=0.3,0.1

Type RM Length L Ch R = 1 ,961     ,0,0,0
BEGIN DESCRIPTION:
BEE CREEK TRIB A 1.0
END DESCRIPTION:
XS GIS Cut Line= 3
      3568235.77     10207030.59      3568494.17     10207042.28
      3569542.14     10206391.62
#Sta/Elev= 30
    4468  261.21  4494.4  259.13  4540.2  261.38  4574.4  259.29  4617.6  252.41
  4704.6  253.46  4731.9  248.11  4812.9  245.47  4834.1  236.97  4841.9   237.2
  4856.7   243.8  4877.3  246.05  4943.9  246.18  4971.4  244.73  4989.3  240.98
  4998.8  235.87  5001.6  235.37  5004.8  235.87  5019.8   244.7  5038.4   248.6
  5138.8  243.71  5154.2  246.05    5160  243.37  5263.7  247.61  5321.9     248
  5461.1  254.63  5654.1  254.88  5785.7  261.42    5879  268.31  5960.2  275.91
#Mann= 13 ,-1 , 0
    4468      .1       0  4540.2     .08       0  4617.6      .1       0
  4731.9     .08       0  4856.7     .12       0  4989.3     .08       0
  4998.8     .07       0  5004.8     .08       0  5019.8     .12       0
  5263.7     .05       0  5461.1      .1       0  5785.7     .08       0
    5879      .1       0
Bank Sta=4998.8,5004.8
XS Rating Curve= 0 ,0
Exp/Cntr=0.3,0.1

Chan Stop Cuts=-1
Use User Specified Reach Order=0
Composite Channel Slope=5