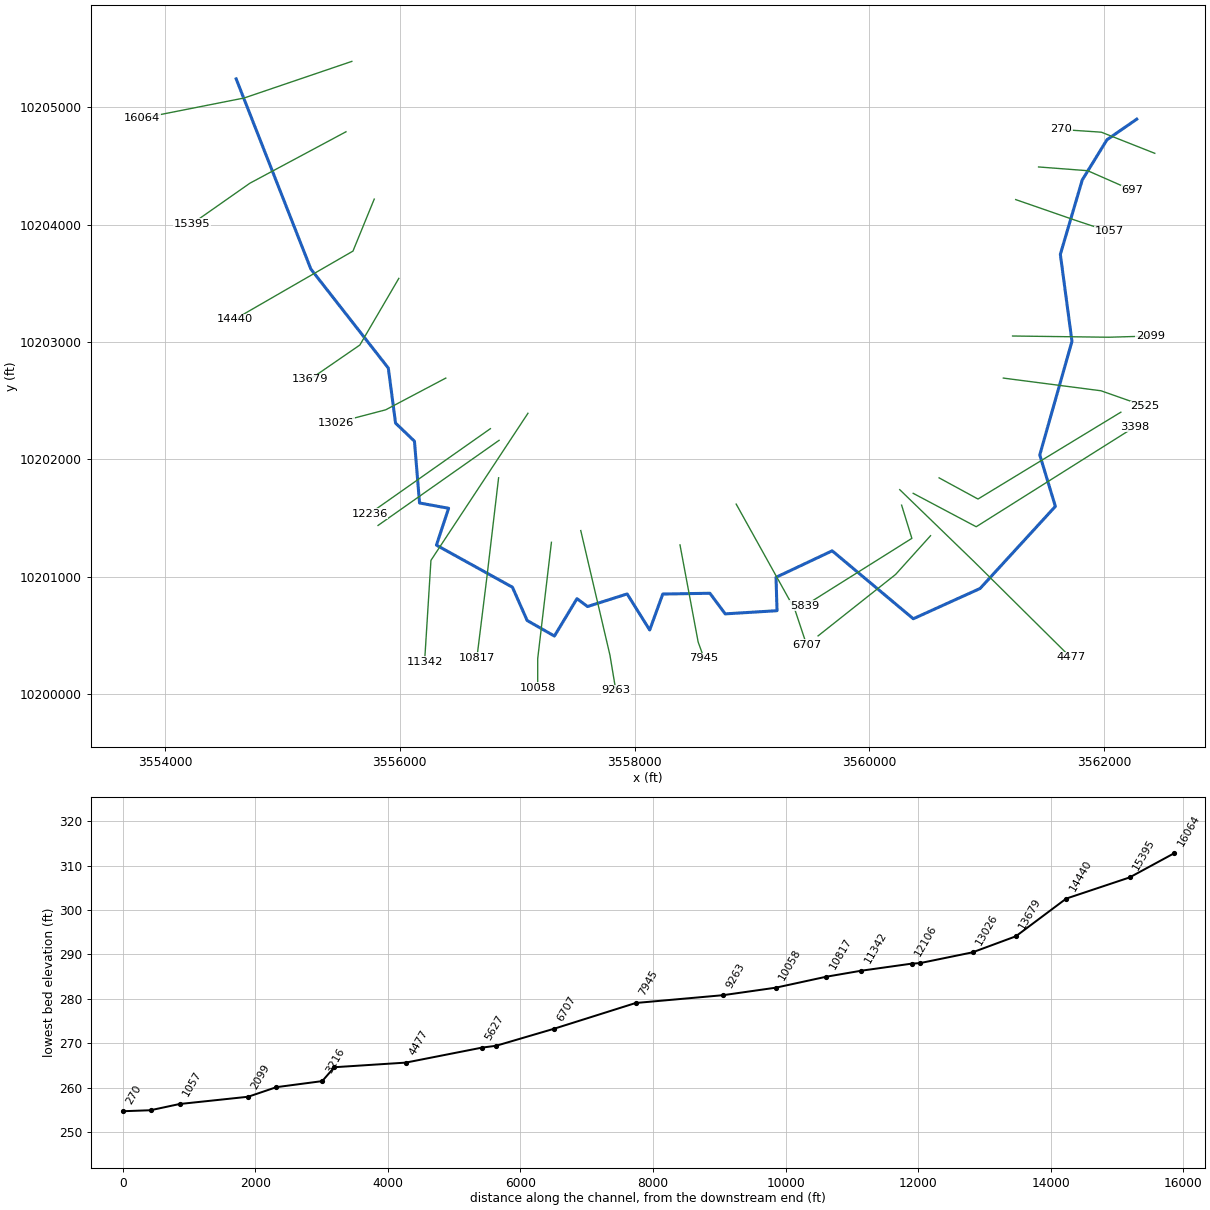
--- BEE CREEK TRIB B.prj (project) ---

Proj Title=BEE CREEK TRIB B Base Level Engineering
Current Plan=p01
Default Exp/Contr=0.3,0.1
English Units
Geom File=g01
Flow File=f01
Plan File=p01
Y Axis Title=Elevation
X Axis Title(PF)=Main Channel Distance
X Axis Title(XS)=Station
BEGIN DESCRIPTION:
BEE CREEK TRIB B
END DESCRIPTION:
DSS Export Rating Curves= 0
DSS Export Rating Curve Sorted= 0
DSS Export Volume Flow Curves= 0
DXF OffsetX= 0
DXF OffsetY= 0
DXF ScaleX= 1
DXF ScaleY= 10

--- BEE CREEK TRIB B.p01 (plan) ---

Plan Title=Multiple Run
Short Identifier=Multiple
Geom File=g01
Flow File=f01
Subcritical Flow
K Sum by GR= 0
Std Step Tol= 0.01
Critical Tol= 0.01
Num of Std Step Trials= 20
Max Error Tol= 0.3
Flow Tol Ratio= 0.001
Split Flow NTrial= 30
Split Flow Tol= 0.02
Split Flow Ratio= 0.02
Log Output Level= 0
Friction Slope Method= 1
Unsteady Friction Slope Method= 2
Unsteady Bridges Friction Slope Method= 1
Parabolic Critical Depth
Global Vel Dist=  1 , 1 , 1
Global Log Level= 0
CheckData=True
Encroach Param= -1, 0, 0, 0
BEGIN DESCRIPTION:
Multiple Run
END DESCRIPTION:

--- BEE CREEK TRIB B.f01 (steady flow) ---

Flow Title=Multiple
Program Version=4.10
Number of Profiles= 7
Profile Names=10-year,25-year,50-year,1pct_min,100-year,1pct_plu,500-year
River Rch & RM=BEE CREEK TRIB B,Reach-1         ,16064
     282     363     426     367     496     671     676
River Rch & RM=BEE CREEK TRIB B,Reach-1         ,11342
     532     711     855     753    1018    1377    1448
River Rch & RM=BEE CREEK TRIB B,Reach-1         ,10817
     532     711     855     753    1018    1377    1448
River Rch & RM=BEE CREEK TRIB B,Reach-1         ,4477
    1055    1461    1800    1620    2191    2964    3260
River Rch & RM=BEE CREEK TRIB B,Reach-1         ,1057
    1172    1630    2012    1815    2455    3320    3665
Boundary for River Rch & Prof#=BEE CREEK TRIB B,Reach-1         , 1
Up Type= 0
Dn Type= 3
Dn Slope=0.005
Boundary for River Rch & Prof#=BEE CREEK TRIB B,Reach-1         , 2
Up Type= 0
Dn Type= 3
Dn Slope=0.005
Boundary for River Rch & Prof#=BEE CREEK TRIB B,Reach-1         , 3
Up Type= 0
Dn Type= 3
Dn Slope=0.005
Boundary for River Rch & Prof#=BEE CREEK TRIB B,Reach-1         , 4
Up Type= 0
Dn Type= 3
Dn Slope=0.005
Boundary for River Rch & Prof#=BEE CREEK TRIB B,Reach-1         , 5
Up Type= 0
Dn Type= 3
Dn Slope=0.005
Boundary for River Rch & Prof#=BEE CREEK TRIB B,Reach-1         , 6
Up Type= 0
Dn Type= 3
Dn Slope=0.005
Boundary for River Rch & Prof#=BEE CREEK TRIB B,Reach-1         , 7
Up Type= 0
Dn Type= 3
Dn Slope=0.005
DSS Import GetInterval= 0
DSS Import GetPeak= 0
DSS Import FillOption= 0

--- BEE CREEK TRIB B.g01 (geometry) ---

Geom Title=Existing Conditions
Program Version=4.10

River Reach=BEE CREEK TRIB B,Reach-1
Reach XY= 30
       3554606.5     10205242.36       3555242.8     10203621.19
       3555902.7     10202776.89      3555964.26     10202307.81
      3556125.28     10202153.65      3556168.65     10201626.92
      3556416.18     10201581.76       3556312.6      10201267.3
      3556960.03     10200908.84      3557085.38     10200624.94
      3557317.51     10200492.31      3557509.76      10200811.1
      3557599.69     10200744.08      3557937.21     10200851.42
      3558129.28     10200544.01      3558240.79     10200850.59
      3558642.47     10200857.21      3558772.33     10200681.51
        3559214.      10200708.6      3559205.54     10200993.21
      3559683.84     10201218.91      3560374.81     10200639.88
      3560944.25     10200898.09      3561585.26     10201598.03
      3561452.32      10202036.4      3561726.62     10203005.15
      3561627.66     10203746.47      3561814.12      10204380.5
      3562024.63     10204723.38      3562278.53     10204899.16

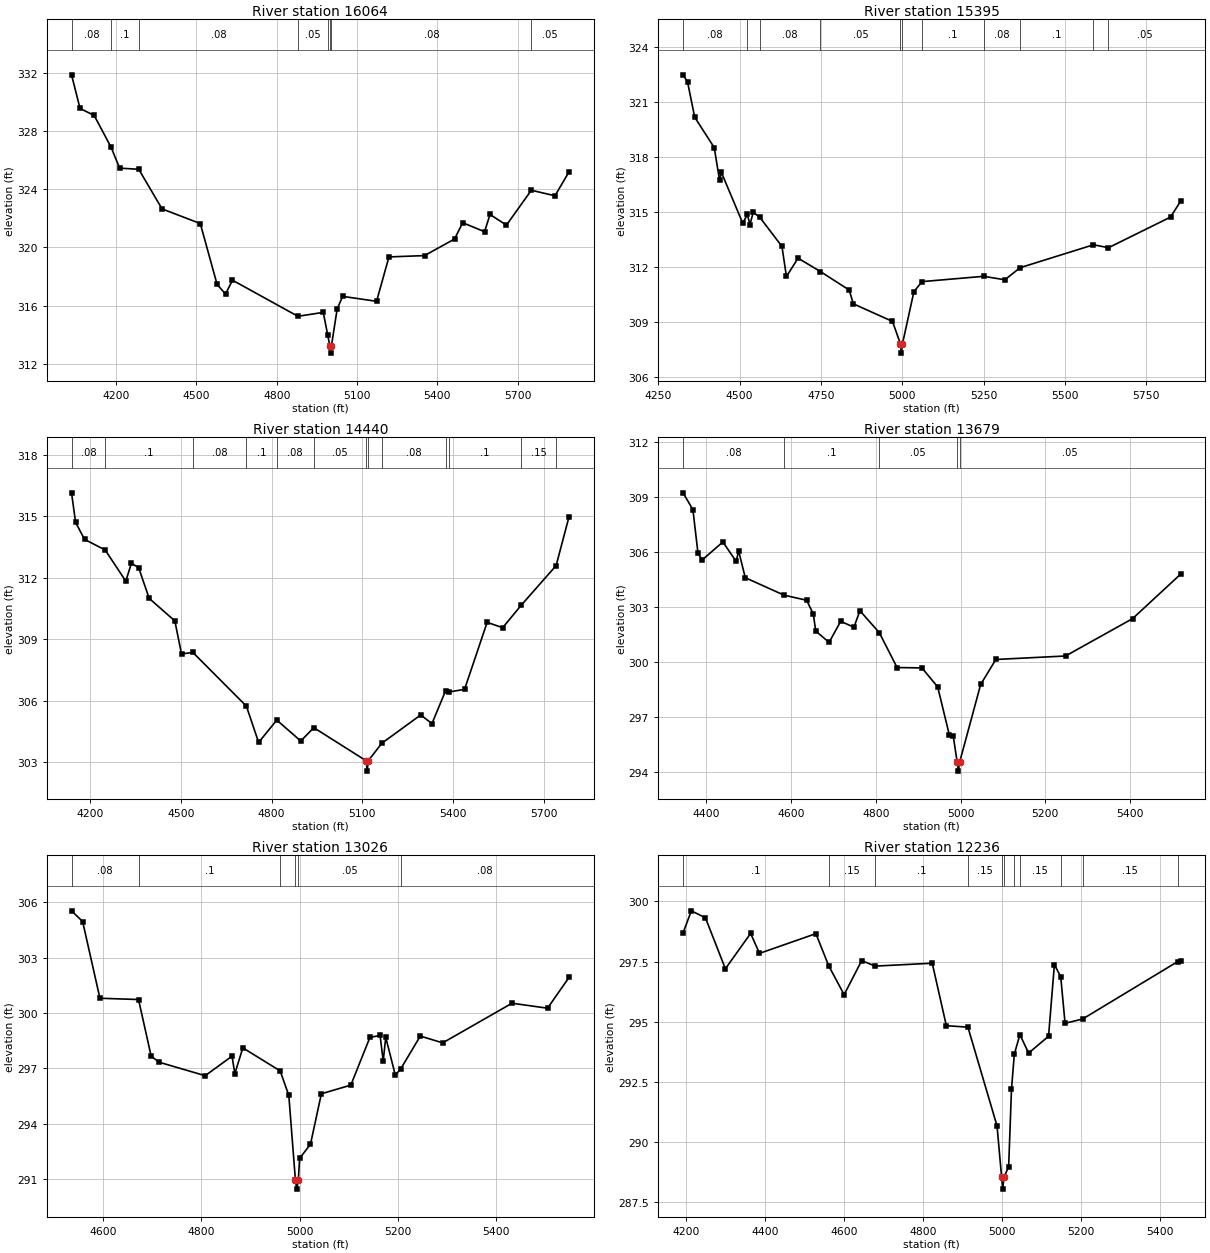
Type RM Length L Ch R = 1 ,16064   ,669,669,669
BEGIN DESCRIPTION:
BEE CREEK TRIB B 31.0
END DESCRIPTION:
XS GIS Cut Line= 3
      3555592.07     10205391.63      3554674.86      10205079.6
      3553802.71     10204907.01
#Sta/Elev= 30
  4033.8  331.86  4065.5  329.55  4118.3  329.07  4181.9  326.87  4213.3  325.45
  4284.8  325.37  4371.8  322.65  4514.7  321.64  4577.4  317.46  4608.8   316.8
  4634.9  317.75  4879.3  315.27  4973.9  315.54  4990.4     314  4998.4  313.24
  5001.2  312.74  5004.4  313.24  5025.8  315.77  5046.2  316.64    5173   316.3
  5219.2  319.35    5352  319.44  5464.2  320.58  5494.7   321.7  5576.3  321.08
  5596.7  322.27  5657.9  321.53    5751  323.93  5839.2  323.55  5891.7  325.19
#Mann= 8 ,-1 , 0
  4033.8     .08       0  4181.9      .1       0  4284.8     .08       0
  4879.3     .05       0  4990.4     .08       0  4998.4     .07       0
  5004.4     .08       0    5751     .05       0
Bank Sta=4998.4,5004.4
XS Rating Curve= 0 ,0
Exp/Cntr=0.3,0.1

Type RM Length L Ch R = 1 ,15395   ,955,955,955
BEGIN DESCRIPTION:
BEE CREEK TRIB B 29.0
END DESCRIPTION:
XS GIS Cut Line= 3
      3555542.07     10204791.62      3554723.32     10204352.93
      3554232.43     10204008.58
#Sta/Elev= 30
  4326.4   322.5  4340.2  322.11  4362.1  320.19  4422.2  318.53  4438.5  316.75
  4444.1  317.18  4509.9   314.4  4523.8  314.89  4531.9  314.33  4541.9     315
  4562.1  314.73  4630.2  313.14    4644   311.5  4679.7   312.5  4748.4  311.77
  4836.9  310.76  4849.5  310.01  4969.8  309.05  4994.4  307.82  4997.1  307.32
  5000.4  307.82  5035.6  310.67  5060.4  311.22    5250  311.51  5315.1  311.32
    5362  311.98  5587.4  313.23  5633.5  313.07  5824.1  314.74  5854.9   315.6
#Mann= 11 ,-1 , 0
  4326.4     .08       0  4523.8     .05       0  4562.1     .08       0
  4748.4     .05       0  4994.4     .04       0  5000.4     .05       0
  5060.4      .1       0    5250     .08       0    5362      .1       0
  5587.4     .08       0  5633.5     .05       0
Bank Sta=4994.4,5000.4
XS Rating Curve= 0 ,0
Exp/Cntr=0.3,0.1

Type RM Length L Ch R = 1 ,14440   ,761,761,761
BEGIN DESCRIPTION:
BEE CREEK TRIB B 28.0
END DESCRIPTION:
XS GIS Cut Line= 3
      3555782.74     10204217.72      3555601.51     10203774.26
      3554592.14     10203191.66
#Sta/Elev= 30
  4138.7  316.14  4152.1   314.7  4181.6  313.87  4249.9  313.35  4318.1  311.83
  4336.5   312.7  4360.5  312.49  4395.3  310.99  4480.2  309.89  4502.2  308.28
  4539.9  308.35  4716.7  305.73  4757.2  303.96  4817.1  305.05  4896.5  304.03
  4939.6  304.68  5113.2  303.06    5116  302.56  5119.2  303.06  5164.4  303.92
  5292.8   305.3  5330.2  304.88  5375.4  306.49  5385.4  306.42  5437.9  306.55
  5512.5  309.82  5563.9  309.56  5626.1  310.67  5740.6  312.59  5783.2  314.97
#Mann= 13 ,-1 , 0
  4138.7     .08       0  4249.9      .1       0  4539.9     .08       0
  4716.7      .1       0  4817.1     .08       0  4939.6     .05       0
  5113.2     .04       0  5119.2     .05       0  5164.4     .08       0
  5375.4     .15       0  5385.4      .1       0  5626.1     .15       0
  5740.6      .1       0
Bank Sta=5113.2,5119.2
XS Rating Curve= 0 ,0
Exp/Cntr=0.3,0.1

Type RM Length L Ch R = 1 ,13679   ,653,653,653
BEGIN DESCRIPTION:
BEE CREEK TRIB B 26.0
END DESCRIPTION:
XS GIS Cut Line= 3
      3555992.11     10203541.66      3555660.19     10202973.56
      3555236.07     10202681.17
#Sta/Elev= 30
  4345.7  309.24  4368.9  308.32  4380.9  305.94  4390.8  305.58  4439.5  306.56
  4470.9   305.5  4476.7  306.07  4492.4  304.61  4583.6  303.66  4637.1  303.38
  4652.8  302.63  4658.6   301.7    4690  301.08  4717.3  302.23  4748.7  301.91
  4762.7  302.81  4808.5  301.61  4850.4  299.71    4909  299.69  4946.2  298.65
  4973.5  296.04  4982.7  295.99    4992  294.56  4994.8  294.06    4998  294.56
  5047.5  298.79  5083.3  300.15  5247.6  300.34  5405.8  302.38  5518.8   304.8
#Mann= 5 ,-1 , 0
  4345.7     .08       0  4583.6      .1       0  4808.5     .05       0
    4992     .04       0    4998     .05       0
Bank Sta=4992,4998
XS Rating Curve= 0 ,0
Exp/Cntr=0.3,0.1

Type RM Length L Ch R = 1 ,13026   ,790,790,790
BEGIN DESCRIPTION:
BEE CREEK TRIB B 24.0
END DESCRIPTION:
XS GIS Cut Line= 3
       3556392.1     10202691.64      3555880.38     10202421.18
      3555459.79     10202310.91
#Sta/Elev= 30
  4535.3  305.54  4557.9  304.96  4593.1   300.8  4671.8  300.73  4697.5  297.66
  4713.9  297.33  4807.6   296.6  4862.3  297.66    4868  296.71  4884.3  298.11
  4960.4  296.86    4978  295.53  4991.4  290.95  4994.1  290.45  4997.4  290.95
    5000  292.12  5022.1  292.88  5044.3  295.62  5104.4  296.09  5143.3  298.68
    5164  298.78  5170.3  297.39  5175.5  298.68    5195  296.63  5206.5  296.99
  5245.9  298.75  5291.5  298.38  5432.8  300.53  5505.2  300.26  5548.9  301.93
#Mann= 6 ,-1 , 0
  4535.3     .08       0  4671.8      .1       0  4960.4     .05       0
  4991.4     .04       0  4997.4     .05       0  5206.5     .08       0
Bank Sta=4991.4,4997.4
XS Rating Curve= 0 ,0
Exp/Cntr=0.3,0.1

Type RM Length L Ch R = 1 ,12236   ,130,130,130
BEGIN DESCRIPTION:
BEE CREEK TRIB B 23.1
END DESCRIPTION:
XS GIS Cut Line= 3
      3556771.98     10202260.21      3556231.73     10201880.04
       3555742.2     10201535.55
#Sta/Elev= 30
  4193.3  298.69  4214.2  299.61  4249.9  299.32  4300.4   297.2  4364.3  298.67
  4386.7  297.84  4529.5  298.66    4562  297.32    4601  296.12  4645.4  297.54
  4679.4  297.31    4824  297.43  4859.7  294.83  4914.3  294.77    4988  290.66
  4999.6  288.53  5002.3  288.03  5005.6  288.53  5017.4  288.96  5024.6  292.19
  5031.8  293.65  5045.9  294.46  5067.9  293.69  5118.4  294.39  5133.2  297.37
  5149.2  296.87  5160.2  294.93  5204.8  295.11  5445.5   297.5  5452.5  297.51
#Mann= 11 ,-1 , 0
  4193.3      .1       0    4562     .15       0  4679.4      .1       0
  4914.3     .15       0  4999.6     .07       0  5005.6     .15       0
  5031.8     .05       0  5045.9     .15       0  5149.2     .05       0
  5204.8     .15       0  5445.5      .1       0
Bank Sta=4999.6,5005.6
XS Rating Curve= 0 ,0
Exp/Cntr=0.3,0.1

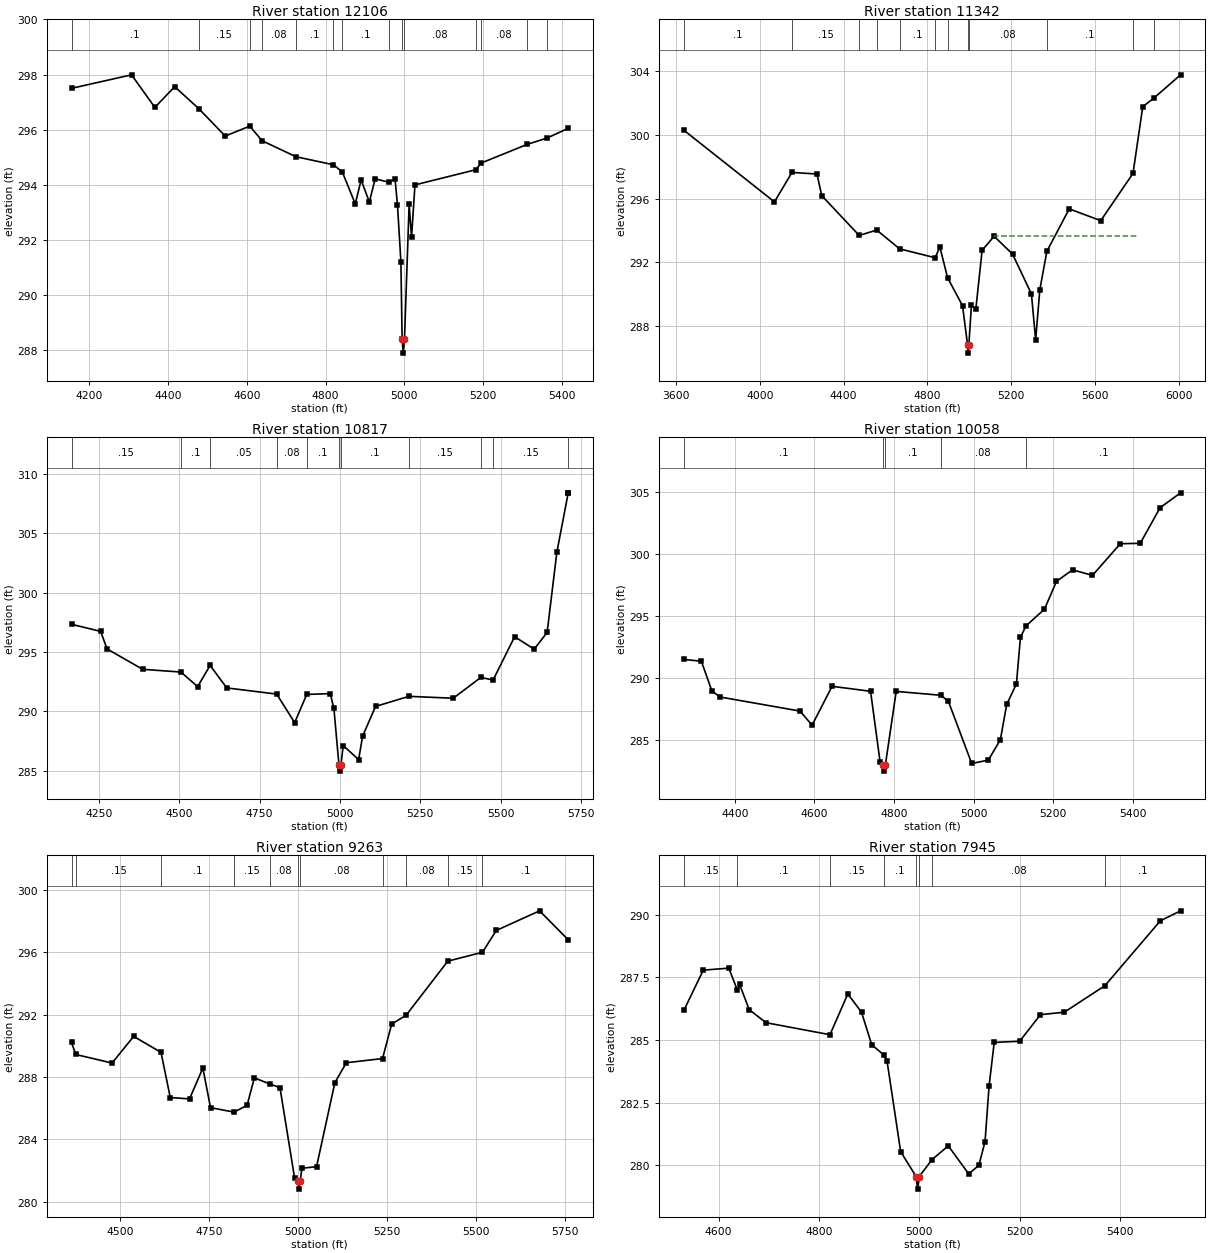
Type RM Length L Ch R = 1 ,12106   ,764,764,764
BEGIN DESCRIPTION:
BEE CREEK TRIB B 23.0
END DESCRIPTION:
XS GIS Cut Line= 3
      3556846.36     10202161.12      3556306.11     10201780.94
      3555815.11     10201435.42
#Sta/Elev= 30
    4155   297.5  4307.4  297.99  4366.6  296.81    4417  297.56  4478.4  296.76
  4545.2  295.77  4607.5  296.13  4638.9   295.6    4725  295.02  4819.8  294.73
  4842.4  294.47  4875.4  293.31  4890.2  294.18  4911.1  293.38  4925.9  294.22
  4959.8   294.1  4976.4  294.21  4982.5  293.27  4991.2  291.22  4994.3   288.4
  4997.1   287.9  5000.3   288.4  5012.1  293.29  5018.2   292.1  5026.9     294
  5181.6  294.55  5194.7  294.79  5312.2  295.47  5362.5   295.7    5416  296.05
#Mann= 14 ,-1 , 0
    4155      .1       0  4478.4     .15       0  4607.5      .1       0
  4638.9     .08       0    4725      .1       0  4819.8     .08       0
  4842.4      .1       0  4959.8     .08       0  4994.3     .07       0
  5000.3     .08       0  5181.6     .15       0  5194.7     .08       0
  5312.2     .15       0  5362.5     .08       0
Bank Sta=4994.3,5000.3
XS Rating Curve= 0 ,0
Exp/Cntr=0.3,0.1

Type RM Length L Ch R = 1 ,11342   ,525,525,525
BEGIN DESCRIPTION:
BEE CREEK TRIB B 21.0
END DESCRIPTION:
XS GIS Cut Line= 3
      3557092.13     10202391.68      3556265.84     10201137.94
       3556211.6     10200271.57
#Sta/Elev= 30
  3637.9   300.3    4070   295.8  4153.8  297.65  4272.7  297.55  4295.9  296.19
  4474.4  293.69  4557.7  294.03  4667.2  292.85  4836.9  292.29  4859.1  292.97
  4896.2  291.03  4967.3  289.28  4991.5   286.8  4994.3   286.3  4997.5   286.8
  5009.6   289.3  5030.7  289.06  5060.8  292.76    5118  293.64  5205.9  292.52
    5296  290.02  5316.1  287.13  5336.1  290.29  5369.8   292.7  5476.4  295.36
  5626.7  294.62  5780.6  297.59  5827.1  301.78  5879.3  302.31  6007.5  303.78
#Mann= 12 ,-1 , 0
  3637.9      .1       0  4153.8     .15       0  4474.4     .08       0
  4557.7     .05       0  4667.2      .1       0  4836.9     .05       0
  4896.2     .08       0  4991.5     .07       0  4997.5     .08       0
  5369.8      .1       0  5780.6     .08       0  5879.3     .15       0
#XS Ineff= 1 ,-1
 5115.91 5799.43  293.68
Permanent Ineff=
       F
Bank Sta=4991.5,4997.5
XS Rating Curve= 0 ,0
Exp/Cntr=0.3,0.1

Type RM Length L Ch R = 1 ,10817   ,759,759,759
BEGIN DESCRIPTION:
BEE CREEK TRIB B 20.0
END DESCRIPTION:
XS GIS Cut Line= 3
       3556842.1     10201841.63      3556742.11     10200991.64
      3556657.12     10200306.44
#Sta/Elev= 30
  4164.2  297.34  4254.8  296.74  4274.9  295.26  4385.7  293.54  4504.7  293.31
  4556.9  292.08  4595.6  293.87  4647.5  291.97  4802.9  291.45  4858.9  289.04
  4896.4  291.42  4969.7  291.49    4981  290.25  4996.9  285.45  4999.7  284.95
  5002.9  285.45    5010  287.11    5058  285.92  5070.4   287.9  5110.7  290.41
  5214.7  291.26  5352.6   291.1  5438.6  292.86  5476.5  292.63  5543.6  296.29
  5604.5  295.24  5644.8  296.65    5675   303.4  5710.3  308.41  5710.5  308.43
#Mann= 11 ,-1 , 0
  4164.2     .15       0  4504.7      .1       0  4595.6     .05       0
  4802.9     .08       0  4896.4      .1       0  4996.9     .07       0
  5002.9      .1       0  5214.7     .15       0  5438.6      .1       0
  5476.5     .15       0  5710.3      .1       0
Bank Sta=4996.9,5002.9
XS Rating Curve= 0 ,0
Exp/Cntr=0.3,0.1

Type RM Length L Ch R = 1 ,10058   ,795,795,795
BEGIN DESCRIPTION:
BEE CREEK TRIB B 18.0
END DESCRIPTION:
XS GIS Cut Line= 3
       3557292.1      10201291.6      3557175.34     10200300.23
      3557175.34     10200050.25
#Sta/Elev= 30
  4272.1  291.51  4316.1  291.37  4342.5  288.97  4362.7  288.48  4564.1  287.34
  4594.3   286.2  4644.6  289.34  4741.3  288.94  4765.4  283.19  4772.5  282.99
  4775.3  282.49  4778.5  282.99  4805.7  288.93  4917.1  288.62  4936.6  288.15
  4995.4  283.11  5037.3  283.38  5067.5  285.03  5083.4  287.88  5107.8  289.53
  5117.9  293.29  5131.8  294.22  5178.3  295.57  5208.5  297.82  5248.8  298.75
  5298.9   298.3  5368.9  300.86  5418.9  300.89  5468.9  303.77  5520.3  304.97
#Mann= 5 ,-1 , 0
  4272.1      .1       0  4772.5     .07       0  4778.5      .1       0
  4917.1     .08       0  5131.8      .1       0
Bank Sta=4772.5,4778.5
XS Rating Curve= 0 ,0
Exp/Cntr=0.3,0.1

Type RM Length L Ch R = 1 ,9263    ,1318,1318,1318
BEGIN DESCRIPTION:
BEE CREEK TRIB B 16.0
END DESCRIPTION:
XS GIS Cut Line= 3
       3557542.1     10201391.65      3557790.72     10200329.66
      3557840.71      10200029.7
#Sta/Elev= 30
  4363.4  290.21  4375.5  289.44  4477.3  288.89    4538   290.6  4614.7  289.58
  4640.7  286.68  4694.8  286.59  4732.2  288.57  4753.7  286.03  4819.9  285.74
  4856.4  286.18  4876.9  287.94    4920  287.55  4948.8  287.31  4989.9   281.5
  4999.4   281.3  5002.2   280.8  5005.4   281.3  5010.4  282.14  5051.5  282.24
  5102.9  287.63    5135  288.91  5236.8  289.18  5262.4  291.39    5303  291.96
    5420  295.43  5517.4     296  5556.2   297.4  5677.8  298.66  5758.2   296.8
#Mann= 11 ,-1 , 0
  4363.4      .1       0  4375.5     .15       0  4614.7      .1       0
  4819.9     .15       0    4920     .08       0  4999.4     .07       0
  5005.4     .08       0  5236.8      .1       0    5303     .08       0
    5420     .15       0  5517.4      .1       0
Bank Sta=4999.4,5005.4
XS Rating Curve= 0 ,0
Exp/Cntr=0.3,0.1

Type RM Length L Ch R = 1 ,7945    ,1238,1238,1238
BEGIN DESCRIPTION:
BEE CREEK TRIB B 14.0
END DESCRIPTION:
XS GIS Cut Line= 3
      3558387.42     10201269.68      3558542.11     10200441.64
      3558592.32     10200302.81
#Sta/Elev= 30
  4530.7  286.18  4569.4  287.79  4620.3  287.87  4637.6  286.98  4641.8  287.22
    4661  286.21  4694.5  285.69  4821.9  285.21  4857.5  286.84  4884.8  286.11
  4905.1  284.81  4929.9  284.39  4935.6  284.17  4962.8  280.54  4993.7  279.54
  4996.4  279.04  4999.7  279.54  5025.4  280.22  5057.7  280.77  5098.4  279.65
  5118.7  279.99    5131  280.94  5139.1  283.18  5149.3   284.9  5200.1  284.95
  5241.4  286.01    5289  286.11    5370  287.17  5480.3  289.76  5520.7  290.16
#Mann= 8 ,-1 , 0
  4530.7     .15       0  4637.6      .1       0  4821.9     .15       0
  4929.9      .1       0  4993.7     .07       0  4999.7      .1       0
  5025.4     .08       0    5370      .1       0
Bank Sta=4993.7,4999.7
XS Rating Curve= 0 ,0
Exp/Cntr=0.3,0.1

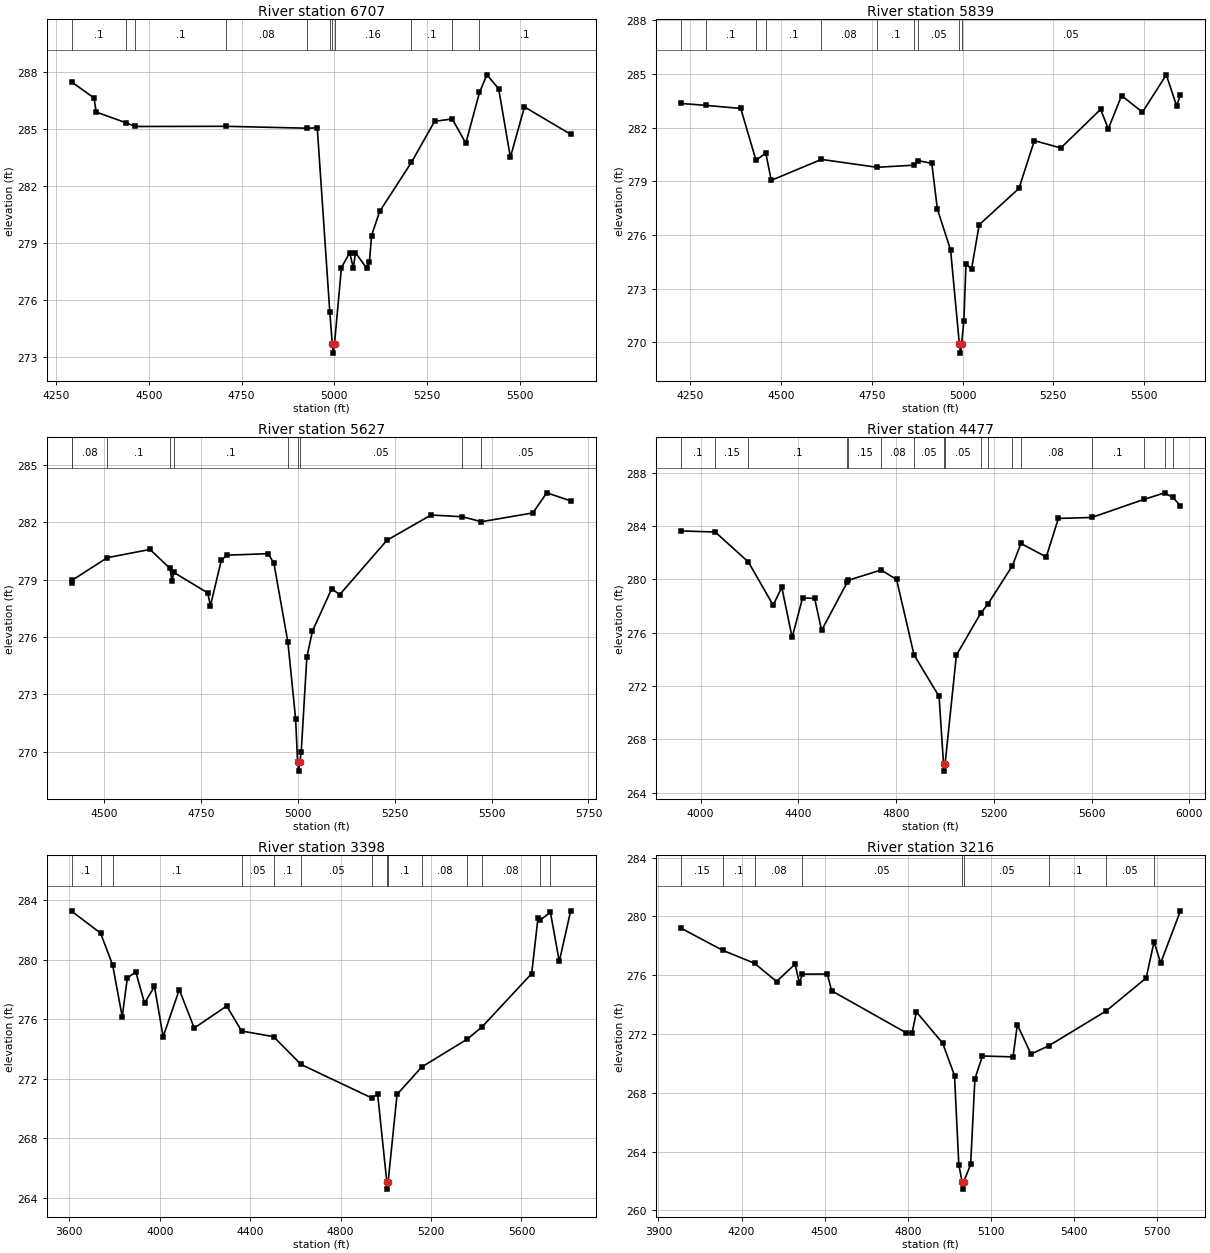
Type RM Length L Ch R = 1 ,6707    ,868,868,868
BEGIN DESCRIPTION:
BEE CREEK TRIB B 13.0
END DESCRIPTION:
XS GIS Cut Line= 3
      3558866.21     10201617.29      3559366.19     10200717.33
      3559466.17     10200417.38
#Sta/Elev= 30
  4291.3  287.49  4352.1  286.64  4357.8   285.9  4437.6  285.34  4463.2  285.14
  4707.8  285.15  4926.6  285.05  4953.8  285.07  4987.6  275.37  4994.3  273.71
    4997  273.21  5000.3  273.71    5019  277.71  5041.3   278.5    5051  277.68
  5056.8   278.5  5087.1  277.68  5094.5  278.01  5100.2   279.4    5122  280.67
  5207.6  283.25  5270.1  285.41  5317.6  285.54  5354.3  284.26  5391.1  286.93
  5411.1  287.86  5442.8  287.13  5474.4  283.52  5512.4  286.17    5637  284.73
#Mann= 11 ,-1 , 0
  4291.3      .1       0  4437.6     .08       0  4463.2      .1       0
  4707.8     .08       0  4926.6      .1       0  4987.6     .16       0
  4994.3     .07       0  5000.3     .16       0  5207.6      .1       0
  5317.6     .05       0  5391.1      .1       0
Bank Sta=4994.3,5000.3
XS Rating Curve= 0 ,0
Exp/Cntr=0.3,0.1

Type RM Length L Ch R = 1 ,5839    ,212,212,212
BEGIN DESCRIPTION:
BEE CREEK TRIB B 12.1
END DESCRIPTION:
XS GIS Cut Line= 3
      3560275.43     10201608.28      3560362.69     10201325.32
        3559449.     10200750.65
#Sta/Elev= 30
  4224.8  283.36  4293.1  283.25  4388.7  283.08  4430.6  280.19  4457.7  280.58
  4472.8  279.06  4610.8  280.23  4764.3  279.79  4867.1  279.91  4878.1  280.16
  4915.1  280.01  4930.4  277.46  4966.9  275.17  4991.1   269.9  4993.9   269.4
  4997.1   269.9  5003.4  271.18  5009.3  274.39  5024.6   274.1  5045.8  276.58
  5155.3  278.61  5197.7  281.28  5270.7  280.87  5380.3  283.03  5401.5  281.94
    5438   283.8  5495.7  282.87  5561.2  284.96  5589.9  283.22  5600.3  283.86
#Mann= 10 ,-1 , 0
  4224.8     .15       0  4293.1      .1       0  4430.6     .08       0
  4457.7      .1       0  4610.8     .08       0  4764.3      .1       0
  4867.1     .08       0  4878.1     .05       0  4991.1     .04       0
  4997.1     .05       0
Bank Sta=4991.1,4997.1
XS Rating Curve= 0 ,0
Exp/Cntr=0.3,0.1

Type RM Length L Ch R = 1 ,5627    ,1150,1150,1150
BEGIN DESCRIPTION:
BEE CREEK TRIB B 12.0
END DESCRIPTION:
XS GIS Cut Line= 3
      3560521.98     10201347.92      3560223.81     10201017.16
      3559563.64     10200493.74
#Sta/Elev= 30
  4416.3  278.81  4418.6  278.98  4508.7  280.15  4618.8  280.58  4670.3  279.59
  4675.6  278.93  4680.2  279.38  4767.6  278.31  4774.8  277.64  4802.7  280.01
  4816.9  280.28    4924  280.36  4938.5  279.85  4974.5  275.74  4994.5  271.72
  4999.5  269.49  5002.3  268.99  5005.5  269.49  5008.9  269.98  5023.4  274.94
  5037.8  276.31  5087.5  278.52  5108.3  278.22  5230.1  281.06  5343.8  282.38
  5424.6  282.29  5473.8  282.03  5606.6  282.49  5642.3  283.54  5704.1  283.12
#Mann= 10 ,-1 , 0
  4416.3      .1       0  4418.6     .08       0  4508.7      .1       0
  4670.3     .08       0  4680.2      .1       0  4974.5     .05       0
  4999.5     .04       0  5005.5     .05       0  5424.6      .1       0
  5473.8     .05       0
Bank Sta=4999.5,5005.5
XS Rating Curve= 0 ,0
Exp/Cntr=0.3,0.1

Type RM Length L Ch R = 1 ,4477    ,1079,1079,1079
BEGIN DESCRIPTION:
BEE CREEK TRIB B 11.0
END DESCRIPTION:
XS GIS Cut Line= 3
      3560259.37     10201740.39       3560891.9     10201127.51
      3561716.43     10200309.66
#Sta/Elev= 30
  3921.1  283.63    4060  283.55  4195.7   281.3    4297  278.06  4332.3   279.4
  4374.7  275.64  4417.2   278.6  4466.8  278.57  4495.1  276.17  4600.1  279.78
  4602.7  279.92  4738.4   280.7  4801.9  279.99  4873.3  274.33  4975.8  271.21
  4994.1  266.11  4996.8  265.61  5000.1  266.11  5046.6  274.31  5145.7  277.45
    5175  278.13    5276  281.03  5310.6  282.69  5414.3  281.68  5463.8  284.57
    5600  284.64  5812.8  285.99  5898.6  286.49  5931.6  286.14  5963.2  285.53
#Mann= 17 ,-1 , 0
  3921.1      .1       0    4060     .15       0  4195.7      .1       0
  4600.1     .08       0  4602.7     .15       0  4738.4     .08       0
  4873.3     .05       0  4994.1     .04       0  5000.1     .05       0
  5145.7      .1       0    5175     .05       0    5276      .1       0
  5310.6     .08       0    5600      .1       0  5812.8     .08       0
  5898.6      .1       0  5931.6     .08       0
Bank Sta=4994.1,5000.1
XS Rating Curve= 0 ,0
Exp/Cntr=0.3,0.1

Type RM Length L Ch R = 1 ,3398    ,182,182,182
BEGIN DESCRIPTION:
BEE CREEK TRIB B 9.0
END DESCRIPTION:
XS GIS Cut Line= 3
      3560373.91     10201709.18      3560910.84     10201424.28
      3562264.71     10202277.63
#Sta/Elev= 30
  3609.4  283.26  3738.1  281.78  3791.3  279.64  3833.8  276.16  3856.4  278.77
  3894.1  279.17  3932.4  277.07  3976.4   278.2  4014.7  274.82  4086.3  277.98
  4152.3   275.4  4296.1  276.88  4361.7   275.2  4503.3  274.82    4625  272.95
  4938.9  270.69  4963.4  270.99  5004.1  265.07  5006.8  264.57  5010.1  265.07
  5049.5  270.94  5158.6  272.78  5359.7  274.65  5424.5  275.46    5645  279.06
  5672.7  282.77  5682.8  282.66  5727.9  283.18  5767.2  279.88  5817.6  283.28
#Mann= 14 ,-1 , 0
  3609.4      .1       0  3738.1     .15       0  3791.3      .1       0
  4361.7     .05       0  4503.3      .1       0    4625     .05       0
  4938.9      .1       0  5004.1     .07       0  5010.1      .1       0
  5158.6     .08       0  5359.7      .1       0  5424.5     .08       0
  5682.8      .1       0  5727.9     .08       0
Bank Sta=5004.1,5010.1
XS Rating Curve= 0 ,0
Exp/Cntr=0.3,0.1

Type RM Length L Ch R = 1 ,3216    ,691,691,691
BEGIN DESCRIPTION:
BEE CREEK TRIB B 7.0
END DESCRIPTION:
XS GIS Cut Line= 3
      3560594.87     10201840.94        3560926.     10201660.56
      3562142.94     10202400.87
#Sta/Elev= 30
  3982.6  279.19  4132.2  277.69  4247.1  276.81  4326.4  275.57  4393.3  276.75
  4408.8  275.49  4420.1  276.07  4509.6  276.08  4525.1  274.94  4794.4  272.08
  4815.7  272.08  4831.2   273.5  4926.1  271.37  4968.7  269.17  4984.2  263.11
  4995.9  261.94  4998.6  261.44  5001.9  261.94  5026.9  263.12  5042.3  268.95
  5069.5   270.5  5179.9  270.44  5195.4  272.63  5244.7  270.63  5310.3  271.21
  5516.3  273.57  5660.4  275.81  5688.8  278.27  5712.6  276.83  5784.1  280.38
#Mann= 9 ,-1 , 0
  3982.6     .15       0  4132.2      .1       0  4247.1     .08       0
  4420.1     .05       0  4995.9     .04       0  5001.9     .05       0
  5310.3      .1       0  5516.3     .05       0  5688.8      .1       0
Bank Sta=4995.9,5001.9
XS Rating Curve= 0 ,0
Exp/Cntr=0.3,0.1

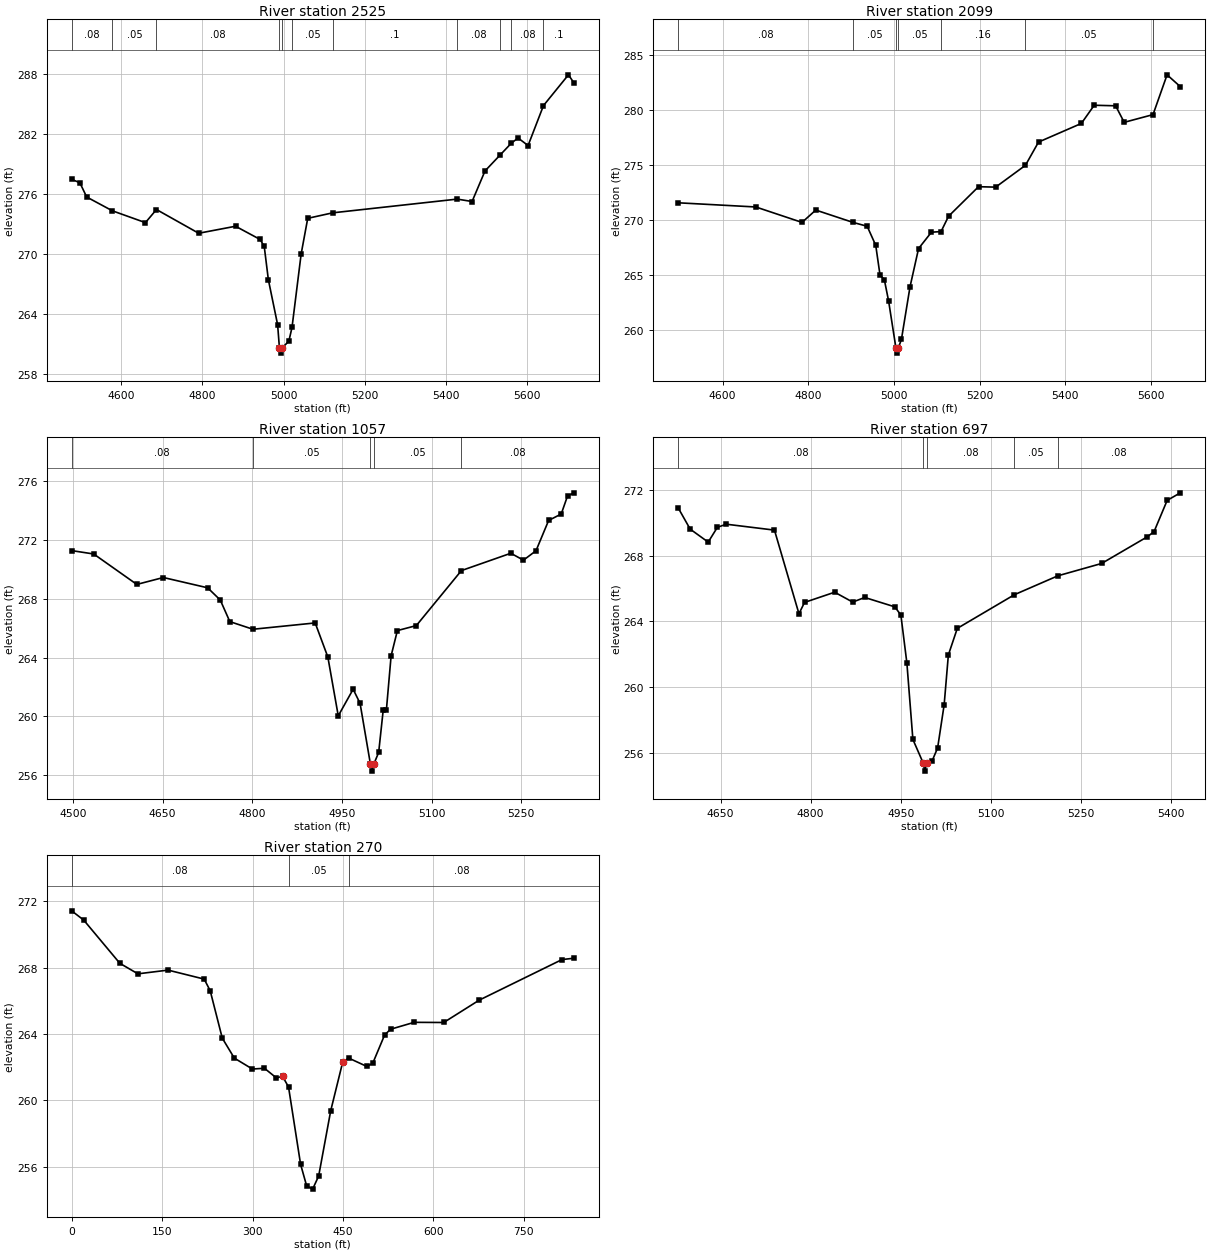
Type RM Length L Ch R = 1 ,2525    ,426,426,426
BEGIN DESCRIPTION:
BEE CREEK TRIB B 5.0
END DESCRIPTION:
XS GIS Cut Line= 3
      3561142.13     10202691.64      3561973.58     10202583.58
      3562348.33     10202451.75
#Sta/Elev= 30
  4478.7  277.43  4498.8   277.1  4515.7  275.67    4579  274.29  4660.2  273.11
  4687.4  274.42  4791.3  272.05    4882  272.75  4942.5  271.43  4952.6  270.73
  4962.7  267.42  4985.5  262.92    4990  260.58  4992.7  260.08    4996  260.58
  5013.1  261.27  5020.9  262.64  5043.4  269.98  5059.6  273.54    5121  274.09
  5427.4  275.46    5464  275.22  5495.8  278.27  5533.6  279.89    5561  281.06
  5577.2  281.56  5601.8  280.81  5639.7   284.8  5701.1  287.87  5714.4  287.08
#Mann= 11 ,-1 , 0
  4478.7     .08       0    4579     .05       0  4687.4     .08       0
    4990     .07       0    4996     .08       0  5020.9     .05       0
    5121      .1       0  5427.4     .08       0  5533.6     .05       0
    5561     .08       0  5639.7      .1       0
Bank Sta=4990,4996
XS Rating Curve= 0 ,0
Exp/Cntr=0.3,0.1

Type RM Length L Ch R = 1 ,2099    ,1036,1036,1036
BEGIN DESCRIPTION:
BEE CREEK TRIB B 4.0
END DESCRIPTION:
XS GIS Cut Line= 3
      3561220.73     10203050.38      3562039.33     10203039.91
      3562393.01     10203050.25
#Sta/Elev= 30
    4496  271.56  4677.4  271.18  4785.3  269.78  4817.4   270.9  4904.4  269.78
  4937.4  269.43  4957.4   267.7  4967.4     265  4977.4   264.6  4987.4  262.66
  5004.4  258.42  5007.2  257.92  5010.4  258.42  5017.4  259.17  5037.4  263.93
  5057.4  267.41  5087.4  268.89  5109.9  268.95  5127.4  270.34  5197.4  273.02
  5237.4  272.98  5306.9  274.96  5337.5  277.07  5437.5  278.76  5467.5  280.41
  5517.5  280.36  5537.5  278.86  5604.8  279.56  5637.6  283.17  5668.5   282.1
#Mann= 7 ,-1 , 0
    4496     .08       0  4904.4     .05       0  5004.4     .04       0
  5010.4     .05       0  5109.9     .16       0  5306.9     .05       0
  5604.8     .08       0
Bank Sta=5004.4,5010.4
XS Rating Curve= 0 ,0
Exp/Cntr=0.3,0.1

Type RM Length L Ch R = 1 ,1057    ,437,437,437
BEGIN DESCRIPTION:
BEE CREEK TRIB B 2.0
END DESCRIPTION:
XS GIS Cut Line= 3
      3561247.22     10204213.44      3561742.11     10204041.64
      3562042.12     10203941.64
#Sta/Elev= 30
    4498  271.28  4534.9  271.05    4607  268.98  4651.4  269.45  4725.5  268.75
  4746.6  267.92  4762.6  266.45  4801.3  265.93  4905.4  266.36  4926.6  264.04
    4944  260.04  4968.9  261.85  4980.5  260.89  4997.7  256.78  5000.4  256.28
  5003.7  256.78  5011.6  257.55  5019.2  260.43  5024.5  260.43  5032.4  264.12
  5042.9  265.84  5074.6  266.18    5150  269.92  5232.7   271.1  5253.8  270.63
  5274.8  271.27  5295.9  273.33    5317  273.77  5327.5  274.99  5338.1  275.21
#Mann= 5 ,-1 , 0
    4498     .08       0  4801.3     .05       0  4997.7     .04       0
  5003.7     .05       0    5150     .08       0
Bank Sta=4997.7,5003.7
XS Rating Curve= 0 ,0
Exp/Cntr=0.3,0.1

Type RM Length L Ch R = 1 ,697     ,420,420,420
BEGIN DESCRIPTION:
BEE CREEK TRIB B 1.0
END DESCRIPTION:
XS GIS Cut Line= 3
      3561442.11     10204491.64      3561860.17      10204459.7
      3562242.15     10204291.62
#Sta/Elev= 30
  4579.3  270.91  4599.4  269.61  4629.4  268.82  4644.7  269.72  4659.5  269.91
  4739.8  269.55  4780.6  264.46  4789.9  265.15  4840.1  265.77  4870.1  265.17
  4890.2  265.45  4940.3  264.88  4950.4  264.38  4960.4  261.46  4970.4  256.81
  4987.5  255.38  4990.2  254.88  4993.5  255.38  5002.4   255.5  5011.6  256.29
  5022.5  258.92  5029.5  261.95  5044.4  263.57  5139.6  265.62    5212  266.77
  5284.8  267.52  5361.2  269.15  5372.2  269.46    5394  271.36  5415.9  271.82
#Mann= 5 ,-1 , 0
  4579.3     .08       0  4987.5     .07       0  4993.5     .08       0
  5139.6     .05       0    5212     .08       0
Bank Sta=4987.5,4993.5
XS Rating Curve= 0 ,0
Exp/Cntr=0.3,0.1

Type RM Length L Ch R = 1 ,270     ,,,
XS GIS Cut Line= 3
        3562432.       10204608.        3561977.       10204788.
        3561635.       10204811.
#Sta/Elev= 30
       0271.434619.98594270.877779.94375268.2699109.9227267.6358159.8875267.8603
219.8453267.3182229.8383266.6128249.8242263.7593269.8102262.5545299.7891261.8958
 319.775261.9416339.7609261.3556349.7539  261.46359.7469260.8133379.7328256.1521
389.7258254.8558399.7188254.6548409.7117255.4444429.6977259.3813449.6836262.3287
459.6765262.5541489.6555262.0511499.4646262.2468519.0828263.9459528.8918264.2937
568.1282264.7117617.1737264.7018676.0283266.0495813.3556268.4958832.9738268.5764
#Mann= 3 ,-1 , 0
       0     .08       0359.7469     .05       0459.6765     .08       0
Bank Sta=349.7539,449.6836
XS Rating Curve= 0 ,0
Exp/Cntr=0.3,0.1

Chan Stop Cuts=-1
Use User Specified Reach Order=0
Composite Channel Slope=5