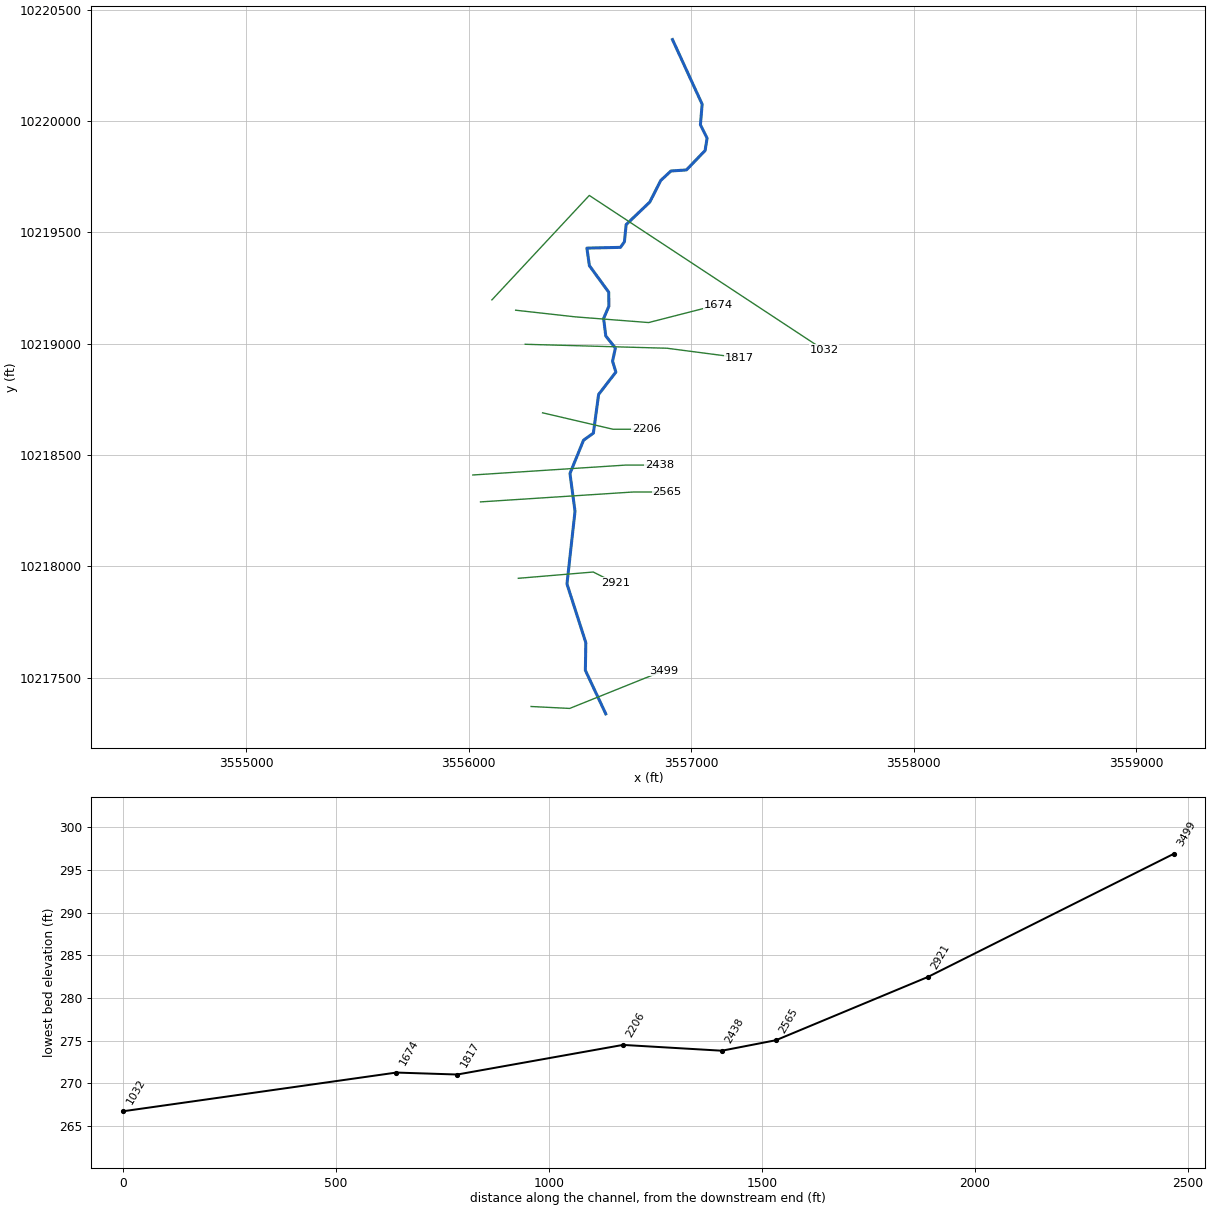
--- BURTON CREEK TRIB 1.prj (project) ---

Proj Title=BURTON CREEK TRIB 1 Base Level Engineering
Current Plan=p01
Default Exp/Contr=0.3,0.1
English Units
Geom File=g01
Flow File=f01
Plan File=p01
Y Axis Title=Elevation
X Axis Title(PF)=Main Channel Distance
X Axis Title(XS)=Station
BEGIN DESCRIPTION:
BURTON CREEK TRIB 1
END DESCRIPTION:
DSS Export Rating Curves= 0
DSS Export Rating Curve Sorted= 0
DSS Export Volume Flow Curves= 0
DXF OffsetX= 0
DXF OffsetY= 0
DXF ScaleX= 1
DXF ScaleY= 10

--- BURTON CREEK TRIB 1.p01 (plan) ---

Plan Title=Multiple Run
Short Identifier=Multiple
Geom File=g01
Flow File=f01
Subcritical Flow
K Sum by GR= 0
Std Step Tol= 0.01
Critical Tol= 0.01
Num of Std Step Trials= 20
Max Error Tol= 0.3
Flow Tol Ratio= 0.001
Split Flow NTrial= 30
Split Flow Tol= 0.02
Split Flow Ratio= 0.02
Log Output Level= 0
Friction Slope Method= 1
Unsteady Friction Slope Method= 2
Unsteady Bridges Friction Slope Method= 1
Parabolic Critical Depth
Global Vel Dist=  1 , 1 , 1
Global Log Level= 0
CheckData=True
Encroach Param= -1, 0, 0, 0
BEGIN DESCRIPTION:
Multiple Run
END DESCRIPTION:

--- BURTON CREEK TRIB 1.f01 (steady flow) ---

Flow Title=Multiple
Number of Profiles=7
Profile Names=10-year,25-year,50-year,1pct_min,100-year,1pct_plu,500-year
River Rch & RM= BURTON CREEK TRI,Reach-1,3499
     183     230     265     226     306     414     405
Boundary for River Rch & Prof#=BURTON CREEK TRI,Reach-1,1
Up Type=0
Dn Type=3
Dn Slope=0.005
Boundary for River Rch & Prof#=BURTON CREEK TRI,Reach-1,2
Up Type=0
Dn Type=3
Dn Slope=0.005
Boundary for River Rch & Prof#=BURTON CREEK TRI,Reach-1,3
Up Type=0
Dn Type=3
Dn Slope=0.005
Boundary for River Rch & Prof#=BURTON CREEK TRI,Reach-1,4
Up Type=0
Dn Type=3
Dn Slope=0.005
Boundary for River Rch & Prof#=BURTON CREEK TRI,Reach-1,5
Up Type=0
Dn Type=3
Dn Slope=0.005
Boundary for River Rch & Prof#=BURTON CREEK TRI,Reach-1,6
Up Type=0
Dn Type=3
Dn Slope=0.005
Boundary for River Rch & Prof#=BURTON CREEK TRI,Reach-1,7
Up Type=0
Dn Type=3
Dn Slope=0.005

--- BURTON CREEK TRIB 1.g01 (geometry) ---

Geom Title=Existing Conditions
Program Version=4.10

River Reach=BURTON CREEK TRI,Reach-1
Reach XY= 30
      3556616.26     10217336.78      3556524.61     10217532.11
      3556526.69     10217656.42      3556441.97     10217920.28
      3556478.16     10218246.46      3556455.45     10218416.19
      3556516.18     10218565.49      3556560.62     10218597.78
      3556584.23     10218771.74      3556661.66     10218871.74
      3556646.73     10218921.04      3556659.58     10218979.72
      3556616.36     10219033.96      3556606.61     10219112.33
      3556630.13     10219167.47      3556629.65     10219230.48
      3556542.74     10219349.69      3556531.45     10219428.68
      3556682.23       10219432.      3556700.03     10219457.12
      3556707.81      10219534.2      3556814.08     10219635.55
      3556863.05     10219732.36      3556909.12     10219775.03
      3556978.46     10219779.72      3557062.37     10219866.79
      3557071.45     10219922.38      3557041.37     10219982.53
      3557049.19     10220074.98      3556915.89     10220365.31

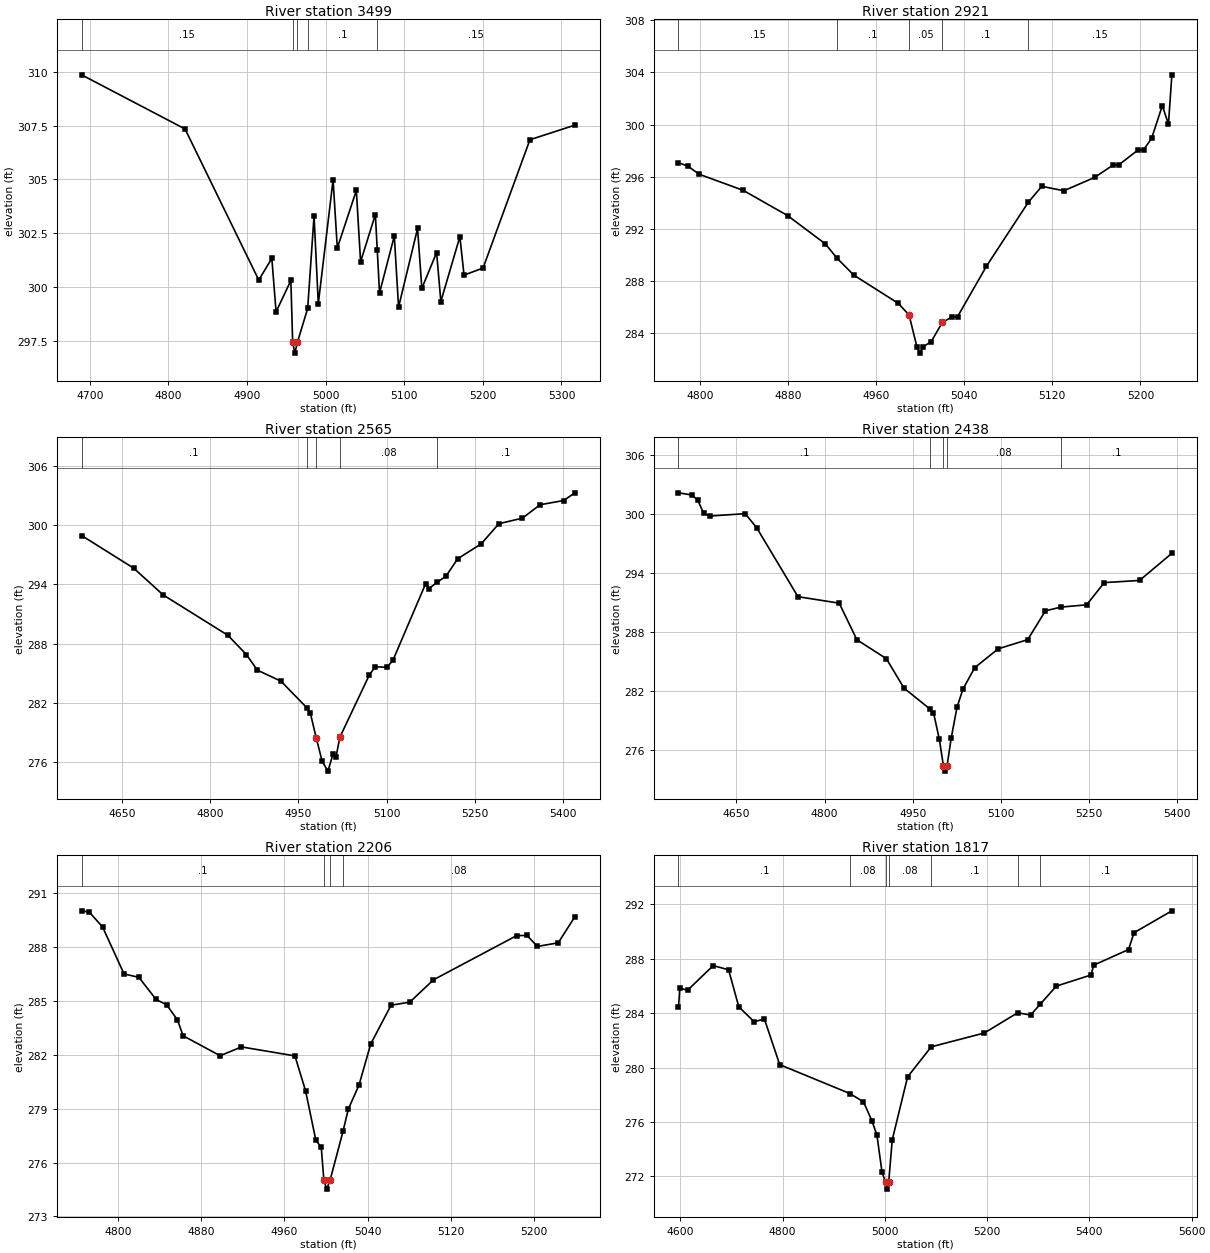
Type RM Length L Ch R = 1 ,3499    ,578,578,578
BEGIN DESCRIPTION:
BURTON CREEK TRIB 1 6.0
END DESCRIPTION:
XS GIS Cut Line= 3
      3556280.63     10217369.76      3556454.25     10217361.08
      3556875.26     10217530.35
#Sta/Elev= 30
  4689.6  309.87  4821.2  307.35    4915  300.32  4931.6  301.33    4937  298.84
  4955.8   300.3  4958.1  297.42  4960.9  296.92  4964.1  297.42  4977.2     299
  4985.3  303.31  4990.7  299.22  5009.5  304.98  5014.9  301.81  5039.1  304.49
  5044.5  301.17  5063.3  303.37  5065.7  301.72  5068.6  299.72  5087.4  302.37
  5092.8  299.06    5117  302.72  5122.4  299.93  5141.2   301.6  5146.6  299.32
  5170.8  302.34  5176.1  300.55  5200.3  300.88  5259.9  306.85  5317.2  307.53
#Mann= 5 ,-1 , 0
  4689.6     .15       0  4958.1     .07       0  4964.1     .15       0
  4977.2      .1       0  5065.7     .15       0
Bank Sta=4958.1,4964.1
XS Rating Curve= 0 ,0
Exp/Cntr=0.3,0.1

Type RM Length L Ch R = 1 ,2921    ,356,356,356
BEGIN DESCRIPTION:
BURTON CREEK TRIB 1 5.0
END DESCRIPTION:
XS GIS Cut Line= 3
      3556223.49     10217945.53      3556560.15     10217973.83
      3556658.59     10217924.61
#Sta/Elev= 30
  4780.6  297.07  4789.1  296.81  4799.3  296.19  4839.4  294.95  4879.6  293.02
    4914  290.84  4924.5  289.75  4939.8  288.45  4979.9   286.3  4989.9   285.4
    4997  282.97  4999.7  282.47    5003  282.97    5010  283.35  5020.1  284.82
  5028.9  285.25  5033.9  285.26  5060.2  289.14  5098.1  294.03  5110.4  295.26
  5130.4  294.92  5158.3  295.94  5175.1  296.89  5180.7  296.93  5197.4  298.02
    5203  298.08  5210.1  298.94  5219.8  301.44  5225.4  300.04  5228.5  303.81
#Mann= 5 ,-1 , 0
  4780.6     .15       0  4924.5      .1       0  4989.9     .05       0
  5020.1      .1       0  5098.1     .15       0
Bank Sta=4989.9,5020.1
XS Rating Curve= 0 ,0
Exp/Cntr=0.3,0.1

Type RM Length L Ch R = 1 ,2565    ,127,127,127
BEGIN DESCRIPTION:
BURTON CREEK TRIB 1 4.1
END DESCRIPTION:
XS GIS Cut Line= 3
      3556053.73     10218288.75      3556741.48     10218333.33
      3556891.49     10218333.33
#Sta/Elev= 30
  4581.3  298.96  4669.9  295.65    4720  292.94  4830.2  288.84  4861.6  286.89
  4880.3  285.31  4920.4  284.19    4964  281.52  4970.5  280.92  4980.5  278.42
  4990.5  276.06  5000.3  275.07  5009.1  276.82  5014.1  276.52  5020.6  278.51
  5070.7  284.81  5080.7  285.65  5100.8   285.6  5110.8   286.3  5166.5  294.07
  5171.5  293.55  5186.6  294.24    5201  294.83    5221   296.6  5261.1  298.12
  5291.1  300.16  5331.1  300.72  5361.1  302.08  5401.1  302.51  5420.5  303.29
#Mann= 5 ,-1 , 0
  4581.3      .1       0    4964     .08       0  4980.5     .05       0
  5020.6     .08       0  5186.6      .1       0
Bank Sta=4980.5,5020.6
XS Rating Curve= 0 ,0
Exp/Cntr=0.3,0.1

Type RM Length L Ch R = 1 ,2438    ,232,232,232
BEGIN DESCRIPTION:
BURTON CREEK TRIB 1 4.2
END DESCRIPTION:
XS GIS Cut Line= 3
      3556019.32     10218409.59       3556707.1     10218454.17
      3556857.07     10218454.17
#Sta/Elev= 30
  4551.6  302.14  4574.4  301.92  4584.5  301.38  4594.5  300.04  4604.5  299.78
  4665.1  300.02  4684.7  298.58  4754.8  291.58    4825  290.92    4855   287.2
  4905.1  285.28  4935.2  282.28  4979.5  280.15  4985.3   279.8  4995.3  277.07
  5002.3  274.34  5005.1  273.84  5008.3  274.34  5015.4  277.18  5025.4  280.35
  5035.4  282.17  5055.4  284.36  5095.5  286.28  5145.6  287.21  5175.7  290.14
    5202  290.52  5245.8  290.75  5275.8  293.01  5335.8  293.23  5390.8  295.99
#Mann= 5 ,-1 , 0
  4551.6      .1       0  4979.5     .08       0  5002.3     .07       0
  5008.3     .08       0    5202      .1       0
Bank Sta=5002.3,5008.3
XS Rating Curve= 0 ,0
Exp/Cntr=0.3,0.1

Type RM Length L Ch R = 1 ,2206    ,389,389,389
BEGIN DESCRIPTION:
BURTON CREEK TRIB 1 4.0
END DESCRIPTION:
XS GIS Cut Line= 3
      3556332.41     10218688.92      3556649.26     10218614.97
      3556798.19     10218614.97
#Sta/Elev= 30
    4765     290  4772.4  289.93  4785.2   289.1  4805.8  286.49  4820.1   286.3
  4836.6  285.07  4846.8  284.77  4857.1  283.94  4862.6  283.05  4898.2  281.94
  4918.7  282.43  4970.1  281.93  4980.3  279.99  4990.2  277.24  4995.4  276.85
  4997.9  275.02  5000.6  274.52  5003.9  275.02  5016.3  277.73  5021.4  278.97
  5031.7  280.31    5043   282.6  5062.5  284.75  5080.5  284.92  5103.2  286.16
  5183.2  288.62  5193.2  288.63  5203.2  288.02  5223.2  288.22  5239.3  289.68
#Mann= 4 ,-1 , 0
    4765      .1       0  4997.9     .07       0  5003.9      .1       0
  5016.3     .08       0
Bank Sta=4997.9,5003.9
XS Rating Curve= 0 ,0
Exp/Cntr=0.3,0.1

Type RM Length L Ch R = 1 ,1817    ,143,143,143
BEGIN DESCRIPTION:
BURTON CREEK TRIB 1 3.0
END DESCRIPTION:
XS GIS Cut Line= 3
      3556254.19     10218996.71      3556891.13     10218978.92
      3557216.19     10218936.52
#Sta/Elev= 30
  4596.3  284.42  4598.9  285.84  4614.2  285.69  4664.2   287.5  4694.3  287.19
  4714.3  284.46  4744.3  283.37  4764.3  283.57  4794.3  280.21  4931.8  278.08
  4958.1  277.47  4974.4   276.1  4984.4  275.03  4994.4  272.29  5001.4  271.55
  5004.1  271.05  5007.4  271.55  5014.4  274.68  5044.4  279.31  5090.6  281.52
  5194.4  282.54  5259.8  284.03  5284.9  283.86  5303.4  284.64  5335.3  285.99
  5403.3  286.81  5408.3  287.53  5476.5  288.68  5487.3  289.92  5561.3  291.53
#Mann= 7 ,-1 , 0
  4596.3      .1       0  4931.8     .08       0  5001.4     .07       0
  5007.4     .08       0  5090.6      .1       0  5259.8     .08       0
  5303.4      .1       0
Bank Sta=5001.4,5007.4
XS Rating Curve= 0 ,0
Exp/Cntr=0.3,0.1

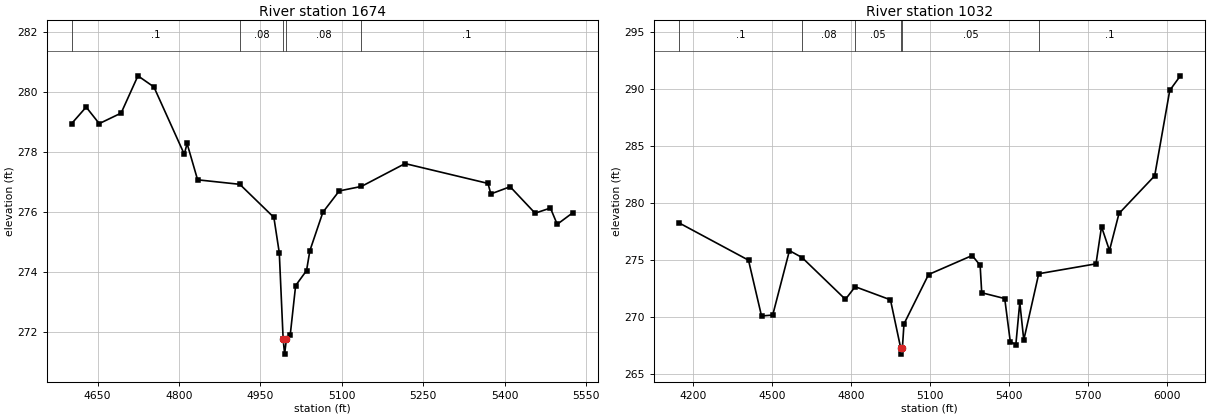
Type RM Length L Ch R = 1 ,1674    ,642,642,642
BEGIN DESCRIPTION:
BURTON CREEK TRIB 1 2.0
END DESCRIPTION:
XS GIS Cut Line= 4
      3556211.47     10219149.72      3556480.55     10219119.73
      3556808.94     10219094.26      3557122.39     10219174.61
#Sta/Elev= 30
  4602.3  278.95  4629.1   279.5  4653.2  278.95  4693.5   279.3  4724.5  280.54
  4753.9  280.17  4809.9  277.93    4815  278.29  4834.4  277.08  4912.2  276.93
  4974.9  275.83  4984.9  274.65    4992  271.78  4994.7  271.28    4998  271.78
    5005  271.91    5015  273.56  5035.1  274.06  5041.2  274.72  5065.2     276
  5095.3  276.71  5136.2  276.86  5216.6  277.62  5369.4  276.96  5374.6  276.61
  5410.2  276.85  5456.1  275.97  5484.4  276.14  5496.9   275.6    5526  275.99
#Mann= 5 ,-1 , 0
  4602.3      .1       0  4912.2     .08       0    4992     .07       0
    4998     .08       0  5136.2      .1       0
Bank Sta=4992,4998
XS Rating Curve= 0 ,0
Exp/Cntr=0.3,0.1

Type RM Length L Ch R = 1 ,1032    ,0,0,0
BEGIN DESCRIPTION:
BURTON CREEK TRIB 1 1.0
END DESCRIPTION:
XS GIS Cut Line= 3
      3556104.76     10219195.98      3556542.29     10219665.25
      3557595.78      10218971.3
#Sta/Elev= 30
  4146.8  278.27  4410.8  274.99  4460.2  270.09  4502.7  270.17  4566.2  275.83
  4614.2  275.22  4778.7  271.55  4815.7  272.66  4949.6  271.51  4988.8  267.24
  4991.5  266.74  4994.8  267.24  5000.9  269.39  5094.2  273.73  5259.8   275.4
    5290  274.54    5296  272.13  5383.3  271.62  5404.4  267.84  5425.5  267.57
  5440.5  271.28  5455.6  267.98  5512.4   273.8  5729.7  274.67  5750.7  277.93
  5780.9  275.84    5817  279.09  5952.5   282.4  6009.7   289.9  6049.9  291.18
#Mann= 6 ,-1 , 0
  4146.8      .1       0  4614.2     .08       0  4815.7     .05       0
  4988.8     .04       0  4994.8     .05       0  5512.4      .1       0
Bank Sta=4988.8,4994.8
XS Rating Curve= 0 ,0
Exp/Cntr=0.3,0.1

Chan Stop Cuts=-1
Use User Specified Reach Order=0
Composite Channel Slope=5