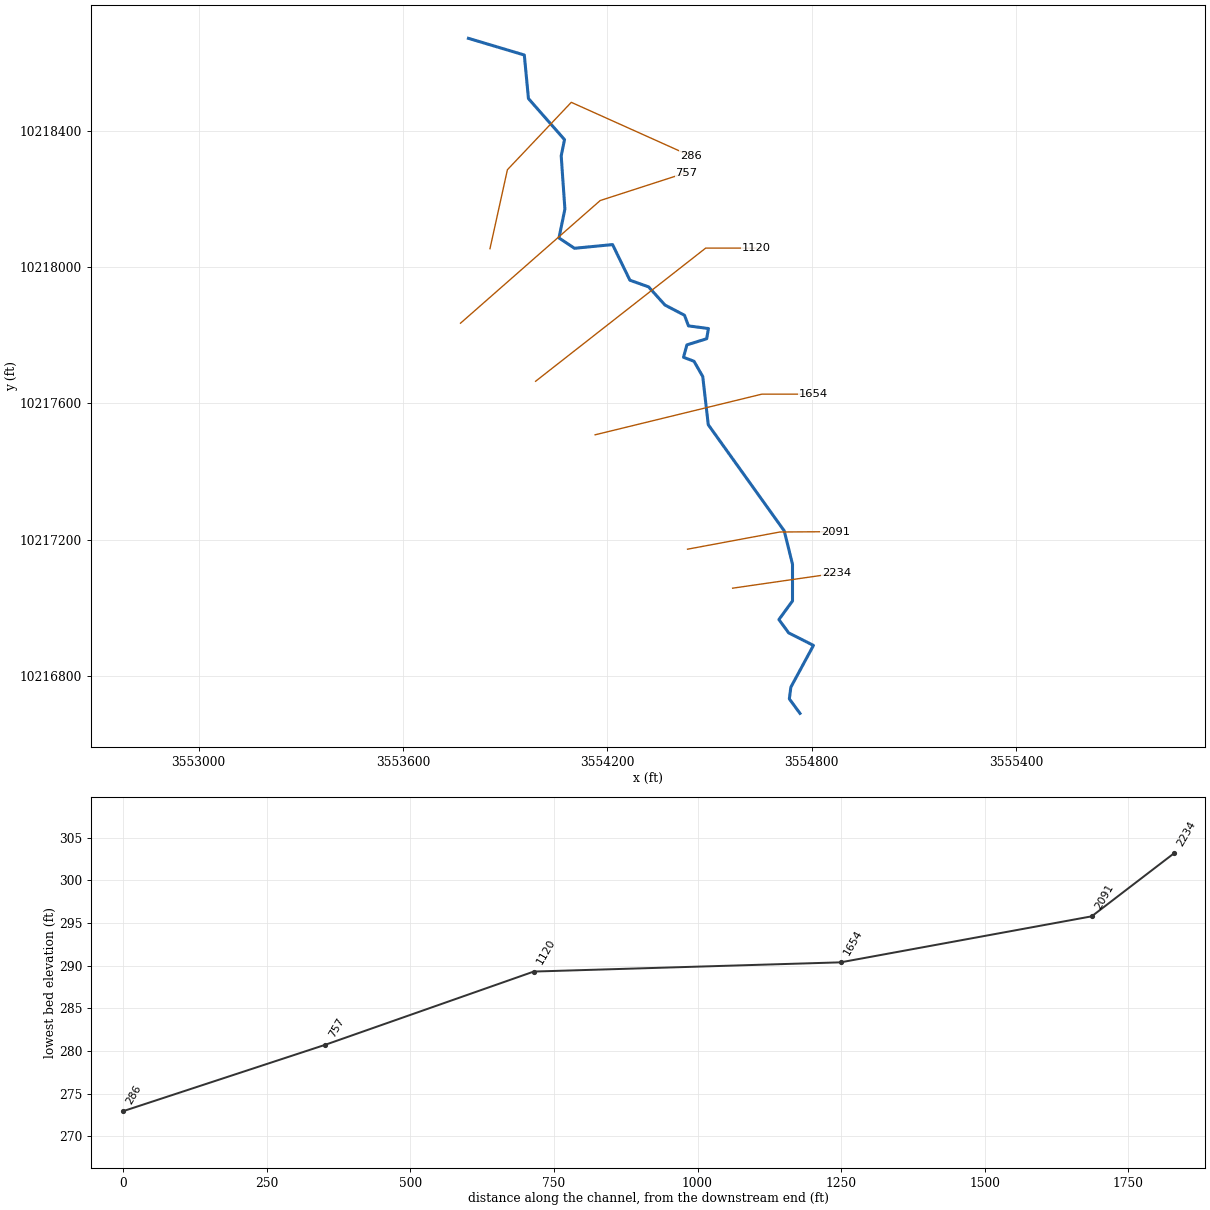
--- BURTON CREEK TRIB C 1.prj (project) ---

Proj Title=BURTON CREEK TRIB C 1 Base Level Engineering
Current Plan=p01
Default Exp/Contr=0.3,0.1
English Units
Geom File=g01
Flow File=f01
Plan File=p01
Y Axis Title=Elevation
X Axis Title(PF)=Main Channel Distance
X Axis Title(XS)=Station
BEGIN DESCRIPTION:
BURTON CREEK TRIB C 1
END DESCRIPTION:
DSS Export Rating Curves= 0
DSS Export Rating Curve Sorted= 0
DSS Export Volume Flow Curves= 0
DXF OffsetX= 0
DXF OffsetY= 0
DXF ScaleX= 1
DXF ScaleY= 10

--- BURTON CREEK TRIB C 1.p01 (plan) ---

Plan Title=Multiple Run
Short Identifier=Multiple
Geom File=g01
Flow File=f01
Subcritical Flow
K Sum by GR= 0
Std Step Tol= 0.01
Critical Tol= 0.01
Num of Std Step Trials= 20
Max Error Tol= 0.3
Flow Tol Ratio= 0.001
Split Flow NTrial= 30
Split Flow Tol= 0.02
Split Flow Ratio= 0.02
Log Output Level= 0
Friction Slope Method= 1
Unsteady Friction Slope Method= 2
Unsteady Bridges Friction Slope Method= 1
Parabolic Critical Depth
Global Vel Dist=  1 , 1 , 1
Global Log Level= 0
CheckData=True
Encroach Param= -1, 0, 0, 0
BEGIN DESCRIPTION:
Multiple Run
END DESCRIPTION:

--- BURTON CREEK TRIB C 1.f01 (steady flow) ---

Flow Title=Multiple
Program Version=4.10
Number of Profiles= 7
Profile Names=10-year,25-year,50-year,1pct_min,100-year,1pct_plu,500-year
River Rch & RM=BURTON CREEK TRI,Reach-1         ,2234
     133     163     186     157     212     286     273
Boundary for River Rch & Prof#=BURTON CREEK TRI,Reach-1         , 1
Up Type= 0
Dn Type= 3
Dn Slope=0.016
Boundary for River Rch & Prof#=BURTON CREEK TRI,Reach-1         , 2
Up Type= 0
Dn Type= 3
Dn Slope=0.016
Boundary for River Rch & Prof#=BURTON CREEK TRI,Reach-1         , 3
Up Type= 0
Dn Type= 3
Dn Slope=0.016
Boundary for River Rch & Prof#=BURTON CREEK TRI,Reach-1         , 4
Up Type= 0
Dn Type= 3
Dn Slope=0.016
Boundary for River Rch & Prof#=BURTON CREEK TRI,Reach-1         , 5
Up Type= 0
Dn Type= 3
Dn Slope=0.016
Boundary for River Rch & Prof#=BURTON CREEK TRI,Reach-1         , 6
Up Type= 0
Dn Type= 3
Dn Slope=0.016
Boundary for River Rch & Prof#=BURTON CREEK TRI,Reach-1         , 7
Up Type= 0
Dn Type= 3
Dn Slope=0.016
DSS Import GetInterval= 0
DSS Import GetPeak= 0
DSS Import FillOption= 0

--- BURTON CREEK TRIB C 1.g01 (geometry) ---

Geom Title=Existing Conditions
Program Version=4.10

River Reach=BURTON CREEK TRI,Reach-1
Reach XY= 30
      3554765.36     10216689.94      3554734.11     10216732.52
      3554738.62     10216766.89      3554804.94     10216889.46
      3554732.16     10216926.27      3554703.51     10216965.33
      3554743.44     10217020.02      3554743.44     10217127.65
      3554719.14     10217225.75      3554496.14     10217537.31
      3554479.89     10217678.86      3554454.29     10217723.57
      3554423.47     10217735.29      3554433.45     10217771.75
      3554491.44     10217789.72      3554496.65     10217819.66
      3554438.05     10217827.48      3554426.34     10217858.73
      3554369.04     10217888.67      3554320.87     10217942.06
      3554266.06     10217961.59      3554215.22     10218066.15
      3554103.46      10218055.3      3554057.89     10218085.68
      3554075.25     10218170.31       3554064.4     10218326.56
      3554074.17     10218374.31      3553968.28     10218494.77
      3553956.09     10218622.67      3553792.11     10218671.64

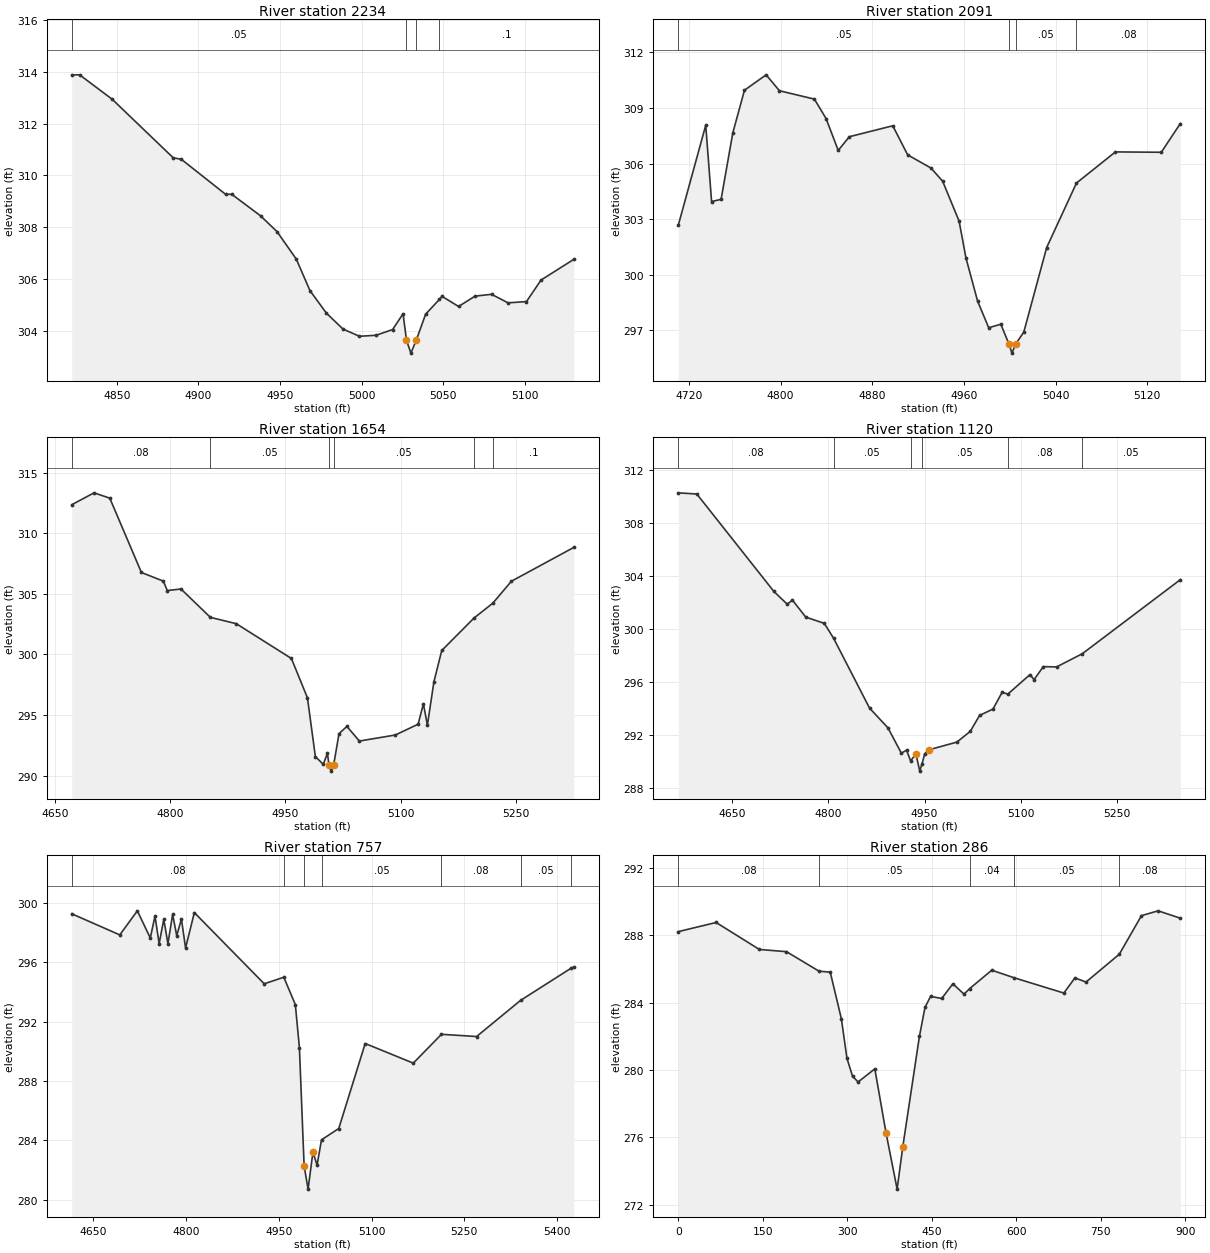
Type RM Length L Ch R = 1 ,2234    ,143,143,143
BEGIN DESCRIPTION:
BURTON CREEK TRIB C.1 5.0
END DESCRIPTION:
XS GIS Cut Line= 3
      3554567.66     10217057.47      3554664.66      10217071.5
      3554872.02     10217101.33
#Sta/Elev= 30
  4822.4  313.88  4827.2  313.88  4847.1  312.94  4884.5  310.68  4889.5  310.62
  4916.6  309.27  4920.4  309.27    4938  308.44  4948.1  307.83  4959.9  306.77
  4968.3  305.55  4978.4  304.68  4988.5  304.07  4998.6  303.79  5008.8  303.83
  5018.9  304.05  5025.3  304.66  5027.4  303.64  5030.1  303.14  5033.4  303.64
  5039.1  304.64  5047.5  305.21  5049.2  305.33  5059.3  304.94  5069.4  305.34
  5079.5  305.41  5089.6  305.08  5100.9  305.13  5109.8  305.96  5129.9  306.76
#Mann= 4 ,-1 , 0
  4822.4     .05       0  5027.4     .04       0  5033.4     .05       0
  5047.5      .1       0
Bank Sta=5027.4,5033.4
XS Rating Curve= 0 ,0
Exp/Cntr=0.3,0.1

Type RM Length L Ch R = 1 ,2091    ,437,437,437
BEGIN DESCRIPTION:
BURTON CREEK TRIB C.1 4.0
END DESCRIPTION:
XS GIS Cut Line= 3
      3554435.32     10217171.92      3554706.24      10217222.4
      3554868.75     10217223.36
#Sta/Elev= 30
  4710.7  302.66  4734.7  308.07  4739.8  303.95  4748.1  304.07  4758.3  307.65
  4768.5  309.96  4787.4  310.79    4799  309.93  4829.5  309.48  4839.7  308.43
  4850.3  306.71    4860  307.45  4897.9  308.04  4910.9  306.47  4931.2  305.76
  4941.4  305.05  4955.8  302.89  4961.7  300.92  4971.9  298.58  4981.6  297.14
  4992.2  297.33  4999.2  296.27  5001.9  295.77  5005.2  296.27  5012.2   296.9
  5032.2  301.47  5058.2  304.95  5092.2  306.63  5132.2  306.61  5148.8  308.16
#Mann= 4 ,-1 , 0
  4710.7     .05       0  4999.2     .04       0  5005.2     .05       0
  5058.2     .08       0
Bank Sta=4999.2,5005.2
XS Rating Curve= 0 ,0
Exp/Cntr=0.3,0.1

Type RM Length L Ch R = 1 ,1654    ,534,534,534
BEGIN DESCRIPTION:
BURTON CREEK TRIB C.1 3.1
END DESCRIPTION:
XS GIS Cut Line= 3
      3554163.97     10217507.73      3554653.44     10217627.08
      3554803.43     10217627.08
#Sta/Elev= 30
  4671.8  312.35  4700.8  313.33  4721.3  312.89  4762.5  306.76    4791  306.05
  4796.2  305.27    4814   305.4  4852.3  303.06    4886  302.54  4957.8  299.67
  4978.7  296.42    4989  291.58  4999.3  290.94  5004.7  291.85  5006.8  290.88
  5009.5  290.38  5012.8  290.88  5019.8  293.47  5030.1  294.07  5046.3  292.86
  5093.2  293.36  5122.8  294.25  5129.7  295.93  5134.9  294.17  5143.4  297.75
  5153.6  300.33  5195.7  303.01  5220.1  304.23  5244.3  306.04  5325.6  308.83
#Mann= 6 ,-1 , 0
  4671.8     .08       0  4852.3     .05       0  5006.8     .04       0
  5012.8     .05       0  5195.7     .08       0  5220.1      .1       0
Bank Sta=5006.8,5012.8
XS Rating Curve= 0 ,0
Exp/Cntr=0.3,0.1

Type RM Length L Ch R = 1 ,1120    ,363,363,363
BEGIN DESCRIPTION:
BURTON CREEK TRIB C.1 3.0
END DESCRIPTION:
XS GIS Cut Line= 3
      3553989.22     10217664.88      3554488.61     10218055.86
      3554637.87     10218055.86
#Sta/Elev= 30
  4565.7  310.26  4594.7  310.17    4715  302.83  4735.8  301.87  4743.9  302.18
  4764.7   300.9  4793.6  300.43  4808.1  299.31  4864.2  294.05  4893.1  292.55
  4913.9  290.65    4922  290.88  4928.4  290.06  4936.5  290.62  4942.6   289.3
  4945.8   289.8  4950.4  290.61  4957.3  290.91  5000.7  291.49  5021.5   292.3
    5036   293.5  5056.8  293.97  5071.2  295.24    5080   295.1  5114.6  296.57
    5121  296.19  5135.4  297.17  5156.2  297.15  5196.2  298.14  5349.2  303.72
#Mann= 6 ,-1 , 0
  4565.7     .08       0  4808.1     .05       0  4928.4     .04       0
  4945.8     .05       0    5080     .08       0  5196.2     .05       0
Bank Sta=4936.5,4957.3
XS Rating Curve= 0 ,0
Exp/Cntr=0.3,0.1

Type RM Length L Ch R = 1 ,757     ,352,352,352
BEGIN DESCRIPTION:
BURTON CREEK TRIB C.1 2.0
END DESCRIPTION:
XS GIS Cut Line= 3
      3553768.86     10217835.41      3554178.87     10218195.45
      3554431.72     10218277.25
#Sta/Elev= 30
  4615.6  299.25  4693.2  297.83  4721.6  299.45  4742.5  297.62  4750.1   299.1
  4756.8  297.24  4764.3  298.88    4771  297.24  4778.6  299.21  4785.2  297.78
  4792.8   298.9  4799.5  296.95  4813.7  299.33  4926.6  294.54  4958.3  294.98
  4976.9  293.14  4983.5  290.23  4991.1  282.28  4997.5  280.72  5005.4  283.23
    5012  282.33  5019.2  284.04  5047.1   284.8  5089.8  290.52  5167.5   289.2
  5213.1  291.14  5269.8  290.99  5340.8  293.42  5422.6  295.59    5427  295.67
#Mann= 7 ,-1 , 0
  4615.6     .08       0  4958.3     .05       0  4991.1     .04       0
  5019.2     .05       0  5213.1     .08       0  5340.8     .05       0
  5422.6     .08       0
Bank Sta=4991.1,5005.4
XS Rating Curve= 0 ,0
Exp/Cntr=0.3,0.1

Type RM Length L Ch R = 1 ,286     ,0,0,0
BEGIN DESCRIPTION:
BURTON CREEK TRIB C.1 1.0
END DESCRIPTION:
XS GIS Cut Line= 4
      3553855.31     10218054.09      3553906.48     10218285.87
      3554093.98     10218483.79      3554444.17     10218326.46
#Sta/Elev= 30
       0288.207967.22585288.7504144.0554287.1496192.0738287.0201249.9846285.8605
269.7692285.8056289.5537283.0361 299.446280.6926309.3383279.6369319.2306279.2914
348.9075280.0714368.6921276.2883388.4767272.9382398.3689275.4094428.0458281.9942
437.9381283.7139447.8304284.3661 467.615284.2443487.3995285.1148507.1841284.5012
517.0275284.8243556.4009285.9209595.7743285.4753684.3644284.5659704.0511285.4649
723.7378285.2179782.7979286.8682822.1713289.1566851.7014289.4418891.0748289.0053
#Mann= 5 ,-1 , 0
       0     .08       0249.9846     .05       0517.0275     .04       0
595.7743     .05       0782.7979     .08       0
Bank Sta=368.6921,398.3689
XS Rating Curve= 0 ,0
Exp/Cntr=0.3,0.1
Stream Node=BURTON CREEK TRI,Reach-1         , 0 , 0 ,Upstream end
Stream Node=BURTON CREEK TRI,Reach-1         , 0 , 1 ,Downstream end

Chan Stop Cuts=-1
Use User Specified Reach Order=0
Composite Channel Slope=5