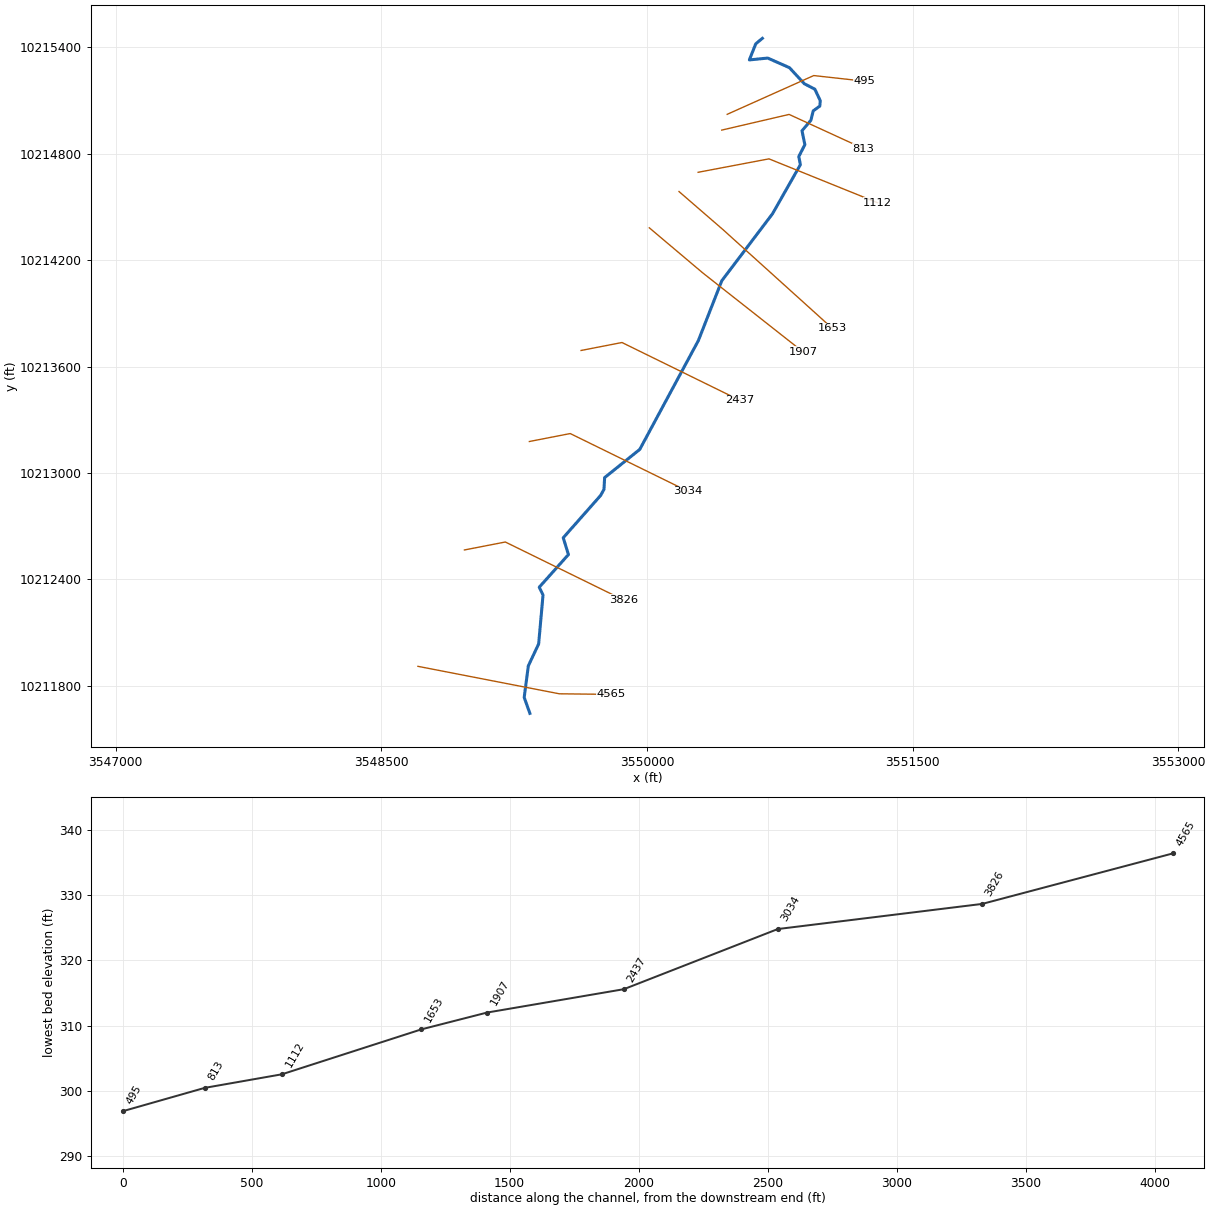
--- BURTON CREEK TRIB C 4.prj (project) ---

Proj Title=BURTON CREEK TRIB C 4 Base Level Engine
Current Plan=p01
Default Exp/Contr=0.3,0.1
English Units
Geom File=g01
Flow File=f01
Plan File=p01
Y Axis Title=Elevation
X Axis Title(PF)=Main Channel Distance
X Axis Title(XS)=Station
BEGIN DESCRIPTION:
BURTONS CREEK TRIB C 4
END DESCRIPTION:
DSS Export Rating Curves= 0
DSS Export Rating Curve Sorted= 0
DSS Export Volume Flow Curves= 0
DXF Filename=BURTONS CREEK TRIB C 4.
DXF OffsetX= 0
DXF OffsetY= 0
DXF ScaleX= 1
DXF ScaleY= 10

--- BURTON CREEK TRIB C 4.p01 (plan) ---

Plan Title=Multiple Run
Short Identifier=Multiple
Geom File=g01
Flow File=f01
Subcritical Flow
K Sum by GR= 0
Std Step Tol= 0.01
Critical Tol= 0.01
Num of Std Step Trials= 20
Max Error Tol= 0.3
Flow Tol Ratio= 0.001
Split Flow NTrial= 30
Split Flow Tol= 0.02
Split Flow Ratio= 0.02
Log Output Level= 0
Friction Slope Method= 1
Unsteady Friction Slope Method= 2
Unsteady Bridges Friction Slope Method= 1
Parabolic Critical Depth
Global Vel Dist=  1 , 1 , 1
Global Log Level= 0
CheckData=True
Encroach Param= -1, 0, 0, 0
BEGIN DESCRIPTION:
Multiple Run
END DESCRIPTION:

--- BURTON CREEK TRIB C 4.f01 (steady flow) ---

Flow Title=Multiple
Program Version=4.10
Number of Profiles= 7
Profile Names=10-year,25-year,50-year,1pct_min,100-year,1pct_plu,500-year
River Rch & RM=BURTONS CREEK TR,Reach-1         ,4565
     264     339     398     344     465     629     634
River Rch & RM=BURTON CREEK TR,Reach-1         ,4565
     264     339     398     344     465     629     634
Boundary for River Rch & Prof#=BURTON CREEK TR,Reach-1         , 1
Up Type= 0
Dn Type= 3
Dn Slope=0.01
Boundary for River Rch & Prof#=BURTON CREEK TR,Reach-1         , 2
Up Type= 0
Dn Type= 3
Dn Slope=0.01
Boundary for River Rch & Prof#=BURTON CREEK TR,Reach-1         , 3
Up Type= 0
Dn Type= 3
Dn Slope=0.01
Boundary for River Rch & Prof#=BURTON CREEK TR,Reach-1         , 4
Up Type= 0
Dn Type= 3
Dn Slope=0.01
Boundary for River Rch & Prof#=BURTON CREEK TR,Reach-1         , 5
Up Type= 0
Dn Type= 3
Dn Slope=0.01
Boundary for River Rch & Prof#=BURTON CREEK TR,Reach-1         , 6
Up Type= 0
Dn Type= 3
Dn Slope=0.01
Boundary for River Rch & Prof#=BURTON CREEK TR,Reach-1         , 7
Up Type= 0
Dn Type= 3
Dn Slope=0.01
DSS Import GetInterval= 0
DSS Import GetPeak= 0
DSS Import FillOption= 0

--- BURTON CREEK TRIB C 4.g01 (geometry) ---

Geom Title=Existing Conditions
Program Version=4.10

River Reach=BURTON CREEK TR ,Reach-1
Reach XY= 30
      3549339.21      10211643.5      3549307.12     10211733.65
      3549330.53     10211911.73      3549388.69     10212034.99
      3549413.46      10212311.2      3549392.16      10212355.3
      3549556.95     10212539.38       3549527.6     10212634.18
      3549738.66     10212872.79      3549757.76     10212907.51
      3549761.23     10212973.48      3549959.63     10213132.52
      3550290.75     10213746.92      3550422.69     10214083.73
      3550709.72     10214462.63      3550866.58     10214738.69
      3550857.66     10214784.73      3550891.91     10214851.67
      3550875.74     10214930.08       3550925.9     10214989.31
      3550939.06     10215042.26      3550976.52      10215069.7
      3550978.97     10215099.91      3550948.46     10215164.65
      3550888.97     10215195.47      3550804.65     10215286.23
      3550682.11     10215340.35       3550578.7     10215329.97
      3550614.45     10215420.51      3550652.11     10215451.64

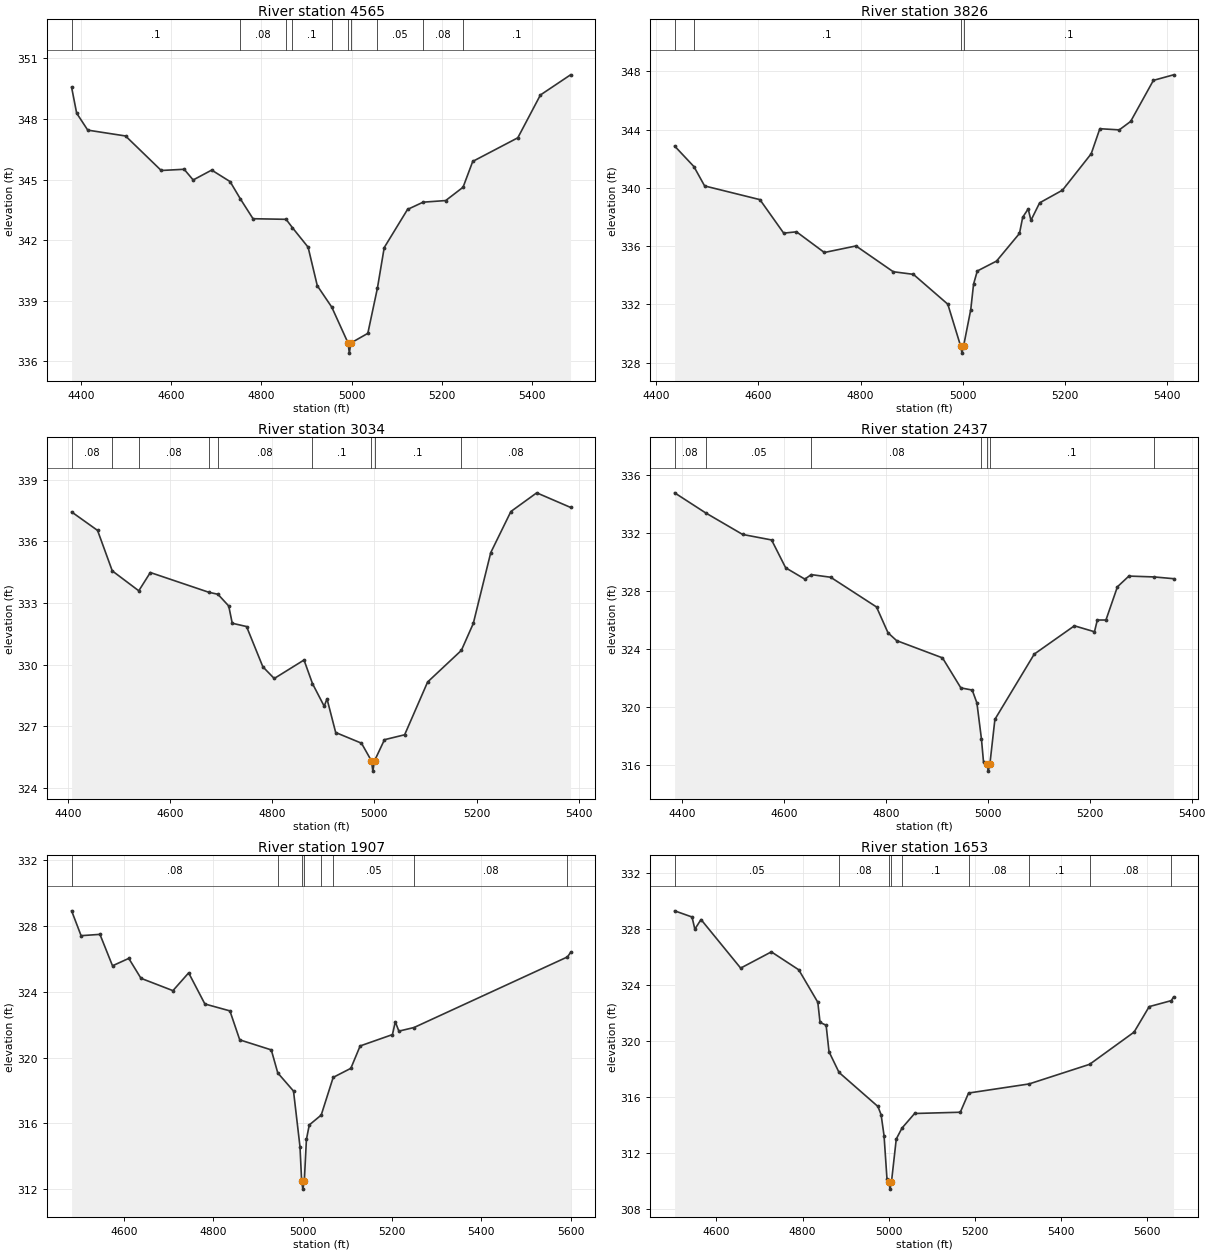
Type RM Length L Ch R = 1 ,4565    ,739,739,739
BEGIN DESCRIPTION:
BURTONS CREEK TRIB C.4 6.0
END DESCRIPTION:
XS GIS Cut Line= 3
      3548706.97     10211908.93      3549505.61     10211753.94
      3549799.05     10211750.61
#Sta/Elev= 30
  4378.7  349.57  4389.9  348.29  4414.5  347.45  4498.4  347.16  4577.5  345.45
  4628.4  345.51  4648.4  344.98  4689.5  345.47  4730.3   344.9  4753.2  344.04
  4781.2  343.06  4854.6  343.03  4868.5  342.62  4903.4  341.65  4923.8  339.74
  4955.9  338.68  4992.1   336.9  4994.9   336.4  4998.1   336.9  5035.9  337.38
  5057.2  339.62  5072.3  341.63    5124  343.52  5158.6  343.88  5208.7  343.96
  5247.2  344.62  5268.7   345.9  5368.7  347.07  5418.8  349.19  5485.7  350.19
#Mann= 10 ,-1 , 0
  4378.7      .1       0  4753.2     .08       0  4854.6     .05       0
  4868.5      .1       0  4955.9     .08       0  4992.1     .07       0
  4998.1     .08       0  5057.2     .05       0  5158.6     .08       0
  5247.2      .1       0
Bank Sta=4992.1,4998.1
XS Rating Curve= 0 ,0
Exp/Cntr=0.3,0.1

Type RM Length L Ch R = 1 ,3826    ,792,792,792
BEGIN DESCRIPTION:
BURTONS CREEK TRIB C.4 5.1
END DESCRIPTION:
XS GIS Cut Line= 3
      3548969.68     10212565.39      3549200.61     10212610.25
      3549867.61     10212283.47
#Sta/Elev= 30
  4435.6  342.88  4473.4  341.47  4494.4  340.14  4602.8   339.2  4649.4   336.9
  4674.5  336.99  4729.1  335.57  4791.1  336.02  4864.1  334.25  4903.6  334.07
  4971.1  332.02  4996.1  329.16  4998.9  328.66  5002.1  329.16  5016.1  331.65
  5021.6   333.4  5028.9   334.3  5066.6  334.98  5111.6  336.88  5117.9  337.99
  5128.6  338.56  5134.1  337.78  5151.1  338.98  5195.9  339.85  5252.2  342.35
  5269.1  344.07  5307.2  343.99  5329.5  344.57  5374.1  347.39  5413.6  347.77
#Mann= 4 ,-1 , 0
  4435.6     .15       0  4473.4      .1       0  4996.1     .07       0
  5002.1      .1       0
Bank Sta=4996.1,5002.1
XS Rating Curve= 0 ,0
Exp/Cntr=0.3,0.1

Type RM Length L Ch R = 1 ,3034    ,597,597,597
BEGIN DESCRIPTION:
BURTONS CREEK TRIB C.4 5.2
END DESCRIPTION:
XS GIS Cut Line= 3
       3549336.2     10213177.17      3549567.16     10213222.05
      3550233.06      10212895.8
#Sta/Elev= 30
  4407.3  337.43  4458.1  336.53  4486.9  334.56  4538.8  333.59  4561.4  334.48
  4675.7  333.52  4693.8  333.42  4714.9  332.85  4721.8  332.01  4749.8  331.85
  4781.7  329.89    4804  329.32  4862.3  330.22  4878.9  329.07  4901.8  327.97
  4907.3  328.33  4924.3  326.69  4974.8  326.17  4994.3  325.31  4997.1  324.81
  5000.3  325.31  5019.8  326.34  5059.3  326.58  5104.3  329.15  5170.4  330.69
  5193.7     332  5227.9  335.45  5267.3  337.45  5317.9  338.36  5384.1  337.65
#Mann= 9 ,-1 , 0
  4407.3     .08       0  4486.9      .1       0  4538.8     .08       0
  4675.7      .1       0  4693.8     .08       0  4878.9      .1       0
  4994.3     .07       0  5000.3      .1       0  5170.4     .08       0
Bank Sta=4994.3,5000.3
XS Rating Curve= 0 ,0
Exp/Cntr=0.3,0.1

Type RM Length L Ch R = 1 ,2437    ,530,530,530
BEGIN DESCRIPTION:
BURTONS CREEK TRIB C.4 5.3
END DESCRIPTION:
XS GIS Cut Line= 3
       3549628.3     10213690.78      3549859.24     10213735.65
      3550526.77      10213408.6
#Sta/Elev= 30
  4385.9  334.78  4446.6   333.4  4519.3  331.91  4576.1  331.53  4603.7  329.61
  4641.3  328.83  4653.9  329.14  4691.9  328.96  4781.9  326.91  4804.4  325.13
  4821.3  324.59  4911.3   323.4  4947.3  321.33  4969.6  321.18  4978.8  320.29
  4987.7  317.81  4991.8   316.2  4998.3  316.09  5001.1  315.59  5004.3  316.09
  5014.1  319.16  5091.3  323.66    5170  325.61  5209.4   325.2    5215  326.01
  5231.9  326.01  5254.4   328.3  5276.9  329.04  5326.6  328.98  5364.5  328.86
#Mann= 7 ,-1 , 0
  4385.9     .08       0  4446.6     .05       0  4653.9     .08       0
  4987.7      .1       0  4998.3     .07       0  5004.3      .1       0
  5326.6     .05       0
Bank Sta=4998.3,5004.3
XS Rating Curve= 0 ,0
Exp/Cntr=0.3,0.1

Type RM Length L Ch R = 1 ,1907    ,254,254,254
BEGIN DESCRIPTION:
BURTONS CREEK TRIB C.4 5.0
END DESCRIPTION:
XS GIS Cut Line= 3
      3550013.62     10214382.64      3550316.14     10214127.76
       3550882.7     10213682.13
#Sta/Elev= 30
  4483.1  328.92  4504.3  327.41  4546.5  327.49  4574.6  325.58    4611  326.03
  4638.3  324.82  4709.8  324.07    4745  325.15  4781.3  323.26  4837.3  322.84
  4859.3  321.08  4929.9  320.47  4944.4  319.07  4979.6  317.97  4994.1  314.59
  4997.8  312.51  5000.5  312.01  5003.8  312.51  5008.5  315.03  5014.9  315.91
  5041.6  316.51  5068.4   318.8  5107.9  319.35  5128.7  320.71    5201   321.4
  5207.3  322.18  5215.4  321.61  5249.3  321.83  5592.6  326.12  5599.5  326.39
#Mann= 8 ,-1 , 0
  4483.1     .08       0  4944.4      .1       0  4997.8     .07       0
  5003.8      .1       0  5041.6     .08       0  5068.4     .05       0
  5249.3     .08       0  5592.6      .1       0
Bank Sta=4997.8,5003.8
XS Rating Curve= 0 ,0
Exp/Cntr=0.3,0.1

Type RM Length L Ch R = 1 ,1653    ,541,541,541
BEGIN DESCRIPTION:
BURTONS CREEK TRIB C.4 4.0
END DESCRIPTION:
XS GIS Cut Line= 3
      3550181.38     10214587.26      3550429.61     10214372.57
      3551046.33     10213816.18
#Sta/Elev= 30
  4502.9  329.31  4543.3  328.87  4549.9     328  4564.2  328.69  4656.3  325.22
  4727.6  326.38  4791.2   325.1  4835.5  322.78  4840.6  321.35  4854.8  321.14
  4861.5  319.25  4884.8  317.77  4975.1  315.34  4982.5  314.75  4989.3  313.26
  4996.1  310.18  5000.5  309.94  5003.2  309.44  5006.5  309.94  5017.7  313.02
    5031   313.8  5060.3  314.84  5166.4  314.93  5185.6   316.3  5326.2  316.95
  5466.7  318.35    5570  320.65  5605.1  322.47  5656.6   322.9  5661.7  323.16
#Mann= 9 ,-1 , 0
  4502.9     .05       0  4884.8     .08       0  5000.5     .07       0
  5006.5     .08       0    5031      .1       0  5185.6     .08       0
  5326.2      .1       0  5466.7     .08       0  5656.6      .1       0
Bank Sta=5000.5,5006.5
XS Rating Curve= 0 ,0
Exp/Cntr=0.3,0.1

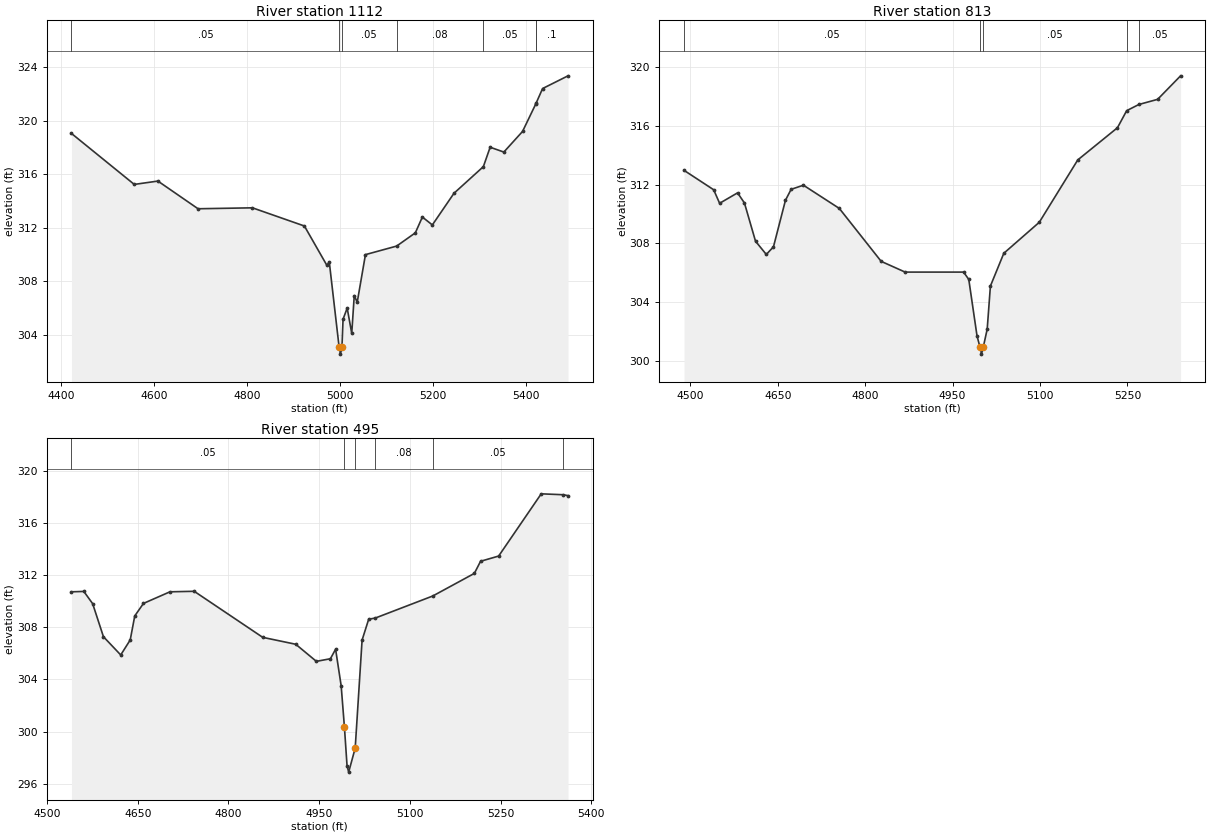
Type RM Length L Ch R = 1 ,1112    ,299,299,299
BEGIN DESCRIPTION:
BURTONS CREEK TRIB C.4 3.0
END DESCRIPTION:
XS GIS Cut Line= 3
      3550289.36     10214695.96      3550689.32     10214771.72
      3551302.84     10214524.04
#Sta/Elev= 30
  4421.6  319.05  4556.7  315.24  4607.6  315.49    4694  313.42  4811.1  313.49
  4922.9  312.13  4971.1   309.2  4976.5  309.43  4997.7  303.05  5000.4  302.55
  5003.7  303.05  5006.1  305.16    5015  305.99  5024.8   304.1  5030.2  306.93
  5036.6  306.43  5054.3  309.99  5121.5  310.63  5161.7  311.62  5176.8   312.8
  5198.3  312.21  5244.9  314.58  5308.1  316.57  5322.7  318.02  5352.2  317.66
  5392.4   319.2  5420.4  321.22  5421.7  321.32  5435.6  322.41  5490.3  323.36
#Mann= 7 ,-1 , 0
  4421.6     .05       0  4997.7     .04       0  5003.7     .05       0
  5121.5     .08       0  5308.1     .05       0  5420.4     .08       0
  5421.7      .1       0
Bank Sta=4997.7,5003.7
XS Rating Curve= 0 ,0
Exp/Cntr=0.3,0.1

Type RM Length L Ch R = 1 ,813     ,318,318,318
BEGIN DESCRIPTION:
BURTONS CREEK TRIB C.4 2.0
END DESCRIPTION:
XS GIS Cut Line= 3
      3550422.66     10214933.99      3550802.96     10215022.38
      3551222.43     10214830.03
#Sta/Elev= 30
  4489.3  312.97  4540.1  311.65  4550.3  310.73  4581.1  311.44  4592.9  310.75
  4611.9  308.15  4630.4  307.25  4642.7  307.77  4663.3  310.94    4673  311.68
  4694.1  311.96  4755.7  310.38  4827.5  306.78  4868.6  306.05  4968.9  306.05
  4977.8  305.55  4991.9  301.72  4996.8  300.97  4999.6  300.47  5002.8  300.97
  5009.4  302.17  5014.9   305.1  5037.9  307.33  5098.8  309.44  5164.8  313.68
  5232.9  315.87  5248.7  317.03  5269.6  317.45  5301.8   317.8  5341.2   319.4
#Mann= 5 ,-1 , 0
  4489.3     .05       0  4996.8     .04       0  5002.8     .05       0
  5248.7     .08       0  5269.6     .05       0
Bank Sta=4996.8,5002.8
XS Rating Curve= 0 ,0
Exp/Cntr=0.3,0.1

Type RM Length L Ch R = 1 ,495     ,0,0,0
BEGIN DESCRIPTION:
BURTONS CREEK TRIB C.4 1.0
END DESCRIPTION:
XS GIS Cut Line= 3
      3550453.51     10215023.04      3550942.11     10215241.64
      3551226.11      10215210.2
#Sta/Elev= 30
  4540.5  310.71  4560.9  310.74  4575.5   309.8  4593.3  307.27  4621.9  305.87
  4637.6  307.02  4645.1  308.86  4659.5  309.82  4703.3  310.71  4743.4  310.75
  4856.7  307.22  4911.3  306.69  4945.4  305.38  4968.6  305.58  4977.2  306.31
  4986.4  303.51  4991.8  300.34  4996.1  297.39  4998.8  296.89  5009.6  298.73
    5021  307.01  5031.9  308.61  5042.9   308.7  5137.9  310.39  5206.6  312.12
  5216.9  313.05  5246.8  313.45  5317.2  318.22  5353.7  318.15  5361.5  318.08
#Mann= 6 ,-1 , 0
  4540.5     .05       0  4991.8     .04       0  5009.6     .05       0
  5042.9     .08       0  5137.9     .05       0  5353.7     .08       0
Bank Sta=4991.8,5009.6
XS Rating Curve= 0 ,0
Exp/Cntr=0.3,0.1

Chan Stop Cuts=-1
Use User Specified Reach Order=0
Composite Channel Slope=5