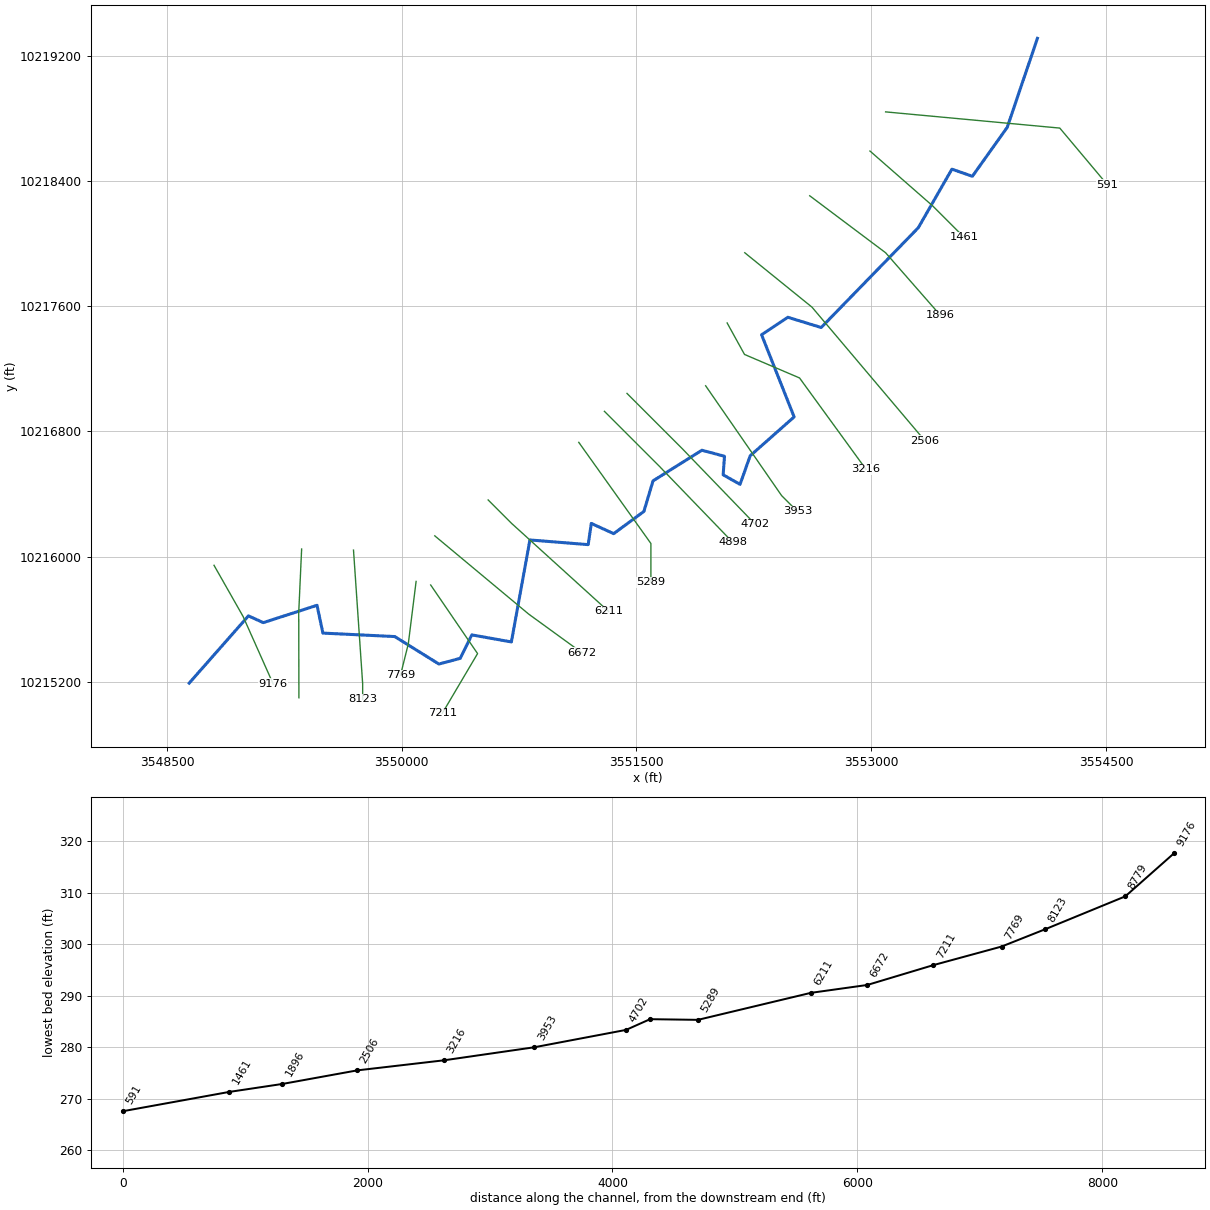
--- BURTON CREEK TRIB C.prj (project) ---

Proj Title=BURTON CREEK TRIB C Base Level Engineer
Current Plan=p01
Default Exp/Contr=0.3,0.1
English Units
Geom File=g01
Flow File=f01
Plan File=p01
Y Axis Title=Elevation
X Axis Title(PF)=Main Channel Distance
X Axis Title(XS)=Station
BEGIN DESCRIPTION:
BURTONS CREEK TRIB C
END DESCRIPTION:
DSS Export Rating Curves= 0
DSS Export Rating Curve Sorted= 0
DSS Export Volume Flow Curves= 0
DXF OffsetX= 0
DXF OffsetY= 0
DXF ScaleX= 1
DXF ScaleY= 10

--- BURTON CREEK TRIB C.p01 (plan) ---

Plan Title=Multiple Run
Short Identifier=Multiple
Geom File=g01
Flow File=f01
Subcritical Flow
K Sum by GR= 0
Std Step Tol= 0.01
Critical Tol= 0.01
Num of Std Step Trials= 20
Max Error Tol= 0.3
Flow Tol Ratio= 0.001
Split Flow NTrial= 30
Split Flow Tol= 0.02
Split Flow Ratio= 0.02
Log Output Level= 0
Friction Slope Method= 1
Unsteady Friction Slope Method= 2
Unsteady Bridges Friction Slope Method= 1
Parabolic Critical Depth
Global Vel Dist=  1 , 1 , 1
Global Log Level= 0
CheckData=True
Encroach Param= -1, 0, 0, 0
BEGIN DESCRIPTION:
Multiple Run
END DESCRIPTION:

--- BURTON CREEK TRIB C.f01 (steady flow) ---

Flow Title=Multiple
Program Version=4.10
Number of Profiles= 7
Profile Names=10-year,25-year,50-year,1pct_min,100-year,1pct_plu,500-year
River Rch & RM=BURTONS CREEK TR,Reach-1         ,9176
     230     295     345     297     401     543     544
River Rch & RM=BURTONS CREEK TR,Reach-1         ,6672
     584     789     955     848    1147    1552    1658
River Rch & RM=BURTONS CREEK TR,Reach-1         ,591
     611     825     999     887    1199    1622    1732
River Rch & RM=BURTON CREEK TR,Reach-1         ,9176
     230     295     345     297     401     543     544
River Rch & RM=BURTON CREEK TR,Reach-1         ,6672
     584     789     955     848    1147    1552    1658
River Rch & RM=BURTON CREEK TR,Reach-1         ,591
     611     825     999     887    1199    1622    1732
Boundary for River Rch & Prof#=BURTON CREEK TR,Reach-1         , 1
Up Type= 0
Dn Type= 3
Dn Slope=0.005
Boundary for River Rch & Prof#=BURTON CREEK TR,Reach-1         , 2
Up Type= 0
Dn Type= 3
Dn Slope=0.005
Boundary for River Rch & Prof#=BURTON CREEK TR,Reach-1         , 3
Up Type= 0
Dn Type= 3
Dn Slope=0.005
Boundary for River Rch & Prof#=BURTON CREEK TR,Reach-1         , 4
Up Type= 0
Dn Type= 3
Dn Slope=0.005
Boundary for River Rch & Prof#=BURTON CREEK TR,Reach-1         , 5
Up Type= 0
Dn Type= 3
Dn Slope=0.005
Boundary for River Rch & Prof#=BURTON CREEK TR,Reach-1         , 6
Up Type= 0
Dn Type= 3
Dn Slope=0.005
Boundary for River Rch & Prof#=BURTON CREEK TR,Reach-1         , 7
Up Type= 0
Dn Type= 3
Dn Slope=0.005
DSS Import GetInterval= 0
DSS Import GetPeak= 0
DSS Import FillOption= 0

--- BURTON CREEK TRIB C.g01 (geometry) ---

Geom Title=Existing Conditions
Program Version=4.10

River Reach=BURTON CREEK TR ,Reach-1
Reach XY= 30
      3548642.11     10215191.64      3549020.82     10215621.39
      3549115.64     10215578.14      3549458.94     10215688.81
      3549496.62     10215511.27      3549955.71     10215489.19
      3550237.81     10215313.59      3550374.11      10215349.9
      3550447.91      10215499.8      3550700.94     10215454.83
      3550819.27     10216106.45      3551191.68     10216076.53
      3551211.58     10216212.15      3551354.46     10216146.68
      3551547.58     10216288.52       3551605.9     10216483.97
      3551918.06      10216679.7       3552062.7     10216641.19
      3552054.02      10216522.6      3552162.01     10216461.74
      3552226.79     10216644.27      3552507.55     10216892.61
      3552299.54      10217417.7      3552467.52     10217529.29
      3552680.61     10217463.89      3553300.79     10218101.24
      3553515.65     10218475.63      3553646.53     10218430.31
      3553869.17     10218742.96      3554062.11     10219311.64

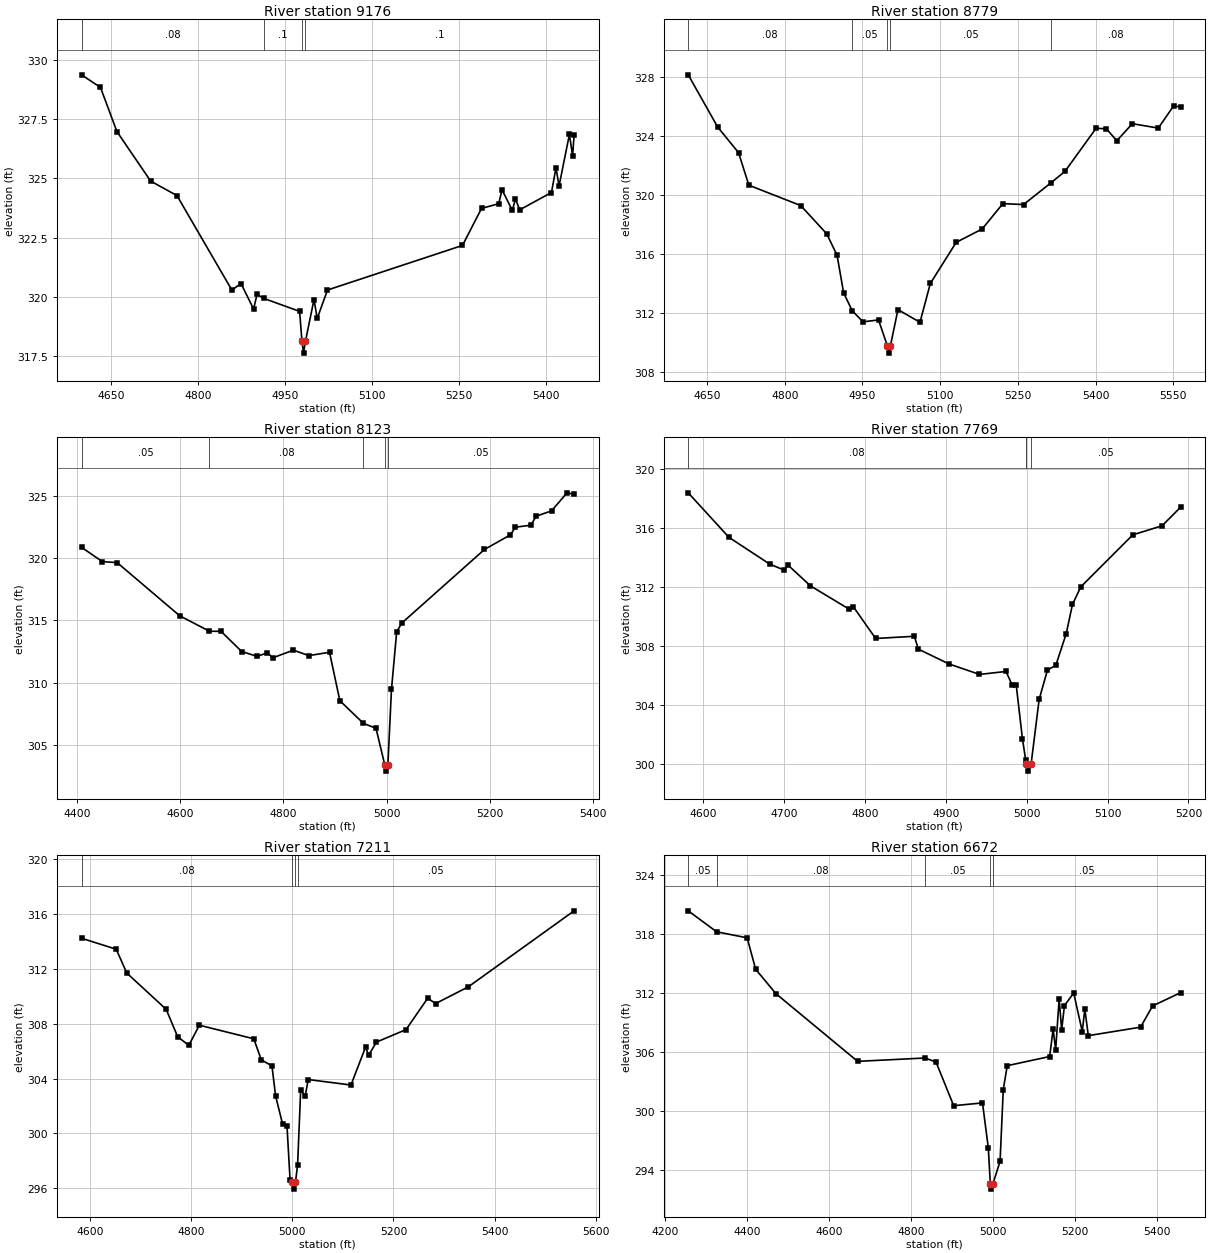
Type RM Length L Ch R = 1 ,9176    ,397,397,397
BEGIN DESCRIPTION:
BURTONS CREEK TRIB C 20.0
END DESCRIPTION:
XS GIS Cut Line= 3
      3548800.76     10215944.55      3548986.38     10215617.94
      3549178.98       10215186.
#Sta/Elev= 30
  4599.4  329.36    4632  328.83  4660.3  326.97  4718.5  324.88  4763.8  324.27
  4858.3  320.29  4874.2  320.56  4895.8  319.49  4901.8  320.11  4912.9  319.94
  4975.1  319.39  4979.1  318.13  4981.9  317.63  4985.1  318.13  4999.9  319.89
  5005.4  319.09  5023.1  320.29  5255.7  322.17  5288.5  323.73  5318.3  323.93
  5323.7  324.52  5341.5  323.65    5347  324.13  5354.2  323.67    5409   324.4
  5416.7  325.44  5422.1  324.68  5439.9  326.85  5445.4  325.95    5448  326.84
#Mann= 4 ,-1 , 0
  4599.4     .08       0  4912.9      .1       0  4979.1     .07       0
  4985.1      .1       0
Bank Sta=4979.1,4985.1
XS Rating Curve= 0 ,0
Exp/Cntr=0.3,0.1

Type RM Length L Ch R = 1 ,8779    ,656,656,656
BEGIN DESCRIPTION:
BURTONS CREEK TRIB C 19.0
END DESCRIPTION:
XS GIS Cut Line= 3
      3549360.66     10216048.65      3549342.11     10215641.64
       3549343.3     10215098.18
#Sta/Elev= 30
  4613.7  328.15  4670.8   324.6  4710.8  322.88  4730.8  320.67  4830.9  319.29
    4881  317.38    4901  315.93  4913.7  313.38  4930.2  312.17  4951.1  311.41
  4981.1  311.54  4998.1  309.79  5000.9  309.29  5004.1  309.79  5018.6  312.24
  5061.1  311.38  5081.1  314.01  5131.1   316.8  5181.1   317.7  5221.1  319.42
  5261.1  319.36  5313.2  320.81  5341.1  321.61  5401.1  324.53  5421.1  324.49
  5441.1  323.68  5471.1  324.84  5521.1  324.54  5551.1  326.06  5564.6  325.96
#Mann= 5 ,-1 , 0
  4613.7     .08       0  4930.2     .05       0  4998.1     .04       0
  5004.1     .05       0  5313.2     .08       0
Bank Sta=4998.1,5004.1
XS Rating Curve= 0 ,0
Exp/Cntr=0.3,0.1

Type RM Length L Ch R = 1 ,8123    ,354,354,354
BEGIN DESCRIPTION:
BURTONS CREEK TRIB C 18.0
END DESCRIPTION:
XS GIS Cut Line= 3
       3549692.1     10216041.67      3549750.61     10215187.82
      3549750.61     10215087.87
#Sta/Elev= 30
  4408.2  320.87  4448.3  319.73  4477.4  319.64  4598.7  315.37  4656.4  314.13
  4678.9  314.12    4719   312.5    4749  312.11    4769   312.4  4779.1  311.99
  4819.2  312.61  4849.3  312.17  4889.4  312.44  4909.4  308.55  4955.1  306.73
  4979.6  306.33  4996.6  303.39  4999.4  302.89  5002.6  303.39  5009.6  309.46
  5019.7  314.09  5029.7  314.79  5190.1   320.7  5240.2  321.87  5250.2  322.49
  5280.2  322.65  5290.2  323.37  5320.2   323.8  5350.2  325.25    5364  325.13
#Mann= 5 ,-1 , 0
  4408.2     .05       0  4656.4     .08       0  4955.1     .05       0
  4996.6     .04       0  5002.6     .05       0
Bank Sta=4996.6,5002.6
XS Rating Curve= 0 ,0
Exp/Cntr=0.3,0.1

Type RM Length L Ch R = 1 ,7769    ,558,558,558
BEGIN DESCRIPTION:
BURTONS CREEK TRIB C 17.0
END DESCRIPTION:
XS GIS Cut Line= 3
      3550092.11     10215841.68      3550042.11     10215441.64
      3549992.11     10215241.65
#Sta/Elev= 30
  4581.3  318.37  4631.7  315.36  4682.1  313.55  4699.8  313.15  4704.8  313.48
  4732.5  312.08  4780.4   310.5  4785.4  310.68  4813.1  308.52    4861  308.67
    4866   307.8  4903.8   306.8  4941.6  306.09  4974.4  306.29  4981.9  305.39
    4987  305.39  4994.8   301.7  4998.7  300.33  4999.5  300.05  5002.2  299.55
  5005.5  300.05  5015.4   304.4  5025.7  306.39    5036   306.7  5048.9  308.85
  5056.6  310.82  5066.9  312.01  5131.3  315.53  5167.4  316.14  5190.6  317.41
#Mann= 4 ,-1 , 0
  4581.3     .08       0  4998.7     .05       0  4999.5     .04       0
  5005.5     .05       0
Bank Sta=4999.5,5005.5
XS Rating Curve= 0 ,0
Exp/Cntr=0.3,0.1

Type RM Length L Ch R = 1 ,7211    ,539,539,539
BEGIN DESCRIPTION:
BURTONS CREEK TRIB C 16.0
END DESCRIPTION:
XS GIS Cut Line= 3
      3550185.29      10215818.7       3550484.8     10215380.29
       3550259.1     10214998.34
#Sta/Elev= 30
  4582.8  314.23  4651.4  313.43  4672.4  311.69  4750.2  309.05    4773  307.05
    4795  306.42  4815.9  307.89  4923.6   306.9  4938.5  305.36  4959.5  304.93
  4966.8  302.72  4980.5   300.7  4989.3  300.54  4995.4  296.61  5000.1  296.44
  5002.9  295.94  5006.1  296.44  5010.3  297.73  5016.4  303.18  5025.2  302.71
  5031.3  303.93  5115.9  303.53  5144.9  306.31  5150.7  305.69  5166.3  306.66
  5224.8  307.57  5267.7  309.86  5283.4  309.47  5347.7  310.68  5557.4  316.23
#Mann= 4 ,-1 , 0
  4582.8     .08       0  5000.1     .07       0  5006.1     .08       0
  5010.3     .05       0
Bank Sta=5000.1,5006.1
XS Rating Curve= 0 ,0
Exp/Cntr=0.3,0.1

Type RM Length L Ch R = 1 ,6672    ,461,461,461
BEGIN DESCRIPTION:
BURTONS CREEK TRIB C 15.0
END DESCRIPTION:
XS GIS Cut Line= 3
      3550211.52     10216132.64      3550811.55     10215632.61
       3551151.8     10215385.64
#Sta/Elev= 30
  4257.3  320.34  4326.7  318.21    4401   317.6  4421.8  314.41  4471.3  311.93
  4670.5  305.06    4835   305.4  4861.8  304.99  4904.8  300.56  4975.1  300.84
  4989.4  296.25  4994.2  292.59  4996.9  292.09  5000.2  292.59    5018  294.91
  5025.8   302.2  5035.5  304.62  5138.9  305.55  5147.4  308.31  5153.6  306.23
  5162.1  311.42  5168.2  308.26    5175  310.72  5197.6     312  5218.5  308.08
  5224.7  310.38  5233.2  307.67  5360.7  308.53  5390.1  310.69  5458.8  312.04
#Mann= 5 ,-1 , 0
  4257.3     .05       0  4326.7     .08       0    4835     .05       0
  4994.2     .04       0  5000.2     .05       0
Bank Sta=4994.2,5000.2
XS Rating Curve= 0 ,0
Exp/Cntr=0.3,0.1

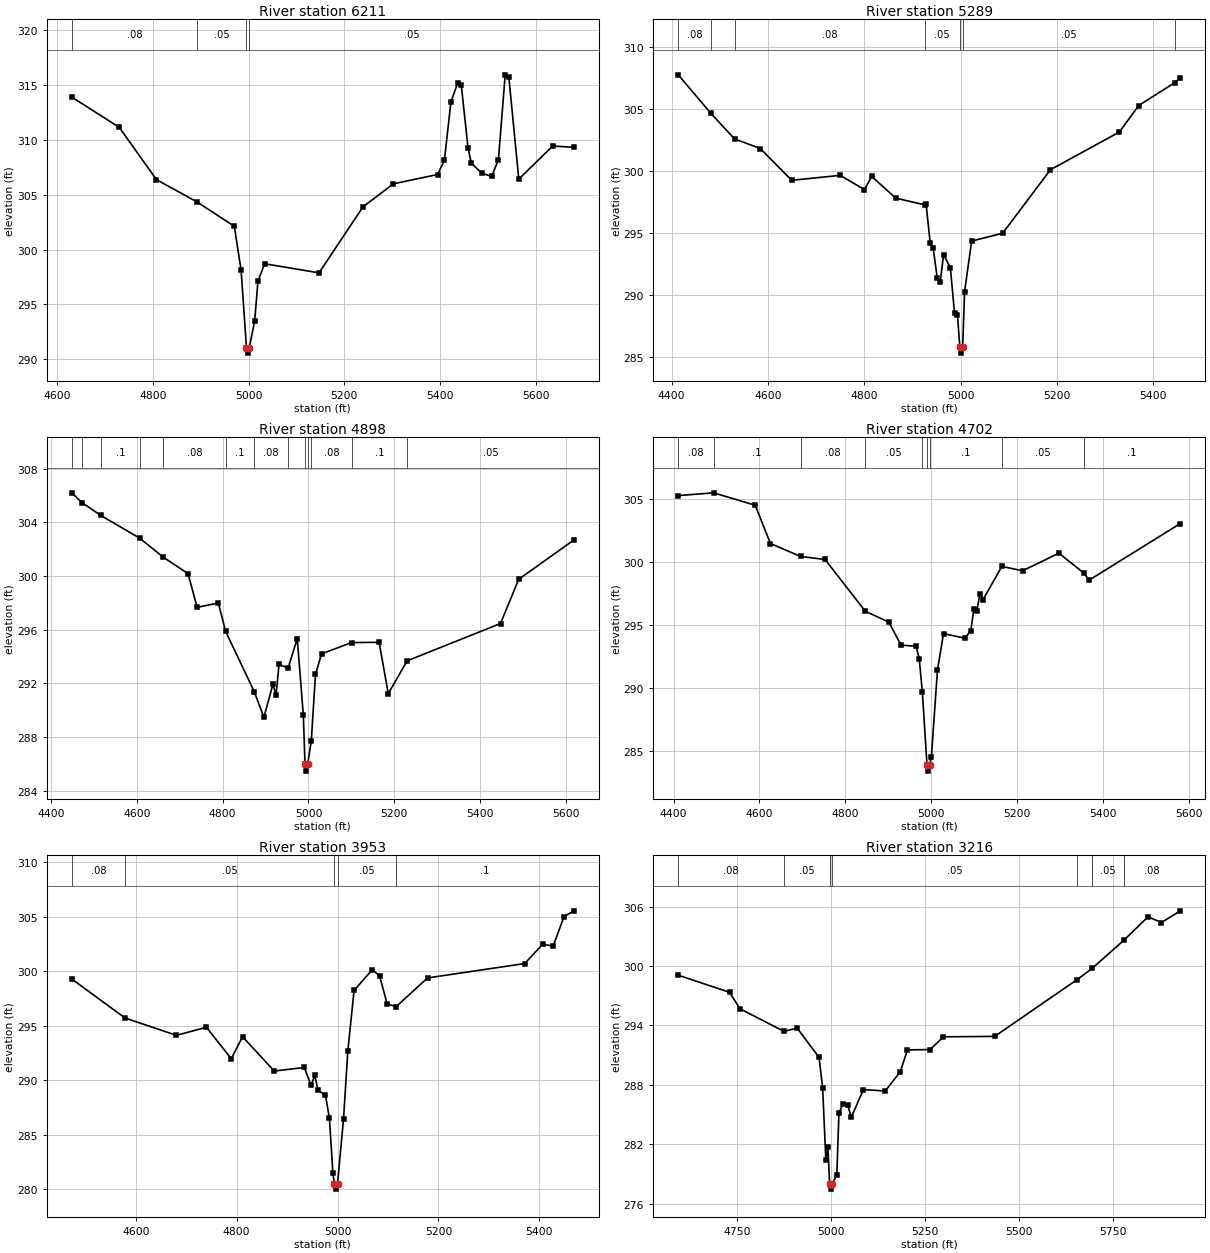
Type RM Length L Ch R = 1 ,6211    ,922,922,922
BEGIN DESCRIPTION:
BURTONS CREEK TRIB C 13.0
END DESCRIPTION:
XS GIS Cut Line= 3
      3550552.34     10216362.28      3550702.37     10216212.25
      3551322.45     10215649.41
#Sta/Elev= 30
  4630.2  313.91  4729.5  311.15  4807.3  306.38  4891.9  304.35    4970  302.13
  4984.2  298.13  4995.4  291.06  4998.2  290.56  5001.4  291.06  5012.6  293.51
  5019.4  297.12  5033.5  298.71  5147.1  297.88    5239   303.9  5302.5     306
  5395.1  306.85  5409.2  308.14  5422.8  313.46    5437  315.19  5444.4  315.04
  5458.6  309.27  5465.4  307.89    5487  306.98  5507.9  306.67  5522.1   308.2
  5536.3  315.94  5543.8  315.76  5564.7  306.43  5635.7  309.45  5679.8  309.33
#Mann= 4 ,-1 , 0
  4630.2     .08       0  4891.9     .05       0  4995.4     .04       0
  5001.4     .05       0
Bank Sta=4995.4,5001.4
XS Rating Curve= 0 ,0
Exp/Cntr=0.3,0.1

Type RM Length L Ch R = 1 ,5289    ,391,391,391
BEGIN DESCRIPTION:
BURTONS CREEK TRIB C 12.0
END DESCRIPTION:
XS GIS Cut Line= 3
      3551131.53     10216730.07      3551592.45     10216083.79
      3551592.45      10215835.2
#Sta/Elev= 30
  4413.6  307.72  4481.1  304.63  4530.5  302.56    4584  301.79  4649.1  299.23
  4749.9  299.63  4800.3  298.48  4815.1  299.54  4865.5  297.79  4925.1  297.26
  4928.2  297.32  4936.8  294.15  4942.9  293.76  4951.5  291.34  4957.7  291.06
  4964.4  293.25  4978.6  292.21  4987.2  288.53  4993.3  288.41  4998.2  285.82
    5001  285.32  5004.2  285.82  5008.1  290.27  5022.8  294.34  5087.2  294.97
  5186.3  300.08  5329.6  303.12  5369.6  305.25    5445   307.1    5456  307.49
#Mann= 7 ,-1 , 0
  4413.6     .08       0  4481.1     .05       0  4530.5     .08       0
  4925.1     .05       0  4998.2     .04       0  5004.2     .05       0
    5445     .08       0
Bank Sta=4998.2,5004.2
XS Rating Curve= 0 ,0
Exp/Cntr=0.3,0.1

Type RM Length L Ch R = 1 ,4898    ,196,196,196
BEGIN DESCRIPTION:
BURTONS CREEK TRIB C 10.1
END DESCRIPTION:
XS GIS Cut Line= 3
      3551295.34     10216928.31      3551645.35     10216578.31
      3552114.56     10216092.21
#Sta/Elev= 30
  4448.2  306.21  4472.8  305.46  4516.1  304.52  4606.5  302.83  4661.5  301.41
  4719.3  300.18  4740.5  297.67    4790  297.99  4806.9  295.87  4873.9  291.37
  4896.1  289.46  4917.3  291.95  4924.4  291.11  4931.5  293.42  4952.4  293.12
  4973.9  295.33  4988.1  289.62    4992  285.95  4994.8  285.45    4998  285.95
  5006.6  287.69  5016.4  292.66  5030.5   294.2  5100.6  295.04  5164.8  295.06
  5186.1  291.23  5230.2  293.68  5447.8  296.46  5490.2  299.76  5618.8  302.69
#Mann= 13 ,-1 , 0
  4448.2     .08       0  4472.8     .05       0  4516.1      .1       0
  4606.5     .05       0  4661.5     .08       0  4806.9      .1       0
  4873.9     .08       0  4952.4      .1       0    4992     .07       0
    4998      .1       0  5006.6     .08       0  5100.6      .1       0
  5230.2     .05       0
Bank Sta=4992,4998
XS Rating Curve= 0 ,0
Exp/Cntr=0.3,0.1

Type RM Length L Ch R = 1 ,4702    ,749,749,749
BEGIN DESCRIPTION:
BURTONS CREEK TRIB C 10.0
END DESCRIPTION:
XS GIS Cut Line= 3
      3551439.65     10217042.82      3551789.63     10216692.85
      3552257.97     10216207.65
#Sta/Elev= 30
    4411  305.28  4493.4   305.5  4590.3  304.51  4625.7  301.47  4695.9  300.44
    4753   300.2  4846.7  296.08  4901.5  295.22  4929.8  293.39    4965   293.3
  4972.2  292.32  4979.6  289.64  4990.3  283.87  4993.1  283.37  4996.3  283.87
  5000.5  284.46  5014.7   291.4  5028.8  294.31  5078.2  293.94  5092.4  294.52
  5099.6   296.3  5106.5  296.14  5113.7  297.48  5120.7     297  5164.8  299.65
  5212.8   299.3  5297.4   300.7  5355.4  299.13  5368.1  298.56  5580.3  303.06
#Mann= 9 ,-1 , 0
    4411     .08       0  4493.4      .1       0  4695.9     .08       0
  4846.7     .05       0  4979.6      .1       0  4990.3     .07       0
  4996.3      .1       0  5164.8     .05       0  5355.4      .1       0
Bank Sta=4990.3,4996.3
XS Rating Curve= 0 ,0
Exp/Cntr=0.3,0.1

Type RM Length L Ch R = 1 ,3953    ,737,737,737
BEGIN DESCRIPTION:
BURTONS CREEK TRIB C 9.0
END DESCRIPTION:
XS GIS Cut Line= 3
      3551942.13     10217091.61      3552428.22     10216388.86
      3552527.65     10216289.43
#Sta/Elev= 30
  4473.2  299.29  4578.8  295.71  4680.6  294.12  4740.1  294.86  4789.3  291.97
  4811.7  293.99  4874.6  290.84  4934.1  291.17  4947.4  289.52    4955  290.44
  4961.1  289.08    4976  288.63  4983.8  286.51  4990.8  281.45  4993.9   280.5
  4996.7     280  4999.9   280.5  5011.8  286.42  5020.3  292.67  5032.7  298.24
    5069  300.16  5083.4  299.56  5098.3     297    5116  296.75  5178.4  299.39
  5370.9  300.71  5406.2  302.46  5427.5  302.33  5448.7  305.01  5468.3  305.55
#Mann= 5 ,-1 , 0
  4473.2     .08       0  4578.8     .05       0  4993.9     .04       0
  4999.9     .05       0    5116      .1       0
Bank Sta=4993.9,4999.9
XS Rating Curve= 0 ,0
Exp/Cntr=0.3,0.1

Type RM Length L Ch R = 1 ,3216    ,710,710,710
BEGIN DESCRIPTION:
BURTONS CREEK TRIB C 7.0
END DESCRIPTION:
XS GIS Cut Line= 4
       3552079.4     10217493.17      3552190.52     10217291.75
      3552542.11     10217141.64      3552967.34     10216556.95
#Sta/Elev= 30
  4594.4  299.07    4731  297.34  4758.5  295.68  4875.7   293.4  4910.8  293.73
  4968.9  290.77  4978.4  287.71    4987  280.41  4992.5  281.71  4997.1  277.97
  4999.9  277.47  5003.1  277.97  5016.1  278.88  5021.9  285.16  5032.8  286.09
  5045.1  285.99  5054.5  284.72  5086.9  287.52    5145  287.38    5185  289.33
    5204  291.53  5264.3  291.56  5299.8  292.85  5435.9  292.89  5655.4  298.63
  5695.4  299.76  5780.1  302.62  5843.9  304.97  5879.5  304.39  5929.7  305.57
#Mann= 7 ,-1 , 0
  4594.4     .08       0  4875.7     .05       0  4997.1     .04       0
  5003.1     .05       0  5655.4     .08       0  5695.4     .05       0
  5780.1     .08       0
Bank Sta=4997.1,5003.1
XS Rating Curve= 0 ,0
Exp/Cntr=0.3,0.1

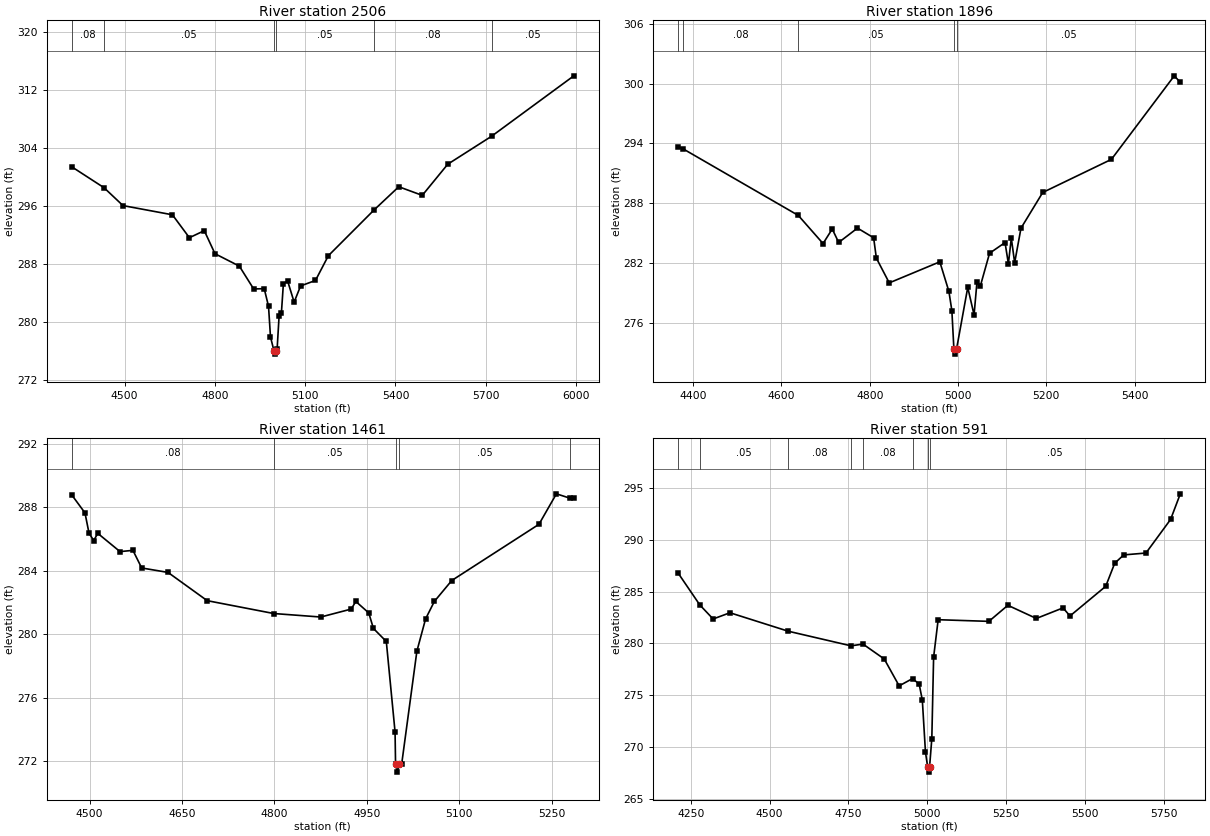
Type RM Length L Ch R = 1 ,2506    ,610,610,610
BEGIN DESCRIPTION:
BURTONS CREEK TRIB C 6.0
END DESCRIPTION:
XS GIS Cut Line= 3
      3552192.14     10217941.61      3552621.86     10217593.76
      3553342.11     10216741.64
#Sta/Elev= 30
  4324.3  301.35  4431.4  298.47  4494.5     296  4658.8  294.73  4715.2  291.57
  4764.7  292.54  4800.3  289.36  4881.2  287.65  4928.8   284.5  4963.9  284.54
  4978.2  282.11  4984.7  277.89    4996  276.01  4998.8  275.51    5002  276.01
  5006.8  276.23  5013.3  280.75  5021.1  281.25  5027.6  285.24  5041.9  285.57
  5063.3  282.68  5084.8  284.92  5134.2  285.67  5177.1  289.09    5328  295.36
  5411.1   298.6  5489.1  297.41  5573.9  301.71  5719.3  305.56  5992.9   313.9
#Mann= 6 ,-1 , 0
  4324.3     .08       0  4431.4     .05       0    4996     .04       0
    5002     .05       0    5328     .08       0  5719.3     .05       0
Bank Sta=4996,5002
XS Rating Curve= 0 ,0
Exp/Cntr=0.3,0.1

Type RM Length L Ch R = 1 ,1896    ,435,435,435
BEGIN DESCRIPTION:
BURTONS CREEK TRIB C 4.0
END DESCRIPTION:
XS GIS Cut Line= 3
       3552607.2     10218305.63      3553092.11     10217941.64
      3553442.09     10217541.66
#Sta/Elev= 30
    4366  293.65  4376.3  293.47  4638.1  286.78  4694.2  283.96    4715  285.42
  4729.6  284.07  4772.2  285.51  4808.8  284.54    4815   282.5  4844.2  280.02
  4958.8  282.13  4979.4  279.16  4986.1  277.24  4990.7  273.38  4993.4  272.88
  4996.7  273.38  5022.1  279.57  5036.4  276.81    5043  280.11  5050.6   279.7
  5071.5  282.99  5106.6  284.06  5114.2  281.94  5120.8   284.5  5128.4  282.04
  5142.7   285.5    5192  289.08  5347.7   292.4  5490.1  300.77  5503.8  300.12
#Mann= 5 ,-1 , 0
    4366     .05       0  4376.3     .08       0  4638.1     .05       0
  4990.7     .04       0  4996.7     .05       0
Bank Sta=4990.7,4996.7
XS Rating Curve= 0 ,0
Exp/Cntr=0.3,0.1

Type RM Length L Ch R = 1 ,1461    ,870,870,870
BEGIN DESCRIPTION:
BURTONS CREEK TRIB C 3.0
END DESCRIPTION:
XS GIS Cut Line= 3
       3552992.1     10218591.65      3553392.11     10218241.64
      3553592.13     10218041.61
#Sta/Elev= 30
  4471.2  288.79  4492.6  287.66  4499.2  286.38  4506.8  285.92  4513.4  286.37
  4549.5  285.22  4570.4   285.3  4584.6  284.19  4627.3  283.91  4690.9  282.13
  4798.9  281.32  4875.1   281.1  4924.4   281.6    4932  282.08  4952.9  281.36
  4960.5  280.38  4981.4  279.56  4995.6  273.86  4996.4  271.83  4999.1  271.33
  5002.4  271.83  5006.3  271.83    5031  278.95  5045.1  280.98  5059.3  282.08
  5087.6   283.4    5229  286.94  5257.3  288.86  5279.7  288.58  5285.6  288.58
#Mann= 5 ,-1 , 0
  4471.2     .08       0  4798.9     .05       0  4996.4     .04       0
  5002.4     .05       0  5279.7     .08       0
Bank Sta=4996.4,5002.4
XS Rating Curve= 0 ,0
Exp/Cntr=0.3,0.1

Type RM Length L Ch R = 1 ,591     ,0,0,0
BEGIN DESCRIPTION:
BURTONS CREEK TRIB C 1.0
END DESCRIPTION:
XS GIS Cut Line= 3
      3553092.07     10218841.65      3554205.18     10218738.12
       3554509.3     10218375.87
#Sta/Elev= 30
  4210.6  286.76  4279.1   283.7  4321.1  282.35  4374.5  282.95  4559.1  281.17
  4758.2  279.76    4796  279.93  4863.4  278.49  4910.6   275.9  4952.9   276.6
  4973.9  276.08    4984  274.54    4994   269.5    5001  268.08  5003.8  267.58
    5007  268.08  5014.1  270.81  5019.8  278.67  5034.2  282.28  5194.9  282.12
  5255.1  283.67  5345.3   282.4  5429.9  283.42  5451.9  282.64  5565.1   285.5
  5593.7  287.73  5622.3  288.53  5692.6  288.71  5770.7  291.95  5801.5  294.42
#Mann= 8 ,-1 , 0
  4210.6     .08       0  4279.1     .05       0  4559.1     .08       0
  4758.2      .1       0    4796     .08       0  4952.9     .05       0
    5001     .04       0    5007     .05       0
Bank Sta=5001,5007
XS Rating Curve= 0 ,0
Exp/Cntr=0.3,0.1

Chan Stop Cuts=-1
Use User Specified Reach Order=0
Composite Channel Slope=5