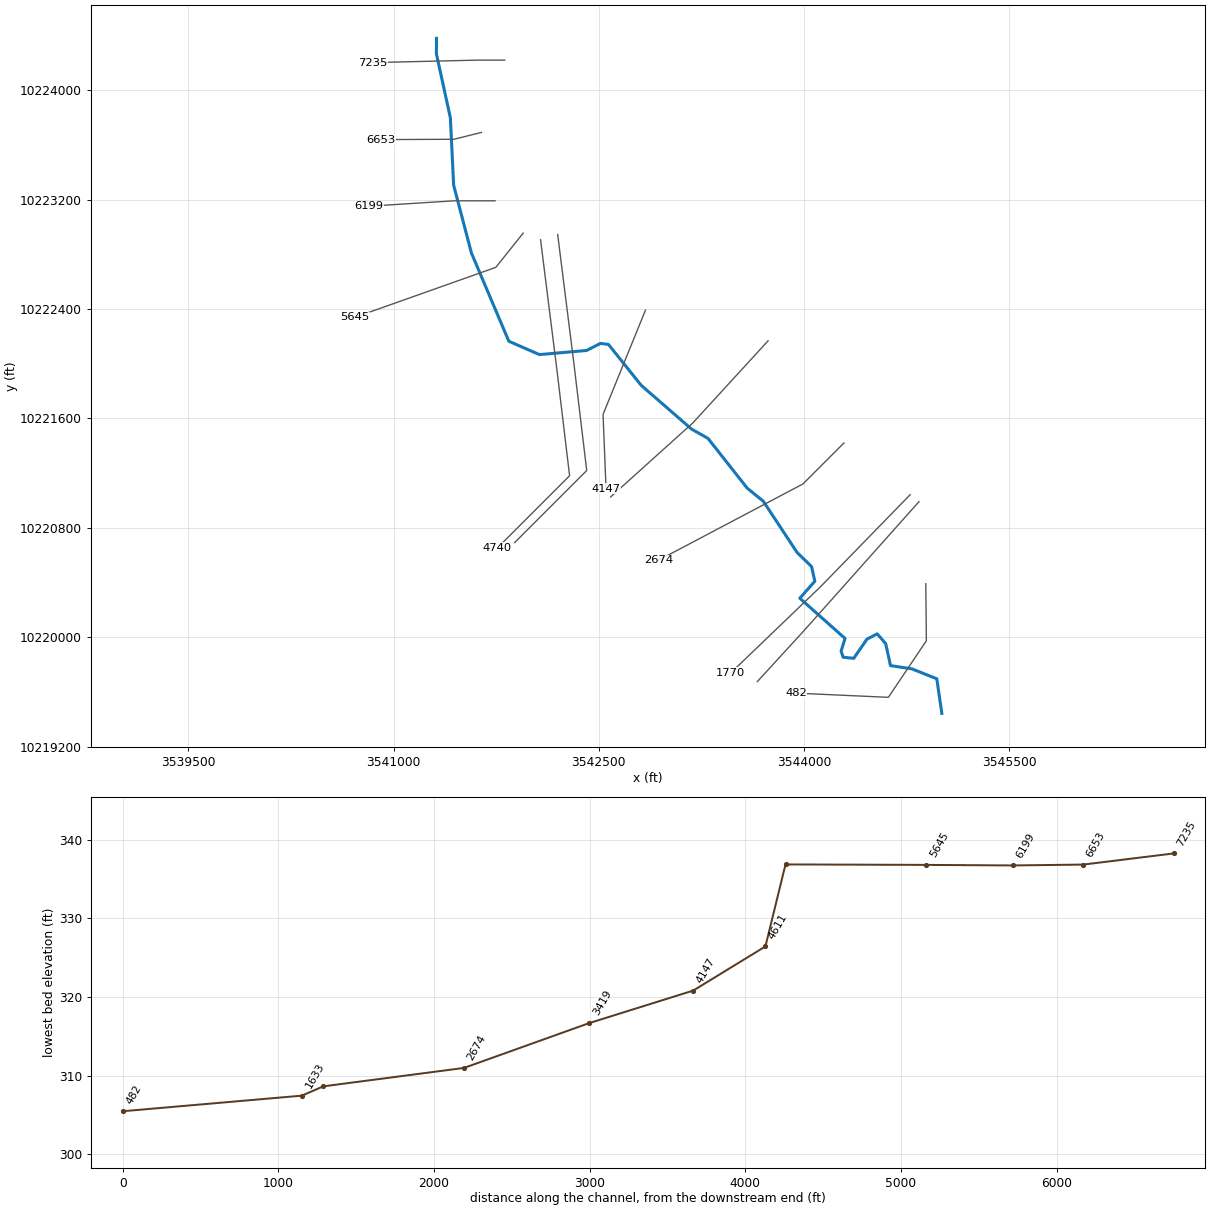
--- BURTON CREEK TRIB D 1.prj (project) ---

Proj Title=BURTON CREEK TRIB D 1 Base Level Engineering
Current Plan=p01
Default Exp/Contr=0.3,0.1
English Units
Geom File=g01
Flow File=f01
Plan File=p01
Y Axis Title=Elevation
X Axis Title(PF)=Main Channel Distance
X Axis Title(XS)=Station
BEGIN DESCRIPTION:
BURTON CREEK TRIB D 1
END DESCRIPTION:
DSS Export Rating Curves= 0
DSS Export Rating Curve Sorted= 0
DSS Export Volume Flow Curves= 0
DXF OffsetX= 0
DXF OffsetY= 0
DXF ScaleX= 1
DXF ScaleY= 10

--- BURTON CREEK TRIB D 1.p01 (plan) ---

Plan Title=Multiple Run
Short Identifier=Multiple
Geom File=g01
Flow File=f01
Subcritical Flow
K Sum by GR= 0
Std Step Tol= 0.01
Critical Tol= 0.01
Num of Std Step Trials= 20
Max Error Tol= 0.3
Flow Tol Ratio= 0.001
Split Flow NTrial= 30
Split Flow Tol= 0.02
Split Flow Ratio= 0.02
Log Output Level= 0
Friction Slope Method= 1
Unsteady Friction Slope Method= 2
Unsteady Bridges Friction Slope Method= 1
Parabolic Critical Depth
Global Vel Dist=  1 , 1 , 1
Global Log Level= 0
CheckData=True
Encroach Param= -1, 0, 0, 0
BEGIN DESCRIPTION:
Multiple Run
END DESCRIPTION:

--- BURTON CREEK TRIB D 1.f01 (steady flow) ---

Flow Title=Multiple
Program Version=4.10
Number of Profiles= 7
Profile Names=10-year,25-year,50-year,1pct_min,100-year,1pct_plu,500-year
River Rch & RM=BURTON CREEK TRI,Reach-1         ,7235
     315     406     478     412     558     754     761
Boundary for River Rch & Prof#=BURTON CREEK TRI,Reach-1         , 1
Up Type= 0
Dn Type= 3
Dn Slope=0.005
Boundary for River Rch & Prof#=BURTON CREEK TRI,Reach-1         , 2
Up Type= 0
Dn Type= 3
Dn Slope=0.005
Boundary for River Rch & Prof#=BURTON CREEK TRI,Reach-1         , 3
Up Type= 0
Dn Type= 3
Dn Slope=0.005
Boundary for River Rch & Prof#=BURTON CREEK TRI,Reach-1         , 4
Up Type= 0
Dn Type= 3
Dn Slope=0.005
Boundary for River Rch & Prof#=BURTON CREEK TRI,Reach-1         , 5
Up Type= 0
Dn Type= 3
Dn Slope=0.005
Boundary for River Rch & Prof#=BURTON CREEK TRI,Reach-1         , 6
Up Type= 0
Dn Type= 3
Dn Slope=0.005
Boundary for River Rch & Prof#=BURTON CREEK TRI,Reach-1         , 7
Up Type= 0
Dn Type= 3
Dn Slope=0.005
DSS Import GetInterval= 0
DSS Import GetPeak= 0
DSS Import FillOption= 0

--- BURTON CREEK TRIB D 1.g01 (geometry) ---

Geom Title=Existing Conditions
Program Version=4.10

River Reach=BURTON CREEK TRI,Reach-1
Reach XY= 30
      3541314.02     10224379.76       3541313.6     10224265.56
       3541415.6     10223798.98      3541439.47     10223306.36
      3541569.68      10222809.4      3541843.12     10222164.87
      3542066.64     10222067.21      3542411.04     10222097.14
      3542513.57     10222149.08      3542571.76     10222141.35
      3542810.15     10221843.31      3543179.24     10221522.35
      3543299.56     10221454.31      3543586.18     10221090.41
      3543703.54     10220995.27      3543950.77     10220620.27
      3544057.02      10220516.8      3544080.63     10220409.85
      3543970.91     10220285.55      3544301.39     10219991.79
      3544272.63     10219897.65      3544288.21     10219854.25
      3544364.87     10219846.03      3544462.05     10219986.59
      3544537.05     10220025.48      3544598.86     10219953.25
      3544634.01     10219793.01      3544790.26     10219769.14
      3544972.33     10219696.79      3545009.45     10219443.62

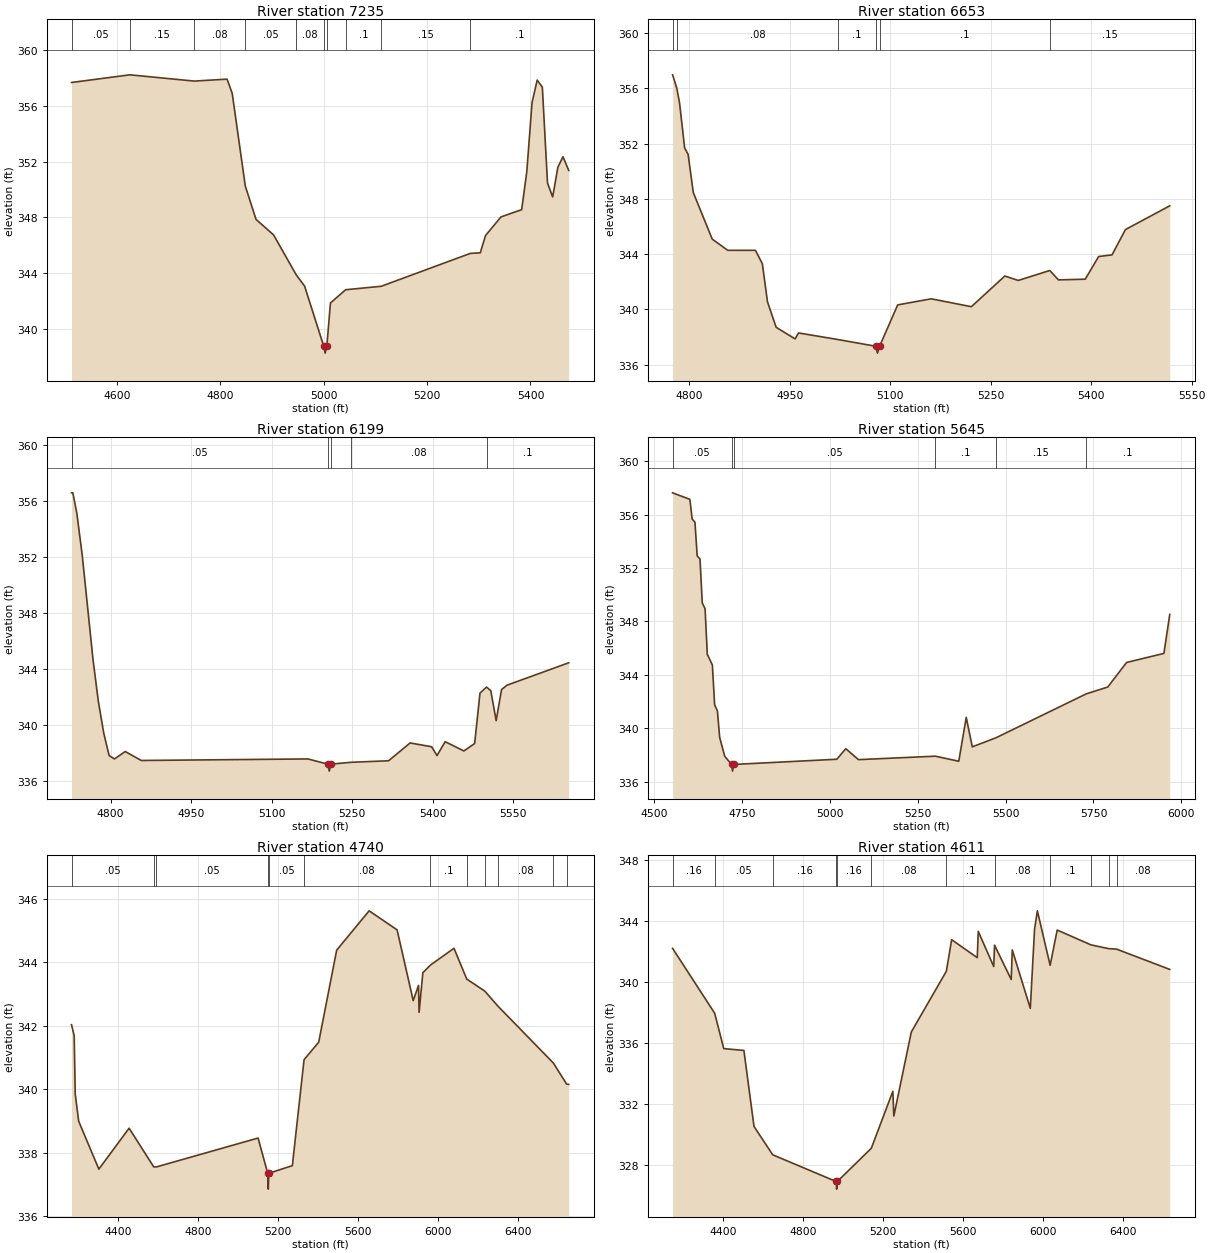
Type RM Length L Ch R = 1 ,7235    ,582,582,582
BEGIN DESCRIPTION:
BURTON CREEK TRIB D.1 14.0
END DESCRIPTION:
XS GIS Cut Line= 3
      3541813.09     10224220.38      3541613.14     10224220.38
       3540851.1     10224202.37
#Sta/Elev= 30
  4511.8  357.68  4624.7  358.23  4749.4  357.78  4812.8  357.92  4822.8   356.9
  4848.1  350.25  4868.9  347.85  4902.8  346.74  4946.7  343.87  4962.9  343.06
  4999.9  338.75  5002.6  338.25  5005.9  338.75  5012.9  341.85  5042.3   342.8
  5111.3  343.05  5283.6  345.41  5302.9  345.45    5313  346.69    5343  348.03
    5383  348.55    5393   351.3    5403  356.22    5413  357.85    5423  357.35
    5433  350.46    5443  349.46    5453  351.59    5463  352.35    5474  351.37
#Mann= 10 ,-1 , 0
  4511.8     .05       0  4624.7     .15       0  4749.4     .08       0
  4848.1     .05       0  4946.7     .08       0  4999.9     .07       0
  5005.9     .08       0  5042.3      .1       0  5111.3     .15       0
  5283.6      .1       0
Bank Sta=4999.9,5005.9
XS Rating Curve= 0 ,0
Exp/Cntr=0.3,0.1

Type RM Length L Ch R = 1 ,6653    ,454,454,454
BEGIN DESCRIPTION:
BURTON CREEK TRIB D.1 13.0
END DESCRIPTION:
XS GIS Cut Line= 3
      3541642.07     10223691.63      3541442.11     10223641.64
      3540905.93     10223639.38
#Sta/Elev= 30
    4775  356.97  4781.2  356.02  4785.3  354.97    4793  351.68  4798.2  351.21
  4805.9  348.45  4834.2  345.08  4857.4  344.27  4898.7  344.27    4909   343.3
  4916.7  340.54  4929.6   338.7  4957.9  337.86  4963.1  338.29  5022.3  337.81
  5078.1  337.33  5080.9  336.83  5084.1  337.33  5111.1  340.32  5161.1  340.76
  5221.1  340.19  5271.1  342.41  5291.1  342.09  5338.2  342.81  5351.1  342.13
  5391.1  342.18  5411.1  343.82  5431.1  343.94  5451.1  345.77  5517.3  347.49
#Mann= 6 ,-1 , 0
    4775     .05       0  4781.2     .08       0  5022.3      .1       0
  5078.1     .07       0  5084.1      .1       0  5338.2     .15       0
Bank Sta=5078.1,5084.1
XS Rating Curve= 0 ,0
Exp/Cntr=0.3,0.1

Type RM Length L Ch R = 1 ,6199    ,554,554,554
BEGIN DESCRIPTION:
BURTON CREEK TRIB D.1 12.0
END DESCRIPTION:
XS GIS Cut Line= 3
      3541742.13     10223191.64      3541442.11     10223191.64
      3540817.28     10223152.13
#Sta/Elev= 30
  4727.4  356.58  4729.9  356.58  4737.4   355.1  4747.4  352.11  4767.4  344.69
  4777.4  341.69  4787.4  339.44  4797.4  337.83  4807.4  337.59  4827.4  338.12
  4857.4  337.48  5167.7  337.59  5204.8  337.22  5207.5  336.72  5210.8  337.22
  5248.2  337.35    5318  337.46  5358.1  338.73  5398.2  338.46  5408.2  337.83
  5423.4  338.82  5458.3  338.16  5478.3  338.69  5488.3  342.29  5500.4  342.72
  5508.4  342.46  5518.4  340.32  5528.4  342.54  5538.4  342.85  5653.5  344.45
#Mann= 5 ,-1 , 0
  4727.4     .05       0  5204.8    .033       0  5210.8     .05       0
  5248.2     .08       0  5500.4      .1       0
Bank Sta=5204.8,5210.8
XS Rating Curve= 0 ,0
Exp/Cntr=0.3,0.1

Type RM Length L Ch R = 1 ,5645    ,905,905,905
BEGIN DESCRIPTION:
BURTON CREEK TRIB D.1 11.0
END DESCRIPTION:
XS GIS Cut Line= 3
      3541947.83     10222955.03      3541747.85     10222705.05
      3540716.31     10222339.28
#Sta/Elev= 30
  4552.4  357.64  4601.6  357.15    4608  355.68    4616  355.44  4622.4  352.92
  4630.4  352.68  4636.8  349.39  4644.8  348.96  4651.2  345.54  4665.6  344.74
    4672  341.76    4680  341.29  4686.4  339.31  4700.8   337.9  4720.2  337.29
    4723  336.79  4726.2  337.29  5019.6  337.68  5045.2  338.47  5081.4  337.65
  5300.1  337.91  5366.7  337.53  5387.9  340.82  5405.1  338.61  5472.7  339.29
  5729.5  342.58  5790.6  343.09  5844.1  344.93  5950.3  345.61    5967  348.53
#Mann= 6 ,-1 , 0
  4552.4     .05       0  4720.2    .033       0  4726.2     .05       0
  5300.1      .1       0  5472.7     .15       0  5729.5      .1       0
Bank Sta=4720.2,4726.2
XS Rating Curve= 0 ,0
Exp/Cntr=0.3,0.1

Type RM Length L Ch R = 1 ,4740    ,129,129,129
BEGIN DESCRIPTION:
BURTON CREEK TRIB D.1 10.0
END DESCRIPTION:
XS GIS Cut Line= 4
      3542075.08     10222907.16      3542194.85     10221954.41
       3542287.4     10221181.35      3541759.35      10220653.3
#Sta/Elev= 30
  4168.8  342.03  4182.2  341.68  4187.3  339.85  4204.6  338.99  4305.4  337.48
  4456.6  338.77  4579.9  337.55  4593.6  337.55  5101.6  338.46  5149.5  337.35
  5152.3  336.85  5155.5  337.35  5272.8  337.59  5331.4  340.93  5404.6  341.48
  5494.4  344.38  5656.7  345.62  5796.5  345.02  5877.1  342.79  5903.7  343.27
  5906.4  342.42  5925.3  343.67  5963.1  343.91  6080.9  344.44  6144.7  343.47
    6235  343.09  6301.6  342.61  6578.3  340.82    6644  340.16  6654.4  340.15
#Mann= 12 ,-1 , 0
  4168.8     .05       0  4579.9     .16       0  4593.6     .05       0
  5149.5    .033       0  5155.5     .05       0  5331.4     .08       0
  5963.1      .1       0  6144.7     .08       0    6235      .1       0
  6301.6     .08       0  6578.3      .1       0    6644     .08       0
Bank Sta=5149.5,5155.5
XS Rating Curve= 0 ,0
Exp/Cntr=0.3,0.1

Type RM Length L Ch R = 1 ,4611    ,464,464,464
BEGIN DESCRIPTION:
BURTON CREEK TRIB D.1 10.1
END DESCRIPTION:
XS GIS Cut Line= 4
       3542200.3      10222945.2      3542320.07     10221992.52
      3542412.61     10221219.45       3541885.8     10220692.64
#Sta/Elev= 30
  4149.4  342.21  4359.6  337.96    4405  335.64  4505.7  335.52  4556.1  330.54
  4649.6  328.68  4966.4  326.93  4969.1  326.43  4972.4  326.93  5142.3  329.11
  5249.7  332.84  5254.7  331.22  5342.1  336.73  5517.1  340.71  5543.5  342.78
  5671.5   341.6  5676.5  343.32  5753.8  341.02  5757.8  342.42  5841.2  340.17
  5846.3  342.11  5936.5  338.28  5957.7  343.46  5971.8  344.67  6035.6   341.1
  6070.8  343.41  6239.3  342.44  6328.3  342.19  6367.5  342.16  6633.2  340.83
#Mann= 12 ,-1 , 0
  4149.4     .16       0  4359.6     .05       0  4649.6     .16       0
  4966.4     .07       0  4972.4     .16       0  5142.3     .08       0
  5517.1      .1       0  5757.8     .08       0  6035.6      .1       0
  6239.3     .08       0  6328.3      .1       0  6367.5     .08       0
Bank Sta=4966.4,4972.4
XS Rating Curve= 0 ,0
Exp/Cntr=0.3,0.1

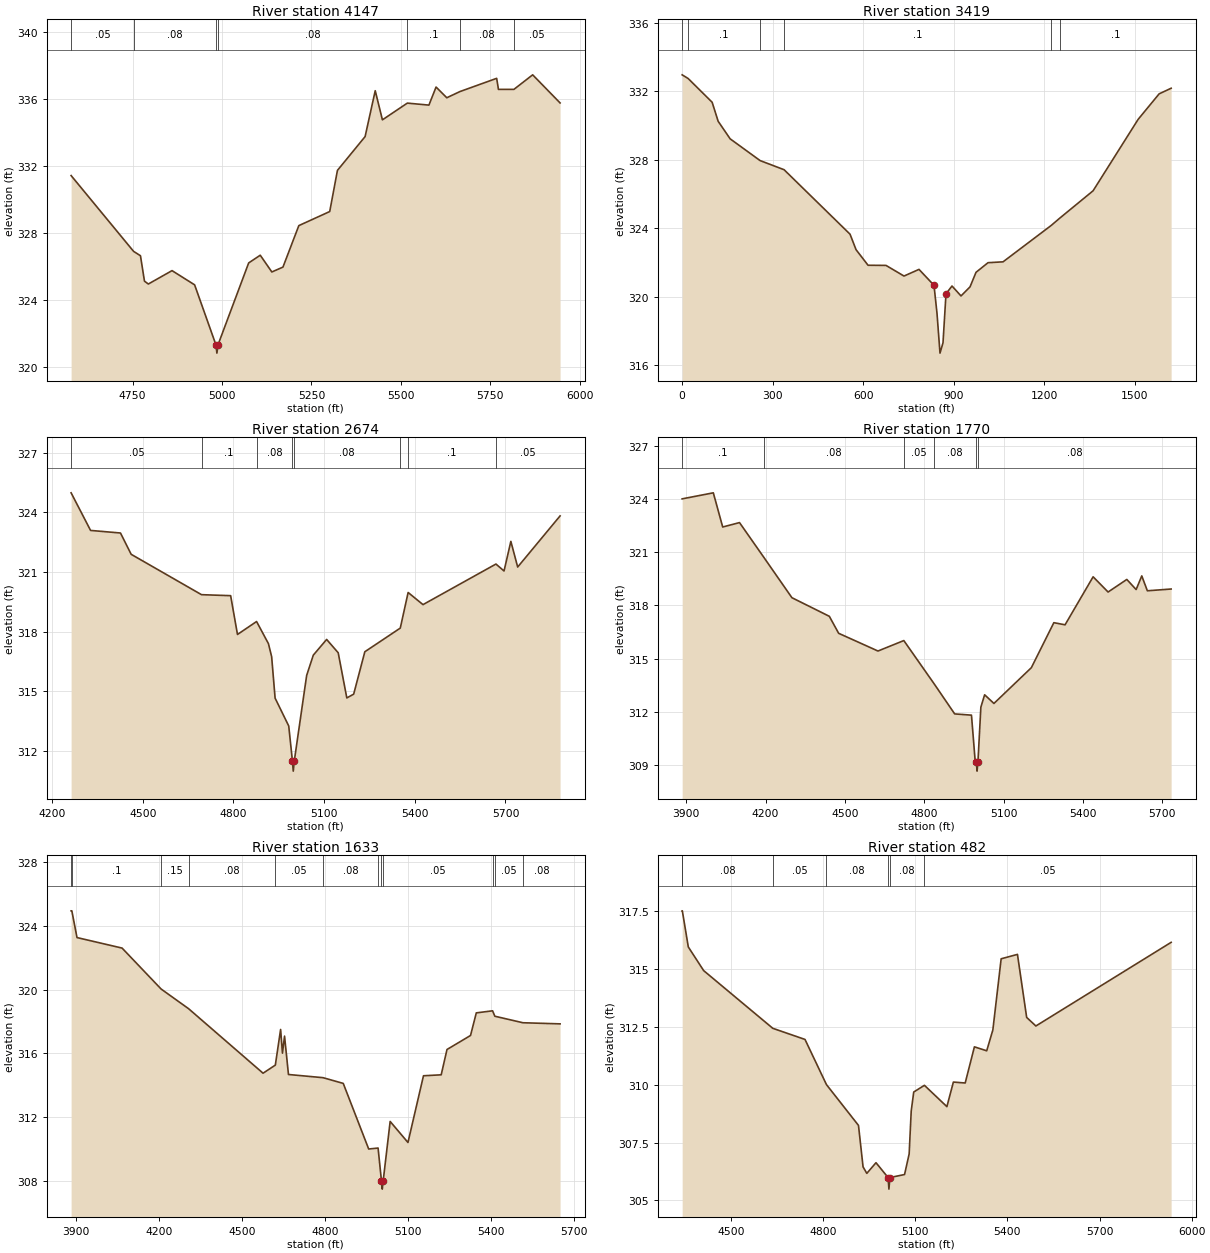
Type RM Length L Ch R = 1 ,4147    ,668,668,668
BEGIN DESCRIPTION:
BURTON CREEK TRIB D.1 8.0
END DESCRIPTION:
XS GIS Cut Line= 3
      3542842.12     10222391.68      3542532.06     10221629.96
      3542554.09     10221085.01
#Sta/Elev= 30
  4577.8  331.43  4752.6   326.9  4771.8  326.64    4783  325.12  4793.8  324.95
  4860.1  325.75  4923.3   324.9  4982.8  321.32  4985.6  320.82  4988.8  321.32
  5074.5  326.21  5106.9  326.67  5139.3  325.67  5170.4  325.96  5214.8  328.44
  5301.2  329.28  5322.8  331.74  5400.2  333.76  5428.5   336.5  5448.6  334.76
  5518.3  335.76  5578.7  335.64  5598.7  336.72  5628.7  336.08  5665.5  336.45
  5768.2  337.24  5773.2  336.58  5816.4  336.58  5868.9  337.45  5945.6  335.77
#Mann= 7 ,-1 , 0
  4577.8     .05       0  4752.6     .08       0  4982.8     .07       0
  4988.8     .08       0  5518.3      .1       0  5665.5     .08       0
  5816.4     .05       0
Bank Sta=4982.8,4988.8
XS Rating Curve= 0 ,0
Exp/Cntr=0.3,0.1

Type RM Length L Ch R = 1 ,3419    ,805,805,805
BEGIN DESCRIPTION:
BURTON CREEK TRIB D.1 6.0
END DESCRIPTION:
XS GIS Cut Line= 3
      3543738.84     10222167.82      3543188.83     10221567.81
      3542587.56     10221026.19
#Sta/Elev= 30
       0332.9681 19.8639332.751899.31952331.3628119.1834330.2527158.9112329.2251
258.2307327.9519337.6863327.4176556.1893323.6458576.0532322.7418 615.781321.8296
675.3727321.8205734.9644 321.198784.6241 321.588834.3252320.6584844.2709319.0239
854.2166316.6896864.1624317.2916 874.108320.1639893.9995320.6149923.8366320.0342
953.6738320.5652973.5652321.41661013.348321.97971063.077 322.0291222.208324.1518
1252.045324.60031361.448326.18521510.634330.36191580.254331.85531620.036332.1835
#Mann= 6 ,-1 , 0
       0     .15       0 19.8639      .1       0258.2307     .08       0
337.6863      .1       01222.208     .07       01252.045      .1       0
Bank Sta=834.3252,874.108
XS Rating Curve= 0 ,0
Exp/Cntr=0.3,0.1

Type RM Length L Ch R = 1 ,2674    ,904,904,904
BEGIN DESCRIPTION:
BURTON CREEK TRIB D.1 4.0
END DESCRIPTION:
XS GIS Cut Line= 3
      3544293.73     10221421.08      3543993.74     10221121.09
      3542938.07     10220563.78
#Sta/Elev= 30
  4262.8  324.98  4327.2  323.09  4426.2  322.96  4461.5  321.89  4694.3  319.86
  4790.7  319.81  4813.3  317.86  4876.5  318.51  4915.7   317.4  4926.4  316.74
  4937.8  314.66  4982.9  313.26  4995.2  311.49  4997.9  310.99  5001.2  311.49
  5042.2   315.8  5064.2  316.82  5108.3  317.61  5146.6  316.94  5175.1  314.67
  5197.8  314.86  5234.7  316.99    5352  318.18    5378  319.97  5427.2  319.36
  5668.6   321.4  5695.3  321.05  5717.9  322.54  5740.5  321.25  5880.8  323.82
#Mann= 8 ,-1 , 0
  4262.8     .05       0  4694.3      .1       0  4876.5     .08       0
  4995.2     .07       0  5001.2     .08       0    5352     .05       0
    5378      .1       0  5668.6     .05       0
Bank Sta=4995.2,5001.2
XS Rating Curve= 0 ,0
Exp/Cntr=0.3,0.1

Type RM Length L Ch R = 1 ,1770    ,137,137,137
BEGIN DESCRIPTION:
BURTON CREEK TRIB D.1 3.0
END DESCRIPTION:
XS GIS Cut Line= 3
      3544777.67     10221042.56      3544122.55     10220369.98
       3543466.7     10219740.16
#Sta/Elev= 30
    3885  324.02  4002.7  324.36  4038.2  322.43  4101.7  322.68  4193.1  320.73
  4299.8  318.44  4441.2  317.39  4476.5  316.43  4625.1  315.43  4722.8  316.02
  4837.8  313.57    4915  311.88  4978.5  311.81  4992.7  309.18  4996.9  309.15
  4999.6  308.65  5002.9  309.15    5014  312.26  5028.2  312.96  5063.4  312.47
  5204.9  314.49  5289.8  317.03  5332.3  316.91  5438.3  319.62  5494.9  318.76
  5565.6  319.47  5600.9   318.9  5622.2  319.67  5643.3  318.83  5733.2  318.93
#Mann= 6 ,-1 , 0
    3885      .1       0  4193.1     .08       0  4722.8     .05       0
  4837.8     .08       0  4996.9     .07       0  5002.9     .08       0
Bank Sta=4996.9,5002.9
XS Rating Curve= 0 ,0
Exp/Cntr=0.3,0.1

Type RM Length L Ch R = 1 ,1633    ,1151,1151,1151
BEGIN DESCRIPTION:
BURTON CREEK TRIB D.1 2.0
END DESCRIPTION:
XS GIS Cut Line= 3
      3544842.11     10220991.64      3544000.15     10220047.06
      3543660.02     10219675.76
#Sta/Elev= 30
  3881.2  324.95  3883.8  324.95  3902.5  323.27  4065.6  322.61  4206.7  320.04
  4306.4   318.8  4575.6  314.75    4620  315.26  4639.1   317.5  4645.8  316.01
  4653.3  317.08  4667.5  314.67  4792.6  314.47  4865.7  314.11  4957.7  309.99
  4991.7  310.05    5004  307.97  5006.8  307.47    5010  307.97  5035.4  311.72
  5099.8   310.4  5155.9  314.59    5220  314.65    5241  316.24  5326.1  317.12
    5347  318.54  5405.9  318.67  5414.1  318.33  5515.8  317.92  5650.1  317.85
#Mann= 12 ,-1 , 0
  3881.2     .08       0  3883.8      .1       0  4206.7     .15       0
  4306.4     .08       0    4620     .05       0  4792.6     .08       0
  4991.7     .05       0    5004     .04       0    5010     .05       0
  5405.9     .08       0  5414.1     .05       0  5515.8     .08       0
Bank Sta=5004,5010
XS Rating Curve= 0 ,0
Exp/Cntr=0.3,0.1

Type RM Length L Ch R = 1 ,482     ,0,0,0
BEGIN DESCRIPTION:
BURTON CREEK TRIB D.1 1.0
END DESCRIPTION:
XS GIS Cut Line= 4
      3544892.11     10220391.61      3544896.26     10219974.29
      3544618.45     10219560.96       3543942.1     10219591.64
#Sta/Elev= 30
  4340.8   317.5  4341.3   317.5  4360.8  315.94  4410.8  314.92  4635.9  312.43
  4740.8  311.95  4810.7     310    4915  308.24  4929.9  306.45  4942.1  306.17
    4972  306.63  5011.4  305.99  5014.1  305.49  5017.4  305.99    5065  306.12
    5080  307.01  5086.7  308.86  5094.9  309.68  5129.7  309.97  5202.9  309.05
    5224  310.11  5262.5  310.07  5292.5  311.63  5332.6  311.46  5352.6  312.36
  5379.6  315.43  5432.7  315.62  5462.7   312.9  5492.7  312.53  5933.2  316.14
#Mann= 7 ,-1 , 0
  4340.8     .15       0  4341.3     .08       0  4635.9     .05       0
  4810.7     .08       0  5011.4     .07       0  5017.4     .08       0
  5129.7     .05       0
Bank Sta=5011.4,5017.4
XS Rating Curve= 0 ,0
Exp/Cntr=0.3,0.1
Stream Node=BURTON CREEK TRI,Reach-1         , 0 , 0 ,Upstream end
Stream Node=BURTON CREEK TRI,Reach-1         , 0 , 1 ,Downstream end

Chan Stop Cuts=-1
Use User Specified Reach Order=0
Composite Channel Slope=5