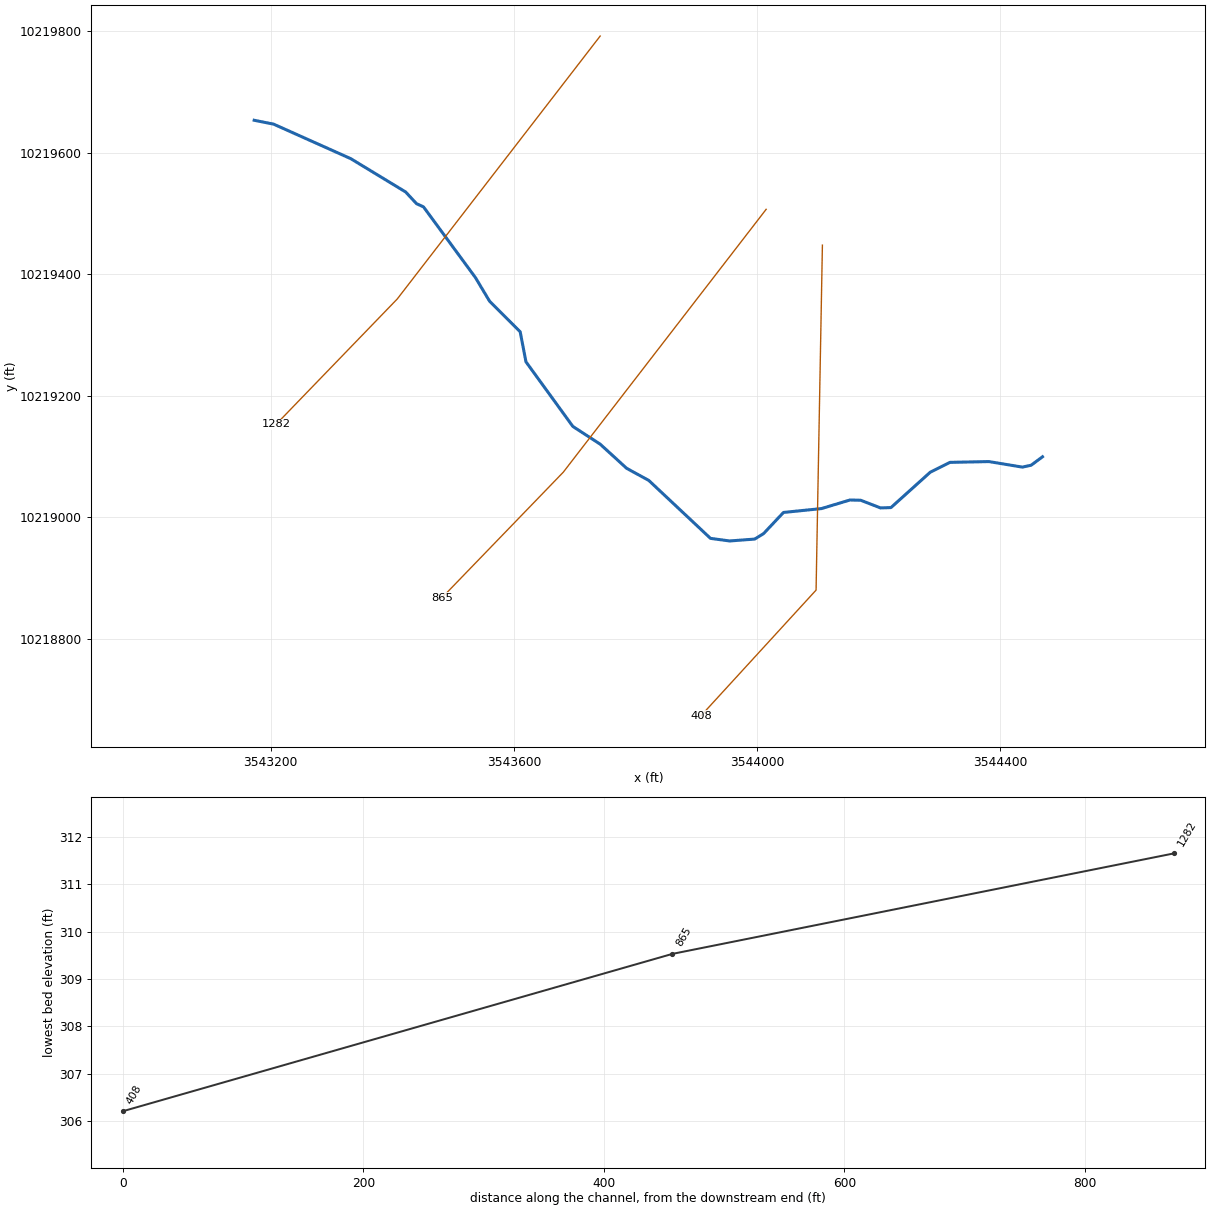
--- BURTON CREEK TRIB D 2.prj (project) ---

Proj Title=BURTON CREEK TRIB D 2 Base Level Engineering
Current Plan=p01
Default Exp/Contr=0.3,0.1
English Units
Geom File=g01
Flow File=f01
Plan File=p01
BEGIN DESCRIPTION:
BURTON CREEK TRIB D 2
END DESCRIPTION:

--- BURTON CREEK TRIB D 2.p01 (plan) ---

Plan Title=Multiple Run
Short Identifier=Multiple
Geom File=g01
Flow File=f01
Subcritical Flow
K Sum by GR= 0
Std Step Tol= 0.01
Critical Tol= 0.01
Num of Std Step Trials= 20
Max Error Tol= 0.3
Flow Tol Ratio= 0.001
Split Flow NTrial= 30
Split Flow Tol= 0.02
Split Flow Ratio= 0.02
Log Output Level= 0
Friction Slope Method= 1
Unsteady Friction Slope Method= 2
Unsteady Bridges Friction Slope Method= 1
Parabolic Critical Depth
Global Vel Dist=  1 , 1 , 1
Global Log Level= 0
CheckData=True
Encroach Param= -1, 0, 0, 0
BEGIN DESCRIPTION:
Multiple Run
END DESCRIPTION:

--- BURTON CREEK TRIB D 2.f01 (steady flow) ---

Flow Title=Multiple
Number of Profiles=7
Profile Names=10-year,25-year,50-year,1pct_min,100-year,1pct_plu,500-year
River Rch & RM= BURTON CREEK TRI,Reach-1,1282
     173     215     246     207     280     378     363
Boundary for River Rch & Prof#=BURTON CREEK TRI,Reach-1,1
Up Type=0
Dn Type=3
Dn Slope=0.005
Boundary for River Rch & Prof#=BURTON CREEK TRI,Reach-1,2
Up Type=0
Dn Type=3
Dn Slope=0.005
Boundary for River Rch & Prof#=BURTON CREEK TRI,Reach-1,3
Up Type=0
Dn Type=3
Dn Slope=0.005
Boundary for River Rch & Prof#=BURTON CREEK TRI,Reach-1,4
Up Type=0
Dn Type=3
Dn Slope=0.005
Boundary for River Rch & Prof#=BURTON CREEK TRI,Reach-1,5
Up Type=0
Dn Type=3
Dn Slope=0.005
Boundary for River Rch & Prof#=BURTON CREEK TRI,Reach-1,6
Up Type=0
Dn Type=3
Dn Slope=0.005
Boundary for River Rch & Prof#=BURTON CREEK TRI,Reach-1,7
Up Type=0
Dn Type=3
Dn Slope=0.005

--- BURTON CREEK TRIB D 2.g01 (geometry) ---

Geom Title=Existing Conditions

River Reach=BURTON CREEK TRI,Reach-1
Reach XY= 30
      3543172.70     10219653.08      3543204.76     10219646.67
      3543331.57     10219589.94      3543421.98     10219535.07
      3543439.81     10219515.88      3543451.38     10219510.52
      3543536.84     10219394.16      3543560.05     10219355.39
      3543610.48     10219304.99      3543620.01     10219255.50
      3543697.15     10219149.21      3543742.16     10219120.00
      3543785.70     10219080.29      3543822.04     10219060.42
      3543923.66     10218965.01      3543955.09     10218960.72
      3543996.32     10218963.80      3544010.96     10218972.72
      3544043.85     10219007.65      3544106.21     10219013.99
      3544153.29     10219028.14      3544171.01     10219027.69
      3544203.41     10219015.10      3544220.71     10219015.66
      3544285.40     10219073.88      3544317.81     10219090.06
      3544381.91     10219091.36      3544436.94     10219082.26
      3544451.37     10219085.34      3544470.15     10219099.24

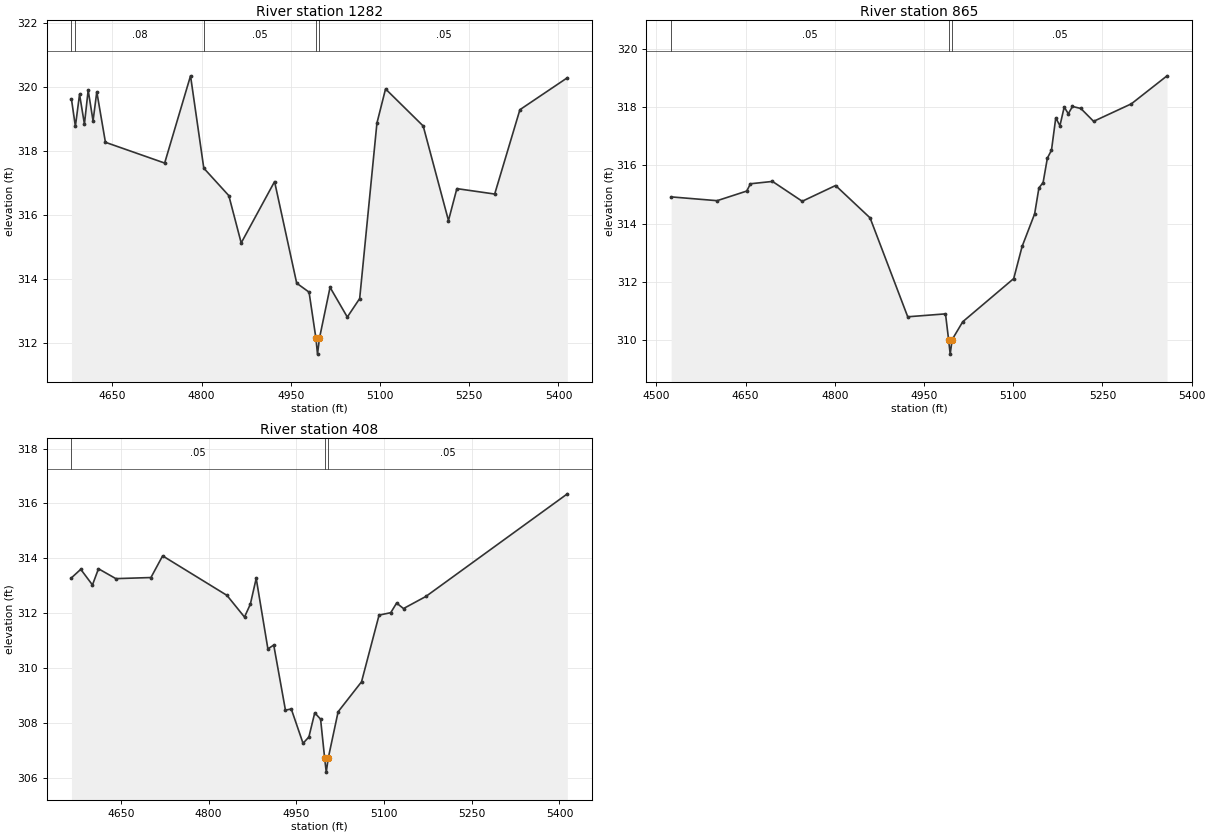
Type RM Length L Ch R = 1,1282,417,417,417
BEGIN DESCRIPTION:
BURTON CREEK TRIB D.2 2.1
END DESCRIPTION:
XS GIS Cut Line= 3
      3543742.13     10219791.68      3543408.21     10219359.00
      3543208.59     10219152.44
#Sta/Elev= 30
  4581.2  319.63  4587.8  318.78  4594.8  319.78  4603.0  318.85  4609.3  319.91
  4617.5  318.95  4623.8  319.86  4638.3  318.28  4737.9  317.63  4781.4  320.36
  4803.7  317.47  4845.8  316.61  4866.6  315.13  4922.7  317.05  4959.9  313.87
  4980.7  313.59  4992.2  312.15  4994.9  311.65  4998.2  312.15  5016.0  313.74
  5045.0  312.81  5065.8  313.39  5094.8  318.88  5109.3  319.95  5172.6  318.79
  5215.1  315.83  5229.2  316.83  5292.8  316.66  5335.2  319.30  5415.0  320.30
#Mann=5,-1,0
  4581.2    0.05       0  4587.8    0.08       0  4803.7    0.05       0
  4992.2    0.04       0  4998.2    0.05       0
Bank Sta=4992.2,4998.2
Exp/Cntr=0.3,0.1

Type RM Length L Ch R = 1,865,457,457,457
BEGIN DESCRIPTION:
BURTON CREEK TRIB D.2 2.0
END DESCRIPTION:
XS GIS Cut Line= 3
      3544015.31     10219506.54      3543681.41     10219073.89
      3543481.77     10218867.31
#Sta/Elev= 30
  4524.8  314.92  4602.1  314.79  4651.9  315.12  4658.2  315.37  4695.2  315.45
  4745.2  314.77  4801.3  315.31  4859.3  314.20  4922.6  310.81  4986.1  310.91
  4991.3  310.03  4994.0  309.53  4997.3  310.03  5015.1  310.64  5100.8  312.12
  5114.9  313.22  5136.0  314.34  5143.2  315.23  5150.2  315.41  5157.4  316.25
  5164.3  316.52  5171.5  317.63  5178.5  317.36  5185.7  318.00  5192.6  317.77
  5199.6  318.02  5213.7  317.95  5235.1  317.51  5298.6  318.11  5358.6  319.07
#Mann=3,-1,0
  4524.8    0.05       0  4991.3    0.04       0  4997.3    0.05       0
Bank Sta=4991.3,4997.3
Exp/Cntr=0.3,0.1

Type RM Length L Ch R = 1,408,0,0,0
BEGIN DESCRIPTION:
BURTON CREEK TRIB D.2 1.0
END DESCRIPTION:
XS GIS Cut Line= 3
      3544107.87     10219447.53      3544097.45     10218879.83
      3543908.18     10218673.20
#Sta/Elev= 30
  4565.5  313.29  4581.4  313.60  4601.4  313.03  4611.7  313.62  4641.4  313.26
  4701.4  313.30  4721.4  314.09  4831.4  312.65  4861.4  311.86  4871.4  312.33
  4881.4  313.27  4901.4  310.70  4911.4  310.84  4931.4  308.47  4941.4  308.51
  4961.5  307.26  4971.5  307.49  4981.5  308.37  4991.5  308.14  4998.5  306.71
  5001.2  306.21  5004.5  306.71  5021.5  308.41  5061.5  309.50  5091.5  311.93
  5111.5  312.02  5121.5  312.37  5133.3  312.17  5171.5  312.61  5413.5  316.35
#Mann=3,-1,0
  4565.5    0.05       0  4998.5    0.04       0  5004.5    0.05       0
Bank Sta=4998.5,5004.5
Exp/Cntr=0.3,0.1

Chan Stop Cuts=-1