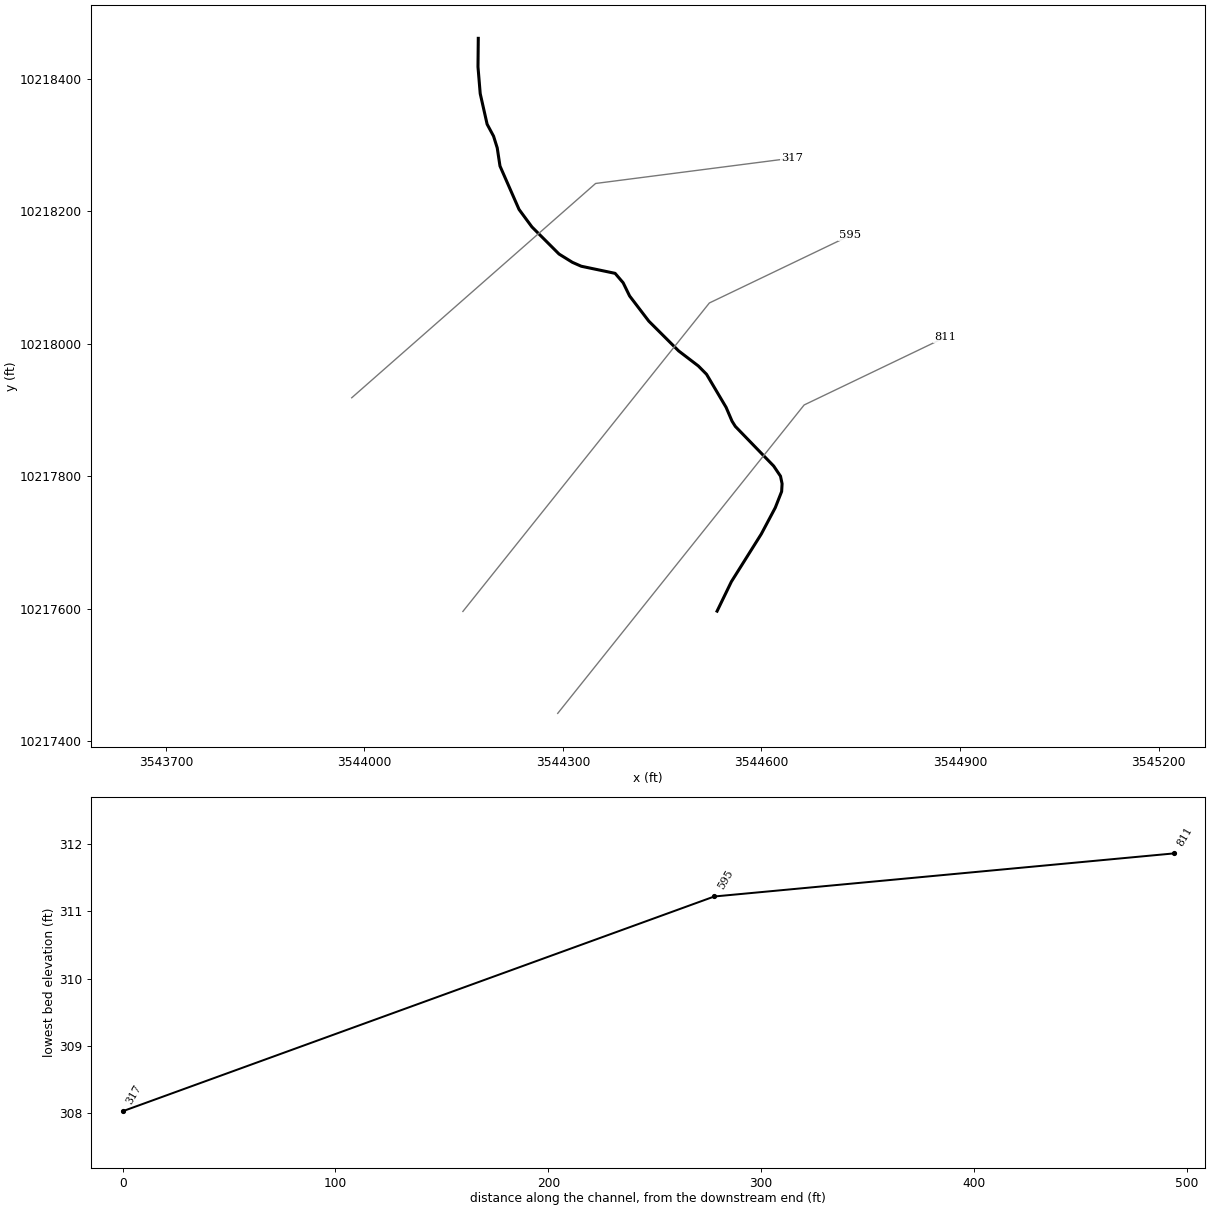
--- BURTON CREEK TRIB D 3.prj (project) ---

Proj Title=BURTON CREEK TRIB D 3 Base Level Engineering
Current Plan=p01
Default Exp/Contr=0.3,0.1
English Units
Geom File=g01
Flow File=f01
Plan File=p01
Y Axis Title=Elevation
X Axis Title(PF)=Main Channel Distance
X Axis Title(XS)=Station
BEGIN DESCRIPTION:
BURTON CREEK TRIB D 3
END DESCRIPTION:
DSS Export Rating Curves= 0
DSS Export Rating Curve Sorted= 0
DSS Export Volume Flow Curves= 0
DXF OffsetX= 0
DXF OffsetY= 0
DXF ScaleX= 1
DXF ScaleY= 10

--- BURTON CREEK TRIB D 3.p01 (plan) ---

Plan Title=Multiple Run
Short Identifier=Multiple
Geom File=g01
Flow File=f01
Subcritical Flow
K Sum by GR= 0
Std Step Tol= 0.01
Critical Tol= 0.01
Num of Std Step Trials= 20
Max Error Tol= 0.3
Flow Tol Ratio= 0.001
Split Flow NTrial= 30
Split Flow Tol= 0.02
Split Flow Ratio= 0.02
Log Output Level= 0
Friction Slope Method= 1
Unsteady Friction Slope Method= 2
Unsteady Bridges Friction Slope Method= 1
Parabolic Critical Depth
Global Vel Dist=  1 , 1 , 1
Global Log Level= 0
CheckData=True
Encroach Param= -1, 0, 0, 0
BEGIN DESCRIPTION:
Multiple Run
END DESCRIPTION:

--- BURTON CREEK TRIB D 3.f01 (steady flow) ---

Flow Title=Multiple
Program Version=4.10
Number of Profiles= 7
Profile Names=10-year,25-year,50-year,1pct_min,100-year,1pct_plu,500-year
River Rch & RM=BURTON CREEK TRI,Reach-1         ,811
     232     295     343     294     398     538     533
Boundary for River Rch & Prof#=BURTON CREEK TRI,Reach-1         , 1
Up Type= 0
Dn Type= 3
Dn Slope=0.011
Boundary for River Rch & Prof#=BURTON CREEK TRI,Reach-1         , 2
Up Type= 0
Dn Type= 3
Dn Slope=0.011
Boundary for River Rch & Prof#=BURTON CREEK TRI,Reach-1         , 3
Up Type= 0
Dn Type= 3
Dn Slope=0.011
Boundary for River Rch & Prof#=BURTON CREEK TRI,Reach-1         , 4
Up Type= 0
Dn Type= 3
Dn Slope=0.011
Boundary for River Rch & Prof#=BURTON CREEK TRI,Reach-1         , 5
Up Type= 0
Dn Type= 3
Dn Slope=0.011
Boundary for River Rch & Prof#=BURTON CREEK TRI,Reach-1         , 6
Up Type= 0
Dn Type= 3
Dn Slope=0.011
Boundary for River Rch & Prof#=BURTON CREEK TRI,Reach-1         , 7
Up Type= 0
Dn Type= 3
Dn Slope=0.011
DSS Import GetInterval= 0
DSS Import GetPeak= 0
DSS Import FillOption= 0

--- BURTON CREEK TRIB D 3.g01 (geometry) ---

Geom Title=Existing Conditions
Program Version=4.10

River Reach=BURTON CREEK TRI,Reach-1
Reach XY= 30
      3544532.93     10217596.16      3544554.51     10217640.63
      3544599.73     10217712.68      3544620.87     10217752.48
      3544630.46     10217776.87      3544631.15     10217788.64
      3544628.76     10217800.07      3544618.44     10217815.42
       3544560.5     10217875.28      3544555.58     10217883.09
      3544546.55     10217904.09        3544517.     10217954.04
      3544504.65     10217966.56      3544474.91     10217989.29
      3544429.73     10218034.37      3544400.75     10218072.37
      3544391.01     10218092.31      3544378.86     10218106.54
      3544327.67     10218117.28      3544314.27     10218123.21
      3544294.14     10218135.71      3544253.16     10218176.68
      3544233.72     10218203.07       3544204.9      10218268.7
      3544200.73     10218296.13      3544195.18     10218313.83
      3544185.46     10218331.89      3544175.04     10218378.07
      3544171.67     10218418.45      3544172.11     10218461.64

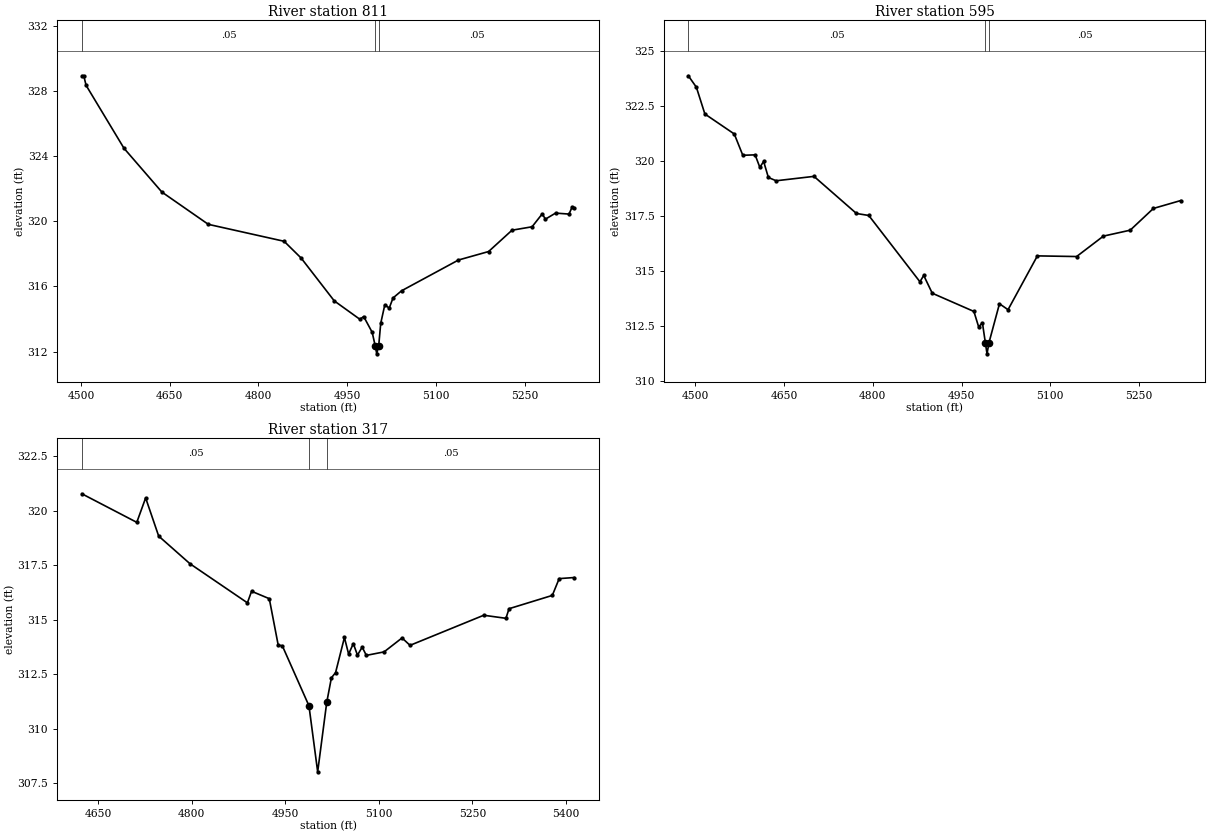
Type RM Length L Ch R = 1 ,811     ,216,216,216
BEGIN DESCRIPTION:
BURTON CREEK TRIB D.3 2.0
END DESCRIPTION:
XS GIS Cut Line= 3
      3544292.13     10217441.67      3544664.48     10217907.68
      3544877.09     10218009.65
#Sta/Elev= 30
  4501.6  328.93  4504.8  328.93  4508.8  328.34  4572.8  324.48  4636.9  321.79
  4715.3  319.81  4843.4  318.77  4872.2  317.74  4928.2  315.11  4971.5  313.98
  4977.9  314.15  4992.3  313.18  4997.3  312.36    5000  311.86  5003.3  312.36
  5006.7  313.73  5013.6  314.87  5021.1  314.67  5027.5  315.29  5041.9  315.73
  5138.1  317.62    5189  318.14  5228.6  319.45  5262.5  319.66  5279.6  320.45
  5285.1  320.13  5302.2   320.5  5324.9  320.44  5330.4  320.89  5333.9  320.81
#Mann= 3 ,-1 , 0
  4501.6     .05       0  4997.3     .04       0  5003.3     .05       0
Bank Sta=4997.3,5003.3
XS Rating Curve= 0 ,0
Exp/Cntr=0.3,0.1

Type RM Length L Ch R = 1 ,595     ,278,278,278
BEGIN DESCRIPTION:
BURTON CREEK TRIB D.3 2.1
END DESCRIPTION:
XS GIS Cut Line= 3
      3544148.85     10217595.69      3544521.25     10218061.76
      3544733.88     10218163.74
#Sta/Elev= 30
  4488.2  323.88  4501.8  323.36  4516.2  322.14  4565.9  321.23  4580.3  320.26
  4601.1  320.28  4609.1  319.71  4615.5  319.98  4623.5  319.25  4636.6   319.1
  4700.6   319.3  4772.4  317.61  4793.2  317.52  4879.7   314.5  4886.1  314.79
  4900.5  313.98  4970.9  313.15  4978.9  312.45  4985.3  312.63  4990.3  311.72
  4993.1  311.22  4996.3  311.72  5014.1   313.5  5028.6  313.23  5078.2  315.68
  5144.5  315.65  5189.8  316.58  5235.1  316.85  5274.3  317.84  5320.6   318.2
#Mann= 3 ,-1 , 0
  4488.2     .05       0  4990.3     .04       0  4996.3     .05       0
Bank Sta=4990.3,4996.3
XS Rating Curve= 0 ,0
Exp/Cntr=0.3,0.1

Type RM Length L Ch R = 1 ,317     ,0,0,0
BEGIN DESCRIPTION:
BURTON CREEK TRIB D.3 1.0
END DESCRIPTION:
XS GIS Cut Line= 3
      3543980.89     10217918.54      3544349.38     10218242.35
      3544646.17     10218280.65
#Sta/Elev= 30
  4623.8  320.78  4711.9  319.47  4726.1  320.59    4747  318.84  4797.3  317.57
  4889.3  315.78    4896  316.31  4924.4  315.97  4938.7  313.84  4945.3  313.81
    4988  311.06    5002  308.03  5016.5  311.21    5024  312.34  5030.7  312.58
  5044.9  314.19  5051.6  313.43  5059.2  313.91  5065.8  313.38  5073.4  313.75
    5080  313.37  5108.5  313.53  5137.3  314.17  5150.1  313.83  5268.3  315.21
  5303.9  315.07  5308.9  315.51  5378.3  316.12  5389.3  316.89  5413.6  316.94
#Mann= 3 , 0 , 0
  4623.8     .05       0    4988     .04       0  5016.5     .05       0
Bank Sta=4988,5016.5
XS Rating Curve= 0 ,0
Exp/Cntr=0.3,0.1

Chan Stop Cuts=-1
Use User Specified Reach Order=0
Composite Channel Slope=5