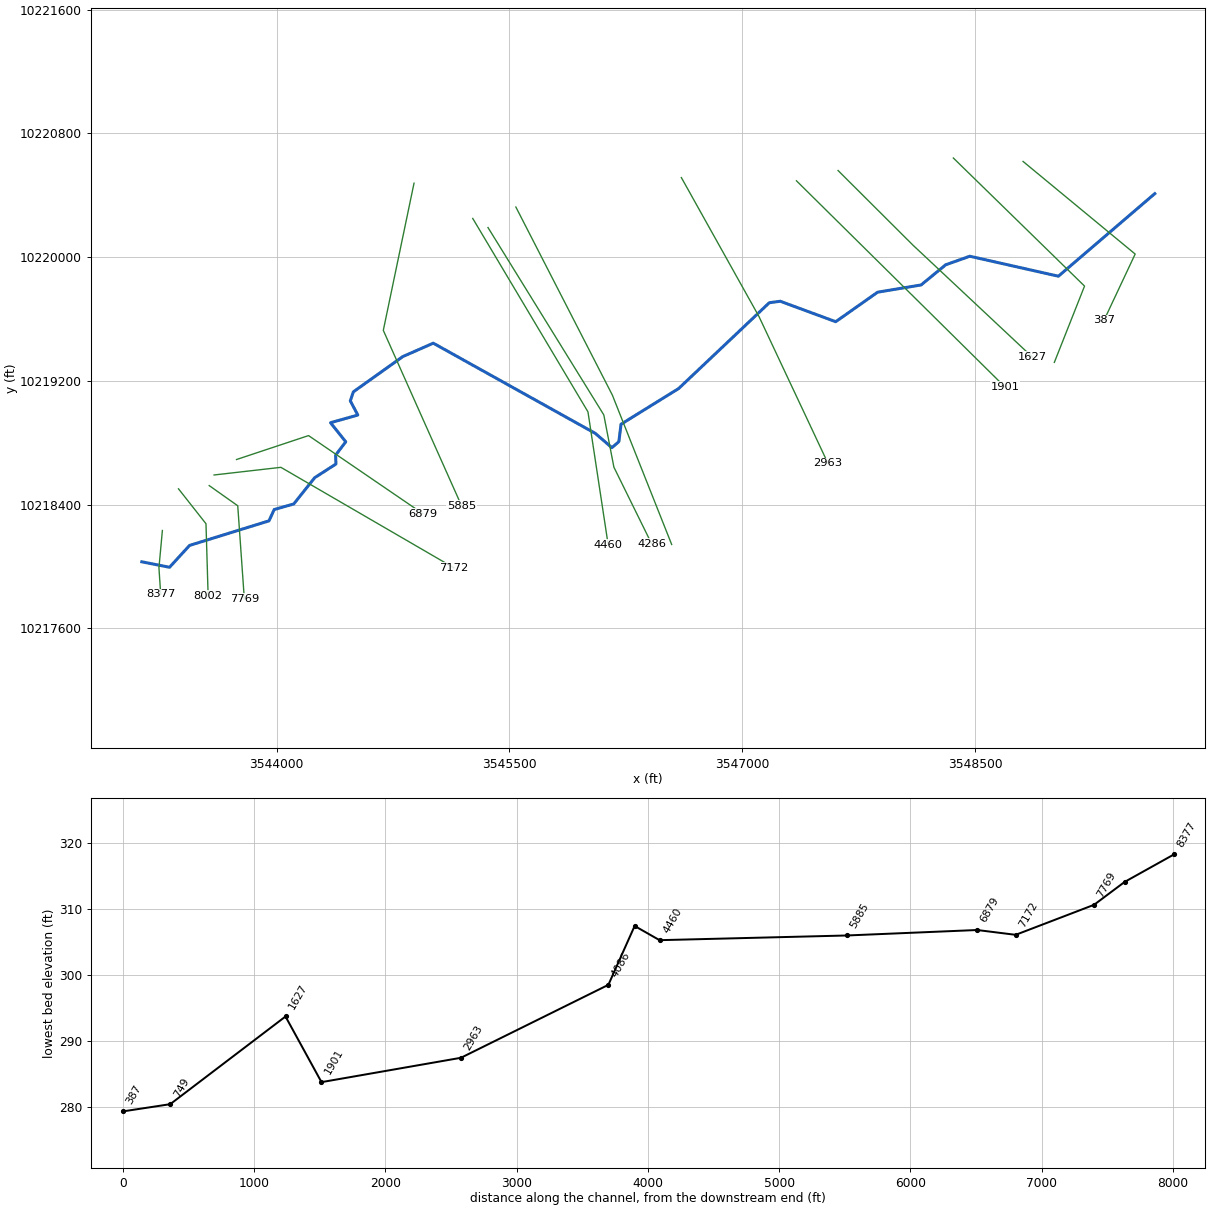
--- BURTON CREEK TRIB D.prj (project) ---

Proj Title=BURTON CREEK TRIB D Base Level Engineering
Current Plan=p01
Default Exp/Contr=0.3,0.1
English Units
Geom File=g01
Flow File=f01
Plan File=p01
Y Axis Title=Elevation
X Axis Title(PF)=Main Channel Distance
X Axis Title(XS)=Station
BEGIN DESCRIPTION:
BURTON CREEK TRIB D
END DESCRIPTION:
DSS Export Rating Curves= 0
DSS Export Rating Curve Sorted= 0
DSS Export Volume Flow Curves= 0
DXF OffsetX= 0
DXF OffsetY= 0
DXF ScaleX= 1
DXF ScaleY= 10

--- BURTON CREEK TRIB D.p01 (plan) ---

Plan Title=Multiple Run
Short Identifier=Multiple
Geom File=g01
Flow File=f01
Subcritical Flow
K Sum by GR= 0
Std Step Tol= 0.01
Critical Tol= 0.01
Num of Std Step Trials= 20
Max Error Tol= 0.3
Flow Tol Ratio= 0.001
Split Flow NTrial= 30
Split Flow Tol= 0.02
Split Flow Ratio= 0.02
Log Output Level= 0
Friction Slope Method= 1
Unsteady Friction Slope Method= 2
Unsteady Bridges Friction Slope Method= 1
Parabolic Critical Depth
Global Vel Dist=  1 , 1 , 1
Global Log Level= 0
CheckData=True
Encroach Param= -1, 0, 0, 0
BEGIN DESCRIPTION:
Multiple Run
END DESCRIPTION:

--- BURTON CREEK TRIB D.f01 (steady flow) ---

Flow Title=Multiple
Number of Profiles=7
Profile Names=10-year,25-year,50-year,1pct_min,100-year,1pct_plu,500-year
River Rch & RM= BURTON CREEK TRI,Reach-1,8377
     120     146     165     138     186     252     236
River Rch & RM= BURTON CREEK TRI,Reach-1,7172
     303     391     461     399     539     729     738
River Rch & RM= BURTON CREEK TRI,Reach-1,5885
     437     579     692     607     821    1110    1157
River Rch & RM= BURTON CREEK TRI,Reach-1,4460
     757    1031    1256    1119    1514    2047    2206
Boundary for River Rch & Prof#=BURTON CREEK TRI,Reach-1,1
Up Type=0
Dn Type=3
Dn Slope=0.005
Boundary for River Rch & Prof#=BURTON CREEK TRI,Reach-1,2
Up Type=0
Dn Type=3
Dn Slope=0.005
Boundary for River Rch & Prof#=BURTON CREEK TRI,Reach-1,3
Up Type=0
Dn Type=3
Dn Slope=0.005
Boundary for River Rch & Prof#=BURTON CREEK TRI,Reach-1,4
Up Type=0
Dn Type=3
Dn Slope=0.005
Boundary for River Rch & Prof#=BURTON CREEK TRI,Reach-1,5
Up Type=0
Dn Type=3
Dn Slope=0.005
Boundary for River Rch & Prof#=BURTON CREEK TRI,Reach-1,6
Up Type=0
Dn Type=3
Dn Slope=0.005
Boundary for River Rch & Prof#=BURTON CREEK TRI,Reach-1,7
Up Type=0
Dn Type=3
Dn Slope=0.005

--- BURTON CREEK TRIB D.g01 (geometry) ---

Geom Title=Existing Conditions
Program Version=4.10

River Reach=BURTON CREEK TRI,Reach-1
Reach XY= 30
      3543131.79      10218030.4      3543310.51     10217995.14
      3543439.43     10218136.34      3543951.08     10218295.16
      3543984.52     10218368.16      3544110.52     10218404.18
      3544245.18      10218573.9      3544382.33     10218662.45
      3544380.25     10218719.74      3544445.52      10218806.2
      3544347.61     10218929.46       3544523.3     10218979.11
      3544474.86     10219070.78      3544494.47     10219128.85
      3544812.53     10219356.63      3545009.45     10219443.62
      3546053.18     10218860.54      3546160.01     10218768.08
       3546205.1      10218807.3      3546218.99      10218919.8
      3546590.19     10219150.44      3547173.96     10219704.91
      3547244.49     10219714.67      3547601.92     10219582.39
      3547872.11     10219773.36      3548152.05     10219820.02
      3548310.47     10219950.23      3548465.64     10220005.57
      3549036.39     10219876.45      3549657.31     10220409.98

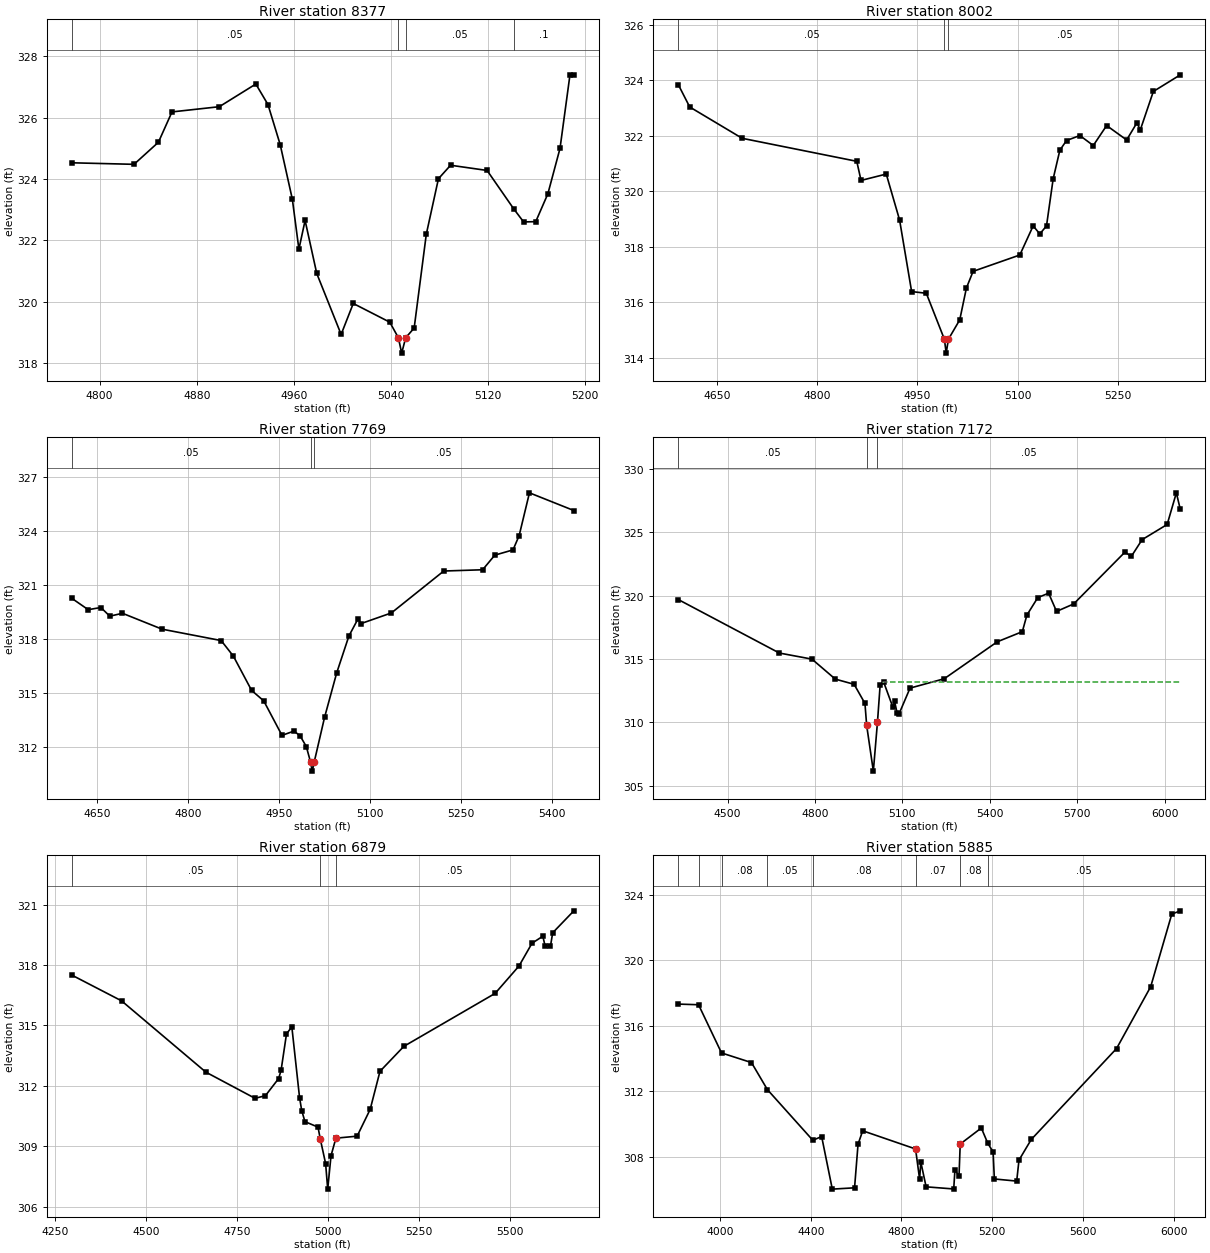
Type RM Length L Ch R = 1 ,8377    ,375,375,375
BEGIN DESCRIPTION:
BURTON CREEK TRIB D 17.0
END DESCRIPTION:
XS GIS Cut Line= 3
      3543264.33     10218232.71      3543242.11     10217991.64
      3543253.48     10217820.31
#Sta/Elev= 30
    4777  324.53  4828.3  324.48  4848.4   325.2  4859.6  326.19  4898.6  326.36
  4928.7   327.1  4938.7  326.43  4948.8  325.12  4958.8  323.34  4964.2  321.71
  4969.3  322.65  4978.9  320.92    4999  318.93    5009  319.94  5039.1  319.33
  5046.2  318.82  5048.9  318.32  5052.2  318.82  5059.2  319.14  5069.2   322.2
  5079.2  324.01  5089.2  324.45  5119.3  324.28  5141.2  323.03  5149.4   322.6
  5159.4  322.61  5169.4  323.52  5179.4     325  5187.6   327.4  5190.8   327.4
#Mann= 4 ,-1 , 0
    4777     .05       0  5046.2     .04       0  5052.2     .05       0
  5141.2      .1       0
Bank Sta=5046.2,5052.2
XS Rating Curve= 0 ,0
Exp/Cntr=0.3,0.1

Type RM Length L Ch R = 1 ,8002    ,233,233,233
BEGIN DESCRIPTION:
BURTON CREEK TRIB D 16.0
END DESCRIPTION:
XS GIS Cut Line= 3
      3543368.07     10218502.17      3543545.14     10218276.49
      3543559.03     10217811.26
#Sta/Elev= 30
  4591.6  323.85  4608.8  323.04  4687.4  321.91  4859.1  321.08  4865.5  320.39
  4903.3  320.62  4923.3  318.96  4941.3  316.38  4963.3  316.32  4990.4  314.66
  4993.1  314.16  4996.4  314.66  5013.4  315.36  5023.4  316.51  5033.4  317.11
  5103.4   317.7  5123.4  318.75  5133.4  318.46  5143.4  318.75  5153.4  320.45
  5163.4  321.48  5173.4  321.83  5193.4  322.01  5213.5  321.65  5233.5  322.37
  5263.5  321.85  5278.9  322.47  5283.9  322.21  5303.5   323.6  5343.9   324.2
#Mann= 3 ,-1 , 0
  4591.6     .05       0  4990.4     .04       0  4996.4     .05       0
Bank Sta=4990.4,4996.4
XS Rating Curve= 0 ,0
Exp/Cntr=0.3,0.1

Type RM Length L Ch R = 1 ,7769    ,597,597,597
BEGIN DESCRIPTION:
BURTON CREEK TRIB D 15.0
END DESCRIPTION:
XS GIS Cut Line= 3
      3543566.01       10218523.      3543749.78     10218392.61
      3543792.11     10217791.63
#Sta/Elev= 30
  4607.9  320.26    4635  319.63  4655.9  319.75  4670.6  319.27  4691.5  319.43
  4756.8  318.55  4854.2  317.92  4874.3  317.06  4904.4  315.16  4924.4  314.58
  4954.5  312.67  4974.5  312.91  4984.6  312.63  4994.6  312.05  5001.6  311.19
  5004.4  310.69  5007.6  311.19  5024.7  313.67  5044.7  316.13  5064.8  318.17
  5079.8  319.12  5084.8  318.86  5134.9  319.45  5221.2  321.77  5285.3  321.84
  5305.4  322.65  5335.4  322.94  5345.5  323.73  5362.5   326.1  5435.7  325.12
#Mann= 3 ,-1 , 0
  4607.9     .05       0  5001.6     .04       0  5007.6     .05       0
Bank Sta=5001.6,5007.6
XS Rating Curve= 0 ,0
Exp/Cntr=0.3,0.1

Type RM Length L Ch R = 1 ,7172    ,293,293,293
BEGIN DESCRIPTION:
BURTON CREEK TRIB D 14.0
END DESCRIPTION:
XS GIS Cut Line= 3
      3543597.27     10218591.65      3544027.78     10218641.08
       3545142.1     10217991.64
#Sta/Elev= 30
  4330.7   319.7  4677.8  315.47  4789.6  314.99  4869.8  313.41  4934.3     313
  4971.5  311.49  4977.4  309.75  5000.3  306.14  5014.5  310.02  5023.7  312.96
    5036  313.16  5067.5  311.18  5073.3  311.65  5081.6  310.75    5089  310.69
  5126.2   312.7  5243.6  313.44  5425.6  316.36  5511.6  317.16  5527.3  318.47
  5564.6  319.85  5601.8   320.2  5629.1  318.76  5687.8  319.35    5864  323.45
  5885.5   323.1  5922.7  324.43  6008.7  325.63  6040.2  328.13  6053.8  326.82
#Mann= 3 , 0 , 0
  4330.7     .05       0  4977.4     .03       0  5014.5     .05       0
#XS Ineff= 2 , 0
                         5032.57          313.18
Permanent Ineff=
       F       F
Bank Sta=4977.4,5014.5
XS Rating Curve= 0 ,0
Exp/Cntr=0.3,0.1

Type RM Length L Ch R = 1 ,6879    ,994,994,994
BEGIN DESCRIPTION:
BURTON CREEK TRIB D 13.0
END DESCRIPTION:
XS GIS Cut Line= 3
      3543742.12     10218691.65      3544205.92     10218846.25
       3544942.1     10218341.65
#Sta/Elev= 30
    4295   317.5    4432  316.22  4663.9  312.68  4799.2  311.38  4827.8  311.51
  4864.1  312.36  4870.9  312.77  4885.8  314.58  4900.5  314.93  4921.7  311.42
  4927.7  310.77  4936.6  310.22  4972.5  309.95  4978.5  309.38  4993.4  308.14
  4999.2  306.87  5008.3  308.53  5021.7   309.4  5080.1   309.5    5116  310.83
    5143  312.72  5208.7  313.96  5459.8  316.59  5525.5  317.95  5561.3  319.08
  5591.1  319.43  5597.2  318.95  5612.1  318.94  5618.2   319.6  5676.4  320.69
#Mann= 3 , 0 , 0
    4295     .05       0  4978.5     .04       0  5021.7     .05       0
Bank Sta=4978.5,5021.7
XS Rating Curve= 0 ,0
Exp/Cntr=0.3,0.1

Type RM Length L Ch R = 1 ,5885    ,1425,1425,1425
BEGIN DESCRIPTION:
BURTON CREEK TRIB D 12.0
END DESCRIPTION:
XS GIS Cut Line= 3
      3544885.42     10220477.86      3544687.51     10219526.49
       3545192.1     10218391.66
#Sta/Elev= 30
  3815.7  317.33  3905.3  317.29  4006.5  314.35  4138.7  313.76  4208.9  312.11
  4409.2  309.02    4448  309.25    4495  306.04  4593.1  306.12  4608.5  308.78
    4629   309.6  4862.1  308.49  4879.9  306.65  4885.3  307.69  4908.6  306.18
  5030.3  306.05  5035.8  307.23  5053.6  306.82    5059  308.79    5152  309.77
  5180.8  308.83    5204  308.31  5209.5  306.66    5308  306.53  5318.1  307.81
  5372.2  309.07  5748.4  314.62  5898.8  318.39  5991.8  322.82  6029.4  323.02
#Mann= 8 ,-1 , 0
  3815.7     .15       0  3905.3      .1       0  4006.5     .08       0
  4208.9     .05       0  4409.2     .08       0  4862.1     .07       0
    5059     .08       0  5180.8     .05       0
Bank Sta=4862.1,5059
XS Rating Curve= 0 ,0
Exp/Cntr=0.3,0.1

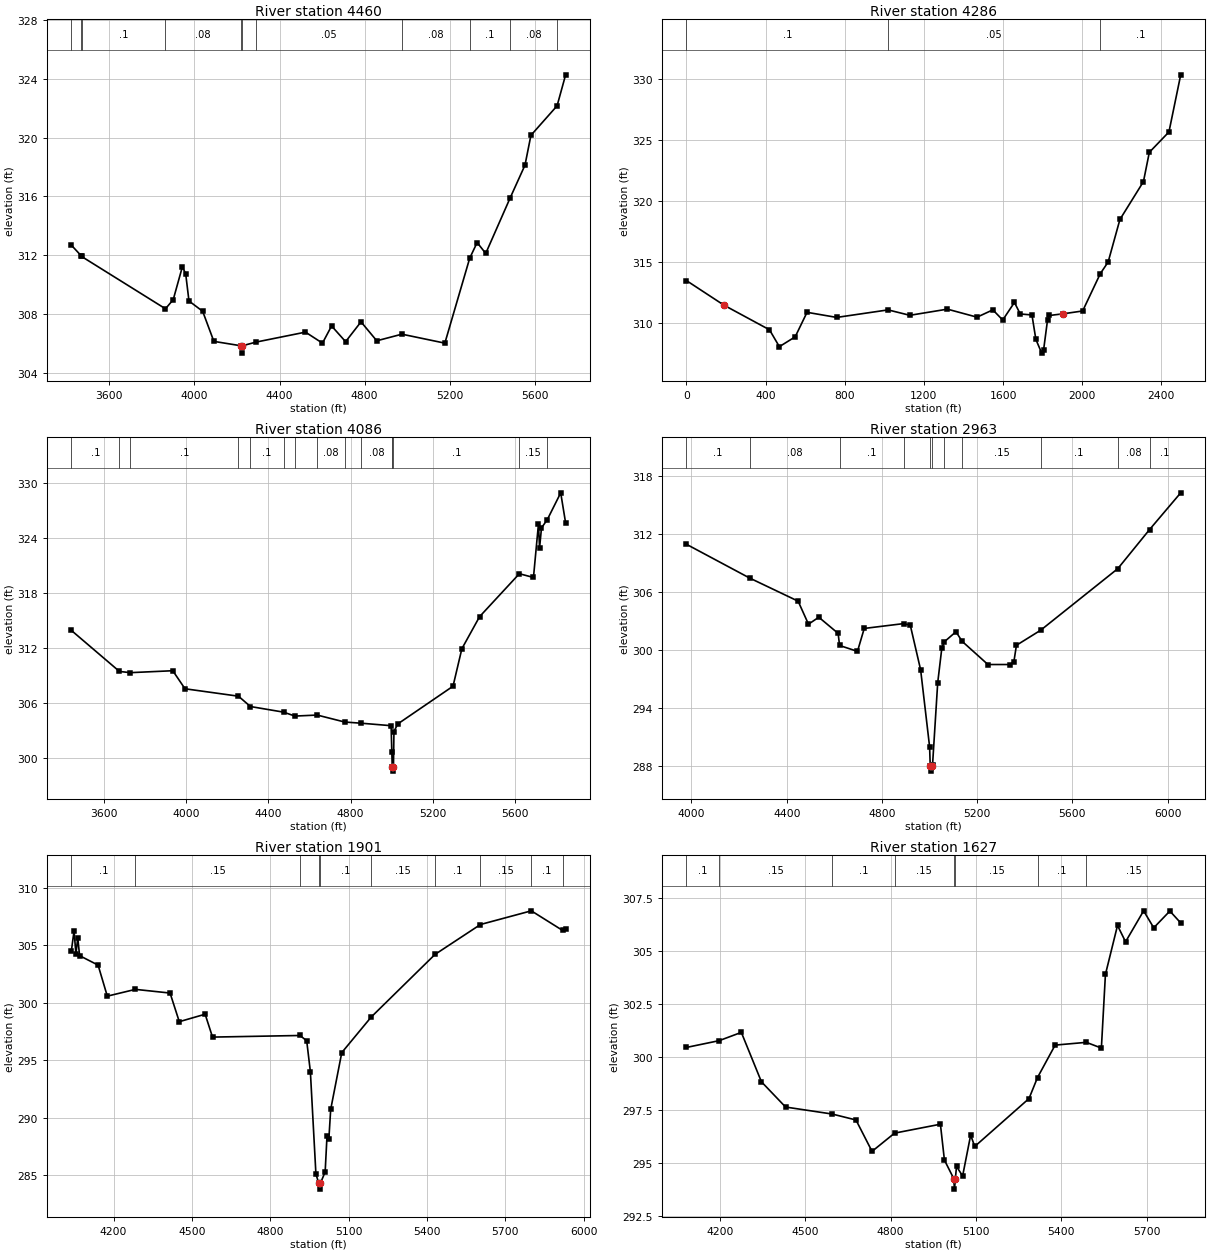
Type RM Length L Ch R = 1 ,4460    ,190,190,190
BEGIN DESCRIPTION:
BURTON CREEK TRIB D 11.0
END DESCRIPTION:
XS GIS Cut Line= 3
      3545263.69     10220249.87       3546005.9     10218999.84
      3546136.11     10218140.42
#Sta/Elev= 30
  3421.5  312.68  3467.6  311.96  3469.7  311.91  3863.7  308.35  3900.2  308.97
    3943   311.2  3958.6  310.75  3974.2  308.88  4038.5  308.18  4091.2  306.13
  4218.9  305.83  4221.7  305.33  4224.9  305.83    4289  306.08  4521.8  306.76
  4601.6  306.01  4644.5  307.18  4710.4  306.11  4782.8  307.46  4856.9  306.17
    4975  306.62  5176.9  306.01  5293.8   311.8  5328.6  312.86    5369  312.12
  5483.2  315.88  5553.5  318.13  5581.4  320.16  5704.4  322.17  5744.5  324.28
#Mann= 11 ,-1 , 0
  3421.5     .08       0  3467.6     .05       0  3469.7      .1       0
  3863.7     .08       0  4218.9     .07       0  4224.9     .08       0
    4289     .05       0    4975     .08       0  5293.8      .1       0
  5483.2     .08       0  5704.4      .1       0
Bank Sta=4218.9,4224.9
XS Rating Curve= 0 ,0
Exp/Cntr=0.3,0.1

Type RM Length L Ch R = 1 ,4286    ,200,200,200
XS GIS Cut Line= 4
        3545362.       10220191.        3546108.       10218980.
        3546173.       10218642.        3546416.       10218147.
#Sta/Elev= 30
       0313.4454189.8181311.4228 419.598309.4028469.5501308.0151549.4735308.8238
609.4161310.8384759.2725 310.4191019.024311.03791128.918310.59231318.736311.0989
1468.593310.43931548.516311.04011598.468 310.2051657.568311.64951687.117 310.702
1746.198310.6211 1765.86308.61691795.355307.48391805.186307.76911824.849310.2031
 1834.68310.5782  1903.5310.71572002.375310.94832091.579314.01722131.226314.9731
2190.695318.46762309.634321.58132339.369323.98872438.484325.66232497.954330.3583
#Mann= 3 ,-1 , 0
       0      .1       01019.024     .05       02091.579      .1       0
Bank Sta=189.8181,1903.5
XS Rating Curve= 0 ,0
Exp/Cntr=0.3,0.1

Type RM Length L Ch R = 1 ,4086    ,1123,1123,1123
BEGIN DESCRIPTION:
BURTON CREEK TRIB D 9.0
END DESCRIPTION:
XS GIS Cut Line= 3
      3545541.49     10220323.62       3546163.2     10219107.74
      3546545.14     10218142.47
#Sta/Elev= 30
  3441.7  313.92  3675.6  309.44  3728.6  309.31  3934.9  309.52  3994.3  307.55
  4254.2  306.74  4312.7  305.61  4473.4     305    4529  304.57  4637.2  304.68
  4770.9  303.92  4851.7  303.79  4996.7  303.52  5000.2  300.63  5002.1  299.06
  5004.9  298.56  5008.1  299.06  5010.5  302.88    5029  303.71  5297.8  307.83
  5340.8  311.92  5426.9  315.42  5620.4  320.11    5689   319.7  5713.3  325.53
  5718.7  322.92    5728  325.11  5756.4  326.02  5821.5  328.94  5845.4  325.65
#Mann= 15 ,-1 , 0
  3441.7      .1       0  3675.6     .08       0  3728.6      .1       0
  4254.2     .08       0  4312.7      .1       0  4473.4     .08       0
    4529      .1       0  4637.2     .08       0  4770.9      .1       0
  4851.7     .08       0  5000.2      .1       0  5002.1     .07       0
  5008.1      .1       0  5620.4     .15       0  5756.4      .1       0
Bank Sta=5002.1,5008.1
XS Rating Curve= 0 ,0
Exp/Cntr=0.3,0.1

Type RM Length L Ch R = 1 ,2963    ,1062,1062,1062
BEGIN DESCRIPTION:
BURTON CREEK TRIB D 7.0
END DESCRIPTION:
XS GIS Cut Line= 3
      3546607.62     10220514.03      3547108.01     10219615.08
       3547552.1     10218666.75
#Sta/Elev= 30
  3978.9  310.95  4244.3  307.46  4447.9  305.07  4491.4  302.69  4534.8  303.41
    4616  301.74    4622  300.49  4697.2  299.88  4725.6  302.25  4890.9  302.75
    4919  302.59  4962.5  297.97  5000.2  290.01  5002.9     288  5005.7   287.5
  5008.9     288  5012.4  288.09  5034.2  296.63  5051.5  300.22  5062.1  300.87
  5110.9  301.91  5136.7  300.92  5245.2  298.52  5336.5  298.52  5353.8  298.75
  5364.9  300.51  5466.9  302.07  5790.6  308.43    5924  312.47  6054.9  316.27
#Mann= 11 ,-1 , 0
  3978.9      .1       0  4244.3     .08       0    4622      .1       0
  4890.9     .08       0  5002.9     .07       0  5008.9     .08       0
  5062.1      .1       0  5136.7     .15       0  5466.9      .1       0
  5790.6     .08       0    5924      .1       0
Bank Sta=5002.9,5008.9
XS Rating Curve= 0 ,0
Exp/Cntr=0.3,0.1

Type RM Length L Ch R = 1 ,1901    ,274,274,274
BEGIN DESCRIPTION:
BURTON CREEK TRIB D 5.0
END DESCRIPTION:
XS GIS Cut Line= 3
      3547349.11     10220493.22      3548306.71     10219543.04
      3548692.86     10219159.88
#Sta/Elev= 30
  4038.3  304.54  4048.6  306.27  4055.7  304.24  4062.7  305.67  4069.8  304.11
  4140.6  303.29  4175.9  300.59  4283.5  301.18  4416.3  300.86  4451.6  298.37
  4550.6  299.02  4578.9  297.03    4914  297.17  4939.6  296.71  4953.7  294.02
  4974.9  285.12    4986  284.31  4988.8  283.81    4992  284.31  5010.3  285.31
  5017.3   288.4  5024.4  288.14  5031.5  290.74  5073.9  295.68  5186.5  298.77
  5431.1  304.22  5605.1  306.82  5799.9  308.01  5920.1   306.3  5931.3  306.47
#Mann= 10 ,-1 , 0
  4038.3      .1       0  4283.5     .15       0    4914      .1       0
    4986     .07       0    4992      .1       0  5186.5     .15       0
  5431.1      .1       0  5605.1     .15       0  5799.9      .1       0
  5920.1     .15       0
Bank Sta=4986,4992
XS Rating Curve= 0 ,0
Exp/Cntr=0.3,0.1

Type RM Length L Ch R = 1 ,1627    ,878,878,878
BEGIN DESCRIPTION:
BURTON CREEK TRIB D 3.0
END DESCRIPTION:
XS GIS Cut Line= 3
      3547617.23     10220559.57       3548099.9     10220076.91
      3548868.51     10219353.93
#Sta/Elev= 30
  4082.2  300.44  4197.3  300.76  4275.1  301.15  4345.8  298.82  4430.7  297.63
  4594.6   297.3  4678.2  297.02  4734.7  295.54    4814   296.4  4975.1  296.82
  4989.2  295.13  5021.8  294.26  5024.6  293.76  5027.8  294.26  5031.7  294.83
  5053.2  294.38  5081.5  296.31  5095.7  295.77  5286.6  298.03  5316.5  299.02
  5378.5  300.55  5488.1  300.68  5541.1  300.41  5555.3  303.88  5597.8  306.19
  5626.1  305.42  5689.6  306.88  5725.2  306.08  5781.9  306.87    5820  306.31
#Mann= 8 ,-1 , 0
  4082.2      .1       0  4197.3     .15       0  4594.6      .1       0
    4814     .15       0  5021.8     .07       0  5027.8     .15       0
  5316.5      .1       0  5488.1     .15       0
Bank Sta=5021.8,5027.8
XS Rating Curve= 0 ,0
Exp/Cntr=0.3,0.1

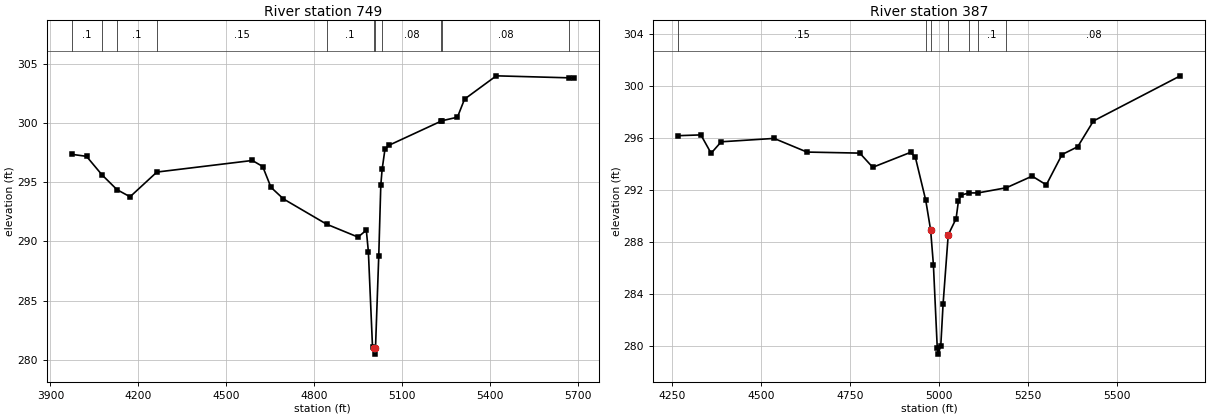
Type RM Length L Ch R = 1 ,749     ,362,362,362
BEGIN DESCRIPTION:
BURTON CREEK TRIB D 2.0
END DESCRIPTION:
XS GIS Cut Line= 3
      3548359.79     10220640.54      3549204.87     10219812.61
      3549010.41     10219319.52
#Sta/Elev= 30
  3972.9  297.37  4023.2   297.2  4075.8  295.64  4127.3  294.38  4171.8  293.78
  4263.3  295.87    4589  296.85  4624.3  296.34  4652.6  294.58    4695   293.6
  4842.5  291.46  4949.6  290.37  4977.9  290.95  4984.9  289.15  4999.1  281.04
  5003.2  280.97  5005.9  280.47  5009.2  280.97  5020.3  288.74  5027.3  294.75
  5031.8  296.09  5041.5   297.8  5055.6  298.14  5232.6  300.17  5237.6  300.22
  5288.8  300.51  5313.1  302.04  5421.4  304.01    5670  303.84    5686  303.82
#Mann= 11 ,-1 , 0
  3972.9      .1       0  4075.8     .15       0  4127.3      .1       0
  4263.3     .15       0  4842.5      .1       0  5003.2     .07       0
  5009.2      .1       0  5031.8     .08       0  5232.6      .1       0
  5237.6     .08       0    5670     .15       0
Bank Sta=5003.2,5009.2
XS Rating Curve= 0 ,0
Exp/Cntr=0.3,0.1

Type RM Length L Ch R = 1 ,387     ,0,0,0
BEGIN DESCRIPTION:
BURTON CREEK TRIB D 1.0
END DESCRIPTION:
XS GIS Cut Line= 3
      3548809.06     10220618.14      3549531.02     10220019.73
      3549329.89     10219590.43
#Sta/Elev= 30
  4266.9  296.16  4330.6  296.22  4359.3  294.81  4387.8  295.69  4536.4  295.95
  4628.9   294.9  4777.4  294.82  4813.8  293.73  4920.3  294.88  4933.6  294.51
  4962.9  291.19  4976.6  288.91  4984.4  286.25  4995.2  279.87    4998  279.37
  5005.2  280.03  5011.7  283.25  5026.1  288.54  5048.2  289.78  5054.7  291.12
  5062.5   291.6  5085.4  291.76  5109.8  291.76  5189.8  292.16  5262.1  293.05
  5301.9  292.38  5346.1  294.71  5390.2  295.31  5434.4  297.29  5678.7  300.76
#Mann= 7 ,-1 , 0
  4266.9     .15       0  4962.9      .1       0  4976.6     .07       0
  5026.1      .1       0  5085.4     .08       0  5109.8      .1       0
  5189.8     .08       0
Bank Sta=4976.6,5026.1
XS Rating Curve= 0 ,0
Exp/Cntr=0.3,0.1

Chan Stop Cuts=-1
Use User Specified Reach Order=0
Composite Channel Slope=5