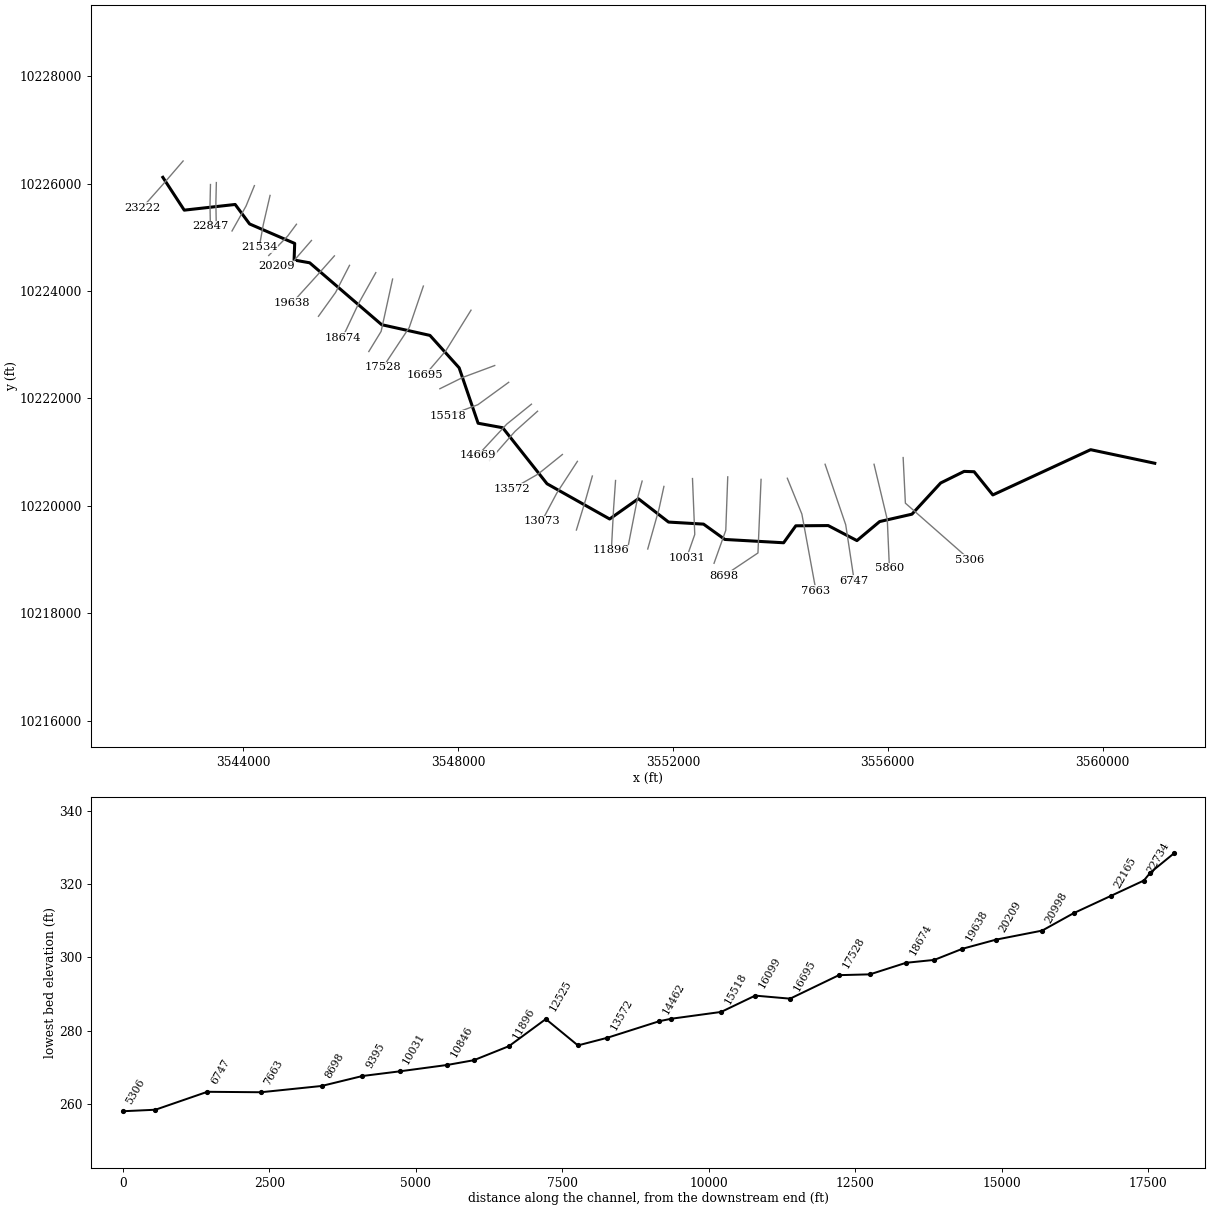
--- BURTON CREEK.prj (project) ---

Proj Title=BURTON CREEK Base Level Engineering
Current Plan=p01
Default Exp/Contr=0.3,0.1
English Units
Geom File=g01
Flow File=f01
Plan File=p01
Y Axis Title=Elevation
X Axis Title(PF)=Main Channel Distance
X Axis Title(XS)=Station
BEGIN DESCRIPTION:
BURTON CREEK
END DESCRIPTION:
DSS Export Rating Curves= 0
DSS Export Rating Curve Sorted= 0
DSS Export Volume Flow Curves= 0
DXF OffsetX= 0
DXF OffsetY= 0
DXF ScaleX= 1
DXF ScaleY= 10

--- BURTON CREEK.p01 (plan) ---

Plan Title=Multiple Run
Short Identifier=Multiple
Geom File=g01
Flow File=f01
Subcritical Flow
K Sum by GR= 0
Std Step Tol= 0.01
Critical Tol= 0.01
Num of Std Step Trials= 20
Max Error Tol= 0.3
Flow Tol Ratio= 0.001
Split Flow NTrial= 30
Split Flow Tol= 0.02
Split Flow Ratio= 0.02
Log Output Level= 0
Friction Slope Method= 1
Unsteady Friction Slope Method= 2
Unsteady Bridges Friction Slope Method= 1
Parabolic Critical Depth
Global Vel Dist=  1 , 1 , 1
Global Log Level= 0
CheckData=True
Encroach Param= -1, 0, 0, 0
BEGIN DESCRIPTION:
Multiple Run
END DESCRIPTION:

--- BURTON CREEK.f01 (steady flow) ---

Flow Title=Multiple
Program Version=4.10
Number of Profiles= 7
Profile Names=10-year,25-year,50-year,1pct_min,100-year,1pct_plu,500-year
River Rch & RM=BURTON CREEK,Reach-1         ,23222
     510     681     818     721     975    1319    1388
River Rch & RM=BURTON CREEK,Reach-1         ,17528
     676     917    1113     989    1338    1809    1937
River Rch & RM=BURTON CREEK,Reach-1         ,13073
    1475    2075    2581    2345    3172    4289    4804
River Rch & RM=BURTON CREEK,Reach-1         ,7663
    1772    2509    3136    2860    3868    5231    5905
River Rch & RM=BURTON CREEK,Reach-1         ,5306
    1822    2575    3214    2927    3959    5354    6024
River Rch & RM=BURTON CREEK,Reach-1         ,4015
    1822    2575    3214    2927    3959    5354    6024
River Rch & RM=BURTON CREEK,Reach-1         ,2228
    2011    2860    3586    3279    4434    5996    6804
River Rch & RM=BURTON CREEK,Reach-1         ,1497
    2011    2860    3586    3279    4434    5996    6804
Boundary for River Rch & Prof#=BURTON CREEK,Reach-1         , 1
Up Type= 0
Dn Type= 3
Dn Slope=0.005
Boundary for River Rch & Prof#=BURTON CREEK,Reach-1         , 2
Up Type= 0
Dn Type= 3
Dn Slope=0.005
Boundary for River Rch & Prof#=BURTON CREEK,Reach-1         , 3
Up Type= 0
Dn Type= 3
Dn Slope=0.005
Boundary for River Rch & Prof#=BURTON CREEK,Reach-1         , 4
Up Type= 0
Dn Type= 3
Dn Slope=0.005
Boundary for River Rch & Prof#=BURTON CREEK,Reach-1         , 5
Up Type= 0
Dn Type= 3
Dn Slope=0.005
Boundary for River Rch & Prof#=BURTON CREEK,Reach-1         , 6
Up Type= 0
Dn Type= 3
Dn Slope=0.005
Boundary for River Rch & Prof#=BURTON CREEK,Reach-1         , 7
Up Type= 0
Dn Type= 3
Dn Slope=0.005
DSS Import GetInterval= 0
DSS Import GetPeak= 0
DSS Import FillOption= 0

--- BURTON CREEK.g01 (geometry) ---

Geom Title=Existing Conditions
Program Version=4.10

River Reach=BURTON CREEK    ,Reach-1
Reach XY= 30
      3542504.57     10226115.34      3542903.07     10225504.07
      3543851.22     10225609.94      3544119.43     10225247.24
      3544959.44     10224884.41       3544948.3     10224575.49
      3545238.53     10224523.92      3546578.31     10223371.79
      3547477.62     10223172.14      3548021.02     10222568.84
      3548374.32     10221536.72      3548831.78     10221453.39
      3549657.31     10220409.98      3550823.33     10219753.96
      3551357.91      10220131.4      3551919.39     10219696.85
      3552570.89     10219658.72      3552967.56      10219373.2
      3554062.11     10219311.64      3554289.11     10219627.37
      3554891.95     10219631.75      3555426.94     10219351.97
      3555849.63     10219706.23      3556451.19     10219843.87
      3556985.63     10220424.48      3557422.56     10220640.28
      3557608.51     10220634.23      3557956.86     10220202.15
      3559777.76     10221044.43      3560972.11     10220791.64

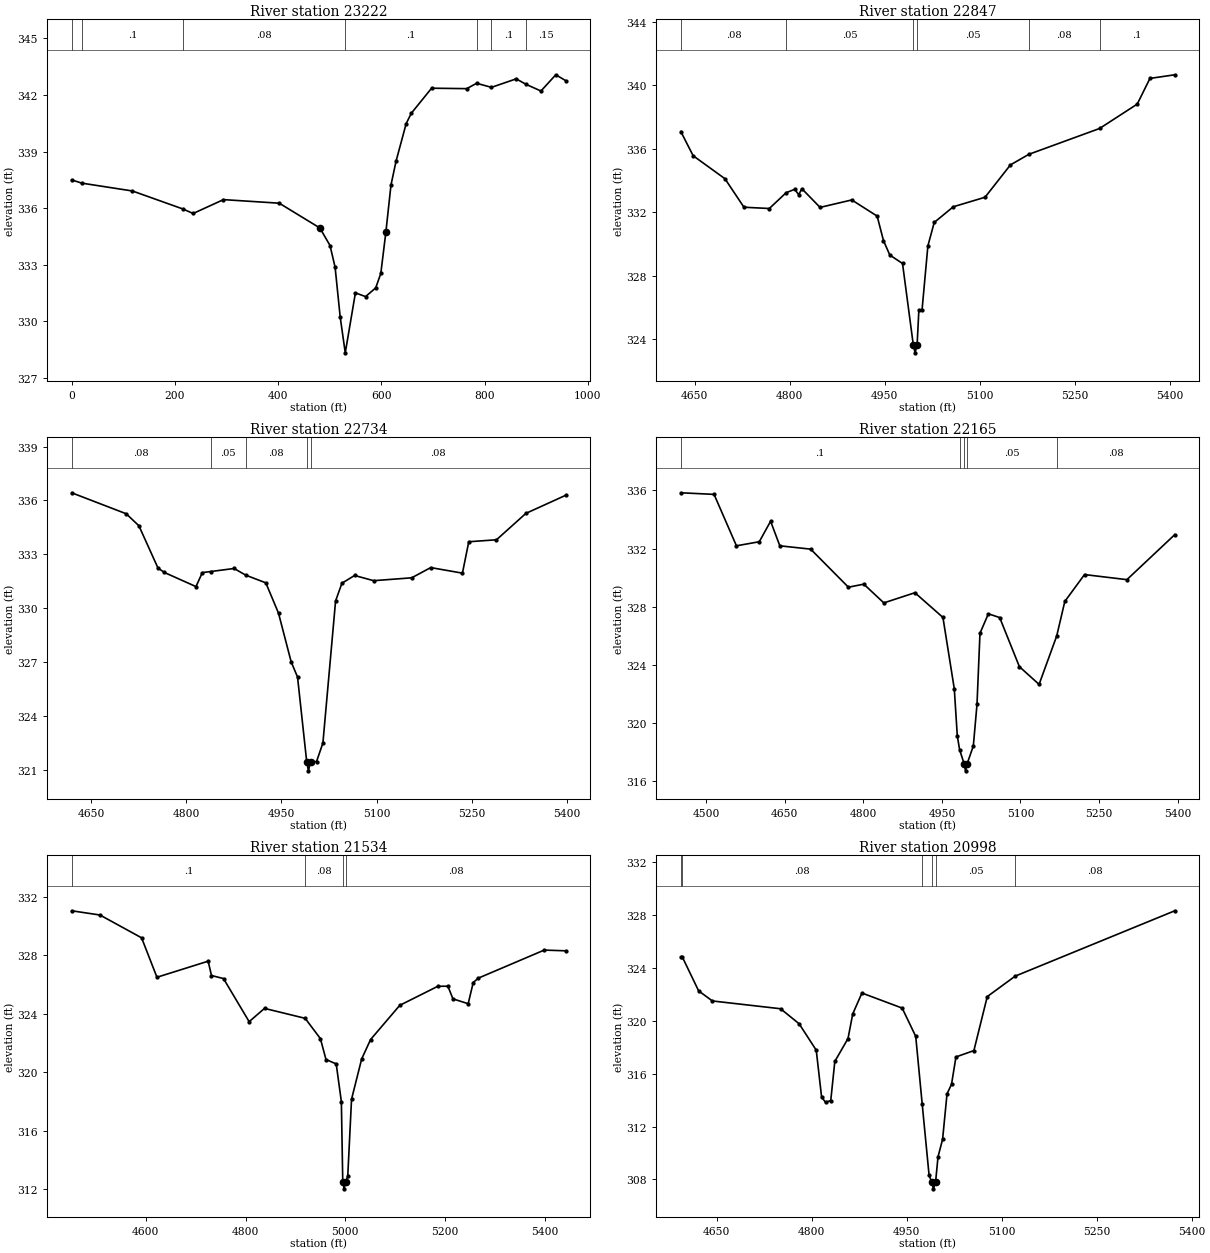
Type RM Length L Ch R = 1 ,23222   ,400,400,400
BEGIN DESCRIPTION:
BURTON CREEK 51.0
END DESCRIPTION:
XS GIS Cut Line= 3
      3542882.09     10226419.43      3542517.15     10225995.56
      3542117.62     10225546.09
#Sta/Elev= 30
       0337.500419.60826337.3279117.6496336.9126215.6908335.9562235.2991335.7192
294.1239336.4542402.1406336.2649480.8477334.9514500.5245334.0211510.3629332.8694
520.2013330.2337530.0397328.3328549.7165331.5126569.3932331.3126589.0701 331.778
598.9084332.5409608.7468334.7392618.5852337.2224628.4236338.4928648.1004 340.487
657.9388341.0304697.2924342.3605765.3981342.3368784.5662342.6207813.3183342.4054
861.2385342.8561880.4066342.5636909.1588342.2113937.9109343.0719 957.079 342.762
#Mann= 7 ,-1 , 0
       0     .08       019.60826      .1       0215.6908     .08       0
530.0397      .1       0784.5662     .07       0813.3183      .1       0
880.4066     .15       0
Bank Sta=480.8477,608.7468
XS Rating Curve= 0 ,0
Exp/Cntr=0.3,0.1

Type RM Length L Ch R = 1 ,22847   ,113,113,113
BEGIN DESCRIPTION:
BURTON CREEK 49.1
END DESCRIPTION:
XS GIS Cut Line= 3
      3543391.44     10225981.18      3543382.73     10225605.18
      3543389.62     10225202.44
#Sta/Elev= 30
  4628.3  337.09  4647.8  335.56  4697.9  334.11  4727.9  332.31  4767.9  332.23
  4794.5  333.23  4807.9  333.44  4814.2   333.1  4819.2  333.48  4847.9   332.3
  4897.9  332.77  4937.9  331.75  4947.9   330.2  4957.9  329.29  4977.9  328.76
  4994.9  323.62  4997.7  323.12  5000.9  323.62  5003.7  325.83  5008.7  325.83
  5017.9  329.87  5027.9  331.35    5058  332.34    5108  332.94    5148  334.98
  5177.1  335.65  5288.6  337.28    5348  338.82    5368  340.44  5407.2  340.67
#Mann= 6 ,-1 , 0
  4628.3     .08       0  4794.5     .05       0  4994.9     .04       0
  5000.9     .05       0  5177.1     .08       0  5288.6      .1       0
Bank Sta=4994.9,5000.9
XS Rating Curve= 0 ,0
Exp/Cntr=0.3,0.1

Type RM Length L Ch R = 1 ,22734   ,569,569,569
BEGIN DESCRIPTION:
BURTON CREEK 49.0
END DESCRIPTION:
XS GIS Cut Line= 3
      3543500.81     10226017.63      3543492.11     10225641.64
        3543499.     10225238.89
#Sta/Elev= 30
  4619.3  336.43  4705.3  335.26  4725.3  334.59  4755.3  332.24  4765.3  331.99
  4815.3   331.2  4825.3  331.98  4838.6  332.04  4875.4  332.21  4893.6  331.84
  4925.4  331.41  4945.4  329.72  4965.4     327  4975.4  326.16  4989.9  321.43
  4992.6  320.93  4995.9  321.43  5005.4  321.45  5015.4  322.48  5035.4   330.4
  5045.4  331.39  5065.4  331.82  5095.4  331.53  5155.4  331.69  5185.4  332.26
  5235.4  331.95  5245.4   333.7  5289.1  333.81  5335.4  335.28  5398.2  336.29
#Mann= 5 ,-1 , 0
  4619.3     .08       0  4838.6     .05       0  4893.6     .08       0
  4989.9     .07       0  4995.9     .08       0
Bank Sta=4989.9,4995.9
XS Rating Curve= 0 ,0
Exp/Cntr=0.3,0.1

Type RM Length L Ch R = 1 ,22165   ,631,631,631
BEGIN DESCRIPTION:
BURTON CREEK 47.0
END DESCRIPTION:
XS GIS Cut Line= 3
      3544209.15     10225960.34      3544054.27     10225581.45
      3543792.49     10225116.61
#Sta/Elev= 30
  4451.7  335.84  4515.2  335.73  4557.9  332.19  4601.5  332.47  4623.1  333.88
  4640.7  332.19  4699.6  331.96  4771.6  329.34    4801  329.55  4839.2  328.26
  4898.5  328.96    4952  327.26  4973.7  322.34  4979.4  319.11  4983.8  318.16
  4992.3   317.2  4995.1   316.7  4998.3   317.2    5010  318.41    5017  321.27
  5022.7  326.17  5038.7  327.51  5060.3  327.25  5097.9  323.87  5135.5  322.65
  5169.1  325.98  5184.6  328.36  5222.2  330.21  5303.1  329.86  5394.5  332.96
#Mann= 5 ,-1 , 0
  4451.7      .1       0  4983.8     .05       0  4992.3     .04       0
  4998.3     .05       0  5169.1     .08       0
Bank Sta=4992.3,4998.3
XS Rating Curve= 0 ,0
Exp/Cntr=0.3,0.1

Type RM Length L Ch R = 1 ,21534   ,536,536,536
BEGIN DESCRIPTION:
BURTON CREEK 46.0
END DESCRIPTION:
XS GIS Cut Line= 3
      3544500.82     10225778.09      3544376.24     10225241.64
       3544297.7     10224809.35
#Sta/Elev= 30
  4451.6  331.05  4508.3  330.76  4591.7   329.2  4622.5   326.5  4725.1   327.6
  4731.8  326.62  4755.9  326.41  4807.3  323.46  4838.1  324.37  4919.5  323.69
  4950.1   322.3  4961.3  320.87  4981.8  320.57  4992.1  317.99  4994.9  312.52
  4997.6  312.02  5000.9  312.52  5004.9  312.88  5012.5  318.15  5032.8  320.91
  5050.7  322.24  5109.2  324.58  5185.3  325.88  5205.6  325.89  5215.8  325.02
  5246.3  324.69  5256.4  326.14  5266.6  326.44  5398.7  328.36  5441.7  328.31
#Mann= 4 ,-1 , 0
  4451.6      .1       0  4919.5     .08       0  4994.9     .07       0
  5000.9     .08       0
Bank Sta=4994.9,5000.9
XS Rating Curve= 0 ,0
Exp/Cntr=0.3,0.1

Type RM Length L Ch R = 1 ,20998   ,789,789,789
BEGIN DESCRIPTION:
BURTON CREEK 45.0
END DESCRIPTION:
XS GIS Cut Line= 3
      3544992.13     10225241.67      3544828.22     10225021.04
      3544475.92     10224659.44
#Sta/Elev= 30
  4593.6  324.83  4596.1  324.83  4621.8  322.27  4643.5  321.51  4751.1  320.92
  4780.4  319.78  4807.4  317.78  4815.8  314.24  4822.1  313.83  4830.3  313.97
  4836.7  316.93  4857.5  318.66    4865  320.53  4879.5  322.11    4943  320.97
  4964.4  318.83  4974.6  313.71  4985.5   308.3  4989.7  307.78  4992.4  307.28
  4995.7  307.78  4999.6  309.71  5006.8  311.03  5013.8  314.47  5020.9   315.2
  5027.9  317.27  5056.2  317.75  5077.3  321.84  5121.4  323.39  5373.3  328.34
#Mann= 6 ,-1 , 0
  4593.6      .1       0  4596.1     .08       0  4974.6     .05       0
  4989.7     .04       0  4995.7     .05       0  5121.4     .08       0
Bank Sta=4989.7,4995.7
XS Rating Curve= 0 ,0
Exp/Cntr=0.3,0.1

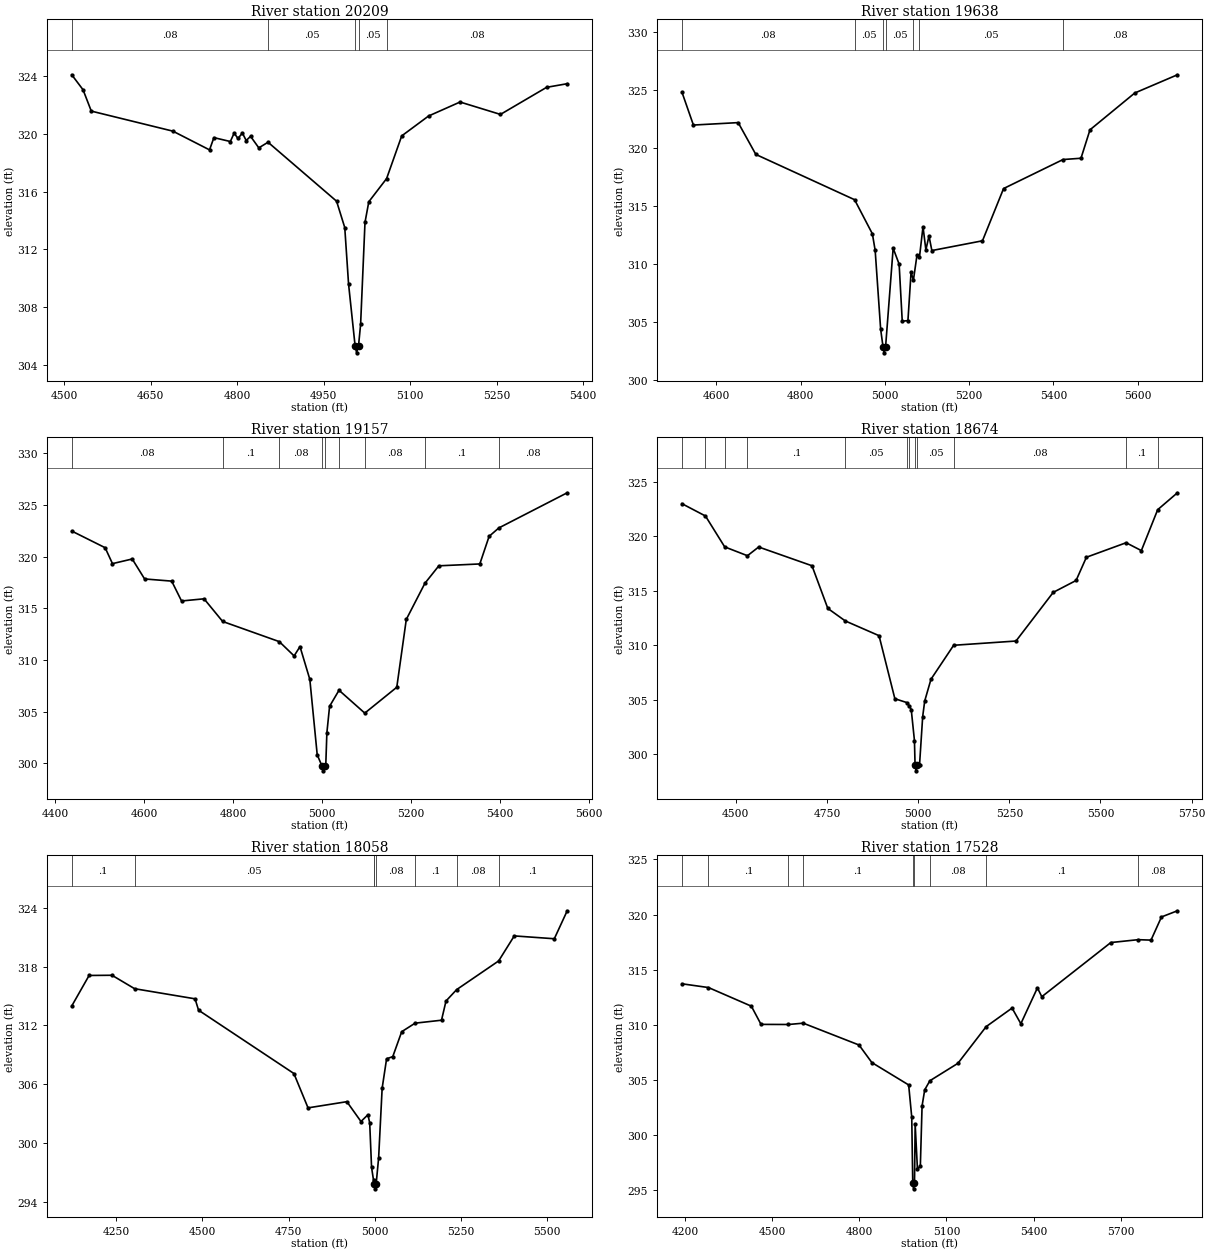
Type RM Length L Ch R = 1 ,20209   ,571,571,571
BEGIN DESCRIPTION:
BURTON CREEK 43.0
END DESCRIPTION:
XS GIS Cut Line= 3
      3545271.65     10224939.51       3544865.4     10224470.76
      3544626.43     10224460.37
#Sta/Elev= 30
  4513.1   324.1  4532.7  323.06    4547  321.58  4688.5  320.19  4752.1  318.89
  4759.7  319.74  4788.2  319.47  4794.8  320.05  4801.5  319.68  4809.1  320.06
  4815.7  319.54  4823.3  319.83  4837.6  319.03  4853.6  319.42  4972.5  315.33
  4986.7   313.5  4993.3  309.58  5004.6  305.31  5007.3  304.81  5010.6  305.31
  5014.2  306.79  5021.8  313.86  5028.4  315.29  5059.3   316.9  5085.5  319.86
  5132.1  321.24  5186.7  322.21  5256.8  321.35  5336.9  323.23  5372.6  323.48
#Mann= 5 ,-1 , 0
  4513.1     .08       0  4853.6     .05       0  5004.6     .04       0
  5010.6     .05       0  5059.3     .08       0
Bank Sta=5004.6,5010.6
XS Rating Curve= 0 ,0
Exp/Cntr=0.3,0.1

Type RM Length L Ch R = 1 ,19638   ,481,481,481
BEGIN DESCRIPTION:
BURTON CREEK 42.0
END DESCRIPTION:
XS GIS Cut Line= 3
       3545698.7     10224653.02      3545385.21     10224298.53
      3544912.26     10223778.03
#Sta/Elev= 30
    4518  324.78  4545.2  321.95  4651.5  322.16  4693.4  319.42  4927.9  315.52
  4970.2  312.58  4976.8  311.15  4989.8  304.37  4995.5  302.83  4998.3  302.33
  5001.5  302.83  5019.5  311.34  5033.7  309.97  5041.1  305.05  5054.6  305.11
    5062  309.27  5067.6  308.59  5076.2  310.77    5082  310.58  5090.4  313.19
  5097.2   311.2  5104.6   312.4  5111.4  311.14  5231.6  311.98  5281.7  316.48
  5422.9  318.98  5465.5  319.09  5486.9  321.54  5593.2  324.71  5694.5  326.28
#Mann= 7 ,-1 , 0
    4518     .08       0  4927.9     .05       0  4995.5     .04       0
  5001.5     .05       0  5067.6     .08       0    5082     .05       0
  5422.9     .08       0
Bank Sta=4995.5,5001.5
XS Rating Curve= 0 ,0
Exp/Cntr=0.3,0.1

Type RM Length L Ch R = 1 ,19157   ,483,483,483
BEGIN DESCRIPTION:
BURTON CREEK 41.0
END DESCRIPTION:
XS GIS Cut Line= 3
        3545980.     10224476.01      3545719.99     10223970.55
      3545401.86     10223528.05
#Sta/Elev= 30
  4437.8  322.47  4512.8  320.86  4529.3  319.32  4573.7  319.77  4601.5  317.84
  4662.4  317.63  4684.5  315.71  4735.1  315.92  4776.9  313.73  4904.2  311.78
  4937.5   310.4  4950.7   311.3  4972.8  308.13  4989.4  300.84  4999.8  299.79
  5002.5  299.29  5005.8  299.79  5008.6  299.79  5011.1  302.96  5017.2  305.53
  5038.4  307.08  5096.3  304.87  5168.2  307.37  5189.6  313.93  5231.4  317.42
  5262.7  319.11  5354.8  319.29  5375.7  321.96  5397.5  322.77  5551.2  326.17
#Mann= 9 ,-1 , 0
  4437.8     .08       0  4776.9      .1       0  4904.2     .08       0
  4999.8     .07       0  5005.8     .08       0  5038.4     .05       0
  5096.3     .08       0  5231.4      .1       0  5397.5     .08       0
Bank Sta=4999.8,5005.8
XS Rating Curve= 0 ,0
Exp/Cntr=0.3,0.1

Type RM Length L Ch R = 1 ,18674   ,616,616,616
BEGIN DESCRIPTION:
BURTON CREEK 40.0
END DESCRIPTION:
XS GIS Cut Line= 3
      3546469.58     10224340.58       3546155.4     10223778.35
      3545849.79     10223132.24
#Sta/Elev= 30
  4352.2  322.99  4416.7  321.86  4469.4  319.03  4531.8  318.22  4562.6  319.02
  4708.8   317.3  4752.2  313.39  4800.2  312.24  4892.7  310.89  4936.1  305.11
  4968.8  304.76  4975.8  304.45    4981  304.12  4989.8  301.28  4991.5     299
  4994.3   298.5  4997.5     299  5003.7  299.02  5012.4  303.48    5018  304.91
  5035.2   306.9  5097.3  310.01  5268.3   310.4  5370.4  314.86  5433.1  315.95
  5461.4  318.08  5570.3  319.41  5612.1  318.69  5656.9  322.44    5711  323.99
#Mann= 12 ,-1 , 0
  4352.2     .08       0  4416.7     .05       0  4469.4     .08       0
  4531.8      .1       0  4800.2     .05       0  4968.8     .08       0
  4975.8     .05       0  4991.5     .04       0  4997.5     .05       0
  5097.3     .08       0  5570.3      .1       0  5656.9     .08       0
Bank Sta=4991.5,4997.5
XS Rating Curve= 0 ,0
Exp/Cntr=0.3,0.1

Type RM Length L Ch R = 1 ,18058   ,530,530,530
BEGIN DESCRIPTION:
BURTON CREEK 38.0
END DESCRIPTION:
XS GIS Cut Line= 3
      3546782.07      10224220.8      3546568.52      10223246.8
      3546339.37     10222871.82
#Sta/Elev= 30
  4121.4  313.98  4171.7  317.09  4238.1  317.11  4303.7  315.74  4478.9  314.71
  4489.1  313.55  4765.5   307.1  4806.5   303.6  4919.1  304.23    4960  302.21
  4980.2   302.9  4985.3  302.07  4990.7  297.54  4996.5   296.2    4998  295.85
  5000.7  295.35    5004  295.85  5011.2  298.51  5021.4   305.6  5034.3   308.6
  5052.2  308.82  5078.1  311.36    5117  312.23  5193.5  312.53  5206.6  314.49
  5237.5  315.65  5359.2  318.57  5404.5  321.12  5520.6  320.83    5558  323.68
#Mann= 8 ,-1 , 0
  4121.4      .1       0  4303.7     .05       0  4996.5     .08       0
    4998     .07       0    5004     .08       0    5117      .1       0
  5237.5     .08       0  5359.2      .1       0
Bank Sta=4998,5004
XS Rating Curve= 0 ,0
Exp/Cntr=0.3,0.1

Type RM Length L Ch R = 1 ,17528   ,833,833,833
BEGIN DESCRIPTION:
BURTON CREEK 37.0
END DESCRIPTION:
XS GIS Cut Line= 3
      3547354.99     10224090.57      3547092.11     10223319.51
      3546600.37     10222575.82
#Sta/Elev= 30
  4189.4  313.72  4280.8  313.38  4428.4  311.69  4461.7  310.04  4556.1  310.03
    4607  310.15  4799.2  308.17  4843.3  306.58  4970.1  304.55  4980.7  301.63
  4984.2  295.63    4987  295.13  4990.2  295.63  4992.5  300.98  5000.3  296.94
  5010.3  297.18  5016.3  302.65  5025.4  304.11  5043.2  304.93  5139.7  306.51
  5237.1  309.84  5326.2  311.52  5356.4   310.1  5413.5  313.35  5428.6  312.55
  5666.3  317.46  5760.5  317.72  5804.7  317.68  5840.7  319.78  5895.6  320.34
#Mann= 9 ,-1 , 0
  4189.4     .08       0  4280.8      .1       0  4556.1     .08       0
    4607      .1       0  4984.2     .07       0  4990.2      .1       0
  5043.2     .08       0  5237.1      .1       0  5760.5     .08       0
Bank Sta=4984.2,4990.2
XS Rating Curve= 0 ,0
Exp/Cntr=0.3,0.1

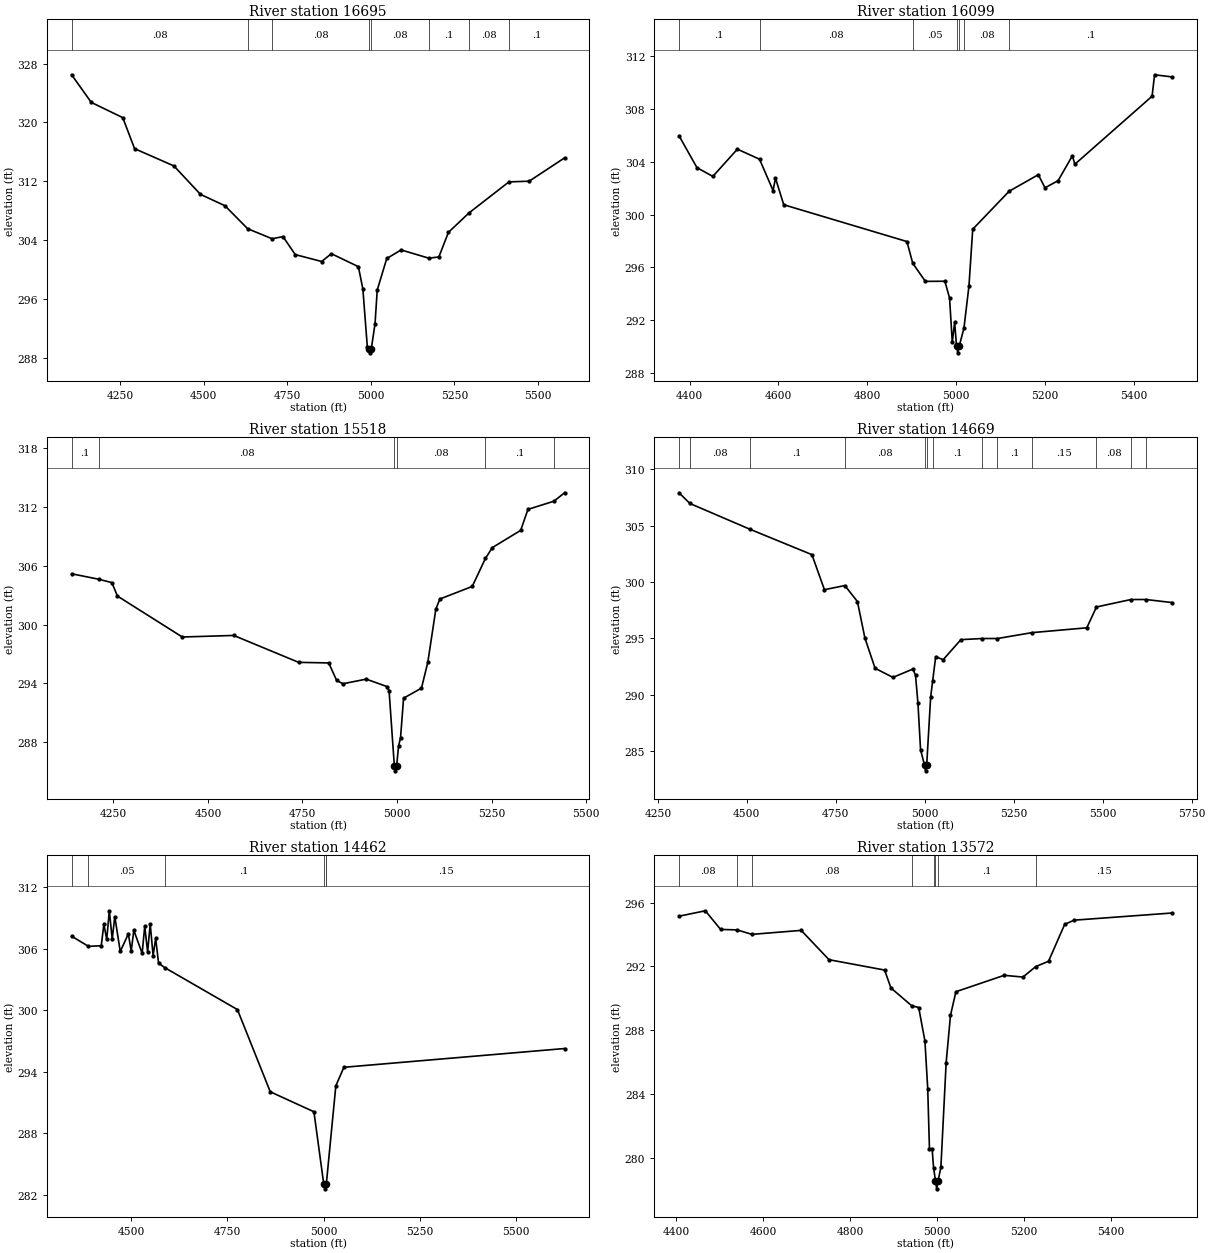
Type RM Length L Ch R = 1 ,16695   ,596,596,596
BEGIN DESCRIPTION:
BURTON CREEK 35.0
END DESCRIPTION:
XS GIS Cut Line= 3
      3548242.09     10223641.61      3547773.38     10222887.22
      3547392.09     10222441.63
#Sta/Elev= 30
  4104.9  326.47  4163.7  322.72  4257.9  320.65  4293.2  316.44    4411  314.09
  4490.4  310.23  4563.6  308.69  4631.5  305.57  4704.7  304.21  4737.2   304.5
  4773.8  302.06  4852.9  301.12  4881.9  302.18  4962.7  300.42  4976.1   297.4
  4989.5  289.51  4995.2  289.22    4998  288.72  5001.2  289.22  5012.5  292.67
  5019.1  297.25  5047.6  301.53  5090.5  302.69  5173.6  301.57  5203.5  301.74
  5232.1  305.08  5293.5  307.71  5413.1  311.93  5473.6  312.02  5579.5  315.19
#Mann= 8 ,-1 , 0
  4104.9     .08       0  4631.5      .1       0  4704.7     .08       0
  4995.2     .07       0  5001.2     .08       0  5173.6      .1       0
  5293.5     .08       0  5413.1      .1       0
Bank Sta=4995.2,5001.2
XS Rating Curve= 0 ,0
Exp/Cntr=0.3,0.1

Type RM Length L Ch R = 1 ,16099   ,581,581,581
BEGIN DESCRIPTION:
BURTON CREEK 33.0
END DESCRIPTION:
XS GIS Cut Line= 3
      3548683.14      10222611.4      3548092.11     10222391.64
      3547662.26     10222179.08
#Sta/Elev= 30
    4376  305.95  4416.4  303.54  4452.1  302.88  4507.4  304.94  4557.3  304.18
  4587.8  301.81  4593.2  302.75  4611.8  300.74  4889.2  297.96  4902.3  296.32
  4930.7  294.95  4974.6  294.96  4985.2   293.7  4991.4  290.34  4996.7  291.88
  5000.9  290.05  5003.7  289.55  5006.9  290.05  5017.6  291.41  5028.9   294.6
  5037.4  298.89  5119.4  301.76  5185.1  303.01  5200.1  302.02  5229.7  302.56
  5261.8  304.44  5267.4   303.8  5441.3  308.94  5446.9  310.56  5486.1   310.4
#Mann= 7 ,-1 , 0
    4376      .1       0  4557.3     .08       0  4902.3     .05       0
  5000.9     .04       0  5006.9     .05       0  5017.6     .08       0
  5119.4      .1       0
Bank Sta=5000.9,5006.9
XS Rating Curve= 0 ,0
Exp/Cntr=0.3,0.1

Type RM Length L Ch R = 1 ,15518   ,849,849,849
BEGIN DESCRIPTION:
BURTON CREEK 32.0
END DESCRIPTION:
XS GIS Cut Line= 3
      3548943.56     10222298.91      3548370.61     10221882.22
      3547813.32     10221673.89
#Sta/Elev= 30
  4139.6  305.17  4211.8  304.61    4246  304.27  4260.7   302.9  4432.2  298.73
  4568.2  298.89  4739.8  296.15  4819.4  296.09  4840.3  294.31  4857.1  293.97
  4918.5  294.44  4973.7  293.68    4979  293.24  4992.9   285.6  4995.7   285.1
  4998.9   285.6    5004  287.61  5009.3  288.48  5017.3   292.5  5064.6  293.52
  5081.3  296.14  5102.7  301.58  5113.3   302.6  5198.8  303.88  5233.7  306.73
  5252.1  307.84  5326.9  309.59  5346.2  311.73  5414.7  312.56    5443  313.42
#Mann= 6 ,-1 , 0
  4139.6      .1       0  4211.8     .08       0  4992.9     .07       0
  4998.9     .08       0  5233.7      .1       0  5414.7     .08       0
Bank Sta=4992.9,4998.9
XS Rating Curve= 0 ,0
Exp/Cntr=0.3,0.1

Type RM Length L Ch R = 1 ,14669   ,207,207,207
BEGIN DESCRIPTION:
BURTON CREEK 30.0
END DESCRIPTION:
XS GIS Cut Line= 3
      3549367.13     10221891.66      3548908.54     10221521.05
      3548366.85     10220938.37
#Sta/Elev= 30
  4309.5  307.92    4340  306.97  4507.6   304.7  4682.9  302.43  4718.1  299.32
  4775.5  299.69  4810.8  298.27  4831.6  295.06  4860.4  292.35  4910.5  291.54
  4966.7  292.28    4974  291.74  4980.9  289.23  4988.2  285.12  4999.4  283.75
  5002.1  283.25  5005.4  283.75  5016.6  289.81  5022.3  291.25  5030.7  293.38
  5051.7  293.11  5101.6  294.89  5161.6  294.99  5204.4  294.99  5300.9  295.51
  5455.3  295.94  5482.6  297.79  5579.4  298.45  5621.7  298.45  5694.7  298.18
#Mann= 13 ,-1 , 0
  4309.5      .1       0    4340     .08       0  4507.6      .1       0
  4775.5     .08       0  4999.4     .07       0  5005.4     .08       0
  5022.3      .1       0  5161.6     .15       0  5204.4      .1       0
  5300.9     .15       0  5482.6     .08       0  5579.4     .15       0
  5621.7      .1       0
Bank Sta=4999.4,5005.4
XS Rating Curve= 0 ,0
Exp/Cntr=0.3,0.1

Type RM Length L Ch R = 1 ,14462   ,890,890,890
BEGIN DESCRIPTION:
BURTON CREEK 28.0
END DESCRIPTION:
XS GIS Cut Line= 3
      3549481.15     10221760.98       3549061.9       10221386.
      3548587.92     10220846.92
#Sta/Elev= 30
  4345.5  307.22  4389.2  306.23  4422.5  306.29  4429.2  308.39  4436.7  306.91
  4443.4   309.7  4450.9  306.94  4457.6  309.13  4471.8  305.73  4492.8  307.44
  4500.3  305.77    4507  307.79  4528.7  305.55  4535.4   308.2  4542.9  305.67
  4549.6  308.41  4557.1  305.33  4563.8     307  4571.3  304.59  4587.5  304.15
  4776.1  300.06  4861.4  292.04  4974.8  290.09  5000.2  283.07    5003  282.57
  5006.2  283.07  5007.3  283.16  5031.7  292.62  5052.6  294.43  5625.8  296.26
#Mann= 6 ,-1 , 0
  4345.5      .1       0  4389.2     .05       0  4587.5      .1       0
  5000.2     .07       0  5006.2      .1       0  5007.3     .15       0
Bank Sta=5000.2,5006.2
XS Rating Curve= 0 ,0
Exp/Cntr=0.3,0.1

Type RM Length L Ch R = 1 ,13572   ,499,499,499
BEGIN DESCRIPTION:
BURTON CREEK 27.0
END DESCRIPTION:
XS GIS Cut Line= 3
      3549943.54     10220955.15      3549492.11     10220591.64
      3549011.24     10220314.51
#Sta/Elev= 30
    4406  295.15  4466.5  295.49  4501.7  294.32  4539.7  294.29  4573.7  294.01
  4687.2  294.26  4751.2  292.42  4879.2  291.77  4893.6  290.65  4941.5  289.53
  4957.6  289.42    4972  287.31  4978.4  284.33  4982.4  280.56  4988.5  280.56
  4991.9  279.36  4996.3  278.54    4999  278.04  5002.3  278.54  5008.7  279.39
  5020.8  285.95  5030.8  288.93  5043.3  290.41  5154.4  291.44  5197.5  291.33
  5227.2  291.99  5256.4  292.32  5293.7  294.64  5315.3   294.9  5540.6  295.35
#Mann= 8 ,-1 , 0
    4406     .08       0  4539.7     .05       0  4573.7     .08       0
  4941.5     .05       0  4991.9      .1       0  4996.3     .07       0
  5002.3      .1       0  5227.2     .15       0
Bank Sta=4996.3,5002.3
XS Rating Curve= 0 ,0
Exp/Cntr=0.3,0.1

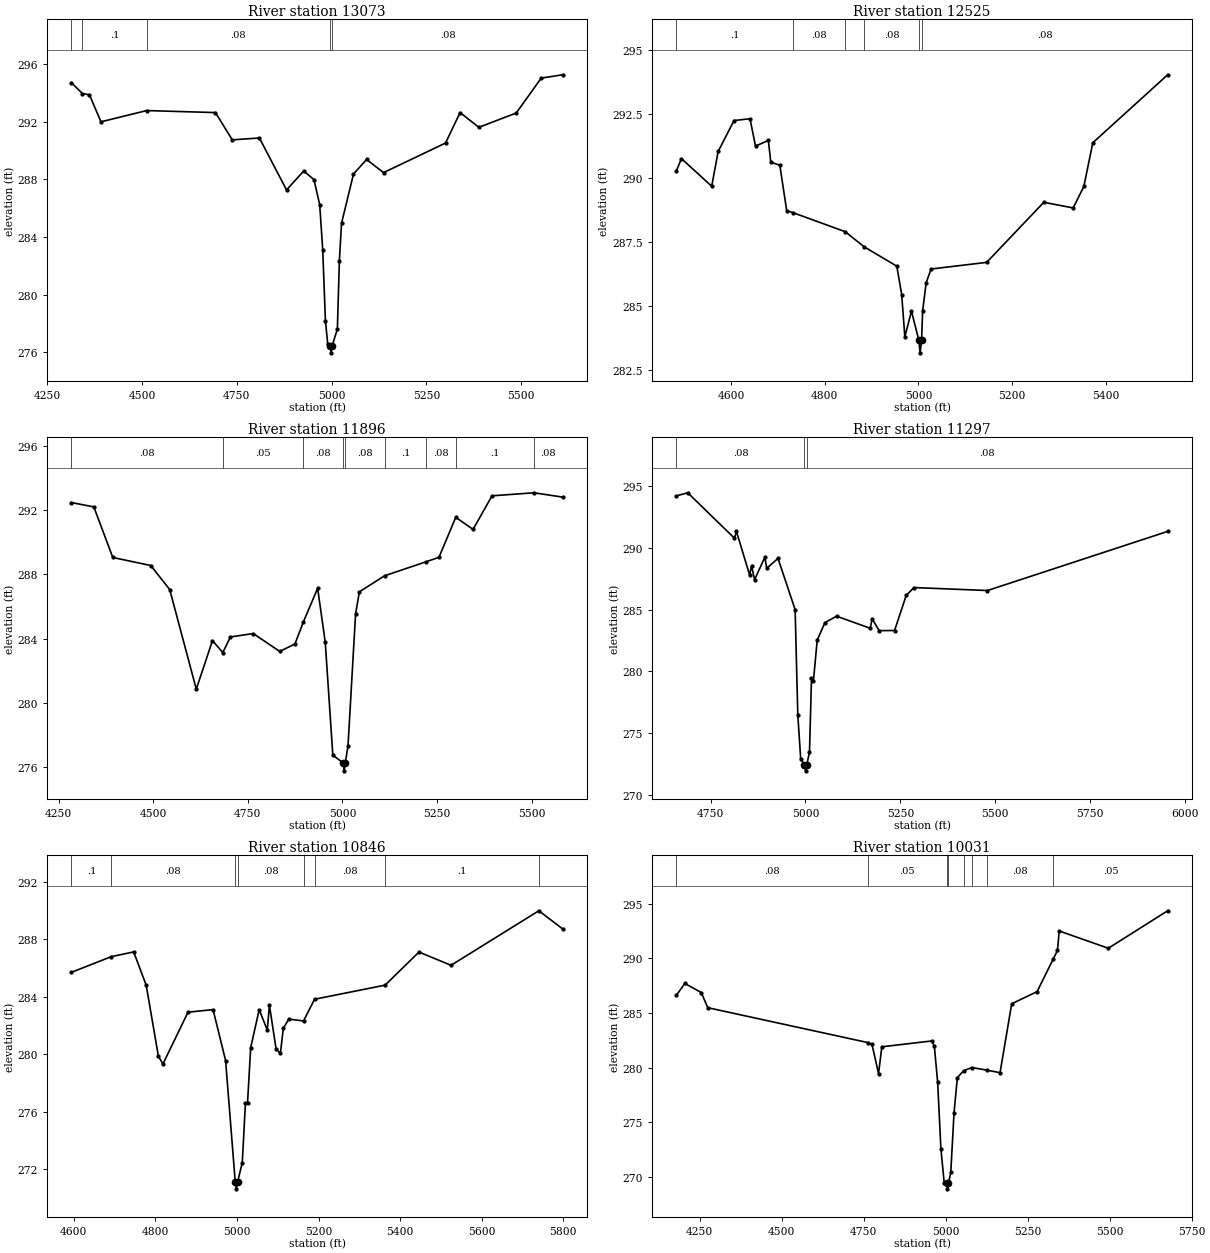
Type RM Length L Ch R = 1 ,13073   ,548,548,548
BEGIN DESCRIPTION:
BURTON CREEK 26.0
END DESCRIPTION:
XS GIS Cut Line= 3
      3550222.67     10220827.21      3549842.11     10220241.64
      3549561.54     10219714.87
#Sta/Elev= 30
  4313.9  294.69    4343  293.94  4361.5  293.85  4391.8  291.98  4512.4  292.76
  4693.7  292.62    4738  290.73  4809.5  290.86  4881.1  287.26  4926.3  288.57
  4953.3  287.98  4968.5  286.24  4976.5  283.12  4983.6  278.19  4989.6  276.61
  4995.7  276.47  4998.5  275.97  5001.7  276.47  5015.1  277.63  5020.4  282.35
  5026.1  284.95  5057.6  288.36    5092  289.37  5136.9  288.46  5300.3  290.51
  5338.6  292.62  5388.2   291.6  5486.7  292.59  5552.6  295.01  5609.1  295.24
#Mann= 5 ,-1 , 0
  4313.9     .08       0    4343      .1       0  4512.4     .08       0
  4995.7     .07       0  5001.7     .08       0
Bank Sta=4995.7,5001.7
XS Rating Curve= 0 ,0
Exp/Cntr=0.3,0.1

Type RM Length L Ch R = 1 ,12525   ,629,629,629
BEGIN DESCRIPTION:
BURTON CREEK 24.0
END DESCRIPTION:
XS GIS Cut Line= 3
      3550500.81     10220554.08      3550380.34     10220127.28
      3550203.93     10219548.86
#Sta/Elev= 30
  4483.6  290.28  4494.3  290.76  4558.9  289.68  4572.7  291.04  4606.6  292.25
  4640.6  292.32  4652.4  291.25  4679.8  291.47    4685  290.62  4704.3   290.5
    4719  288.72  4731.6  288.65  4843.8   287.9  4884.1  287.31  4953.9  286.55
  4964.3  285.44    4971  283.79  4985.2  284.79  5000.8  283.66  5003.6  283.16
  5006.8  283.66    5009  284.81  5016.6  285.91  5027.1  286.44  5145.6   286.7
  5267.5  289.05  5330.2  288.83    5353  289.67  5372.1  291.38  5531.8  294.04
#Mann= 6 ,-1 , 0
  4483.6      .1       0  4731.6     .08       0  4843.8     .05       0
  4884.1     .08       0  5000.8     .07       0  5006.8     .08       0
Bank Sta=5000.8,5006.8
XS Rating Curve= 0 ,0
Exp/Cntr=0.3,0.1

Type RM Length L Ch R = 1 ,11896   ,599,599,599
BEGIN DESCRIPTION:
BURTON CREEK 23.0
END DESCRIPTION:
XS GIS Cut Line= 3
       3550933.1     10220470.72      3550896.53     10219951.18
      3550855.06     10219175.31
#Sta/Elev= 30
    4284  292.48  4343.2  292.21  4393.3  289.06  4493.6  288.56  4543.7  287.06
  4613.9  280.86  4656.6  283.88    4684  283.14  4704.1  284.11  4764.3  284.32
  4834.4  283.21  4874.5  283.67  4896.9  285.05  4934.5  287.14  4954.6  283.78
  4974.6  276.75  5001.6  276.27  5004.4  275.77  5007.6  276.27  5014.7  277.32
  5034.7  285.53  5044.7  286.92  5111.4  287.92  5221.9   288.8    5255  289.07
  5299.4  291.56  5345.1  290.81  5395.2   292.9  5505.8  293.09  5581.8  292.82
#Mann= 9 ,-1 , 0
    4284     .08       0    4684     .05       0  4896.9     .08       0
  5001.6     .07       0  5007.6     .08       0  5111.4      .1       0
  5221.9     .08       0  5299.4      .1       0  5505.8     .08       0
Bank Sta=5001.6,5007.6
XS Rating Curve= 0 ,0
Exp/Cntr=0.3,0.1

Type RM Length L Ch R = 1 ,11297   ,451,451,451
BEGIN DESCRIPTION:
BURTON CREEK 22.0
END DESCRIPTION:
XS GIS Cut Line= 3
      3551427.91     10220460.37      3551342.11     10220141.64
      3551157.28     10219195.81
#Sta/Elev= 30
  4660.1  294.22  4689.9  294.47    4813  290.79  4818.2  291.34  4852.9  287.81
  4858.1  288.56  4865.9  287.42  4892.9  289.24  4898.1  288.36  4927.7  289.15
  4972.8     285  4979.8  276.48  4987.6  272.86  4997.4  272.44  5000.1  271.94
  5003.4  272.44  5010.6  273.44  5015.9  279.44    5021  279.24  5030.9  282.53
  5051.3  283.95  5081.9  284.47  5170.6  283.49  5175.7  284.26    5194   283.3
  5234.7  283.31  5265.3  286.15  5285.7  286.79  5479.3  286.55  5953.9  291.34
#Mann= 3 ,-1 , 0
  4660.1     .08       0  4997.4     .07       0  5003.4     .08       0
Bank Sta=4997.4,5003.4
XS Rating Curve= 0 ,0
Exp/Cntr=0.3,0.1

Type RM Length L Ch R = 1 ,10846   ,815,815,815
BEGIN DESCRIPTION:
BURTON CREEK 21.0
END DESCRIPTION:
XS GIS Cut Line= 3
      3551833.39     10220360.77      3551742.11     10219941.64
      3551532.35     10219195.73
#Sta/Elev= 30
  4594.5   285.7  4692.1  286.79  4747.1  287.12  4777.8   284.8  4807.7  279.86
  4818.8  279.33  4880.2  282.93  4941.6  283.11  4972.3  279.57  4995.9  271.15
  4998.7  270.65  5001.9  271.15  5013.2  272.47  5020.9  276.59    5026  276.59
  5033.8  280.46  5054.6   283.1  5074.5  281.69  5079.7  283.42  5096.2  280.34
  5106.6  280.08  5113.8  281.81  5127.3  282.45  5163.3  282.32  5190.3  283.83
  5363.1  284.81  5446.2  287.11  5524.7  286.19  5739.9  289.98  5798.3  288.72
#Mann= 8 ,-1 , 0
  4594.5      .1       0  4692.1     .08       0  4995.9     .07       0
  5001.9     .08       0  5163.3     .05       0  5190.3     .08       0
  5363.1      .1       0  5739.9     .08       0
Bank Sta=4995.9,5001.9
XS Rating Curve= 0 ,0
Exp/Cntr=0.3,0.1

Type RM Length L Ch R = 1 ,10031   ,636,636,636
BEGIN DESCRIPTION:
BURTON CREEK 19.0
END DESCRIPTION:
XS GIS Cut Line= 3
       3552365.4     10220507.18      3552407.88     10219466.56
      3552257.16      10219036.5
#Sta/Elev= 30
  4179.6  286.61  4205.2   287.7  4255.2  286.87  4275.2  285.48  4762.5  282.29
  4775.6  282.13  4795.7  279.45  4805.7   281.9  4958.9  282.44  4965.8  281.94
  4975.8  278.67  4985.8  272.54  4995.8  269.45  5002.8   269.4  5005.6   268.9
  5008.8   269.4  5015.8  270.41  5025.8  275.87  5035.9  279.08  5055.3  279.72
  5080.6     280  5126.5  279.76    5166  279.53  5201.5  285.84  5278.9  286.95
  5328.3  289.95    5341  290.72  5346.3   292.5    5496  290.92  5676.8  294.35
#Mann= 8 ,-1 , 0
  4179.6     .08       0  4762.5     .05       0  5002.8     .04       0
  5008.8     .05       0  5055.3     .08       0  5080.6     .05       0
  5126.5     .08       0  5328.3     .05       0
Bank Sta=5002.8,5008.8
XS Rating Curve= 0 ,0
Exp/Cntr=0.3,0.1

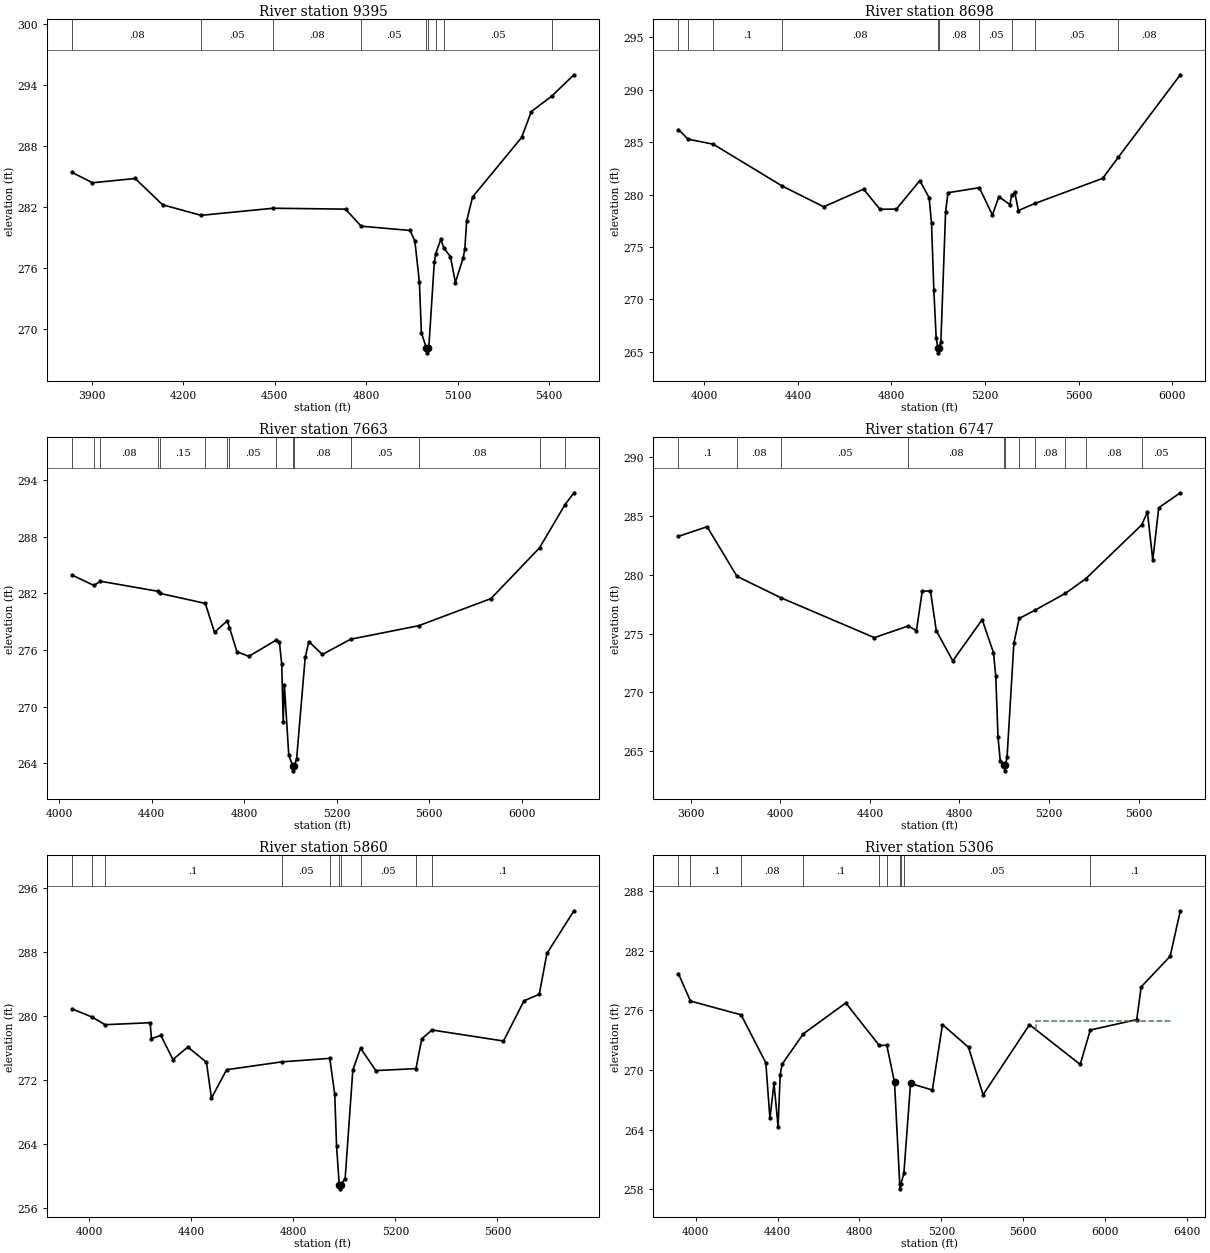
Type RM Length L Ch R = 1 ,9395    ,697,697,697
BEGIN DESCRIPTION:
BURTON CREEK 18.0
END DESCRIPTION:
XS GIS Cut Line= 3
      3553021.65     10220538.51      3552985.19     10219543.67
      3552766.76     10218929.99
#Sta/Elev= 30
  3834.5  285.41  3901.4  284.39  4041.5  284.81  4131.6  282.22    4258  281.18
  4494.8  281.88    4732  281.79  4783.1  280.11  4943.6  279.69  4959.5  278.65
  4974.4  274.57  4980.8  269.61    4997  268.13  4999.7  267.63    5003  268.13
  5005.3  268.19  5023.2  276.56  5027.9  277.41  5044.4  278.81  5054.5  277.97
  5076.3   277.1  5092.4  274.56    5118  276.99  5123.3  277.84  5129.4  280.62
  5148.8  282.99  5309.8  288.85  5341.7  291.41  5408.8  292.93  5481.4  295.03
#Mann= 9 ,-1 , 0
  3834.5     .08       0    4258     .05       0  4494.8     .08       0
  4783.1     .05       0    4997     .04       0    5003     .05       0
  5027.9     .08       0  5054.5     .05       0  5408.8     .08       0
Bank Sta=4997,5003
XS Rating Curve= 0 ,0
Exp/Cntr=0.3,0.1

Type RM Length L Ch R = 1 ,8698    ,1035,1035,1035
BEGIN DESCRIPTION:
BURTON CREEK 16.0
END DESCRIPTION:
XS GIS Cut Line= 3
      3553642.11     10220491.69      3553584.15      10219121.8
      3552942.13     10218691.66
#Sta/Elev= 30
    3890  286.21  3930.7  285.29  4038.4  284.81  4333.9  280.81  4510.6  278.84
  4680.8  280.52  4750.8   278.6  4820.9  278.62    4921  281.33    4961   279.7
    4971  277.25    4981  270.86    4991  266.31    4998  265.41  5000.8  264.91
    5004  265.41    5011  265.97  5031.1  278.32  5041.1  280.18  5175.1  280.66
  5231.2  278.06  5258.7   279.8    5306  279.05  5313.7     280    5327  280.21
    5342  278.48    5413  279.16  5702.2  281.55  5769.1  283.57  6033.9  291.43
#Mann= 10 ,-1 , 0
    3890      .1       0  3930.7     .08       0  4038.4      .1       0
  4333.9     .08       0    4998     .07       0    5004     .08       0
  5175.1     .05       0  5313.7     .08       0    5413     .05       0
  5769.1     .08       0
Bank Sta=4998,5004
XS Rating Curve= 0 ,0
Exp/Cntr=0.3,0.1

Type RM Length L Ch R = 1 ,7663    ,916,916,916
BEGIN DESCRIPTION:
BURTON CREEK 14.0
END DESCRIPTION:
XS GIS Cut Line= 3
      3554131.01     10220512.47      3554401.86     10219845.76
      3554664.47     10218418.64
#Sta/Elev= 30
  4055.6  283.92  4150.3  282.82  4178.1  283.27  4425.2  282.21  4436.3  281.98
  4631.9  280.92  4671.7  277.86  4726.8  279.08  4736.3  278.37  4768.9   275.8
  4820.1  275.32  4936.6  277.01  4952.3  276.86  4962.4  274.51  4968.8  268.41
  4973.8  272.32  4992.9  264.86  5010.3   263.7    5013   263.2  5016.3   263.7
  5026.9  264.48  5064.1  275.24  5079.9  276.88  5138.1  275.52  5260.6  277.13
  5554.8  278.56  5867.4  281.43  6077.5   286.8  6186.9  291.34  6226.3  292.63
#Mann= 15 ,-1 , 0
  4055.6     .08       0  4150.3      .1       0  4178.1     .08       0
  4425.2      .1       0  4436.3     .15       0  4631.9      .1       0
  4726.8     .08       0  4736.3     .05       0  4936.6     .08       0
  5010.3     .07       0  5016.3     .08       0  5260.6     .05       0
  5554.8     .08       0  6077.5     .05       0  6186.9     .08       0
Bank Sta=5010.3,5016.3
XS Rating Curve= 0 ,0
Exp/Cntr=0.3,0.1

Type RM Length L Ch R = 1 ,6747    ,887,887,887
BEGIN DESCRIPTION:
BURTON CREEK 12.0
END DESCRIPTION:
XS GIS Cut Line= 3
      3554834.13     10220772.88       3555218.1     10219646.57
      3555375.78     10218606.42
#Sta/Elev= 30
  3544.8  283.28  3672.8   284.1    3806  279.88    4004  278.04  4419.8  274.66
  4571.1  275.65  4607.8  275.26  4633.9  278.62  4670.5  278.63  4696.6  275.25
  4770.1  272.68  4901.6  276.19  4952.1  273.38  4962.3  271.37  4972.4  266.16
  4982.5  264.16  4999.7  263.82  5002.5  263.32  5005.7  263.82  5012.8  264.49
  5043.2  274.19  5066.9  276.29    5136  276.98  5273.7  278.43  5364.2  279.67
  5614.3  284.26  5639.9  285.35  5663.7  281.27  5690.5  285.72  5786.8  286.99
#Mann= 11 ,-1 , 0
  3544.8      .1       0    3806     .08       0    4004     .05       0
  4571.1     .08       0  4999.7     .07       0  5005.7     .08       0
  5066.9     .05       0    5136     .08       0  5273.7     .05       0
  5364.2     .08       0  5614.3     .05       0
Bank Sta=4999.7,5005.7
XS Rating Curve= 0 ,0
Exp/Cntr=0.3,0.1

Type RM Length L Ch R = 1 ,5860    ,554,554,554
BEGIN DESCRIPTION:
BURTON CREEK 10.0
END DESCRIPTION:
XS GIS Cut Line= 3
      3555745.61     10220772.83      3555992.11     10219741.64
      3556032.04     10218835.96
#Sta/Elev= 30
    3933  280.94  4012.5   279.9    4062  278.96    4239  279.21  4244.2  277.22
  4281.1  277.62  4328.3   274.6  4386.6  276.17  4459.7  274.26  4479.2  269.77
  4538.7  273.33  4754.2  274.31    4943  274.75  4962.4  270.27  4969.6  263.77
    4980  258.93  4982.7  258.43    4986  258.93  5003.2  259.72  5033.3  273.29
  5063.6  276.02  5123.4  273.22  5280.8  273.47  5303.5  277.19  5343.4   278.3
  5623.8  276.92  5703.9  281.94    5764  282.77    5794  287.87  5899.8  293.21
#Mann= 10 ,-1 , 0
    3933      .1       0  4012.5     .08       0    4062      .1       0
  4754.2     .05       0    4943     .08       0    4980     .07       0
    4986     .08       0  5063.6     .05       0  5280.8     .08       0
  5343.4      .1       0
Bank Sta=4980,4986
XS Rating Curve= 0 ,0
Exp/Cntr=0.3,0.1

Type RM Length L Ch R = 1 ,5306    ,1291,1291,1291
BEGIN DESCRIPTION:
BURTON CREEK 9.0
END DESCRIPTION:
XS GIS Cut Line= 3
      3556287.27      10220897.8      3556328.94     10220048.88
      3557532.05      10218991.6
#Sta/Elev= 30
  3915.7   279.7  3974.2  276.95  4221.7  275.56  4342.4  270.72  4362.4  265.12
  4382.4  268.65  4402.4  264.25  4412.5  269.54  4422.5   270.6  4525.2  273.64
    4733  276.76  4896.8  272.47  4933.5  272.49  4971.1  268.76  4996.5  258.52
  4999.3  258.02  5002.5  258.52  5016.8  259.58  5049.4  268.64  5155.9  267.98
  5205.4  274.58  5332.6  272.29  5403.7   267.5  5630.5  274.57  5878.2  270.56
  5927.5  274.03  6154.4  275.08  6176.1  278.38  6317.5  281.46  6367.3  286.05
#Mann= 10 ,-1 , 0
  3915.7     .08       0  3974.2      .1       0  4221.7     .08       0
  4525.2      .1       0  4896.8     .05       0  4933.5     .08       0
  4996.5     .07       0  5002.5     .08       0  5016.8     .05       0
  5927.5      .1       0
#XS Ineff= 1 ,-1
 5663.07 6327.84  274.97
Permanent Ineff=
       F
Bank Sta=4971.1,5049.4
XS Rating Curve= 0 ,0
Exp/Cntr=0.3,0.1