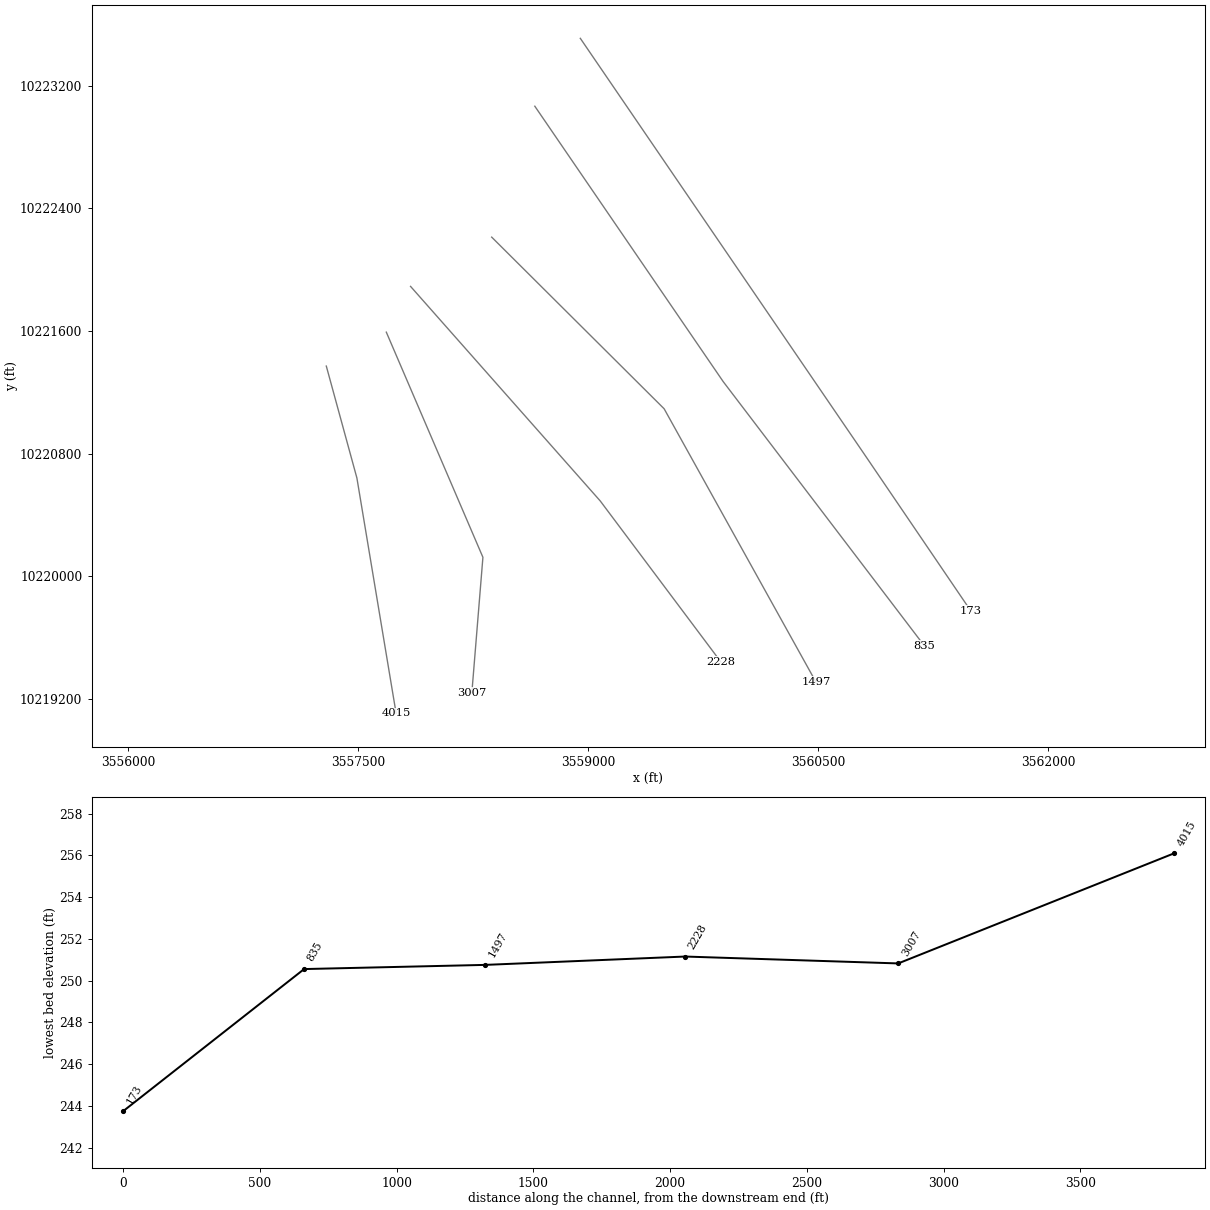
HEC-RAS study BURTON CREEK.prj: BURTON CREEK Base Level Engineering

--- BURTON CREEK.g01 (geometry) --- (continued)

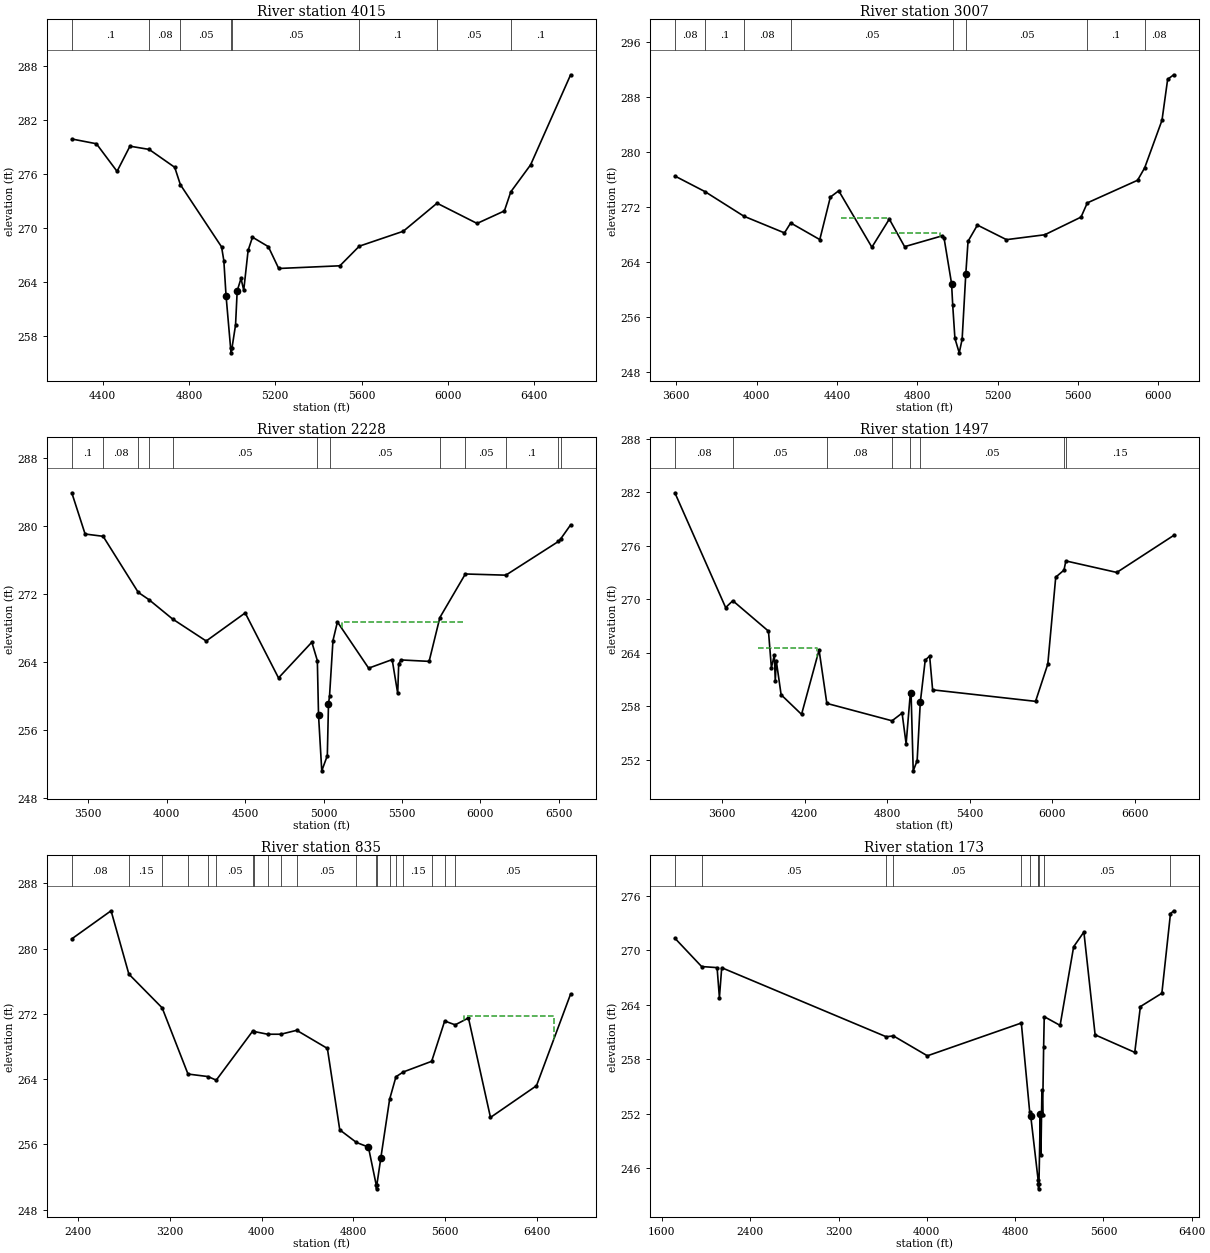
Type RM Length L Ch R = 1 ,4015    ,1008,1008,1008
BEGIN DESCRIPTION:
BURTON CREEK 7.0
END DESCRIPTION:
XS GIS Cut Line= 3
      3557292.49     10221371.77      3557492.11     10220641.64
      3557748.02     10219106.15
#Sta/Elev= 30
  4256.3  279.87  4370.5  279.34  4466.2  276.27    4526  279.07    4615  278.71
  4733.7  276.72  4759.9  274.79    4951  267.87  4961.5  266.34  4971.8  262.42
    4993  256.59  4995.7  256.09    4999  256.59  5015.8  259.18  5023.4  262.98
  5041.1  264.36  5053.8  263.05  5074.1  267.48  5094.3  268.95  5167.8   267.9
    5216  265.47  5499.8  265.77  5589.7  267.95  5793.8  269.61  5950.3  272.73
    6136  270.48  6262.7  271.87  6292.4  273.99  6384.4     277  6569.9  287.01
#Mann= 8 ,-1 , 0
  4256.3      .1       0    4615     .08       0  4759.9     .05       0
    4993     .04       0    4999     .05       0  5589.7      .1       0
  5950.3     .05       0  6292.4      .1       0
Bank Sta=4971.8,5023.4
XS Rating Curve= 0 ,0
Exp/Cntr=0.3,0.1

Type RM Length L Ch R = 1 ,3007    ,779,779,779
BEGIN DESCRIPTION:
BURTON CREEK 6.0
END DESCRIPTION:
XS GIS Cut Line= 3
      3557683.98     10221593.15      3558314.18      10220124.4
      3558242.11     10219241.68
#Sta/Elev= 30
  3593.1  276.55  3742.4  274.29  3936.8   270.7  4138.9  268.27  4169.8  269.72
  4314.7   267.3  4367.3  273.48    4409   274.4  4574.1  266.19  4660.9  270.28
  4737.1  266.27  4923.8  267.84  4933.2  267.58  4970.9   260.9  4976.7  257.72
  4987.6  252.92  5009.1  250.82  5023.5  252.79  5041.6  262.22  5052.9  267.05
  5099.6  269.41  5244.3  267.29  5434.9     268  5615.5  270.57  5646.9  272.64
  5897.1  275.93  5932.5  277.74  6018.7  284.66  6046.9  290.62    6077  291.28
#Mann= 8 ,-1 , 0
  3593.1     .08       0  3742.4      .1       0  3936.8     .08       0
  4169.8     .05       0  4976.7     .06       0  5041.6     .05       0
  5646.9      .1       0  5932.5     .08       0
#XS Ineff= 2 ,-1
 4418.75  4660.8  270.46 4671.02 4911.36  268.21
Permanent Ineff=
       F       F
Bank Sta=4970.9,5041.6
XS Rating Curve= 0 ,0
Exp/Cntr=0.3,0.1

Type RM Length L Ch R = 1 ,2228    ,731,731,731
BEGIN DESCRIPTION:
BURTON CREEK 4.0
END DESCRIPTION:
XS GIS Cut Line= 3
      3557842.14      10221891.6      3559079.81     10220491.64
      3559866.26     10219442.12
#Sta/Elev= 30
  3394.8  283.92  3479.6  279.06  3594.5  278.79  3818.6  272.18  3886.3  271.33
  4036.9  269.05  4251.7  266.45  4500.2  269.76  4712.7   262.1  4925.1  266.31
  4960.2  264.14  4967.8   257.7  4988.4  251.15  5023.8  252.94  5031.3  259.03
    5038  259.98  5059.8   266.5  5088.2   268.7  5287.2  263.25  5437.2  264.26
  5472.6  260.27  5478.9  263.73  5493.5  264.22  5672.7  264.05  5741.4  269.22
  5903.8  274.35  6161.8  274.21  6496.9  278.18  6513.3  278.53  6574.9  280.14
#Mann= 12 ,-1 , 0
  3394.8      .1       0  3594.5     .08       0  3818.6      .1       0
  3886.3     .08       0  4036.9     .05       0  4960.2     .06       0
    5038     .05       0  5741.4      .1       0  5903.8     .05       0
  6161.8      .1       0  6496.9     .15       0  6513.3      .1       0
#XS Ineff= 1 ,-1
 5115.91 5890.91   268.7
Permanent Ineff=
       F
#Block Obstruct= 2 , 0
         4927.27  266.34
Bank Sta=4967.8,5031.3
XS Rating Curve= 0 ,0
Exp/Cntr=0.3,0.1

Type RM Length L Ch R = 1 ,1497    ,662,662,662
BEGIN DESCRIPTION:
BURTON CREEK 3.0
END DESCRIPTION:
XS GIS Cut Line= 3
      3558371.48     10222212.94      3559496.47     10221093.15
      3560486.07     10219311.89
#Sta/Elev= 30
  3255.8  281.92  3624.8  269.05  3676.8  269.82    3936  266.41  3957.2  262.31
  3978.4  263.72  3985.5  260.82  3992.5  263.11  4027.9  259.28  4176.4  257.08
  4303.7   264.3  4360.2  258.31    4834  256.36    4907  257.22  4936.3  253.78
  4966.5  259.36  4972.2  259.53  4987.9  250.75  5016.4  251.89  5039.3  258.43
  5075.1  263.15  5107.2  263.62  5128.9  259.83    5877  258.54  5965.9  262.72
  6023.5  272.46  6083.5  273.25  6097.2  274.28  6467.3  272.99  6880.8  277.14
#Mann= 8 ,-1 , 0
  3255.8     .08       0  3676.8     .05       0  4360.2     .08       0
    4834     .05       0  4966.5     .04       0  5039.3     .05       0
  6083.5      .1       0  6097.2     .15       0
#XS Ineff= 2 ,-1
 3859.09 4288.64   264.5 5104.55 6072.73  263.54
Permanent Ineff=
       F       F
Bank Sta=4972.2,5039.3
XS Rating Curve= 0 ,0
Exp/Cntr=0.3,0.1

Type RM Length L Ch R = 1 ,835     ,662,662,662
BEGIN DESCRIPTION:
BURTON CREEK 3.1
END DESCRIPTION:
XS GIS Cut Line= 3
      3558652.75     10223067.08      3559881.89     10221270.24
      3561194.24     10219546.47
#Sta/Elev= 30
  2347.2  281.19  2689.2  284.63  2844.1  276.87  3134.1  272.73  3358.9  264.62
  3533.4  264.31  3604.9  263.87  3922.2  269.88  3935.8  269.83  4051.7   269.5
  4167.7   269.5  4305.5  269.98  4572.7  267.76  4680.5  257.78  4826.1  256.23
    4930  255.67  4997.7  251.05  5000.5  250.55  5003.7  251.05  5037.8  254.31
  5114.6  261.52  5169.9  264.29  5234.5  264.88  5480.8  266.18  5594.2  271.12
  5685.5  270.65  5801.1  271.49  5992.9   259.3  6393.6  263.19  6690.7  274.43
#Mann= 20 ,-1 , 0
  2347.2     .08       0  2844.1     .15       0  3134.1     .08       0
  3358.9      .1       0  3533.4     .08       0  3604.9     .05       0
  3922.2     .08       0  3935.8     .05       0  4051.7      .1       0
  4167.7     .08       0  4305.5     .05       0  4826.1     .08       0
  4997.7     .07       0  5003.7     .05       0  5114.6     .05       0
  5169.9     .08       0  5234.5     .15       0  5480.8     .08       0
  5594.2      .1       0  5685.5     .05       0
#XS Ineff= 1 ,-1
 5758.52 6542.61  271.68
Permanent Ineff=
       F
Bank Sta=4930,5037.8
XS Rating Curve= 0 ,0
Exp/Cntr=0.3,0.1

Type RM Length L Ch R = 1 ,173     ,0,0,0
BEGIN DESCRIPTION:
BURTON CREEK 1.0
END DESCRIPTION:
XS GIS Cut Line= 3
      3558949.58     10223509.85      3560800.96     10220798.92
      3561496.06     10219776.05
#Sta/Elev= 30
  1717.2  271.34  1959.5  268.22  2099.7   268.1  2120.7   264.8  2141.6  268.09
  3631.6  260.49  3697.5  260.58    4005  258.39  4856.2     262  4932.2  252.18
  4941.1  251.79  5008.9  244.67  5009.9  244.24  5012.6  243.74  5015.9  244.24
  5027.8  251.98  5033.9  247.51  5042.8  254.64  5048.8  251.83  5058.3  259.35
  5063.8   262.7  5207.5  261.74  5330.2   270.4    5423  272.02  5524.8   260.7
    5884  258.77  5934.9  263.81  6129.5  265.28  6207.4  274.04  6236.7  274.36
#Mann= 11 ,-1 , 0
  1717.2     .05       0  1959.5     .05       0  3631.6     .16       0
  3697.5     .05       0  4856.2     .08       0  4932.2     .05       0
  5008.9     .08       0  5009.9     .04       0  5015.9     .08       0
  5058.3     .05       0  6207.4     .08       0
Bank Sta=4941.1,5027.8
XS Rating Curve= 0 ,0
Exp/Cntr=0.3,0.1

Chan Stop Cuts=-1
Use User Specified Reach Order=0
Composite Channel Slope=5