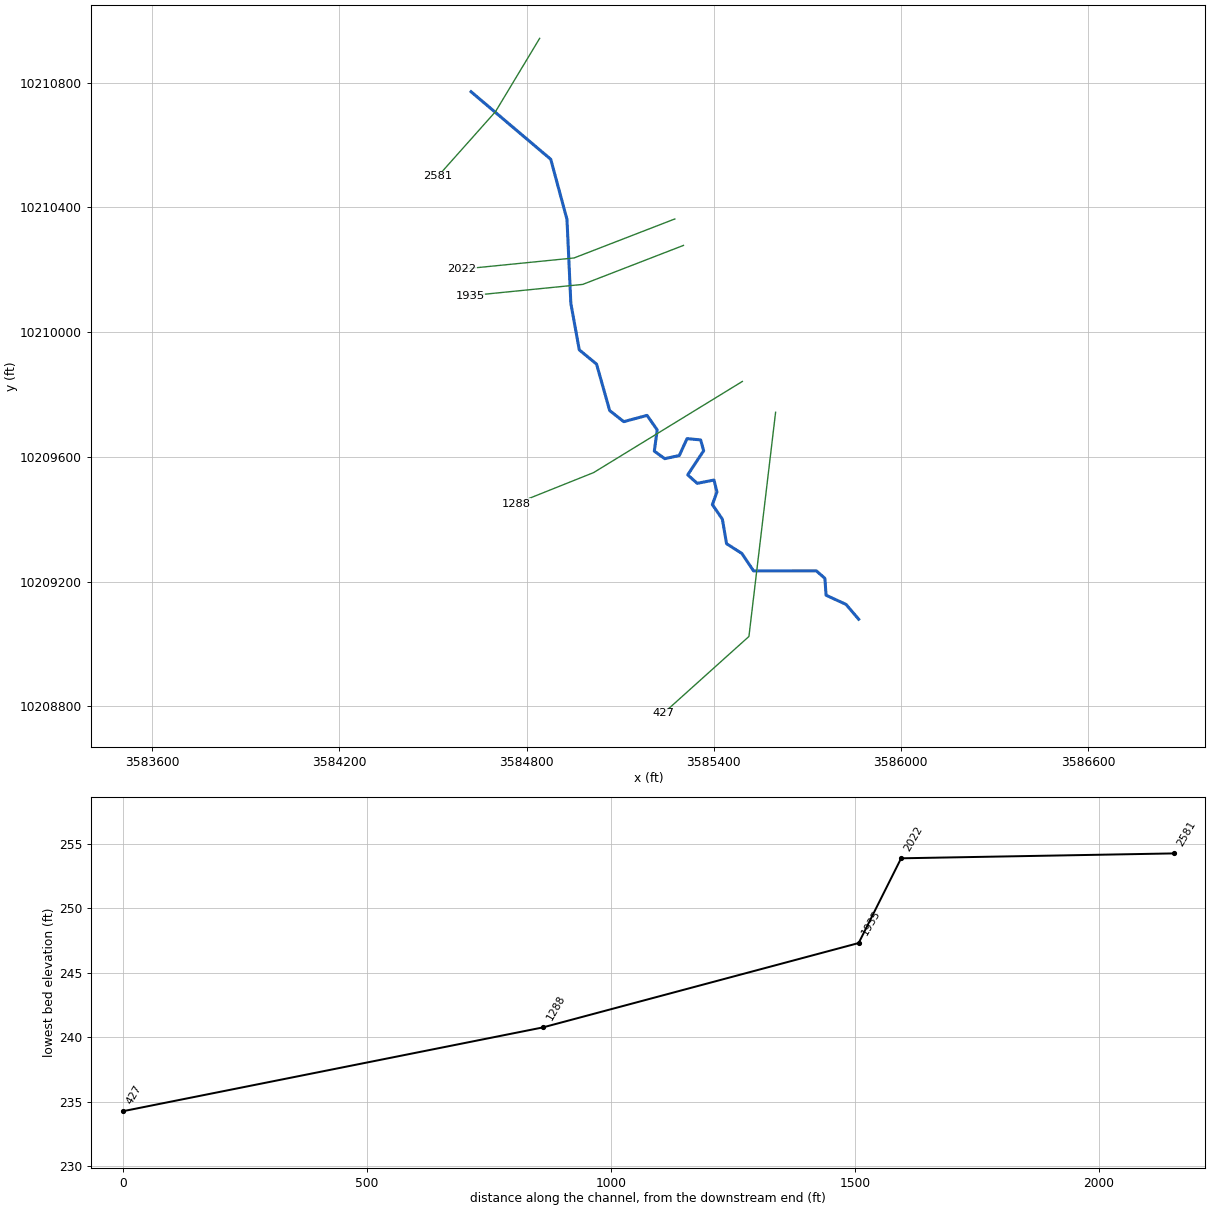
--- CARTERS CREEK TRIB 13 1.prj (project) ---

Proj Title=CARTERS CREEK TRIB 13 1 Base Level Engineering
Current Plan=p01
Default Exp/Contr=0.3,0.1
English Units
Geom File=g01
Flow File=f01
Plan File=p01
Y Axis Title=Elevation
X Axis Title(PF)=Main Channel Distance
X Axis Title(XS)=Station
BEGIN DESCRIPTION:
CARTERS CREEK TRIB 13 1
END DESCRIPTION:
DSS Export Rating Curves= 0
DSS Export Rating Curve Sorted= 0
DSS Export Volume Flow Curves= 0
DXF OffsetX= 0
DXF OffsetY= 0
DXF ScaleX= 1
DXF ScaleY= 10

--- CARTERS CREEK TRIB 13 1.p01 (plan) ---

Plan Title=Multiple Run
Short Identifier=Multiple
Geom File=g01
Flow File=f01
Subcritical Flow
K Sum by GR= 0
Std Step Tol= 0.01
Critical Tol= 0.01
Num of Std Step Trials= 20
Max Error Tol= 0.3
Flow Tol Ratio= 0.001
Split Flow NTrial= 30
Split Flow Tol= 0.02
Split Flow Ratio= 0.02
Log Output Level= 0
Friction Slope Method= 1
Unsteady Friction Slope Method= 2
Unsteady Bridges Friction Slope Method= 1
Parabolic Critical Depth
Global Vel Dist=  1 , 1 , 1
Global Log Level= 0
CheckData=True
Encroach Param= -1, 0, 0, 0
BEGIN DESCRIPTION:
Multiple Run
END DESCRIPTION:

--- CARTERS CREEK TRIB 13 1.f01 (steady flow) ---

Flow Title=Multiple
Program Version=4.10
Number of Profiles= 7
Profile Names=10-year,25-year,50-year,1pct_min,100-year,1pct_plu,500-year
River Rch & RM=CARTERS CREEK TR,Reach-1         ,2581
     128     156     176     147     199     269     254
Boundary for River Rch & Prof#=CARTERS CREEK TR,Reach-1         , 1
Up Type= 0
Dn Type= 3
Dn Slope=0.01
Boundary for River Rch & Prof#=CARTERS CREEK TR,Reach-1         , 2
Up Type= 0
Dn Type= 3
Dn Slope=0.01
Boundary for River Rch & Prof#=CARTERS CREEK TR,Reach-1         , 3
Up Type= 0
Dn Type= 3
Dn Slope=0.01
Boundary for River Rch & Prof#=CARTERS CREEK TR,Reach-1         , 4
Up Type= 0
Dn Type= 3
Dn Slope=0.01
Boundary for River Rch & Prof#=CARTERS CREEK TR,Reach-1         , 5
Up Type= 0
Dn Type= 3
Dn Slope=0.01
Boundary for River Rch & Prof#=CARTERS CREEK TR,Reach-1         , 6
Up Type= 0
Dn Type= 3
Dn Slope=0.01
Boundary for River Rch & Prof#=CARTERS CREEK TR,Reach-1         , 7
Up Type= 0
Dn Type= 3
Dn Slope=0.01
DSS Import GetInterval= 0
DSS Import GetPeak= 0
DSS Import FillOption= 0

--- CARTERS CREEK TRIB 13 1.g01 (geometry) ---

Geom Title=Existing Conditions
Program Version=4.10

River Reach=CARTERS CREEK TR,Reach-1
Reach XY= 30
      3584622.13     10210770.45      3584877.61     10210553.89
      3584929.69     10210361.18      3584942.11     10210091.64
      3584969.09     10209942.78      3585024.43      10209897.2
      3585066.67     10209748.11      3585111.66     10209712.65
      3585186.46     10209732.74      3585218.99     10209686.14
      3585209.68     10209618.09      3585243.09     10209593.98
      3585289.79     10209604.04      3585314.67     10209658.25
      3585358.24     10209654.07      3585367.91     10209619.41
      3585316.77     10209542.04      3585347.22     10209514.84
      3585401.03     10209525.41      3585410.54     10209487.35
      3585395.82     10209446.71       3585427.9     10209399.94
      3585441.33     10209321.35      3585490.46     10209289.98
      3585527.85     10209234.12      3585728.96     10209234.48
      3585756.65     10209210.19      3585760.34     10209156.11
      3585824.52     10209126.66      3585864.77     10209079.22

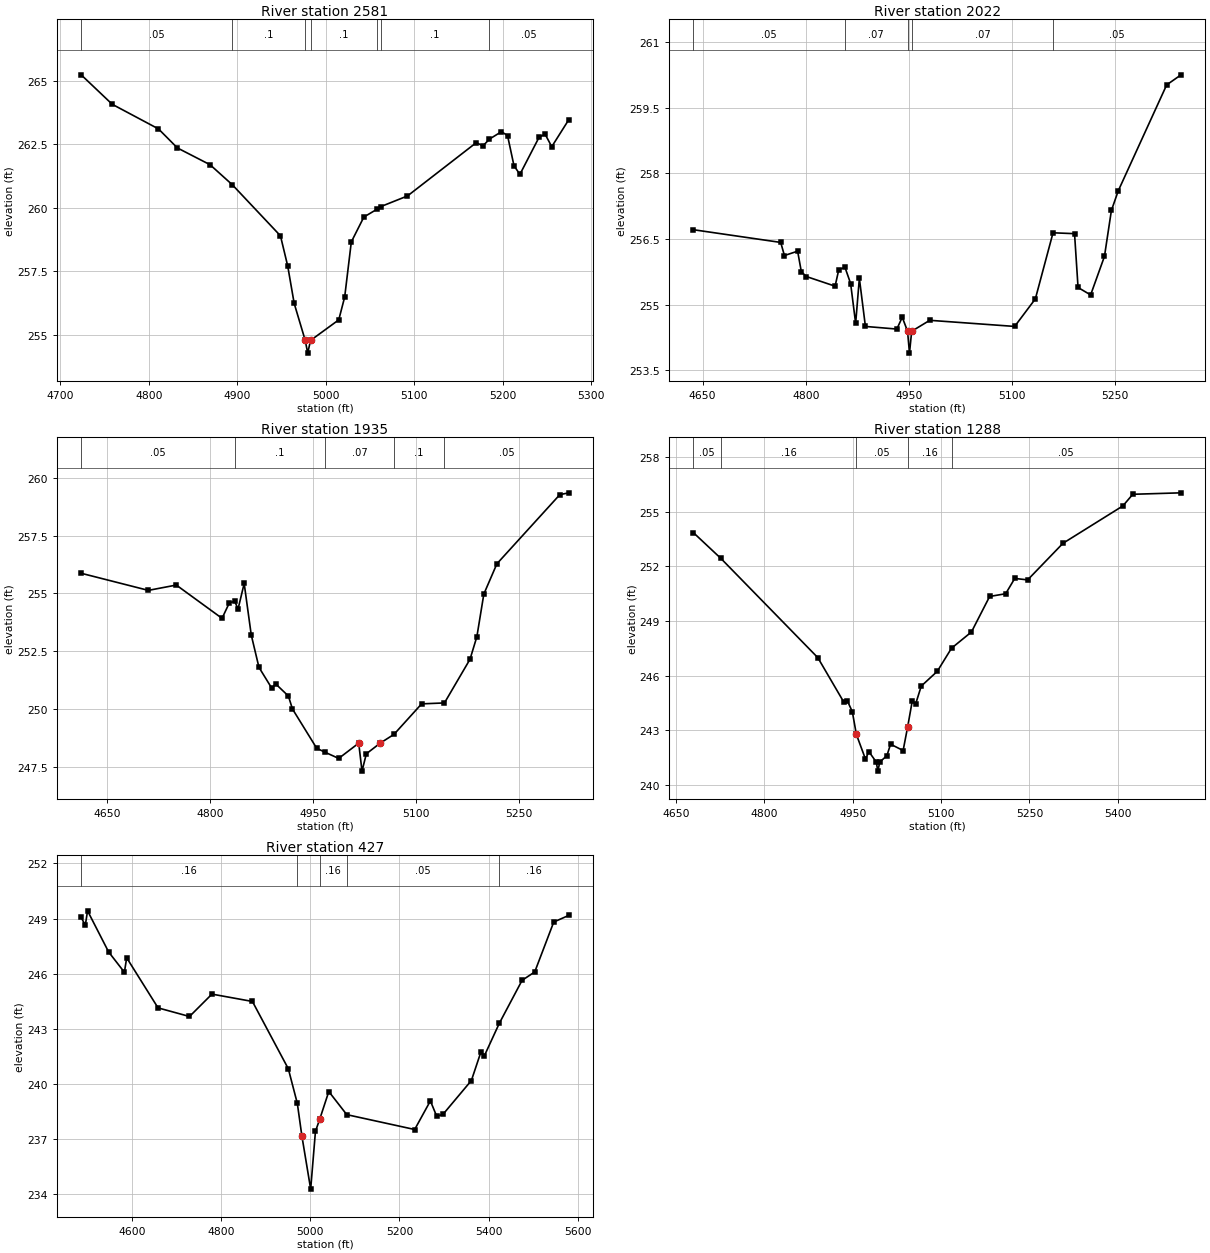
Type RM Length L Ch R = 1 ,2581    ,559,559,559
BEGIN DESCRIPTION:
CARTERS CREEK TRIB 13.1 4.0
END DESCRIPTION:
XS GIS Cut Line= 3
      3584842.12     10210941.67      3584700.52     10210706.67
      3584516.41     10210499.93
#Sta/Elev= 30
  4723.6  265.23  4758.7  264.07    4811   263.1  4832.4  262.35  4869.3  261.69
  4894.5   260.9  4948.9  258.89  4957.1   257.7  4964.4  256.23  4976.9  254.77
  4979.7  254.27  4982.9  254.77  5014.8  255.58  5021.5  256.48    5029  258.65
  5043.2  259.63  5058.2  259.94  5062.3  260.04  5092.5  260.46  5170.3  262.56
  5177.8  262.43  5185.2   262.7  5198.7  262.99  5205.6  262.84  5212.9  261.65
  5219.6  261.31  5241.4  262.78  5248.1  262.89  5255.6   262.4  5274.8  263.46
#Mann= 7 ,-1 , 0
  4723.6     .05       0  4894.5      .1       0  4976.9     .07       0
  4982.9      .1       0  5058.2     .05       0  5062.3      .1       0
  5185.2     .05       0
Bank Sta=4976.9,4982.9
XS Rating Curve= 0 ,0
Exp/Cntr=0.3,0.1

Type RM Length L Ch R = 1 ,2022    ,87,87,87
BEGIN DESCRIPTION:
CARTERS CREEK TRIB 13.1 3.1
END DESCRIPTION:
XS GIS Cut Line= 3
      3585275.33     10210362.51      3584952.44     10210237.52
      3584591.28     10210201.41
#Sta/Elev= 30
  4636.7  256.71  4763.6  256.42    4769  256.12  4788.2  256.22  4793.6  255.75
    4801  255.64  4842.7  255.42  4848.1   255.8  4857.1  255.85  4865.3  255.48
  4872.6  254.57    4878   255.6  4886.8   254.5  4932.5  254.44  4940.4  254.71
  4948.1  254.39  4950.9  253.89  4954.1  254.39  4980.4  254.64  5103.9   254.5
    5134  255.13  5159.7  256.64    5191  256.62  5196.1  255.39  5214.4  255.22
  5234.5   256.1  5244.6  257.15  5254.6   257.6    5325  260.02  5345.9  260.25
#Mann= 5 ,-1 , 0
  4636.7     .05       0  4857.1     .07       0  4948.1     .07       0
  4954.1     .07       0  5159.7     .05       0
Bank Sta=4948.1,4954.1
XS Rating Curve= 0 ,0
Exp/Cntr=0.3,0.1

Type RM Length L Ch R = 1 ,1935    ,647,647,647
BEGIN DESCRIPTION:
CARTERS CREEK TRIB 13.1 3.0
END DESCRIPTION:
XS GIS Cut Line= 3
      3585303.22     10210277.76       3584980.3     10210152.75
      3584619.18     10210116.64
#Sta/Elev= 30
  4612.7  255.87  4710.4  255.13  4751.1  255.36  4817.6  253.92  4828.4   254.6
  4836.2  254.65  4840.9  254.32  4849.8  255.43  4860.1   253.2  4871.3   251.8
  4890.1  250.89  4895.4  251.09  4914.1  250.56    4920     250  4955.3   248.3
  4967.2  248.13  4987.3  247.86  5016.4  248.52  5021.2  247.31  5027.5  248.06
  5047.6  248.52  5067.7   248.9  5107.9  250.22  5141.1  250.26  5178.3  252.15
  5188.3  253.13  5198.4  254.97  5217.4  256.28  5308.9  259.27  5321.9  259.35
#Mann= 5 ,-1 , 0
  4612.7     .05       0  4836.2      .1       0  4967.2     .07       0
  5067.7      .1       0  5141.1     .05       0
Bank Sta=5016.4,5047.6
XS Rating Curve= 0 ,0
Exp/Cntr=0.3,0.1

Type RM Length L Ch R = 1 ,1288    ,861,861,861
BEGIN DESCRIPTION:
CARTERS CREEK TRIB 13.1 2.0
END DESCRIPTION:
XS GIS Cut Line= 3
      3585492.09     10209841.63      3585015.02     10209549.28
      3584766.03     10209449.68
#Sta/Elev= 30
  4679.6  253.85  4726.1  252.44  4890.7  246.99  4934.8  244.55  4940.7  244.63
  4949.3  244.02  4956.1  242.78  4971.6  241.42  4977.4  241.83  4989.9  241.26
  4992.6  240.76  4995.9  241.26    5008  241.61  5014.2  242.24  5035.5  241.89
  5043.2  243.19  5050.9  244.59  5056.8  244.45  5066.3  245.43  5093.5  246.24
  5117.7  247.51  5151.5   248.4  5182.4  250.35  5209.6   250.5    5225  251.34
  5246.9  251.26  5306.9  253.27  5408.5  255.32  5425.4  255.96  5507.3  256.04
#Mann= 5 ,-1 , 0
  4679.6     .05       0  4726.1     .16       0  4956.1     .05       0
  5043.2     .16       0  5117.7     .05       0
Bank Sta=4956.1,5043.2
XS Rating Curve= 0 ,0
Exp/Cntr=0.3,0.1

Type RM Length L Ch R = 1 ,427     ,0,0,0
BEGIN DESCRIPTION:
CARTERS CREEK TRIB 13.1 1.0
END DESCRIPTION:
XS GIS Cut Line= 3
      3585598.57     10209742.74      3585513.06     10209023.86
      3585238.72      10208777.3
#Sta/Elev= 30
  4486.6  249.06  4495.9  248.63  4500.9  249.42  4548.1  247.18  4583.5  246.07
  4588.6  246.86  4658.9  244.13  4729.4  243.66  4779.7  244.88  4870.4  244.48
  4950.9  240.81  4971.1  238.92  4981.2  237.16    5001  234.25  5011.7   237.4
  5021.4  238.07  5041.6  239.57  5081.9  238.31  5234.1   237.5  5269.3  239.06
  5283.5  238.22  5297.7  238.33  5361.2  240.17  5382.9  241.75  5389.6  241.48
  5423.6  243.28  5474.8  245.63  5503.2  246.09  5545.8  248.81  5579.4  249.17
#Mann= 5 ,-1 , 0
  4486.6     .16       0  4971.1     .04       0  5021.4     .16       0
  5081.9     .05       0  5423.6     .16       0
Bank Sta=4981.2,5021.4
XS Rating Curve= 0 ,0
Exp/Cntr=0.3,0.1

Chan Stop Cuts=-1
Use User Specified Reach Order=0
Composite Channel Slope=5