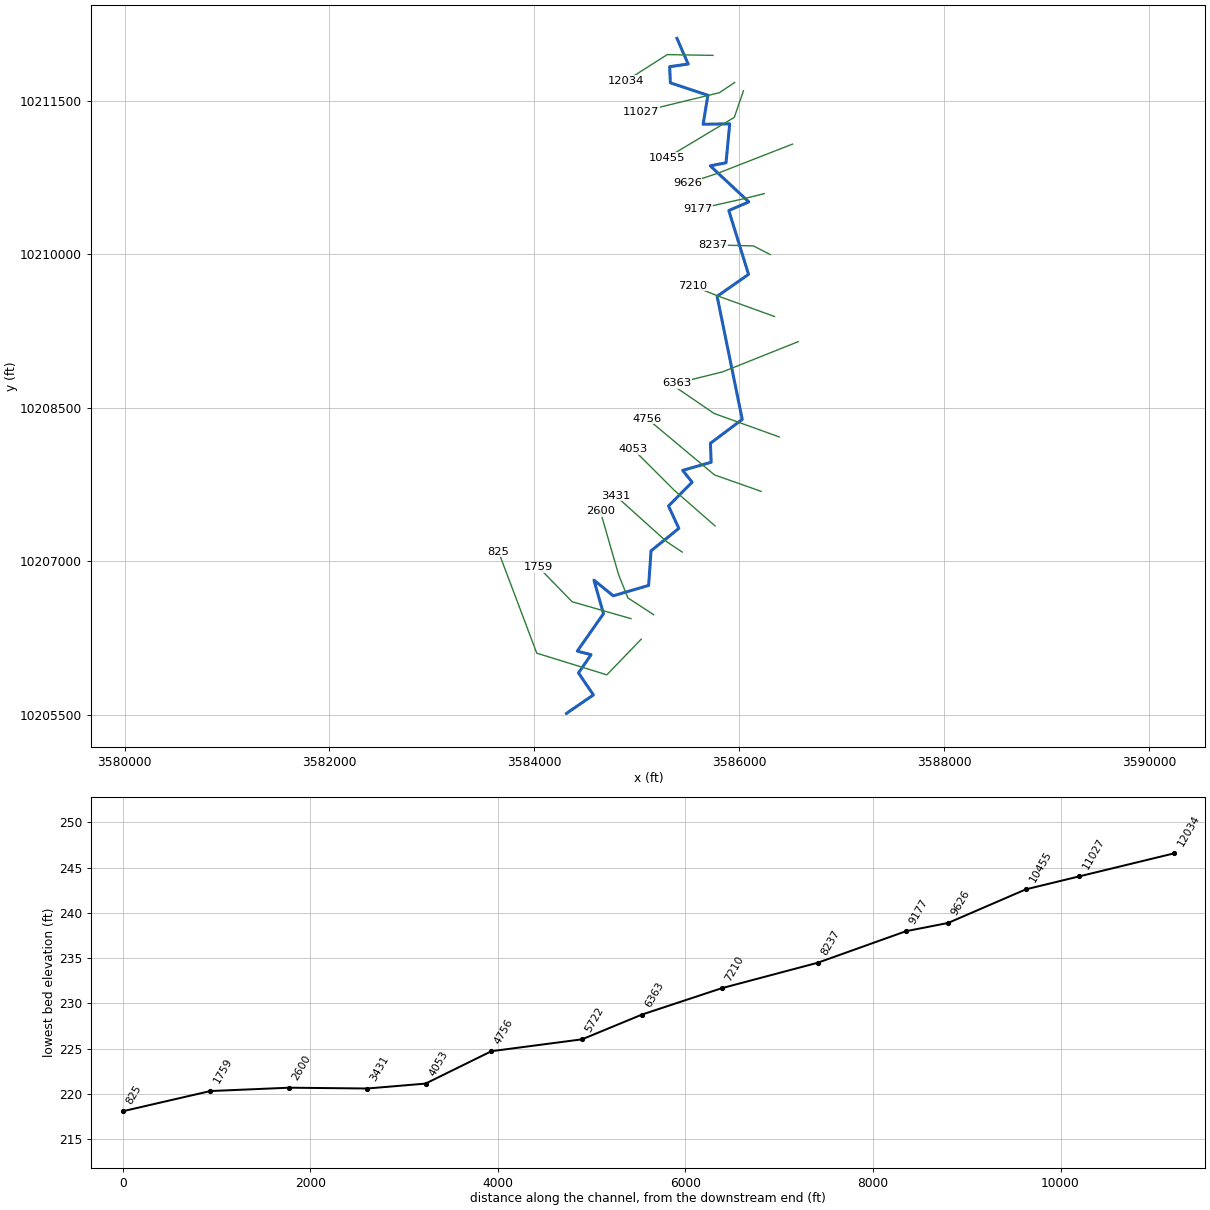
--- CARTERS CREEK TRIB 13.prj (project) ---

Proj Title=CARTERS CREEK TRIB 13 Base Level Engineering
Current Plan=p01
Default Exp/Contr=0.3,0.1
English Units
Geom File=g01
Flow File=f01
Plan File=p01
BEGIN DESCRIPTION:
CARTERS CREEK TRIB 13
END DESCRIPTION:

--- CARTERS CREEK TRIB 13.p01 (plan) ---

Plan Title=Multiple Run
Short Identifier=Multiple
Geom File=g01
Flow File=f01
Subcritical Flow
K Sum by GR= 0
Std Step Tol= 0.01
Critical Tol= 0.01
Num of Std Step Trials= 20
Max Error Tol= 0.3
Flow Tol Ratio= 0.001
Split Flow NTrial= 30
Split Flow Tol= 0.02
Split Flow Ratio= 0.02
Log Output Level= 0
Friction Slope Method= 1
Unsteady Friction Slope Method= 2
Unsteady Bridges Friction Slope Method= 1
Parabolic Critical Depth
Global Vel Dist=  1 , 1 , 1
Global Log Level= 0
CheckData=True
Encroach Param= -1, 0, 0, 0
BEGIN DESCRIPTION:
Multiple Run
END DESCRIPTION:

--- CARTERS CREEK TRIB 13.f01 (steady flow) ---

Flow Title=Multiple
Number of Profiles=7
Profile Names=10-year,25-year,50-year,1pct_min,100-year,1pct_plu,500-year
River Rch & RM= CARTERS CREEK TR,Reach-1,12034
     405     531     631     551     745    1007    1037
River Rch & RM= CARTERS CREEK TR,Reach-1,6363
     587     787     948     837    1132    1530    1616
Boundary for River Rch & Prof#=CARTERS CREEK TR,Reach-1,1
Up Type=0
Dn Type=3
Dn Slope=0.005
Boundary for River Rch & Prof#=CARTERS CREEK TR,Reach-1,2
Up Type=0
Dn Type=3
Dn Slope=0.005
Boundary for River Rch & Prof#=CARTERS CREEK TR,Reach-1,3
Up Type=0
Dn Type=3
Dn Slope=0.005
Boundary for River Rch & Prof#=CARTERS CREEK TR,Reach-1,4
Up Type=0
Dn Type=3
Dn Slope=0.005
Boundary for River Rch & Prof#=CARTERS CREEK TR,Reach-1,5
Up Type=0
Dn Type=3
Dn Slope=0.005
Boundary for River Rch & Prof#=CARTERS CREEK TR,Reach-1,6
Up Type=0
Dn Type=3
Dn Slope=0.005
Boundary for River Rch & Prof#=CARTERS CREEK TR,Reach-1,7
Up Type=0
Dn Type=3
Dn Slope=0.005

--- CARTERS CREEK TRIB 13.g01 (geometry) ---

Geom Title=Existing Conditions

River Reach=CARTERS CREEK TR,Reach-1
Reach XY= 30
      3585390.36     10212107.93      3585499.55     10211856.84
      3585319.14     10211831.28      3585326.11     10211673.31
      3585692.18     10211552.14      3585645.62     10211269.16
      3585905.17     10211273.07      3585869.04     10210892.75
      3585715.06     10210863.10      3586091.47     10210510.98
      3585896.26     10210426.89      3586088.73     10209803.23
      3585782.15     10209588.94      3586027.46     10208386.99
      3585717.02     10208154.76      3585723.93     10207968.20
      3585446.07     10207889.69      3585538.28     10207773.65
      3585307.84     10207541.74      3585408.69     10207323.12
      3585137.69     10207103.79      3585113.96     10206766.19
      3584768.91     10206665.06      3584580.54     10206817.41
      3584673.71     10206490.25      3584417.63     10206124.58
      3584552.18     10206089.86      3584429.57     10205911.90
      3584574.96     10205697.06      3584312.59     10205516.85

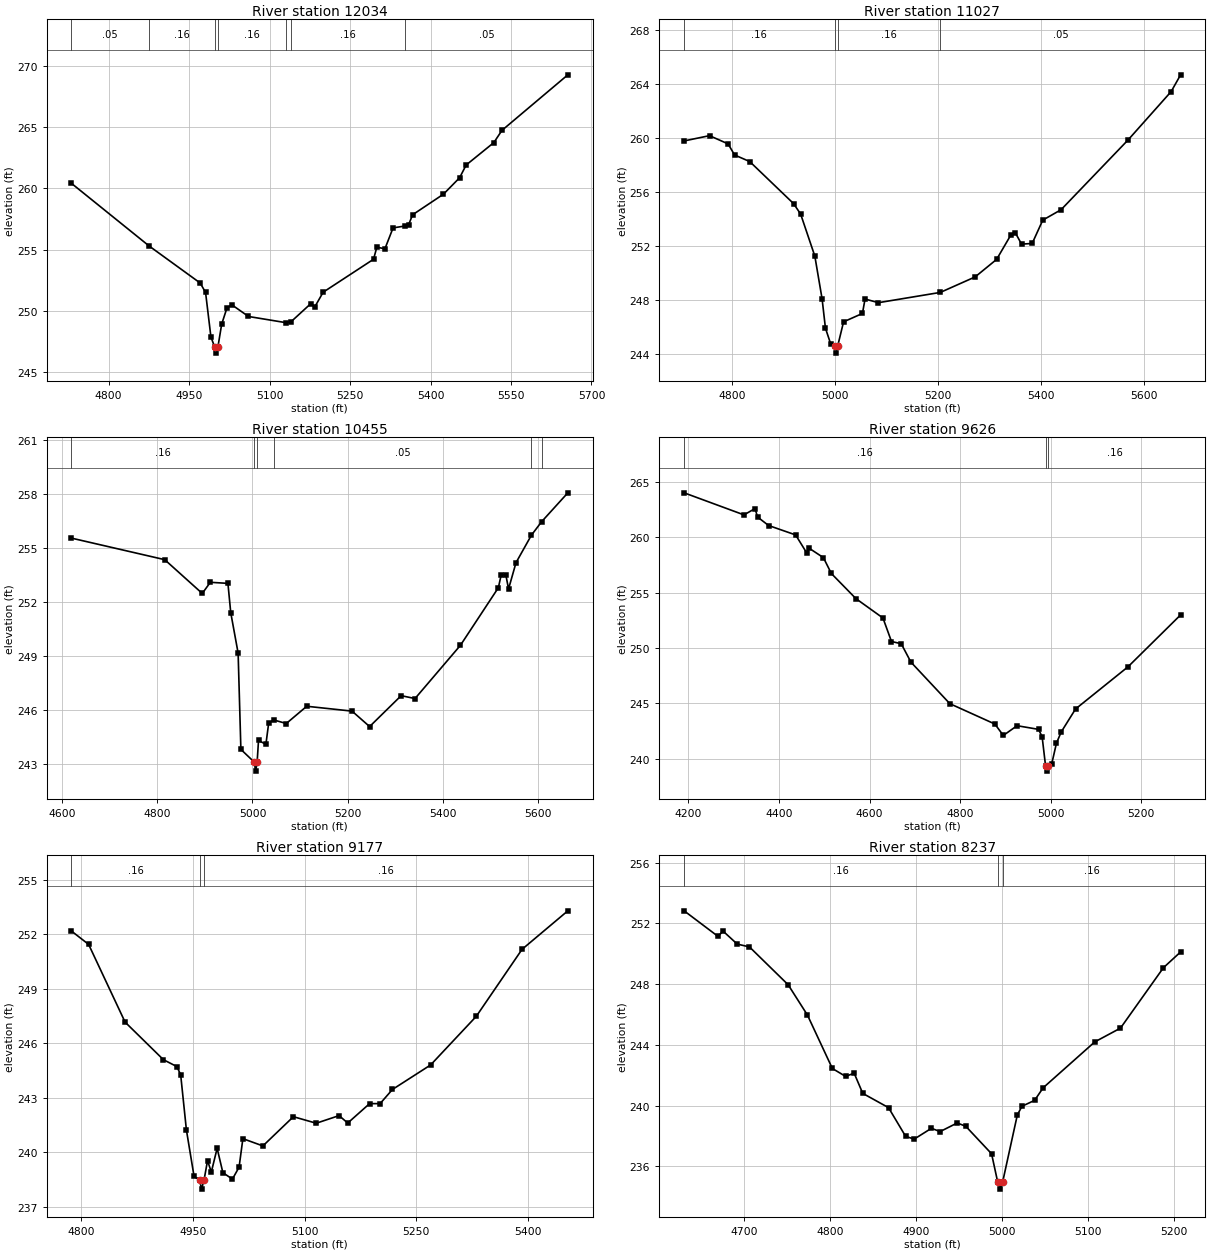
Type RM Length L Ch R = 1,12034,1007,1007,1007
BEGIN DESCRIPTION:
CARTERS CREEK TRIB 13 19.0
END DESCRIPTION:
XS GIS Cut Line= 3
      3585742.13     10211941.64      3585295.27     10211949.00
      3584892.12     10211691.65
#Sta/Elev= 30
  4730.7  260.42  4875.7  255.30  4970.8  252.28  4980.8  251.51  4990.8  247.87
  4997.8  247.06  5000.5  246.56  5003.8  247.06  5010.8  248.92  5020.8  250.27
  5030.2  250.49  5060.8  249.55  5131.4  249.04  5140.3  249.13  5176.7  250.59
  5184.7  250.36  5199.9  251.53  5293.8  254.22  5300.0  255.21  5315.0  255.07
  5330.2  256.78  5352.1  256.93  5359.3  257.05  5366.6  257.85  5424.1  259.53
  5454.2  260.87  5466.4  261.91  5518.0  263.74  5533.2  264.74  5655.9  269.27
#Mann=7,-1,0
  4730.7    0.05       0  4875.7    0.16       0  4997.8    0.07       0
  5003.8    0.16       0  5131.4    0.05       0  5140.3    0.16       0
  5352.1    0.05       0
Bank Sta=4997.8,5003.8
Exp/Cntr=0.3,0.1

Type RM Length L Ch R = 1,11027,572,572,572
BEGIN DESCRIPTION:
CARTERS CREEK TRIB 13 17.0
END DESCRIPTION:
XS GIS Cut Line= 3
      3585953.54     10211677.04      3585803.56     10211577.06
      3585042.06     10211391.63
#Sta/Elev= 30
  4706.6  259.76  4755.9  260.15  4792.0  259.54  4804.5  258.72  4834.0  258.23
  4919.2  255.11  4932.8  254.34  4960.4  251.22  4974.5  248.05  4981.0  245.88
  4991.3  244.70  4998.6  244.53  5001.3  244.03  5004.6  244.53  5016.2  246.35
  5052.8  246.97  5057.9  248.04  5083.9  247.77  5204.0  248.53  5271.7  249.68
  5313.4  250.98  5341.2  252.80  5350.0  252.93  5361.8  252.11  5382.4  252.16
  5403.0  253.89  5438.5  254.66  5568.8  259.84  5652.3  263.42  5670.6  264.66
#Mann=4,-1,0
  4706.6    0.16       0  4998.6    0.07       0  5004.6    0.16       0
  5204.0    0.05       0
Bank Sta=4998.6,5004.6
Exp/Cntr=0.3,0.1

Type RM Length L Ch R = 1,10455,829,829,829
BEGIN DESCRIPTION:
CARTERS CREEK TRIB 13 16.0
END DESCRIPTION:
XS GIS Cut Line= 3
      3586039.35     10211596.18      3585949.92     10211336.17
      3585292.11     10210941.65
#Sta/Elev= 30
  4619.9  255.56  4815.8  254.36  4894.6  252.48  4911.6  253.10  4948.5  253.04
  4954.4  251.41  4969.9  249.16  4975.7  243.80  5003.8  243.09  5006.6  242.59
  5009.8  243.09  5012.7  244.30  5028.2  244.08  5034.0  245.26  5044.5  245.44
  5071.0  245.24  5113.9  246.20  5209.0  245.93  5245.9  245.07  5312.1  246.79
  5341.2  246.63  5436.4  249.59  5516.1  252.80  5522.0  253.51  5531.7  253.52
  5537.5  252.73  5553.1  254.19  5585.4  255.72  5606.8  256.47  5661.9  258.08
#Mann=6,-1,0
  4619.9    0.16       0  5003.8    0.07       0  5009.8    0.16       0
  5044.5    0.05       0  5585.4     0.1       0  5606.8    0.05       0
Bank Sta=5003.8,5009.8
Exp/Cntr=0.3,0.1

Type RM Length L Ch R = 1,9626,449,449,449
BEGIN DESCRIPTION:
CARTERS CREEK TRIB 13 15.0
END DESCRIPTION:
XS GIS Cut Line= 3
      3586518.52     10211075.38      3585792.11     10210791.64
      3585492.09     10210691.64
#Sta/Elev= 30
  4190.5  264.00  4322.6  262.01  4347.1  262.58  4352.5  261.82  4377.0  261.05
  4436.7  260.20  4461.1  258.58  4466.5  259.00  4498.0  258.15  4515.5  256.72
  4569.8  254.45  4629.5  252.70  4648.3  250.58  4669.8  250.38  4691.2  248.72
  4777.1  244.97  4876.6  243.13  4895.2  242.10  4925.6  242.98  4973.0  242.65
  4980.9  241.98  4988.4  239.38  4991.2  238.88  4994.4  239.38  5002.0  239.52
  5012.5  241.40  5023.1  242.42  5054.7  244.49  5170.6  248.30  5286.6  252.98
#Mann=3,-1,0
  4190.5    0.16       0  4988.4    0.07       0  4994.4    0.16       0
Bank Sta=4988.4,4994.4
Exp/Cntr=0.3,0.1

Type RM Length L Ch R = 1,9177,940,940,940
BEGIN DESCRIPTION:
CARTERS CREEK TRIB 13 14.0
END DESCRIPTION:
XS GIS Cut Line= 3
      3586242.12     10210591.65      3586042.11     10210541.64
      3585592.06     10210441.63
#Sta/Elev= 30
  4786.6  252.19  4809.8  251.45  4858.8  247.17  4910.3  245.10  4928.4  244.72
  4933.5  244.27  4941.2  241.23  4951.5  238.67  4958.9  238.47  4961.6  237.97
  4964.9  238.47  4969.6  239.54  4974.7  238.91  4982.5  240.22  4990.2  238.88
  5003.0  238.52  5012.0  239.18  5017.1  240.75  5044.0  240.35  5085.0  241.96
  5115.7  241.60  5146.4  242.02  5158.0  241.61  5187.4  242.68  5201.5  242.68
  5218.1  243.46  5269.4  244.81  5330.8  247.49  5392.3  251.18  5453.8  253.30
#Mann=3,-1,0
  4786.6    0.16       0  4958.9    0.07       0  4964.9    0.16       0
Bank Sta=4958.9,4964.9
Exp/Cntr=0.3,0.1

Type RM Length L Ch R = 1,8237,1027,1027,1027
BEGIN DESCRIPTION:
CARTERS CREEK TRIB 13 12.0
END DESCRIPTION:
XS GIS Cut Line= 3
      3586299.81     10209997.25      3586137.22     10210080.92
      3585742.12     10210091.64
#Sta/Elev= 30
  4630.1  252.83  4669.7  251.14  4675.3  251.50  4691.9  250.64  4706.2  250.45
  4751.2  247.96  4773.7  245.96  4802.7  242.44  4818.1  241.92  4828.1  242.13
  4838.1  240.80  4868.1  239.86  4888.1  237.96  4898.1  237.79  4918.1  238.50
  4928.1  238.28  4948.1  238.85  4958.1  238.63  4988.1  236.82  4995.1  234.99
  4997.9  234.49  5001.1  234.99  5018.1  239.38  5023.5  239.95  5038.2  240.34
  5048.2  241.17  5108.2  244.19  5138.2  245.10  5188.2  249.08  5208.2  250.12
#Mann=3,-1,0
  4630.1    0.16       0  4995.1    0.07       0  5001.1    0.16       0
Bank Sta=4995.1,5001.1
Exp/Cntr=0.3,0.1

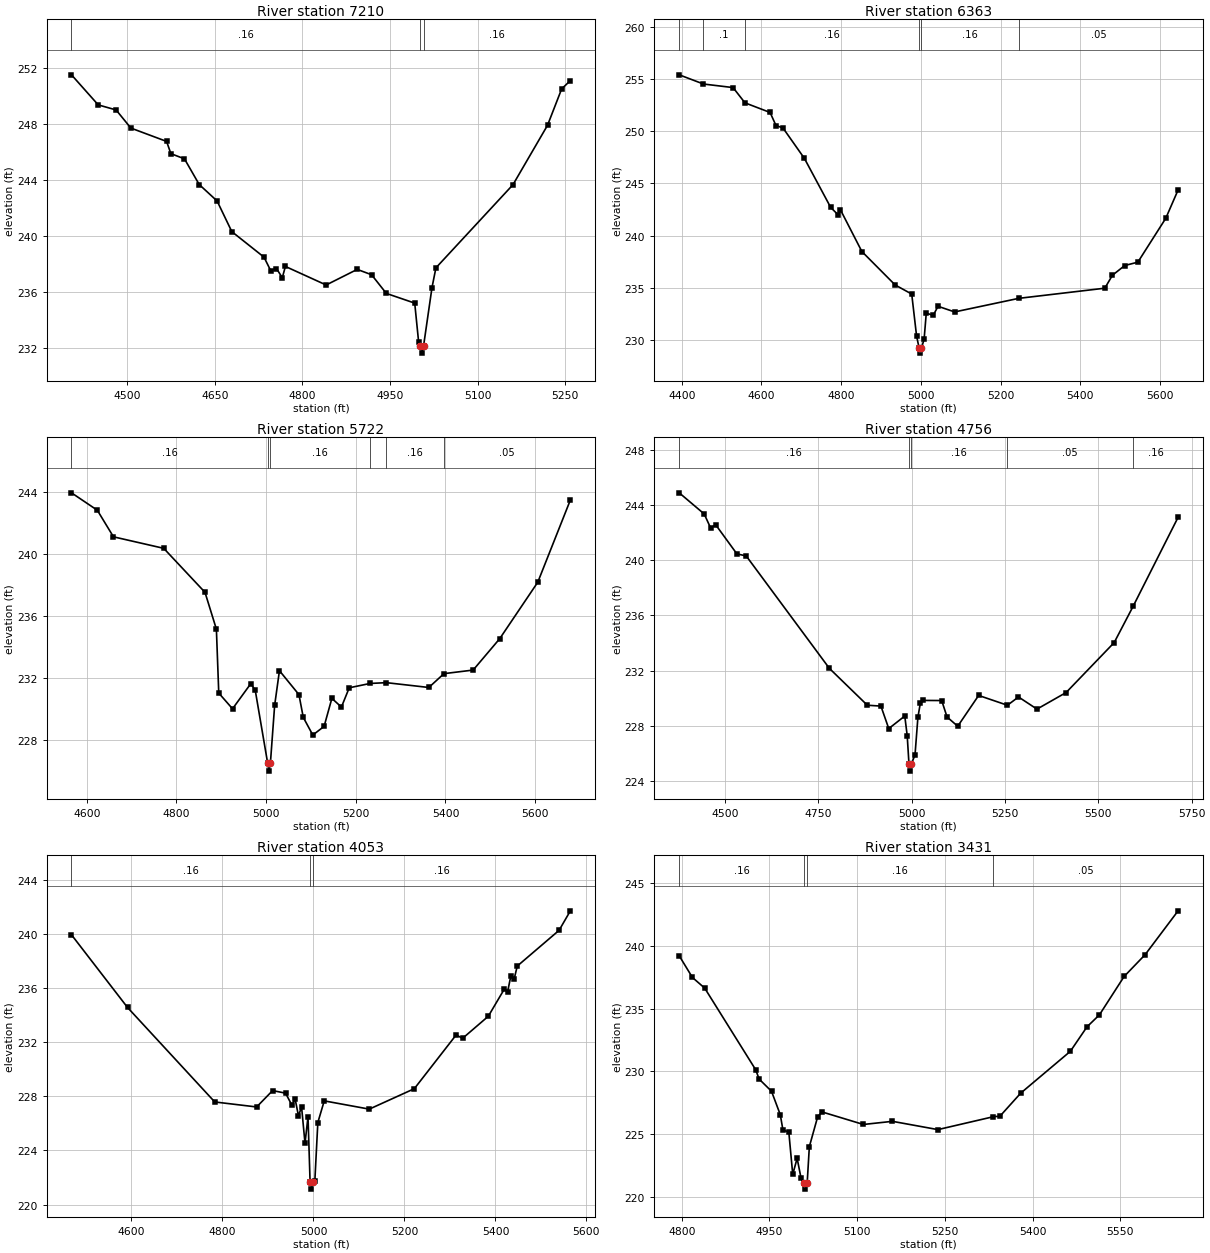
Type RM Length L Ch R = 1,7210,847,847,847
BEGIN DESCRIPTION:
CARTERS CREEK TRIB 13 11.0
END DESCRIPTION:
XS GIS Cut Line= 3
      3586342.07     10209391.66      3585792.11     10209591.64
      3585542.06     10209691.66
#Sta/Elev= 30
  4404.5  251.48  4450.3  249.34  4480.9  248.98  4506.2  247.69  4567.4  246.74
  4574.7  245.87  4598.0  245.50  4623.3  243.67  4653.9  242.50  4679.1  240.32
  4734.3  238.50  4745.6  237.55  4755.6  237.69  4765.6  237.04  4770.9  237.84
  4840.7  236.52  4893.9  237.63  4918.5  237.25  4943.8  235.92  4992.4  235.23
  4999.1  232.46  5001.5  232.17  5004.3  231.67  5007.5  232.17  5022.0  236.34
  5028.7  237.74  5160.7  243.66  5219.9  247.89  5244.1  250.48  5259.0  251.07
#Mann=3,-1,0
  4404.5    0.16       0  5001.5    0.07       0  5007.5    0.16       0
Bank Sta=5001.5,5007.5
Exp/Cntr=0.3,0.1

Type RM Length L Ch R = 1,6363,641,641,641
BEGIN DESCRIPTION:
CARTERS CREEK TRIB 13 10.0
END DESCRIPTION:
XS GIS Cut Line= 3
      3586573.83     10209146.25      3585836.24     10208851.43
      3585392.13     10208741.65
#Sta/Elev= 30
  4393.8  255.39  4454.7  254.51  4528.9  254.17  4558.8  252.71  4621.8  251.79
  4636.6  250.54  4654.1  250.31  4708.0  247.39  4774.0  242.70  4792.8  241.99
  4798.2  242.49  4852.1  238.49  4935.6  235.29  4977.2  234.42  4989.4  230.40
  4995.7  229.27  4998.5  228.77  5001.7  229.27  5008.3  230.10  5013.7  232.60
  5031.0  232.38  5043.3  233.25  5084.9  232.71  5245.8  234.01  5461.7  234.98
  5480.8  236.22  5511.7  237.15  5544.6  237.47  5614.7  241.67  5645.6  244.38
#Mann=6,-1,0
  4393.8    0.16       0  4454.7     0.1       0  4558.8    0.16       0
  4995.7    0.07       0  5001.7    0.16       0  5245.8    0.05       0
Bank Sta=4995.7,5001.7
Exp/Cntr=0.3,0.1

Type RM Length L Ch R = 1,5722,966,966,966
BEGIN DESCRIPTION:
CARTERS CREEK TRIB 13 9.0
END DESCRIPTION:
XS GIS Cut Line= 3
      3586388.28     10208216.03      3585752.91     10208445.18
      3585392.09     10208691.65
#Sta/Elev= 30
  4566.1  243.93  4623.7  242.81  4659.7  241.10  4771.8  240.36  4863.8  237.53
  4889.2  235.16  4894.5  231.05  4925.2  230.04  4966.0  231.66  4975.9  231.22
  5003.6  226.53  5006.4  226.03  5009.6  226.53  5019.1  230.26  5029.8  232.49
  5073.3  230.95  5082.9  229.49  5104.2  228.35  5129.4  228.91  5146.7  230.71
  5168.0  230.15  5185.4  231.39  5232.1  231.67  5268.3  231.72  5362.9  231.41
  5396.6  232.30  5461.7  232.53  5521.0  234.55  5605.8  238.18  5678.5  243.47
#Mann=6,-1,0
  4566.1    0.16       0  5003.6    0.07       0  5009.6    0.16       0
  5232.1    0.05       0  5268.3    0.16       0  5396.6    0.05       0
Bank Sta=5003.6,5009.6
Exp/Cntr=0.3,0.1

Type RM Length L Ch R = 1,4756,703,703,703
BEGIN DESCRIPTION:
CARTERS CREEK TRIB 13 7.0
END DESCRIPTION:
XS GIS Cut Line= 3
      3586211.28     10207684.75      3585756.10     10207845.40
      3585101.89     10208393.08
#Sta/Elev= 30
  4377.9  244.87  4444.8  243.34  4461.9  242.33  4475.8  242.55  4532.3  240.45
  4557.3  240.30  4780.0  232.16  4881.7  229.49  4918.0  229.43  4939.0  227.80
  4981.9  228.71  4988.4  227.29  4993.2  225.22  4996.0  224.72  4999.2  225.22
  5009.3  225.89  5017.1  228.63  5023.6  229.64  5031.4  229.84  5080.8  229.83
  5095.1  228.64  5123.7  227.97  5179.7  230.20  5256.8  229.49  5286.4  230.09
  5335.9  229.21  5413.9  230.41  5542.7  234.03  5593.1  236.64  5713.8  243.10
#Mann=5,-1,0
  4377.9    0.16       0  4993.2    0.07       0  4999.2    0.16       0
  5256.8    0.05       0  5593.1    0.16       0
Bank Sta=4993.2,4999.2
Exp/Cntr=0.3,0.1

Type RM Length L Ch R = 1,4053,622,622,622
BEGIN DESCRIPTION:
CARTERS CREEK TRIB 13 6.0
END DESCRIPTION:
XS GIS Cut Line= 3
      3585761.93     10207347.39      3585361.96     10207697.36
      3584962.35     10208096.97
#Sta/Elev= 30
  4468.1  239.93  4591.3  234.56  4783.0  227.58  4875.1  227.21  4910.2  228.42
  4938.7  228.23  4952.9  227.32  4959.5  227.83  4967.1  226.54  4973.8  227.23
  4981.4  224.53  4988.0  226.49  4992.6  221.64  4995.4  221.14  4998.6  221.64
  5003.0  221.73  5009.6  226.06  5023.7  227.66  5122.7  227.05  5221.7  228.56
  5313.6  232.53  5327.8  232.28  5384.3  233.91  5419.7  235.93  5426.8  235.73
  5433.8  236.88  5440.9  236.63  5448.0  237.62  5539.9  240.26  5564.7  241.70
#Mann=3,-1,0
  4468.1    0.16       0  4992.6    0.07       0  4998.6    0.16       0
Bank Sta=4992.6,4998.6
Exp/Cntr=0.3,0.1

Type RM Length L Ch R = 1,3431,831,831,831
BEGIN DESCRIPTION:
CARTERS CREEK TRIB 13 5.0
END DESCRIPTION:
XS GIS Cut Line= 3
      3585442.14     10207091.62      3585292.11     10207191.64
      3584792.10     10207641.64
#Sta/Elev= 30
  4795.7  239.22  4818.3  237.49  4839.3  236.64  4926.4  230.13  4932.4  229.38
  4953.5  228.41  4968.5  226.54  4973.0  225.33  4983.1  225.15  4989.8  221.77
  4997.3  223.06  5004.0  221.48  5008.5  221.10  5011.3  220.60  5014.5  221.10
  5018.2  223.99  5032.4  226.37  5039.9  226.76  5110.6  225.76  5160.3  226.01
  5238.0  225.35  5332.9  226.38  5344.1  226.42  5379.6  228.26  5464.5  231.60
  5492.9  233.55  5514.2  234.51  5556.4  237.57  5592.3  239.31  5648.7  242.81
#Mann=4,-1,0
  4795.7    0.16       0  5008.5    0.07       0  5014.5    0.16       0
  5332.9    0.05       0
Bank Sta=5008.5,5014.5
Exp/Cntr=0.3,0.1

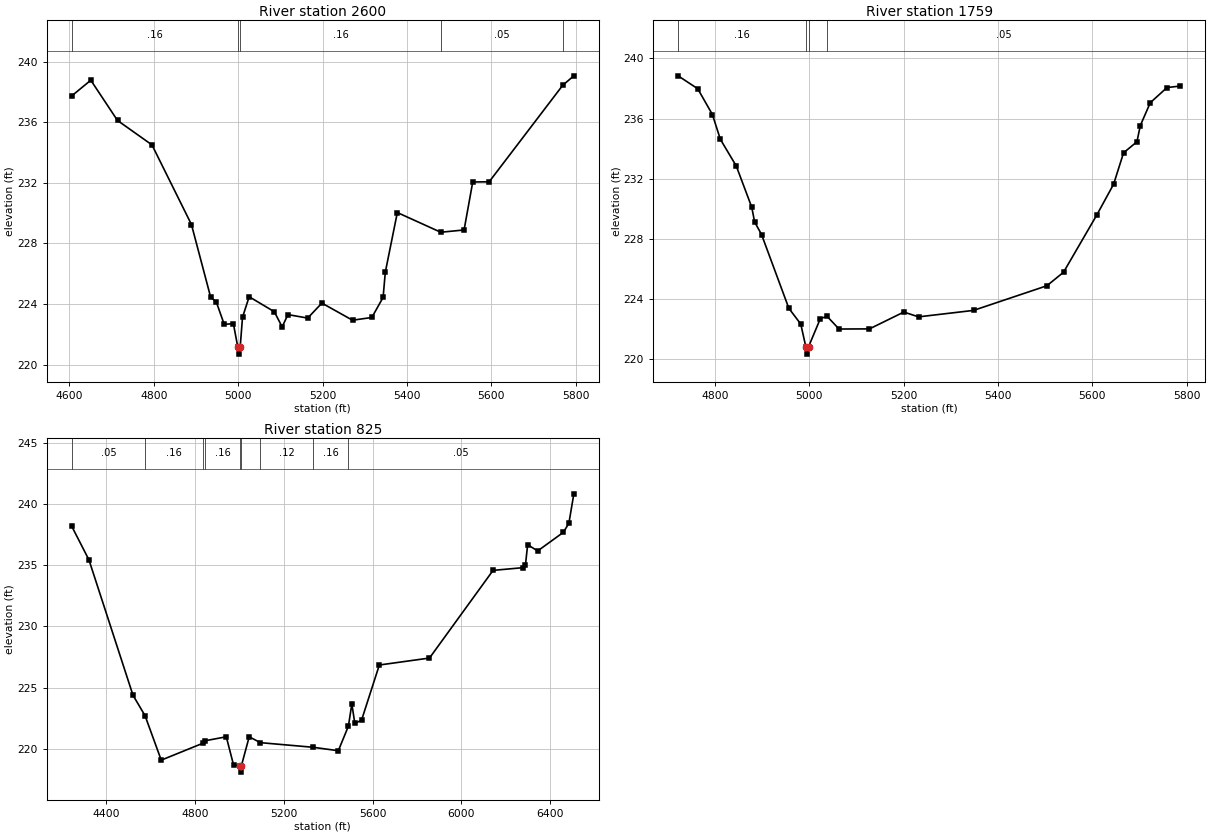
Type RM Length L Ch R = 1,2600,841,841,841
BEGIN DESCRIPTION:
CARTERS CREEK TRIB 13 4.0
END DESCRIPTION:
XS GIS Cut Line= 4
      3585163.11     10206480.49      3584911.89     10206644.07
      3584820.62     10206872.26      3584642.12     10207491.60
#Sta/Elev= 30
  4605.5  237.74  4650.9  238.78  4714.2  236.12  4795.8  234.51  4889.4  229.25
  4935.0  224.44  4948.1  224.15  4967.0  222.66  4988.8  222.70  4999.0  221.19
  5001.7  220.69  5005.0  221.19  5010.4  223.12  5026.2  224.48  5085.8  223.49
  5104.3  222.49  5118.1  223.30  5164.9  223.07  5198.5  224.06  5271.1  222.93
  5316.9  223.11  5343.6  224.44  5348.8  226.10  5377.3  230.04  5480.2  228.74
  5535.5  228.89  5556.0  232.06  5594.9  232.07  5769.4  238.45  5795.6  239.07
#Mann=5,-1,0
  4605.5    0.16       0  4999.0    0.07       0  5005.0    0.16       0
  5480.2    0.05       0  5769.4    0.16       0
Bank Sta=4999,5005
Exp/Cntr=0.3,0.1

Type RM Length L Ch R = 1,1759,934,934,934
BEGIN DESCRIPTION:
CARTERS CREEK TRIB 13 3.0
END DESCRIPTION:
XS GIS Cut Line= 3
      3584942.12     10206441.64      3584367.49     10206606.64
      3584042.08     10206941.67
#Sta/Elev= 30
  4721.7  238.84  4763.3  237.98  4794.5  236.26  4811.2  234.62  4845.0  232.84
  4877.8  230.10  4883.9  229.12  4898.6  228.28  4956.5  223.37  4981.8  222.32
  4992.4  220.82  4995.2  220.32  4998.4  220.82  5023.4  222.69  5037.8  222.83
  5062.9  221.99  5127.5  222.00  5200.3  223.12  5231.5  222.80  5348.1  223.23
  5503.7  224.87  5539.0  225.77  5609.7  229.59  5645.2  231.63  5666.3  233.72
  5694.6  234.45  5701.8  235.53  5722.9  237.05  5758.4  238.06  5786.6  238.16
#Mann=4,-1,0
  4721.7    0.16       0  4992.4    0.07       0  4998.4    0.16       0
  5037.8    0.05       0
Bank Sta=4992.4,4998.4
Exp/Cntr=0.3,0.1

Type RM Length L Ch R = 1,825,0,0,0
BEGIN DESCRIPTION:
CARTERS CREEK TRIB 13 1.0
END DESCRIPTION:
XS GIS Cut Line= 4
      3585042.08     10206241.62      3584706.03     10205893.09
      3584022.47     10206104.73      3583648.74     10207096.21
#Sta/Elev= 30
  4246.4  238.21  4324.2  235.45  4522.3  224.38  4576.8  222.70  4649.4  219.07
  4836.5  220.45  4848.2  220.66  4942.1  220.98  4974.7  218.68  5003.8  218.59
  5006.6  218.09  5009.8  218.59  5045.2  220.98  5095.6  220.50  5333.8  220.12
  5446.1  219.84  5491.5  221.85  5506.9  223.67  5520.5  222.07  5550.7  222.34
  5630.6  226.85  5856.3  227.42  6142.3  234.59  6276.4  234.81  6288.0  235.02
  6297.8  236.69  6343.0  236.18  6458.5  237.70  6483.4  238.44  6505.7  240.85
#Mann=9,-1,0
  4246.4    0.05       0  4576.8    0.16       0  4836.5    0.12       0
  4848.2    0.16       0  5003.8    0.07       0  5009.8    0.16       0
  5095.6    0.12       0  5333.8    0.16       0  5491.5    0.05       0
Bank Sta=5003.8,5009.8
Exp/Cntr=0.3,0.1

Chan Stop Cuts=-1