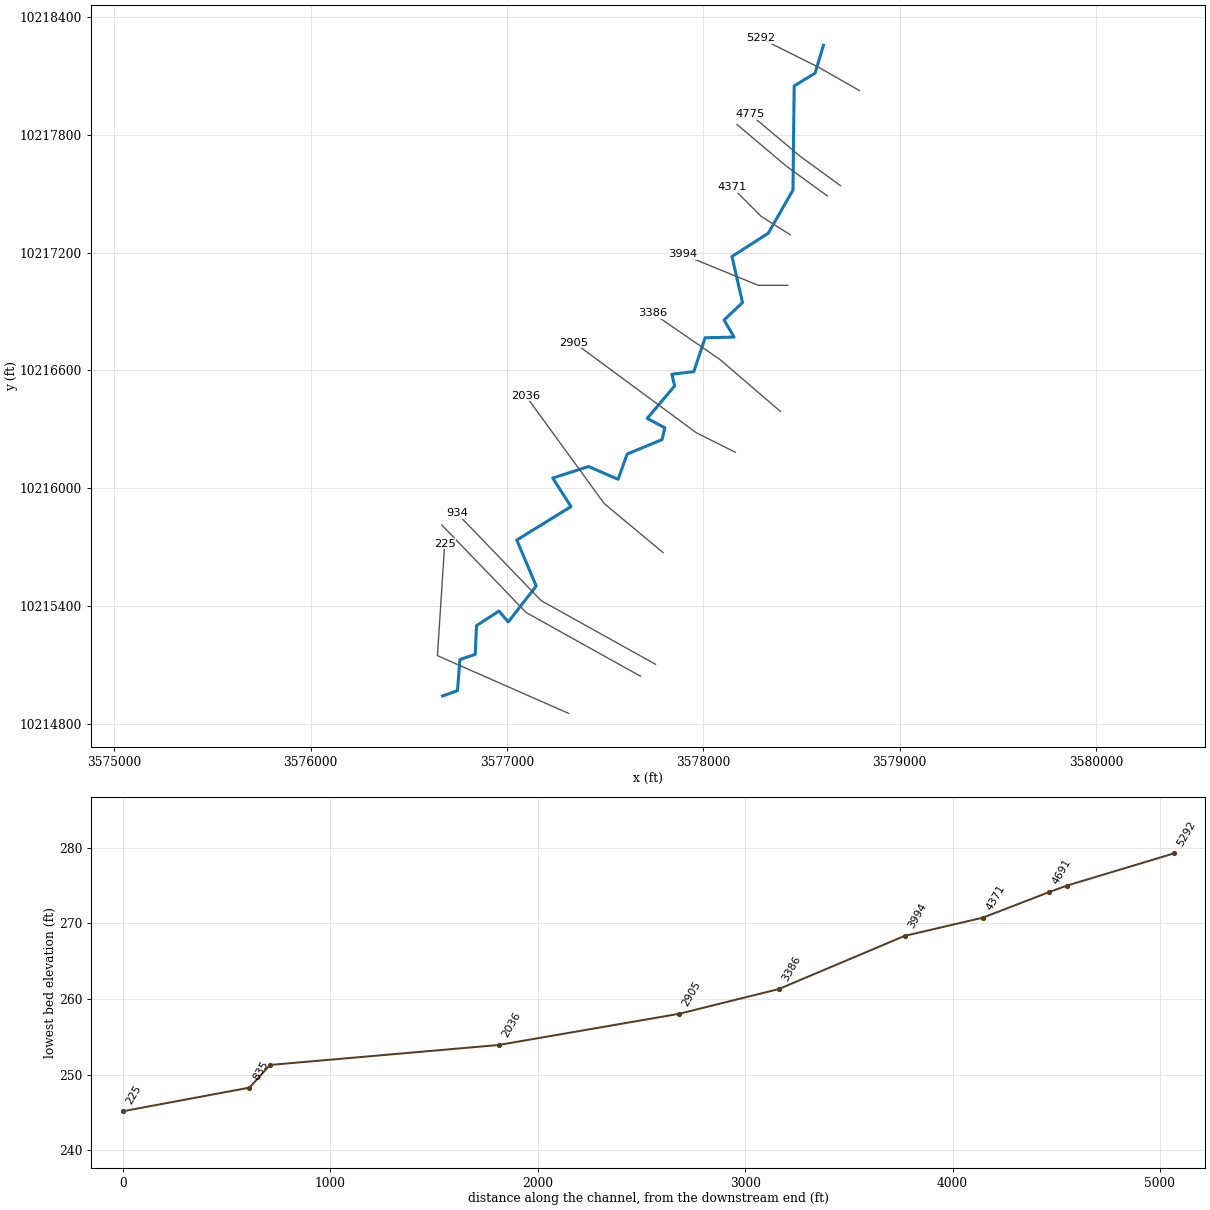
--- CARTERS CREEK TRIB 15 1 1.prj (project) ---

Proj Title=CARTERS CREEK TRIB 15 1 1 Base Level Engineering
Current Plan=p01
Default Exp/Contr=0.3,0.1
English Units
Geom File=g01
Flow File=f01
Plan File=p01
Y Axis Title=Elevation
X Axis Title(PF)=Main Channel Distance
X Axis Title(XS)=Station
BEGIN DESCRIPTION:
CARTERS CREEK TRIB 15 1 1
END DESCRIPTION:
DSS Export Rating Curves= 0
DSS Export Rating Curve Sorted= 0
DSS Export Volume Flow Curves= 0
DXF OffsetX= 0
DXF OffsetY= 0
DXF ScaleX= 1
DXF ScaleY= 10

--- CARTERS CREEK TRIB 15 1 1.p01 (plan) ---

Plan Title=Multiple Run
Short Identifier=Multiple
Geom File=g01
Flow File=f01
Subcritical Flow
K Sum by GR= 0
Std Step Tol= 0.01
Critical Tol= 0.01
Num of Std Step Trials= 20
Max Error Tol= 0.3
Flow Tol Ratio= 0.001
Split Flow NTrial= 30
Split Flow Tol= 0.02
Split Flow Ratio= 0.02
Log Output Level= 0
Friction Slope Method= 1
Unsteady Friction Slope Method= 2
Unsteady Bridges Friction Slope Method= 1
Parabolic Critical Depth
Global Vel Dist=  1 , 1 , 1
Global Log Level= 0
CheckData=True
Encroach Param= -1, 0, 0, 0
BEGIN DESCRIPTION:
Multiple Run
END DESCRIPTION:

--- CARTERS CREEK TRIB 15 1 1.f01 (steady flow) ---

Flow Title=Multiple
Program Version=4.10
Number of Profiles= 7
Profile Names=10-year,25-year,50-year,1pct_min,100-year,1pct_plu,500-year
River Rch & RM=CARTERS CREEK TR,Reach-1         ,5292
     274     352     414     358     484     654     660
Boundary for River Rch & Prof#=CARTERS CREEK TR,Reach-1         , 1
Up Type= 0
Dn Type= 1
Dn Known WS=251.2
Boundary for River Rch & Prof#=CARTERS CREEK TR,Reach-1         , 2
Up Type= 0
Dn Type= 1
Dn Known WS=251.74
Boundary for River Rch & Prof#=CARTERS CREEK TR,Reach-1         , 3
Up Type= 0
Dn Type= 1
Dn Known WS=252.12
Boundary for River Rch & Prof#=CARTERS CREEK TR,Reach-1         , 4
Up Type= 0
Dn Type= 1
Dn Known WS=251.91
Boundary for River Rch & Prof#=CARTERS CREEK TR,Reach-1         , 5
Up Type= 0
Dn Type= 1
Dn Known WS=252.51
Boundary for River Rch & Prof#=CARTERS CREEK TR,Reach-1         , 6
Up Type= 0
Dn Type= 1
Dn Known WS=253.21
Boundary for River Rch & Prof#=CARTERS CREEK TR,Reach-1         , 7
Up Type= 0
Dn Type= 1
Dn Known WS=253.41
DSS Import GetInterval= 0
DSS Import GetPeak= 0
DSS Import FillOption= 0

--- CARTERS CREEK TRIB 15 1 1.g01 (geometry) ---

Geom Title=Existing Conditions
Program Version=4.10

River Reach=CARTERS CREEK TR,Reach-1
Reach XY= 30
      3578612.11     10218256.64      3578569.19     10218114.18
      3578462.86     10218049.07      3578456.79     10217519.11
      3578330.93     10217299.01      3578146.08     10217180.35
      3578199.79     10216946.02      3578105.98     10216856.66
      3578156.47     10216769.79      3578009.16     10216766.37
      3577951.58     10216593.78      3577839.61     10216580.63
      3577854.14     10216521.29      3577714.35     10216355.78
      3577804.11     10216307.64      3577789.68     10216247.42
      3577612.17     10216174.07      3577565.73     10216045.38
      3577415.77     10216110.49      3577232.83     10216051.89
      3577326.14     10215906.28      3577049.67     10215735.92
      3577148.76     10215502.05      3577006.61     10215318.67
      3576959.15     10215374.22      3576844.81     10215300.09
       3576838.2     10215153.72      3576760.25     10215127.34
      3576747.66     10214968.68      3576672.11     10214941.64

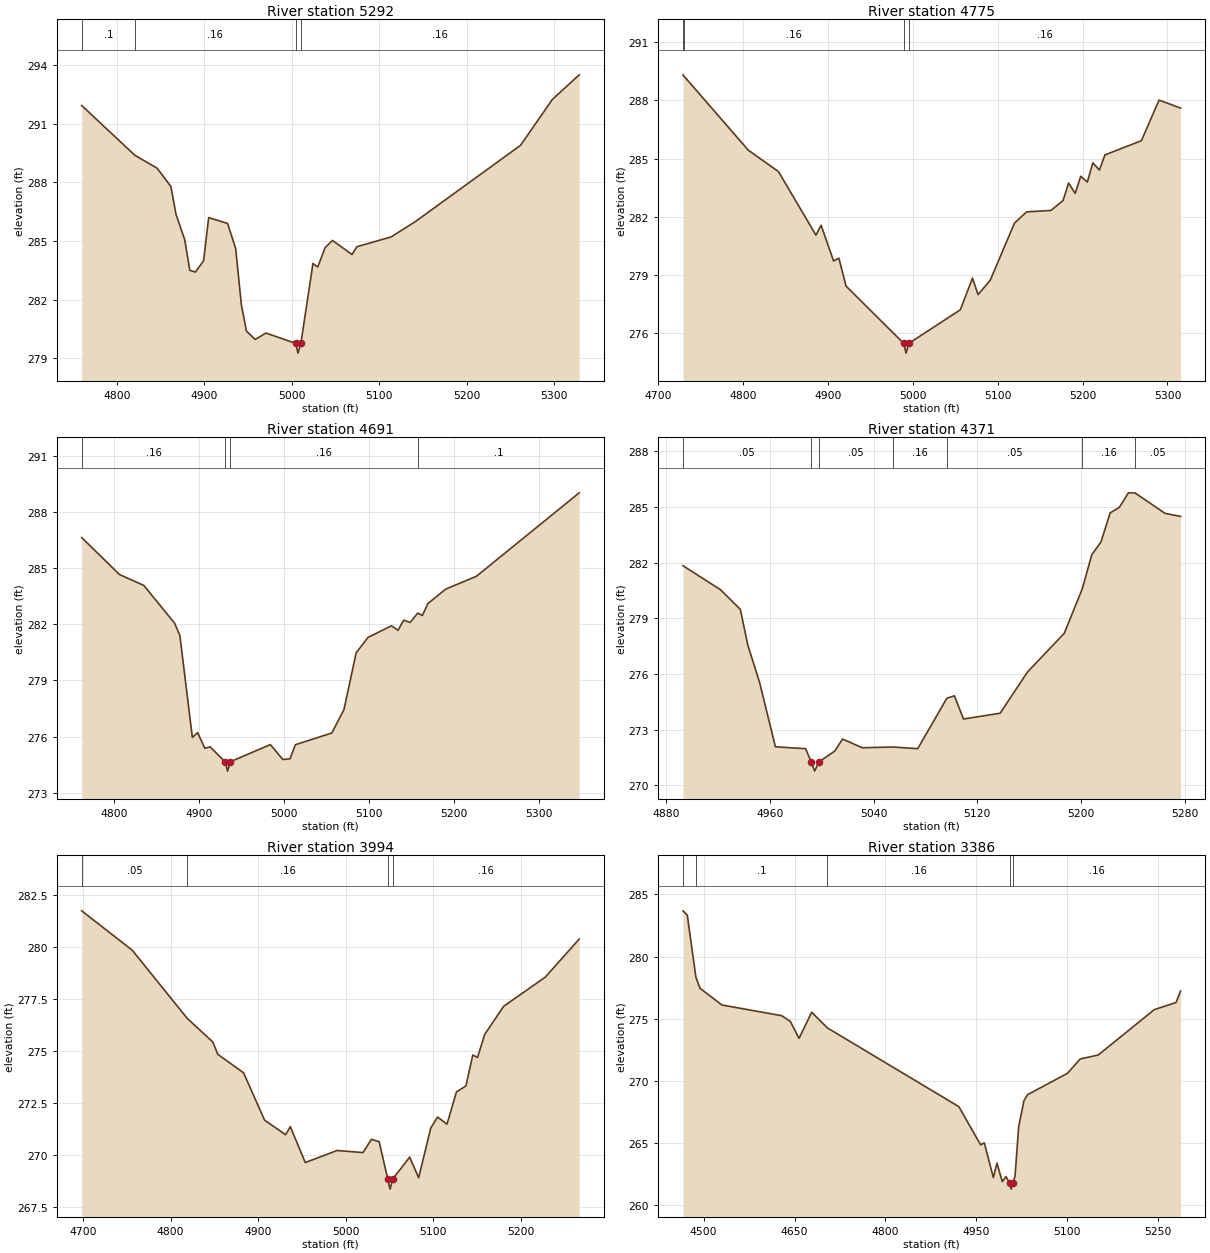
Type RM Length L Ch R = 1 ,5292    ,517,517,517
BEGIN DESCRIPTION:
CARTERS CREEK TRIB 15.1.1 9.0
END DESCRIPTION:
XS GIS Cut Line= 3
      3578795.07     10218025.58      3578592.11     10218141.64
      3578292.12     10218291.64
#Sta/Elev= 30
  4759.5  291.94  4820.4  289.39  4845.8  288.73  4861.6  287.79  4867.4  286.37
  4877.4  285.07  4883.2   283.5  4889.6  283.41    4899  283.99  4904.8   286.2
  4926.4   285.9  4935.7  284.62  4942.2  281.74    4948  280.39    4958  279.96
  4970.3  280.29  5004.3  279.76    5007  279.26  5010.3  279.76  5024.1  283.85
  5029.6  283.67    5038  284.66  5046.4  285.03  5068.8  284.31  5074.4  284.71
  5113.5  285.21  5141.4     286  5261.6   289.9    5298  292.25  5328.7  293.51
#Mann= 4 ,-1 , 0
  4759.5      .1       0  4820.4     .16       0  5004.3     .07       0
  5010.3     .16       0
Bank Sta=5004.3,5010.3
XS Rating Curve= 0 ,0
Exp/Cntr=0.3,0.1

Type RM Length L Ch R = 1 ,4775    ,84,84,84
BEGIN DESCRIPTION:
CARTERS CREEK TRIB 15.1.1 8.1
END DESCRIPTION:
XS GIS Cut Line= 3
      3578698.96     10217541.08      3578492.11     10217691.64
      3578239.55     10217904.43
#Sta/Elev= 30
  4729.3  289.31  4729.9  289.27  4806.3  285.43  4841.8  284.33  4885.9  281.06
    4892  281.57  4906.7  279.73  4912.9  279.88  4921.4  278.44  4989.3  275.49
  4992.1  274.99  4995.3  275.49    5056  277.22  5070.3  278.85  5076.9     278
  5091.2  278.74  5119.8  281.68  5134.1  282.26  5162.7  282.33    5177  282.84
  5183.5  283.74  5191.3  283.21  5197.8  284.09  5205.6  283.79  5212.1  284.78
  5219.8  284.41  5226.4  285.19  5269.3  285.92  5290.1  288.01  5315.4   287.6
#Mann= 4 ,-1 , 0
  4729.3     .05       0  4729.9     .16       0  4989.3     .07       0
  4995.3     .16       0
Bank Sta=4989.3,4995.3
XS Rating Curve= 0 ,0
Exp/Cntr=0.3,0.1

Type RM Length L Ch R = 1 ,4691    ,320,320,320
BEGIN DESCRIPTION:
CARTERS CREEK TRIB 15.1.1 8.0
END DESCRIPTION:
XS GIS Cut Line= 3
      3578631.26     10217488.99       3578424.4     10217639.56
      3578171.84     10217852.35
#Sta/Elev= 30
  4761.6  286.64  4806.2  284.66  4834.8  284.08  4871.1  282.06  4877.3   281.4
    4892  275.95  4898.2  276.21  4906.7  275.37  4912.8  275.45  4930.7  274.65
  4933.5  274.15  4936.7  274.65  4983.9  275.57  4998.6  274.77  5007.1  274.81
  5013.3  275.56  5056.3  276.19  5070.6  277.44  5084.9  280.47  5098.9   281.3
  5126.6  281.92  5134.3  281.68  5140.9  282.22  5148.6   282.1  5157.5   282.6
  5162.9  282.47  5169.5  283.11  5190.4  283.88  5226.7  284.57  5347.7  289.03
#Mann= 4 ,-1 , 0
  4761.6     .16       0  4930.7     .07       0  4936.7     .16       0
  5157.5      .1       0
Bank Sta=4930.7,4936.7
XS Rating Curve= 0 ,0
Exp/Cntr=0.3,0.1

Type RM Length L Ch R = 1 ,4371    ,377,377,377
BEGIN DESCRIPTION:
CARTERS CREEK TRIB 15.1.1 7.0
END DESCRIPTION:
XS GIS Cut Line= 3
      3578442.14     10217291.62      3578296.28     10217383.54
      3578146.73     10217533.09
#Sta/Elev= 30
  4892.9  281.83  4921.8  280.54  4937.1  279.48    4943  277.53    4952  275.54
  4964.2  272.07  4987.5  271.97  4991.8  271.26  4994.5  270.76  4997.8  271.26
    5010  271.84    5016  272.49  5031.2  272.02  5055.1  272.06    5074  271.97
  5096.5  274.69  5102.3  274.82  5109.3  273.57  5137.6  273.88  5158.8  276.11
  5187.1  278.19    5201  280.59  5208.3  282.42  5215.4  283.11  5222.5  284.68
  5229.5  284.97  5236.6  285.76  5241.8  285.75  5264.9  284.65  5276.8  284.49
#Mann= 7 ,-1 , 0
  4892.9     .05       0  4991.8     .04       0  4997.8     .05       0
  5055.1     .16       0  5096.5     .05       0    5201     .16       0
  5241.8     .05       0
Bank Sta=4991.8,4997.8
XS Rating Curve= 0 ,0
Exp/Cntr=0.3,0.1

Type RM Length L Ch R = 1 ,3994    ,608,608,608
BEGIN DESCRIPTION:
CARTERS CREEK TRIB 15.1.1 6.0
END DESCRIPTION:
XS GIS Cut Line= 3
      3578429.85     10217033.54      3578279.82     10217033.54
      3577892.15     10217191.63
#Sta/Elev= 30
  4698.3  281.75    4756  279.86  4818.8  276.58  4848.3  275.43  4853.9  274.84
  4883.4  273.95  4907.4  271.67  4931.4  270.97  4936.8  271.36  4953.9  269.63
  4990.3  270.21  5019.8  270.11  5029.5  270.75  5038.4  270.63  5048.1  268.85
  5050.8  268.35  5054.1  268.85  5073.2  269.89  5083.5   268.9  5097.3  271.29
  5105.1  271.82  5115.9  271.48  5126.7  273.03  5137.5  273.32  5145.4  274.81
  5150.8  274.69    5159   275.8  5180.6  277.15  5228.3  278.56    5267  280.39
#Mann= 4 ,-1 , 0
  4698.3     .05       0  4818.8     .16       0  5048.1     .07       0
  5054.1     .16       0
Bank Sta=5048.1,5054.1
XS Rating Curve= 0 ,0
Exp/Cntr=0.3,0.1

Type RM Length L Ch R = 1 ,3386    ,481,481,481
BEGIN DESCRIPTION:
CARTERS CREEK TRIB 15.1.1 5.0
END DESCRIPTION:
XS GIS Cut Line= 3
      3578392.11     10216391.64      3578084.98     10216655.53
      3577742.14     10216891.62
#Sta/Elev= 30
  4465.9  283.68    4473  283.33  4487.2  278.34  4493.9  277.46  4530.1  276.11
  4628.9  275.25  4643.1  274.79  4657.4  273.43  4678.3  275.53  4704.2  274.27
  4921.2  267.94  4957.1  264.87  4963.2  265.03  4978.1  262.24  4984.1   263.4
  4992.9  261.91    4999  262.32  5004.8  261.81  5007.6  261.31  5010.8  261.81
  5013.9  262.34    5020  266.35  5028.8  268.44  5034.9  268.91  5100.5  270.62
  5121.4  271.77  5151.2  272.09  5243.8  275.74  5279.7  276.31  5287.1  277.23
#Mann= 5 ,-1 , 0
  4465.9     .05       0  4487.2      .1       0  4704.2     .16       0
  5004.8     .07       0  5010.8     .16       0
Bank Sta=5004.8,5010.8
XS Rating Curve= 0 ,0
Exp/Cntr=0.3,0.1

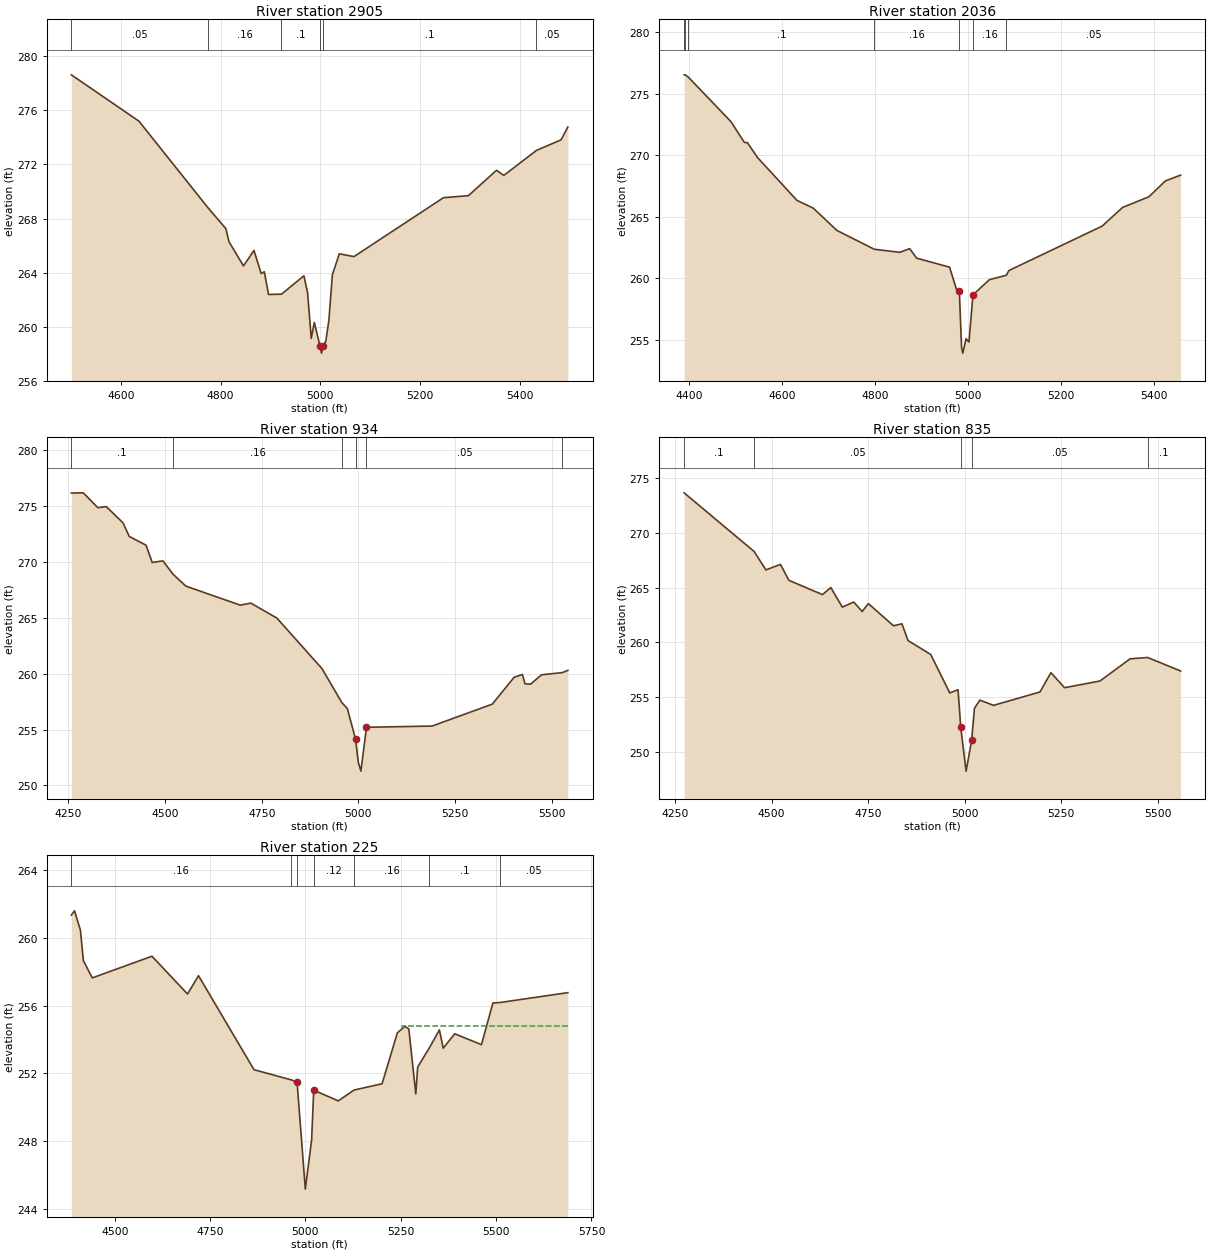
Type RM Length L Ch R = 1 ,2905    ,869,869,869
BEGIN DESCRIPTION:
CARTERS CREEK TRIB 15.1.1 4.0
END DESCRIPTION:
XS GIS Cut Line= 3
       3578163.4     10216183.14      3577963.36     10216283.16
      3577342.08     10216741.66
#Sta/Elev= 30
  4500.6  278.63  4636.2   275.2  4775.2  268.77  4810.5  267.25  4816.7  266.28
  4845.9  264.49  4866.8  265.64  4881.4  263.92  4887.6  264.06  4896.1  262.38
    4922   262.4    4967  263.76  4974.4  262.51  4981.7  259.13  4987.9  260.31
  4999.5  258.54  5002.3  258.04  5005.5  258.54  5010.9  258.92  5017.1  260.47
  5024.1  263.84    5038  265.39  5067.3  265.18  5246.9  269.54    5297  269.69
  5353.3  271.57    5368  271.19  5433.5  273.04  5482.8  273.82  5496.4  274.77
#Mann= 6 ,-1 , 0
  4500.6     .05       0  4775.2     .16       0    4922      .1       0
  4999.5     .07       0  5005.5      .1       0  5433.5     .05       0
Bank Sta=4999.5,5005.5
XS Rating Curve= 0 ,0
Exp/Cntr=0.3,0.1

Type RM Length L Ch R = 1 ,2036    ,1102,1102,1102
BEGIN DESCRIPTION:
CARTERS CREEK TRIB 15.1.1 3.0
END DESCRIPTION:
XS GIS Cut Line= 3
      3577794.86     10215672.07      3577494.85     10215922.08
      3577095.97     10216470.54
#Sta/Elev= 30
  4388.6  276.53  4391.4  276.53    4398  276.33  4489.6  272.72  4518.3  271.04
  4524.8  271.02  4546.9   269.8  4631.5  266.33  4666.7   265.7  4717.4  263.89
  4797.9  262.36  4852.8  262.11  4874.3  262.41    4889  261.64  4960.1   260.9
  4974.8  259.11    4981  258.99  4985.8  254.42  4988.5  253.92  4995.6  255.09
  5001.8  254.82  5010.3  258.65  5045.9  259.89  5082.4  260.25  5087.7  260.63
  5288.5  264.24  5332.6  265.76    5389  266.62  5424.6  267.91  5457.3  268.38
#Mann= 7 ,-1 , 0
  4388.6      .1       0  4391.4     .16       0    4398      .1       0
  4797.9     .16       0    4981     .07       0  5010.3     .16       0
  5082.4     .05       0
Bank Sta=4981,5010.3
XS Rating Curve= 0 ,0
Exp/Cntr=0.3,0.1

Type RM Length L Ch R = 1 ,934     ,99,99,99
BEGIN DESCRIPTION:
CARTERS CREEK TRIB 15.1.1 2.1
END DESCRIPTION:
XS GIS Cut Line= 3
      3577756.43     10215103.03      3577173.98     10215427.36
      3576745.76     10215871.62
#Sta/Elev= 30
  4257.8  276.14  4288.6  276.16  4326.3  274.83    4348  274.93  4391.5  273.47
  4407.5  272.26  4450.9  271.48  4466.9  269.93  4494.4  270.08  4520.8  268.88
  4553.8  267.82  4694.4  266.12  4721.9   266.3  4789.3  264.96  4905.9  260.44
  4957.1  257.41  4971.4  256.87  4992.5  254.15  4999.7  252.08  5006.4  251.28
  5020.8   255.2  5190.5  255.31  5346.2  257.27  5402.6  259.67  5423.9  259.92
  5430.8  259.09    5445  259.05  5473.3  259.89  5527.5  260.09  5541.5  260.29
#Mann= 6 ,-1 , 0
  4257.8      .1       0  4520.8     .16       0  4957.1     .05       0
  4992.5     .04       0  5020.8     .05       0  5527.5      .1       0
Bank Sta=4992.5,5020.8
XS Rating Curve= 0 ,0
Exp/Cntr=0.3,0.1

Type RM Length L Ch R = 1 ,835     ,610,610,610
BEGIN DESCRIPTION:
CARTERS CREEK TRIB 15.1.1 2.0
END DESCRIPTION:
XS GIS Cut Line= 3
      3577680.07     10215042.31      3577097.54     10215366.68
      3576667.93     10215812.39
#Sta/Elev= 30
  4273.2  273.63  4454.5  268.29  4485.1  266.61  4522.7  267.11  4544.6  265.66
  4631.5  264.36  4653.2     265  4682.9  263.22  4712.6  263.68  4734.4  262.82
  4750.4  263.54  4815.5  261.52  4837.3   261.7  4853.3  260.17  4911.8  258.91
  4961.3   255.4  4982.7   255.7  4989.6  252.28  5003.5  248.28  5017.9   251.1
  5025.1  254.01  5039.3  254.75  5074.5  254.27  5194.9  255.49  5223.2  257.25
  5258.5  255.88  5350.3  256.49  5428.3  258.51  5473.8  258.63    5559   257.4
#Mann= 5 ,-1 , 0
  4273.2      .1       0  4454.5     .05       0  4989.6     .04       0
  5017.9     .05       0  5473.8      .1       0
Bank Sta=4989.6,5017.9
XS Rating Curve= 0 ,0
Exp/Cntr=0.3,0.1

Type RM Length L Ch R = 1 ,225     ,0,0,0
BEGIN DESCRIPTION:
CARTERS CREEK TRIB 15.1.1 1.0
END DESCRIPTION:
XS GIS Cut Line= 3
      3577313.77     10214853.01      3576645.71       10215147.
      3576682.66     10215717.71
#Sta/Elev= 30
  4386.3  261.34  4394.5  261.59    4410  260.46  4417.8  258.65  4441.1  257.63
  4597.6  258.91  4690.9  256.68  4719.7  257.76  4865.2  252.21  4962.9  251.61
  4978.1  251.48  4999.7  245.16  5016.2  248.06  5021.8     251  5086.2  250.37
  5127.5  251.01    5201  251.38  5241.1  254.39  5261.1  254.77  5271.2  254.61
  5289.4  250.78  5294.4  252.37    5325   253.5  5351.3  254.56  5361.3  253.48
  5391.4  254.33  5461.6  253.69  5491.6  256.15  5511.1  256.18  5688.1  256.76
#Mann= 7 ,-1 , 0
  4386.3     .16       0  4962.9     .12       0  4978.1     .07       0
  5021.8     .12       0  5127.5     .16       0    5325      .1       0
  5511.1     .05       0
#XS Ineff= 2 , 0
                         5254.49          254.81
Permanent Ineff=
       F       F
Bank Sta=4978.1,5021.8
XS Rating Curve= 0 ,0
Exp/Cntr=0.3,0.1

Chan Stop Cuts=-1
Use User Specified Reach Order=0
Composite Channel Slope=5