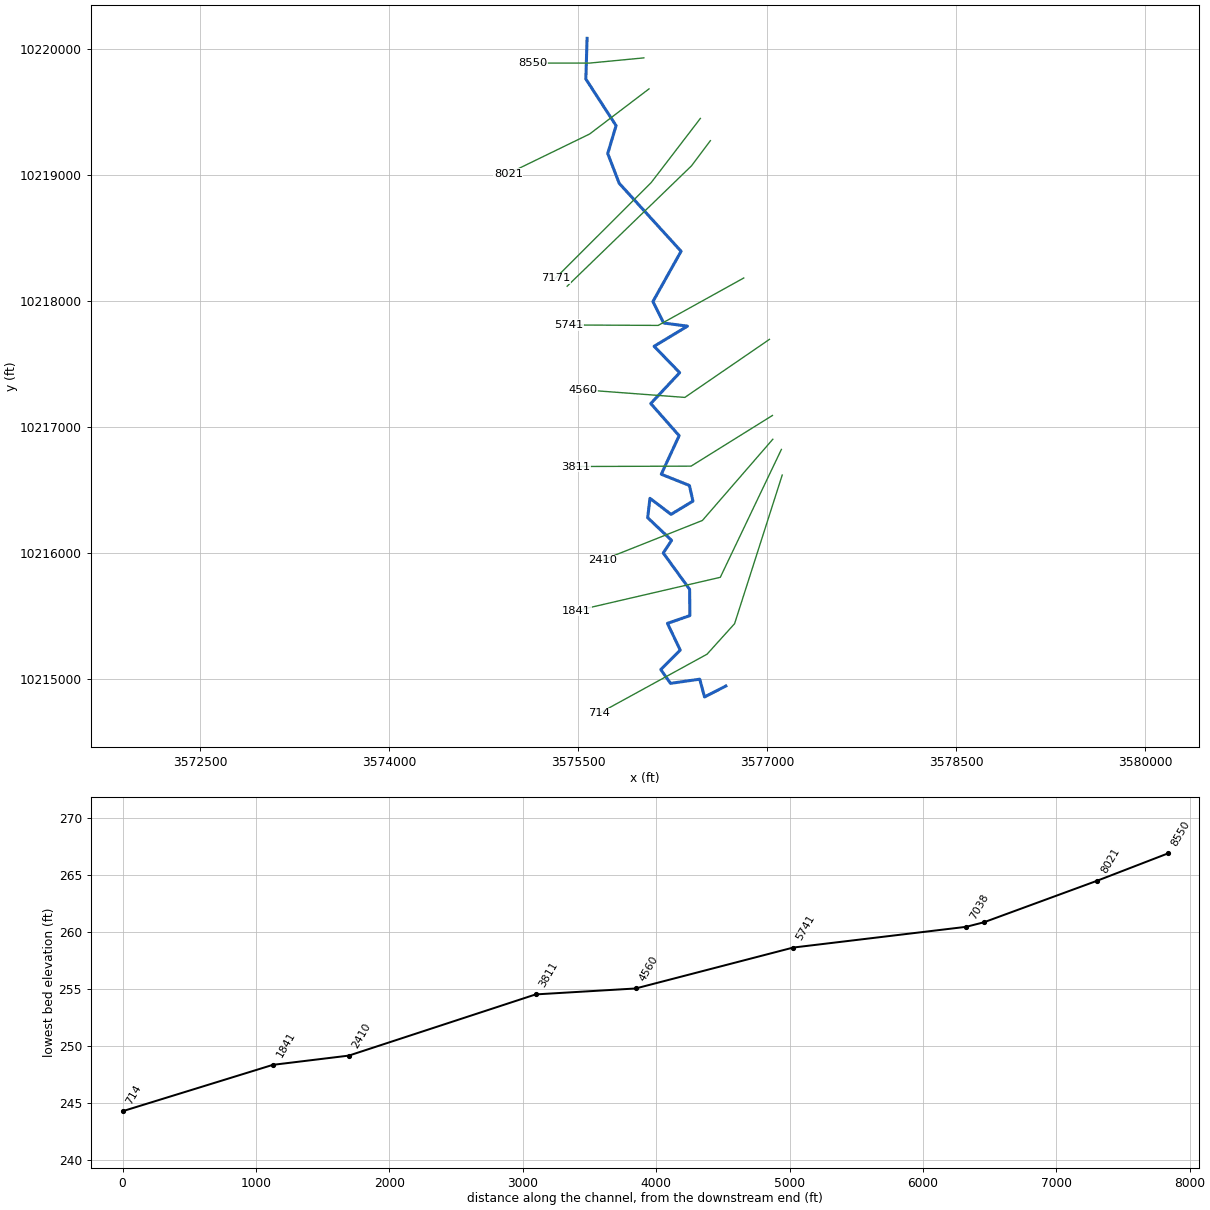
--- CARTERS CREEK TRIB 15 1.prj (project) ---

Proj Title=CARTERS CREEK TRIB 15 1 Base Level Engineering
Current Plan=p01
Default Exp/Contr=0.3,0.1
English Units
Geom File=g01
Flow File=f01
Plan File=p01
Y Axis Title=Elevation
X Axis Title(PF)=Main Channel Distance
X Axis Title(XS)=Station
BEGIN DESCRIPTION:
CARTERS CREEK TRIB 15 1
END DESCRIPTION:
DSS Export Rating Curves= 0
DSS Export Rating Curve Sorted= 0
DSS Export Volume Flow Curves= 0
DXF OffsetX= 0
DXF OffsetY= 0
DXF ScaleX= 1
DXF ScaleY= 10

--- CARTERS CREEK TRIB 15 1.p01 (plan) ---

Plan Title=Multiple Run
Short Identifier=Multiple
Geom File=g01
Flow File=f01
Subcritical Flow
K Sum by GR= 0
Std Step Tol= 0.01
Critical Tol= 0.01
Num of Std Step Trials= 20
Max Error Tol= 0.3
Flow Tol Ratio= 0.001
Split Flow NTrial= 30
Split Flow Tol= 0.02
Split Flow Ratio= 0.02
Log Output Level= 0
Friction Slope Method= 1
Unsteady Friction Slope Method= 2
Unsteady Bridges Friction Slope Method= 1
Parabolic Critical Depth
Global Vel Dist=  1 , 1 , 1
Global Log Level= 0
CheckData=True
Encroach Param= -1, 0, 0, 0
BEGIN DESCRIPTION:
Multiple Run
END DESCRIPTION:

--- CARTERS CREEK TRIB 15 1.f01 (steady flow) ---

Flow Title=Multiple
Program Version=4.10
Number of Profiles= 7
Profile Names=10-year,25-year,50-year,1pct_min,100-year,1pct_plu,500-year
River Rch & RM=CARTERS CREEK TR,Reach-1         ,8550
     462     613     734     645     872    1179    1232
River Rch & RM=CARTERS CREEK TR,Reach-1         ,7038
     625     842    1018     901    1219    1648    1752
Boundary for River Rch & Prof#=CARTERS CREEK TR,Reach-1         , 1
Up Type= 0
Dn Type= 1
Dn Known WS=251.2
Boundary for River Rch & Prof#=CARTERS CREEK TR,Reach-1         , 2
Up Type= 0
Dn Type= 1
Dn Known WS=251.74
Boundary for River Rch & Prof#=CARTERS CREEK TR,Reach-1         , 3
Up Type= 0
Dn Type= 1
Dn Known WS=252.12
Boundary for River Rch & Prof#=CARTERS CREEK TR,Reach-1         , 4
Up Type= 0
Dn Type= 1
Dn Known WS=251.91
Boundary for River Rch & Prof#=CARTERS CREEK TR,Reach-1         , 5
Up Type= 0
Dn Type= 1
Dn Known WS=252.51
Boundary for River Rch & Prof#=CARTERS CREEK TR,Reach-1         , 6
Up Type= 0
Dn Type= 1
Dn Known WS=253.21
Boundary for River Rch & Prof#=CARTERS CREEK TR,Reach-1         , 7
Up Type= 0
Dn Type= 1
Dn Known WS=253.41
DSS Import GetInterval= 0
DSS Import GetPeak= 0
DSS Import FillOption= 0

--- CARTERS CREEK TRIB 15 1.g01 (geometry) ---

Geom Title=Existing Conditions

River Reach=CARTERS CREEK TR,Reach-1
Reach XY= 30
      3575570.92     10220088.21      3575561.32     10219764.64
      3575801.11     10219394.35      3575734.96     10219173.00
      3575825.94     10218936.16      3576316.88     10218396.28
      3576093.48     10217996.63      3576179.01     10217826.15
      3576367.38     10217801.21      3576102.91     10217641.18
      3576305.88     10217431.55      3576076.46     10217186.30
      3576301.52     10216930.93      3576159.83     10216624.55
      3576383.13     10216535.33      3576411.01     10216411.02
      3576237.46     10216305.69      3576070.03     10216433.24
      3576051.82     10216279.20      3576241.56     10216099.22
      3576175.59     10215998.52      3576384.62     10215710.33
      3576386.70     10215501.30      3576208.92     10215439.49
      3576310.27     10215226.88      3576156.04     10215072.46
      3576232.83     10214962.88      3576464.93     10214996.06
      3576503.15     10214854.93      3576672.11     10214941.64

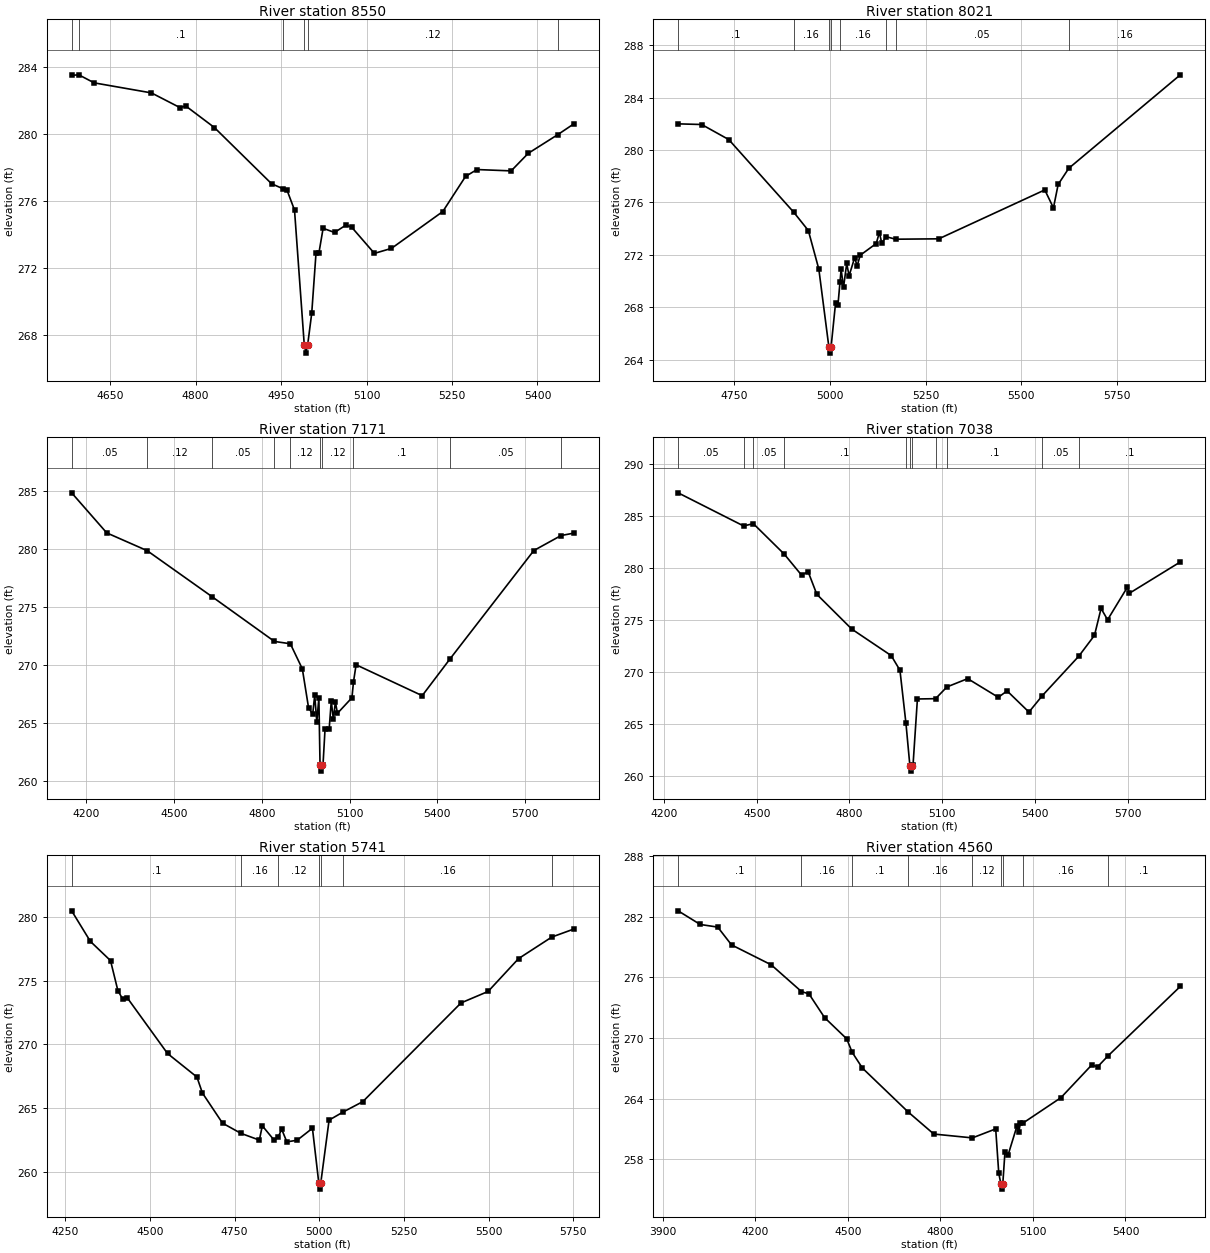
Type RM Length L Ch R = 1,8550,529,529,529
BEGIN DESCRIPTION:
CARTERS CREEK TRIB 15.1 13.0
END DESCRIPTION:
XS GIS Cut Line= 3
      3576021.43     10219932.94      3575592.11     10219891.64
      3575142.11     10219891.64
#Sta/Elev= 30
  4582.5  283.49  4595.1  283.52  4622.0  283.04  4722.5  282.44  4772.7  281.56
  4782.7  281.66  4833.0  280.37  4933.4  277.01  4953.7  276.71  4960.1  276.66
  4973.6  275.44  4990.7  267.39  4993.5  266.89  4996.7  267.39  5003.8  269.27
  5011.3  272.85  5016.3  272.85  5023.8  274.35  5043.8  274.10  5063.8  274.54
  5073.8  274.42  5113.8  272.85  5143.8  273.15  5233.8  275.35  5273.8  277.45
  5293.8  277.86  5353.8  277.78  5383.8  278.83  5435.8  279.95  5463.8  280.59
#Mann=6,-1,0
  4582.5    0.05       0  4595.1     0.1       0  4953.7    0.12       0
  4990.7    0.07       0  4996.7    0.12       0  5435.8    0.16       0
Bank Sta=4990.7,4996.7
Exp/Cntr=0.3,0.1

Type RM Length L Ch R = 1,8021,850,850,850
BEGIN DESCRIPTION:
CARTERS CREEK TRIB 15.1 12.0
END DESCRIPTION:
XS GIS Cut Line= 3
      3576062.48     10219686.56      3575591.64     10219328.22
      3574945.55     10219013.63
#Sta/Elev= 30
  4604.5  281.99  4666.0  281.94  4736.7  280.79  4906.4  275.24  4944.3  273.85
  4971.7  270.90  4997.7  265.00  5000.5  264.50  5003.7  265.00  5015.3  268.32
  5021.6  268.19  5026.9  269.93  5029.8  270.88  5036.1  269.52  5044.4  271.34
  5050.6  270.40  5065.2  271.79  5071.5  271.15  5079.7  271.97  5121.4  272.86
  5129.6  273.70  5135.9  272.89  5147.3  273.38  5172.2  273.19  5284.7  273.22
  5561.2  276.95  5583.8  275.58  5596.1  277.37  5623.8  278.60  5914.8  285.73
#Mann=8,-1,0
  4604.5     0.1       0  4906.4    0.16       0  4997.7    0.07       0
  5003.7    0.16       0  5026.9    0.16       0  5147.3    0.12       0
  5172.2    0.05       0  5623.8    0.16       0
Bank Sta=4997.7,5003.7
Exp/Cntr=0.3,0.1

Type RM Length L Ch R = 1,7171,133,133,133
BEGIN DESCRIPTION:
CARTERS CREEK TRIB 15.1 10.0
END DESCRIPTION:
XS GIS Cut Line= 3
      3576469.99     10219451.94      3576079.39     10218941.55
      3575318.97     10218181.13
#Sta/Elev= 30
  4149.4  284.82  4269.4  281.37  4407.6  279.84  4630.0  275.87  4843.2  272.02
  4897.6  271.82  4938.6  269.66  4959.8  266.33  4974.0  265.74  4981.0  267.40
  4988.1  265.07  4995.2  267.18  4999.2  261.35  5002.0  260.85  5005.2  261.35
  5009.3  261.37  5016.4  264.51  5030.5  264.49  5037.6  266.88  5044.7  265.33
  5051.7  266.80  5058.8  265.83  5108.3  267.17  5113.6  268.53  5122.5  270.01
  5348.7  267.35  5442.5  270.47  5730.6  279.85  5823.7  281.14  5867.5  281.35
#Mann=10,-1,0
  4149.4    0.05       0  4407.6    0.12       0  4630.0    0.05       0
  4843.2     0.1       0  4897.6    0.12       0  4999.2    0.07       0
  5005.2    0.12       0  5113.6     0.1       0  5442.5    0.05       0
  5823.7     0.1       0
Bank Sta=4999.2,5005.2
Exp/Cntr=0.3,0.1

Type RM Length L Ch R = 1,7038,1297,1297,1297
BEGIN DESCRIPTION:
CARTERS CREEK TRIB 15.1 9.0
END DESCRIPTION:
XS GIS Cut Line= 3
      3576549.56     10219275.10      3576399.59     10219075.13
      3575412.71     10218118.62
#Sta/Elev= 30
  4245.7  287.26  4457.4  284.07  4489.0  284.29  4588.8  281.36  4645.0  279.33
  4666.1  279.67  4694.4  277.48  4807.5  274.13  4934.9  271.58  4963.2  270.17
  4982.6  265.06  4995.4  260.95  4998.2  260.45  5001.4  260.95  5005.6  261.07
  5019.7  267.40  5078.4  267.43  5115.1  268.56  5182.3  269.36  5281.4  267.56
  5309.7  268.18  5380.4  266.14  5423.7  267.72  5541.6  271.52  5592.4  273.53
  5613.7  276.12  5634.8  275.03  5698.6  278.16  5705.6  277.59  5870.0  280.60
#Mann=11,-1,0
  4245.7    0.05       0  4457.4     0.1       0  4489.0    0.05       0
  4588.8     0.1       0  4982.6    0.12       0  4995.4    0.07       0
  5001.4    0.12       0  5078.4    0.16       0  5115.1     0.1       0
  5423.7    0.05       0  5541.6     0.1       0
Bank Sta=4995.4,5001.4
Exp/Cntr=0.3,0.1

Type RM Length L Ch R = 1,5741,1181,1181,1181
BEGIN DESCRIPTION:
CARTERS CREEK TRIB 15.1 7.0
END DESCRIPTION:
XS GIS Cut Line= 3
      3576814.51     10218184.02      3576135.11     10217807.14
      3575428.95     10217810.60
#Sta/Elev= 30
  4268.6  280.48  4323.9  278.08  4383.4  276.57  4405.2  274.21  4420.0  273.52
  4432.6  273.66  4551.7  269.28  4638.6  267.43  4654.7  266.18  4714.2  263.81
  4768.5  263.01  4822.9  262.48  4831.7  263.60  4866.4  262.48  4879.0  262.75
  4888.9  263.33  4904.1  262.34  4934.6  262.47  4979.7  263.41  4998.4  259.13
  5001.2  258.63  5004.4  259.13  5028.9  264.05  5070.7  264.69  5128.5  265.50
  5418.5  273.25  5498.5  274.15  5588.5  276.73  5686.6  278.42  5751.7  279.05
#Mann=7,-1,0
  4268.6     0.1       0  4768.5    0.16       0  4879.0    0.12       0
  4998.4    0.07       0  5004.4    0.12       0  5070.7    0.16       0
  5686.6     0.1       0
Bank Sta=4998.4,5004.4
Exp/Cntr=0.3,0.1

Type RM Length L Ch R = 1,4560,749,749,749
BEGIN DESCRIPTION:
CARTERS CREEK TRIB 15.1 6.0
END DESCRIPTION:
XS GIS Cut Line= 3
      3577017.91     10217695.98      3576346.81     10217235.02
      3575535.25     10217295.89
#Sta/Elev= 30
  3949.8  282.58  4021.4  281.23  4078.2  280.97  4122.9  279.21  4251.5  277.24
  4349.7  274.59  4374.0  274.36  4424.7  272.01  4496.4  269.91  4514.0  268.58
  4547.2  267.02  4695.0  262.69  4778.7  260.49  4903.8  260.11  4979.3  261.00
  4989.3  256.61  4996.3  255.54  4999.1  255.04  5002.3  255.54  5009.3  258.69
  5019.4  258.41  5048.7  261.32  5053.8  260.65  5059.5  261.58  5068.9  261.60
  5190.8  264.09  5290.1  267.31  5310.2  267.16  5342.6  268.20  5577.8  275.10
#Mann=9,-1,0
  3949.8     0.1       0  4349.7    0.16       0  4514.0     0.1       0
  4695.0    0.16       0  4903.8    0.12       0  4996.3    0.07       0
  5002.3    0.12       0  5068.9    0.16       0  5342.6     0.1       0
Bank Sta=4996.3,5002.3
Exp/Cntr=0.3,0.1

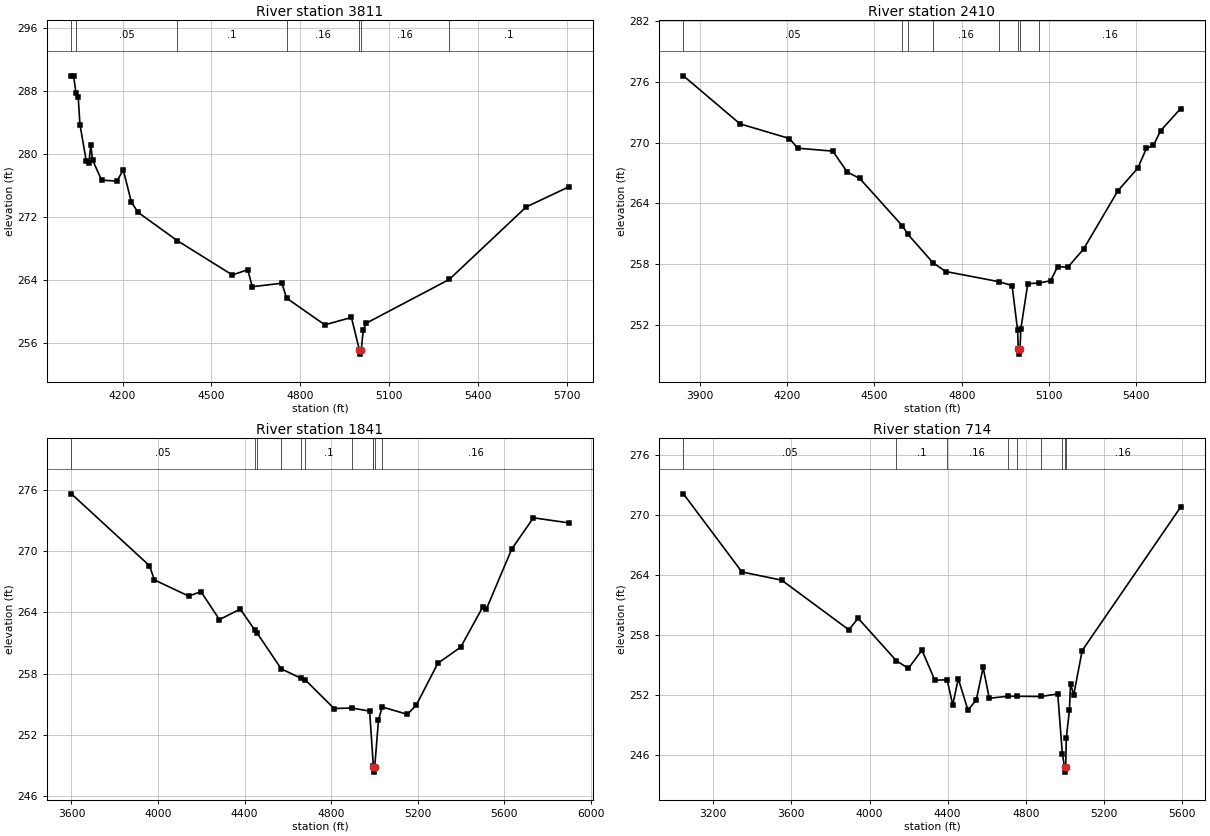
Type RM Length L Ch R = 1,3811,1401,1401,1401
BEGIN DESCRIPTION:
CARTERS CREEK TRIB 15.1 4.0
END DESCRIPTION:
XS GIS Cut Line= 3
      3577042.09     10217091.63      3576396.27     10216688.92
      3575479.17     10216685.95
#Sta/Elev= 30
  4027.3  289.95  4035.0  289.88  4042.6  287.79  4050.3  287.21  4056.2  283.75
  4077.4  279.13  4086.2  278.84  4092.8  281.13  4098.7  279.23  4129.3  276.67
  4180.5  276.55  4202.5  277.95  4229.6  273.90  4251.2  272.60  4384.5  268.97
  4570.6  264.60  4622.5  265.26  4637.9  263.10  4738.1  263.55  4753.4  261.66
  4882.6  258.25  4972.6  259.19  4999.6  255.02  5002.3  254.52  5005.6  255.02
  5012.6  257.59  5022.6  258.46  5302.8  264.03  5562.6  273.26  5705.5  275.80
#Mann=7,-1,0
  4027.3    0.08       0  4042.6    0.05       0  4384.5     0.1       0
  4753.4    0.16       0  4999.6    0.07       0  5005.6    0.16       0
  5302.8     0.1       0
Bank Sta=4999.6,5005.6
Exp/Cntr=0.3,0.1

Type RM Length L Ch R = 1,2410,569,569,569
BEGIN DESCRIPTION:
CARTERS CREEK TRIB 15.1 3.0
END DESCRIPTION:
XS GIS Cut Line= 3
      3577044.98     10216902.83      3576486.25     10216257.29
      3575692.14     10215941.66
#Sta/Elev= 30
  3843.5  276.57  4037.9  271.84  4207.9  270.39  4236.4  269.44  4357.0  269.15
  4406.4  267.09  4449.1  266.47  4596.1  261.78  4615.1  260.95  4700.9  258.16
  4744.8  257.29  4927.1  256.29  4972.9  255.91  4991.9  251.49  4994.2  249.65
  4997.0  249.15  5000.2  249.65  5003.0  251.64  5026.9  256.09  5065.8  256.16
  5105.2  256.38  5129.5  257.77  5164.5  257.71  5218.5  259.50  5336.6  265.25
  5404.7  267.47  5434.4  269.41  5458.7  269.72  5483.0  271.15  5551.8  273.34
#Mann=8,-1,0
  3843.5    0.05       0  4596.1    0.16       0  4615.1     0.1       0
  4700.9    0.16       0  4927.1    0.12       0  4994.2    0.07       0
  5000.2    0.12       0  5065.8    0.16       0
Bank Sta=4994.2,5000.2
Exp/Cntr=0.3,0.1

Type RM Length L Ch R = 1,1841,1127,1127,1127
BEGIN DESCRIPTION:
CARTERS CREEK TRIB 15.1 2.0
END DESCRIPTION:
XS GIS Cut Line= 3
      3577112.80     10216821.52      3576628.25     10215805.59
      3575486.49     10215540.48
#Sta/Elev= 30
  3599.8  275.60  3960.6  268.56  3983.3  267.17  4142.1  265.58  4198.6  266.02
  4283.9  263.28  4380.2  264.31  4447.6  262.25  4458.5  261.95  4569.4  258.46
  4659.5  257.55  4680.4  257.38  4814.0  254.57  4895.0  254.62  4978.1  254.32
  4995.4  248.91  4995.6  248.84  4998.3  248.34  5001.6  248.84  5019.1  253.45
  5036.3  254.72  5152.6  254.00  5193.6  254.90  5293.3  259.00  5399.0  260.58
  5501.6  264.54  5516.8  264.27  5635.1  270.20  5735.1  273.25  5897.5  272.76
#Mann=11,-1,0
  3599.8    0.05       0  4447.6     0.1       0  4458.5    0.05       0
  4569.4     0.1       0  4659.5    0.16       0  4680.4     0.1       0
  4895.0    0.16       0  4995.4    0.12       0  4995.6    0.07       0
  5001.6    0.12       0  5036.3    0.16       0
Bank Sta=4995.6,5001.6
Exp/Cntr=0.3,0.1

Type RM Length L Ch R = 1,714,0,0,0
BEGIN DESCRIPTION:
CARTERS CREEK TRIB 15.1 1.0
END DESCRIPTION:
XS GIS Cut Line= 4
      3577119.58     10216618.15      3576741.65     10215437.30
      3576523.05     10215194.64      3575666.04     10214724.40
#Sta/Elev= 30
  3047.7  272.12  3347.2  264.30  3550.6  263.48  3894.5  258.51  3941.7  259.67
  4137.8  255.41  4198.9  254.65  4268.5  256.48  4334.0  253.47  4397.4  253.51
  4425.9  251.00  4454.3  253.62  4503.7  250.48  4546.3  251.49  4581.4  254.75
  4612.8  251.66  4706.3  251.86  4754.1  251.86  4876.4  251.84  4963.3  252.09
  4986.7  246.13  4998.2  244.77  5000.9  244.27  5004.2  244.77  5006.9  247.67
  5023.0  250.45  5028.7  253.13  5044.8  251.99  5088.4  256.44  5591.7  270.78
#Mann=9,-1,0
  3047.7    0.05       0  4137.8     0.1       0  4397.4    0.16       0
  4706.3    0.12       0  4754.1    0.16       0  4876.4    0.12       0
  4986.7    0.16       0  4998.2    0.07       0  5004.2    0.16       0
Bank Sta=4998.2,5004.2
Exp/Cntr=0.3,0.1

Chan Stop Cuts=-1