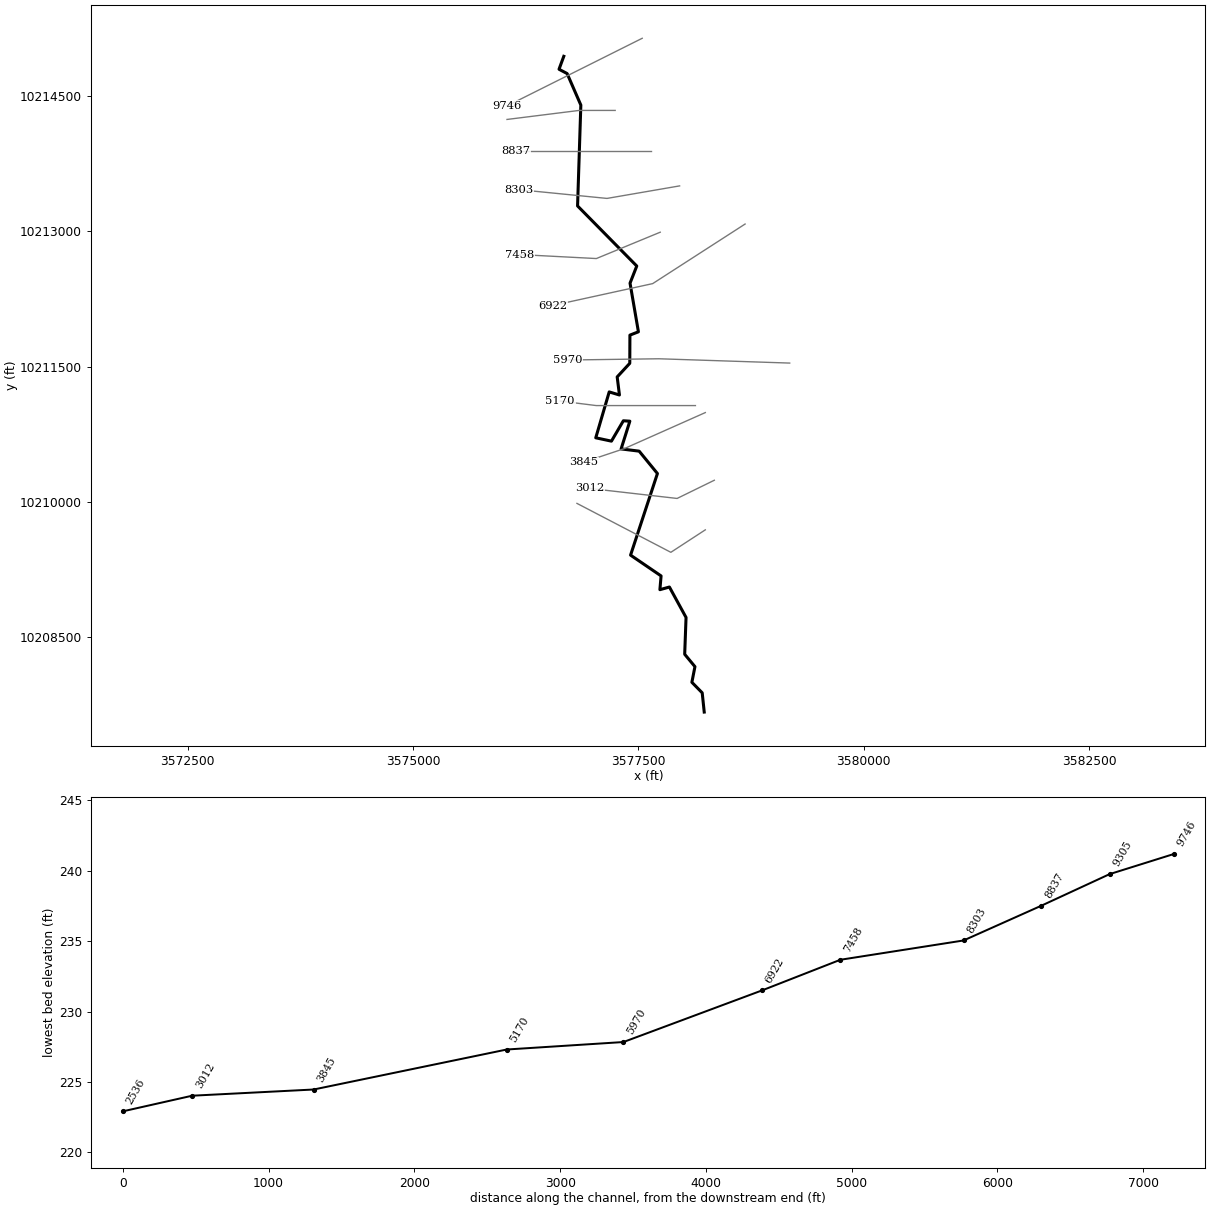
--- CARTERS CREEK TRIB 15.prj (project) ---

Proj Title=CARTERS CREEK TRIB 15 Base Level Engineering
Current Plan=p01
Default Exp/Contr=0.3,0.1
English Units
Geom File=g01
Flow File=f01
Plan File=p01
Y Axis Title=Elevation
X Axis Title(PF)=Main Channel Distance
X Axis Title(XS)=Station
BEGIN DESCRIPTION:
CARTERS CREEK TRIB 15
END DESCRIPTION:
DSS Export Rating Curves= 0
DSS Export Rating Curve Sorted= 0
DSS Export Volume Flow Curves= 0
DXF OffsetX= 0
DXF OffsetY= 0
DXF ScaleX= 1
DXF ScaleY= 10

--- CARTERS CREEK TRIB 15.p01 (plan) ---

Plan Title=Multiple Run
Short Identifier=Multiple
Geom File=g01
Flow File=f01
Subcritical Flow
K Sum by GR= 0
Std Step Tol= 0.01
Critical Tol= 0.01
Num of Std Step Trials= 20
Max Error Tol= 0.3
Flow Tol Ratio= 0.001
Split Flow NTrial= 30
Split Flow Tol= 0.02
Split Flow Ratio= 0.02
Log Output Level= 0
Friction Slope Method= 1
Unsteady Friction Slope Method= 2
Unsteady Bridges Friction Slope Method= 1
Parabolic Critical Depth
Global Vel Dist=  1 , 1 , 1
Global Log Level= 0
CheckData=True
Encroach Param= -1, 0, 0, 0
BEGIN DESCRIPTION:
Multiple Run
END DESCRIPTION:

--- CARTERS CREEK TRIB 15.f01 (steady flow) ---

Flow Title=Multiple
Number of Profiles=7
Profile Names=10-year,25-year,50-year,1pct_min,100-year,1pct_plu,500-year
River Rch & RM= CARTERS CREEK TR,Reach-1,9746
    1055    1454    1786    1603    2167    2931    3202
Boundary for River Rch & Prof#=CARTERS CREEK TR,Reach-1,1
Up Type=0
Dn Type=3
Dn Slope=0.005
Boundary for River Rch & Prof#=CARTERS CREEK TR,Reach-1,2
Up Type=0
Dn Type=3
Dn Slope=0.005
Boundary for River Rch & Prof#=CARTERS CREEK TR,Reach-1,3
Up Type=0
Dn Type=3
Dn Slope=0.005
Boundary for River Rch & Prof#=CARTERS CREEK TR,Reach-1,4
Up Type=0
Dn Type=3
Dn Slope=0.005
Boundary for River Rch & Prof#=CARTERS CREEK TR,Reach-1,5
Up Type=0
Dn Type=3
Dn Slope=0.005
Boundary for River Rch & Prof#=CARTERS CREEK TR,Reach-1,6
Up Type=0
Dn Type=3
Dn Slope=0.005
Boundary for River Rch & Prof#=CARTERS CREEK TR,Reach-1,7
Up Type=0
Dn Type=3
Dn Slope=0.005

--- CARTERS CREEK TRIB 15.g01 (geometry) ---

Geom Title=Existing Conditions
Program Version=4.10

River Reach=CARTERS CREEK TR,Reach-1
Reach XY= 30
      3576672.11     10214941.64       3576619.2     10214798.08
      3576709.03     10214750.56      3576861.19     10214401.12
      3576824.93     10213282.64      3577481.69     10212616.41
      3577407.08     10212426.69      3577499.99     10211887.18
      3577405.65      10211850.5       3577404.2     10211538.18
      3577264.44     10211387.01      3577289.49     10211186.62
      3577175.95     10211220.82      3577026.74     10210712.05
      3577200.69     10210674.94      3577333.04     10210900.79
      3577404.91     10210896.27        3577308.     10210588.66
      3577508.16     10210564.05      3577710.92     10210315.99
      3577412.89     10209411.17       3577751.4     10209180.74
      3577738.34     10209028.25      3577843.91      10209057.6
       3578028.4     10208720.21      3578013.37     10208312.09
       3578127.1     10208174.83      3578093.07     10208001.42
      3578207.72      10207884.6       3578230.1     10207671.26

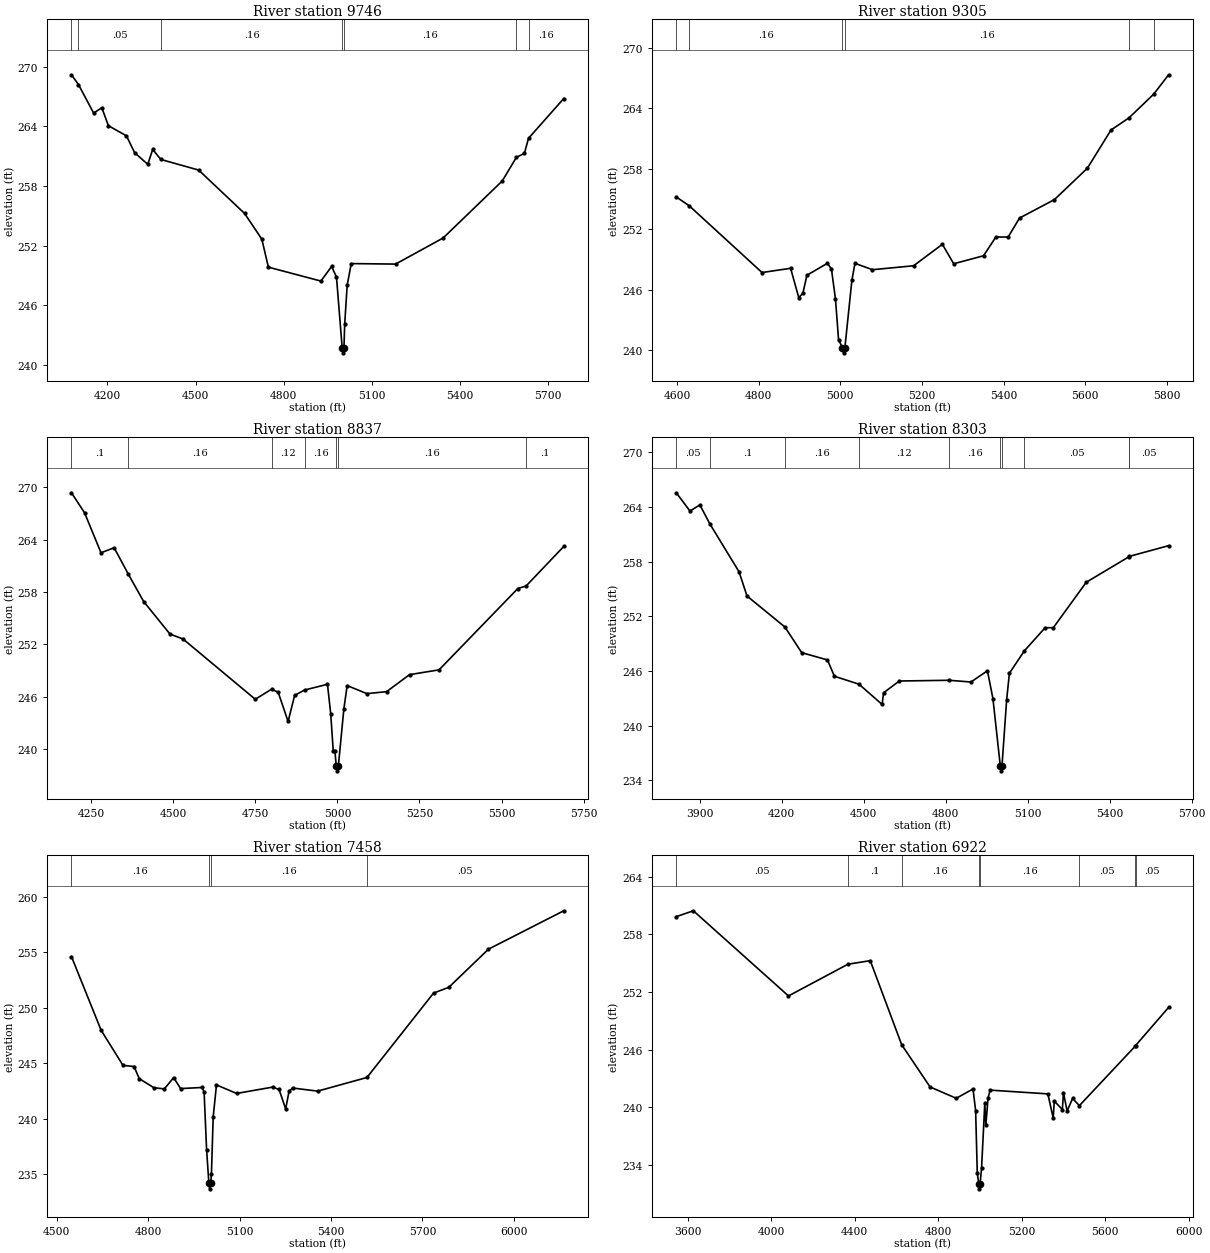
Type RM Length L Ch R = 1 ,9746    ,441,441,441
BEGIN DESCRIPTION:
CARTERS CREEK TRIB 15 15.0
END DESCRIPTION:
XS GIS Cut Line= 3
      3577542.12     10215141.65      3576742.11     10214741.64
      3576042.07     10214391.63
#Sta/Elev= 30
  4077.3   269.2  4101.1  268.22  4152.8  265.34  4180.7  265.88  4203.1  264.07
  4264.6  263.05  4292.5  261.35  4337.3  260.18    4354  261.68  4381.7  260.67
  4510.6   259.6  4667.1  255.23  4725.8  252.64  4748.1  249.82    4927  248.42
  4963.4  249.89  4980.1  248.82  4999.5  241.69  5002.2  241.19  5005.5  241.69
  5008.1  244.11  5016.5  247.99  5030.4  250.18  5181.4  250.13  5343.5  252.76
  5544.7   258.5  5593.1  260.89  5620.2  261.28  5634.3   262.8  5754.4  266.81
#Mann= 7 ,-1 , 0
  4077.3      .1       0  4101.1     .05       0  4381.7     .16       0
  4999.5     .07       0  5005.5     .16       0  5593.1      .1       0
  5634.3     .16       0
Bank Sta=4999.5,5005.5
XS Rating Curve= 0 ,0
Exp/Cntr=0.3,0.1

Type RM Length L Ch R = 1 ,9305    ,468,468,468
BEGIN DESCRIPTION:
CARTERS CREEK TRIB 15 14.0
END DESCRIPTION:
XS GIS Cut Line= 3
      3577242.06     10214341.64      3576842.11     10214341.64
      3576042.08     10214241.64
#Sta/Elev= 30
  4598.1  255.21  4629.9  254.33  4808.1  247.72  4878.1  248.14  4898.1  245.24
  4908.1  245.65  4918.1  247.45  4968.1  248.63  4978.1  248.09  4988.1  245.08
  4995.6  241.07  5005.1  240.26  5007.9  239.76  5011.1  240.26  5028.3  246.96
  5035.8  248.63  5078.7     248  5179.5  248.39    5250  250.52  5277.7  248.59
  5350.8  249.38    5381  251.24  5411.2  251.24    5439  253.12  5524.6  254.95
  5605.2  258.06  5663.2  261.85  5707.2  263.05  5767.5  265.39  5804.3  267.32
#Mann= 6 ,-1 , 0
  4598.1      .1       0  4629.9     .16       0  5005.1     .07       0
  5011.1     .16       0  5707.2      .1       0  5767.5     .16       0
Bank Sta=5005.1,5011.1
XS Rating Curve= 0 ,0
Exp/Cntr=0.3,0.1

Type RM Length L Ch R = 1 ,8837    ,534,534,534
BEGIN DESCRIPTION:
CARTERS CREEK TRIB 15 13.0
END DESCRIPTION:
XS GIS Cut Line= 3
      3577642.11     10213891.64      3576842.11     10213891.64
      3576142.11     10213891.64
#Sta/Elev= 30
  4189.7  269.35  4229.7  267.05  4279.7  262.48  4319.7  263.06  4363.4     260
  4409.7   256.9  4489.7  253.18  4529.7  252.61  4749.7  245.71  4799.5  246.87
  4819.7   246.5  4849.7  243.17  4869.7  246.16  4900.1  246.77  4969.7  247.43
  4979.7  244.01  4987.2  239.83  4992.2  239.83  4996.7  238.02  4999.5  237.52
  5002.7  238.02  5019.7  244.63  5029.7  247.28  5089.7  246.36  5149.7  246.58
  5219.7  248.53  5309.7  249.08  5549.7  258.39  5574.9  258.68  5689.7  263.21
#Mann= 7 ,-1 , 0
  4189.7      .1       0  4363.4     .16       0  4799.5     .12       0
  4900.1     .16       0  4996.7     .07       0  5002.7     .16       0
  5574.9      .1       0
Bank Sta=4996.7,5002.7
XS Rating Curve= 0 ,0
Exp/Cntr=0.3,0.1

Type RM Length L Ch R = 1 ,8303    ,845,845,845
BEGIN DESCRIPTION:
CARTERS CREEK TRIB 15 11.0
END DESCRIPTION:
XS GIS Cut Line= 3
      3577957.02     10213504.98      3577151.46     10213366.09
      3576172.32     10213463.31
#Sta/Elev= 30
  3814.3  265.54  3864.2  263.54  3900.5  264.21  3936.8  262.14  4043.8  256.88
    4073  254.22  4211.7  250.82  4273.1  248.01  4367.3  247.21  4392.9  245.42
  4482.7  244.55  4567.4  242.33  4572.5   243.6  4630.1   244.9  4812.9  244.98
  4892.4  244.79  4952.7  246.02  4972.8  242.98  4999.9  235.55  5002.7  235.05
  5005.9  235.55    5023  242.84  5033.1  245.75  5087.6   248.2  5163.7  250.74
  5193.9  250.75  5314.4  255.73  5469.8  258.51  5472.3  258.57  5615.7  259.74
#Mann= 10 ,-1 , 0
  3814.3     .05       0  3936.8      .1       0  4211.7     .16       0
  4482.7     .12       0  4812.9     .16       0  4999.9     .07       0
  5005.9     .16       0  5087.6     .05       0  5469.8     .16       0
  5472.3     .05       0
Bank Sta=4999.9,5005.9
XS Rating Curve= 0 ,0
Exp/Cntr=0.3,0.1

Type RM Length L Ch R = 1 ,7458    ,536,536,536
BEGIN DESCRIPTION:
CARTERS CREEK TRIB 15 10.0
END DESCRIPTION:
XS GIS Cut Line= 3
      3577742.08     10212991.63       3577033.4     10212699.43
       3576185.3     10212743.54
#Sta/Elev= 30
  4548.3  254.62  4645.6  247.98  4717.4  244.81  4753.8  244.71  4770.6  243.62
  4818.5   242.8  4853.2  242.69  4883.6  243.71  4906.5  242.72  4978.3  242.82
  4983.7  242.37  4991.8   237.2  4999.3  234.18    5002  233.68  5005.3  234.18
  5007.7  235.06  5013.4  240.15  5024.2  243.05  5090.3  242.28  5208.1  242.85
  5229.7  242.64  5251.4  240.88  5262.2  242.46    5274  242.77  5356.2  242.49
  5518.1  243.72  5736.7  251.33  5786.8  251.85    5917  255.29  6164.1  258.75
#Mann= 4 ,-1 , 0
  4548.3     .16       0  4999.3     .07       0  5005.3     .16       0
  5518.1     .05       0
Bank Sta=4999.3,5005.3
XS Rating Curve= 0 ,0
Exp/Cntr=0.3,0.1

Type RM Length L Ch R = 1 ,6922    ,952,952,952
BEGIN DESCRIPTION:
CARTERS CREEK TRIB 15 9.0
END DESCRIPTION:
XS GIS Cut Line= 3
      3578683.52     10213082.15       3577658.4     10212421.65
      3576547.26     10212178.59
#Sta/Elev= 30
  3546.3  259.83  3627.8  260.44  4083.3  251.58    4368  254.88  4474.8  255.25
  4625.3   246.5  4761.2  242.11  4886.4  240.93  4966.7   241.9  4979.2  239.66
  4987.2  233.14  4994.4  232.01  4997.2  231.51  5000.4  232.01  5007.7  233.65
  5023.1  240.43  5028.2  238.13  5038.4  240.92  5048.6  241.78    5325  241.39
  5350.7  238.88  5355.8  240.64  5394.5  239.76  5399.7  241.53  5417.1  239.61
  5443.5  240.91    5476  240.17  5743.6  246.36    5745  246.42  5903.2  250.39
#Mann= 8 ,-1 , 0
  3546.3     .05       0    4368      .1       0  4625.3     .16       0
  4994.4     .07       0  5000.4     .16       0    5476     .05       0
  5743.6     .16       0    5745     .05       0
Bank Sta=4994.4,5000.4
XS Rating Curve= 0 ,0
Exp/Cntr=0.3,0.1

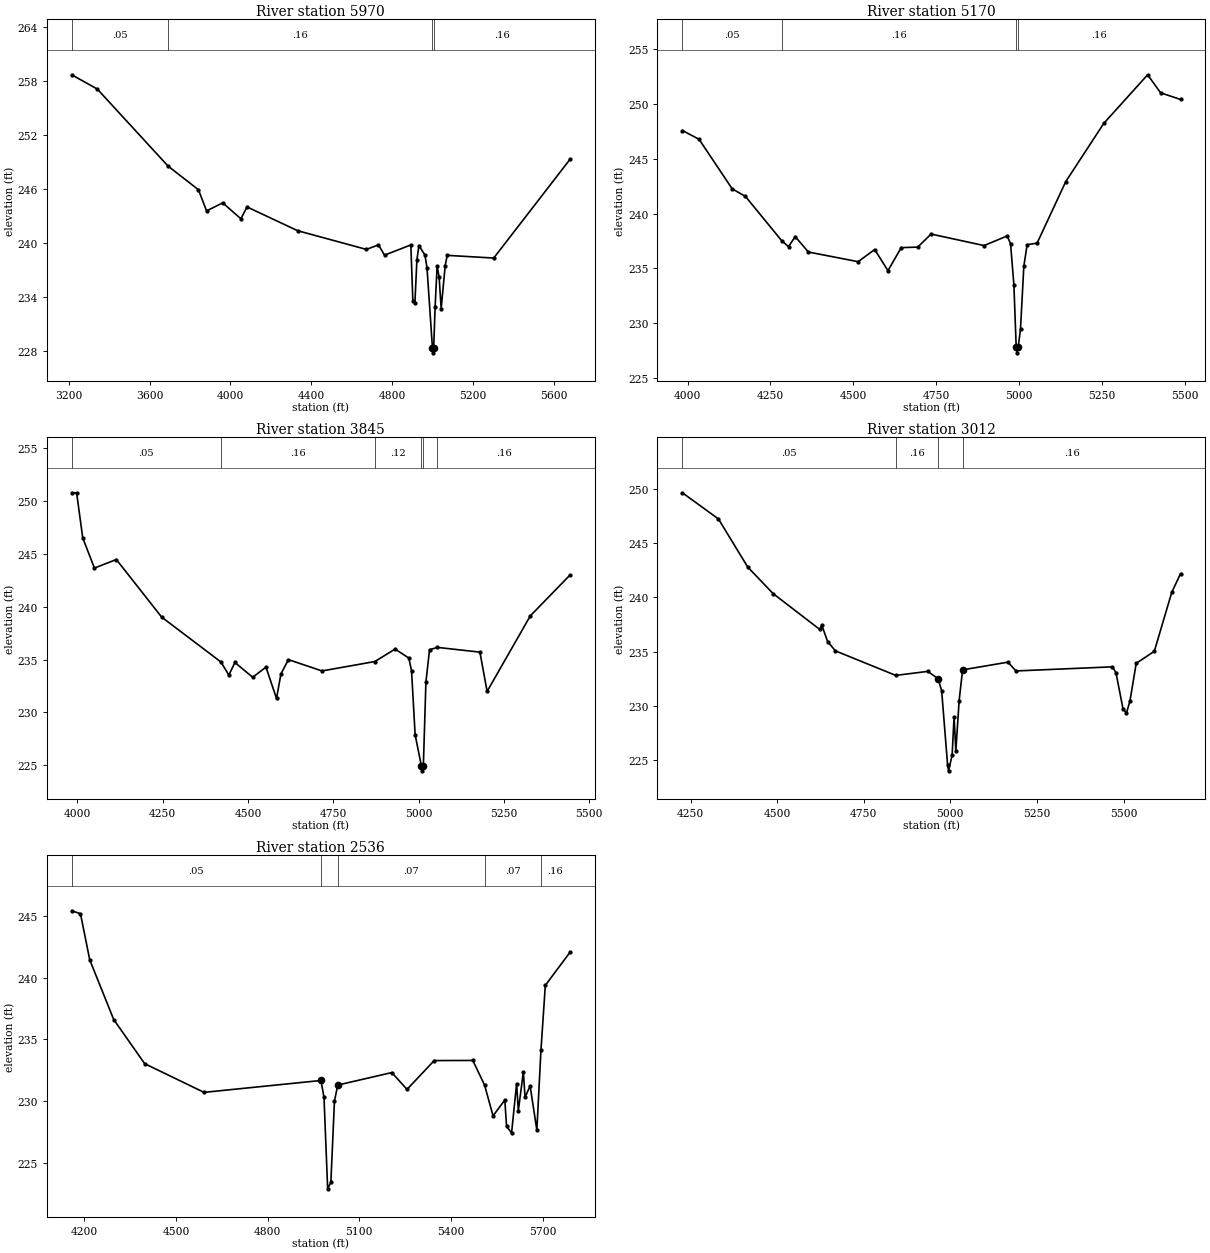
Type RM Length L Ch R = 1 ,5970    ,800,800,800
BEGIN DESCRIPTION:
CARTERS CREEK TRIB 15 7.0
END DESCRIPTION:
XS GIS Cut Line= 3
       3579178.4     10211540.51      3577727.85     10211588.31
      3576715.58     10211574.45
#Sta/Elev= 30
  3215.4  258.73  3341.8  257.14    3692  248.58    3842  245.96  3882.1  243.61
  3962.1   244.5  4052.1  242.73  4082.2  244.05  4332.3  241.41  4672.5  239.33
  4732.5  239.83  4762.5  238.69  4892.5  239.83  4902.5  233.59  4912.5  233.33
  4922.5  238.17  4932.5  239.76  4962.5  238.69  4972.5  237.27  4999.5  228.34
  5002.3  227.84  5005.5  228.34  5012.5  232.91  5022.5  237.52  5032.5  236.23
  5042.5  232.75  5062.5  237.54  5072.5  238.67  5302.5  238.37  5679.1  249.32
#Mann= 4 ,-1 , 0
  3215.4     .05       0    3692     .16       0  4999.5     .07       0
  5005.5     .16       0
Bank Sta=4999.5,5005.5
XS Rating Curve= 0 ,0
Exp/Cntr=0.3,0.1

Type RM Length L Ch R = 1 ,5170    ,1325,1325,1325
BEGIN DESCRIPTION:
CARTERS CREEK TRIB 15 6.0
END DESCRIPTION:
XS GIS Cut Line= 3
      3578132.39     10211069.42      3577032.38     10211069.42
       3576632.4     10211119.42
#Sta/Elev= 30
  3984.4  247.58  4034.7  246.78  4134.7  242.26  4174.7  241.57  4284.1  237.53
  4304.7  236.99  4324.7  237.91  4364.7   236.5  4514.7  235.62  4564.7  236.73
  4604.7   234.8  4644.7   236.9  4694.7  236.95  4734.7  238.14  4894.7  237.09
  4964.7  237.97  4974.7  237.24  4984.7  233.51  4991.7  227.81  4994.4  227.31
  4997.7  227.81  5004.7   229.5  5014.7   235.2  5024.7  237.17  5054.7  237.31
  5141.4  242.93    5256  248.23  5388.3  252.66  5427.3  251.02  5487.5  250.41
#Mann= 4 ,-1 , 0
  3984.4     .05       0  4284.1     .16       0  4991.7     .07       0
  4997.7     .16       0
Bank Sta=4991.7,4997.7
XS Rating Curve= 0 ,0
Exp/Cntr=0.3,0.1

Type RM Length L Ch R = 1 ,3845    ,833,833,833
BEGIN DESCRIPTION:
CARTERS CREEK TRIB 15 4.0
END DESCRIPTION:
XS GIS Cut Line= 3
      3578242.06     10210991.62      3577342.11     10210591.64
      3576892.09     10210441.64
#Sta/Elev= 30
  3983.7   250.8    3998  250.79  4015.8  246.54    4050  243.67  4114.3  244.48
    4247  239.03  4420.6  234.78  4443.9  233.54  4461.7  234.73  4513.7  233.33
  4552.7  234.29  4583.5  231.32  4596.5  233.65  4618.4     235  4716.8  233.93
  4871.5  234.82  4930.9     236  4971.2  235.15  4979.1  233.93  4989.6  227.89
  5007.7  224.97  5010.5  224.47  5013.7  224.97  5021.2  232.88  5031.8  235.94
  5054.8  236.16  5179.4  235.71  5200.4  231.99  5326.9  239.14  5442.9     243
#Mann= 6 ,-1 , 0
  3983.7     .05       0  4420.6     .16       0  4871.5     .12       0
  5007.7     .07       0  5013.7     .12       0  5054.8     .16       0
Bank Sta=5007.7,5013.7
XS Rating Curve= 0 ,0
Exp/Cntr=0.3,0.1

Type RM Length L Ch R = 1 ,3012    ,476,476,476
BEGIN DESCRIPTION:
CARTERS CREEK TRIB 15 2.0
END DESCRIPTION:
XS GIS Cut Line= 3
      3578342.14     10210241.66      3577929.24      10210039.7
      3576957.01     10210150.81
#Sta/Elev= 30
  4226.4  249.64  4330.5  247.23    4415   242.8  4488.1  240.36  4623.2  237.05
  4628.7  237.46  4645.7  235.94  4668.2  235.08  4842.4  232.82  4934.8  233.19
    4965  232.51    4975  231.39  4992.2  224.53  4994.9  224.03  5005.2  225.48
  5010.8  229.01  5015.9  225.86  5025.4  230.49  5035.4  233.33  5166.3  234.04
  5189.5  233.23  5468.2  233.61  5478.3  233.06  5498.4  229.77  5508.5  229.34
  5518.6  230.46  5536.7  233.93    5589  235.04  5639.3  240.47  5664.6  242.18
#Mann= 4 ,-1 , 0
  4226.4     .05       0  4842.4     .16       0    4965     .07       0
  5035.4     .16       0
Bank Sta=4965,5035.4
XS Rating Curve= 0 ,0
Exp/Cntr=0.3,0.1

Type RM Length L Ch R = 1 ,2536    ,0,0,0
BEGIN DESCRIPTION:
CARTERS CREEK TRIB 15 1.0
END DESCRIPTION:
XS GIS Cut Line= 3
      3578242.09     10209691.63      3577859.79     10209442.48
       3576818.1     10209984.94
#Sta/Elev= 30
  4158.6   245.4  4187.2  245.16  4217.5  241.43  4295.9  236.61  4397.3  233.04
  4591.6  230.72  4974.5  231.68  4984.4  230.32  4996.4  222.92  5006.9  223.45
  5018.7  230.03  5029.5  231.31  5206.4  232.32  5256.2  230.96  5345.2  233.29
  5471.6   233.3  5510.1  231.31  5537.9  228.82  5576.4   230.1  5582.1  227.99
  5598.5  227.43    5615  231.43  5620.6  229.24  5637.1  232.36  5642.7  230.31
  5659.2  231.25  5681.3  227.67  5694.7  234.11    5709  239.37  5789.4  242.03
#Mann= 5 ,-1 , 0
  4158.6     .05       0  4974.5     .03       0  5029.5     .07       0
  5510.1     .07       0  5694.7     .16       0
Bank Sta=4974.5,5029.5
XS Rating Curve= 0 ,0
Exp/Cntr=0.3,0.1

Chan Stop Cuts=-1
Use User Specified Reach Order=0
Composite Channel Slope=5