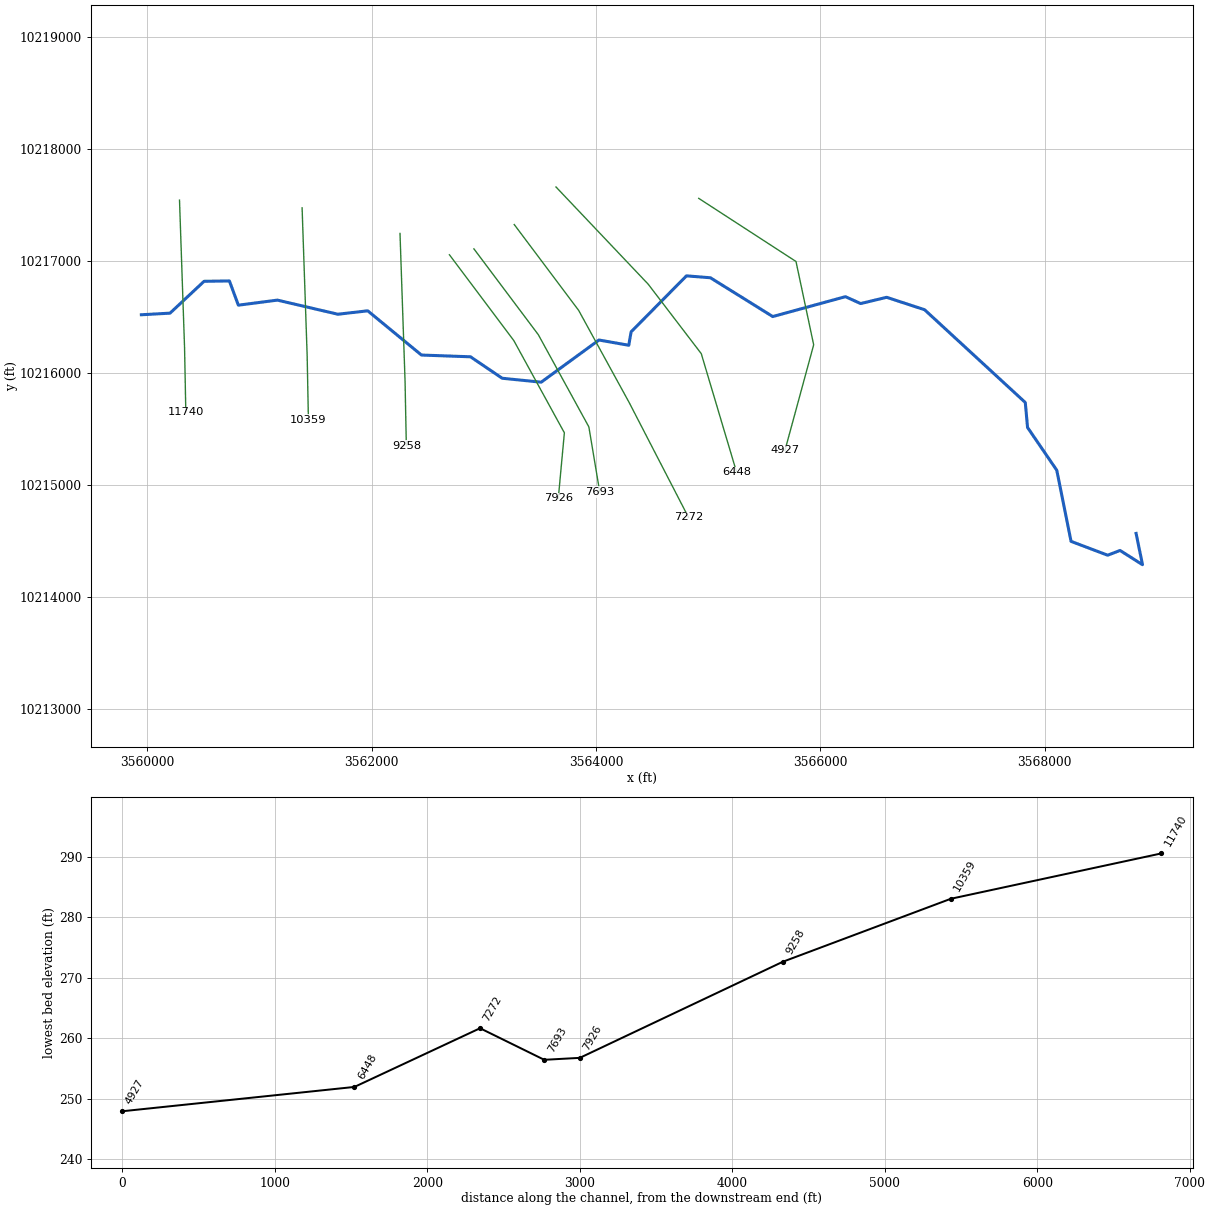
--- CARTERS CREEK TRIB 17.prj (project) ---

Proj Title=CARTERS CREEK TRIB 17 Base Level Engineering
Current Plan=p01
Default Exp/Contr=0.3,0.1
English Units
Geom File=g01
Flow File=f01
Plan File=p01
BEGIN DESCRIPTION:
CARTERS CREEK TRIB 17
END DESCRIPTION:

--- CARTERS CREEK TRIB 17.p01 (plan) ---

Plan Title=Multiple Run
Short Identifier=Multiple
Geom File=g01
Flow File=f01
Subcritical Flow
K Sum by GR= 0
Std Step Tol= 0.01
Critical Tol= 0.01
Num of Std Step Trials= 20
Max Error Tol= 0.3
Flow Tol Ratio= 0.001
Split Flow NTrial= 30
Split Flow Tol= 0.02
Split Flow Ratio= 0.02
Log Output Level= 0
Friction Slope Method= 1
Unsteady Friction Slope Method= 2
Unsteady Bridges Friction Slope Method= 1
Parabolic Critical Depth
Global Vel Dist=  1 , 1 , 1
Global Log Level= 0
CheckData=True
Encroach Param= -1, 0, 0, 0
BEGIN DESCRIPTION:
Multiple Run
END DESCRIPTION:

--- CARTERS CREEK TRIB 17.f01 (steady flow) ---

Flow Title=Multiple
Number of Profiles=7
Profile Names=10-year,25-year,50-year,1pct_min,100-year,1pct_plu,500-year
River Rch & RM= CARTERS CREEK TR,Reach-1,11740
     228     289     336     287     388     525     517
River Rch & RM= CARTERS CREEK TR,Reach-1,7272
     467     621     745     655     886    1198    1257
Boundary for River Rch & Prof#=CARTERS CREEK TR,Reach-1,1
Up Type=0
Dn Type=3
Dn Slope=0.005
Boundary for River Rch & Prof#=CARTERS CREEK TR,Reach-1,2
Up Type=0
Dn Type=3
Dn Slope=0.005
Boundary for River Rch & Prof#=CARTERS CREEK TR,Reach-1,3
Up Type=0
Dn Type=3
Dn Slope=0.005
Boundary for River Rch & Prof#=CARTERS CREEK TR,Reach-1,4
Up Type=0
Dn Type=3
Dn Slope=0.005
Boundary for River Rch & Prof#=CARTERS CREEK TR,Reach-1,5
Up Type=0
Dn Type=3
Dn Slope=0.005
Boundary for River Rch & Prof#=CARTERS CREEK TR,Reach-1,6
Up Type=0
Dn Type=3
Dn Slope=0.005
Boundary for River Rch & Prof#=CARTERS CREEK TR,Reach-1,7
Up Type=0
Dn Type=3
Dn Slope=0.005

--- CARTERS CREEK TRIB 17.g01 (geometry) ---

Geom Title=Existing Conditions

River Reach=CARTERS CREEK TR,Reach-1
Reach XY= 30
      3559945.42     10216517.53      3560201.21     10216531.88
      3560505.07     10216816.14      3560730.72     10216819.21
      3560810.58     10216603.06      3561158.67     10216648.20
      3561697.73     10216522.33      3561964.23     10216552.72
      3562443.39     10216158.19      3562880.89     10216142.56
      3563163.45     10215951.15      3563511.10     10215916.00
      3564026.73     10216292.30      3564292.35     10216245.43
      3564313.19     10216365.22      3564806.89     10216864.63
      3565020.30     10216847.77      3565576.60     10216501.55
      3566224.23     10216678.89      3566360.43     10216617.58
      3566592.35     10216673.29      3566930.55     10216562.42
      3567828.61     10215734.78      3567848.82     10215511.97
      3568109.24     10215130.72      3568236.88     10214495.92
      3568563.41     10214372.39      3568673.82     10214414.75
      3568874.04     10214287.58      3568816.78     10214566.81

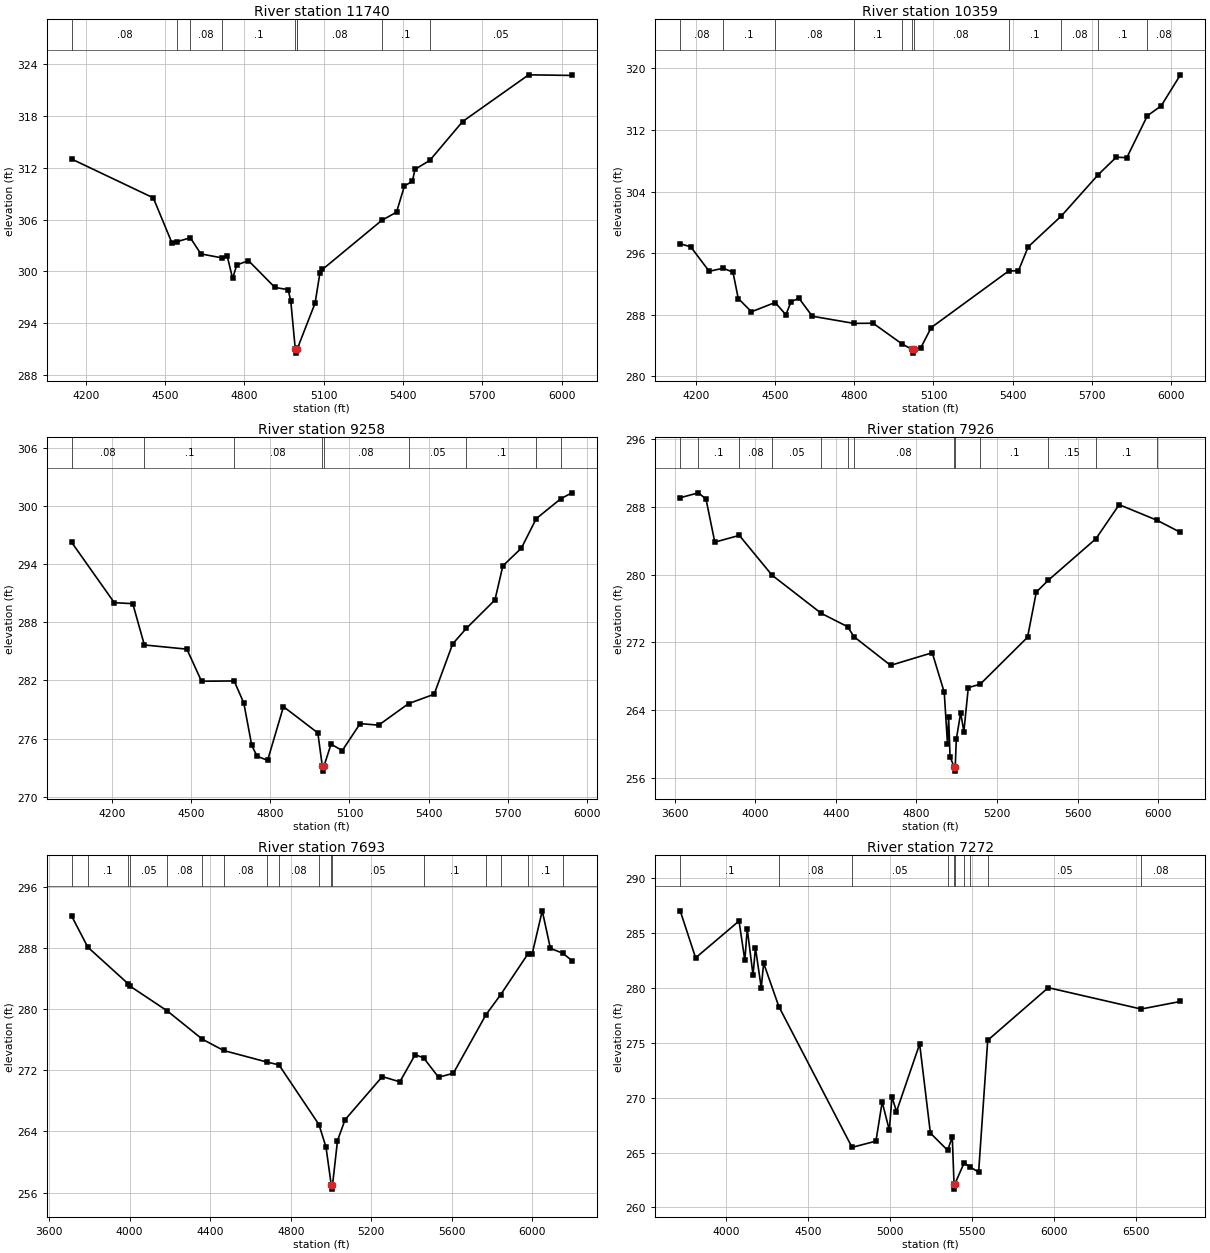
Type RM Length L Ch R = 1,11740,1381,1381,1381
BEGIN DESCRIPTION:
CARTERS CREEK TRIB 17 7.0
END DESCRIPTION:
XS GIS Cut Line= 3
      3560285.73     10217540.39      3560330.79     10216222.51
      3560342.05     10215648.07
#Sta/Elev= 30
  4146.0  313.03  4454.9  308.53  4525.0  303.34  4545.0  303.45  4595.0  303.90
  4635.0  302.03  4715.8  301.56  4735.1  301.73  4755.1  299.18  4770.8  300.74
  4815.1  301.25  4915.2  298.14  4965.2  297.88  4975.2  296.59  4992.2  291.02
  4995.0  290.52  4998.2  291.02  5000.4  291.06  5067.2  296.31  5085.3  299.76
  5095.3  300.23  5319.3  305.91  5375.5  306.87  5405.5  309.91  5435.5  310.45
  5445.5  311.84  5501.3  312.87  5625.6  317.38  5875.6  322.80  6039.2  322.73
#Mann=9,-1,0
  4146.0    0.08       0  4545.0     0.1       0  4595.0    0.08       0
  4715.8     0.1       0  4992.2    0.07       0  4998.2     0.1       0
  5000.4    0.08       0  5319.3     0.1       0  5501.3    0.05       0
Bank Sta=4992.2,4998.2
Exp/Cntr=0.3,0.1

Type RM Length L Ch R = 1,10359,1101,1101,1101
BEGIN DESCRIPTION:
CARTERS CREEK TRIB17 5.0
END DESCRIPTION:
XS GIS Cut Line= 3
      3561379.06     10217471.27      3561424.12     10216153.35
      3561435.39     10215578.85
#Sta/Elev= 30
  4141.3  297.22  4181.0  296.83  4251.0  293.65  4304.3  294.05  4341.0  293.53
  4361.1  290.11  4411.1  288.40  4500.7  289.60  4541.2  288.01  4561.2  289.73
  4591.2  290.13  4641.2  287.82  4798.6  286.89  4871.4  286.91  4982.3  284.19
  5018.4  283.53  5021.2  283.03  5024.4  283.53  5051.5  283.70  5091.5  286.35
  5384.1  293.68  5421.7  293.73  5458.3  296.82  5584.2  300.84  5723.5  306.19
  5791.8  308.46  5831.8  308.40  5909.6  313.84  5961.8  315.12  6034.6  319.15
#Mann=11,-1,0
  4141.3    0.08       0  4304.3     0.1       0  4500.7    0.08       0
  4798.6     0.1       0  4982.3    0.08       0  5018.4    0.07       0
  5024.4    0.08       0  5384.1     0.1       0  5584.2    0.08       0
  5723.5     0.1       0  5909.6    0.08       0
Bank Sta=5018.4,5024.4
Exp/Cntr=0.3,0.1

Type RM Length L Ch R = 1,9258,1332,1332,1332
BEGIN DESCRIPTION:
CARTERS CREEK TRIB 17 6.0
END DESCRIPTION:
XS GIS Cut Line= 3
      3562252.21     10217242.81      3562297.26     10215924.93
      3562308.53     10215350.49
#Sta/Elev= 30
  4048.6  296.23  4209.9  290.01  4279.9  289.91  4323.7  285.65  4484.6  285.22
  4540.1  281.91  4663.6  281.94  4700.1  279.66  4730.2  275.29  4750.2  274.18
  4790.2  273.75  4850.2  279.29  4980.3  276.58  4997.3  273.14  5000.1  272.64
  5003.3  273.14  5030.3  275.42  5072.7  274.76  5140.4  277.54  5210.4  277.38
  5323.6  279.60  5420.5  280.57  5490.6  285.76  5542.7  287.37  5650.6  290.29
  5680.6  293.81  5750.6  295.63  5807.0  298.68  5899.9  300.73  5941.8  301.34
#Mann=9,-1,0
  4048.6    0.08       0  4323.7     0.1       0  4663.6    0.08       0
  4997.3    0.07       0  5003.3    0.08       0  5323.6    0.05       0
  5542.7     0.1       0  5807.0    0.08       0  5899.9     0.1       0
Bank Sta=4997.3,5003.3
Exp/Cntr=0.3,0.1

Type RM Length L Ch R = 1,7926,233,233,233
BEGIN DESCRIPTION:
CARTERS CREEK TRIB 17 4.1
END DESCRIPTION:
XS GIS Cut Line= 4
      3562693.01     10217052.68      3563267.50     10216286.69
      3563718.06     10215464.42      3563663.74     10214879.04
#Sta/Elev= 30
  3627.2  289.08  3717.6  289.66  3755.2  288.92  3799.0  283.83  3920.5  284.63
  4082.9  279.93  4327.9  275.41  4458.1  273.84  4490.0  272.65  4671.5  269.27
  4878.2  270.76  4937.9  266.09  4954.0  259.97  4959.7  263.13  4966.7  258.49
  4986.5  257.27  4989.3  256.77  4992.5  257.27  4997.7  260.52  5019.5  263.66
  5035.2  261.44  5057.4  266.64  5116.3  267.04  5351.3  272.59  5394.9  277.93
  5454.9  279.34  5690.7  284.23  5806.3  288.26  5995.0  286.41  6110.2  284.99
#Mann=13,-1,0
  3627.2    0.05       0  3717.6     0.1       0  3920.5    0.08       0
  4082.9    0.05       0  4327.9    0.08       0  4458.1     0.1       0
  4490.0    0.08       0  4986.5    0.07       0  4992.5    0.08       0
  5116.3     0.1       0  5454.9    0.15       0  5690.7     0.1       0
  5995.0    0.15       0
Bank Sta=4986.5,4992.5
Exp/Cntr=0.3,0.1

Type RM Length L Ch R = 1,7693,421,421,421
BEGIN DESCRIPTION:
CARTERS CREEK TRIB 17 4.0
END DESCRIPTION:
XS GIS Cut Line= 4
      3562911.41     10217105.52      3563485.90     10216339.53
      3563936.46     10215517.26      3564033.51     10214936.52
#Sta/Elev= 30
  3712.0  292.17  3792.2  288.10  3992.8  283.31  4001.2  283.02  4186.9  279.76
  4360.6  276.07  4466.4  274.59  4683.5  273.06  4741.2  272.71  4939.9  264.90
  4975.0  261.94  5001.2  256.95  5004.0  256.45  5007.2  256.95  5032.0  262.79
  5069.6  265.53  5254.5  271.17  5341.7  270.49  5417.6  274.04  5459.8  273.62
  5533.7  271.09  5607.1  271.60  5769.2  279.26  5842.3  281.89  5978.1  287.24
  5998.1  287.15  6048.8  292.86  6089.3  287.95  6150.2  287.32  6195.9  286.36
#Mann=17,-1,0
  3712.0    0.08       0  3792.2     0.1       0  3992.8    0.08       0
  4001.2    0.05       0  4186.9    0.08       0  4360.6    0.05       0
  4466.4    0.08       0  4683.5    0.05       0  4741.2    0.08       0
  4939.9    0.05       0  5001.2    0.04       0  5007.2    0.05       0
  5459.8     0.1       0  5769.2    0.05       0  5842.3    0.08       0
  5978.1     0.1       0  6150.2    0.15       0
Bank Sta=5001.2,5007.2
Exp/Cntr=0.3,0.1

Type RM Length L Ch R = 1,7272,824,824,824
BEGIN DESCRIPTION:
CARTERS CREEK TRIB 17 3.0
END DESCRIPTION:
XS GIS Cut Line= 4
      3563271.11     10217322.27      3563845.57     10216556.33
      3564296.13     10215734.06      3564825.53     10214709.05
#Sta/Elev= 30
  3721.9  287.05  3815.8  282.76  4080.4  286.12  4115.8  282.53  4130.4  285.41
  4165.8  281.18  4180.4  283.68  4215.8  280.03  4230.4  282.28  4323.0  278.32
  4769.3  265.47  4914.9  266.04  4952.9  269.61  4996.5  267.03  5012.6  270.08
  5040.1  268.73  5181.3  274.90  5246.8  266.77  5352.0  265.20  5380.2  266.43
  5390.7  262.16  5393.5  261.66  5396.7  262.16  5452.3  264.05  5486.5  263.70
  5540.7  263.21  5596.2  275.24  5965.3  280.04  6531.2  278.09  6770.6  278.78
#Mann=10,-1,0
  3721.9     0.1       0  4323.0    0.08       0  4769.3    0.05       0
  5352.0    0.08       0  5390.7    0.04       0  5396.7    0.08       0
  5452.3     0.1       0  5486.5    0.08       0  5596.2    0.05       0
  6531.2    0.08       0
Bank Sta=5390.7,5396.7
Exp/Cntr=0.3,0.1

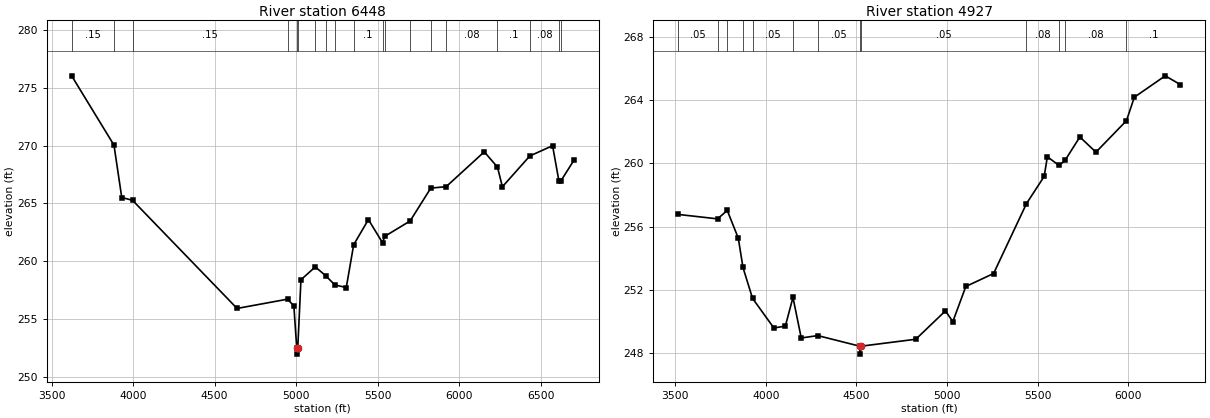
Type RM Length L Ch R = 1,6448,1521,1521,1521
BEGIN DESCRIPTION:
CARTERS CREEK TRIB 17 2.0
END DESCRIPTION:
XS GIS Cut Line= 4
      3563643.56     10217657.45      3564465.86     10216790.09
      3564938.95     10216170.57      3565254.35     10215111.74
#Sta/Elev= 30
  3622.9  276.03  3882.4  270.04  3930.2  265.51  3996.1  265.27  4637.3  255.92
  4946.6  256.72  4985.5  256.15  5003.3  252.47  5006.0  251.97  5009.3  252.47
  5029.0  258.40  5116.9  259.51  5180.9  258.75  5236.9  257.95  5306.9  257.73
  5352.4  261.43  5442.6  263.60  5529.4  261.60  5542.5  262.15  5698.4  263.48
  5825.0  266.32  5919.7  266.45  6153.2  269.46  6234.0  268.14  6264.3  266.44
  6432.3  269.10  6572.0  269.99  6610.5  266.97  6622.2  266.93  6702.4  268.72
#Mann=19,-1,0
  3622.9    0.15       0  3882.4     0.1       0  3996.1    0.15       0
  4946.6     0.1       0  5003.3    0.07       0  5009.3     0.1       0
  5116.9    0.08       0  5180.9    0.05       0  5236.9    0.08       0
  5352.4     0.1       0  5529.4    0.08       0  5542.5     0.1       0
  5698.4    0.08       0  5825.0     0.1       0  5919.7    0.08       0
  6234.0     0.1       0  6432.3    0.08       0  6610.5    0.05       0
  6622.2     0.1       0
Bank Sta=5003.3,5009.3
Exp/Cntr=0.3,0.1

Type RM Length L Ch R = 1,4927,0,0,0
BEGIN DESCRIPTION:
CARTERS CREEK TRIB 17 1.0
END DESCRIPTION:
XS GIS Cut Line= 4
      3564916.41     10217556.05      3565783.75     10216992.84
      3565941.45     10216249.42      3565685.13     10215306.87
#Sta/Elev= 30
  3516.8  256.78  3734.2  256.50  3788.0  257.03  3848.9  255.28  3874.7  253.43
  3927.5  251.48  4045.2  249.61  4108.5  249.73  4150.5  251.54  4196.2  248.98
  4287.4  249.13  4519.4  248.46  4522.2  247.96  4525.4  248.46  4828.2  248.90
  4991.8  250.69  5032.6  250.01  5104.2  252.23  5257.5  253.05  5438.8  257.46
  5536.6  259.18  5554.1  260.42  5619.0  259.87  5651.6  260.19  5733.5  261.67
  5822.2  260.71  5990.7  262.70  6034.0  264.18  6204.5  265.53  6287.7  264.98
#Mann=13,-1,0
  3516.8    0.05       0  3734.2    0.08       0  3788.0    0.05       0
  3874.7    0.08       0  3927.5    0.05       0  4150.5    0.08       0
  4287.4    0.05       0  4519.4    0.04       0  4525.4    0.05       0
  5438.8    0.08       0  5619.0     0.1       0  5651.6    0.08       0
  5990.7     0.1       0
Bank Sta=4519.4,4525.4
Exp/Cntr=0.3,0.1

Chan Stop Cuts=-1