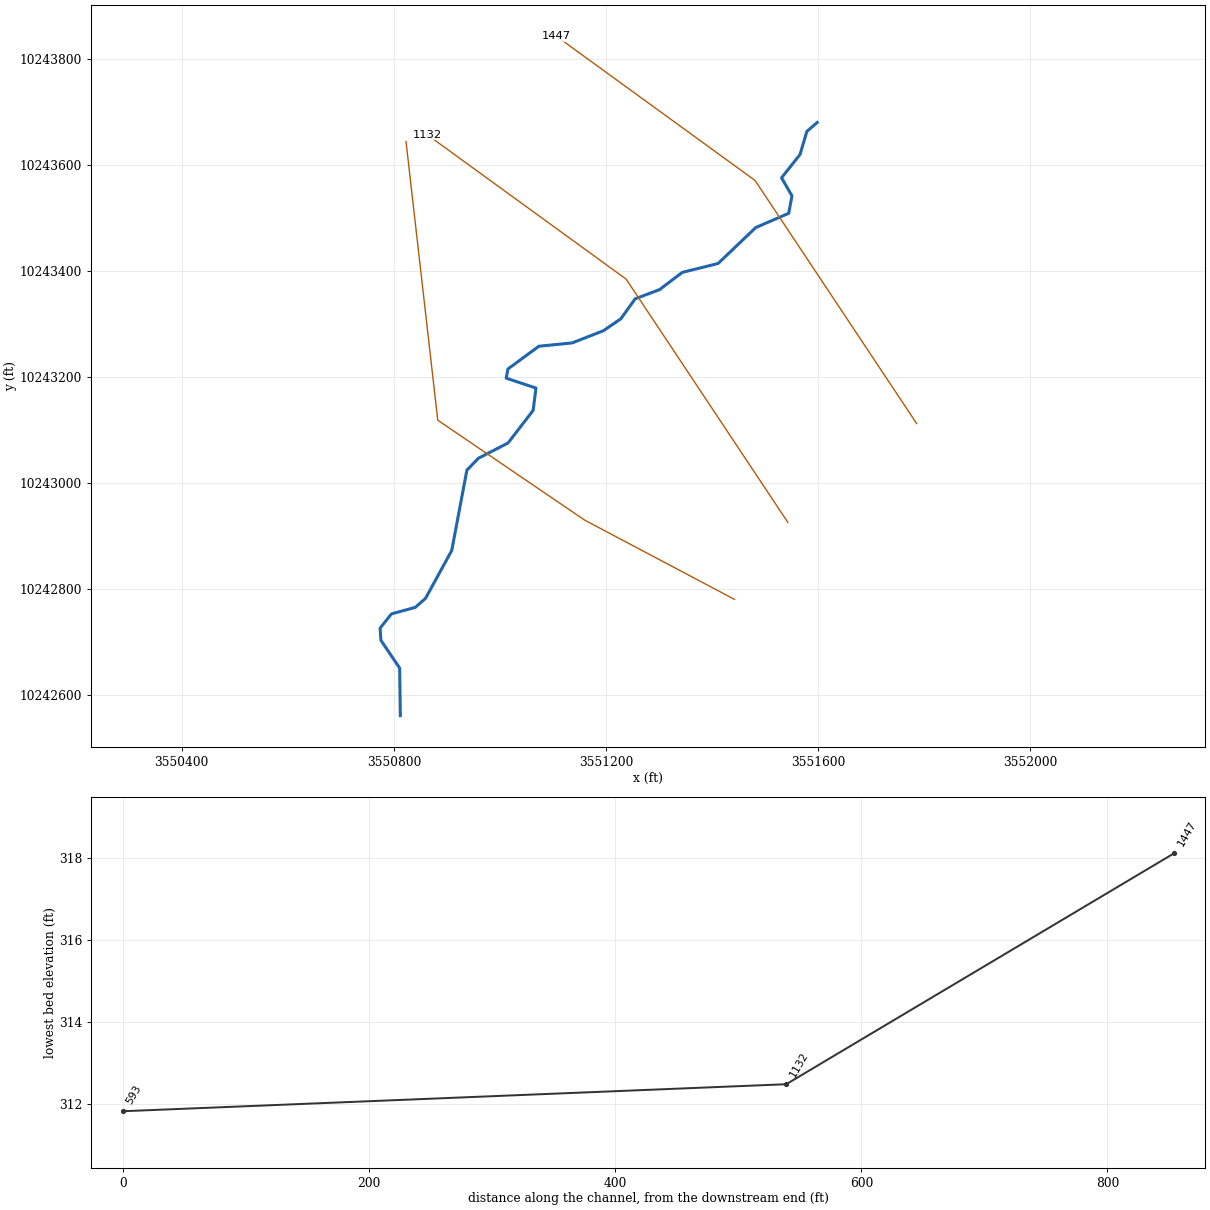
--- CARTERS CREEK TRIB 29.prj (project) ---

Proj Title=CARTERS CREEK TRIB 29 Base Level Engineering
Current Plan=p01
Default Exp/Contr=0.3,0.1
English Units
Geom File=g01
Flow File=f01
Plan File=p01
Y Axis Title=Elevation
X Axis Title(PF)=Main Channel Distance
X Axis Title(XS)=Station
BEGIN DESCRIPTION:
CARTERS CREEK TRIB 29
END DESCRIPTION:
DSS Export Rating Curves= 0
DSS Export Rating Curve Sorted= 0
DSS Export Volume Flow Curves= 0
DXF OffsetX= 0
DXF OffsetY= 0
DXF ScaleX= 1
DXF ScaleY= 10

--- CARTERS CREEK TRIB 29.p01 (plan) ---

Plan Title=Multiple Run
Short Identifier=Multiple
Geom File=g01
Flow File=f01
Subcritical Flow
K Sum by GR= 0
Std Step Tol= 0.01
Critical Tol= 0.01
Num of Std Step Trials= 20
Max Error Tol= 0.3
Flow Tol Ratio= 0.001
Split Flow NTrial= 30
Split Flow Tol= 0.02
Split Flow Ratio= 0.02
Log Output Level= 0
Friction Slope Method= 1
Unsteady Friction Slope Method= 2
Unsteady Bridges Friction Slope Method= 1
Parabolic Critical Depth
Global Vel Dist=  1 , 1 , 1
Global Log Level= 0
CheckData=True
Encroach Param= -1, 0, 0, 0
BEGIN DESCRIPTION:
Multiple Run
END DESCRIPTION:

--- CARTERS CREEK TRIB 29.f01 (steady flow) ---

Flow Title=Multiple
Program Version=4.10
Number of Profiles= 7
Profile Names=10-year,25-year,50-year,1pct_min,100-year,1pct_plu,500-year
River Rch & RM=CARTERS CREEK TR,Reach-1         ,1447
     320     415     489     423     573     774     786
Boundary for River Rch & Prof#=CARTERS CREEK TR,Reach-1         , 1
Up Type= 0
Dn Type= 3
Dn Slope=0.009
Boundary for River Rch & Prof#=CARTERS CREEK TR,Reach-1         , 2
Up Type= 0
Dn Type= 3
Dn Slope=0.009
Boundary for River Rch & Prof#=CARTERS CREEK TR,Reach-1         , 3
Up Type= 0
Dn Type= 3
Dn Slope=0.009
Boundary for River Rch & Prof#=CARTERS CREEK TR,Reach-1         , 4
Up Type= 0
Dn Type= 3
Dn Slope=0.009
Boundary for River Rch & Prof#=CARTERS CREEK TR,Reach-1         , 5
Up Type= 0
Dn Type= 3
Dn Slope=0.009
Boundary for River Rch & Prof#=CARTERS CREEK TR,Reach-1         , 6
Up Type= 0
Dn Type= 3
Dn Slope=0.009
Boundary for River Rch & Prof#=CARTERS CREEK TR,Reach-1         , 7
Up Type= 0
Dn Type= 3
Dn Slope=0.009
DSS Import GetInterval= 0
DSS Import GetPeak= 0
DSS Import FillOption= 0

--- CARTERS CREEK TRIB 29.g01 (geometry) ---

Geom Title=Existing Conditions
Program Version=4.10

River Reach=CARTERS CREEK TR,Reach-1
Reach XY= 30
      3551597.93     10243679.78       3551578.4     10243662.85
       3551565.6     10243619.46      3551530.71     10243575.39
      3551550.34     10243541.47      3551544.24     10243508.53
      3551482.11     10243481.64      3551411.06     10243413.91
      3551343.59     10243397.15       3551300.8     10243364.68
      3551254.72     10243347.26      3551227.77     10243309.64
      3551194.71     10243287.06      3551136.03     10243264.19
      3551073.16     10243257.88      3551014.94     10243215.04
      3551011.69     10243197.68      3551067.84      10243179.1
      3551062.43     10243136.98      3551015.12      10243075.5
      3550959.16      10243046.7      3550937.56     10243024.27
        3550909.     10242872.92      3550859.57     10242782.57
      3550840.31     10242765.69      3550795.44     10242753.43
      3550774.04     10242726.69      3550775.44     10242703.62
      3550810.83     10242651.22      3550812.11     10242561.64

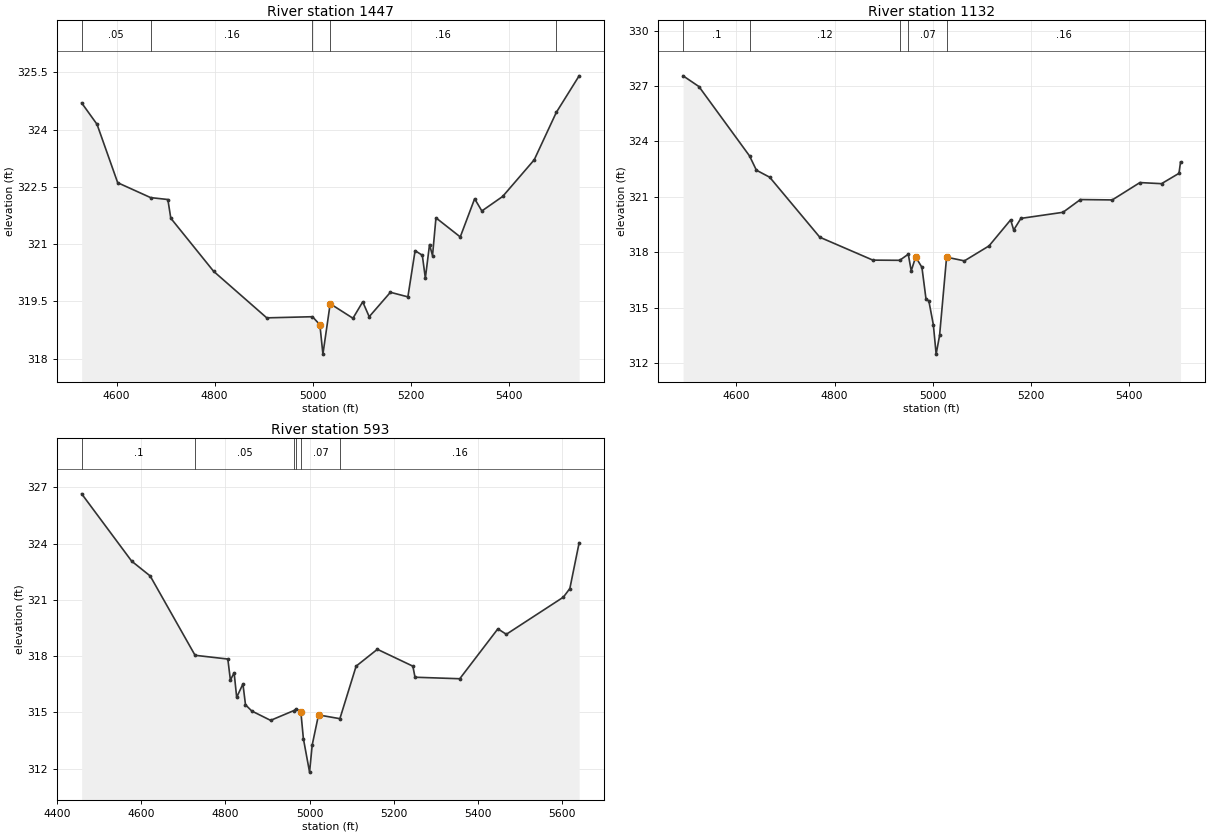
Type RM Length L Ch R = 1 ,1447    ,315,315,315
BEGIN DESCRIPTION:
CARTERS CREEK TRIB 29 2.0
END DESCRIPTION:
XS GIS Cut Line= 3
      3551785.48      10243112.1      3551480.79     10243570.44
      3551106.05     10243842.56
#Sta/Elev= 30
    4529   324.7  4560.3  324.14  4602.4  322.61  4669.5  322.22  4704.6  322.17
  4710.6  321.68  4797.8  320.29  4906.1  319.07  4999.2   319.1  5014.3  318.89
  5020.5  318.12  5035.3  319.44  5081.7  319.06  5101.6  319.49  5114.8   319.1
    5158  319.74  5193.6  319.62  5208.3  320.83    5223  320.71  5229.2  320.11
  5237.7  320.99  5243.8   320.7  5250.8  321.69  5300.3  321.19  5329.6  322.19
  5344.3  321.87  5386.7  322.25    5451  323.21  5495.9  324.45  5542.5  325.41
#Mann= 5 ,-1 , 0
    4529     .05       0  4669.5     .16       0  4999.2     .07       0
  5035.3     .16       0  5495.9     .05       0
Bank Sta=5014.3,5035.3
XS Rating Curve= 0 ,0
Exp/Cntr=0.3,0.1

Type RM Length L Ch R = 1 ,1132    ,539,539,539
BEGIN DESCRIPTION:
CARTERS CREEK TRIB 29 2.1
END DESCRIPTION:
XS GIS Cut Line= 3
       3551542.5     10242926.07      3551237.83     10243384.38
      3550862.41     10243656.99
#Sta/Elev= 30
  4491.2  327.55  4523.5  326.97  4626.8  323.21  4640.7  322.44  4667.8  322.06
    4770  318.81  4878.2  317.57  4932.8  317.56  4950.4  317.89  4956.4  316.99
  4965.4  317.74  4978.2  317.18  4986.4  315.49  4992.4  315.35  5001.5  314.07
  5007.2  312.48  5014.2  313.49  5028.5  317.73  5064.8  317.53    5115  318.34
  5159.1  319.75  5165.3   319.2    5180  319.83  5265.8  320.16  5301.3  320.85
  5366.3  320.83  5422.7  321.77  5466.7  321.71  5502.3  322.27  5505.5  322.88
#Mann= 5 ,-1 , 0
  4491.2      .1       0  4626.8     .12       0  4932.8     .16       0
  4950.4     .07       0  5028.5     .16       0
Bank Sta=4965.4,5028.5
XS Rating Curve= 0 ,0
Exp/Cntr=0.3,0.1

Type RM Length L Ch R = 1 ,593     ,0,0,0
BEGIN DESCRIPTION:
CARTERS CREEK TRIB 29 1.0
END DESCRIPTION:
XS GIS Cut Line= 4
       3551441.8     10242780.86      3551159.63     10242930.13
      3550882.68     10243118.49      3550822.83     10243643.64
#Sta/Elev= 30
  4458.1  326.66    4577  323.07    4621  322.28  4727.7  318.05  4805.6  317.85
  4811.7  316.73  4820.6  317.12  4826.6  315.81  4841.5  316.52  4847.6  315.41
  4862.5  315.08  4907.3  314.58  4962.4   315.1  4968.2  315.19  4979.2  315.03
  4985.2  313.61  4999.9  311.82  5006.2  313.27  5021.2  314.87    5072  314.67
  5110.6  317.47  5161.1  318.37  5245.5  317.47  5250.6  316.88    5357   316.8
  5447.6  319.46  5467.7  319.17  5603.3  321.15  5618.7  321.61  5640.8  324.05
#Mann= 6 ,-1 , 0
  4458.1      .1       0  4727.7     .05       0  4962.4     .12       0
  4968.2     .16       0  4979.2     .07       0    5072     .16       0
Bank Sta=4979.2,5021.2
XS Rating Curve= 0 ,0
Exp/Cntr=0.3,0.1

Chan Stop Cuts=-1
Use User Specified Reach Order=0
Composite Channel Slope=5