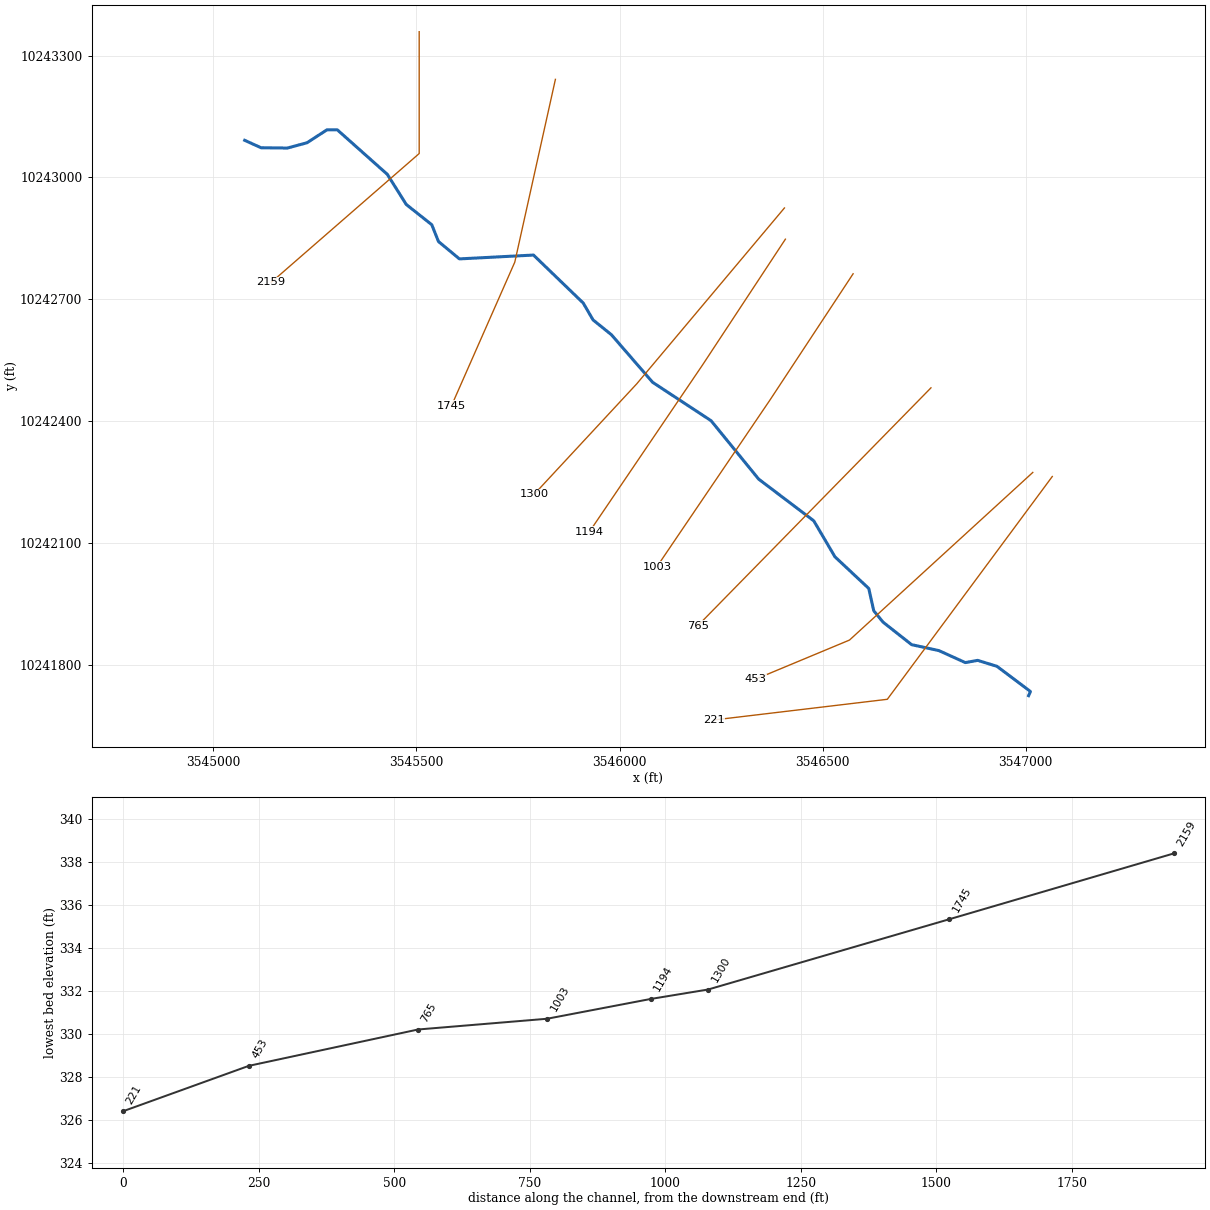
--- CARTERS CREEK TRIB A EAST FORK.prj (project) ---

Proj Title=CARTERS CREEK TRIB A EAST FORK Base Level Engineering
Current Plan=p01
Default Exp/Contr=0.3,0.1
English Units
Geom File=g01
Flow File=f01
Plan File=p01
Y Axis Title=Elevation
X Axis Title(PF)=Main Channel Distance
X Axis Title(XS)=Station
BEGIN DESCRIPTION:
CARTERS CREEK TRIB A EAST FORK
END DESCRIPTION:
DSS Export Rating Curves= 0
DSS Export Rating Curve Sorted= 0
DSS Export Volume Flow Curves= 0
DXF OffsetX= 0
DXF OffsetY= 0
DXF ScaleX= 1
DXF ScaleY= 10

--- CARTERS CREEK TRIB A EAST FORK.p01 (plan) ---

Plan Title=Multiple Run
Short Identifier=Multiple
Geom File=g01
Flow File=f01
Subcritical Flow
K Sum by GR= 0
Std Step Tol= 0.01
Critical Tol= 0.01
Num of Std Step Trials= 20
Max Error Tol= 0.3
Flow Tol Ratio= 0.001
Split Flow NTrial= 30
Split Flow Tol= 0.02
Split Flow Ratio= 0.02
Log Output Level= 0
Friction Slope Method= 1
Unsteady Friction Slope Method= 2
Unsteady Bridges Friction Slope Method= 1
Parabolic Critical Depth
Global Vel Dist=  1 , 1 , 1
Global Log Level= 0
CheckData=True
Encroach Param= -1, 0, 0, 0
BEGIN DESCRIPTION:
Multiple Run
END DESCRIPTION:

--- CARTERS CREEK TRIB A EAST FORK.f01 (steady flow) ---

Flow Title=Multiple
Program Version=4.10
Number of Profiles= 7
Profile Names=10-year,25-year,50-year,1pct_min,100-year,1pct_plu,500-year
River Rch & RM=CARTERS CREEK TR,Reach-1         ,2159
     182     227     262     222     301     407     395
Boundary for River Rch & Prof#=CARTERS CREEK TR,Reach-1         , 1
Up Type= 0
Dn Type= 1
Dn Known WS=326.68
Boundary for River Rch & Prof#=CARTERS CREEK TR,Reach-1         , 2
Up Type= 0
Dn Type= 1
Dn Known WS=327.04
Boundary for River Rch & Prof#=CARTERS CREEK TR,Reach-1         , 3
Up Type= 0
Dn Type= 1
Dn Known WS=327.31
Boundary for River Rch & Prof#=CARTERS CREEK TR,Reach-1         , 4
Up Type= 0
Dn Type= 1
Dn Known WS=327.11
Boundary for River Rch & Prof#=CARTERS CREEK TR,Reach-1         , 5
Up Type= 0
Dn Type= 1
Dn Known WS=327.51
Boundary for River Rch & Prof#=CARTERS CREEK TR,Reach-1         , 6
Up Type= 0
Dn Type= 1
Dn Known WS=327.88
Boundary for River Rch & Prof#=CARTERS CREEK TR,Reach-1         , 7
Up Type= 0
Dn Type= 1
Dn Known WS=327.94
DSS Import GetInterval= 0
DSS Import GetPeak= 0
DSS Import FillOption= 0

--- CARTERS CREEK TRIB A EAST FORK.g01 (geometry) ---

Geom Title=Existing Conditions
Program Version=4.10

River Reach=CARTERS CREEK TR,Reach-1
Reach XY= 30
      3545076.95     10243091.57      3545117.47     10243073.25
      3545182.19     10243072.51      3545230.55     10243085.57
      3545279.39     10243117.29      3545304.99     10243117.46
      3545428.22     10243007.76      3545474.89     10242933.55
      3545537.69     10242883.71      3545554.21     10242842.31
      3545605.78     10242799.58      3545788.16     10242809.01
      3545910.56     10242690.95      3545934.86     10242649.29
        3545980.     10242612.83      3546081.57     10242495.64
      3546225.42     10242401.16      3546342.53     10242257.37
      3546478.26     10242154.64      3546530.42     10242066.04
      3546613.69     10241988.07      3546626.03     10241933.11
      3546648.69     10241905.31      3546719.19      10241849.7
      3546786.43     10241835.05      3546851.53     10241805.54
      3546881.85     10241811.02      3546929.35     10241796.38
      3547011.84     10241734.36      3547007.27     10241724.01

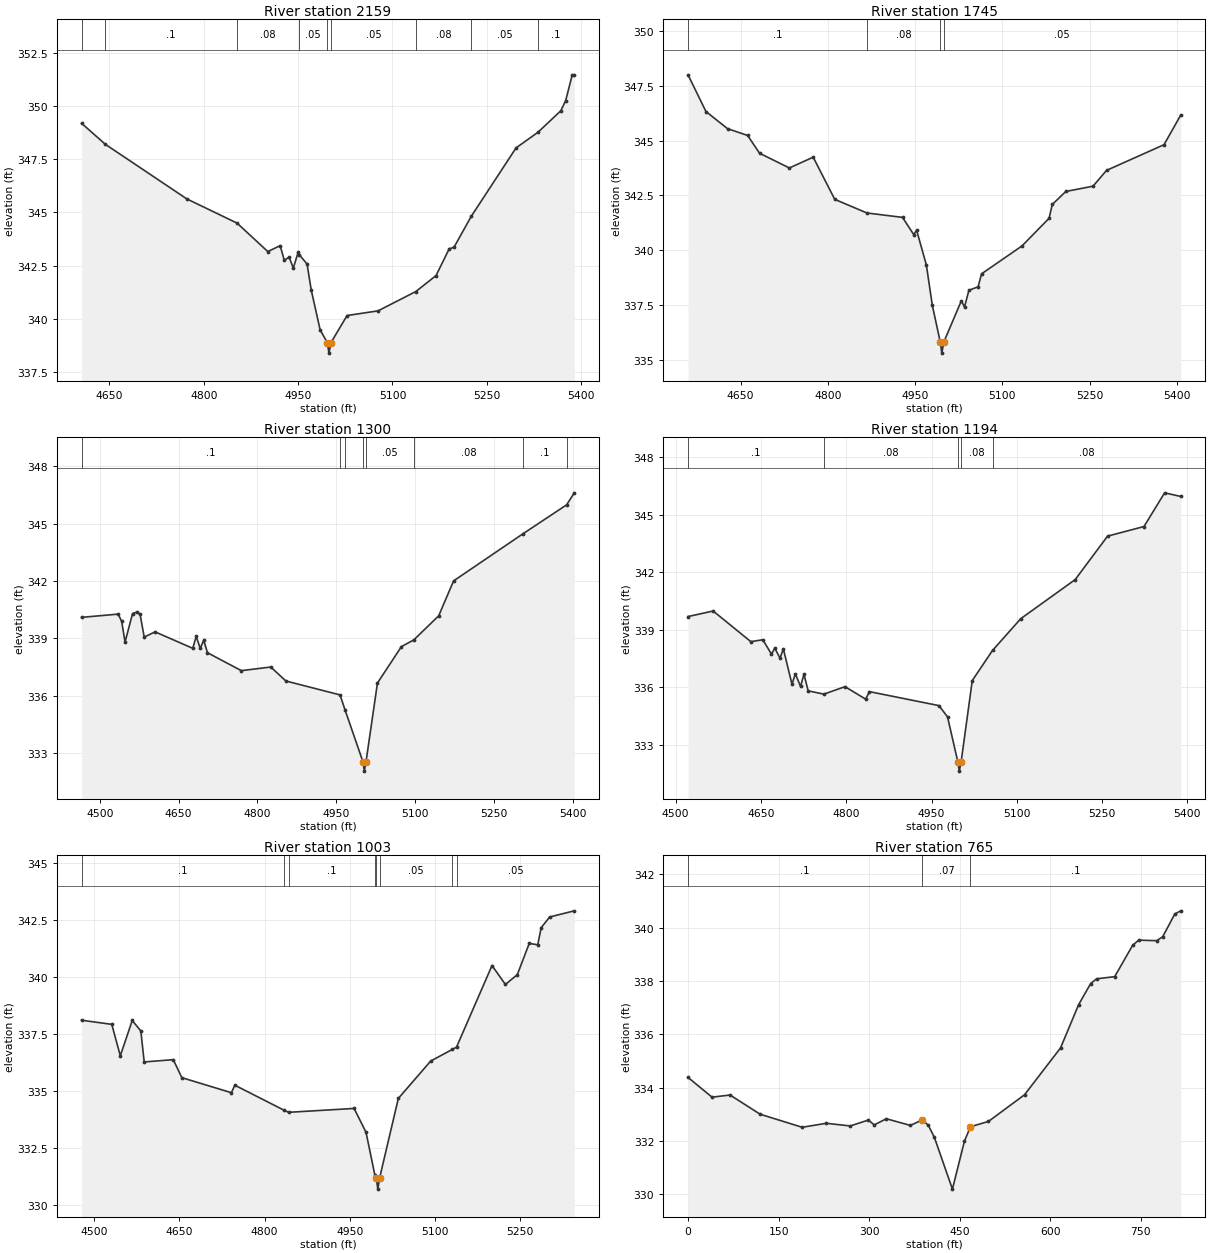
Type RM Length L Ch R = 1 ,2159    ,414,414,414
BEGIN DESCRIPTION:
CARTERS CREEK TRIB A EAST FORK 5.0
END DESCRIPTION:
XS GIS Cut Line= 3
      3545506.69     10243358.96      3545506.69       10243059.
      3545142.12     10242741.65
#Sta/Elev= 30
  4605.8   349.2  4643.6  348.21  4773.1  345.64    4853   344.5  4901.9  343.16
  4921.5  343.44  4928.1  342.75  4935.8   342.9  4942.4  342.38    4950  343.12
  4951.8  343.02  4964.3  342.57  4970.9  341.35  4985.1  339.47  4996.4  338.88
  4999.1  338.38  5002.4  338.88  5027.9  340.15  5077.2  340.37  5137.2  341.28
  5169.3  342.03  5190.2  343.29  5197.8  343.36  5225.3  344.82  5296.5  348.04
  5331.5  348.78  5367.7  349.79  5375.4  350.27  5385.8  351.48  5389.1  351.48
#Mann= 9 ,-1 , 0
  4605.8     .05       0  4643.6      .1       0    4853     .08       0
  4951.8     .05       0  4996.4     .04       0  5002.4     .05       0
  5137.2     .08       0  5225.3     .05       0  5331.5      .1       0
Bank Sta=4996.4,5002.4
XS Rating Curve= 0 ,0
Exp/Cntr=0.3,0.1

Type RM Length L Ch R = 1 ,1745    ,445,445,445
BEGIN DESCRIPTION:
CARTERS CREEK TRIB A EAST FORK 4.0
END DESCRIPTION:
XS GIS Cut Line= 3
      3545842.11     10243241.68      3545742.11     10242791.64
      3545586.36     10242438.25
#Sta/Elev= 30
  4559.6  347.99  4590.4  346.32  4627.5  345.54  4662.1  345.23  4682.6  344.42
  4733.8  343.75  4774.8  344.24  4811.9  342.32  4867.2   341.7  4928.4   341.5
  4947.6  340.72  4952.7  340.91  4969.4  339.33  4979.6   337.5  4993.3  335.82
    4996  335.32  4999.3  335.82  5029.5   337.7    5035  337.42  5042.5  338.18
  5058.3  338.34  5064.3  338.93  5133.8   340.2  5180.4  341.46  5185.9  342.09
  5209.2  342.68  5255.9  342.92  5279.2  343.64    5378  344.81  5406.8  346.16
#Mann= 4 ,-1 , 0
  4559.6      .1       0  4867.2     .08       0  4993.3     .03       0
  4999.3     .05       0
Bank Sta=4993.3,4999.3
XS Rating Curve= 0 ,0
Exp/Cntr=0.3,0.1

Type RM Length L Ch R = 1 ,1300    ,106,106,106
BEGIN DESCRIPTION:
CARTERS CREEK TRIB A EAST FORK 3.0
END DESCRIPTION:
XS GIS Cut Line= 3
      3546406.07     10242924.99      3546042.11     10242491.64
      3545789.68     10242219.77
#Sta/Elev= 30
  4465.5   340.1  4535.1  340.27  4541.7   339.9  4548.2  338.81  4562.5   340.3
  4570.3  340.37  4576.8  340.26  4584.6  339.07  4605.4  339.34  4676.9  338.48
  4683.5   339.1  4691.2  338.48  4697.8   338.9  4704.9  338.25  4769.3  337.31
  4825.3   337.5  4853.9  336.77    4957  336.04  4966.8  335.23  5000.4  332.55
  5003.2  332.05  5006.4  332.55  5028.1  336.66  5073.7  338.57  5097.2  338.92
  5144.5  340.18  5172.9  342.01    5305  344.48  5387.7  345.99  5402.4  346.62
#Mann= 8 ,-1 , 0
  4465.5      .1       0    4957     .08       0  4966.8     .05       0
  5000.4     .04       0  5006.4     .05       0  5097.2     .08       0
    5305      .1       0  5387.7     .15       0
Bank Sta=5000.4,5006.4
XS Rating Curve= 0 ,0
Exp/Cntr=0.3,0.1

Type RM Length L Ch R = 1 ,1194    ,191,191,191
BEGIN DESCRIPTION:
CARTERS CREEK TRIB A EAST FORK 2.1
END DESCRIPTION:
XS GIS Cut Line= 3
      3546408.43     10242848.13      3546204.21      10242538.1
       3545926.2     10242128.12
#Sta/Elev= 30
  4521.7  339.68  4565.9  339.97  4632.2  338.37  4653.3  338.47  4668.4  337.72
  4674.3  338.03  4683.4  337.51  4689.4  337.99  4704.5  336.15  4710.5  336.69
  4719.6  336.03  4725.6  336.67    4733   335.8  4760.7  335.63  4797.8  336.02
    4834  335.37  4840.8  335.76  4963.1  335.03  4978.1  334.44  4996.1  332.11
  4998.8  331.61  5002.1  332.11  5021.6  336.34  5057.2  337.91  5106.9  339.57
  5202.6  341.61  5259.6  343.88  5323.6  344.38  5359.9  346.14  5388.3  345.95
#Mann= 5 ,-1 , 0
  4521.7      .1       0  4760.7     .08       0  4996.1     .07       0
  5002.1     .08       0  5057.2     .08       0
Bank Sta=4996.1,5002.1
XS Rating Curve= 0 ,0
Exp/Cntr=0.3,0.1

Type RM Length L Ch R = 1 ,1003    ,238,238,238
BEGIN DESCRIPTION:
CARTERS CREEK TRIB A EAST FORK 2.0
END DESCRIPTION:
XS GIS Cut Line= 3
      3546575.16     10242762.88      3546370.98      10242452.9
      3546092.09     10242041.62
#Sta/Elev= 30
  4477.5   338.1  4530.7  337.92  4545.8  336.54  4566.8  338.09  4581.9  337.63
  4587.9  336.27  4639.1  336.37  4654.2  335.58  4741.5  334.92  4747.5  335.25
  4833.6  334.16  4842.2  334.06  4957.7  334.23  4978.7  333.18  4994.1  331.32
  4996.7  331.19  4999.4  330.69  5002.7  331.19  5035.6  334.67  5092.6  336.31
  5130.9  336.82  5138.1  336.92  5200.6   340.5  5224.2  339.67  5245.2   340.1
  5266.2  341.47  5281.2  341.41  5287.2  342.16  5302.2  342.63  5345.6   342.9
#Mann= 8 ,-1 , 0
  4477.5      .1       0  4833.6     .08       0  4842.2      .1       0
  4994.1     .05       0  4996.7     .04       0  5002.7     .05       0
  5130.9     .08       0  5138.1     .05       0
Bank Sta=4996.7,5002.7
XS Rating Curve= 0 ,0
Exp/Cntr=0.3,0.1

Type RM Length L Ch R = 1 ,765     ,312,312,312
XS GIS Cut Line= 2
     3546766.854    10242482.061      3546192.09    10241895.724
#Sta/Elev= 30
       0  334.38   39.81  333.64   69.66  333.72  119.42     333  189.09  332.51
   228.9  332.66  268.71  332.56  298.56  332.78  308.51   332.6  328.42  332.83
  368.23  332.58  388.13  332.79  398.08  332.58  408.03  332.13  437.89  330.19
  457.79  331.99  467.75  332.53   497.6  332.73  557.32  333.73  617.03  335.49
  646.88  337.11  666.79   337.9  676.74  338.08   706.6  338.16  736.45  339.34
   746.4  339.53  776.26  339.51  786.21  339.66  806.12  340.51  816.07  340.63
#Mann= 3 ,-1 , 0
       0      .1       0  388.13     .07       0  467.75      .1       0
Bank Sta=388.13,467.75
XS Rating Curve= 0 ,0
Exp/Cntr=0.3,0.1

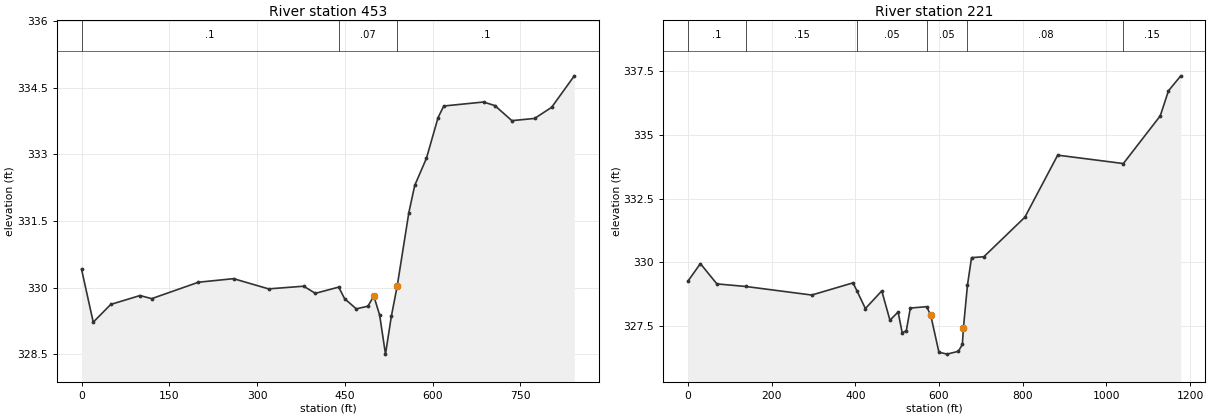
Type RM Length L Ch R = 1 ,453     ,232,232,232
XS GIS Cut Line= 3
     3547017.591    10242273.757     3546566.265    10241861.007
     3546334.817     10241764.57
#Sta/Elev= 30
       0  330.41   19.98  329.22   49.95  329.62   99.91  329.82  119.89  329.75
  199.82  330.12  259.77   330.2  319.71  329.97  379.66  330.03  399.64  329.87
   439.6  330.01  449.59  329.75  469.58  329.52  489.56  329.58  499.55  329.81
  509.54  329.38  519.53   328.5  529.52  329.35  539.51  330.03  559.49  331.69
  569.49   332.3  589.47  332.91  609.45  333.83  619.15  334.09  687.07  334.18
  706.47   334.1  735.58  333.76  774.38  333.81  803.49  334.06   842.3  334.77
#Mann= 3 ,-1 , 0
       0      .1       0   439.6     .07       0  539.51      .1       0
Bank Sta=499.55,539.51
XS Rating Curve= 0 ,0
Exp/Cntr=0.3,0.1

Type RM Length L Ch R = 1 ,221     ,0,0,0
BEGIN DESCRIPTION:
CARTERS CREEK TRIB A EAST FORK 1.0
END DESCRIPTION:
XS GIS Cut Line= 3
      3547065.62     10242263.76      3546659.38     10241715.16
      3546231.95      10241664.2
#Sta/Elev= 30
       0329.262129.58172 329.94569.02402329.1481 138.048329.0469295.8172328.7106
 394.423329.1891404.2836328.8606424.0047328.1793 463.233328.8729482.7401327.7213
502.2472328.0434512.0008327.2312521.7543327.3031531.5079328.1988570.5222328.2535
580.2757327.9162599.7828326.4658  619.29326.3887  646.36   326.5  655.91  326.77
658.3042327.4026668.0577329.0971677.8113330.1795707.2374330.2151805.3245331.7687
883.7942334.20721040.734333.87721129.012335.75131148.629336.73591178.055337.3239
#Mann= 6 ,-1 , 0
       0      .1       0 138.048     .15       0404.2836     .05       0
570.5222     .05       0668.0577     .08       01040.734     .15       0
Bank Sta=580.2757,658.3042
XS Rating Curve= 0 ,0
Exp/Cntr=0.3,0.1
Stream Node=CARTERS CREEK TR,Reach-1         , 0 , 0 ,Upstream end
Stream Node=CARTERS CREEK TR,Reach-1         , 0 , 1 ,Downstream end

Chan Stop Cuts=-1
Use User Specified Reach Order=0
Composite Channel Slope=5