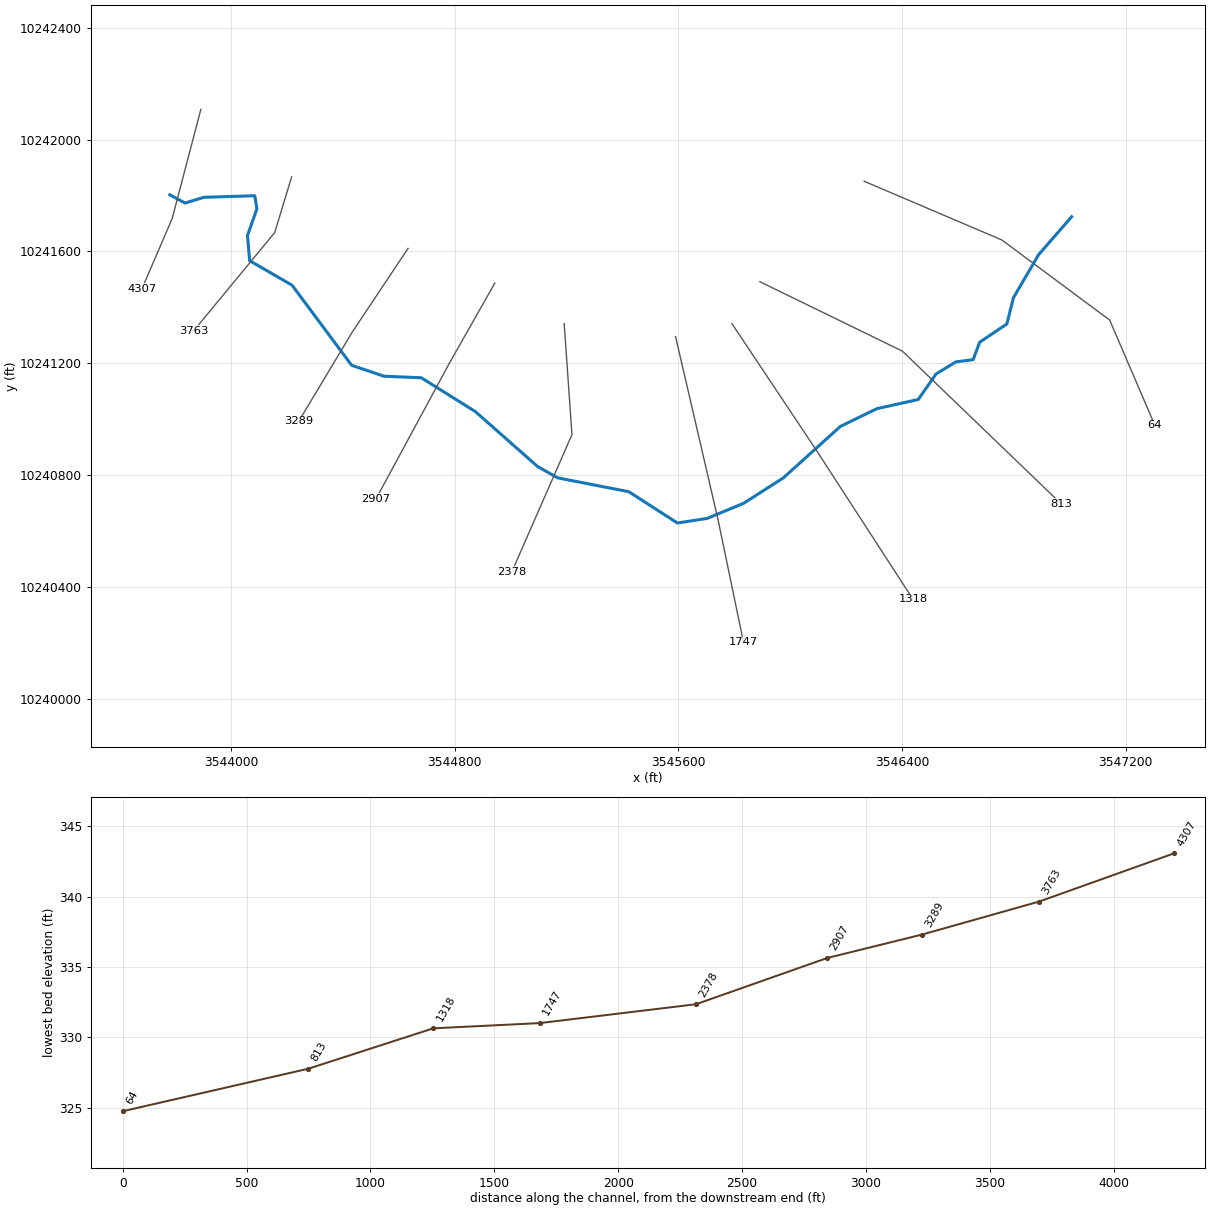
--- CARTERS CREEK TRIB A WEST FORK.prj (project) ---

Proj Title=CARTERS CREEK TRIB A WEST FORK Base Level Engineering
Current Plan=p01
Default Exp/Contr=0.3,0.1
English Units
Geom File=g01
Flow File=f01
Plan File=p01
Y Axis Title=Elevation
X Axis Title(PF)=Main Channel Distance
X Axis Title(XS)=Station
BEGIN DESCRIPTION:
CARTERS CREEK TRIB A WEST FORK
END DESCRIPTION:
DSS Export Rating Curves= 0
DSS Export Rating Curve Sorted= 0
DSS Export Volume Flow Curves= 0
DXF OffsetX= 0
DXF OffsetY= 0
DXF ScaleX= 1
DXF ScaleY= 10

--- CARTERS CREEK TRIB A WEST FORK.p01 (plan) ---

Plan Title=Multiple Run
Short Identifier=Multiple
Geom File=g01
Flow File=f01
Subcritical Flow
K Sum by GR= 0
Std Step Tol= 0.01
Critical Tol= 0.01
Num of Std Step Trials= 20
Max Error Tol= 0.3
Flow Tol Ratio= 0.001
Split Flow NTrial= 30
Split Flow Tol= 0.02
Split Flow Ratio= 0.02
Log Output Level= 0
Friction Slope Method= 1
Unsteady Friction Slope Method= 2
Unsteady Bridges Friction Slope Method= 1
Parabolic Critical Depth
Global Vel Dist=  1 , 1 , 1
Global Log Level= 0
CheckData=True
Encroach Param= -1, 0, 0, 0
BEGIN DESCRIPTION:
Multiple Run
END DESCRIPTION:

--- CARTERS CREEK TRIB A WEST FORK.f01 (steady flow) ---

Flow Title=Multiple
Program Version=4.10
Number of Profiles= 7
Profile Names=10-year,25-year,50-year,1pct_min,100-year,1pct_plu,500-year
River Rch & RM=CARTERS CREEK TR,Reach-1         ,4307
     307     397     466     402     544     736     742
Boundary for River Rch & Prof#=CARTERS CREEK TR,Reach-1         , 1
Up Type= 0
Dn Type= 1
Dn Known WS=326.68
Boundary for River Rch & Prof#=CARTERS CREEK TR,Reach-1         , 2
Up Type= 0
Dn Type= 1
Dn Known WS=327.04
Boundary for River Rch & Prof#=CARTERS CREEK TR,Reach-1         , 3
Up Type= 0
Dn Type= 1
Dn Known WS=327.31
Boundary for River Rch & Prof#=CARTERS CREEK TR,Reach-1         , 4
Up Type= 0
Dn Type= 1
Dn Known WS=327.11
Boundary for River Rch & Prof#=CARTERS CREEK TR,Reach-1         , 5
Up Type= 0
Dn Type= 1
Dn Known WS=327.51
Boundary for River Rch & Prof#=CARTERS CREEK TR,Reach-1         , 6
Up Type= 0
Dn Type= 1
Dn Known WS=327.88
Boundary for River Rch & Prof#=CARTERS CREEK TR,Reach-1         , 7
Up Type= 0
Dn Type= 1
Dn Known WS=327.94
DSS Import GetInterval= 0
DSS Import GetPeak= 0
DSS Import FillOption= 0

--- CARTERS CREEK TRIB A WEST FORK.g01 (geometry) ---

Geom Title=Existing Conditions
Program Version=4.10

River Reach=CARTERS CREEK TR,Reach-1
Reach XY= 30
      3543781.18     10241802.63      3543835.65     10241773.11
      3543904.01     10241793.73      3544085.22     10241799.16
      3544092.81      10241752.5      3544059.18     10241657.01
      3544066.77     10241566.95      3544218.68     10241479.06
      3544431.77     10241192.66      3544547.72     10241153.53
      3544680.64      10241148.1      3544873.91     10241027.35
      3545096.68     10240830.78      3545168.73     10240789.98
      3545423.07      10240740.5      3545597.19     10240628.45
      3545703.45     10240645.02      3545833.66     10240698.84
      3545976.02     10240789.98      3546180.02     10240974.01
      3546310.23     10241037.38      3546458.66     10241070.37
      3546522.03     10241161.51      3546593.21     10241204.91
      3546654.84     10241212.73      3546678.28     10241275.23
       3546775.5     10241340.33      3546798.94     10241434.08
      3546889.22     10241588.59      3547007.27     10241724.01

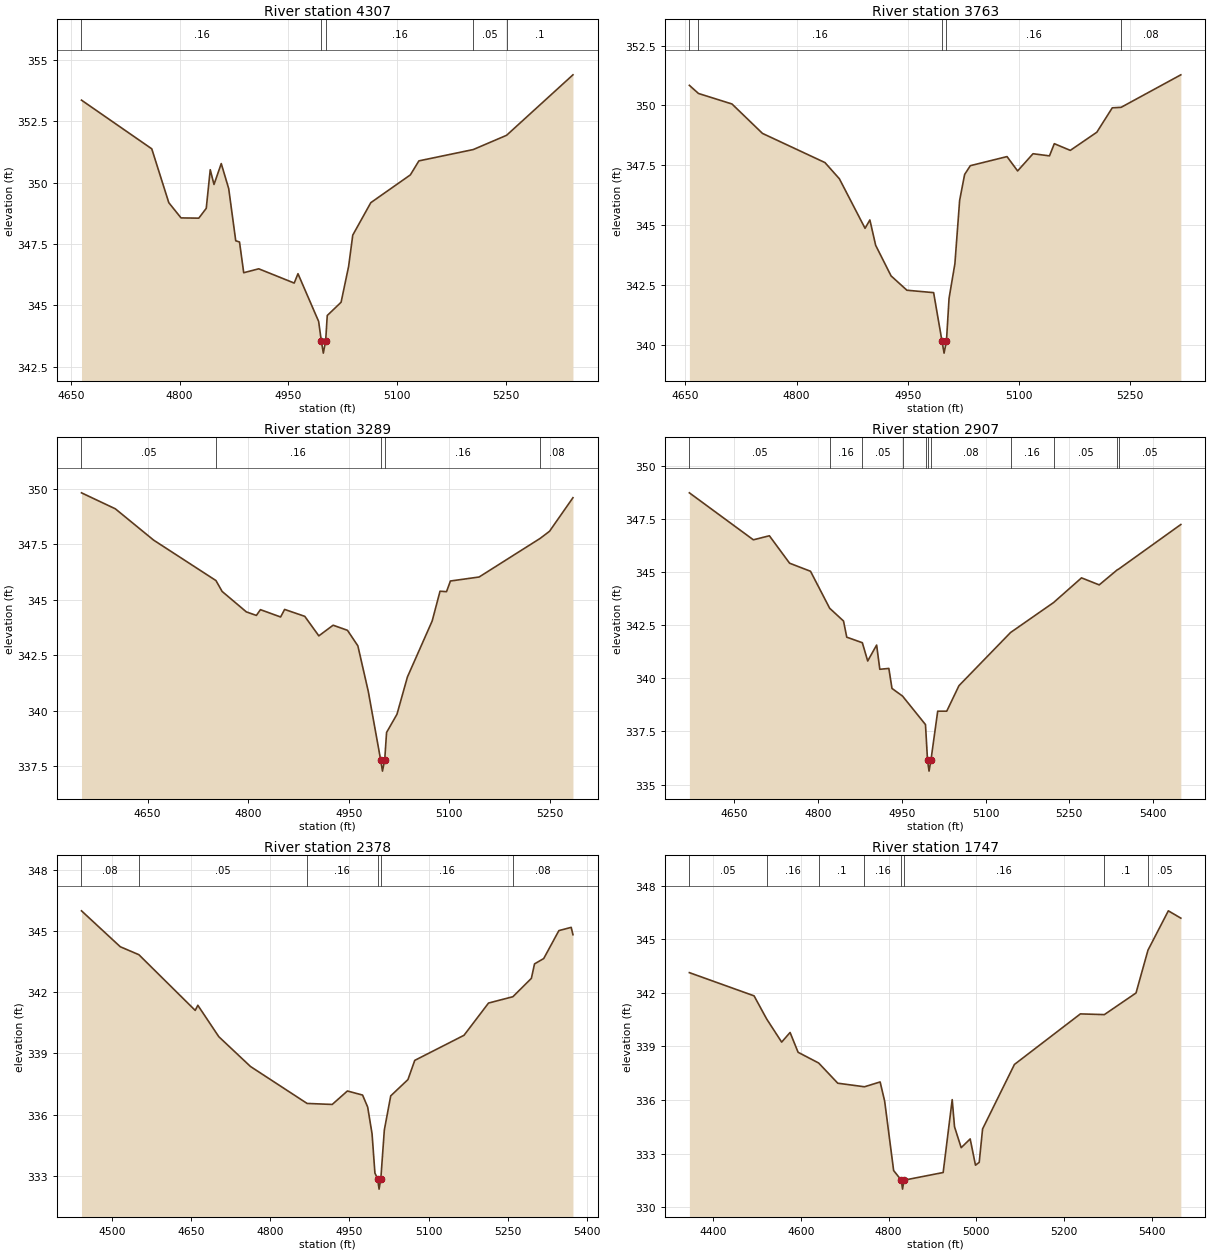
Type RM Length L Ch R = 1 ,4307    ,544,544,544
BEGIN DESCRIPTION:
UNT070 IN GIBB 10.0
END DESCRIPTION:
XS GIS Cut Line= 3
      3543892.34     10242108.21       3543789.7     10241717.43
      3543681.13     10241465.57
#Sta/Elev= 30
  4664.6  353.35  4761.6  351.37  4785.1  349.18    4802  348.56  4826.5  348.55
  4836.8  348.95  4842.3  350.52  4847.5  349.92  4857.5  350.77  4867.8  349.75
  4877.5  347.63  4882.7  347.58  4888.5  346.33  4909.2  346.49  4958.2  345.91
  4963.4  346.29  4991.9  344.35  4995.6  343.56  4998.4  343.06  5001.6  343.56
  5003.8  344.59  5022.9  345.13  5033.3  346.59    5039  347.86  5063.9  349.18
  5118.5  350.31  5130.3  350.88  5205.3  351.34  5251.3  351.92  5342.9  354.38
#Mann= 5 ,-1 , 0
  4664.6     .16       0  4995.6     .07       0  5001.6     .16       0
  5205.3     .05       0  5251.3      .1       0
Bank Sta=4995.6,5001.6
XS Rating Curve= 0 ,0
Exp/Cntr=0.3,0.1

Type RM Length L Ch R = 1 ,3763    ,474,474,474
BEGIN DESCRIPTION:
UNT070 IN GIBB 9.0
END DESCRIPTION:
XS GIS Cut Line= 3
       3544217.1     10241866.63      3544156.53     10241667.35
       3543867.1     10241316.64
#Sta/Elev= 30
  4655.4  350.84  4667.7   350.5  4712.9  350.06    4754  348.83  4838.3  347.61
  4857.8  346.93  4892.4  344.86  4898.9  345.21  4906.7  344.15  4927.5  342.87
  4948.9  342.27  4984.9  342.17  4996.2  340.14    4999  339.64  5002.2  340.14
  5005.7  341.93  5013.6  343.38    5020  346.03  5026.7  347.11  5034.4  347.48
  5083.9  347.86  5098.2  347.26    5119  347.98  5141.2  347.89  5147.7   348.4
  5169.3  348.12  5205.1  348.88  5225.9   349.9  5237.8  349.92  5318.4  351.28
#Mann= 5 ,-1 , 0
  4655.4     .05       0  4667.7     .16       0  4996.2     .07       0
  5002.2     .16       0  5237.8     .08       0
Bank Sta=4996.2,5002.2
XS Rating Curve= 0 ,0
Exp/Cntr=0.3,0.1

Type RM Length L Ch R = 1 ,3289    ,382,382,382
BEGIN DESCRIPTION:
UNT070 IN GIBB 7.0
END DESCRIPTION:
XS GIS Cut Line= 3
       3544633.6     10241610.91       3544433.6     10241310.91
      3544242.13     10240991.68
#Sta/Elev= 30
  4551.5  349.82    4602   349.1  4659.1  347.69    4752  345.87  4761.2  345.38
  4797.3  344.46  4812.3   344.3  4818.3  344.56  4848.4  344.23  4854.4  344.57
  4884.4  344.26  4905.4  343.38  4926.7  343.86  4948.1  343.63  4963.6  342.93
  4979.2  340.87  4997.6  337.79  5000.3  337.29  5003.6  337.79  5006.4  339.03
  5021.9  339.85  5037.5  341.53  5074.4  344.05  5086.1  345.39  5095.8  345.37
  5101.6  345.85  5144.4  346.03  5235.5  347.77  5249.4  348.09  5284.3   349.6
#Mann= 5 ,-1 , 0
  4551.5     .05       0    4752     .16       0  4997.6     .07       0
  5003.6     .16       0  5235.5     .08       0
Bank Sta=4997.6,5003.6
XS Rating Curve= 0 ,0
Exp/Cntr=0.3,0.1

Type RM Length L Ch R = 1 ,2907    ,529,529,529
BEGIN DESCRIPTION:
UNT070 IN GIBB 6.0
END DESCRIPTION:
XS GIS Cut Line= 3
      3544943.71     10241486.24      3544781.34     10241200.22
      3544519.15     10240715.13
#Sta/Elev= 30
  4569.5  348.72  4684.1  346.51  4712.8   346.7    4749  345.41  4786.5  345.03
  4820.8  343.29  4845.6  342.69  4851.4  341.93  4879.3  341.67  4888.9  340.81
  4904.9  341.56  4910.6  340.42  4926.8  340.46  4932.4  339.52  4951.3  339.16
  4992.4  337.82  4993.7  337.23  4996.1  336.13  4998.8  335.63  5002.1  336.13
  5014.3  338.45  5030.5  338.45  5052.4  339.65  5144.8  342.15  5221.9  343.56
  5271.9  344.72  5303.6  344.39    5336   345.1  5338.3  345.13  5449.8  347.23
#Mann= 11 ,-1 , 0
  4569.5     .05       0  4820.8     .16       0  4879.3     .05       0
  4951.3     .16       0  4993.7     .08       0  4996.1     .07       0
  5002.1     .08       0  5144.8     .16       0  5221.9     .05       0
    5336     .08       0  5338.3     .05       0
Bank Sta=4996.1,5002.1
XS Rating Curve= 0 ,0
Exp/Cntr=0.3,0.1

Type RM Length L Ch R = 1 ,2378    ,631,631,631
BEGIN DESCRIPTION:
UNT070 IN GIBB 5.0
END DESCRIPTION:
XS GIS Cut Line= 3
      3545192.11     10241341.61      3545219.73     10240944.45
       3545005.2     10240454.91
#Sta/Elev= 30
  4441.5  345.99  4515.1  344.23  4550.4  343.84  4657.3  341.11  4662.3  341.36
  4702.1  339.82  4762.2  338.36  4869.6  336.55  4917.3   336.5  4946.1  337.16
  4974.9  336.96  4984.6  336.37  4992.9  335.06  4998.3  333.14  5003.5  332.85
  5006.2  332.35  5009.5  332.85  5016.2  335.25  5028.3  336.92    5061  337.72
  5073.9  338.66  5167.4  339.89  5213.9  341.47  5260.1  341.78  5295.2  342.68
  5301.2  343.39  5318.6  343.65  5347.4  345.02  5370.8  345.18  5374.1  344.82
#Mann= 6 ,-1 , 0
  4441.5     .08       0  4550.4     .05       0  4869.6     .16       0
  5003.5     .07       0  5009.5     .16       0  5260.1     .08       0
Bank Sta=5003.5,5009.5
XS Rating Curve= 0 ,0
Exp/Cntr=0.3,0.1

Type RM Length L Ch R = 1 ,1747    ,429,429,429
BEGIN DESCRIPTION:
UNT070 IN GIBB 4.0
END DESCRIPTION:
XS GIS Cut Line= 3
      3545590.41      10241295.3      3545742.11     10240641.64
      3545833.46     10240201.56
#Sta/Elev= 30
  4345.8  343.13  4493.3  341.83  4521.9  340.54  4556.2  339.24  4575.4  339.78
  4593.7  338.67  4640.6  338.07  4684.1  336.94    4745  336.74  4780.7  337.01
    4791  335.94  4811.5  332.05    4829  331.51  4831.8  331.01    4835  331.51
  4924.4  331.94    4945  336.02  4950.3   334.5  4965.5  333.33    4986  333.82
  4998.1  332.35  5006.6  332.51  5014.3  334.38  5086.9  337.99  5237.3  340.82
  5291.9  340.78  5364.1  341.99  5391.4  344.39  5437.8  346.59  5466.3  346.18
#Mann= 8 ,-1 , 0
  4345.8     .05       0  4521.9     .16       0  4640.6      .1       0
    4745     .16       0    4829     .07       0    4835     .16       0
  5291.9      .1       0  5391.4     .05       0
Bank Sta=4829,4835
XS Rating Curve= 0 ,0
Exp/Cntr=0.3,0.1

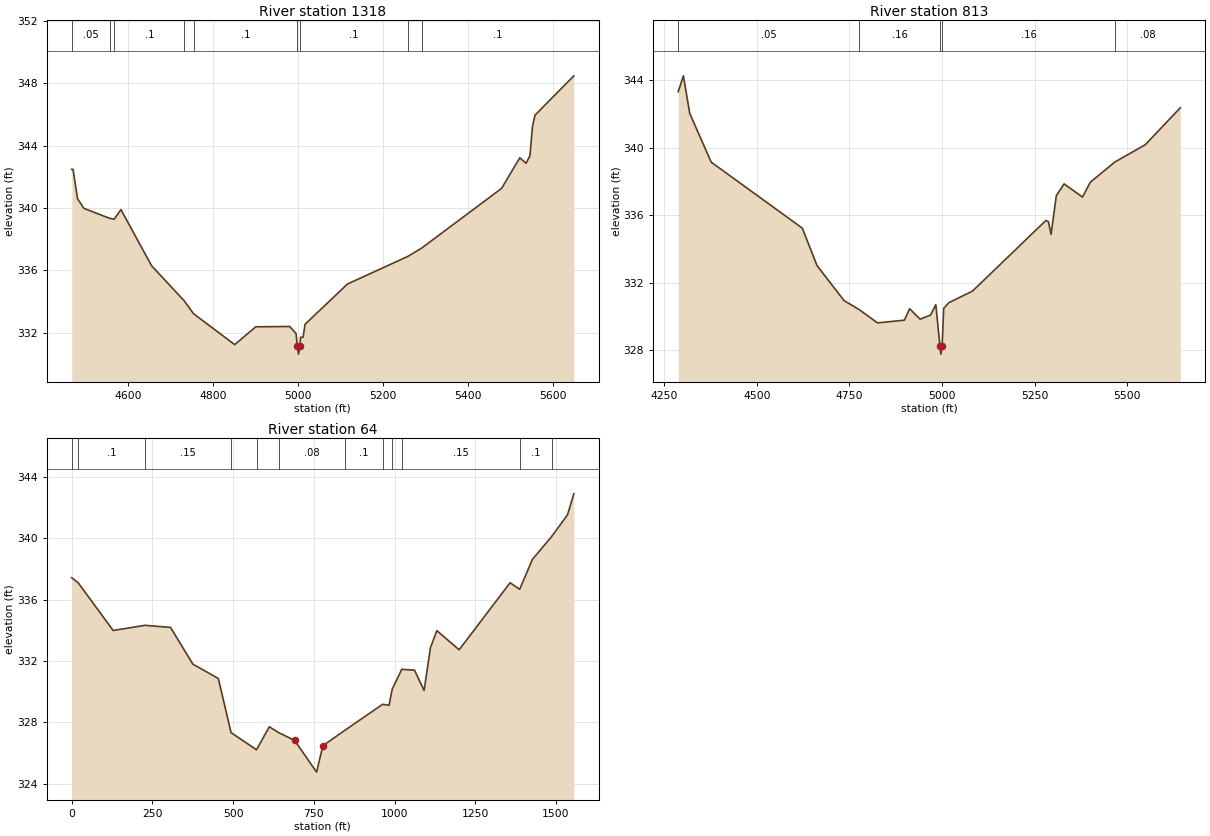
Type RM Length L Ch R = 1 ,1318    ,505,505,505
BEGIN DESCRIPTION:
UNT070 IN GIBB 3.0
END DESCRIPTION:
XS GIS Cut Line= 3
      3545792.13      10241341.6      3546092.11     10240891.64
      3546440.05     10240355.07
#Sta/Elev= 30
    4468  342.48    4471  342.48  4481.5   340.6  4496.5  339.98  4556.9  339.34
  4567.8  339.29  4583.6   339.9  4655.7   336.3  4732.5  334.05  4754.2  333.23
    4851  331.25  4900.6  332.39  4980.2  332.41  4995.3  331.96  4998.3  331.14
    5001  330.64  5004.3  331.14  5005.8  331.72  5011.8  331.72  5016.4  332.55
  5116.1  335.13    5258   336.9  5290.4  337.43  5478.5  341.26  5521.3  343.22
  5535.9  342.87  5545.1  343.35    5551  345.21    5557  345.95  5648.3  348.47
#Mann= 9 ,-1 , 0
    4468     .05       0  4556.9     .16       0  4567.8      .1       0
  4732.5     .05       0  4754.2      .1       0  4998.3     .07       0
  5004.3      .1       0    5258     .15       0  5290.4      .1       0
Bank Sta=4998.3,5004.3
XS Rating Curve= 0 ,0
Exp/Cntr=0.3,0.1

Type RM Length L Ch R = 1 ,813     ,749,749,749
BEGIN DESCRIPTION:
UNT070 IN GIBB 2.0
END DESCRIPTION:
XS GIS Cut Line= 3
      3545892.14     10241491.63      3546402.05     10241243.19
      3546970.48     10240696.46
#Sta/Elev= 30
  4287.7  343.31  4301.7  344.25  4318.7  342.03  4376.7  339.14  4622.8  335.23
  4662.3  333.02  4735.5  330.94  4776.2  330.41  4825.7  329.62  4898.4  329.78
  4912.5  330.46  4940.8  329.84  4969.1  330.08  4983.3   330.7  4994.4  328.27
  4997.2  327.77  5000.4  328.27  5004.6  330.48  5018.8  330.82  5082.3   331.5
  5280.4  335.68  5287.4  335.62  5294.6  334.86  5308.7  337.15  5329.8  337.85
  5379.5  337.07  5400.6  337.95  5466.5  339.14    5549  340.17  5643.6  342.36
#Mann= 5 ,-1 , 0
  4287.7     .05       0  4776.2     .16       0  4994.4     .07       0
  5000.4     .16       0  5466.5     .08       0
Bank Sta=4994.4,5000.4
XS Rating Curve= 0 ,0
Exp/Cntr=0.3,0.1

Type RM Length L Ch R = 1 ,64      ,0,0,0
BEGIN DESCRIPTION:
UNT070 IN GIBB 1.0
END DESCRIPTION:
XS GIS Cut Line= 4
      3546265.04     10241851.01      3546758.02     10241640.77
      3547143.44     10241354.31      3547304.61     10240978.79
#Sta/Elev= 30
       0337.429919.73722 337.108128.2919333.9907 226.978334.3286305.9269 334.191
375.0072331.7993 453.956330.8608493.4305327.3307572.3793326.2121611.8538327.7091
641.4596 327.324 690.354326.8217758.3873324.7523777.8254326.4731845.8587327.4776
963.0921 329.177982.8326329.1122992.7029330.16461022.314  331.461061.795331.3999
1091.406330.07681111.146 332.8691130.887333.98351199.979332.73261357.903337.1054
1387.514336.67651426.995338.63021486.216340.11221535.568341.52991555.308342.9054
#Mann= 12 ,-1 , 0
       0     .05       019.73722      .1       0 226.978     .15       0
493.4305     .08       0572.3793     .15       0641.4596     .08       0
845.8587      .1       0963.0921     .07       0992.7029      .1       0
1022.314     .15       01387.514      .1       01486.216     .08       0
Bank Sta=690.354,777.8254
XS Rating Curve= 0 ,0
Exp/Cntr=0.3,0.1
Stream Node=CARTERS CREEK TR,Reach-1         , 0 , 0 ,Upstream end
Stream Node=CARTERS CREEK TR,Reach-1         , 0 , 1 ,Downstream end

Chan Stop Cuts=-1
Use User Specified Reach Order=0
Composite Channel Slope=5