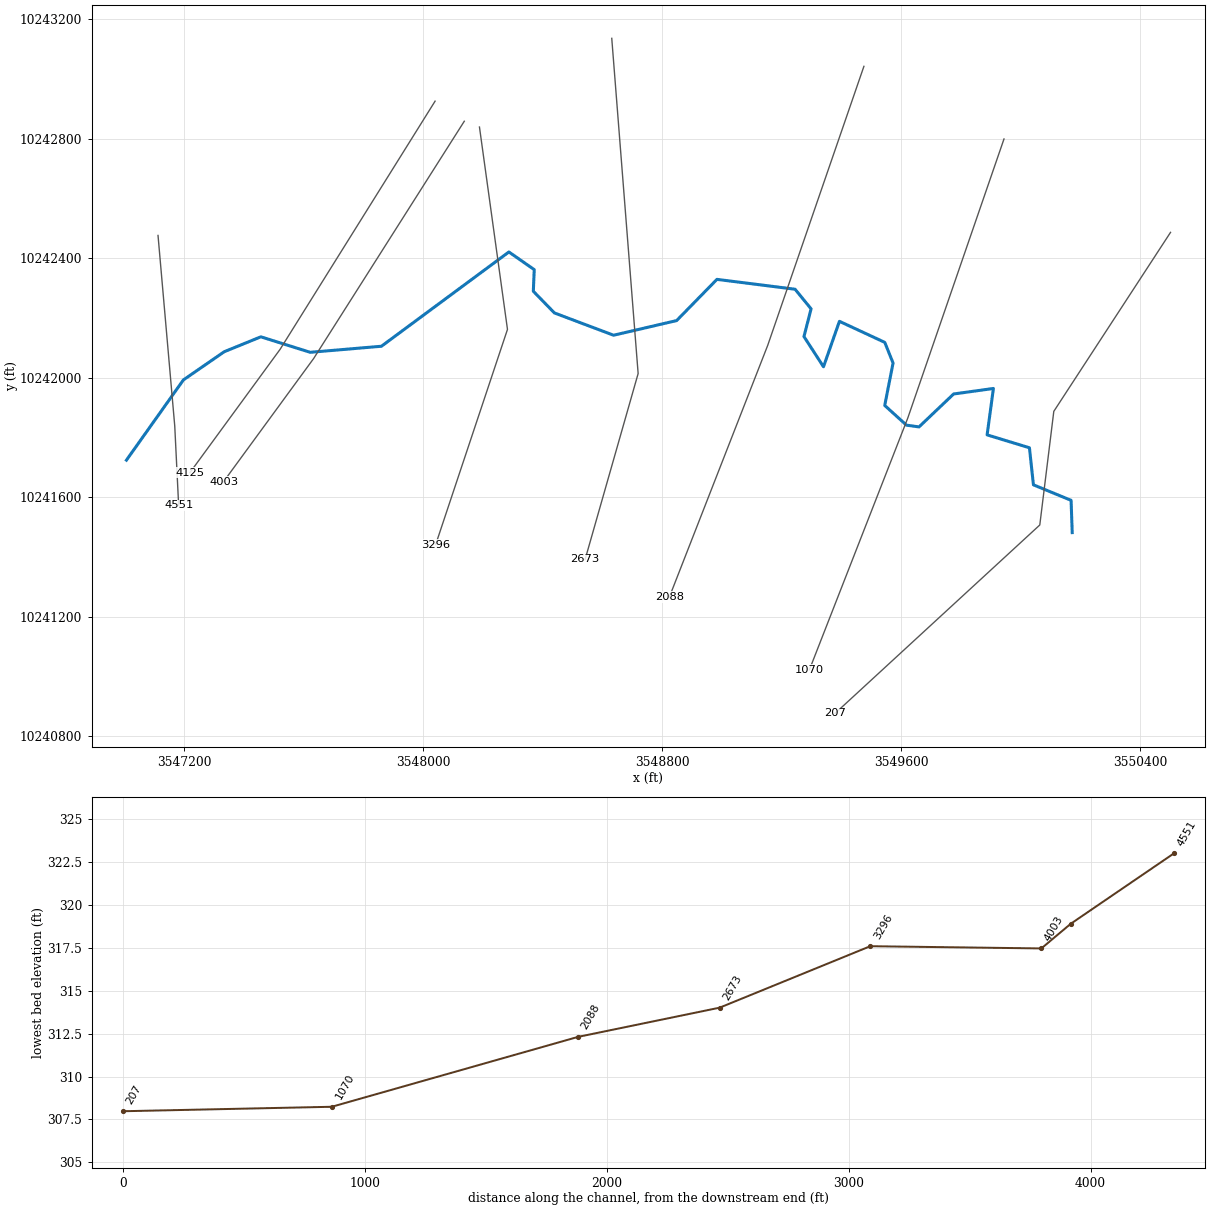
--- CARTERS CREEK TRIB A.prj (project) ---

Proj Title=CARTERS CREEK TRIB A Base Level Engineering
Current Plan=p01
Default Exp/Contr=0.3,0.1
English Units
Geom File=g01
Flow File=f01
Plan File=p01
Y Axis Title=Elevation
X Axis Title(PF)=Main Channel Distance
X Axis Title(XS)=Station
BEGIN DESCRIPTION:
CARTERS CREEK TRIB A
END DESCRIPTION:
DSS Export Rating Curves= 0
DSS Export Rating Curve Sorted= 0
DSS Export Volume Flow Curves= 0
DXF OffsetX= 0
DXF OffsetY= 0
DXF ScaleX= 1
DXF ScaleY= 10

--- CARTERS CREEK TRIB A.p01 (plan) ---

Plan Title=Multiple Run
Short Identifier=Multiple
Geom File=g01
Flow File=f01
Subcritical Flow
K Sum by GR= 0
Std Step Tol= 0.01
Critical Tol= 0.01
Num of Std Step Trials= 20
Max Error Tol= 0.3
Flow Tol Ratio= 0.001
Split Flow NTrial= 30
Split Flow Tol= 0.02
Split Flow Ratio= 0.02
Log Output Level= 0
Friction Slope Method= 1
Unsteady Friction Slope Method= 2
Unsteady Bridges Friction Slope Method= 1
Parabolic Critical Depth
Global Vel Dist=  1 , 1 , 1
Global Log Level= 0
CheckData=True
Encroach Param= -1, 0, 0, 0
BEGIN DESCRIPTION:
Multiple Run
END DESCRIPTION:

--- CARTERS CREEK TRIB A.f01 (steady flow) ---

Flow Title=Multiple
Program Version=4.10
Number of Profiles= 7
Profile Names=10-year,25-year,50-year,1pct_min,100-year,1pct_plu,500-year
River Rch & RM=CARTERS CREEK TR,Reach-1         ,4551
     459     606     723     633     856    1157    1199
River Rch & RM=CARTERS CREEK TR,Reach-1         ,4003
     528     702     843     740    1001    1354    1417
Boundary for River Rch & Prof#=CARTERS CREEK TR,Reach-1         , 1
Up Type= 0
Dn Type= 3
Dn Slope=0.005
Boundary for River Rch & Prof#=CARTERS CREEK TR,Reach-1         , 2
Up Type= 0
Dn Type= 3
Dn Slope=0.005
Boundary for River Rch & Prof#=CARTERS CREEK TR,Reach-1         , 3
Up Type= 0
Dn Type= 3
Dn Slope=0.005
Boundary for River Rch & Prof#=CARTERS CREEK TR,Reach-1         , 4
Up Type= 0
Dn Type= 3
Dn Slope=0.005
Boundary for River Rch & Prof#=CARTERS CREEK TR,Reach-1         , 5
Up Type= 0
Dn Type= 3
Dn Slope=0.005
Boundary for River Rch & Prof#=CARTERS CREEK TR,Reach-1         , 6
Up Type= 0
Dn Type= 3
Dn Slope=0.005
Boundary for River Rch & Prof#=CARTERS CREEK TR,Reach-1         , 7
Up Type= 0
Dn Type= 3
Dn Slope=0.005
DSS Import GetInterval= 0
DSS Import GetPeak= 0
DSS Import FillOption= 0

--- CARTERS CREEK TRIB A.g01 (geometry) ---

Geom Title=Existing Conditions
Program Version=4.10

River Reach=CARTERS CREEK TR,Reach-1
Reach XY= 30
      3547007.27     10241724.01      3547197.81     10241992.46
      3547334.53     10242086.86      3547457.14     10242136.77
      3547622.22     10242084.94      3547860.62     10242105.22
      3548287.13     10242420.71      3548371.91     10242361.53
      3548368.84     10242289.17      3548439.58     10242216.59
      3548637.55     10242142.07      3548848.41     10242191.13
      3548983.25     10242328.98      3549244.73     10242296.01
      3549298.27     10242230.34      3549274.46     10242137.61
      3549339.82     10242036.57      3549393.19     10242188.58
      3549544.84      10242118.2      3549572.63      10242049.1
      3549544.74     10241907.08      3549617.44      10241841.2
      3549659.52     10241835.31      3549775.25     10241945.45
       3549908.4     10241963.94      3549887.35     10241808.64
      3550028.94     10241765.49      3550042.32     10241641.48
      3550168.34     10241589.62      3550172.11     10241481.64

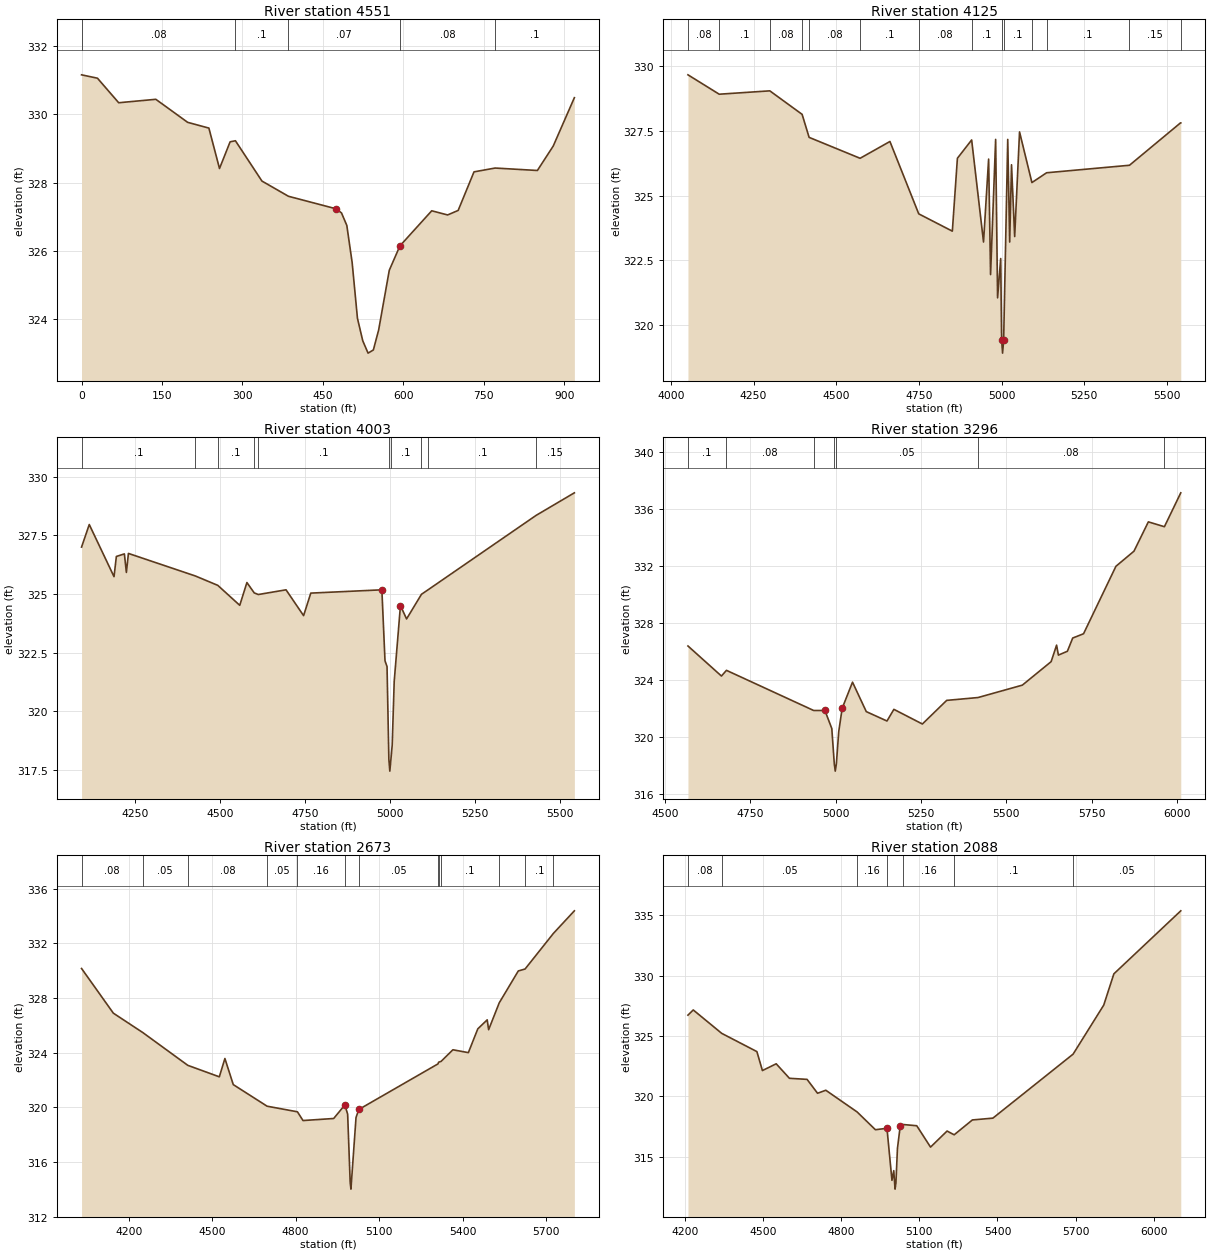
Type RM Length L Ch R = 1 ,4551    ,426,426,426
BEGIN DESCRIPTION:
CARTERS CR TRIB A 7.0
END DESCRIPTION:
XS GIS Cut Line= 3
        3547113.       10242476.        3547169.       10241838.
        3547182.       10241573.
#Sta/Elev= 30
       0 331.16329.68329331.063669.26101330.3436 138.522330.4445197.8886329.7682
237.4663329.5996257.2552328.4129 277.044329.1963286.9385329.2277336.4106328.0444
385.8828327.5976474.9326327.2291484.8271327.1077494.7215326.7403504.6159325.6542
514.5104324.0167524.4048 323.356534.2992322.9937544.1937323.0871554.0881323.6769
 573.877325.4253593.6658326.1408653.0324 327.172682.6278327.0496702.3289327.1823
731.8804328.3149771.2824328.4267850.0864 328.355879.6379 329.073  919.04330.4915
#Mann= 5 ,-1 , 0
       0     .08       0286.9385      .1       0385.8828     .07       0
593.6658     .08       0771.2824      .1       0
Bank Sta=474.9326,593.6658
XS Rating Curve= 0 ,0
Exp/Cntr=0.3,0.1

Type RM Length L Ch R = 1 ,4125    ,122,122,122
BEGIN DESCRIPTION:
CARTERS CR TRIB A 6.0
END DESCRIPTION:
XS GIS Cut Line= 3
      3548040.13     10242925.35      3547521.24     10242094.54
      3547219.83     10241682.44
#Sta/Elev= 30
  4051.8  329.67  4146.3  328.92  4299.3  329.05    4397  328.14  4418.1  327.25
  4572.3  326.44  4662.5  327.09  4749.6  324.29  4851.2  323.62  4866.5  326.44
  4909.6  327.15  4945.5   323.2  4960.9  326.41  4966.8  321.94  4982.1  327.17
    4988  321.04  4997.4  322.56  5000.3   319.4  5003.1   318.9  5006.3   319.4
  5018.7  327.17  5024.6   323.2  5030.1  326.19  5039.7  323.41  5054.4  327.46
  5091.8   325.5  5136.2  325.88  5386.8  326.17  5541.1  327.81  5541.9  327.81
#Mann= 14 ,-1 , 0
  4051.8     .08       0  4146.3      .1       0  4299.3     .08       0
    4397      .1       0  4418.1     .08       0  4572.3      .1       0
  4749.6     .08       0  4909.6      .1       0  5000.3     .07       0
  5006.3      .1       0  5091.8     .08       0  5136.2      .1       0
  5386.8     .15       0  5541.1      .1       0
Bank Sta=5000.3,5006.3
XS Rating Curve= 0 ,0
Exp/Cntr=0.3,0.1

Type RM Length L Ch R = 1 ,4003    ,707,707,707
BEGIN DESCRIPTION:
CARTERS CR TRIB A 6.1
END DESCRIPTION:
XS GIS Cut Line= 3
      3548137.83     10242858.15      3547633.71     10242064.13
      3547332.29     10241652.03
#Sta/Elev= 30
  4091.9     327  4114.6  327.96  4187.5  325.74  4194.4   326.6    4218  326.71
  4223.9  325.92  4229.9  326.73  4426.9  325.77  4493.1  325.37  4557.7  324.52
  4578.8  325.49  4600.3  325.05  4612.4  324.98    4694  325.18  4745.7  324.08
  4766.9  325.04  4976.2  325.18  4985.4  322.16  4991.4  321.91  4996.8  317.96
  4999.6  317.46  5002.8  317.96  5006.6  318.57  5012.5  321.28  5030.9  324.51
  5048.9  323.94  5092.8  324.99  5113.1  325.19  5430.4  328.35    5543  329.31
#Mann= 10 ,-1 , 0
  4091.9      .1       0  4426.9     .08       0  4493.1      .1       0
  4600.3     .08       0  4612.4      .1       0  4996.8     .07       0
  5002.8      .1       0  5092.8     .08       0  5113.1      .1       0
  5430.4     .15       0
Bank Sta=4976.2,5030.9
XS Rating Curve= 0 ,0
Exp/Cntr=0.3,0.1

Type RM Length L Ch R = 1 ,3296    ,623,623,623
BEGIN DESCRIPTION:
CARTERS CR TRIB A 5.0
END DESCRIPTION:
XS GIS Cut Line= 3
       3548188.6     10242838.76      3548282.35     10242161.64
      3548042.11     10241441.64
#Sta/Elev= 30
  4567.9  326.38  4665.9  324.27  4680.6  324.67  4935.9  321.85  4968.8  321.85
    4989  320.58  4996.3  318.09  4999.1  317.59  5002.3  318.09  5009.2  320.35
  5019.3     322  5049.6  323.84  5089.9  321.77  5150.5  321.11  5170.7  321.93
  5254.1   320.9  5325.3  322.56  5417.1  322.76  5546.7  323.63    5631  325.28
    5647  326.44  5652.3  325.74  5678.6  326.01  5694.2  326.94  5725.9  327.24
  5820.7  331.98  5873.5  333.04  5915.6   335.1  5962.6  334.76  6010.5  337.14
#Mann= 7 ,-1 , 0
  4567.9      .1       0  4680.6     .08       0  4935.9     .05       0
  4996.3     .04       0  5002.3     .05       0  5417.1     .08       0
  5962.6     .05       0
Bank Sta=4968.8,5019.3
XS Rating Curve= 0 ,0
Exp/Cntr=0.3,0.1

Type RM Length L Ch R = 1 ,2673    ,585,585,585
BEGIN DESCRIPTION:
CARTERS CR TRIB A 3.0
END DESCRIPTION:
XS GIS Cut Line= 3
      3548631.31     10243135.56      3548719.59     10242013.88
      3548542.11     10241391.64
#Sta/Elev= 30
  4030.1  330.16  4144.4  326.89  4250.3  325.47  4412.2  323.07  4525.5  322.23
  4545.6  323.57  4575.7  321.66  4697.3  320.08  4806.4  319.67  4826.5  319.03
  4936.8  319.18  4976.9  320.17    4987   319.5  4996.1  314.51  4998.8  314.01
  5017.1  319.25  5027.1  319.84  5312.1  323.18    5314   323.3    5323  323.36
  5365.5  324.21  5421.1     324    5455  325.74  5488.8   326.4    5494  325.68
    5532  327.64  5600.7  329.98    5625  330.12    5727  332.73  5802.3  334.38
#Mann= 13 ,-1 , 0
  4030.1     .08       0  4250.3     .05       0  4412.2     .08       0
  4697.3     .05       0  4806.4     .16       0  4976.9     .07       0
  5027.1     .05       0  5312.1     .08       0    5314     .05       0
    5323      .1       0    5532     .05       0    5625      .1       0
    5727     .05       0
Bank Sta=4976.9,5027.1
XS Rating Curve= 0 ,0
Exp/Cntr=0.3,0.1

Type RM Length L Ch R = 1 ,2088    ,1018,1018,1018
BEGIN DESCRIPTION:
CARTERS CR TRIB A 2.0
END DESCRIPTION:
XS GIS Cut Line= 3
      3549475.06     10243041.87      3549153.16     10242108.14
      3548824.17     10241266.19
#Sta/Elev= 30
  4212.1  326.72  4232.4  327.15  4341.8  325.21  4476.7   323.7  4497.9  322.13
  4550.8  322.69  4601.6  321.49  4669.3   321.4  4709.5  320.25  4741.2   320.5
  4861.5   318.7  4931.6  317.23    4976  317.35  4995.1  313.04    5002  313.84
    5007  312.31  5010.3  312.81  5016.2  315.68  5026.8  317.52  5038.5  317.66
  5090.3  317.56  5143.2  315.79  5206.7  317.12  5233.9  316.81  5303.8  318.04
  5382.6  318.19  5690.4  323.49    5808  327.55  5846.9  330.14  6103.7  335.36
#Mann= 7 ,-1 , 0
  4212.1     .08       0  4341.8     .05       0  4861.5     .16       0
    4976     .07       0  5038.5     .16       0  5233.9      .1       0
  5690.4     .05       0
Bank Sta=4976,5026.8
XS Rating Curve= 0 ,0
Exp/Cntr=0.3,0.1

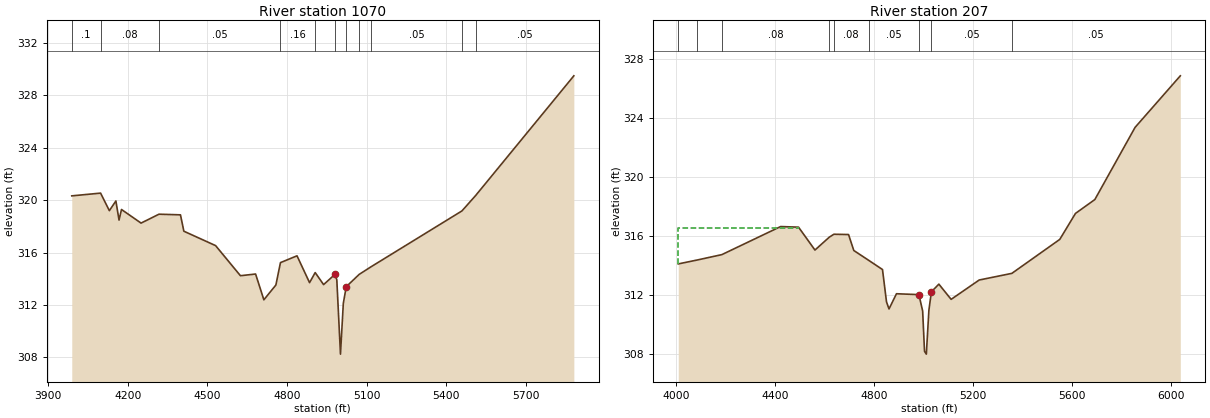
Type RM Length L Ch R = 1 ,1070    ,863,863,863
BEGIN DESCRIPTION:
CARTERS CR TRIB A 2.1
END DESCRIPTION:
XS GIS Cut Line= 3
      3549943.82     10242798.83      3549621.91     10241865.08
      3549292.78     10241022.79
#Sta/Elev= 30
    3989  320.33  4097.6  320.54  4130.6   319.2  4155.3  319.94  4167.1  318.48
  4176.4  319.29  4250.1  318.25  4317.8  318.93  4398.6  318.88  4411.4  317.63
    4531  316.53  4624.6  314.23  4681.7  314.36  4712.9  312.39  4758.2  313.52
  4775.4  315.23  4837.8  315.75  4885.1   313.7  4906.3  314.47    4938  313.55
  4981.2  314.34  4987.8  313.91  5001.6  308.24  5012.3  312.12  5023.3  313.39
    5072  314.33  5115.8   314.9  5459.3  319.18  5511.1  320.36    5881   329.5
#Mann= 11 ,-1 , 0
    3989      .1       0  4097.6     .08       0  4317.8     .05       0
  4775.4     .16       0  4906.3     .05       0  4981.2     .03       0
  5023.3     .05       0    5072     .16       0  5115.8     .05       0
  5459.3      .1       0  5511.1     .05       0
Bank Sta=4981.2,5023.3
XS Rating Curve= 0 ,0
Exp/Cntr=0.3,0.1

Type RM Length L Ch R = 1 ,207     ,0,0,0
BEGIN DESCRIPTION:
CARTERS CR TRIB A 1.0
END DESCRIPTION:
XS GIS Cut Line= 4
      3550501.09     10242486.28      3550110.48     10241887.34
       3550063.6     10241507.13      3549378.58     10240876.72
#Sta/Elev= 30
  4009.7  314.09    4085  314.35  4186.1  314.72  4423.4  316.62  4495.9  316.58
  4562.3  315.03    4620   315.9  4638.8   316.1    4698  316.08  4719.2     315
  4778.8  314.34  4835.2  313.71  4851.4  311.52  4861.5  311.04  4891.7  312.07
  4982.4  312.01  4997.5   310.9 5005.03  308.17  5012.4  307.98  5022.7  310.95
  5032.8   312.2    5063  312.72  5112.6  311.69  5226.1     313    5358  313.45
  5551.6  315.75  5615.1  317.51  5693.4  318.45  5856.1  323.34  6038.8  326.83
#Mann= 9 ,-1 , 0
  4009.7     .16       0    4085     .05       0  4186.1     .08       0
    4620     .05       0  4638.8     .08       0  4778.8     .05       0
  4982.4     .03       0  5032.8     .05       0    5358     .05       0
#XS Ineff= 2 , 0
         4495.74  316.55
Permanent Ineff=
       F       F
Bank Sta=4982.4,5032.8
XS Rating Curve= 0 ,0
Exp/Cntr=0.3,0.1

Chan Stop Cuts=-1
Use User Specified Reach Order=0
Composite Channel Slope=5