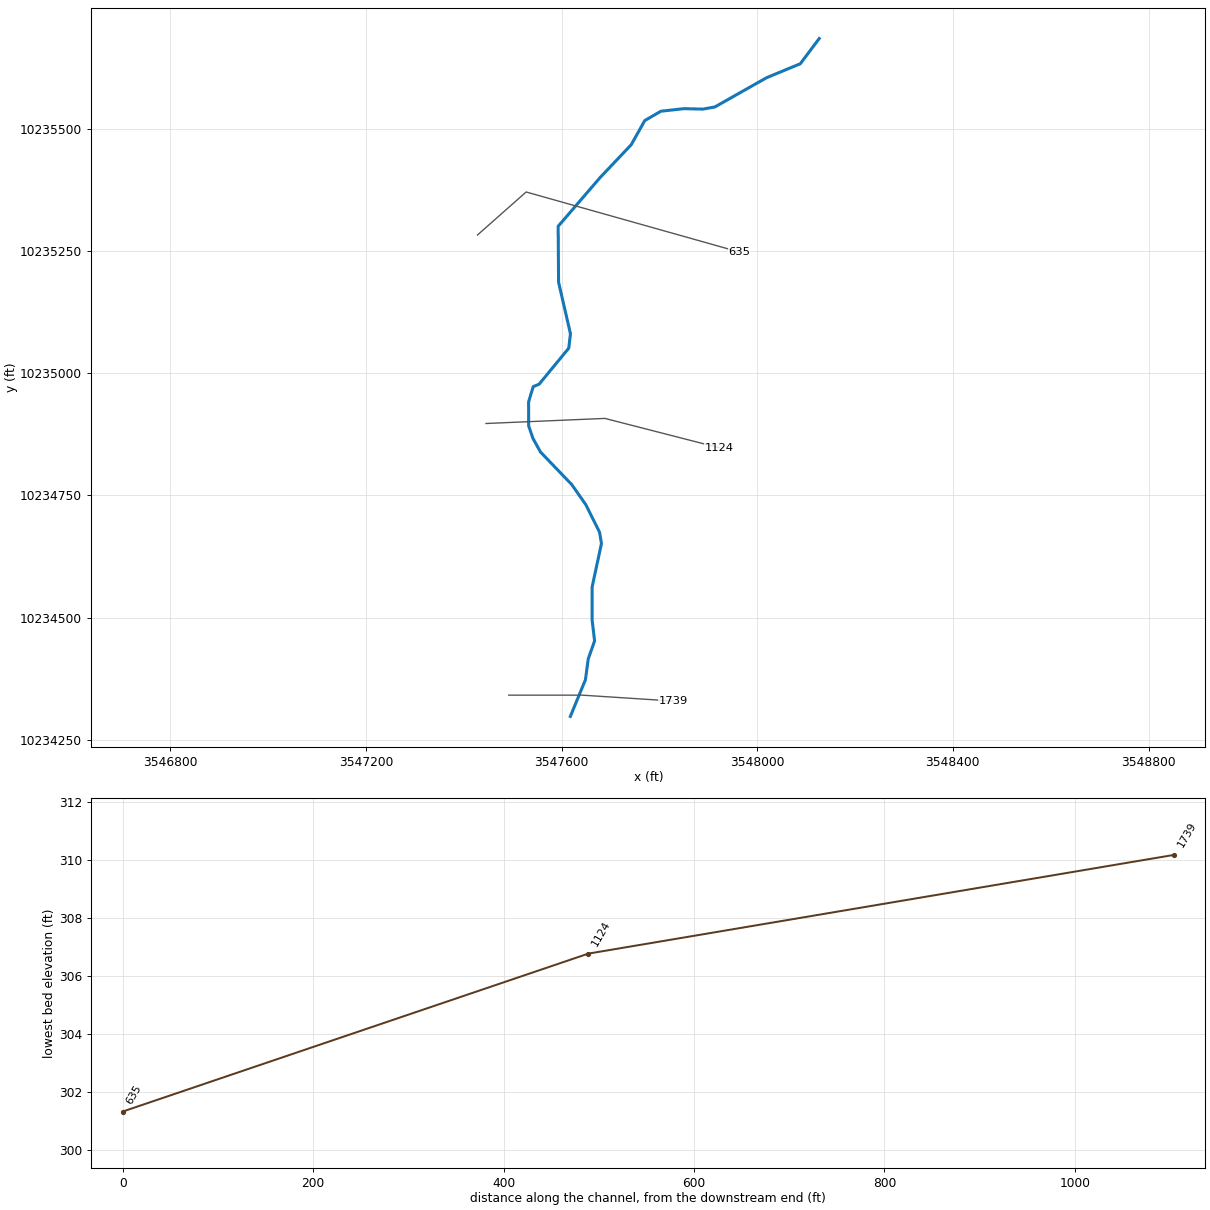
--- CARTERSCREEKTRIB.prj (project) ---

Proj Title=CARTERS CREEK TRIB B 4
Current Plan=p01
Default Exp/Contr=0.3,0.1
English Units
Geom File=g01
Flow File=f01
Plan File=p01
Y Axis Title=Elevation
X Axis Title(PF)=Main Channel Distance
X Axis Title(XS)=Station
BEGIN DESCRIPTION:
UNT073 IN GIBB
END DESCRIPTION:
DSS Export Rating Curves= 0
DSS Export Rating Curve Sorted= 0
DSS Export Volume Flow Curves= 0
DXF OffsetX= 0
DXF OffsetY= 0
DXF ScaleX= 1
DXF ScaleY= 10

--- CARTERSCREEKTRIB.p01 (plan) ---

Plan Title=Multiple Run
Short Identifier=Multiple
Geom File=g01
Flow File=f01
Subcritical Flow
K Sum by GR= 0
Std Step Tol= 0.01
Critical Tol= 0.01
Num of Std Step Trials= 20
Max Error Tol= 0.3
Flow Tol Ratio= 0.001
Split Flow NTrial= 30
Split Flow Tol= 0.02
Split Flow Ratio= 0.02
Log Output Level= 0
Friction Slope Method= 1
Unsteady Friction Slope Method= 2
Unsteady Bridges Friction Slope Method= 1
Parabolic Critical Depth
Global Vel Dist=  1 , 1 , 1
Global Log Level= 0
CheckData=True
Encroach Param= -1, 0, 0, 0
BEGIN DESCRIPTION:
Multiple Run
END DESCRIPTION:

--- CARTERSCREEKTRIB.f01 (steady flow) ---

Flow Title=Multiple
Program Version=4.10
Number of Profiles= 7
Profile Names=10-year,25-year,50-year,1pct_min,100-year,1pct_plu,500-year
River Rch & RM=UNT073 IN GIBB,Reach-1         ,1739
     210     267     310     265     358     485     479
River Rch & RM=S CREEK TRIB B 4,Reach-1         ,1739
     210     267     310     265     358     485     479
River Rch & RM=CARTERSCRTRIBB4,Reach-1         ,1739
     210     267     310     265     358     485     479
Boundary for River Rch & Prof#=CARTERSCRTRIBB4,Reach-1         , 1
Up Type= 0
Dn Type= 3
Dn Slope=0.005
Boundary for River Rch & Prof#=CARTERSCRTRIBB4,Reach-1         , 2
Up Type= 0
Dn Type= 3
Dn Slope=0.005
Boundary for River Rch & Prof#=CARTERSCRTRIBB4,Reach-1         , 3
Up Type= 0
Dn Type= 3
Dn Slope=0.005
Boundary for River Rch & Prof#=CARTERSCRTRIBB4,Reach-1         , 4
Up Type= 0
Dn Type= 3
Dn Slope=0.005
Boundary for River Rch & Prof#=CARTERSCRTRIBB4,Reach-1         , 5
Up Type= 0
Dn Type= 3
Dn Slope=0.005
Boundary for River Rch & Prof#=CARTERSCRTRIBB4,Reach-1         , 6
Up Type= 0
Dn Type= 3
Dn Slope=0.005
Boundary for River Rch & Prof#=CARTERSCRTRIBB4,Reach-1         , 7
Up Type= 0
Dn Type= 3
Dn Slope=0.005
DSS Import GetInterval= 0
DSS Import GetPeak= 0
DSS Import FillOption= 0

--- CARTERSCREEKTRIB.g01 (geometry) ---

Geom Title=Existing Conditions
Program Version=4.10

River Reach=CARTERSCRTRIBB4 ,Reach-1
Reach XY= 30
      3547618.05     10234298.14      3547648.86     10234373.02
      3547654.63     10234415.71      3547667.57     10234452.44
      3547662.52     10234495.59      3547662.48     10234562.33
      3547681.66     10234651.73      3547677.85     10234674.44
      3547649.85     10234730.69      3547621.14     10234771.86
      3547556.95     10234838.75      3547541.61     10234866.51
       3547532.8     10234892.12      3547532.71     10234941.19
      3547542.15      10234972.4      3547554.05     10234977.22
      3547614.82       10235051.      3547618.29     10235080.52
      3547593.99     10235185.55      3547593.12     10235300.14
      3547679.05     10235399.96      3547742.42      10235466.8
       3547770.2     10235516.28      3547803.19     10235535.38
      3547850.06     10235540.59      3547889.12     10235539.72
      3547913.43     10235544.06      3548019.33     10235603.95
      3548088.09     10235632.37       3548126.8     10235683.99

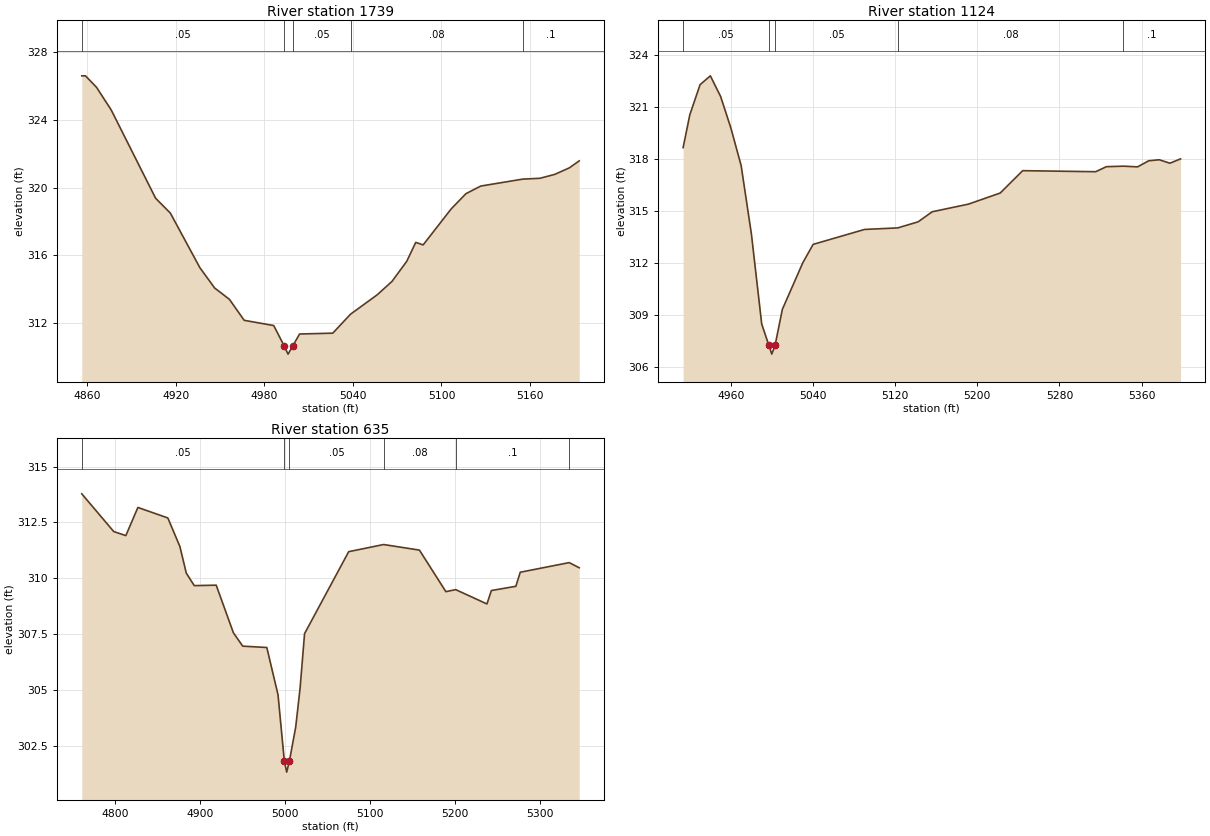
Type RM Length L Ch R = 1 ,1739    ,615,615,615
BEGIN DESCRIPTION:
UNT073 IN GIBB 3.0
END DESCRIPTION:
XS GIS Cut Line= 3
      3547492.14     10234341.64      3547642.11     10234341.64
      3547828.65     10234329.55
#Sta/Elev= 30
  4856.4  326.62  4858.9  326.62  4866.4  325.94  4876.4  324.59  4906.4  319.38
  4916.4   318.5  4936.4  315.27  4946.4  314.07  4956.4   313.4  4966.4  312.16
  4986.4  311.85  4993.4  310.66  4996.1  310.16  4999.4  310.66  5003.9  311.35
  5026.4   311.4  5038.4  312.52  5056.5  313.67  5066.5  314.46  5076.5  315.65
  5082.6  316.77  5087.6  316.62  5106.6  318.75  5116.6  319.65  5126.6   320.1
    5155  320.51  5166.7  320.56  5176.7  320.79  5186.7  321.18  5193.3  321.59
#Mann= 5 ,-1 , 0
  4856.4     .05       0  4993.4     .04       0  4999.4     .05       0
  5038.4     .08       0    5155      .1       0
Bank Sta=4993.4,4999.4
XS Rating Curve= 0 ,0
Exp/Cntr=0.3,0.1

Type RM Length L Ch R = 1 ,1124    ,489,489,489
BEGIN DESCRIPTION:
UNT073 IN GIBB 2.0
END DESCRIPTION:
XS GIS Cut Line= 3
      3547445.64     10234896.97      3547688.66     10234907.38
      3547922.14     10234847.41
#Sta/Elev= 30
  4913.6  318.67  4920.1  320.56  4930.1   322.3  4940.1  322.81  4950.1  321.62
  4960.1   319.8  4970.1  317.63  4980.1  313.68  4990.1   308.5  4997.1  307.26
  4999.9  306.76  5003.1  307.26  5010.2  309.34  5030.2  312.04  5040.2  313.09
  5090.2  313.95  5122.6  314.04  5142.4  314.39  5156.1  314.97  5191.4  315.41
  5222.3  316.05  5244.2  317.34  5315.3  317.28  5325.7  317.57  5342.3   317.6
  5356.1  317.56  5366.9  317.91  5377.2  317.97  5387.5  317.77  5397.9  318.02
#Mann= 5 ,-1 , 0
  4913.6     .05       0  4997.1     .04       0  5003.1     .05       0
  5122.6     .08       0  5342.3      .1       0
Bank Sta=4997.1,5003.1
XS Rating Curve= 0 ,0
Exp/Cntr=0.3,0.1

Type RM Length L Ch R = 1 ,635     ,0,0,0
BEGIN DESCRIPTION:
UNT073 IN GIBB 1.0
END DESCRIPTION:
XS GIS Cut Line= 3
      3547428.23     10235282.37      3547527.67     10235370.27
      3547963.01     10235247.65
#Sta/Elev= 30
  4761.1  313.78  4798.7  312.09  4812.9  311.91  4827.1  313.17  4862.3   312.7
  4876.5  311.42    4884  310.23  4893.4  309.67  4919.2  309.69  4939.4  307.56
  4950.4  306.96  4978.7   306.9  4991.9  304.78  4999.3  301.82  5002.1  301.32
  5005.3  301.82  5012.7  303.34  5017.9   305.1  5023.1  307.52    5075  311.19
  5116.1  311.51  5158.2  311.26  5189.3   309.4  5200.9  309.49  5237.6  308.85
  5242.8  309.45  5271.6  309.64  5276.8  310.27  5334.3   310.7  5346.1  310.47
#Mann= 6 ,-1 , 0
  4761.1     .05       0  4999.3     .04       0  5005.3     .05       0
  5116.1     .08       0  5200.9      .1       0  5334.3     .08       0
Bank Sta=4999.3,5005.3
XS Rating Curve= 0 ,0
Exp/Cntr=0.3,0.1

Chan Stop Cuts=-1
Use User Specified Reach Order=0
Composite Channel Slope=5