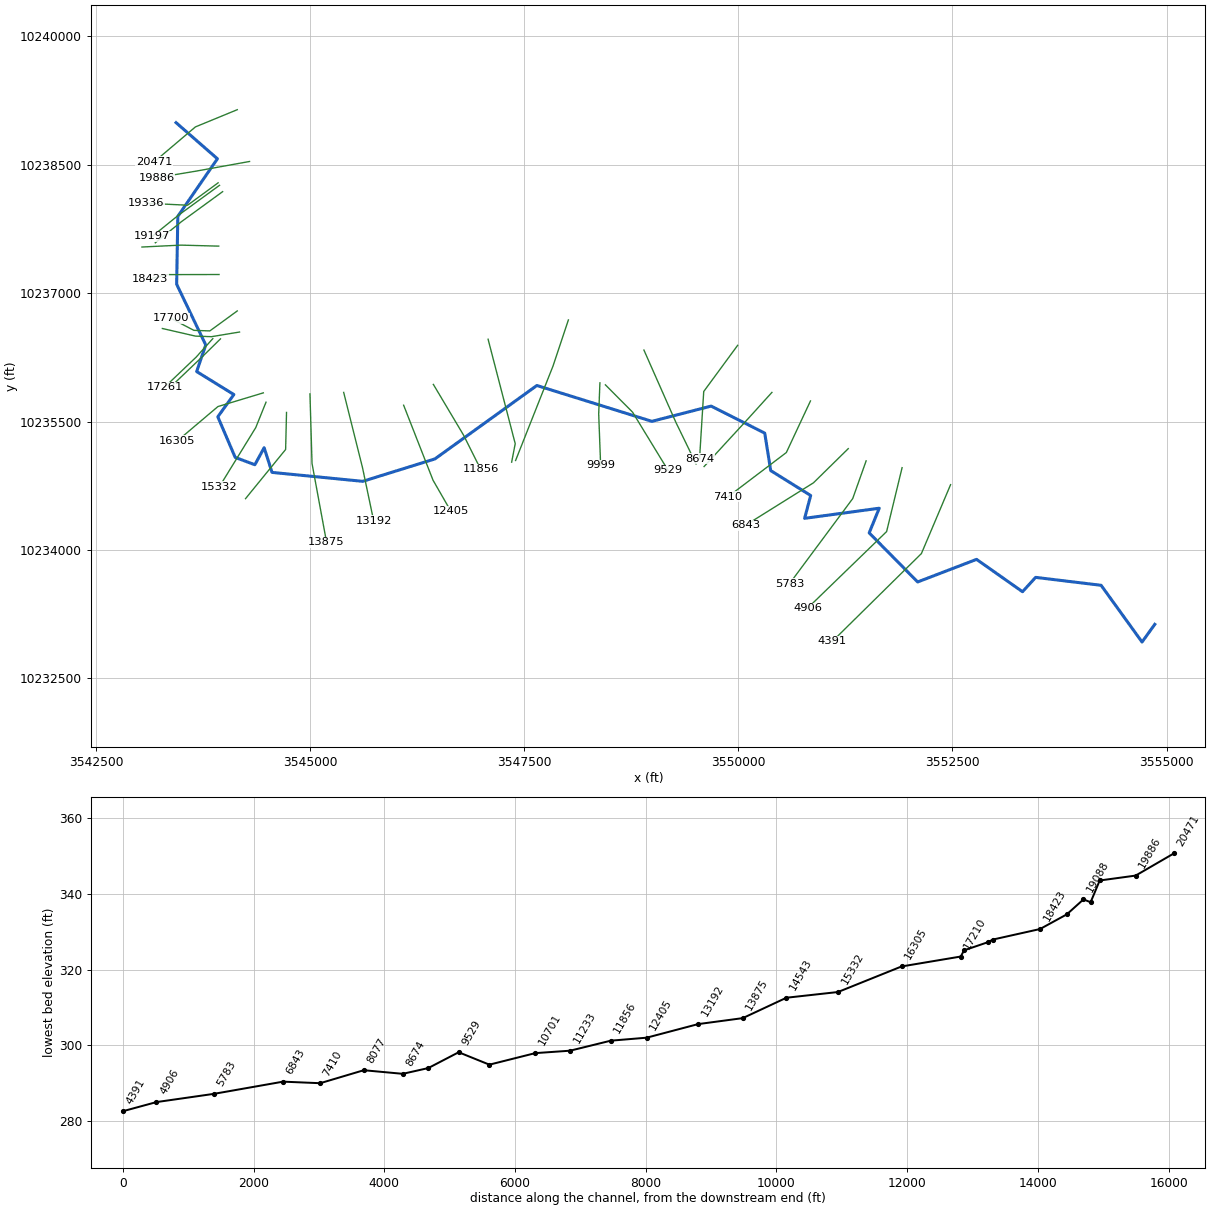
--- CARTERS CREEK TRIB B.prj (project) ---

Proj Title=CARTERS CREEK TRIB B Base Level Engineering
Current Plan=p01
Default Exp/Contr=0.3,0.1
English Units
Geom File=g01
Flow File=f01
Plan File=p01
Y Axis Title=Elevation
X Axis Title(PF)=Main Channel Distance
X Axis Title(XS)=Station
BEGIN DESCRIPTION:
CARTERS CREEK TRIB B
END DESCRIPTION:
DSS Export Rating Curves= 0
DSS Export Rating Curve Sorted= 0
DSS Export Volume Flow Curves= 0
DXF OffsetX= 0
DXF OffsetY= 0
DXF ScaleX= 1
DXF ScaleY= 10

--- CARTERS CREEK TRIB B.p01 (plan) ---

Plan Title=Multiple Run
Short Identifier=Multiple
Geom File=g01
Flow File=f01
Subcritical Flow
K Sum by GR= 0
Std Step Tol= 0.01
Critical Tol= 0.01
Num of Std Step Trials= 20
Max Error Tol= 0.3
Flow Tol Ratio= 0.001
Split Flow NTrial= 30
Split Flow Tol= 0.02
Split Flow Ratio= 0.02
Log Output Level= 0
Friction Slope Method= 1
Unsteady Friction Slope Method= 2
Unsteady Bridges Friction Slope Method= 1
Parabolic Critical Depth
Global Vel Dist=  1 , 1 , 1
Global Log Level= 0
CheckData=True
Encroach Param= -1, 0, 0, 0
BEGIN DESCRIPTION:
Multiple Run
END DESCRIPTION:

--- CARTERS CREEK TRIB B.f01 (steady flow) ---

Flow Title=Multiple
Number of Profiles=7
Profile Names=10-year,25-year,50-year,1pct_min,100-year,1pct_plu,500-year
River Rch & RM= CARTERS CREEK TR,Reach-1,20471
     163     202     232     196     265     359     346
River Rch & RM= CARTERS CREEK TR,Reach-1,17261
     364     478     567     494     668     904     929
River Rch & RM= CARTERS CREEK TR,Reach-1,13875
     811    1115    1366    1226    1658    2242    2446
River Rch & RM= CARTERS CREEK TR,Reach-1,9999
    1089    1507    1854    1668    2255    3050    3347
Boundary for River Rch & Prof#=CARTERS CREEK TR,Reach-1,1
Up Type=0
Dn Type=3
Dn Slope=0.005
Boundary for River Rch & Prof#=CARTERS CREEK TR,Reach-1,2
Up Type=0
Dn Type=3
Dn Slope=0.005
Boundary for River Rch & Prof#=CARTERS CREEK TR,Reach-1,3
Up Type=0
Dn Type=3
Dn Slope=0.005
Boundary for River Rch & Prof#=CARTERS CREEK TR,Reach-1,4
Up Type=0
Dn Type=3
Dn Slope=0.005
Boundary for River Rch & Prof#=CARTERS CREEK TR,Reach-1,5
Up Type=0
Dn Type=3
Dn Slope=0.005
Boundary for River Rch & Prof#=CARTERS CREEK TR,Reach-1,6
Up Type=0
Dn Type=3
Dn Slope=0.005
Boundary for River Rch & Prof#=CARTERS CREEK TR,Reach-1,7
Up Type=0
Dn Type=3
Dn Slope=0.005

--- CARTERS CREEK TRIB B.g01 (geometry) ---

Geom Title=Existing Conditions
Program Version=4.10

River Reach=CARTERS CREEK TR,Reach-1
Reach XY= 30
      3543435.19     10238993.12      3543917.83     10238571.24
      3543455.61     10237898.81      3543441.87     10237105.34
      3543781.49     10236396.11      3543675.64     10236085.09
      3544109.85     10235816.53      3543922.51     10235556.68
      3544125.43     10235082.14      3544355.13     10234996.35
      3544463.37     10235195.45      3544555.55     10234906.83
      3545614.55     10234802.57      3546457.82     10235064.63
      3547647.63     10235922.27      3548990.51     10235503.43
       3549682.7     10235681.56      3550308.17     10235365.74
      3550377.97     10234927.96      3550844.55     10234637.17
      3550774.02     10234370.24      3551644.99     10234488.32
      3551527.75     10234200.15      3552093.29      10233626.8
      3552781.48      10233890.8      3553317.81      10233512.8
      3553471.24     10233680.36      3554235.29     10233587.76
      3554713.49      10232925.1      3554862.11     10233131.64

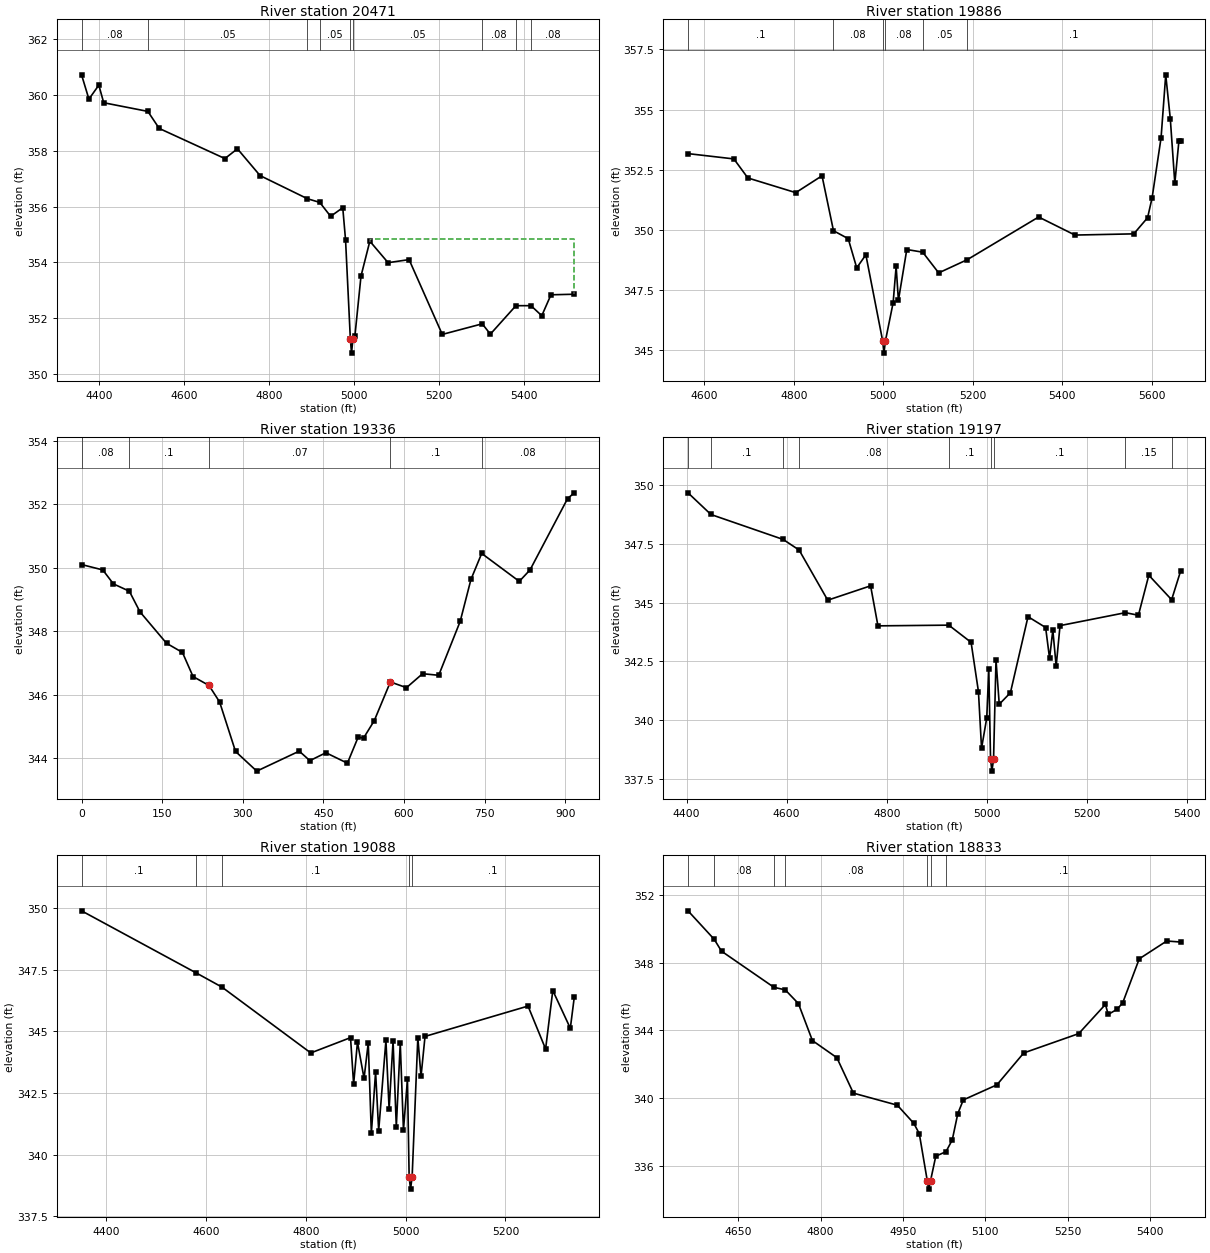
Type RM Length L Ch R = 1 ,20471   ,585,585,585
BEGIN DESCRIPTION:
UNT076 IN GIBB 6.0
END DESCRIPTION:
XS GIS Cut Line= 3
      3544149.62     10239144.67      3543660.99     10238943.46
      3543180.26     10238535.87
#Sta/Elev= 30
  4359.1  360.72  4376.4  359.85  4399.7  360.35  4411.2  359.72    4515  359.41
  4541.7   358.8  4696.2  357.72  4725.6  358.07  4778.9  357.11  4890.4  356.28
  4919.2  356.15  4944.8  355.65  4973.3  355.96  4979.9   354.8  4991.2  351.25
  4993.9  350.75  4997.2  351.25  5001.9  351.37  5016.2  353.51    5037  354.76
  5079.9  353.99  5129.3   354.1  5207.3  351.42  5301.3   351.8  5320.4  351.43
  5380.5  352.45  5415.9  352.45  5441.3  352.09  5462.9  352.84  5517.8  352.86
#Mann= 9 ,-1 , 0
  4359.1     .08       0    4515     .05       0  4890.4     .08       0
  4919.2     .05       0  4991.2     .04       0  4997.2     .05       0
  5301.3     .08       0  5380.5     .05       0  5415.9     .08       0
#XS Ineff= 1 ,-1
 5036.81 5516.03  354.84
Permanent Ineff=
       F
Bank Sta=4991.2,4997.2
XS Rating Curve= 0 ,0
Exp/Cntr=0.3,0.1

Type RM Length L Ch R = 1 ,19886   ,550,550,550
BEGIN DESCRIPTION:
UNT076 IN GIBB 5.0
END DESCRIPTION:
XS GIS Cut Line= 3
      3544292.84     10238539.63      3543667.79      10238426.6
        3543209.     10238350.18
#Sta/Elev= 30
    4564  353.17  4666.4  352.95  4697.6  352.16  4804.6  351.55  4863.2  352.25
  4888.8  349.97  4921.7  349.64  4940.7  348.43  4961.1  348.97  4998.7  345.39
  5001.5  344.89  5004.7  345.39    5022  346.98  5028.7  348.49  5033.8  347.08
  5052.5  349.19    5088  349.08  5123.7  348.22  5187.7  348.77  5346.9  350.54
    5428  349.79  5559.4  349.84  5590.2  350.51  5600.3  351.34  5620.3  353.83
  5630.7  356.44  5640.9  354.62    5651  351.94  5660.2  353.71  5664.3  353.71
#Mann= 6 ,-1 , 0
    4564      .1       0  4888.8     .08       0  4998.7     .07       0
  5004.7     .08       0    5088     .05       0  5187.7      .1       0
Bank Sta=4998.7,5004.7
XS Rating Curve= 0 ,0
Exp/Cntr=0.3,0.1

Type RM Length L Ch R = 1 ,19336   ,139,139,139
XS GIS Cut Line= 3
     3543926.325    10238290.267     3543569.554    10238028.549
     3543085.179    10238051.986
#Sta/Elev= 30
       0   350.1   39.52  349.93   59.28  349.49   88.93  349.26  108.69  348.61
  158.09  347.62  187.73  347.33  207.49  346.57  237.14  346.29   256.9  345.77
  286.54  344.21  326.06  343.59  405.11  344.22  424.87  343.92  454.74  344.17
  494.72  343.84  514.71  344.66  524.71  344.63   544.7  345.18  574.69   346.4
  604.67  346.22  634.66  346.66  664.65  346.61  704.63  348.31  724.62  349.63
  744.61  350.45  814.58  349.57  834.57  349.93  904.54  352.18  916.99  352.36
#Mann= 5 ,-1 , 0
       0     .08       0   88.93      .1       0  237.14     .07       0
  574.69      .1       0  744.61     .08       0
Bank Sta=237.14,574.69
XS Rating Curve= 0 ,0
Exp/Cntr=0.3,0.1

Type RM Length L Ch R = 1 ,19197   ,109,109,109
BEGIN DESCRIPTION:
UNT076 IN GIBB 4.1
END DESCRIPTION:
XS GIS Cut Line= 3
      3543942.55     10238261.37      3543460.03     10237909.49
      3543158.33     10237665.69
#Sta/Elev= 30
  4402.8  349.66  4448.6  348.74    4593  347.68  4624.9  347.23  4682.1   345.1
  4767.8  345.71  4782.5  344.01  4924.1  344.04  4968.7  343.31  4983.4  341.22
  4989.6  338.81    5000   340.1  5004.1  342.17  5007.6  338.34  5010.3  337.84
  5013.6  338.34  5018.5  342.56    5025  340.68  5047.3  341.17  5082.5   344.4
  5117.7  343.94  5125.6  342.63  5132.1  343.83  5138.8   342.3  5146.5  344.02
  5277.3  344.57  5303.2  344.46    5324  346.16  5369.6  345.12  5387.9  346.36
#Mann= 9 ,-1 , 0
  4402.8     .08       0  4448.6      .1       0    4593     .05       0
  4624.9     .08       0  4924.1      .1       0  5007.6     .07       0
  5013.6      .1       0  5277.3     .15       0  5369.6      .1       0
Bank Sta=5007.6,5013.6
XS Rating Curve= 0 ,0
Exp/Cntr=0.3,0.1

Type RM Length L Ch R = 1 ,19088   ,255,255,255
BEGIN DESCRIPTION:
UNT076 IN GIBB 4.0
END DESCRIPTION:
XS GIS Cut Line= 3
      3543978.55     10238186.84      3543496.05     10237834.97
      3543192.93     10237590.02
#Sta/Elev= 30
    4351  349.88  4580.9  347.36  4632.1  346.79  4810.1  344.12  4889.7  344.74
  4895.9  342.86  4903.6  344.56  4916.8  343.09  4925.2  344.53  4931.4  340.86
  4939.9  343.35  4946.1  340.97  4960.6  344.63    4967  341.84  4974.9   344.6
  4981.4  341.13  4989.3  344.52  4995.7  340.99  5003.7  343.05  5007.1   339.1
  5009.9   338.6  5013.1   339.1  5024.5  344.74  5030.9  343.17  5038.9  344.79
  5245.2  346.02  5280.4  344.28  5294.8  346.65  5329.9  345.12  5337.9  346.39
#Mann= 5 ,-1 , 0
    4351      .1       0  4580.9     .08       0  4632.1      .1       0
  5007.1     .07       0  5013.1      .1       0
Bank Sta=5007.1,5013.1
XS Rating Curve= 0 ,0
Exp/Cntr=0.3,0.1

Type RM Length L Ch R = 1 ,18833   ,410,410,410
BEGIN DESCRIPTION:
UNT076 IN GIBB 3.0
END DESCRIPTION:
XS GIS Cut Line= 3
      3543933.05     10237550.57      3543492.11     10237562.37
      3543036.55     10237540.13
#Sta/Elev= 30
  4558.7  351.05  4606.4  349.37  4619.7  348.67  4715.1  346.54  4735.7  346.39
  4759.7  345.58  4785.2   343.4  4829.7  342.39  4859.8   340.3  4939.8  339.59
  4969.8  338.52  4979.8  337.91  4994.3  335.14    4997  334.64  5000.3  335.14
  5009.8  336.58  5028.4  336.85  5039.8  337.54  5049.9  339.09  5059.9   339.9
  5121.1  340.79    5170  342.67  5270.1  343.81  5318.7  345.53  5323.8  344.94
  5340.2  345.25  5350.2  345.63  5380.3  348.22  5430.3  349.27  5455.9  349.21
#Mann= 7 ,-1 , 0
  4558.7     .05       0  4606.4     .08       0  4715.1     .05       0
  4735.7     .08       0  4994.3     .07       0  5000.3     .08       0
  5028.4      .1       0
Bank Sta=4994.3,5000.3
XS Rating Curve= 0 ,0
Exp/Cntr=0.3,0.1

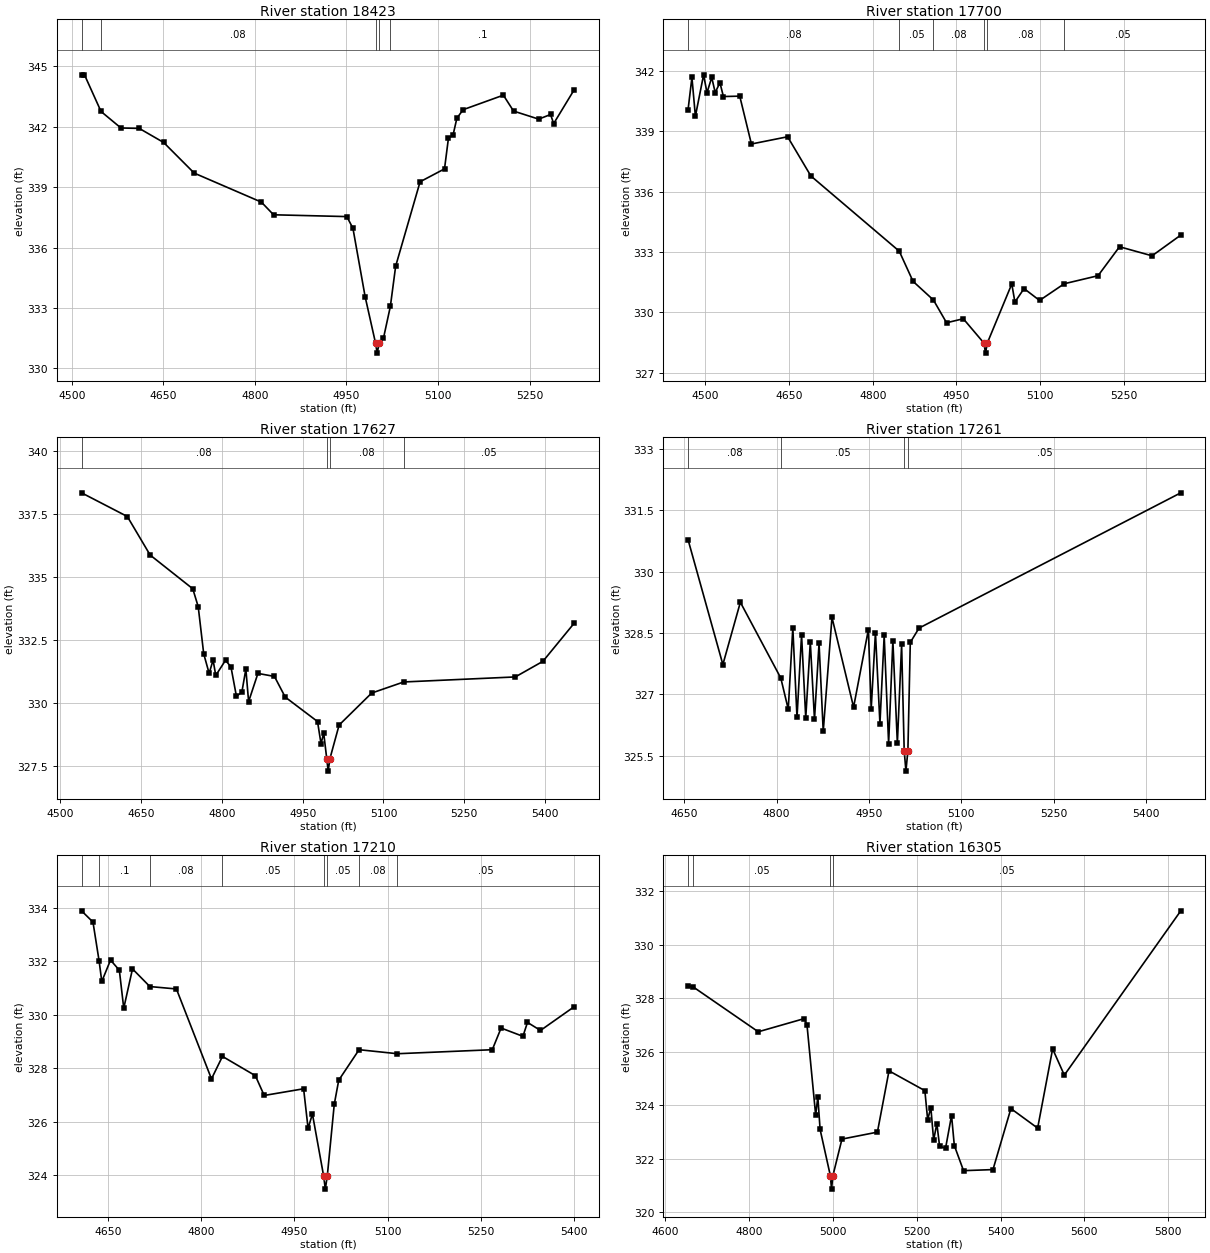
Type RM Length L Ch R = 1 ,18423   ,723,723,723
BEGIN DESCRIPTION:
UNT076 IN GIBB 2.0
END DESCRIPTION:
XS GIS Cut Line= 3
      3543936.57     10237219.01      3543334.03     10237217.77
      3543135.58     10237168.15
#Sta/Elev= 30
  4516.1  344.58  4520.9  344.58    4548  342.76  4580.6  341.94  4610.6  341.92
  4650.6  341.22  4700.6   339.7  4810.6  338.26  4830.6  337.63  4950.6  337.54
  4960.6  336.96  4980.6  333.56  4997.6  331.26  5000.3  330.76  5003.6  331.26
  5010.6   331.5  5021.9  333.08  5030.6  335.08  5070.6  339.27  5110.6  339.91
  5117.1  341.45  5124.5  341.58  5130.9  342.43  5141.2  342.85    5207  343.57
  5223.7  342.78  5264.9  342.38  5284.3  342.61  5289.4  342.16  5323.2  343.85
#Mann= 5 ,-1 , 0
  4516.1     .05       0    4548     .08       0  4997.6     .04       0
  5003.6     .08       0  5021.9      .1       0
Bank Sta=4997.6,5003.6
XS Rating Curve= 0 ,0
Exp/Cntr=0.3,0.1

Type RM Length L Ch R = 1 ,17700   ,73,73,73
BEGIN DESCRIPTION:
UNT076 IN GIBB 1.0
END DESCRIPTION:
XS GIS Cut Line= 4
      3544149.42      10236793.2      3543829.58     10236559.97
      3543643.38     10236566.48      3543376.44     10236705.65
#Sta/Elev= 30
  4468.8  340.06  4475.8  341.68    4482  339.75  4496.7  341.81  4502.8  340.92
  4511.3  341.68  4517.5  340.93    4526  341.42  4532.2  340.73  4561.5  340.75
  4582.4  338.37  4647.3  338.73    4689  336.78  4847.4  333.04  4872.1  331.54
  4908.7  330.61  4932.2  329.48  4962.2  329.68  4999.2  328.47    5002  327.97
  5005.2  328.47  5049.1  331.41  5054.7  330.51  5071.1  331.18  5098.9  330.59
  5143.1  331.42  5203.7  331.82  5242.2  333.26  5300.5  332.81    5352  333.84
#Mann= 6 ,-1 , 0
  4468.8     .08       0  4847.4     .05       0  4908.7     .08       0
  4999.2     .07       0  5005.2     .08       0  5143.1     .05       0
Bank Sta=4999.2,5005.2
XS Rating Curve= 0 ,0
Exp/Cntr=0.3,0.1

Type RM Length L Ch R = 1 ,17627   ,366,366,366
BEGIN DESCRIPTION:
UNT076 IN GIBB 1.1
END DESCRIPTION:
XS GIS Cut Line= 4
      3544175.91     10236546.95      3543848.36     10236492.65
      3543662.16     10236499.16      3543275.32     10236588.22
#Sta/Elev= 30
  4539.2  338.34  4624.2   337.4  4666.6  335.87  4745.8  334.53  4755.9  333.82
  4766.1  331.95  4776.2  331.17  4783.5   331.7  4788.5  331.09  4806.6  331.69
  4816.7  331.43  4826.9  330.26    4837  330.43  4844.4  331.34  4849.5  330.05
  4866.8  331.17  4897.5  331.05  4917.5  330.23  4977.5  329.26    4984  328.38
    4989   328.8  4994.6  327.79  4997.3  327.29  5000.6  327.79  5017.6  329.12
  5078.1  330.39  5137.6  330.83  5344.9  331.03  5396.2  331.65  5454.5  333.17
#Mann= 4 ,-1 , 0
  4539.2     .08       0  4994.6     .07       0  5000.6     .08       0
  5137.6     .05       0
Bank Sta=4994.6,5000.6
XS Rating Curve= 0 ,0
Exp/Cntr=0.3,0.1

Type RM Length L Ch R = 1 ,17261   ,51,51,51
BEGIN DESCRIPTION:
UNT075 IN GIBB 4.1
END DESCRIPTION:
XS GIS Cut Line= 3
      3543864.13      10236469.7      3543667.97     10236252.19
      3543300.65     10235902.15
#Sta/Elev= 30
    4656  330.78  4712.6  327.73    4741  329.25  4806.7   327.4  4818.8  326.64
  4826.2  328.63    4833  326.44  4840.4  328.45  4847.2  326.43  4854.6  328.28
  4861.4  326.39  4868.8  328.25  4875.6   326.1  4889.8  328.88  4924.9  326.69
  4948.9  328.58  4953.5  326.65  4960.4  328.51  4967.7  326.29  4974.6  328.44
  4981.8   325.8  4988.7  328.31    4996  325.81  5002.9  328.22  5007.1  325.63
  5009.9  325.13  5013.1  325.63    5017  328.27  5031.2  328.62  5456.3  331.92
#Mann= 4 ,-1 , 0
    4656     .08       0  4806.7     .05       0  5007.1     .04       0
  5013.1     .05       0
Bank Sta=5007.1,5013.1
XS Rating Curve= 0 ,0
Exp/Cntr=0.3,0.1

Type RM Length L Ch R = 1 ,17210   ,905,905,905
BEGIN DESCRIPTION:
UNT075 IN GIBB 4.0
END DESCRIPTION:
XS GIS Cut Line= 3
      3543953.16      10236466.7      3543747.47     10236264.16
      3543381.51     10235915.41
#Sta/Elev= 30
  4606.8  333.89  4625.2  333.47  4635.2     332  4639.4  331.25  4653.5  332.05
  4667.7  331.67  4674.8  330.25  4688.9  331.72  4716.9  331.06  4759.7  330.97
  4816.2  327.61  4833.9  328.45  4886.9  327.73  4901.2  326.99  4964.7  327.24
  4971.9  325.76  4978.9   326.3  4996.9  323.99  4999.7  323.49  5002.9  323.99
  5014.1  326.66  5021.3  327.56  5054.1   328.7  5115.9  328.55  5268.8   328.7
    5283  329.51  5318.2   329.2  5325.5  329.72  5346.5  329.42    5401  330.31
#Mann= 8 ,-1 , 0
  4606.8     .08       0  4635.2      .1       0  4716.9     .08       0
  4833.9     .05       0  4996.9     .04       0  5002.9     .05       0
  5054.1     .08       0  5115.9     .05       0
Bank Sta=4996.9,5002.9
XS Rating Curve= 0 ,0
Exp/Cntr=0.3,0.1

Type RM Length L Ch R = 1 ,16305   ,973,973,973
BEGIN DESCRIPTION:
UNT075 IN GIBB 3.0
END DESCRIPTION:
XS GIS Cut Line= 3
      3544453.86      10235836.3      3543923.65     10235675.97
      3543448.66      10235273.8
#Sta/Elev= 30
  4653.8  328.46  4666.7  328.42  4821.5  326.75  4930.8  327.24  4937.7  327.02
  4958.5  323.64  4963.7  324.31  4969.1   323.1  4993.6  321.37  4996.4  320.87
  4999.6  321.37  5021.3  322.74  5105.9     323  5133.6  325.29  5219.2  324.55
  5225.8  323.47  5233.5  323.91  5240.1   322.7  5247.8  323.32  5254.4  322.47
  5268.6   322.4  5282.9  323.62  5289.5   322.5  5311.5  321.56  5381.8   321.6
  5424.6  323.88  5488.4  323.15  5524.2  326.11  5552.1  325.13  5830.1  331.27
#Mann= 4 ,-1 , 0
  4653.8     .08       0  4666.7     .05       0  4993.6     .04       0
  4999.6     .05       0
Bank Sta=4993.6,4999.6
XS Rating Curve= 0 ,0
Exp/Cntr=0.3,0.1

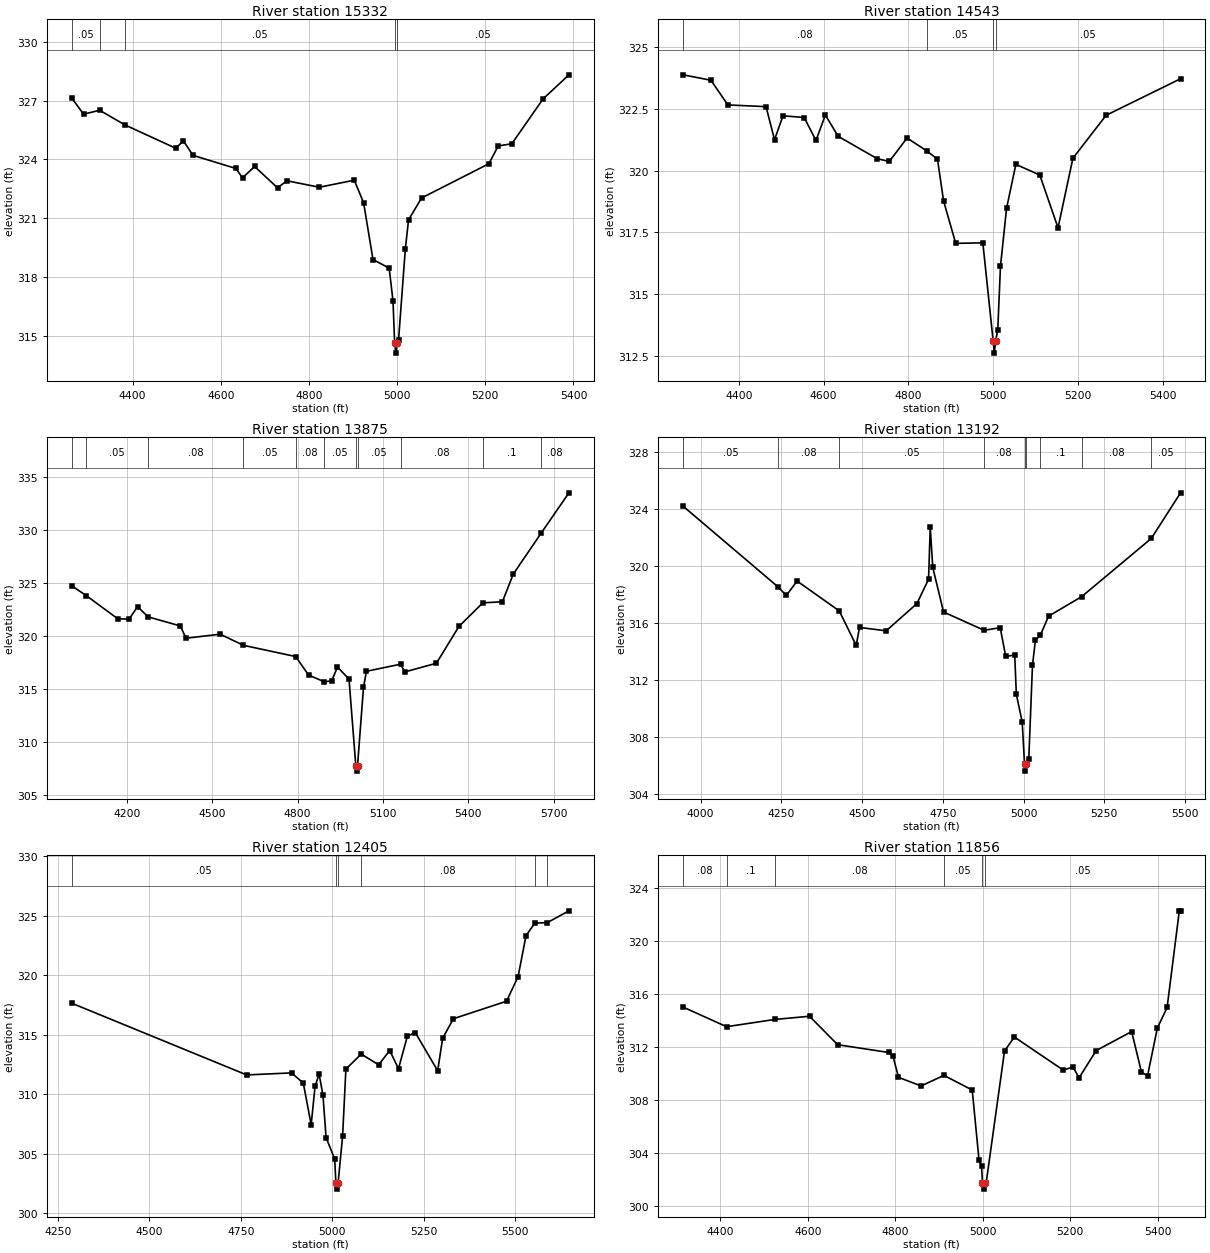
Type RM Length L Ch R = 1 ,15332   ,789,789,789
BEGIN DESCRIPTION:
UNT075 IN GIBB 2.0
END DESCRIPTION:
XS GIS Cut Line= 3
      3544485.14     10235726.96      3544365.34     10235430.06
      3543942.09     10234741.62
#Sta/Elev= 30
  4261.5  327.15  4288.8  326.31  4325.2  326.51  4382.9  325.76  4497.9  324.57
  4515.3  324.95  4536.8  324.21  4634.1  323.54  4649.5  323.06  4676.7  323.64
  4728.8  322.55  4750.1  322.91  4823.5  322.58  4902.8  322.94    4924  321.79
  4945.3  318.89    4982  318.45  4990.7  316.77  4994.4  314.61  4997.2  314.11
  5000.4  314.61  5003.3  314.79  5018.7  319.44  5025.9  320.91  5055.4  322.03
  5208.1  323.78  5229.4  324.69  5260.2   324.8  5331.1  327.09  5389.8  328.32
#Mann= 5 ,-1 , 0
  4261.5     .05       0  4325.2     .08       0  4382.9     .05       0
  4994.4     .04       0  5000.4     .05       0
Bank Sta=4994.4,5000.4
XS Rating Curve= 0 ,0
Exp/Cntr=0.3,0.1

Type RM Length L Ch R = 1 ,14543   ,668,668,668
BEGIN DESCRIPTION:
UNT075 IN GIBB 1.0
END DESCRIPTION:
XS GIS Cut Line= 3
      3544724.72     10235607.18       3544714.3     10235174.85
      3544246.27     10234600.44
#Sta/Elev= 30
  4268.8  323.88  4334.4  323.66  4374.4  322.66  4464.4  322.59  4484.4  321.25
  4504.4  322.22  4554.4  322.15  4582.1  321.22  4604.4  322.25  4634.4  321.39
  4726.6  320.48  4755.3  320.37    4797  321.32  4843.4   320.8  4868.8  320.46
  4883.2  318.77  4911.8  317.05  4975.8  317.07  5000.1   313.1  5002.8   312.6
  5006.1   313.1    5011  313.54  5017.4  316.12  5031.8  318.47  5053.7  320.25
  5110.1  319.82  5153.2  317.68  5188.3   320.5  5266.6  322.24  5442.2  323.72
#Mann= 4 ,-1 , 0
  4268.8     .08       0  4843.4     .05       0  5000.1     .04       0
  5006.1     .05       0
Bank Sta=5000.1,5006.1
XS Rating Curve= 0 ,0
Exp/Cntr=0.3,0.1

Type RM Length L Ch R = 1 ,13875   ,683,683,683
BEGIN DESCRIPTION:
UNT074 IN GIBB 9.0
END DESCRIPTION:
XS GIS Cut Line= 3
      3544998.26     10235823.74      3545022.56     10235011.29
      3545192.11      10234091.6
#Sta/Elev= 30
  4005.4  324.71  4057.3  323.77  4167.6  321.59  4207.6  321.55  4237.6  322.74
  4273.9  321.77  4387.7  320.91  4407.7  319.75  4527.7  320.13  4609.7  319.08
  4793.3  318.02  4838.2  316.28  4892.7  315.65  4919.5  315.72  4939.9  317.03
  4980.5   315.9  5004.4  307.71  5007.1  307.21  5010.4  307.71  5031.4  315.12
  5041.6  316.63  5161.6   317.3  5176.5  316.57  5287.6  317.39    5367  320.87
  5450.8  323.09  5519.5  323.19  5557.7   325.8  5655.5  329.66  5753.4  333.47
#Mann= 11 ,-1 , 0
  4005.4     .08       0  4057.3     .05       0  4273.9     .08       0
  4609.7     .05       0  4793.3     .08       0  4892.7     .05       0
  5004.4     .04       0  5010.4     .05       0  5161.6     .08       0
  5450.8      .1       0  5655.5     .08       0
Bank Sta=5004.4,5010.4
XS Rating Curve= 0 ,0
Exp/Cntr=0.3,0.1

Type RM Length L Ch R = 1 ,13192   ,787,787,787
BEGIN DESCRIPTION:
UNT074 IN GIBB 7.0
END DESCRIPTION:
XS GIS Cut Line= 3
      3545392.11     10235841.62      3545611.39     10234964.66
       3545742.1     10234341.68
#Sta/Elev= 30
  3945.8  324.21  4239.8  318.55  4265.3  317.95  4298.8  318.96  4429.3  316.87
  4481.8  314.45  4492.1  315.71  4574.6  315.47  4669.8  317.38  4705.9  319.09
  4711.1  322.75  4718.9  319.92  4752.3  316.79  4877.9  315.51  4927.9  315.69
  4944.8  313.67  4972.7  313.78  4977.8  311.01  4995.9  309.08  5003.1  306.13
  5005.9  305.63  5009.1  306.13  5016.3   306.5  5027.7  313.04  5036.8  314.81
  5052.3  315.17  5077.6   316.5  5180.2  317.87  5395.7  321.95  5486.3  325.15
#Mann= 9 ,-1 , 0
  3945.8     .05       0  4239.8     .08       0  4429.3     .05       0
  4877.9     .08       0  5003.1     .07       0  5009.1     .08       0
  5052.3      .1       0  5180.2     .08       0  5395.7     .05       0
Bank Sta=5003.1,5009.1
XS Rating Curve= 0 ,0
Exp/Cntr=0.3,0.1

Type RM Length L Ch R = 1 ,12405   ,549,549,549
BEGIN DESCRIPTION:
UNT074 IN GIBB 5.0
END DESCRIPTION:
XS GIS Cut Line= 3
      3546092.12     10235691.61      3546435.16     10234815.95
       3546644.1     10234452.25
#Sta/Elev= 30
  4286.9  317.66  4765.7  311.63  4888.3   311.8  4920.5  310.95    4942  307.45
  4952.7  310.67  4963.7   311.7  4974.2  309.94  4982.8  306.37  5006.4  304.57
  5009.6  302.54  5012.3  302.04  5015.6  302.54  5027.9  306.46    5037  312.12
  5078.9  313.38  5126.5  312.48  5156.8  313.68  5180.8  312.15  5205.2  314.91
    5227  315.17  5287.9  311.98  5301.5  314.71    5331  316.35  5476.2  317.82
  5507.8  319.89  5529.4  323.33  5553.7  324.38  5587.6  324.42  5646.8  325.41
#Mann= 6 ,-1 , 0
  4286.9     .05       0  5009.6     .04       0  5015.6     .05       0
  5078.9     .08       0  5553.7      .1       0  5587.6     .08       0
Bank Sta=5009.6,5015.6
XS Rating Curve= 0 ,0
Exp/Cntr=0.3,0.1

Type RM Length L Ch R = 1 ,11856   ,623,623,623
BEGIN DESCRIPTION:
UNT074 IN GIBB 4.0
END DESCRIPTION:
XS GIS Cut Line= 3
      3546439.21     10235934.93      3546792.11     10235341.64
       3546992.1     10234941.66
#Sta/Elev= 30
    4315  315.01  4414.4  313.53  4525.1  314.08  4604.1  314.32  4668.3  312.17
  4785.2  311.58    4795   311.3  4807.5   309.7  4859.2  309.05  4911.4  309.85
  4976.1  308.74  4991.7  303.43  4997.5  303.02  4999.4  301.75  5002.1  301.25
  5005.4  301.75  5008.1  301.75    5050  311.69  5072.4  312.75  5184.2  310.25
  5206.5  310.48  5220.5  309.67  5259.7  311.73  5340.7  313.16  5363.1   310.1
    5377  309.81  5399.4  313.42  5421.8  314.99  5449.7  322.29  5452.5  322.29
#Mann= 6 ,-1 , 0
    4315     .08       0  4414.4      .1       0  4525.1     .08       0
  4911.4     .05       0  4999.4     .04       0  5005.4     .05       0
Bank Sta=4999.4,5005.4
XS Rating Curve= 0 ,0
Exp/Cntr=0.3,0.1

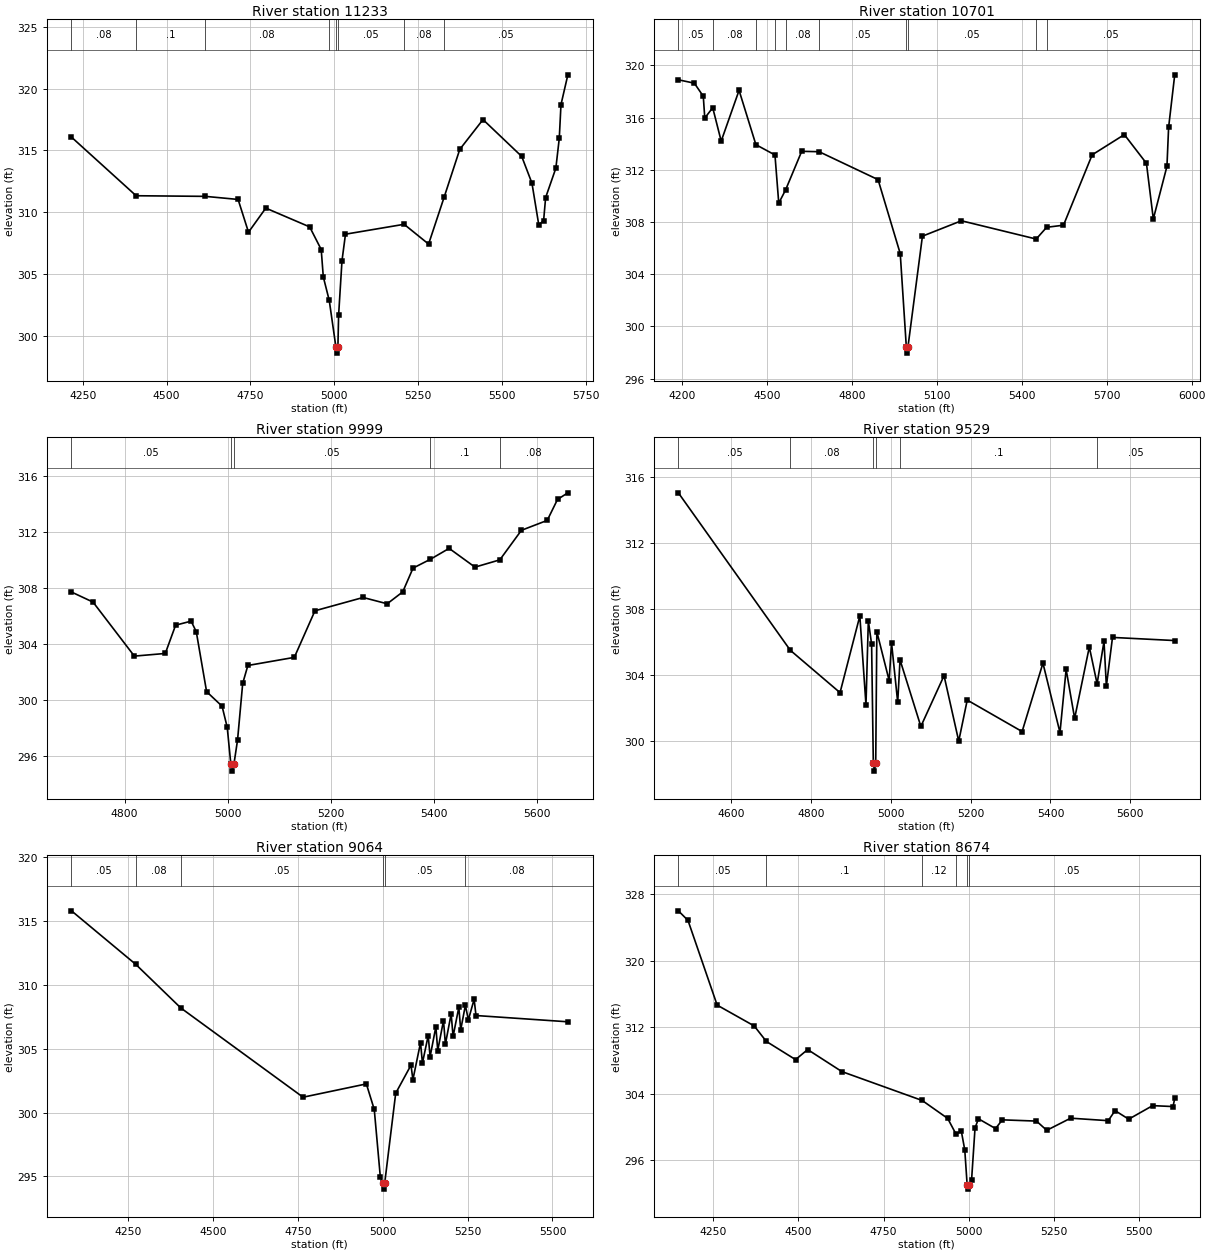
Type RM Length L Ch R = 1 ,11233   ,532,532,532
BEGIN DESCRIPTION:
UNT074 IN GIBB 2.0
END DESCRIPTION:
XS GIS Cut Line= 3
      3547078.12     10236462.67      3547394.88     10235242.48
      3547353.24      10235026.5
#Sta/Elev= 30
  4216.5  316.07  4409.3  311.33  4615.7  311.28  4713.5  311.03  4744.5  308.38
  4796.1  310.33    4927  308.81  4961.4  306.98  4967.6  304.77  4985.4  302.86
  5005.2   299.1  5007.9   298.6  5011.2   299.1  5013.3  301.67  5023.4  306.08
  5033.8  308.22  5208.7  309.02  5281.7  307.42  5327.8  311.19  5374.7  315.08
    5444  317.49  5559.5  314.51    5590  312.35  5610.4  308.97  5624.8  309.32
  5630.8  311.18  5661.3  313.56  5671.5  315.97  5676.6   318.7  5697.1  321.11
#Mann= 8 ,-1 , 0
  4216.5     .08       0  4409.3      .1       0  4615.7     .08       0
  4985.4     .05       0  5005.2     .04       0  5011.2     .05       0
  5208.7     .08       0  5327.8     .05       0
Bank Sta=5005.2,5011.2
XS Rating Curve= 0 ,0
Exp/Cntr=0.3,0.1

Type RM Length L Ch R = 1 ,10701   ,702,702,702
BEGIN DESCRIPTION:
UNT074 IN GIBB 1.0
END DESCRIPTION:
XS GIS Cut Line= 3
      3548015.61     10236688.35      3547835.06      10236146.7
      3547399.31     10235046.07
#Sta/Elev= 30
  4185.5   318.9    4242  318.64  4273.6  317.64  4278.9  315.97    4307  316.76
  4336.9   314.2  4400.1  318.09  4459.6  313.93    4527  313.14  4540.4  309.45
  4564.5  310.46  4621.5  313.42  4683.1  313.39  4891.5  311.25  4969.9  305.58
  4991.3  298.46    4994  297.96  4997.3  298.46  5048.3  306.92  5186.1   308.1
  5450.5   306.7  5487.4   307.6    5547  307.76  5648.3  313.15  5762.1   314.7
  5840.2   312.5  5864.5  308.24  5912.7  312.27  5918.6  315.26  5940.2  319.28
#Mann= 10 ,-1 , 0
  4185.5     .05       0    4307     .08       0  4459.6      .1       0
    4527     .05       0  4564.5     .08       0  4683.1     .05       0
  4991.3     .04       0  4997.3     .05       0  5450.5     .08       0
  5487.4     .05       0
Bank Sta=4991.3,4997.3
XS Rating Curve= 0 ,0
Exp/Cntr=0.3,0.1

Type RM Length L Ch R = 1 ,9999    ,470,470,470
BEGIN DESCRIPTION:
CARTERS CR TRIB B 16.0
END DESCRIPTION:
XS GIS Cut Line= 3
      3548383.87     10235953.42      3548369.55     10235590.68
      3548392.11     10234991.62
#Sta/Elev= 30
    4697  307.71  4738.8  306.99  4818.9  303.13  4878.9  303.32  4898.9  305.34
    4929  305.63    4939  304.87    4959  300.59    4989  299.55    4999  298.04
    5006  295.41  5008.8  294.91    5012  295.41    5019  297.13    5029  301.18
    5039  302.46  5129.1  303.04  5169.1  306.37  5262.5  307.32  5309.2  306.87
  5339.3  307.72  5359.3  309.42  5392.9  310.05  5429.3  310.83  5479.4  309.49
  5527.6  310.01  5569.4  312.12  5619.5  312.83  5639.5  314.33  5659.5   314.8
#Mann= 5 ,-1 , 0
    4697     .05       0    5006     .04       0    5012     .05       0
  5392.9      .1       0  5527.6     .08       0
Bank Sta=5006,5012
XS Rating Curve= 0 ,0
Exp/Cntr=0.3,0.1

Type RM Length L Ch R = 1 ,9529    ,465,465,465
BEGIN DESCRIPTION:
CARTERS CR TRIB B 15.0
END DESCRIPTION:
XS GIS Cut Line= 3
      3548447.58     10235930.04      3548764.73     10235611.01
      3549178.11     10234933.28
#Sta/Elev= 30
  4467.7  315.07  4748.2  305.52  4872.8  302.95  4922.4   307.6  4937.8  302.21
  4943.7  307.31  4951.9  305.89  4956.2  298.69  4958.9  298.19  4962.2  298.69
    4965  306.65  4995.9  303.68  5001.8  305.98  5017.3  302.36  5023.1  304.94
  5075.3   300.9  5133.4  303.98  5170.2  300.01  5191.5   302.5    5329  300.59
  5381.2  304.74  5423.9  300.53  5439.3  304.36  5460.6  301.39  5497.4  305.72
  5516.9  303.49  5534.2  306.06  5540.1  303.35  5555.5   306.3  5711.4  306.11
#Mann= 6 ,-1 , 0
  4467.7     .05       0  4748.2     .08       0  4956.2     .07       0
  4962.2     .08       0  5023.1      .1       0  5516.9     .05       0
Bank Sta=4956.2,4962.2
XS Rating Curve= 0 ,0
Exp/Cntr=0.3,0.1

Type RM Length L Ch R = 1 ,9064    ,390,390,390
BEGIN DESCRIPTION:
CARTERS CR TRIB B 14.0
END DESCRIPTION:
XS GIS Cut Line= 3
      3548897.63     10236336.11      3549270.82     10235491.64
       3549506.7     10235005.83
#Sta/Elev= 30
  4082.1  315.78  4271.7  311.59  4404.5  308.18  4764.8   301.2  4951.4  302.24
  4974.7  300.24  4992.6  294.95  4999.6  294.51  5002.4  294.01  5005.6  294.51
  5037.9  301.51    5083  303.71  5088.6  302.57  5111.1  305.47  5116.7  303.87
  5133.7  306.02  5139.3  304.37  5156.3  306.71  5161.8  304.85  5178.8   307.2
  5184.4  305.35  5201.4  307.72    5207  305.95    5224  308.23  5229.5  306.47
  5243.3  308.39  5252.1  307.25  5269.1  308.86  5274.6  307.59  5545.4   307.1
#Mann= 6 ,-1 , 0
  4082.1     .05       0  4271.7     .08       0  4404.5     .05       0
  4999.6     .04       0  5005.6     .05       0  5243.3     .08       0
Bank Sta=4999.6,5005.6
XS Rating Curve= 0 ,0
Exp/Cntr=0.3,0.1

Type RM Length L Ch R = 1 ,8674    ,597,597,597
BEGIN DESCRIPTION:
CARTERS CR TRIB B 13.0
END DESCRIPTION:
XS GIS Cut Line= 3
       3549992.1     10236391.64       3549595.8     10235851.98
      3549547.09     10235066.94
#Sta/Elev= 30
  4148.1  325.99  4176.3  324.84  4261.9  314.64  4370.7  312.13  4406.2  310.27
  4491.9  308.08  4527.4  309.29  4627.7  306.64  4863.4  303.16  4938.2     301
  4962.1  299.15  4978.3  299.44  4988.3  297.21  4995.3  292.99  4998.1  292.49
  5001.3  292.99  5008.3  293.62  5018.4  299.85  5028.4  300.96  5078.5  299.78
  5098.5  300.83  5198.7  300.68  5228.8  299.57  5298.9  301.03  5409.1  300.73
  5429.2  301.94  5469.2  300.91  5539.4  302.54  5599.2  302.43  5604.2   303.4
#Mann= 6 ,-1 , 0
  4148.1     .05       0  4406.2      .1       0  4863.4     .12       0
  4962.1     .05       0  4995.3     .04       0  5001.3     .05       0
Bank Sta=4995.3,5001.3
XS Rating Curve= 0 ,0
Exp/Cntr=0.3,0.1

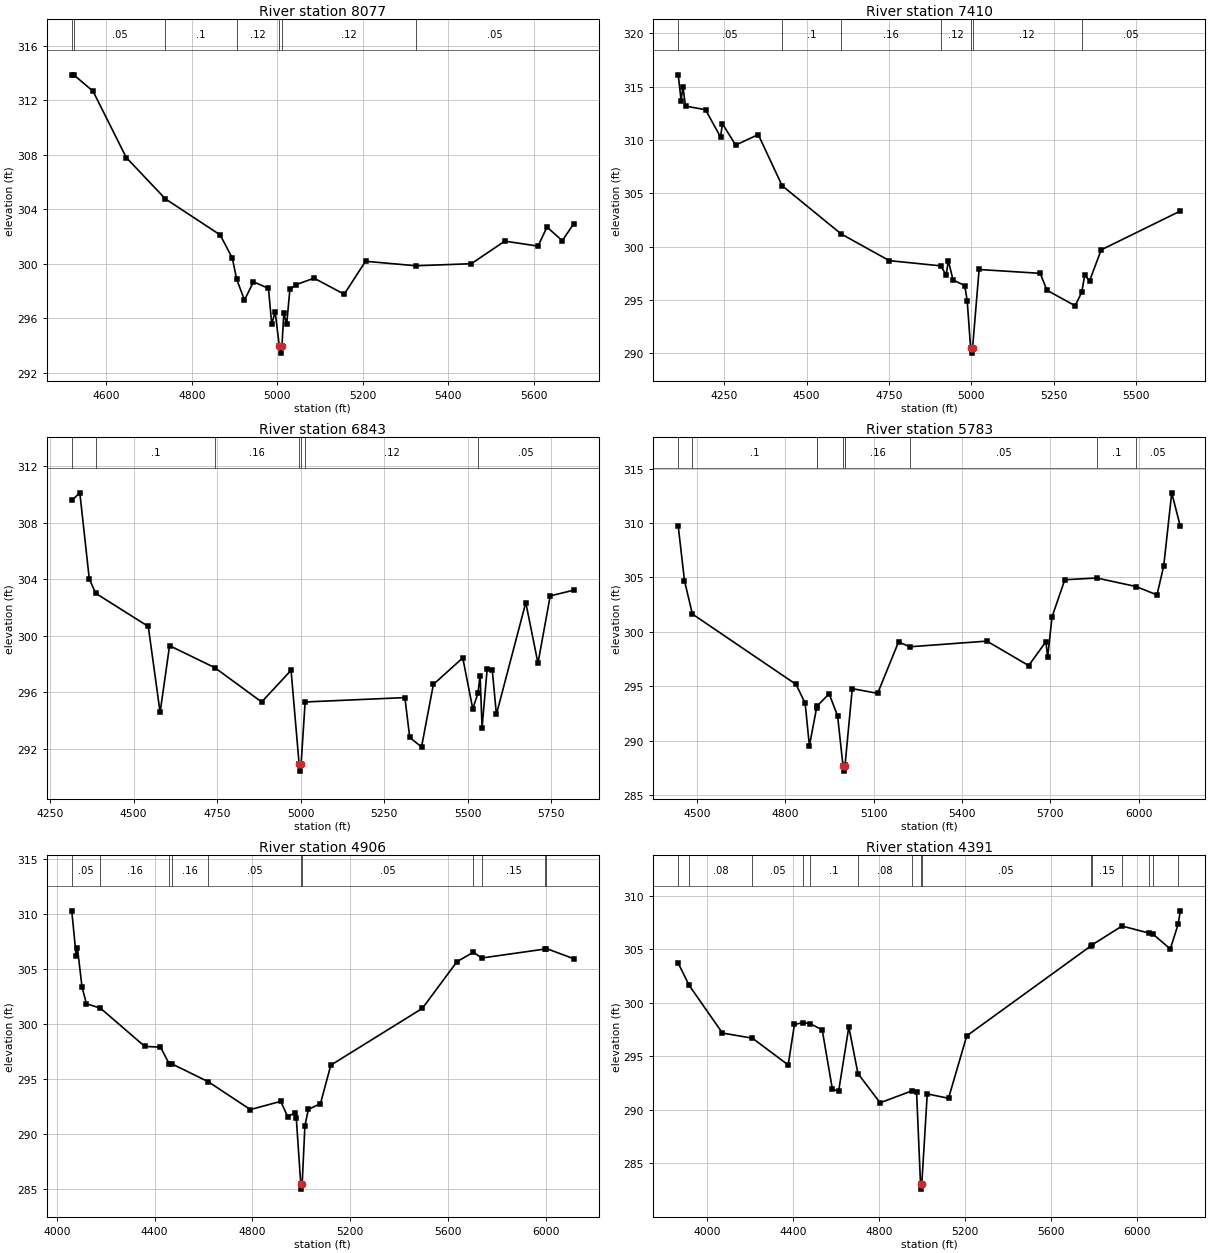
Type RM Length L Ch R = 1 ,8077    ,667,667,667
BEGIN DESCRIPTION:
CARTERS CR TRIB B 12.0
END DESCRIPTION:
XS GIS Cut Line= 3
      3550392.11     10235841.64      3550075.23     10235491.64
      3549600.16     10234975.27
#Sta/Elev= 30
  4519.5  313.86  4524.8  313.84  4569.2  312.66  4646.9  307.79  4738.3  304.76
  4866.6  302.11    4895   300.4    4905  298.86  4923.3  297.34  4944.3  298.67
  4979.4  298.19  4986.9  295.59    4995  296.46  5004.8  293.94  5007.6  293.44
  5010.8  293.94  5015.2  296.36    5022  295.57  5029.4  298.11  5043.6  298.46
  5086.1  298.94  5156.4  297.76  5206.3  300.18  5323.9  299.85  5453.6     300
  5531.9  301.66  5609.5  301.29  5630.5  302.69  5666.3  301.69  5693.3  302.95
#Mann= 7 ,-1 , 0
  4519.5     .08       0  4524.8     .05       0  4738.3      .1       0
    4905     .12       0  5004.8     .07       0  5010.8     .12       0
  5323.9     .05       0
Bank Sta=5004.8,5010.8
XS Rating Curve= 0 ,0
Exp/Cntr=0.3,0.1

Type RM Length L Ch R = 1 ,7410    ,567,567,567
BEGIN DESCRIPTION:
CARTERS CR TRIB B 10.0
END DESCRIPTION:
XS GIS Cut Line= 3
      3550842.12     10235741.67      3550560.34     10235138.92
       3549877.1      10234620.7
#Sta/Elev= 30
  4110.8   316.1  4119.5  313.69    4125     315  4132.9  313.17  4193.6  312.83
  4239.2  310.26  4244.8  311.52  4284.9  309.51  4353.5   310.5  4425.8  305.71
  4605.1  301.18  4751.1  298.68  4907.4  298.19  4923.6  297.31  4929.9  298.68
  4944.4  296.87  4979.8  296.34  4987.3  294.92  4997.6  290.51  5000.4  290.01
  5003.6  290.51  5023.4  297.85  5208.6  297.49  5229.4   295.9  5314.7  294.45
  5334.6  295.71  5343.8  297.33  5358.3  296.77  5393.7  299.69  5633.7  303.33
#Mann= 7 ,-1 , 0
  4110.8     .05       0  4425.8      .1       0  4605.1     .16       0
  4907.4     .12       0  4997.6     .07       0  5003.6     .12       0
  5334.6     .05       0
Bank Sta=4997.6,5003.6
XS Rating Curve= 0 ,0
Exp/Cntr=0.3,0.1

Type RM Length L Ch R = 1 ,6843    ,1060,1060,1060
BEGIN DESCRIPTION:
CARTERS CR TRIB B 9.0
END DESCRIPTION:
XS GIS Cut Line= 3
      3551283.38     10235184.38      3550877.14     10234785.09
       3550085.5     10234290.06
#Sta/Elev= 30
  4315.1  309.56  4339.2   310.1  4367.5  304.02  4386.4     303  4544.2  300.65
  4579.6  294.57  4607.9  299.29  4743.8  297.73  4883.6  295.31  4971.7  297.55
  4995.8  290.92  4998.6  290.42  5001.8  290.92  5013.8  295.31  5312.5  295.62
    5327   292.8  5362.4  292.13  5397.8  296.55  5485.8  298.43  5515.8  294.82
  5531.1  295.92  5537.7  297.18  5543.6  293.49  5558.9  297.66  5574.2  297.56
  5586.5  294.43  5674.5  302.34    5711  298.05  5747.6  302.81  5818.4  303.22
#Mann= 7 ,-1 , 0
  4315.1     .05       0  4386.4      .1       0  4743.8     .16       0
  4995.8     .07       0  5001.8     .16       0  5013.8     .12       0
  5531.1     .05       0
Bank Sta=4995.8,5001.8
XS Rating Curve= 0 ,0
Exp/Cntr=0.3,0.1

Type RM Length L Ch R = 1 ,5783    ,877,877,877
BEGIN DESCRIPTION:
CARTERS CR TRIB B 7.0
END DESCRIPTION:
XS GIS Cut Line= 3
       3551492.1     10235041.62      3551335.47     10234601.06
       3550597.3     10233606.43
#Sta/Elev= 30
  4435.8   309.7    4457   304.7  4483.8  301.63  4836.3  295.16  4867.1  293.43
  4881.5  289.51  4905.7  292.97    4909  293.21  4948.6   294.3  4977.4  292.26
  4995.7  287.69  4998.4  287.19  5001.7  287.69  5002.7  287.75  5027.2  294.77
  5113.5  294.34  5184.4  299.06    5223  298.62  5484.8  299.14  5626.7  296.89
  5685.1  299.08  5691.4   297.7    5706  301.36  5749.5  304.78  5858.2  304.94
  5991.1  304.16  6062.7  303.39  6085.7  306.06  6112.8  312.77    6142  309.69
#Mann= 10 ,-1 , 0
  4435.8     .05       0  4483.8      .1       0  4905.7     .16       0
    4909     .12       0  4995.7     .07       0  5001.7     .12       0
  5002.7     .16       0    5223     .05       0  5858.2      .1       0
  5991.1     .05       0
Bank Sta=4995.7,5001.7
XS Rating Curve= 0 ,0
Exp/Cntr=0.3,0.1

Type RM Length L Ch R = 1 ,4906    ,515,515,515
BEGIN DESCRIPTION:
CARTERS CR TRIB B 6.0
END DESCRIPTION:
XS GIS Cut Line= 3
      3551911.85     10234962.13      3551731.31     10234215.64
       3550807.7     10233319.81
#Sta/Elev= 30
  4060.8  310.32  4078.9  306.18    4084  306.95  4102.5  303.43  4120.7  301.87
  4177.6  301.48  4359.7  297.99  4423.9  297.93  4459.8   296.4  4472.1  296.39
  4619.7  294.78  4791.8  292.25  4915.9     293  4944.2  291.62  4972.5  291.93
  4979.7  291.45  4997.8  285.52  5000.5  285.02  5003.8  285.52  5014.9  290.79
  5029.1  292.27  5078.5  292.79  5120.9  296.29  5495.9  301.46  5637.2   305.7
  5704.3  306.55  5738.5  306.03  5998.5  306.85  6003.5  306.89  6115.5  305.96
#Mann= 11 ,-1 , 0
  4060.8     .05       0  4177.6     .16       0  4459.8     .05       0
  4472.1     .16       0  4619.7     .05       0  4997.8     .04       0
  5003.8     .05       0  5704.3      .1       0  5738.5     .15       0
  5998.5      .1       0  6003.5     .08       0
Bank Sta=4997.8,5003.8
XS Rating Curve= 0 ,0
Exp/Cntr=0.3,0.1

Type RM Length L Ch R = 1 ,4391    ,539,539,539
BEGIN DESCRIPTION:
CARTERS CR TRIB B 5.0
END DESCRIPTION:
XS GIS Cut Line= 3
      3552478.21     10234763.85      3552137.56      10233958.7
      3551096.53     10232931.55
#Sta/Elev= 30
    3867  303.69  3917.6  301.63  4072.7  297.17  4212.3  296.69  4378.7  294.19
  4407.8  297.97  4446.3  298.14  4481.5  298.05  4537.1  297.46  4584.5  291.92
  4613.6  291.75    4661  297.74  4703.4  293.39  4806.6  290.66  4956.9  291.79
  4976.3  291.64  4994.6   283.1  4997.4   282.6  5000.6   283.1  5025.9  291.49
  5124.9  291.08  5209.8  296.91  5786.5  305.29  5793.1   305.4  5932.2  307.16
  6060.1  306.49  6077.9  306.38  6157.2  305.02  6193.6  307.33  6203.7  308.58
#Mann= 15 ,-1 , 0
    3867      .1       0  3917.6     .08       0  4212.3     .05       0
  4446.3     .08       0  4481.5      .1       0  4703.4     .08       0
  4956.9     .05       0  4994.6     .04       0  5000.6     .05       0
  5786.5      .1       0  5793.1     .15       0  5932.2      .1       0
  6060.1     .15       0  6077.9      .1       0  6193.6     .08       0
Bank Sta=4994.6,5000.6
XS Rating Curve= 0 ,0
Exp/Cntr=0.3,0.1