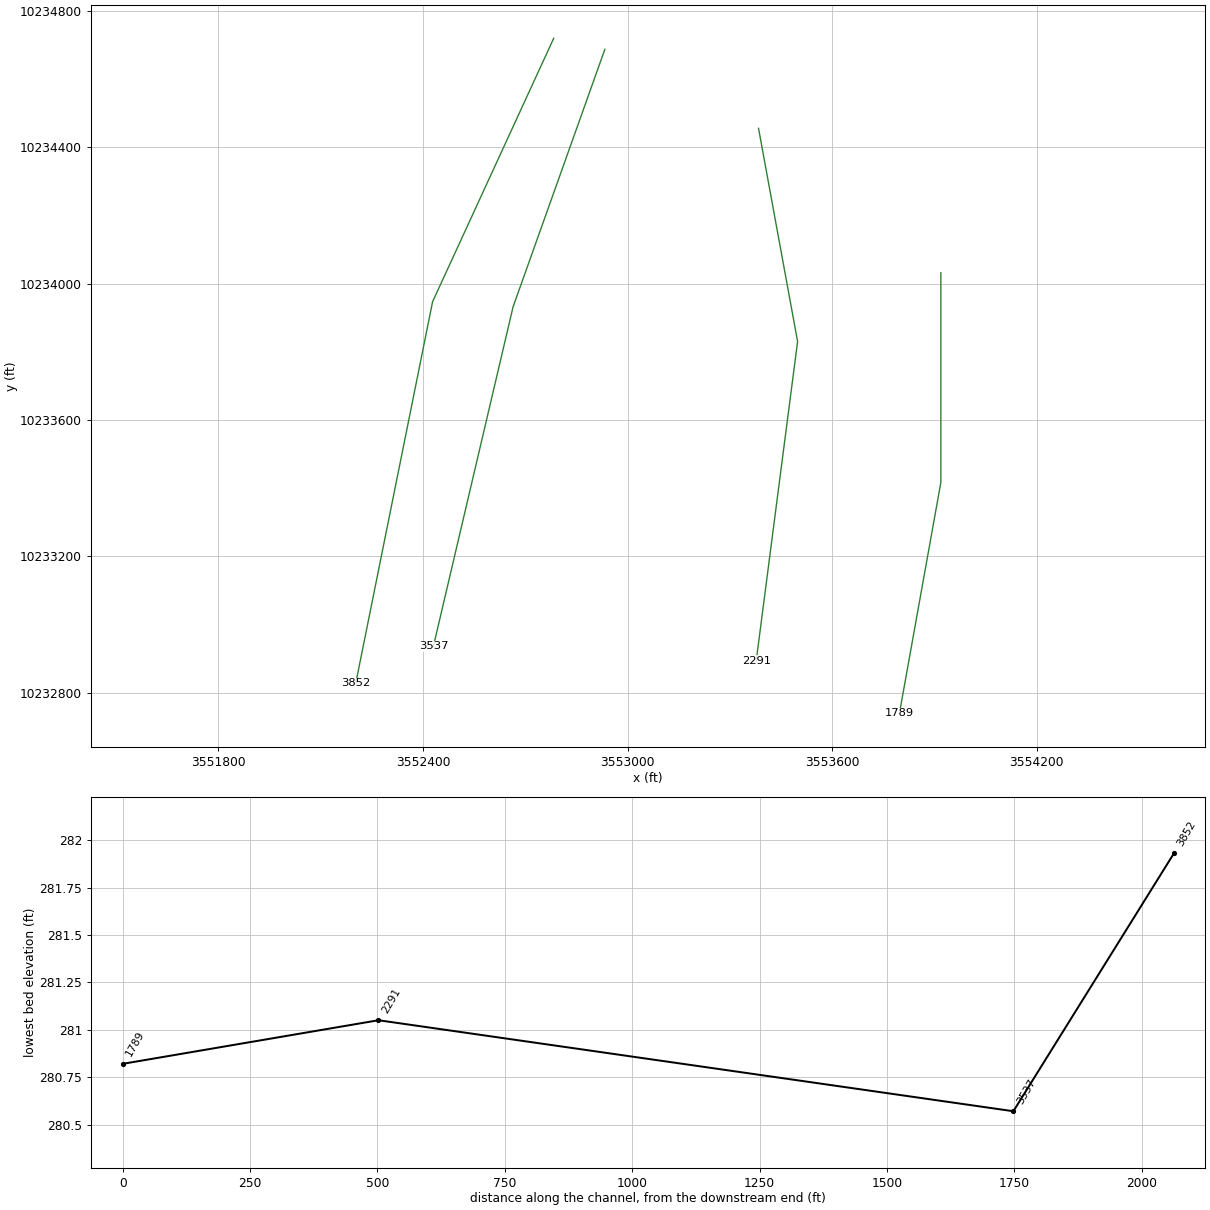
HEC-RAS study CARTERS CREEK TRIB B.prj: CARTERS CREEK TRIB B Base Level Engineering

--- CARTERS CREEK TRIB B.g01 (geometry) --- (continued)

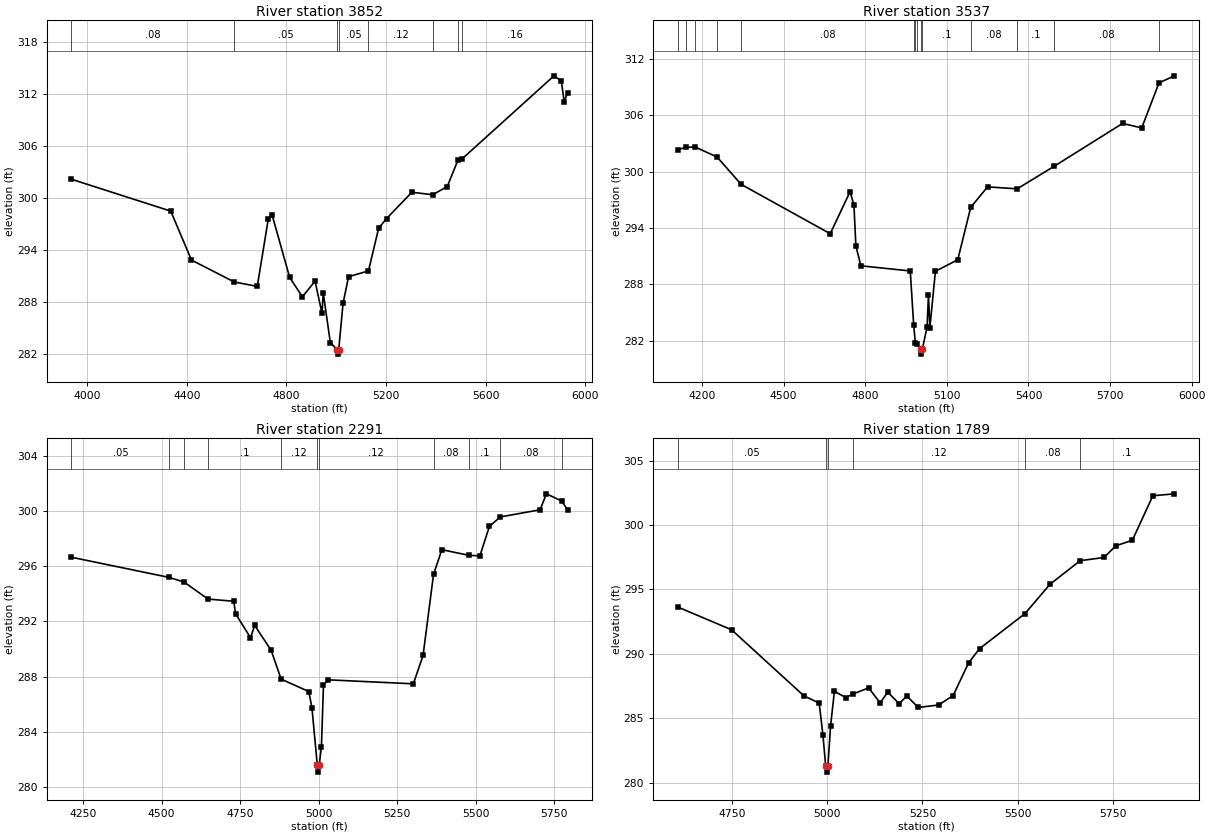
Type RM Length L Ch R = 1 ,3852    ,315,315,315
BEGIN DESCRIPTION:
CARTERS CR TRIB B 4.0
END DESCRIPTION:
XS GIS Cut Line= 3
      3552783.38     10234719.09      3552428.19     10233946.87
      3552202.77     10232827.94
#Sta/Elev= 30
  3937.2  302.12  4335.6  298.44  4418.7  292.79  4590.5  290.26  4682.9  289.75
  4726.9   297.5  4742.7  297.97  4812.9  290.78  4863.9  288.55  4914.9  290.36
  4942.5  286.64  4947.6  288.99  4976.1  283.27  5003.7  282.43  5006.5  281.93
  5009.7  282.43  5027.1  287.78  5049.3  290.87  5129.2  291.54    5170  296.47
  5201.7  297.58  5303.4  300.62  5386.8  300.33  5445.4  301.28  5487.9   304.3
  5505.6  304.49  5873.8  314.06    5903  313.48  5914.6  311.08  5928.6  312.13
#Mann= 8 ,-1 , 0
  3937.2     .08       0  4590.5     .05       0  5003.7     .04       0
  5009.7     .05       0  5129.2     .12       0  5386.8     .05       0
  5487.9     .08       0  5505.6     .16       0
Bank Sta=5003.7,5009.7
XS Rating Curve= 0 ,0
Exp/Cntr=0.3,0.1

Type RM Length L Ch R = 1 ,3537    ,1246,1246,1246
BEGIN DESCRIPTION:
CARTERS CR TRIB B 3.0
END DESCRIPTION:
XS GIS Cut Line= 3
      3552933.44     10234686.95      3552664.19     10233931.73
      3552430.46     10232936.18
#Sta/Elev= 30
  4112.2  302.37  4140.2  302.59  4173.5  302.65  4255.2  301.57  4343.4  298.66
  4671.1   293.4  4744.2  297.88  4758.3  296.44  4765.4   292.1  4783.8  289.98
  4965.4  289.43    4978  283.66  4984.2  281.76  4988.8  281.65  5003.5  281.07
  5006.3  280.57  5009.5  281.07  5027.1  283.43  5032.3  286.84  5037.5   283.4
  5057.9   289.4    5140  290.62  5187.6   296.2  5249.6  298.39  5358.6  298.18
  5493.2  300.56  5746.1  305.15  5816.4  304.67    5880  309.47  5936.6  310.22
#Mann= 14 ,-1 , 0
  4112.2     .08       0  4140.2      .1       0  4173.5     .08       0
  4255.2      .1       0  4343.4     .08       0    4978      .1       0
  4984.2     .12       0  4988.8      .1       0  5003.5     .07       0
  5009.5      .1       0  5187.6     .08       0  5358.6      .1       0
  5493.2     .08       0    5880     .16       0
Bank Sta=5003.5,5009.5
XS Rating Curve= 0 ,0
Exp/Cntr=0.3,0.1

Type RM Length L Ch R = 1 ,2291    ,502,502,502
BEGIN DESCRIPTION:
CARTERS CR TRIB B 2.0
END DESCRIPTION:
XS GIS Cut Line= 3
      3553384.09     10234455.22      3553498.67     10233830.22
      3553377.39     10232894.67
#Sta/Elev= 30
  4213.5  296.67  4525.1   295.2  4572.2  294.86    4648  293.63  4729.9  293.47
  4735.6  292.57  4783.1  290.82  4796.6  291.71  4848.9   289.9  4880.6  287.81
  4968.5  286.91  4978.6  285.74  4995.7  281.55  4998.5  281.05  5001.7  281.55
  5008.8   282.9  5015.3  287.35    5029  287.76  5301.3  287.47  5332.2  289.53
  5365.5  295.42    5392  297.22  5478.1  296.81    5513  296.77  5543.3  298.91
  5577.7   299.6  5704.6  300.12  5724.8  301.28  5774.1  300.75  5792.3  300.08
#Mann= 11 ,-1 , 0
  4213.5     .05       0  4525.1      .1       0  4572.2     .05       0
    4648      .1       0  4880.6     .12       0  4995.7     .07       0
  5001.7     .12       0  5365.5     .08       0  5478.1      .1       0
  5577.7     .08       0  5774.1     .05       0
Bank Sta=4995.7,5001.7
XS Rating Curve= 0 ,0
Exp/Cntr=0.3,0.1

Type RM Length L Ch R = 1 ,1789    ,0,0,0
BEGIN DESCRIPTION:
CARTERS CR TRIB B 1.0
END DESCRIPTION:
XS GIS Cut Line= 3
      3553918.81      10234031.6      3553918.81     10233417.03
      3553797.28     10232739.92
#Sta/Elev= 30
  4608.8  293.62  4748.8  291.87  4938.8  286.74  4978.8  286.18  4988.8  283.67
  4995.8  281.32  4998.5  280.82  5001.8  281.32  5008.8  284.42  5018.8  287.09
  5048.8  286.61  5067.9  286.89  5108.8  287.36  5138.8  286.19  5158.8  287.03
  5188.8  286.13  5208.8  286.73    5239  285.84  5292.2  286.03  5330.4  286.76
  5371.1   289.3  5399.7   290.4  5519.3  293.13  5584.4  295.39  5663.7  297.23
  5726.7  297.48  5757.2  298.38    5801  298.82  5854.7  302.27  5911.3  302.42
#Mann= 6 ,-1 , 0
  4608.8     .05       0  4995.8     .04       0  5001.8     .05       0
  5067.9     .12       0  5519.3     .08       0  5663.7      .1       0
Bank Sta=4995.8,5001.8
XS Rating Curve= 0 ,0
Exp/Cntr=0.3,0.1

Chan Stop Cuts=-1
Use User Specified Reach Order=0
Composite Channel Slope=5