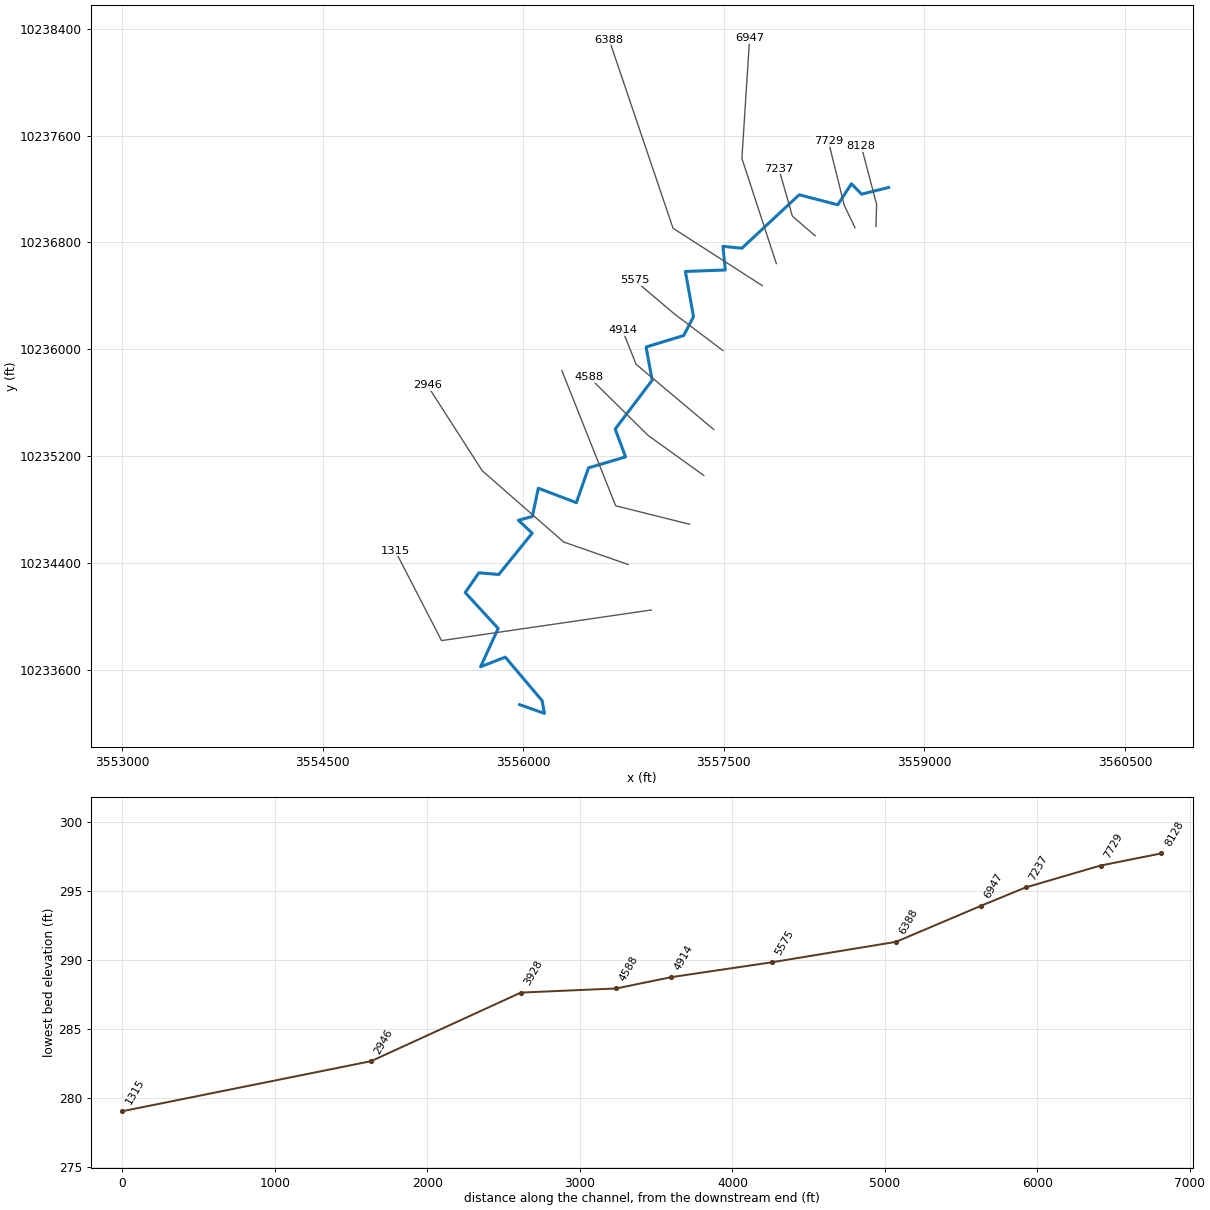
--- CARTERS CREEK TRIB C.prj (project) ---

Proj Title=CARTERS CREEK TRIB C Base Level Engineering
Current Plan=p01
Default Exp/Contr=0.3,0.1
English Units
Geom File=g01
Flow File=f01
Plan File=p01
Y Axis Title=Elevation
X Axis Title(PF)=Main Channel Distance
X Axis Title(XS)=Station
BEGIN DESCRIPTION:
CARTERS CREEK TRIB C
END DESCRIPTION:
DSS Export Rating Curves= 0
DSS Export Rating Curve Sorted= 0
DSS Export Volume Flow Curves= 0
DXF OffsetX= 0
DXF OffsetY= 0
DXF ScaleX= 1
DXF ScaleY= 10

--- CARTERS CREEK TRIB C.p01 (plan) ---

Plan Title=Multiple Run
Short Identifier=Multiple
Geom File=g01
Flow File=f01
Subcritical Flow
K Sum by GR= 0
Std Step Tol= 0.01
Critical Tol= 0.01
Num of Std Step Trials= 20
Max Error Tol= 0.3
Flow Tol Ratio= 0.001
Split Flow NTrial= 30
Split Flow Tol= 0.02
Split Flow Ratio= 0.02
Log Output Level= 0
Friction Slope Method= 1
Unsteady Friction Slope Method= 2
Unsteady Bridges Friction Slope Method= 1
Parabolic Critical Depth
Global Vel Dist=  1 , 1 , 1
Global Log Level= 0
CheckData=True
Encroach Param= -1, 0, 0, 0
BEGIN DESCRIPTION:
Multiple Run
END DESCRIPTION:

--- CARTERS CREEK TRIB C.f01 (steady flow) ---

Flow Title=Multiple
Program Version=4.10
Number of Profiles= 7
Profile Names=10-year,25-year,50-year,1pct_min,100-year,1pct_plu,500-year
River Rch & RM=CARTERS CREEK TR,Reach-1         ,8128
     529     710     856     758    1024    1385    1470
River Rch & RM=CARTERS CREEK TR,Reach-1         ,4914
     599     807     976     864    1169    1581    1681
Boundary for River Rch & Prof#=CARTERS CREEK TR,Reach-1         , 1
Up Type= 0
Dn Type= 3
Dn Slope=0.005
Boundary for River Rch & Prof#=CARTERS CREEK TR,Reach-1         , 2
Up Type= 0
Dn Type= 3
Dn Slope=0.005
Boundary for River Rch & Prof#=CARTERS CREEK TR,Reach-1         , 3
Up Type= 0
Dn Type= 3
Dn Slope=0.005
Boundary for River Rch & Prof#=CARTERS CREEK TR,Reach-1         , 4
Up Type= 0
Dn Type= 3
Dn Slope=0.005
Boundary for River Rch & Prof#=CARTERS CREEK TR,Reach-1         , 5
Up Type= 0
Dn Type= 3
Dn Slope=0.005
Boundary for River Rch & Prof#=CARTERS CREEK TR,Reach-1         , 6
Up Type= 0
Dn Type= 3
Dn Slope=0.005
Boundary for River Rch & Prof#=CARTERS CREEK TR,Reach-1         , 7
Up Type= 0
Dn Type= 3
Dn Slope=0.005
DSS Import GetInterval= 0
DSS Import GetPeak= 0
DSS Import FillOption= 0

--- CARTERS CREEK TRIB C.g01 (geometry) ---

Geom Title=Existing Conditions
Program Version=4.10

River Reach=CARTERS CREEK TR,Reach-1
Reach XY= 30
      3558732.11     10237211.64      3558530.24     10237161.35
      3558453.73     10237238.77      3558351.67     10237081.91
      3558063.17     10237156.65      3557634.46     10236756.86
      3557492.66     10236770.95      3557510.53     10236593.99
      3557211.95     10236582.94      3557272.71      10236244.4
      3557198.93     10236103.34      3556917.89     10236017.62
      3556963.47     10235769.14      3556686.77     10235403.47
      3556764.31     10235195.23      3556487.15     10235113.31
      3556396.36     10234852.98      3556111.72     10234960.88
      3556066.94     10234749.11      3555962.62     10234721.01
      3556066.08     10234624.57      3555816.08     10234315.54
      3555666.99     10234327.91      3555564.96     10234179.95
      3555811.25     10233911.83      3555680.03     10233625.11
      3555864.69     10233696.79      3556140.46     10233370.84
      3556157.48     10233276.14      3555972.11     10233341.64

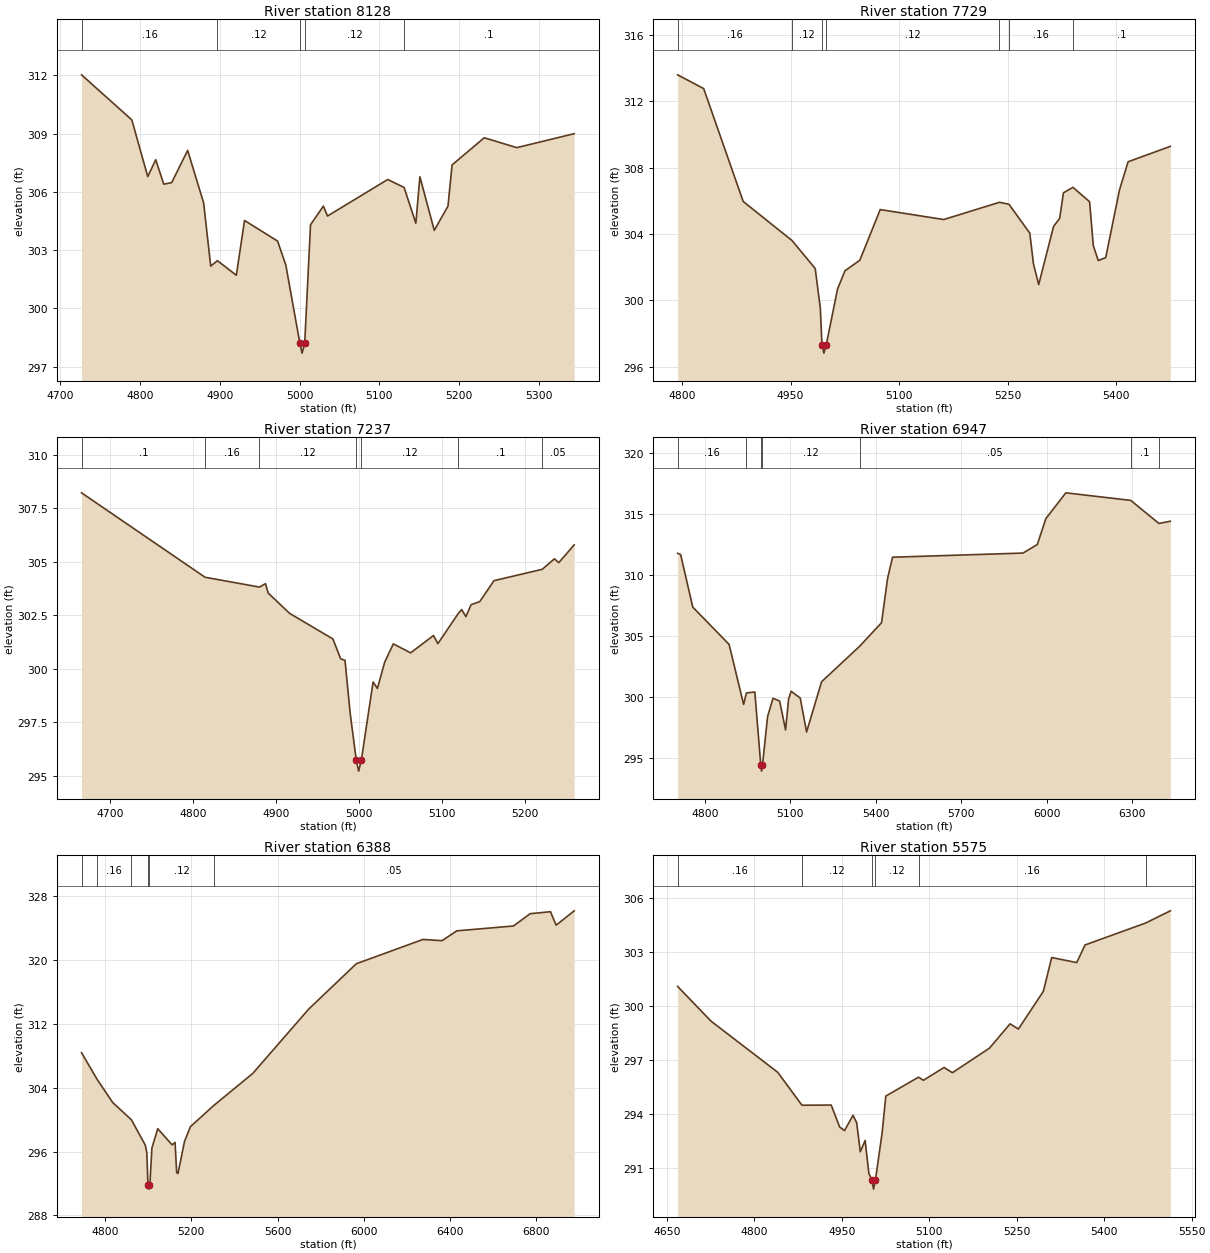
Type RM Length L Ch R = 1 ,8128    ,399,399,399
BEGIN DESCRIPTION:
CARTERS CREEK TRIB C 12.0
END DESCRIPTION:
XS GIS Cut Line= 3
      3558637.64     10236918.66      3558642.24     10237084.28
      3558527.25     10237521.22
#Sta/Elev= 30
  4726.8  312.03  4789.8  309.71  4809.8  306.79  4819.8  307.66  4829.8   306.4
  4839.8  306.48  4859.8  308.14  4879.8  305.44  4888.7  302.18  4897.1  302.46
  4920.8  301.71  4931.1  304.53  4972.5  303.47  4982.8  302.24  5000.5   298.2
  5003.2   297.7  5006.5   298.2  5013.8  304.31  5029.9  305.27  5035.1  304.76
  5110.6  306.64  5131.1  306.23  5145.8  304.39  5150.9  306.78  5168.9  304.02
  5186.1  305.27  5191.2  307.39  5231.6  308.79  5272.3  308.28  5344.3     309
#Mann= 5 ,-1 , 0
  4726.8     .16       0  4897.1     .12       0  5000.5     .07       0
  5006.5     .12       0  5131.1      .1       0
Bank Sta=5000.5,5006.5
XS Rating Curve= 0 ,0
Exp/Cntr=0.3,0.1

Type RM Length L Ch R = 1 ,7729    ,492,492,492
BEGIN DESCRIPTION:
CARTERS CREEK TRIB C 11.0
END DESCRIPTION:
XS GIS Cut Line= 3
      3558480.64     10236909.95      3558400.56     10237076.83
      3558281.05     10237558.32
#Sta/Elev= 30
  4793.9  313.59  4829.9  312.76  4884.5  305.96  4951.9  303.61  4984.1  301.92
  4991.2  299.52  4993.4  297.32  4996.1  296.82  4999.4  297.32  5014.9  300.67
  5025.2  301.78  5045.8  302.42    5074  305.47  5161.8  304.87  5238.9  305.91
    5252  305.79  5280.8  304.05  5285.9  302.19  5293.1  300.95  5313.7  304.46
  5322.1  304.94  5327.3  306.48  5340.5  306.81  5363.5  305.94  5368.6   303.3
  5375.5   302.4  5385.8  302.58  5404.8  306.65  5416.7  308.35  5475.1  309.28
#Mann= 7 ,-1 , 0
  4793.9     .16       0  4951.9     .12       0  4993.4     .07       0
  4999.4     .12       0  5238.9      .1       0    5252     .16       0
  5340.5      .1       0
Bank Sta=4993.4,4999.4
XS Rating Curve= 0 ,0
Exp/Cntr=0.3,0.1

Type RM Length L Ch R = 1 ,7237    ,290,290,290
BEGIN DESCRIPTION:
CARTERS CREEK TRIB C 10.0
END DESCRIPTION:
XS GIS Cut Line= 3
      3558182.33     10236849.73      3558012.16      10236996.9
      3557910.98     10237351.05
#Sta/Elev= 30
  4666.1  308.22  4814.8  304.28  4880.4  303.82  4887.6  303.98  4890.9  303.54
  4916.8  302.59  4968.8   301.4  4978.2  300.47  4983.4   300.4  4989.6  297.93
    4997  295.73  4999.8  295.23    5003  295.73  5017.2  299.39  5022.4  299.09
  5031.2  300.32  5041.6  301.17  5062.4  300.75    5090  301.56  5095.2  301.18
  5119.8  302.59  5123.8  302.77    5129  302.44  5135.2     303  5145.6  303.14
  5162.8  304.12  5220.9  304.65  5235.6  305.14  5240.8  304.96  5259.4  305.79
#Mann= 7 ,-1 , 0
  4666.1      .1       0  4814.8     .16       0  4880.4     .12       0
    4997     .07       0    5003     .12       0  5119.8      .1       0
  5220.9     .05       0
Bank Sta=4997,5003
XS Rating Curve= 0 ,0
Exp/Cntr=0.3,0.1

Type RM Length L Ch R = 1 ,6947    ,559,559,559
BEGIN DESCRIPTION:
CARTERS CREEK TRIB C 9.0
END DESCRIPTION:
XS GIS Cut Line= 3
      3557892.09     10236641.69      3557634.44     10237429.21
      3557692.43     10238327.34
#Sta/Elev= 30
  4704.6  311.77  4715.1  311.67  4757.6  307.36  4885.1   304.3    4936  299.38
  4945.9  300.32  4975.4   300.4  4996.2  294.41  4998.9  293.91  5002.2  294.41
  5020.2  298.39  5039.1  299.88  5062.3  299.66  5083.3  297.29  5093.8  299.81
  5102.8  300.46  5134.7   299.9    5157  297.12  5209.6  301.24  5343.2  304.15
    5420  306.08  5441.1  309.71  5458.6  311.45  5916.4  311.79  5966.5  312.49
  5996.6  314.62  6066.7  316.73  6294.4  316.11  6393.1  314.22  6433.2   314.4
#Mann= 7 ,-1 , 0
  4704.6     .16       0  4945.9     .12       0  4996.2     .07       0
  5002.2     .12       0  5343.2     .05       0  6294.4      .1       0
  6393.1     .16       0
Bank Sta=4996.2,5002.2
XS Rating Curve= 0 ,0
Exp/Cntr=0.3,0.1

Type RM Length L Ch R = 1 ,6388    ,813,813,813
BEGIN DESCRIPTION:
CARTERS CREEK TRIB C 8.0
END DESCRIPTION:
XS GIS Cut Line= 3
      3557786.81      10236477.2      3557119.56     10236906.17
      3556641.05     10238318.46
#Sta/Elev= 30
  4691.4  308.39  4763.8  305.04    4836  302.14  4922.7  299.98  4987.2  296.79
  4994.2  295.83  4999.4  291.79  5002.2  291.29  5005.4  291.79  5008.4   291.9
  5017.6  296.44  5044.7  298.86  5111.4  296.84    5125  297.14  5132.5  293.37
  5138.5  293.24  5168.9  297.28  5196.3  299.12  5306.1  301.81  5484.6  305.77
  5745.3  313.87  5965.6  319.54  6274.2  322.58  6363.2  322.43  6431.3  323.66
  6694.1  324.27  6771.6  325.81  6865.9  326.06    6892  324.37  6975.8  326.17
#Mann= 6 ,-1 , 0
  4691.4     .05       0  4763.8     .16       0  4922.7     .12       0
  4999.4     .07       0  5005.4     .12       0  5306.1     .05       0
Bank Sta=4999.4,5005.4
XS Rating Curve= 0 ,0
Exp/Cntr=0.3,0.1

Type RM Length L Ch R = 1 ,5575    ,661,661,661
BEGIN DESCRIPTION:
CARTERS CREEK TRIB C 6.0
END DESCRIPTION:
XS GIS Cut Line= 3
      3557492.08     10235991.66      3557129.14     10236265.64
      3556831.37      10236517.6
#Sta/Elev= 30
  4668.6  301.09  4725.8  299.16  4840.3  296.31  4881.7  294.48  4931.9  294.49
  4946.5  293.26  4954.8  293.07  4969.3  293.92  4975.6   293.5  4981.8  291.89
  4990.1  292.52  4996.4   290.7  5001.7  290.31  5004.5  289.81  5007.7  290.31
  5019.3  292.96  5025.5  294.99  5081.6  296.04  5090.1  295.87  5125.4  296.58
  5139.7  296.29  5203.4  297.66  5238.6  299.01  5252.9  298.72  5295.7  300.82
    5310   302.7  5352.9  302.42  5367.2   303.4    5471  304.62  5513.4   305.3
#Mann= 6 ,-1 , 0
  4668.6     .16       0  4881.7     .12       0  5001.7     .07       0
  5007.7     .12       0  5081.6     .16       0    5471     .05       0
Bank Sta=5001.7,5007.7
XS Rating Curve= 0 ,0
Exp/Cntr=0.3,0.1

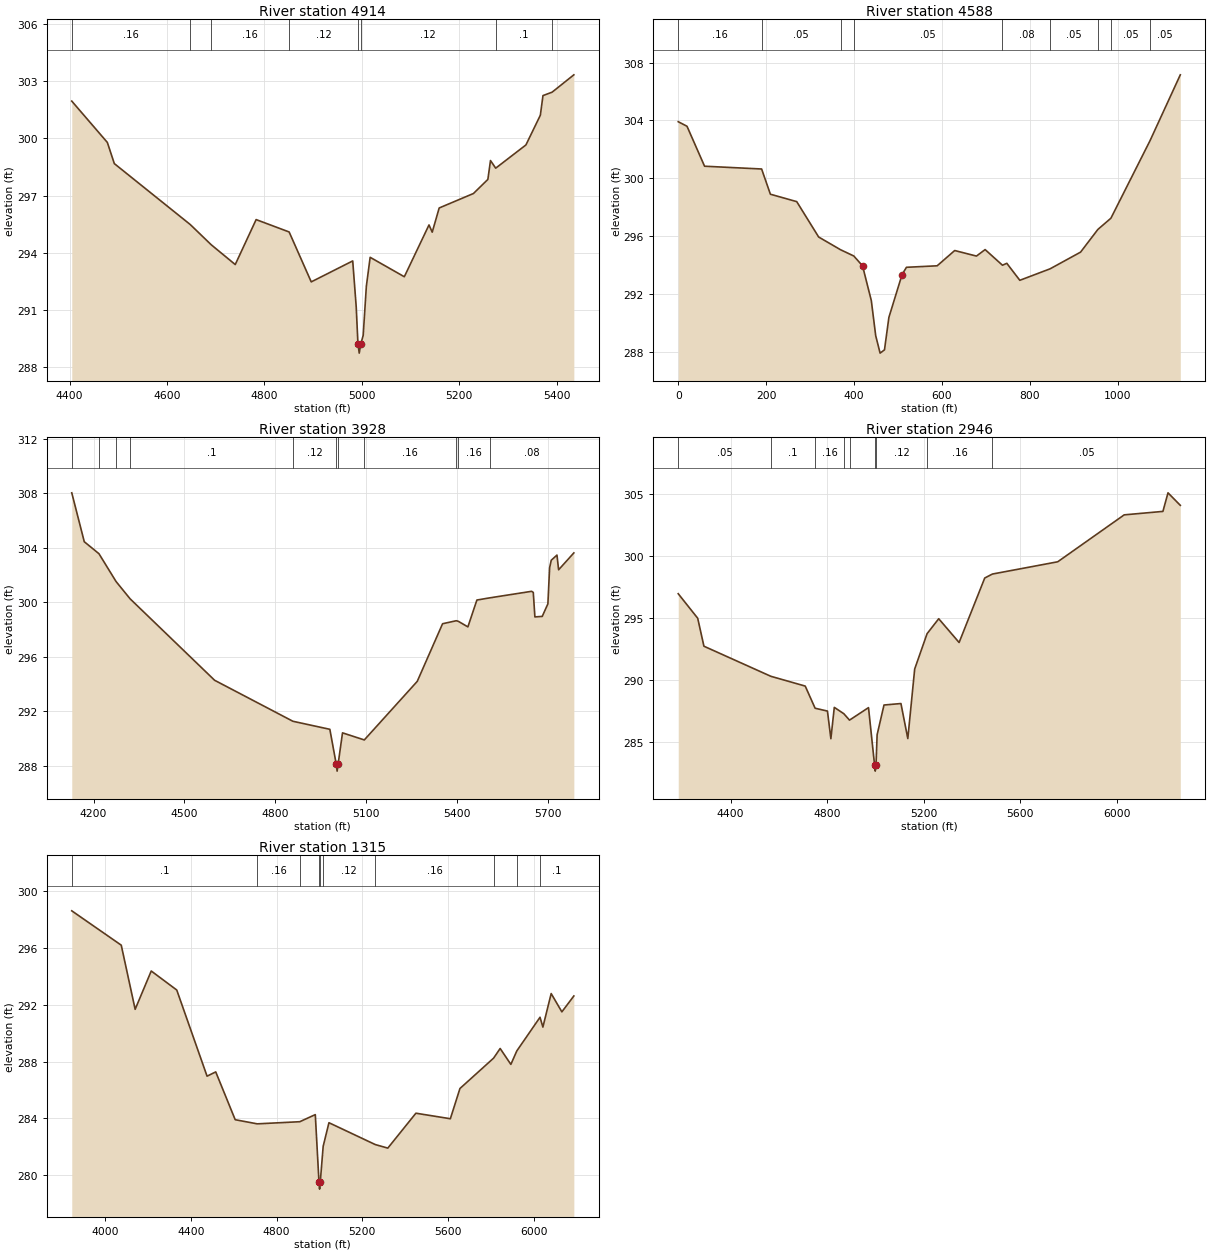
Type RM Length L Ch R = 1 ,4914    ,360,360,360
BEGIN DESCRIPTION:
CARTERS CREEK TRIB C 5.0
END DESCRIPTION:
XS GIS Cut Line= 3
      3557423.89     10235400.31      3556843.06     10235888.53
      3556742.09     10236141.67
#Sta/Elev= 30
  4404.3  301.96  4477.4  299.79  4491.7  298.68  4647.7  295.48  4690.7  294.42
  4740.1  293.38    4783  295.74  4850.8  295.09  4896.2  292.47  4981.4  293.57
  4988.6  291.15  4992.1  289.23  4994.8  288.73  4998.1  289.23  5002.9  289.66
  5009.4  292.24  5017.2  293.76  5087.4  292.74  5138.1  295.46  5144.7  295.08
    5159  296.35  5229.4  297.11    5259  297.85  5264.4  298.84  5275.1  298.44
  5337.2  299.66  5366.8  301.22  5372.2  302.25    5391  302.43  5435.6  303.34
#Mann= 8 ,-1 , 0
  4404.3     .16       0  4647.7      .1       0  4690.7     .16       0
  4850.8     .12       0  4992.1     .07       0  4998.1     .12       0
  5275.1      .1       0    5391     .05       0
Bank Sta=4992.1,4998.1
XS Rating Curve= 0 ,0
Exp/Cntr=0.3,0.1

Type RM Length L Ch R = 1 ,4588    ,626,626,626
BEGIN DESCRIPTION:
CARTERS CREEK TRIB C 4.0
END DESCRIPTION:
XS GIS Cut Line= 3
      3557349.86     10235056.11      3556931.58       10235357.
      3556492.08     10235791.67
#Sta/Elev= 30
       0303.915719.96869303.600259.90606300.8374189.7025300.6453209.6712298.9012
269.5773298.3885 319.499295.9411369.4207295.0598399.3737294.6302419.3424293.9473
439.3111291.5397449.2954289.1144459.2798287.9115469.2641288.1388479.2485290.3793
509.2015293.3411519.1859293.8469589.0762293.9505629.0136295.0064678.4714294.6234
698.2082 295.072737.6816  293.99  747.55294.1237777.1552 292.947846.2337293.7449
915.3123294.8946954.7858296.4665984.3909297.24121073.206302.59181142.285307.1576
#Mann= 9 ,-1 , 0
       0     .16       0189.7025     .05       0369.4207     .08       0
399.3737     .05       0737.6816     .08       0846.2337     .05       0
954.7858     .07       0984.3909     .05       01073.206     .05       0
Bank Sta=419.3424,509.2015
XS Rating Curve= 0 ,0
Exp/Cntr=0.3,0.1

Type RM Length L Ch R = 1 ,3928    ,982,982,982
BEGIN DESCRIPTION:
CARTERS CREEK TRIB C 3.0
END DESCRIPTION:
XS GIS Cut Line= 3
      3557242.13     10234691.64      3556690.28      10234829.6
      3556287.66      10235841.3
#Sta/Elev= 30
    4128  308.04  4169.3  304.45  4217.8  303.57  4274.2  301.53  4320.6  300.26
  4599.6  294.28  4858.1  291.27  4980.1  290.68  5001.3  288.11  5004.1  287.61
  5007.3  288.11  5021.9  290.42  5093.9   289.9  5268.7   294.2  5352.3  298.43
  5397.5  298.65    5404  298.61  5435.9   298.2  5465.6  300.17  5508.1  300.33
  5646.2  300.81  5651.8  300.73  5657.1  298.93  5681.4  298.97    5700  299.89
  5705.7  302.54  5711.1  303.09    5730  303.47  5735.4  302.39  5785.7  303.63
#Mann= 11 ,-1 , 0
    4128     .05       0  4217.8      .1       0  4274.2     .05       0
  4320.6      .1       0  4858.1     .12       0  5001.3     .07       0
  5007.3     .12       0  5093.9     .16       0  5397.5     .05       0
    5404     .16       0  5508.1     .08       0
Bank Sta=5001.3,5007.3
XS Rating Curve= 0 ,0
Exp/Cntr=0.3,0.1

Type RM Length L Ch R = 1 ,2946    ,1631,1631,1631
BEGIN DESCRIPTION:
CARTERS CREEK TRIB C 2.0
END DESCRIPTION:
XS GIS Cut Line= 4
      3556783.51      10234390.1      3556300.79     10234558.77
      3555692.11     10235091.64      3555281.03      10235731.8
#Sta/Elev= 30
  4183.2  296.97  4263.9  294.99  4289.7  292.73  4567.1   290.3  4709.6  289.51
  4750.5  287.72  4801.7  287.49  4815.9  285.26  4830.1  287.79  4869.4  287.28
  4893.2  286.76  4971.9  287.77    4997  283.14  4999.8  282.64    5003  283.14
  5007.6  285.58  5036.1  287.98  5106.3   288.1  5134.8  285.27  5163.3  290.89
  5214.6  293.74  5262.9  294.95  5347.4  293.03  5453.7  298.24  5485.6  298.56
  5756.2  299.55  6031.7  303.34  6192.2  303.62  6213.3  305.12  6264.3  304.11
#Mann= 9 ,-1 , 0
  4183.2     .05       0  4567.1      .1       0  4750.5     .16       0
  4869.4      .1       0  4893.2     .12       0    4997     .07       0
    5003     .12       0  5214.6     .16       0  5485.6     .05       0
Bank Sta=4997,5003
XS Rating Curve= 0 ,0
Exp/Cntr=0.3,0.1

Type RM Length L Ch R = 1 ,1315    ,0,0,0
BEGIN DESCRIPTION:
CARTERS CREEK TRIB C 1.0
END DESCRIPTION:
XS GIS Cut Line= 3
      3556957.11     10234049.81       3555387.7     10233820.65
      3555040.47     10234494.27
#Sta/Elev= 30
  3843.8  298.62  4074.8   296.2  4139.7  291.68  4214.8  294.38  4333.9  293.04
  4475.4  286.97  4515.9  287.27  4606.8   283.9  4709.9  283.61  4908.3  283.76
  4980.7  284.26  4997.9  279.51  5000.7  279.01  5003.9  279.51  5017.5  282.03
  5044.4  283.69  5260.7  282.15  5319.2   281.9  5450.4  284.36  5611.2  283.97
    5656   286.1  5813.1  288.24  5843.7  288.92  5893.7   287.8  5921.5  288.75
  6029.8  291.12  6043.2  290.43  6081.9  292.79  6131.8   291.5  6187.7  292.62
#Mann= 10 ,-1 , 0
  3843.8      .1       0  4709.9     .16       0  4908.3      .1       0
  4997.9     .07       0  5003.9      .1       0  5017.5     .12       0
  5260.7     .16       0  5813.1     .05       0  5921.5     .08       0
  6029.8      .1       0
Bank Sta=4997.9,5003.9
XS Rating Curve= 0 ,0
Exp/Cntr=0.3,0.1
Stream Node=CARTERS CREEK TR,Reach-1         , 0 , 0 ,Upstream end
Stream Node=CARTERS CREEK TR,Reach-1         , 0 , 1 ,Downstream end

Chan Stop Cuts=-1
Use User Specified Reach Order=0
Composite Channel Slope=5