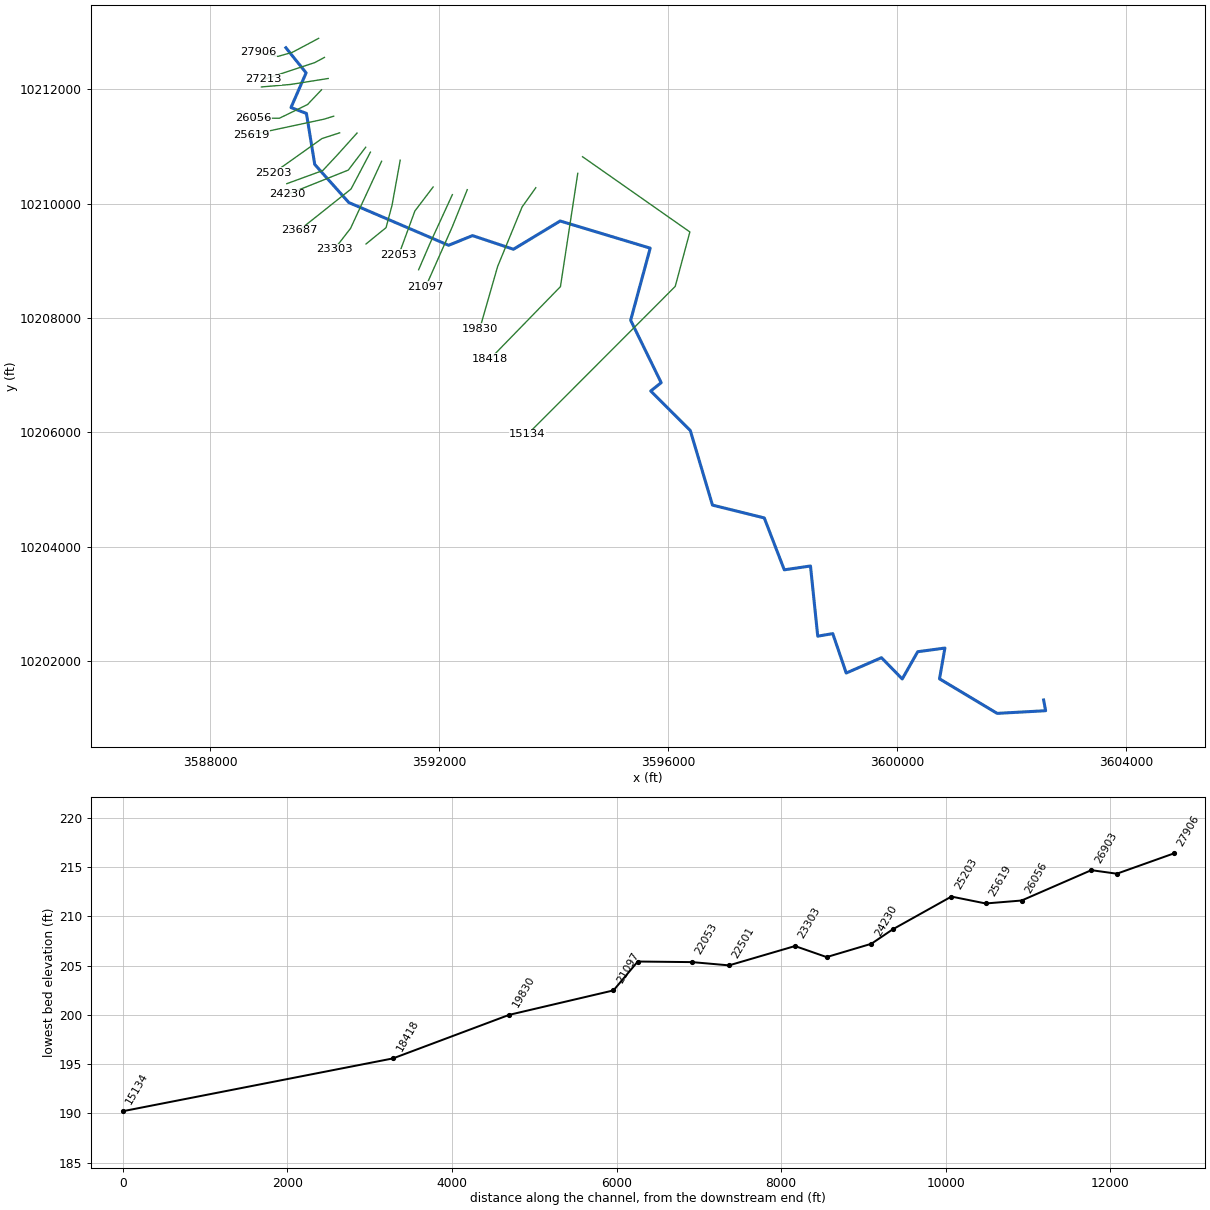
--- CARTERS CREEK TRIBUTARY 1.prj (project) ---

Proj Title=CARTERS CREEK TRIBUTARY 1 Base Level Engineering
Current Plan=p01
Default Exp/Contr=0.3,0.1
English Units
Geom File=g01
Flow File=f01
Plan File=p01
Y Axis Title=Elevation
X Axis Title(PF)=Main Channel Distance
X Axis Title(XS)=Station
BEGIN DESCRIPTION:
CARTERS CREEK TRIBUTARY 1
END DESCRIPTION:
DSS Export Rating Curves= 0
DSS Export Rating Curve Sorted= 0
DSS Export Volume Flow Curves= 0
DXF OffsetX= 0
DXF OffsetY= 0
DXF ScaleX= 1
DXF ScaleY= 10

--- CARTERS CREEK TRIBUTARY 1.p01 (plan) ---

Plan Title=Multiple Run
Short Identifier=Multiple
Geom File=g01
Flow File=f01
Subcritical Flow
K Sum by GR= 0
Std Step Tol= 0.01
Critical Tol= 0.01
Num of Std Step Trials= 20
Max Error Tol= 0.3
Flow Tol Ratio= 0.001
Split Flow NTrial= 30
Split Flow Tol= 0.02
Split Flow Ratio= 0.02
Log Output Level= 0
Friction Slope Method= 1
Unsteady Friction Slope Method= 2
Unsteady Bridges Friction Slope Method= 1
Parabolic Critical Depth
Global Vel Dist=  1 , 1 , 1
Global Log Level= 0
CheckData=True
Encroach Param= -1, 0, 0, 0
BEGIN DESCRIPTION:
Multiple Run
END DESCRIPTION:

--- CARTERS CREEK TRIBUTARY 1.f01 (steady flow) ---

Flow Title=Multiple
Program Version=4.10
Number of Profiles= 7
Profile Names=10-year,25-year,50-year,1pct_min,100-year,1pct_plu,500-year
River Rch & RM=CARTERS CREEK TR,Reach-1         ,27906
     557     748     902     798    1080    1460    1548
River Rch & RM=CARTERS CREEK TR,Reach-1         ,26056
     876    1200    1467    1312    1774    2399    2602
River Rch & RM=CARTERS CREEK TR,Reach-1         ,18418
    1334    1857    2295    2072    2802    3789    4188
Boundary for River Rch & Prof#=CARTERS CREEK TR,Reach-1         , 1
Up Type= 0
Dn Type= 3
Dn Slope=0.002
Boundary for River Rch & Prof#=CARTERS CREEK TR,Reach-1         , 2
Up Type= 0
Dn Type= 3
Dn Slope=0.002
Boundary for River Rch & Prof#=CARTERS CREEK TR,Reach-1         , 3
Up Type= 0
Dn Type= 3
Dn Slope=0.002
Boundary for River Rch & Prof#=CARTERS CREEK TR,Reach-1         , 4
Up Type= 0
Dn Type= 3
Dn Slope=0.002
Boundary for River Rch & Prof#=CARTERS CREEK TR,Reach-1         , 5
Up Type= 0
Dn Type= 3
Dn Slope=0.002
Boundary for River Rch & Prof#=CARTERS CREEK TR,Reach-1         , 6
Up Type= 0
Dn Type= 3
Dn Slope=0.002
Boundary for River Rch & Prof#=CARTERS CREEK TR,Reach-1         , 7
Up Type= 0
Dn Type= 3
Dn Slope=0.002
DSS Import GetInterval= 0
DSS Import GetPeak= 0
DSS Import FillOption= 0

--- CARTERS CREEK TRIBUTARY 1.g01 (geometry) ---

Geom Title=Existing Conditions
Program Version=4.10

River Reach=CARTERS CREEK TR,Reach-1
Reach XY= 30
       3589319.8     10212726.56      3589672.74      10212287.7
      3589408.68     10211681.45      3589678.47     10211578.32
      3589823.83     10210686.37      3590419.58      10210019.8
      3592162.65     10209272.95      3592581.68     10209441.92
      3593296.26      10209203.2      3594112.69      10209697.3
      3595686.11     10209222.56      3595344.51     10207961.57
      3595877.75     10206870.52      3595695.51     10206724.24
      3596386.63     10206034.14      3596774.36     10204729.31
      3597679.52     10204505.04      3598029.41     10203597.35
      3598487.21     10203664.67      3598613.97     10202437.43
      3598876.64      10202481.8      3599111.72     10201792.55
      3599727.48     10202061.07      3600091.12     10201688.83
      3600360.79     10202165.41      3600836.44     10202229.65
      3600742.22     10201691.57      3601749.63     10201087.23
      3602596.48     10201133.85       3602561.5     10201321.47

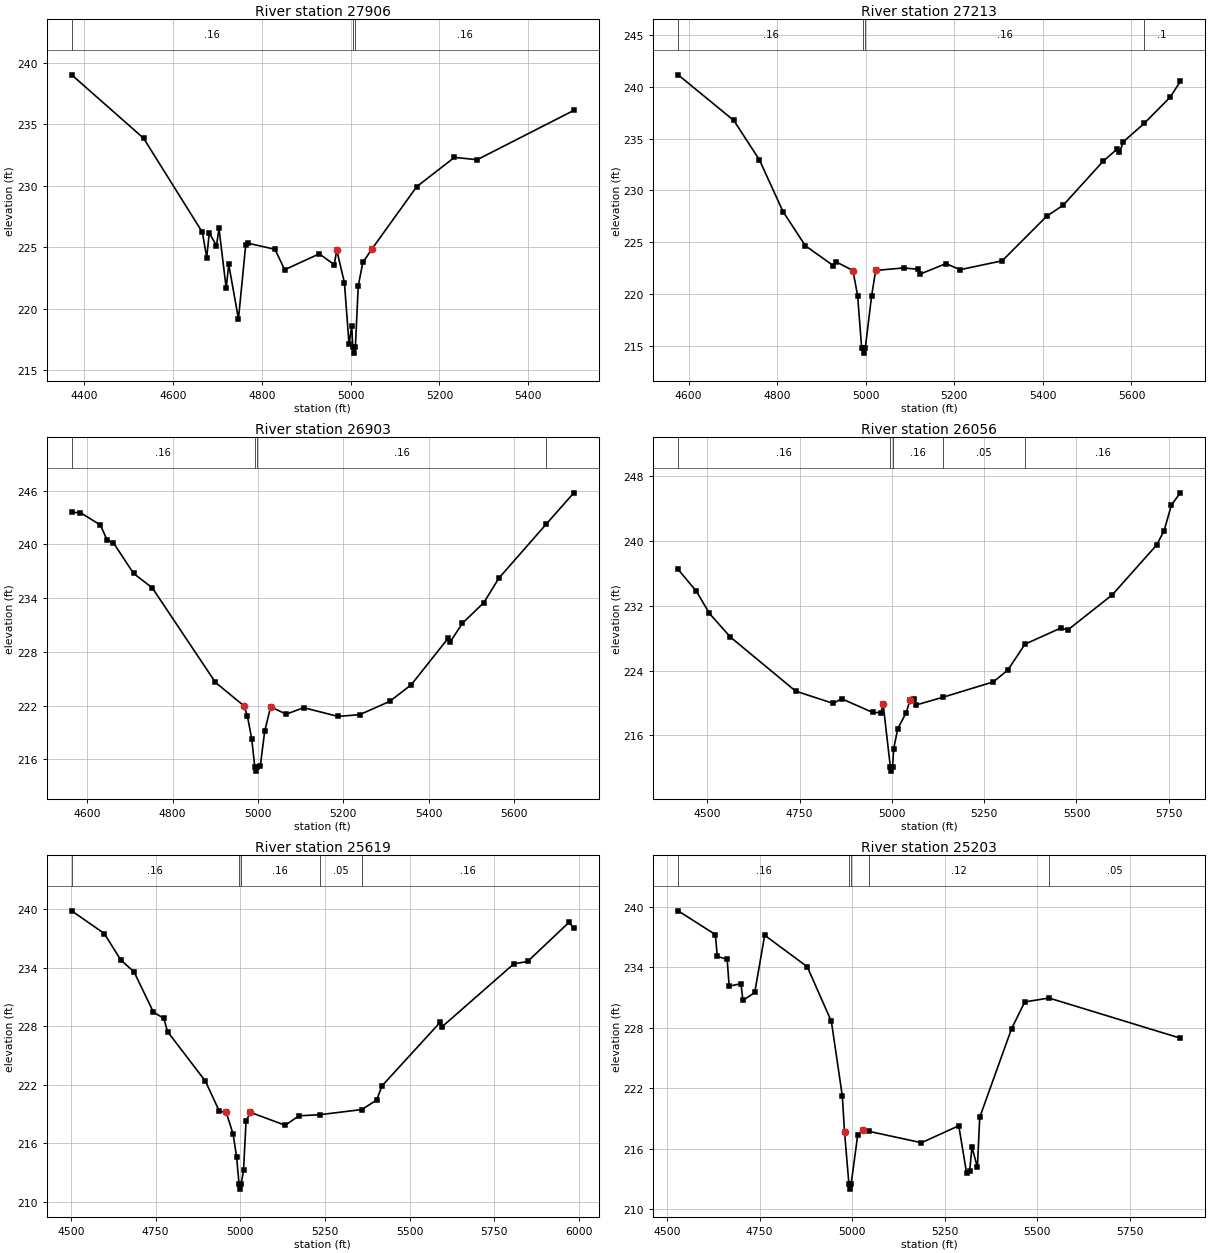
Type RM Length L Ch R = 1 ,27906   ,693,693,693
BEGIN DESCRIPTION:
CARTERS CREEK TRIBUTARY 1 37.0
END DESCRIPTION:
XS GIS Cut Line= 4
      3589892.15     10212891.66      3589432.74     10212646.96
      3589178.84     10212575.34      3588838.89      10212646.8
#Sta/Elev= 30
  4371.1     239  4533.1  233.85  4665.7   226.2  4675.5  224.15  4681.2  226.15
  4697.5  225.11  4703.1  226.51  4719.4  221.65  4725.1  223.59    4747  219.16
  4763.3  225.15    4769  225.31  4829.2  224.82  4851.2  223.16  4929.1  224.45
  4963.1  223.57  4968.3  224.78  4985.8  222.11  4996.2   217.1  5002.3  218.59
  5004.5  216.88  5007.3  216.38  5010.5  216.88    5017  221.85  5027.3  223.75
  5048.1  224.86  5148.7  229.91  5233.8  232.29  5284.9   232.1  5502.8  236.11
#Mann= 3 ,-1 , 0
  4371.1     .16       0  5004.5     .07       0  5010.5     .16       0
Bank Sta=4968.3,5048.1
XS Rating Curve= 0 ,0
Exp/Cntr=0.3,0.1

Type RM Length L Ch R = 1 ,27213   ,310,310,310
BEGIN DESCRIPTION:
CARTERS CREEK TRIBUTARY 1 36.0
END DESCRIPTION:
XS GIS Cut Line= 3
      3589993.67     10212558.57      3589824.38     10212467.42
       3588930.3     10212172.28
#Sta/Elev= 30
  4576.5  241.14  4702.3  236.74    4760  232.95  4813.3  227.96  4863.8  224.67
  4927.3  222.74  4932.6  223.13  4971.2  222.28  4981.8  219.84  4990.8  214.86
  4993.1  214.82  4995.8  214.32  4999.1  214.82  5013.4  219.84  5022.5  222.29
    5086  222.53  5117.8   222.4  5123.1  221.94  5181.3  222.95    5213  222.36
  5308.2  223.22  5408.8  227.52  5445.8  228.57  5535.8   232.8  5567.5  233.98
  5572.8  233.67    5582   234.7  5628.5  236.45  5687.3  238.98  5710.3   240.5
#Mann= 4 ,-1 , 0
  4576.5     .16       0  4993.1     .07       0  4999.1     .16       0
  5628.5      .1       0
Bank Sta=4971.2,5022.5
XS Rating Curve= 0 ,0
Exp/Cntr=0.3,0.1

Type RM Length L Ch R = 1 ,26903   ,847,847,847
BEGIN DESCRIPTION:
CARTERS CREEK TRIBUTARY 1 35.0
END DESCRIPTION:
XS GIS Cut Line= 3
      3590058.79     10212189.64      3589403.37     10212085.47
       3588892.1     10212041.64
#Sta/Elev= 30
  4563.6  243.58  4584.1  243.56  4631.1  242.17  4646.4  240.52  4661.5  240.19
  4708.6  236.77  4752.6  235.15  4900.4   224.6  4967.6  221.96  4975.4  220.83
  4985.5  218.32  4992.6  215.18  4995.4  214.68  4998.6  215.18  5005.8  215.28
  5015.9  219.12  5029.9  221.86  5066.5  221.04    5107  221.77    5188  220.79
  5238.6  220.99  5308.8  222.47    5359  224.31    5446  229.53    5451  229.14
  5479.4   231.2  5529.6  233.51  5564.8  236.24    5676  242.29  5740.4  245.77
#Mann= 4 ,-1 , 0
  4563.6     .16       0  4992.6     .07       0  4998.6     .16       0
    5676      .1       0
Bank Sta=4967.6,5029.9
XS Rating Curve= 0 ,0
Exp/Cntr=0.3,0.1

Type RM Length L Ch R = 1 ,26056   ,437,437,437
BEGIN DESCRIPTION:
CARTERS CREEK TRIBUTARY 1 34.0
END DESCRIPTION:
XS GIS Cut Line= 4
      3589942.12     10211991.65      3589697.69     10211734.02
      3589207.16      10211494.9        3588748.     10211495.19
#Sta/Elev= 30
  4421.2   236.5  4470.8   233.8    4506  231.07  4562.6  228.16  4739.4  221.48
  4841.3  219.96  4863.8  220.54  4948.4  218.84  4970.9  218.83  4976.5  219.85
    4996   212.1  4998.8   211.6    5002   212.1    5005  214.36    5016  216.84
  5038.4  218.78  5049.7  220.41  5060.7  220.49  5066.6  219.78  5137.5  220.71
    5275  222.62  5314.5   224.1  5360.4  227.27  5457.1  229.26  5477.1  229.05
  5597.1  233.37  5717.1  239.52  5737.1  241.26  5757.1  244.45  5781.2  245.96
#Mann= 5 ,-1 , 0
  4421.2     .16       0    4996     .07       0    5002     .16       0
  5137.5     .05       0  5360.4     .16       0
Bank Sta=4976.5,5049.7
XS Rating Curve= 0 ,0
Exp/Cntr=0.3,0.1

Type RM Length L Ch R = 1 ,25619   ,416,416,416
BEGIN DESCRIPTION:
CARTERS CREEK TRIBUTARY 1 33.0
END DESCRIPTION:
XS GIS Cut Line= 3
      3590154.27     10211529.92      3589984.97     10211477.83
      3588708.97      10211204.4
#Sta/Elev= 30
  4502.3  239.84  4598.7  237.51  4647.6  234.78  4686.3  233.59  4743.7  229.45
  4774.4  228.81  4785.2  227.46  4897.1  222.37    4938   219.3  4958.5  219.17
  4978.9  216.93  4989.2  214.56  4996.4   211.8  4999.1   211.3  5002.4   211.8
  5009.6  213.24    5017  218.28  5030.1  219.17  5132.4  217.85  5173.3  218.82
  5233.9  218.93  5358.4  219.46  5402.2  220.42  5418.7  221.91  5589.7   228.4
  5594.8  227.93  5807.3   234.4  5848.2  234.65  5969.8  238.65  5984.4  238.09
#Mann= 5 ,-1 , 0
  4502.3     .16       0  4996.4     .07       0  5002.4     .16       0
  5233.9     .05       0  5358.4     .16       0
Bank Sta=4958.5,5030.1
XS Rating Curve= 0 ,0
Exp/Cntr=0.3,0.1

Type RM Length L Ch R = 1 ,25203   ,714,714,714
BEGIN DESCRIPTION:
CARTERS CREEK TRIBUTARY 1 32.0
END DESCRIPTION:
XS GIS Cut Line= 3
      3590258.37     10211239.11      3589950.25     10211139.29
      3589108.23     10210540.33
#Sta/Elev= 30
  4529.6  239.58  4630.2  237.23  4635.5  235.07  4662.2  234.76  4667.5  232.12
  4699.5  232.35  4704.7   230.7  4736.7  231.49  4763.5  237.16  4878.6  234.04
  4943.8  228.62  4973.3  221.24  4979.4  217.65  4991.2   212.5    4994     212
  4997.2   212.5  5015.1  217.41  5029.9  217.84    5045  217.73  5187.3   216.6
  5288.1  218.28    5309  213.64  5317.5  213.82  5323.8  216.15  5338.5  214.16
  5344.7  219.11  5430.7  227.89  5466.4  230.55  5531.9  230.94  5886.8  226.96
#Mann= 5 ,-1 , 0
  4529.6     .16       0  4991.2     .07       0  4997.2     .16       0
    5045     .12       0  5531.9     .05       0
Bank Sta=4979.4,5029.9
XS Rating Curve= 0 ,0
Exp/Cntr=0.3,0.1

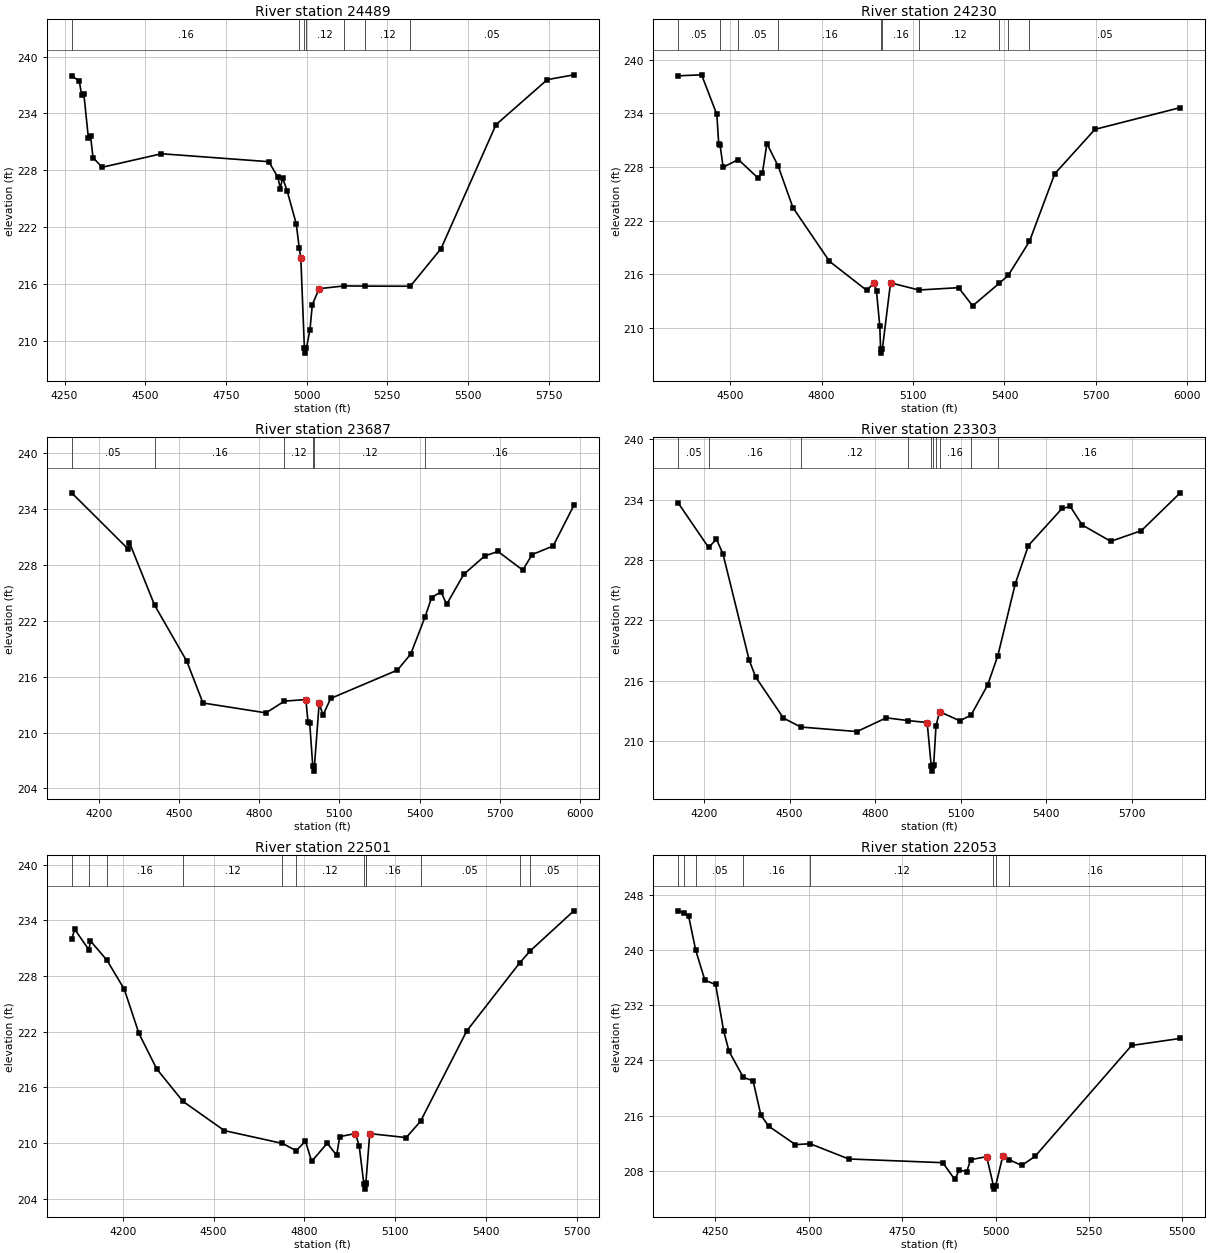
Type RM Length L Ch R = 1 ,24489   ,259,259,259
BEGIN DESCRIPTION:
CARTERS CREEK TRIBUTARY 1 31.0
END DESCRIPTION:
XS GIS Cut Line= 4
      3590562.25      10211234.8      3590215.01     10210848.49
      3589963.27      10210579.4      3589335.51     10210349.94
#Sta/Elev= 30
    4272  237.94  4295.5  237.46    4303  235.93  4309.7  236.09  4323.9   231.4
  4330.7  231.58  4338.1  229.34  4366.5  228.31  4550.4  229.74    4883   228.9
  4911.3  227.24  4918.7  226.05  4925.5   227.2  4939.7  225.83    4968  222.34
  4977.3  219.79  4982.2  218.73  4993.3  209.17  4996.1  208.67  4999.3  209.17
  5010.5  211.12  5017.8  213.79  5038.8  215.48    5116  215.77  5182.6  215.75
  5321.6  215.74  5416.7  219.71    5587  232.81    5746  237.57  5828.3  238.08
#Mann= 7 ,-1 , 0
    4272     .16       0  4977.3     .12       0  4993.3     .07       0
  4999.3     .12       0    5116     .16       0  5182.6     .12       0
  5321.6     .05       0
Bank Sta=4982.2,5038.8
XS Rating Curve= 0 ,0
Exp/Cntr=0.3,0.1

Type RM Length L Ch R = 1 ,24230   ,543,543,543
BEGIN DESCRIPTION:
CARTERS CREEK TRIBUTARY 1 30.0
END DESCRIPTION:
XS GIS Cut Line= 3
      3590714.14     10210987.38      3590410.32     10210588.08
      3589347.07     10210162.78
#Sta/Elev= 30
  4329.7  238.18  4406.7  238.29  4456.6  233.87  4462.9  230.57  4467.3  230.44
  4477.4  227.97  4527.3  228.83  4591.8  226.76  4606.3  227.37  4620.9  230.62
  4658.2  228.06  4706.1  223.47  4826.1  217.46  4948.2  214.22  4972.4  215.05
  4980.3  214.12  4991.1  210.21  4993.7  207.71  4996.4  207.21  4999.7  207.71
  5026.3  215.06  5119.1  214.26  5249.6  214.52  5295.5  212.49  5383.2  215.02
  5412.5   215.9    5482   219.7  5564.8  227.24  5696.7   232.2  5976.6  234.63
#Mann= 10 ,-1 , 0
  4329.7     .05       0  4467.3     .16       0  4527.3     .05       0
  4658.2     .16       0  4993.7     .07       0  4999.7     .16       0
  5119.1     .12       0  5383.2     .05       0  5412.5     .16       0
    5482     .05       0
Bank Sta=4972.4,5026.3
XS Rating Curve= 0 ,0
Exp/Cntr=0.3,0.1

Type RM Length L Ch R = 1 ,23687   ,384,384,384
BEGIN DESCRIPTION:
CARTERS CREEK TRIBUTARY 1 29.0
END DESCRIPTION:
XS GIS Cut Line= 3
      3590796.59     10210900.55      3590458.04     10210256.49
       3589556.2     10209538.46
#Sta/Elev= 30
  4097.5  235.72  4308.3  229.71  4313.9  230.38    4408  223.67  4528.7  217.65
  4589.2  213.17    4825  212.11  4894.4  213.37  4974.5  213.54  4982.6  211.09
    4989  210.99  5000.4  206.36  5003.1  205.86  5006.4  206.36  5024.4  213.15
  5038.6  211.86  5067.4  213.66  5317.3   216.7    5367  218.41  5420.3  222.37
  5445.4  224.48  5480.7  225.11  5501.5  223.75  5565.5  226.97    5644  228.94
  5693.7  229.43  5786.6  227.43  5821.8   229.1  5900.3  230.01  5977.9  234.37
#Mann= 6 ,-1 , 0
  4097.5     .05       0    4408     .16       0  4894.4     .12       0
  5000.4     .07       0  5006.4     .12       0  5420.3     .16       0
Bank Sta=4974.5,5024.4
XS Rating Curve= 0 ,0
Exp/Cntr=0.3,0.1

Type RM Length L Ch R = 1 ,23303   ,802,802,802
BEGIN DESCRIPTION:
CARTERS CREEK TRIBUTARY 1 28.0
END DESCRIPTION:
XS GIS Cut Line= 3
      3590992.12     10210741.68      3590449.38     10209568.11
      3590162.91     10209199.17
#Sta/Elev= 30
  4109.6  233.69  4216.4  229.25    4244  230.07  4266.9   228.6  4358.7  218.03
  4381.6  216.34  4478.8  212.26  4539.7  211.37  4736.6  210.92  4839.3  212.29
  4915.7  212.01  4982.4  211.82  4996.8  207.48  4999.5  206.98  5002.8  207.48
  5005.3  207.58  5013.4  211.48    5026   212.9    5097  211.99  5136.3  212.56
  5194.2  215.54  5230.2  218.48  5291.5  225.66  5337.3  229.44  5455.2  233.13
  5484.1  233.33  5525.8  231.49    5626  229.86    5733  230.92  5869.7  234.69
#Mann= 10 ,-1 , 0
  4109.6     .05       0  4216.4     .16       0  4539.7     .12       0
  4915.7     .16       0  4996.8     .07       0  5002.8     .16       0
  5013.4     .12       0    5026     .16       0  5136.3     .05       0
  5230.2     .16       0
Bank Sta=4982.4,5026
XS Rating Curve= 0 ,0
Exp/Cntr=0.3,0.1

Type RM Length L Ch R = 1 ,22501   ,448,448,448
BEGIN DESCRIPTION:
CARTERS CREEK TRIBUTARY 1 27.0
END DESCRIPTION:
XS GIS Cut Line= 4
      3591317.44      10210761.7      3591174.21     10209971.76
      3591070.04     10209581.13      3590719.71     10209295.68
#Sta/Elev= 30
  4030.8  232.01    4041  233.04  4087.9  230.83  4092.8   231.8  4147.7   229.7
  4204.8  226.57  4253.1  221.81  4311.6     218  4398.3  214.49  4535.5  211.33
  4727.1  209.95  4772.6  209.17  4803.3  210.19  4823.6  208.01  4875.1  209.97
  4906.2  208.67  4916.5  210.68  4968.3  211.02  4980.7  209.68  4996.3  205.52
  4999.1  205.02  5002.3  205.52  5002.7  205.68  5015.6  211.01    5136  210.58
  5183.3  212.34    5336  222.08  5510.5  229.41    5546  230.73  5689.8  235.04
#Mann= 12 ,-1 , 0
  4030.8     .16       0  4087.9      .1       0  4147.7     .16       0
  4398.3     .12       0  4727.1     .16       0  4772.6     .12       0
  4996.3     .07       0  5002.3     .12       0  5002.7     .16       0
  5183.3     .05       0  5510.5     .16       0    5546     .05       0
Bank Sta=4968.3,5015.6
XS Rating Curve= 0 ,0
Exp/Cntr=0.3,0.1

Type RM Length L Ch R = 1 ,22053   ,661,661,661
BEGIN DESCRIPTION:
CARTERS CREEK TRIBUTARY 1 26.0
END DESCRIPTION:
XS GIS Cut Line= 3
       3591892.1     10210291.64      3591573.51     10209871.93
      3591291.92     10209105.13
#Sta/Elev= 30
  4150.5  245.66  4167.1  245.32  4178.6   244.9  4197.7  239.92  4222.2   235.6
  4250.9  234.99  4272.2  228.31  4286.7  225.31  4324.8  221.56  4351.2  221.01
    4372  216.07  4392.8  214.47  4464.4   211.8  4503.9  211.92    4607  209.72
  4858.8  209.18  4890.8  206.75  4902.9  208.09  4922.8   207.9  4933.4  209.61
    4976  210.06  4994.3  205.85  4997.1  205.35  5000.3  205.85  5019.5  210.19
  5037.1   209.6  5069.8  208.78  5105.7   210.1    5364  226.16  5494.3  227.18
#Mann= 8 ,-1 , 0
  4150.5     .05       0  4167.1      .1       0  4197.7     .05       0
  4324.8     .16       0  4503.9     .12       0  4994.3     .07       0
  5000.3     .12       0  5037.1     .16       0
Bank Sta=4976,5019.5
XS Rating Curve= 0 ,0
Exp/Cntr=0.3,0.1

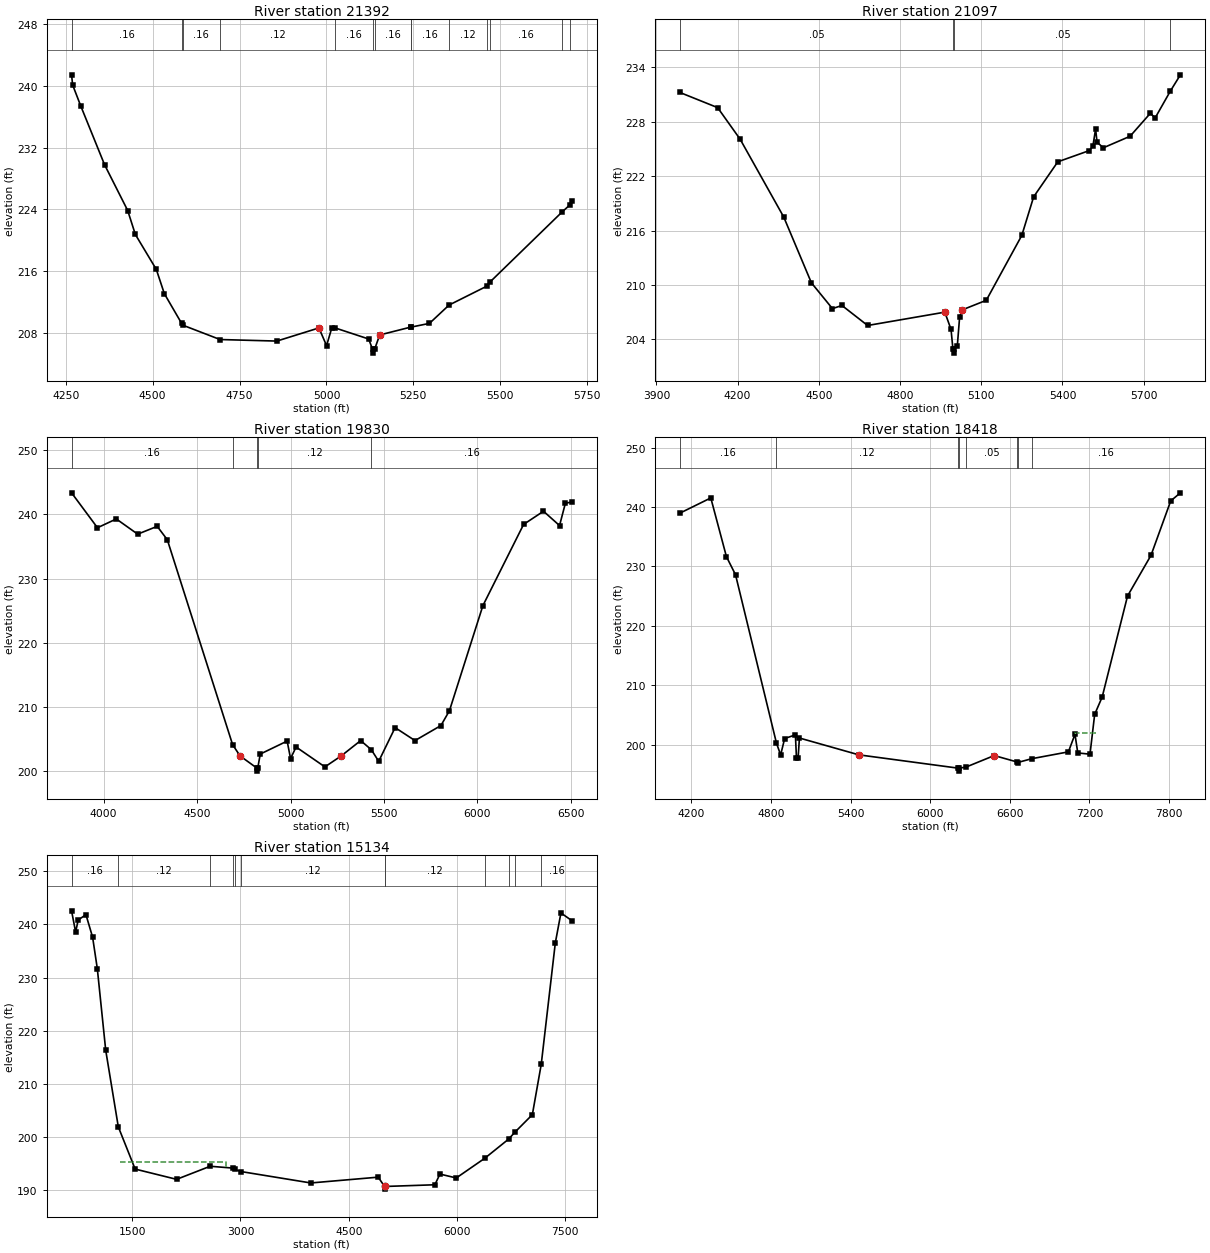
Type RM Length L Ch R = 1 ,21392   ,295,295,295
BEGIN DESCRIPTION:
CARTERS CREEK TRIBUTARY 1 25.0
END DESCRIPTION:
XS GIS Cut Line= 3
      3592228.89     10210158.37      3591842.11     10209316.37
      3591639.32     10208844.92
#Sta/Elev= 30
  4266.6  241.43  4269.7  240.12  4292.7  237.44  4361.6  229.79  4428.1  223.87
  4450.1  220.77  4510.5  216.24  4533.5  213.11    4583  209.28  4585.9  209.04
  4693.9  207.17  4857.2  206.97  4978.3  208.67  5000.3  206.38  5015.2  208.65
  5024.3  208.68  5121.4  207.24  5132.6  205.91  5135.3  205.41  5138.6  205.91
  5153.1  207.76  5241.8  208.77  5243.9  208.78  5296.3  209.26  5352.7  211.63
  5461.5  214.08  5470.7  214.62  5679.1  223.73  5699.6  224.56  5706.4  225.06
#Mann= 14 ,-1 , 0
  4266.6     .16       0    4583     .05       0  4585.9     .16       0
  4693.9     .12       0  5024.3     .16       0  5132.6     .07       0
  5138.6     .16       0  5241.8     .12       0  5243.9     .16       0
  5352.7     .12       0  5461.5     .05       0  5470.7     .16       0
  5679.1     .05       0  5699.6     .16       0
Bank Sta=4978.3,5153.1
XS Rating Curve= 0 ,0
Exp/Cntr=0.3,0.1

Type RM Length L Ch R = 1 ,21097   ,1267,1267,1267
BEGIN DESCRIPTION:
CARTERS CREEK TRIBUTARY 1 23.0
END DESCRIPTION:
XS GIS Cut Line= 3
       3592489.3     10210245.17      3592228.34     10209598.07
      3591762.01     10208546.13
#Sta/Elev= 30
  3987.2  231.24  4126.3  229.57  4209.5  226.08  4370.6  217.49  4472.6  210.24
  4550.4  207.39  4585.4  207.74  4680.3  205.53  4965.4     207  4988.4   205.1
  4995.2  202.98    4998  202.48  5001.2  202.98  5011.7  203.31  5020.1  206.45
  5029.5  207.25  5118.6  208.31  5249.8  215.47  5293.6  219.73  5382.7  223.59
  5499.1  224.83  5512.4  225.32  5522.4  227.21  5527.8  225.75  5551.1  225.14
  5649.7  226.41    5725  228.96  5742.1  228.42  5798.4  231.39  5835.6  233.19
#Mann= 4 ,-1 , 0
  3987.2     .05       0  4995.2    .035       0  5001.2     .05       0
  5798.4     .16       0
Bank Sta=4965.4,5029.5
XS Rating Curve= 0 ,0
Exp/Cntr=0.3,0.1

Type RM Length L Ch R = 1 ,19830   ,1412,1412,1412
BEGIN DESCRIPTION:
CARTERS CREEK TRIBUTARY 1 22.0
END DESCRIPTION:
XS GIS Cut Line= 4
      3593687.22      10210279.9      3593447.21     10209942.52
      3593020.44     10208903.63      3592705.76     10207807.68
#Sta/Elev= 30
  3828.2  243.36  3966.8  237.92  4067.6  239.29    4182  236.92  4286.4  238.14
  4340.5  236.05  4689.8  204.13  4729.7  202.37  4818.5   200.5  4821.3     200
  4824.5   200.5  4837.8  202.66  4981.6  204.68    5000  201.96  5029.5  203.76
  5183.7  200.66  5272.3   202.4    5375  204.76    5432  203.34  5471.5  201.53
  5559.3  206.78  5665.6  204.76  5804.4   207.1  5849.9  209.41  6028.9  225.78
  6246.8  238.44  6353.2  240.49  6439.1  238.26  6470.3  241.74  6505.6  241.93
#Mann= 5 ,-1 , 0
  3828.2     .16       0  4689.8     .12       0  4818.5     .07       0
  4824.5     .12       0    5432     .16       0
Bank Sta=4729.7,5272.3
XS Rating Curve= 0 ,0
Exp/Cntr=0.3,0.1

Type RM Length L Ch R = 1 ,18418   ,3284,3284,3284
BEGIN DESCRIPTION:
CARTERS CREEK TRIBUTARY 1 20.0
END DESCRIPTION:
XS GIS Cut Line= 3
      3594420.17     10210531.21      3594117.42      10208549.6
      3592886.54     10207284.06
#Sta/Elev= 30
  4115.2  238.98  4347.4  241.53  4465.2  231.65  4533.7  228.61  4842.2  200.28
  4873.5  198.31  4903.8  201.06  4984.7  201.68    4993  197.72    5005  197.76
  5015.1  201.15  5462.5  198.32  6211.1  196.08  6213.9  195.58  6217.1  196.08
  6268.7  196.25  6482.7   198.2  6654.7  197.12  6659.3  197.03  6765.2  197.67
  7041.4  198.82    7091  201.78  7112.1  198.64  7204.2  198.43  7239.4  205.13
    7296  208.05  7486.9  225.03  7663.8  231.88  7812.3  241.03  7885.2  242.39
#Mann= 8 ,-1 , 0
  4115.2     .16       0  4842.2     .12       0  6211.1     .07       0
  6217.1     .12       0  6268.7     .05       0  6654.7     .16       0
  6659.3     .05       0  6765.2     .16       0
#XS Ineff= 1 ,-1
 7090.91 7261.36  202.02
Permanent Ineff=
       F
Bank Sta=5462.5,6482.7
XS Rating Curve= 0 ,0
Exp/Cntr=0.3,0.1

Type RM Length L Ch R = 1 ,15134   ,0,0,0
BEGIN DESCRIPTION:
CARTERS CREEK TRIBUTARY 1 1.0
END DESCRIPTION:
XS GIS Cut Line= 4
      3594504.21     10210821.16      3596379.24     10209506.03
      3596123.38     10208553.17       3593541.8     10205965.48
#Sta/Elev= 30
   660.3  242.55   716.5  238.56   752.3  240.83   859.5  241.83   951.9  237.59
  1017.3  231.65  1133.2  216.35  1307.8  201.93  1541.1  193.99  2115.5  192.06
  2580.4  194.52  2900.1  194.17  2922.5  193.92  3004.9  193.53  3974.5  191.38
  4907.9  192.47  4996.8  190.72  4999.6  190.22  5002.8  190.72  5692.8  191.04
  5763.5  193.05  5989.8  192.32  6385.3  196.03  6715.2  199.63  6798.4  200.88
  7043.4  204.22  7166.7   213.7  7361.6  236.52  7439.3  242.15  7592.4  240.69
#Mann= 12 ,-1 , 0
   660.3     .16       0  1307.8     .12       0  2580.4      .1       0
  2900.1     .12       0  2922.5     .16       0  3004.9     .12       0
  4996.8     .07       0  5002.8     .12       0  6385.3     .05       0
  6715.2     .16       0  6798.4     .05       0  7166.7     .16       0
#XS Ineff= 1 ,-1
 1336.36    2800  195.33
Permanent Ineff=
       F
Bank Sta=4996.8,5002.8
XS Rating Curve= 0 ,0
Exp/Cntr=0.3,0.1

Chan Stop Cuts=-1
Use User Specified Reach Order=0
Composite Channel Slope=5