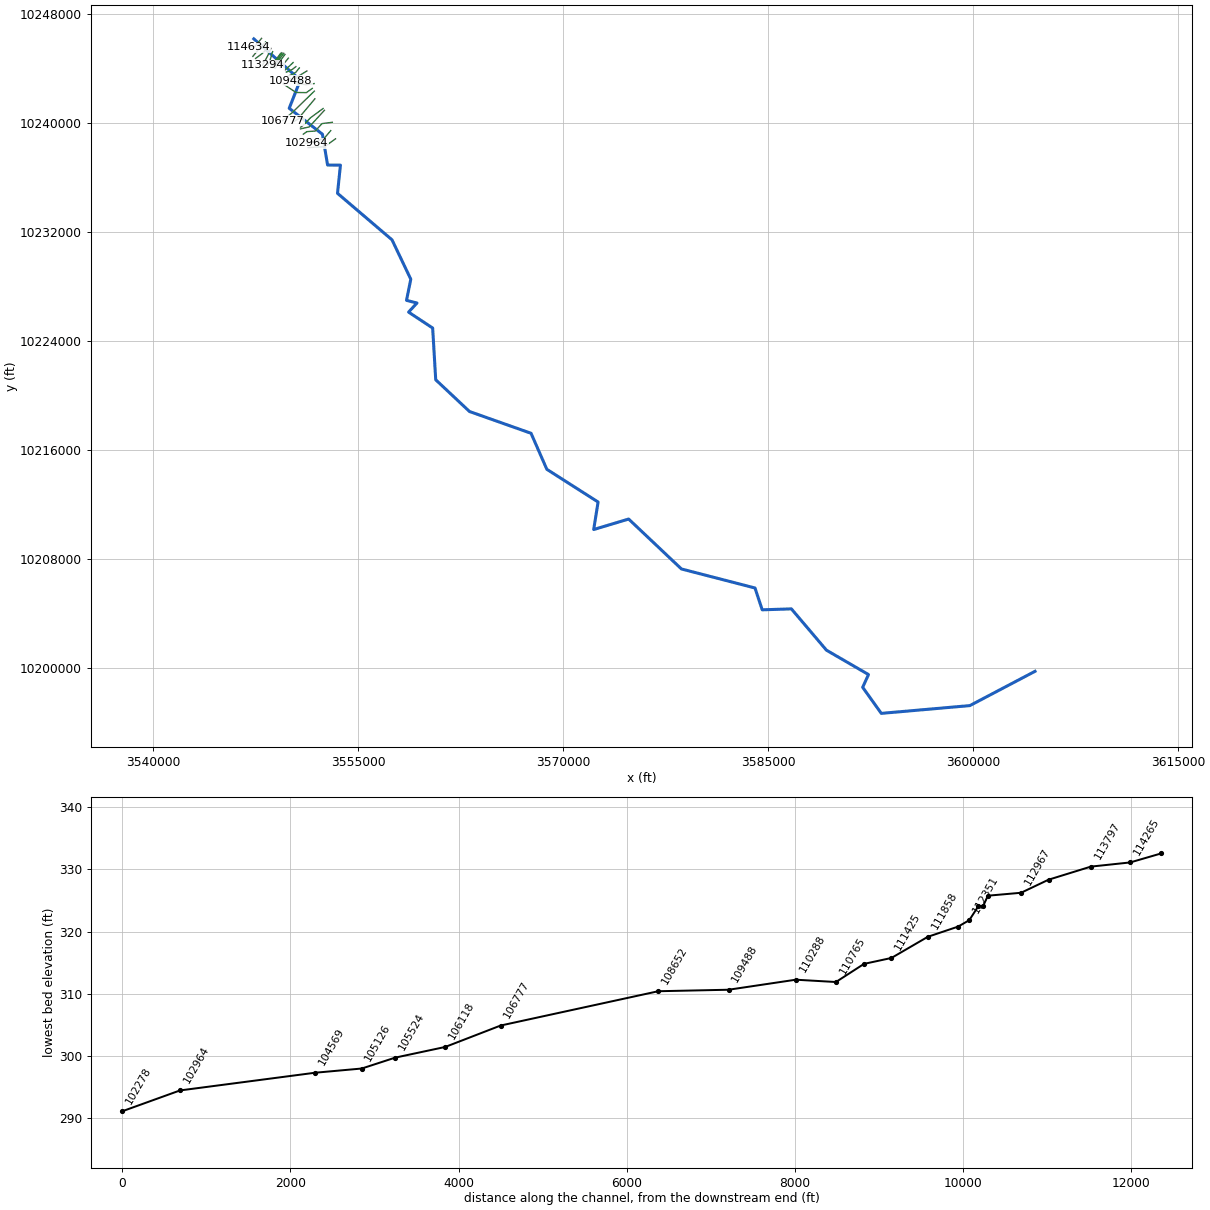
--- CARTERS CREEK.prj (project) ---

Proj Title=CARTERS CREEK Base Level Engineering
Current Plan=p01
Default Exp/Contr=0.3,0.1
English Units
Geom File=g01
Flow File=f01
Plan File=p01
Y Axis Title=Elevation
X Axis Title(PF)=Main Channel Distance
X Axis Title(XS)=Station
BEGIN DESCRIPTION:
CARTERS CREEK
END DESCRIPTION:
DSS Export Rating Curves= 0
DSS Export Rating Curve Sorted= 0
DSS Export Volume Flow Curves= 0
DXF OffsetX= 0
DXF OffsetY= 0
DXF ScaleX= 1
DXF ScaleY= 10

--- CARTERS CREEK.p01 (plan) ---

Plan Title=Multiple Run
Short Identifier=Multiple
Geom File=g01
Flow File=f01
Subcritical Flow
K Sum by GR= 0
Std Step Tol= 0.01
Critical Tol= 0.01
Num of Std Step Trials= 20
Max Error Tol= 0.3
Flow Tol Ratio= 0.001
Split Flow NTrial= 30
Split Flow Tol= 0.02
Split Flow Ratio= 0.02
Log Output Level= 0
Friction Slope Method= 1
Unsteady Friction Slope Method= 2
Unsteady Bridges Friction Slope Method= 1
Parabolic Critical Depth
Global Vel Dist=  1 , 1 , 1
Global Log Level= 0
CheckData=True
Encroach Param= -1, 0, 0, 0
BEGIN DESCRIPTION:
Multiple Run
END DESCRIPTION:

--- CARTERS CREEK.f01 (steady flow) ---

Flow Title=Multiple
Program Version=4.10
Number of Profiles= 7
Profile Names=10-year,25-year,50-year,1pct_min,100-year,1pct_plu,500-year
River Rch & RM=CARTERS CREEK,Reach-1         ,114634
     341     443     523     454     614     830     844
River Rch & RM=CARTERS CREEK,Reach-1         ,112219
     387     507     602     524     708     958     982
River Rch & RM=CARTERS CREEK,Reach-1         ,109488
     596     800     965     852    1153    1559    1649
River Rch & RM=CARTERS CREEK,Reach-1         ,108652
     596     800     965     852    1153    1559    1649
River Rch & RM=CARTERS CREEK,Reach-1         ,106777
    1094    1512    1858    1668    2256    3051    3337
River Rch & RM=CARTERS CREEK,Reach-1         ,98481
    1313    1824    2250    2026    2740    3705    4077
River Rch & RM=CARTERS CREEK,Reach-1         ,93119
    2241    3177    3973    3621    4897    6623    7466
River Rch & RM=CARTERS CREEK,Reach-1         ,91351
    2241    3177    3973    3621    4897    6623    7466
River Rch & RM=CARTERS CREEK,Reach-1         ,90412
    2231    3155    3938    3582    4844    6551    7356
River Rch & RM=CARTERS CREEK,Reach-1         ,86047
    2231    3155    3938    3582    4844    6551    7356
River Rch & RM=CARTERS CREEK,Reach-1         ,81317
    2790    3977    4992    4563    6171    8346    9464
River Rch & RM=CARTERS CREEK,Reach-1         ,79519
    2790    3977    4992    4563    6171    8346    9464
River Rch & RM=CARTERS CREEK,Reach-1         ,71382
    3767    5419    6846    6294    8512   11512   13203
River Rch & RM=CARTERS CREEK,Reach-1         ,69930
    4052    5830    7365    6770    9156   12382   14193
River Rch & RM=CARTERS CREEK,Reach-1         ,65235
    4281    6169    7803    7181    9711   13133   15085
River Rch & RM=CARTERS CREEK,Reach-1         ,63285
    4281    6169    7803    7181    9711   13133   15085
River Rch & RM=CARTERS CREEK,Reach-1         ,57762
    4478    6427    8106    7435   10056   13599   15519
River Rch & RM=CARTERS CREEK,Reach-1         ,56352
    4478    6427    8106    7435   10056   13599   15519
River Rch & RM=CARTERS CREEK,Reach-1         ,47068
    5437    7852    9946    9160   12388   16754   19270
River Rch & RM=CARTERS CREEK,Reach-1         ,45126
    5686    8206   10392    9566   12937   17495   20101
River Rch & RM=CARTERS CREEK,Reach-1         ,41414
    5686    8206   10392    9566   12937   17495   20101
River Rch & RM=CARTERS CREEK,Reach-1         ,32860
    5778    8341   10563    9723   13150   17784   20433
River Rch & RM=CARTERS CREEK,Reach-1         ,30803
    6081    8777   11117   10233   13839   18716   21501
River Rch & RM=CARTERS CREEK,Reach-1         ,26682
    6175    8907   11275   10373   14028   18971   21768
River Rch & RM=CARTERS CREEK,Reach-1         ,15728
    6128    8823   11155   10249   13860   18744   21450
River Rch & RM=CARTERS CREEK,Reach-1         ,8640
    6144    8827   11144   10223   13826   18698   21330
Boundary for River Rch & Prof#=CARTERS CREEK,Reach-1         , 1
Up Type= 0
Dn Type= 3
Dn Slope=0.0005
Boundary for River Rch & Prof#=CARTERS CREEK,Reach-1         , 2
Up Type= 0
Dn Type= 3
Dn Slope=0.0005
Boundary for River Rch & Prof#=CARTERS CREEK,Reach-1         , 3
Up Type= 0
Dn Type= 3
Dn Slope=0.0005
Boundary for River Rch & Prof#=CARTERS CREEK,Reach-1         , 4
Up Type= 0
Dn Type= 3
Dn Slope=0.0005
Boundary for River Rch & Prof#=CARTERS CREEK,Reach-1         , 5
Up Type= 0
Dn Type= 3
Dn Slope=0.0005
Boundary for River Rch & Prof#=CARTERS CREEK,Reach-1         , 6
Up Type= 0
Dn Type= 3
Dn Slope=0.0005
Boundary for River Rch & Prof#=CARTERS CREEK,Reach-1         , 7
Up Type= 0
Dn Type= 3
Dn Slope=0.0005
DSS Import GetInterval= 0
DSS Import GetPeak= 0
DSS Import FillOption= 0

--- CARTERS CREEK.g01 (geometry) ---

Geom Title=Existing Conditions
Program Version=4.10

River Reach=CARTERS CREEK   ,Reach-1
Reach XY= 30
      3547364.18      10246177.5      3550766.22     10243154.85
      3549954.89     10241082.93      3552382.72     10239181.29
      3552761.61     10236916.36      3553701.46     10236909.37
      3553488.44     10234839.58      3557475.36     10231426.07
      3558850.54     10228533.79      3558535.88     10226983.17
      3559300.32      10226785.8      3558687.25     10226119.26
      3560449.69     10224950.15      3560673.91     10221152.39
      3563147.12     10218821.67      3567650.03     10217223.49
        3568803.     10214580.78      3572554.65     10212177.99
      3572231.68     10210157.95      3574790.75     10210928.35
       3578653.1     10207264.06      3584035.05     10205866.68
      3584563.32     10204264.68      3586698.71     10204333.69
      3589262.41     10201302.37      3592341.88     10199511.78
      3591913.65     10198576.99      3593277.48      10196662.6
       3599756.5     10197233.47      3604525.59     10199750.35

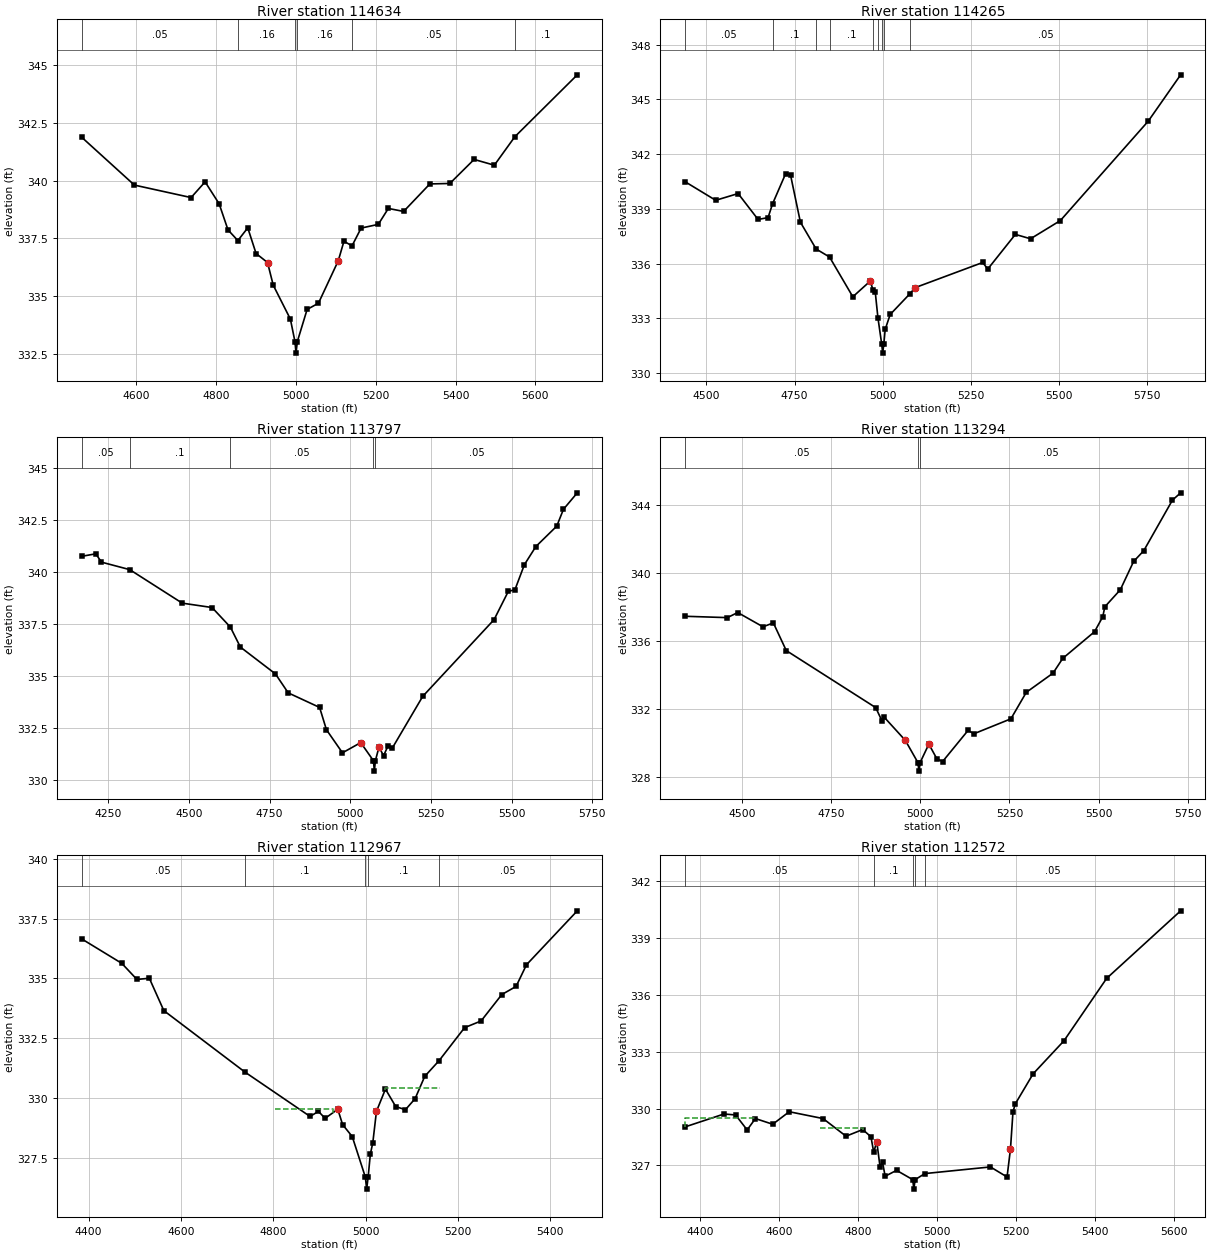
Type RM Length L Ch R = 1 ,114634  ,369,369,369
BEGIN DESCRIPTION:
CARTERS CREEK 76.0
END DESCRIPTION:
XS GIS Cut Line= 3
      3547932.06     10246217.36       3547441.6     10245622.73
      3546977.23     10245544.61
#Sta/Elev= 30
  4463.3  341.88  4595.3  339.81  4737.4  339.27  4772.5  339.95  4807.7     339
  4829.9  337.87  4854.6  337.41  4879.4  337.96  4900.2  336.85  4928.9  336.46
  4943.2  335.48  4986.2  334.01  4997.6  333.04  5000.3  332.54  5003.6  333.04
  5028.1  334.43  5056.5   334.7    5106  336.53  5120.4  337.38  5140.6  337.18
  5163.4  337.95  5206.4  338.11  5231.6   338.8  5269.9  338.67  5335.6  339.86
  5385.7  339.88  5446.5  340.92  5497.2  340.67  5548.5   341.9    5705  344.58
#Mann= 6 ,-1 , 0
  4463.3     .05       0  4854.6     .16       0  4997.6     .07       0
  5003.6     .16       0  5140.6     .05       0  5548.5      .1       0
Bank Sta=4928.9,5106
XS Rating Curve= 0 ,0
Exp/Cntr=0.3,0.1

Type RM Length L Ch R = 1 ,114265  ,468,468,468
BEGIN DESCRIPTION:
CARTERS CREEK 75.0
END DESCRIPTION:
XS GIS Cut Line= 3
       3548218.5     10245948.23      3547762.78     10245470.82
      3547292.11     10244891.65
#Sta/Elev= 30
  4439.4  340.49  4526.4  339.47    4590  339.84  4646.6  338.42  4674.9  338.52
  4687.8  339.28  4724.6  340.92  4738.7  340.86  4766.7  338.27  4811.3   336.8
  4849.4  336.36  4915.5  334.18  4964.9  335.04    4973  334.54    4979  334.46
  4986.7  333.03  4997.4  331.59  5000.2  331.09  5003.4  331.59  5007.3  332.39
  5021.5  333.21  5077.7  334.35  5092.2  334.68    5284  336.06  5298.4   335.7
  5376.7   337.6  5419.8  337.36  5504.5  338.36  5753.8  343.81  5845.7  346.35
#Mann= 9 ,-1 , 0
  4439.4     .05       0  4687.8      .1       0  4811.3     .05       0
  4849.4      .1       0    4973     .05       0  4986.7      .1       0
  4997.4     .07       0  5003.4      .1       0  5077.7     .05       0
Bank Sta=4964.9,5092.2
XS Rating Curve= 0 ,0
Exp/Cntr=0.3,0.1

Type RM Length L Ch R = 1 ,113797  ,503,503,503
BEGIN DESCRIPTION:
CARTERS CREEK 74.0
END DESCRIPTION:
XS GIS Cut Line= 4
      3548442.11     10245891.65       3548185.2     10245304.43
       3547959.4     10245088.01       3547492.1     10244741.64
#Sta/Elev= 30
    4168  340.74  4211.7  340.86  4229.2  340.46  4316.9   340.1  4479.5  338.49
  4571.9  338.28  4628.6  337.34  4659.6  336.38  4768.3  335.09  4807.8  334.18
  4905.1  333.48  4926.2  332.41  4975.9   331.3  5032.5  331.79  5071.9  330.92
  5074.7  330.42  5077.9  330.92  5089.1  331.58  5103.2  331.16  5116.4  331.61
  5130.8  331.54  5224.5  334.01  5445.7   337.7  5489.5  339.05  5510.4  339.14
  5539.6  340.34  5575.1  341.21  5639.8  342.19  5660.6     343  5703.4  343.79
#Mann= 5 ,-1 , 0
    4168     .05       0  4316.9      .1       0  4628.6     .05       0
  5071.9     .03       0  5077.9     .05       0
Bank Sta=5032.5,5089.1
XS Rating Curve= 0 ,0
Exp/Cntr=0.3,0.1

Type RM Length L Ch R = 1 ,113294  ,327,327,327
BEGIN DESCRIPTION:
CARTERS CREEK 73.0
END DESCRIPTION:
XS GIS Cut Line= 4
      3548614.79     10245483.01      3548403.56     10244986.31
      3548241.52     10244680.02      3547992.12     10244241.66
#Sta/Elev= 30
  4339.8  337.44  4458.5  337.36  4487.6  337.66  4558.5  336.82  4587.6  337.05
  4623.8  335.42  4874.8  332.06  4891.9   331.3  4897.6  331.52  4957.9  330.13
  4993.3  328.82    4996  328.32  4999.3  328.82  5023.9  329.91    5046  329.06
  5062.3  328.88    5134  330.72  5150.3  330.52  5254.1   331.4  5297.3  332.96
  5372.3  334.09  5399.6  334.96  5488.8  336.53  5511.8  337.41  5517.8     338
  5561.1     339  5598.5  340.67  5626.9   341.3  5707.4  344.28  5730.4  344.71
#Mann= 3 ,-1 , 0
  4339.8     .05       0  4993.3     .03       0  4999.3     .05       0
Bank Sta=4957.9,5023.9
XS Rating Curve= 0 ,0
Exp/Cntr=0.3,0.1

Type RM Length L Ch R = 1 ,112967  ,395,395,395
BEGIN DESCRIPTION:
CARTERS CREEK 72.0
END DESCRIPTION:
XS GIS Cut Line= 3
      3548742.11     10245241.66      3548509.75     10244488.18
      3548383.03     10244233.01
#Sta/Elev= 30
    4385  336.65  4471.9  335.63  4504.6  334.96  4531.5  335.01  4562.9  333.66
  4738.5   331.1  4879.6  329.25  4897.8  329.46  4912.2  329.17  4939.7  329.55
  4950.1  328.91    4971  328.41  4999.4  326.72  5002.2  326.22  5005.4  326.72
  5010.2  327.68  5015.5  328.15  5023.4  329.46  5042.9  330.39  5065.2  329.66
  5086.2  329.53  5107.1  329.99    5128  330.92  5159.3  331.58  5214.3  332.95
  5250.1  333.23  5294.9  334.33  5325.9  334.67  5348.3  335.57  5458.4  337.82
#Mann= 5 ,-1 , 0
    4385     .05       0  4738.5      .1       0  4999.4     .07       0
  5005.4      .1       0  5159.3     .05       0
#XS Ineff= 2 ,-1
 4802.95 4929.43  329.56 5042.39  5161.7  330.45
Permanent Ineff=
       F       F
Bank Sta=4939.7,5023.4
XS Rating Curve= 0 ,0
Exp/Cntr=0.3,0.1

Type RM Length L Ch R = 1 ,112572  ,55,55,55
BEGIN DESCRIPTION:
CARTERS CREEK 71.3
END DESCRIPTION:
XS GIS Cut Line= 3
       3549321.8     10245111.04      3548923.13     10244564.98
      3548601.33     10244083.28
#Sta/Elev= 30
  4362.5  329.03  4461.1  329.71  4490.5  329.66  4519.8  328.87  4540.7  329.47
  4584.6  329.17  4626.4  329.83  4712.1  329.47  4770.3  328.54  4812.5  328.89
  4833.4  328.51  4840.5  327.69  4848.1  328.26  4856.5  326.92  4862.7  327.17
  4869.4  326.43  4898.3  326.74  4939.3  326.25    4942  325.75  4945.3  326.25
    4970  326.57  5136.1  326.92  5178.2  326.39  5186.9  327.88  5193.2  329.83
  5199.2  330.25  5244.3  331.83  5322.4  333.57  5430.5  336.86  5617.9  340.42
#Mann= 5 ,-1 , 0
  4362.5     .05       0  4840.5      .1       0  4939.3    .033       0
  4945.3      .1       0    4970     .05       0
#XS Ineff= 2 ,-1
 4345.45 4541.82  329.52 4703.64 4812.73  328.98
Permanent Ineff=
       F       F
Bank Sta=4848.1,5186.9
XS Rating Curve= 0 ,0
Exp/Cntr=0.3,0.1

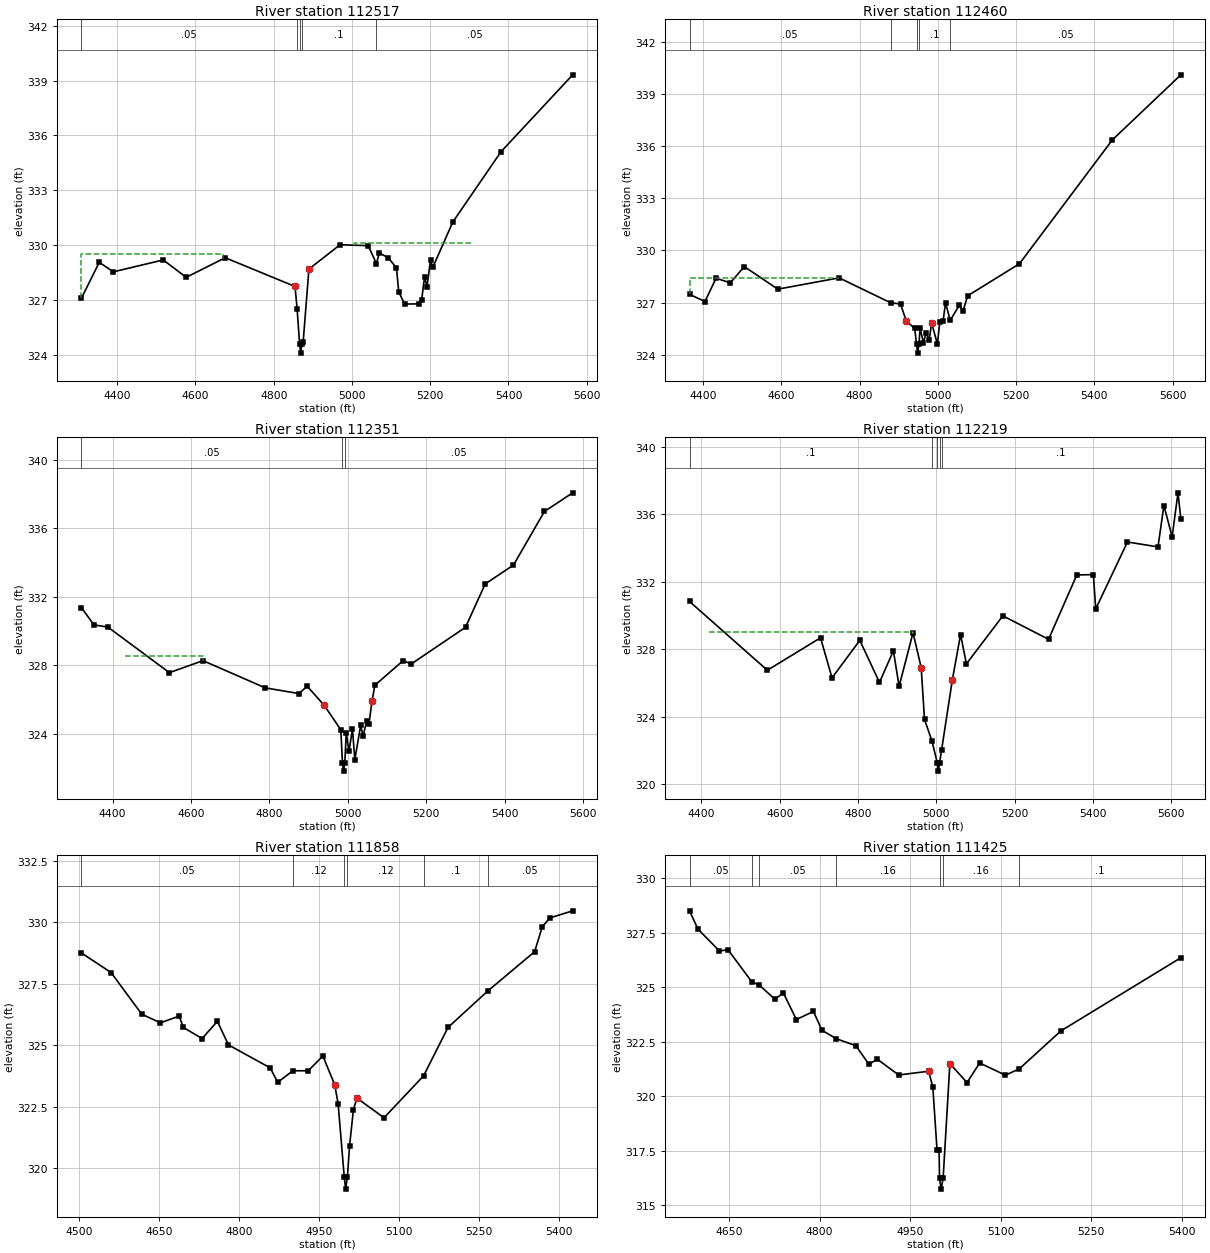
Type RM Length L Ch R = 1 ,112517  ,57,57,57
BEGIN DESCRIPTION:
CARTERS CREEK 71.2
END DESCRIPTION:
XS GIS Cut Line= 3
      3549408.38     10245158.52      3549009.69     10244612.45
      3548687.85     10244130.69
#Sta/Elev= 30
  4308.5   327.1  4354.2  329.07  4390.3  328.55  4517.7   329.2  4576.4  328.25
  4676.1  329.32  4854.5  327.75  4859.8  326.54  4866.2  324.61  4868.9  324.11
  4872.2  324.61  4875.3  324.71    4890   328.7  4969.6  330.03  5041.5  329.98
  5062.5     329  5069.8  329.58  5092.6  329.32  5113.6  328.77  5119.6  327.45
  5134.6  326.79  5170.7   326.8    5178  327.01  5185.7  328.29  5191.7  327.73
  5200.7  329.19  5206.7   328.8  5257.7  331.27  5380.9  335.11    5564  339.31
#Mann= 5 ,-1 , 0
  4308.5     .05       0  4859.8      .1       0  4866.2     .07       0
  4872.2      .1       0  5062.5     .05       0
#XS Ineff= 2 ,-1
 4301.82 4670.11  329.53    5005 5306.48  330.11
Permanent Ineff=
       F       F
Bank Sta=4854.5,4890
XS Rating Curve= 0 ,0
Exp/Cntr=0.3,0.1

Type RM Length L Ch R = 1 ,112460  ,109,109,109
BEGIN DESCRIPTION:
CARTERS CREEK 71.1
END DESCRIPTION:
XS GIS Cut Line= 3
      3549431.82     10245106.44      3549033.13     10244560.36
      3548711.29     10244078.61
#Sta/Elev= 30
  4365.6  327.47    4405  327.06  4433.5   328.4  4469.9  328.13  4505.4  329.07
  4591.1  327.77  4747.9  328.42  4880.1  326.98  4904.7  326.92  4919.4  325.94
  4941.1  325.51  4945.7  324.59  4948.5  324.09  4951.7  324.59  4954.9  325.51
  4963.4  324.68  4969.6  325.25  4978.1  324.86  4984.3  325.82  4998.9  324.62
  5005.1  325.87  5013.6  325.96  5019.8  326.99  5031.6  325.97  5055.4  326.86
  5064.2   326.5  5076.4  327.39  5208.6  329.23  5445.8  336.35  5621.1   340.1
#Mann= 5 ,-1 , 0
  4365.6     .05       0  4880.1      .1       0  4945.7     .07       0
  4951.7      .1       0  5031.6     .05       0
#XS Ineff= 1 ,-1
 4353.64 4747.27  328.44
Permanent Ineff=
       F
Bank Sta=4919.4,4984.3
XS Rating Curve= 0 ,0
Exp/Cntr=0.3,0.1

Type RM Length L Ch R = 1 ,112351  ,132,132,132
BEGIN DESCRIPTION:
CARTERS CREEK 71.0
END DESCRIPTION:
XS GIS Cut Line= 3
      3549556.62     10245121.87      3549157.95      10244575.8
      3548837.49     10244096.11
#Sta/Elev= 30
  4320.2  331.37  4352.4  330.36  4387.9  330.23  4544.7  327.57  4630.4  328.27
  4789.5  326.68  4875.2  326.35  4896.1  326.78  4939.6  325.66  4981.8  324.24
  4986.1  322.32  4988.8  321.82  4992.1  322.32  4995.8  324.06  5002.6  322.97
  5011.6  324.27  5017.6  322.49  5032.6   324.5  5038.6  323.85  5047.6  324.73
  5053.6  324.58  5061.4  325.89  5068.6  326.83  5140.7  328.27  5161.8  328.08
  5299.9  330.22  5350.1  332.75  5422.2  333.85  5501.1  336.98  5573.2  338.07
#Mann= 3 ,-1 , 0
  4320.2     .05       0  4986.1     .04       0  4992.1     .05       0
#XS Ineff= 1 ,-1
 4432.27 4629.55  328.54
Permanent Ineff=
       F
Bank Sta=4939.6,5061.4
XS Rating Curve= 0 ,0
Exp/Cntr=0.3,0.1

Type RM Length L Ch R = 1 ,112219  ,361,361,361
BEGIN DESCRIPTION:
CARTERS CREEK 71.4
END DESCRIPTION:
XS GIS Cut Line= 3
      3549643.53     10245038.31      3549244.87     10244492.26
      3548923.06     10244010.56
#Sta/Elev= 30
  4369.5  330.83  4568.3  326.76  4704.2  328.68  4733.6  326.31  4804.6  328.53
  4854.8  326.04  4890.4  327.91    4905  325.81  4940.6  328.98  4961.4  326.92
  4969.9  323.85  4989.1  322.56  5002.4  321.29  5005.2  320.79  5008.4  321.29
  5013.5  322.03    5041  326.19    5062  328.87    5077  327.14  5170.1  329.98
  5286.9  328.59    5359   332.4  5401.4  332.42  5407.4  330.39  5488.4  334.35
  5566.5  334.06  5581.6  336.51  5602.6  334.66  5617.6  337.26  5624.9  335.72
#Mann= 5 ,-1 , 0
  4369.5      .1       0  4989.1     .08       0  5002.4     .07       0
  5008.4     .08       0  5013.5      .1       0
#XS Ineff= 1 ,-1
 4418.18    4940  329.01
Permanent Ineff=
       F
Bank Sta=4961.4,5041
XS Rating Curve= 0 ,0
Exp/Cntr=0.3,0.1

Type RM Length L Ch R = 1 ,111858  ,433,433,433
BEGIN DESCRIPTION:
CARTERS CREEK 70.0
END DESCRIPTION:
XS GIS Cut Line= 3
      3549891.61     10244760.95      3549498.46     10244281.58
      3549291.61     10244060.94
#Sta/Elev= 30
  4503.5  328.75  4559.4  327.95  4616.8  326.26  4651.9  325.91  4687.1  326.18
    4695  325.72  4730.2  325.27  4758.9  325.97  4779.7  325.01  4857.9  324.08
  4872.2  323.49  4900.5  323.96  4929.4  323.96  4956.9  324.56  4979.2  323.39
  4985.6  322.61    4997  319.65  4999.7  319.15    5003  319.65    5007  320.91
  5014.3  322.38  5020.8  322.85  5071.7  322.05  5145.9  323.75  5191.8  325.72
  5266.4   327.2  5354.5   328.8  5368.6   329.8  5382.8  330.17  5425.9  330.46
#Mann= 6 ,-1 , 0
  4503.5     .05       0  4900.5     .12       0    4997     .07       0
    5003     .12       0  5145.9      .1       0  5266.4     .05       0
Bank Sta=4979.2,5020.8
XS Rating Curve= 0 ,0
Exp/Cntr=0.3,0.1

Type RM Length L Ch R = 1 ,111425  ,326,326,326
BEGIN DESCRIPTION:
CARTERS CREEK 69.0
END DESCRIPTION:
XS GIS Cut Line= 3
      3550242.11     10244441.65      3549942.11     10244157.05
      3549642.08     10243891.62
#Sta/Elev= 30
  4584.6   328.5  4598.6  327.66  4634.2  326.66  4648.3  326.72    4688  325.24
  4699.7  325.11    4726  324.45  4740.1  324.74  4761.6  323.52  4789.9  323.89
    4804  323.03  4827.8  322.64  4860.3  322.32  4881.7  321.47  4895.9   321.7
  4931.1  320.98  4980.8  321.15  4987.7  320.43  4994.7  317.55  4998.1  317.55
  4998.8  316.25  5001.5  315.75  5004.8  316.25    5016   321.5  5044.4  320.63
  5065.3  321.53    5108  320.97    5131  321.26    5200     323  5398.7  326.35
#Mann= 7 ,-1 , 0
  4584.6     .05       0    4688     .16       0  4699.7     .05       0
  4827.8     .16       0  4998.8     .07       0  5004.8     .16       0
    5131      .1       0
Bank Sta=4980.8,5016
XS Rating Curve= 0 ,0
Exp/Cntr=0.3,0.1

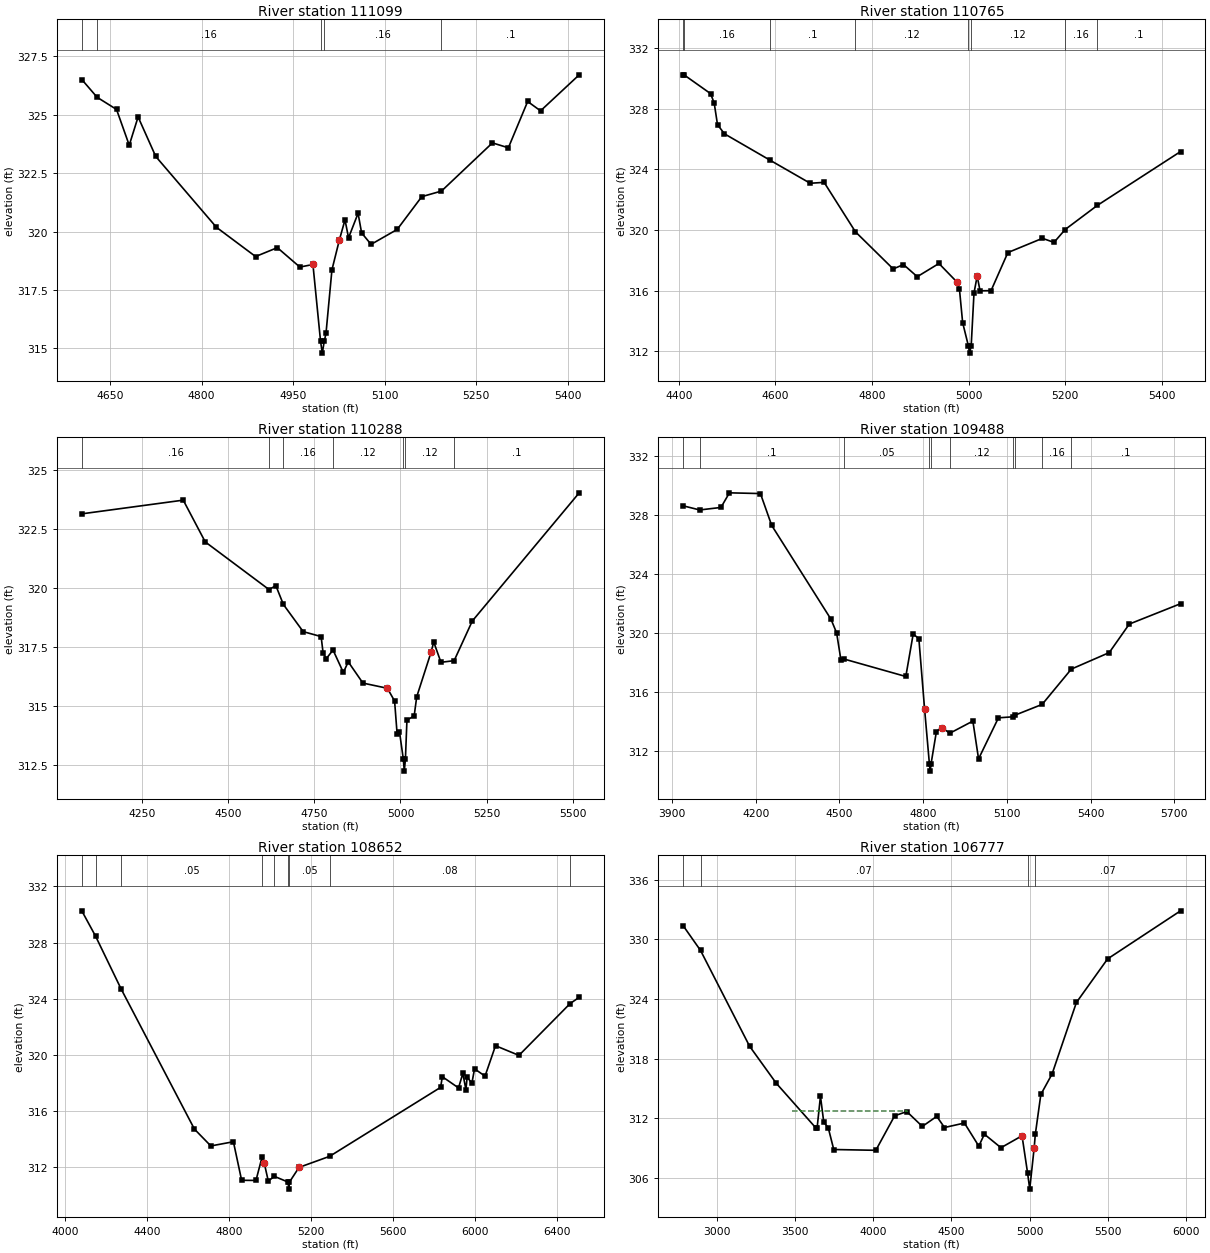
Type RM Length L Ch R = 1 ,111099  ,334,334,334
BEGIN DESCRIPTION:
CARTERS CREEK 68.0
END DESCRIPTION:
XS GIS Cut Line= 4
       3550442.1     10244141.64      3550202.89     10243953.46
      3549985.87     10243823.25      3549742.11     10243741.64
#Sta/Elev= 30
  4603.9   326.5    4629  325.74  4660.8  325.22  4681.6  323.69  4696.1   324.9
    4725  323.21  4824.4  320.18  4888.5  318.93  4924.1  319.31    4961  318.48
  4982.4  318.59  4994.9   315.3  4997.7   314.8  5000.9   315.3  5003.8  315.65
  5013.5  318.36  5025.8  319.65  5034.9   320.5  5040.7  319.73  5056.3  320.78
  5062.1  319.94  5077.6  319.45  5120.4  320.09  5160.6  321.49  5192.9  321.73
  5276.3  323.79  5302.4  323.58    5334  325.56  5355.1  325.16  5418.4   326.7
#Mann= 5 ,-1 , 0
  4603.9     .05       0    4629     .16       0  4994.9     .07       0
  5000.9     .16       0  5192.9      .1       0
Bank Sta=4982.4,5025.8
XS Rating Curve= 0 ,0
Exp/Cntr=0.3,0.1

Type RM Length L Ch R = 1 ,110765  ,477,477,477
BEGIN DESCRIPTION:
CARTERS CREEK 67.0
END DESCRIPTION:
XS GIS Cut Line= 4
      3550692.11     10244041.65      3550431.65     10243718.86
      3550218.08     10243587.14      3549881.68     10243447.81
#Sta/Elev= 30
  4408.8  330.24  4410.6  330.24  4465.6     329  4473.1  328.38    4480  326.95
  4494.4  326.35  4588.8  324.61  4671.9  323.09  4700.7  323.15  4765.5  319.89
  4843.7  317.44    4865  317.73  4893.5  316.93  4938.4   317.8    4975   316.6
  4980.9  316.09  4987.5   313.9  4999.2  312.39  5001.9  311.89  5005.2  312.39
    5011  315.86  5017.6  316.97  5023.5     316  5046.3  316.01  5081.1  318.52
  5152.7  319.46  5176.6  319.19  5199.7  320.04  5266.3  321.63  5438.6  325.18
#Mann= 8 ,-1 , 0
  4408.8     .05       0  4410.6     .16       0  4588.8      .1       0
  4765.5     .12       0  4999.2     .07       0  5005.2     .12       0
  5199.7     .16       0  5266.3      .1       0
Bank Sta=4975,5017.6
XS Rating Curve= 0 ,0
Exp/Cntr=0.3,0.1

Type RM Length L Ch R = 1 ,110288  ,800,800,800
BEGIN DESCRIPTION:
CARTERS CREEK 66.0
END DESCRIPTION:
XS GIS Cut Line= 4
      3551246.74     10243821.53      3550604.21     10243426.72
      3550383.01      10243226.9      3549992.12     10243241.64
#Sta/Elev= 30
  4075.2  323.16  4369.6  323.74  4433.5  321.97  4618.7  319.95  4638.3  320.12
  4660.2  319.32  4717.6  318.17  4769.7  317.96  4775.6  317.25  4784.9  317.03
  4804.3  317.39  4834.2  316.44  4848.4  316.89    4891  315.99    4962  315.77
  4982.9  315.23  4990.3  313.82  4997.1  313.93  5008.3  312.76    5011  312.26
  5014.3  312.76  5018.7  314.42  5039.7   314.6  5047.1  315.41    5089  317.31
  5096.5  317.73  5117.4  316.87  5155.7  316.94  5208.4  318.62  5518.6  324.05
#Mann= 7 ,-1 , 0
  4075.2     .16       0  4618.7      .1       0  4660.2     .16       0
  4804.3     .12       0  5008.3     .07       0  5014.3     .12       0
  5155.7      .1       0
Bank Sta=4962,5089
XS Rating Curve= 0 ,0
Exp/Cntr=0.3,0.1

Type RM Length L Ch R = 1 ,109488  ,836,836,836
BEGIN DESCRIPTION:
CARTERS CREEK 65.0
END DESCRIPTION:
XS GIS Cut Line= 4
       3551776.2     10242897.03      3551176.61     10242811.04
      3550599.95     10242920.53      3550036.49     10243092.13
#Sta/Elev= 30
  3940.2  328.62  3999.6  328.34  4075.7  328.51    4106   329.5  4217.1  329.45
  4257.5  327.29  4469.7  320.94  4489.9  320.02  4505.7  318.15  4515.1  318.25
  4737.8  317.06  4764.3  319.94  4784.6  319.62    4805  314.87  4822.3  311.15
  4825.1  310.65  4828.3  311.15  4847.4  313.33    4866   313.6  4895.7  313.22
    4978  314.04  4998.4  311.48  5069.6  314.26    5122  314.33  5130.2  314.45
  5226.2  315.17  5330.6  317.56  5466.6  318.68  5538.3  320.61  5721.9  321.99
#Mann= 10 ,-1 , 0
  3940.2     .08       0  3999.6      .1       0  4515.1     .05       0
  4822.3     .07       0  4828.3     .05       0  4895.7     .12       0
    5122     .16       0  5130.2     .12       0  5226.2     .16       0
  5330.6      .1       0
Bank Sta=4805,4866
XS Rating Curve= 0 ,0
Exp/Cntr=0.3,0.1

Type RM Length L Ch R = 1 ,108652  ,1875,1875,1875
BEGIN DESCRIPTION:
CARTERS CREEK 64.0
END DESCRIPTION:
XS GIS Cut Line= 4
      3551642.14     10242541.66        3551212.     10242232.97
      3550453.92     10242241.93      3549506.06     10242871.75
#Sta/Elev= 30
  4081.4  330.26  4148.7  328.45  4272.4  324.71  4630.7  314.69  4710.7  313.49
  4820.7  313.79  4860.8  311.04  4930.8  311.03  4960.8  312.71  4970.8  312.29
  4990.8  310.99  5020.8  311.32  5087.8  310.91  5090.5  310.41  5093.8  310.91
  5140.8  311.96  5290.1  312.75  5831.3  317.67  5839.4  318.43  5918.5  317.63
  5939.5  318.66  5954.6  317.51  5960.6   318.4  5983.5  317.96  5996.7  318.99
  6047.8  318.47  6098.9  320.64  6213.1  319.95    6463  323.65    6507  324.09
#Mann= 9 ,-1 , 0
  4081.4      .1       0  4148.7     .08       0  4272.4     .05       0
  4960.8     .12       0  5020.8     .05       0  5087.8     .04       0
  5093.8     .05       0  5290.1     .08       0    6463     .05       0
Bank Sta=4970.8,5140.8
XS Rating Curve= 0 ,0
Exp/Cntr=0.3,0.1

Type RM Length L Ch R = 1 ,106777  ,659,659,659
BEGIN DESCRIPTION:
CARTERS CREEK 63.0
END DESCRIPTION:
XS GIS Cut Line= 3
       3551792.1     10242341.64      3550138.43     10240729.44
      3549466.56     10240181.94
#Sta/Elev= 30
  2786.6  331.37  2897.7  328.88  3210.9  319.26  3380.6  315.55  3635.2  311.03
  3642.2  311.06  3663.5  314.24  3684.7  311.61    3713  311.08  3748.4  308.88
    4017   308.8  4137.3  312.27    4215  312.69    4314   311.2  4406.1  312.21
  4455.5  311.09  4582.8  311.54  4674.7  309.22  4710.1  310.42  4816.1  309.06
  4950.6  310.26  4985.9  306.54  4999.8   304.9  5028.3  309.07  5035.3  310.39
  5070.7  314.41  5142.3  316.46  5297.8  323.65    5497  328.03  5962.8  332.86
#Mann= 4 ,-1 , 0
  2786.6      .1       0  2897.7     .07       0  4985.9     .05       0
  5035.3     .07       0
#XS Ineff= 1 ,-1
 3484.38 4218.18   312.7
Permanent Ineff=
       F
Bank Sta=4950.6,5028.3
XS Rating Curve= 0 ,0
Exp/Cntr=0.3,0.1

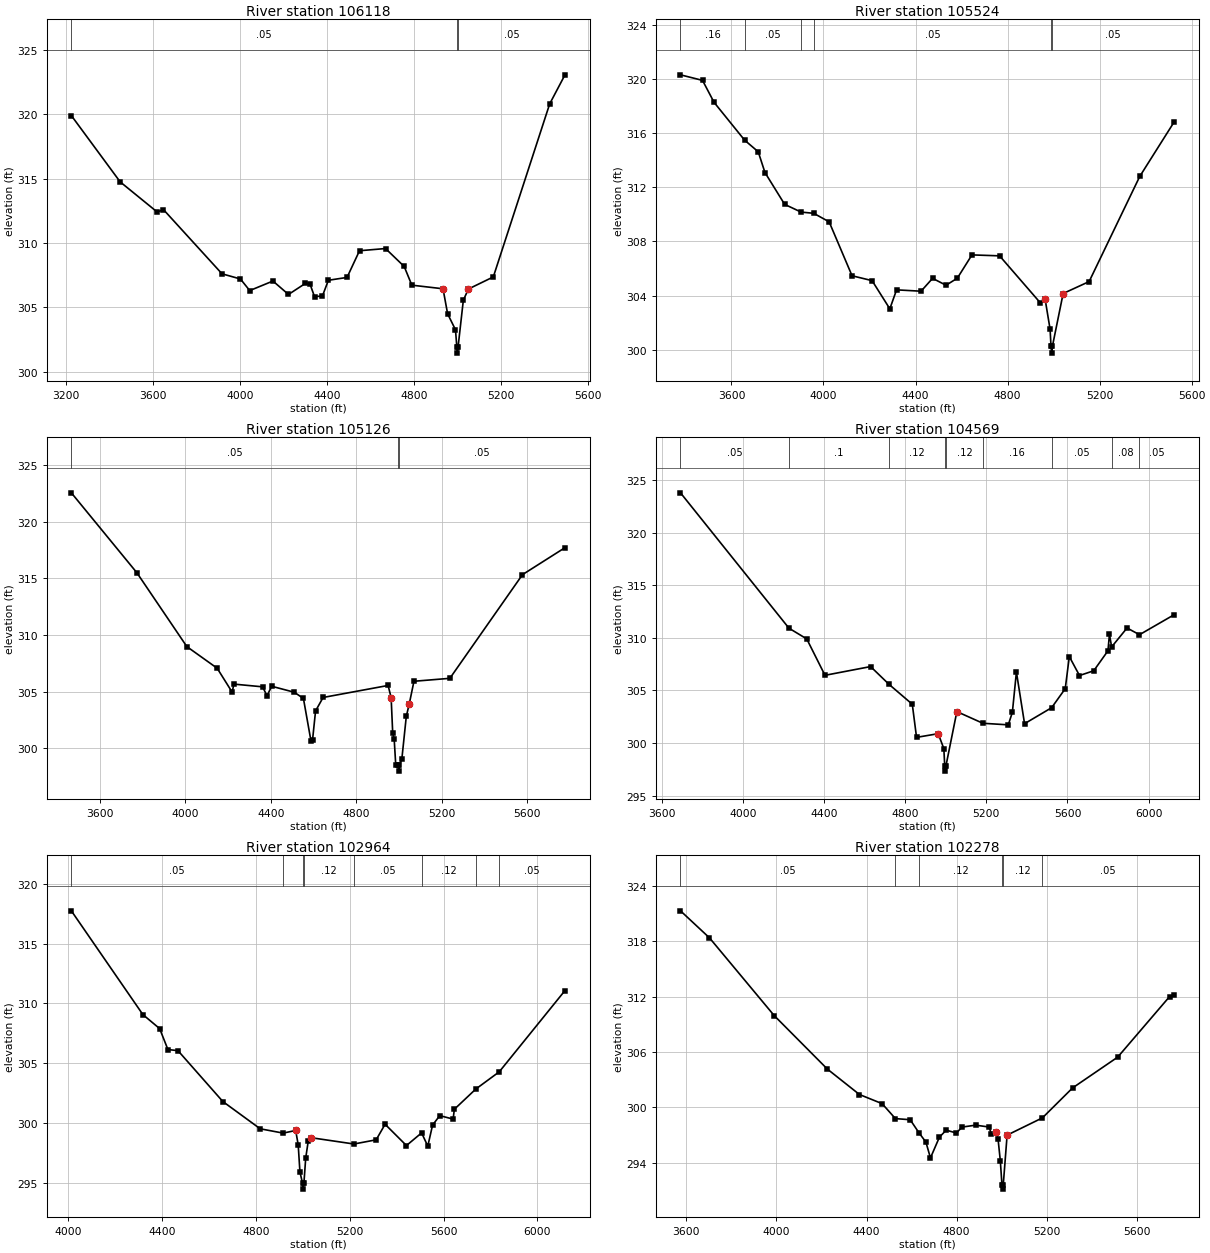
Type RM Length L Ch R = 1 ,106118  ,594,594,594
BEGIN DESCRIPTION:
CARTERS CREEK 61.0
END DESCRIPTION:
XS GIS Cut Line= 4
      3551832.63     10241777.21      3550810.34     10240557.92
      3550647.77     10240310.23      3550313.57      10240123.6
#Sta/Elev= 30
  3224.6  319.88  3449.1  314.74  3619.6   312.4  3648.2  312.59  3917.5  307.61
  4002.1  307.21    4045  306.31  4151.7  307.05  4223.2  306.01  4301.3  306.87
  4322.1  306.82  4342.9  305.84  4379.3  305.89  4406.7  307.11  4492.5  307.33
  4549.8   309.4  4669.5  309.57  4755.3  308.18  4790.5  306.73  4933.9  306.45
    4955  304.51  4991.2  303.27  4997.3  301.96    5000  301.46  5003.3  301.96
  5027.3  305.56  5050.5  306.43  5165.2  307.37  5424.5  320.79  5494.8  323.04
#Mann= 3 ,-1 , 0
  3224.6     .05       0  4997.3     .03       0  5003.3     .05       0
#XS Ineff= 1 ,-1
    3750 4670.45  309.51
Permanent Ineff=
       F
Bank Sta=4933.9,5050.5
XS Rating Curve= 0 ,0
Exp/Cntr=0.3,0.1

Type RM Length L Ch R = 1 ,105524  ,398,398,398
BEGIN DESCRIPTION:
CARTERS CREEK 60.0
END DESCRIPTION:
XS GIS Cut Line= 4
       3552431.6     10241065.42      3551498.46     10240375.33
      3551033.19      10239887.6      3550792.13     10239691.66
#Sta/Elev= 30
  3378.5  320.29  3474.3  319.88  3524.4  318.26  3657.1  315.47  3716.4  314.61
  3745.6  313.08  3831.2  310.73  3902.6  310.16  3957.5  310.07  4024.6  309.44
  4124.1  305.46  4211.2   305.1  4288.3  303.02  4317.6  304.42    4424  304.32
  4474.1  305.27  4532.6  304.76  4581.6  305.28  4645.2     307  4765.3  306.93
  4942.4  303.46  4963.4  303.71  4984.8  301.51  4988.8  300.25  4991.5  299.75
  4994.8  300.25  5041.5  304.15  5154.4  305.03  5374.4  312.79  5523.8  316.81
#Mann= 6 ,-1 , 0
  3378.5     .16       0  3657.1     .05       0  3902.6     .16       0
  3957.5     .05       0  4988.8     .03       0  4994.8     .05       0
Bank Sta=4963.4,5041.5
XS Rating Curve= 0 ,0
Exp/Cntr=0.3,0.1

Type RM Length L Ch R = 1 ,105126  ,557,557,557
BEGIN DESCRIPTION:
CARTERS CREEK 59.0
END DESCRIPTION:
XS GIS Cut Line= 3
      3552531.48     10240935.27      3551414.33     10239711.54
      3550777.93     10239572.37
#Sta/Elev= 30
  3467.4  322.56  3773.7  315.51  4007.5  308.99  4149.3  307.08  4219.6  304.96
  4227.1  305.68  4361.5  305.44  4382.5  304.65  4404.1  305.49  4510.1  304.96
  4552.7  304.41  4587.8  300.68  4595.3  300.75  4609.4  303.31  4644.6   304.5
  4948.6  305.56  4962.8  304.49  4970.2  301.35    4977  300.85  4984.4  298.54
  4995.6   298.5  4998.3     298  5001.6   298.5  5012.8  299.05  5033.7  302.83
  5047.9  303.96  5069.5  305.93  5237.5  306.19    5577  315.34  5775.8  317.72
#Mann= 3 ,-1 , 0
  3467.4     .05       0  4995.6     .04       0  5001.6     .05       0
Bank Sta=4962.8,5047.9
XS Rating Curve= 0 ,0
Exp/Cntr=0.3,0.1

Type RM Length L Ch R = 1 ,104569  ,1605,1605,1605
BEGIN DESCRIPTION:
CARTERS CREEK 58.0
END DESCRIPTION:
XS GIS Cut Line= 5
      3553108.72     10240054.16       3552353.5     10239958.67
      3551857.27     10239411.25      3551242.38     10239368.39
      3550986.75     10239182.08
#Sta/Elev= 30
  3692.7  323.78  4227.3  310.91    4315  309.89  4404.9  306.43  4629.7  307.26
  4721.1  305.56  4835.1  303.68  4856.1  300.53  4962.8  300.88  4990.6  299.46
    4995  297.82  4997.8  297.32    5001  297.82  5054.8  302.98  5183.1  301.87
  5308.2  301.72  5328.3  302.91  5348.3  306.74  5388.4  301.83  5521.8  303.35
  5588.9  305.16    5609  308.21  5659.1  306.41  5729.3  306.86  5799.4  308.76
  5806.8  310.33  5817.6  309.13  5893.5  310.93  5954.8  310.29  6125.5  312.19
#Mann= 9 ,-1 , 0
  3692.7     .05       0  4227.3      .1       0  4721.1     .12       0
    4995     .07       0    5001     .12       0  5183.1     .16       0
  5521.8     .05       0  5817.6     .08       0  5954.8     .05       0
Bank Sta=4962.8,5054.8
XS Rating Curve= 0 ,0
Exp/Cntr=0.3,0.1

Type RM Length L Ch R = 1 ,102964  ,686,686,686
BEGIN DESCRIPTION:
CARTERS CREEK 57.0
END DESCRIPTION:
XS GIS Cut Line= 4
      3552992.12     10239441.66      3552535.79     10238903.98
      3551871.72      10238647.9        3551199.     10238513.36
#Sta/Elev= 30
  4014.4  317.73  4319.2  309.06  4390.6  307.89  4425.8  306.14  4468.6  306.05
  4659.7   301.8    4819  299.52  4916.8  299.16  4970.1  299.38  4980.8  298.19
  4988.2  295.92  4999.2  294.98    5002  294.48  5005.2  294.98  5012.8  297.07
  5023.7  298.51  5034.4  298.78  5218.3  298.25    5313   298.6    5351   299.9
    5442  298.12  5506.6  299.18  5532.9  298.07  5553.3  299.83  5583.9  300.62
  5640.9  300.33    5646  301.15  5737.4  302.84  5837.3  304.28  6117.4  311.07
#Mann= 8 ,-1 , 0
  4014.4     .05       0  4916.8     .12       0  4999.2     .07       0
  5005.2     .12       0  5218.3     .05       0  5506.6     .12       0
  5737.4      .1       0  5837.3     .05       0
Bank Sta=4970.1,5034.4
XS Rating Curve= 0 ,0
Exp/Cntr=0.3,0.1

Type RM Length L Ch R = 1 ,102278  ,627,627,627
BEGIN DESCRIPTION:
CARTERS CREEK 56.0
END DESCRIPTION:
XS GIS Cut Line= 4
      3553342.14     10238841.67      3552535.79     10238257.28
      3551974.81     10238231.19      3551342.08     10238191.64
#Sta/Elev= 30
  3573.9  321.29  3702.7  318.36  3989.6  309.95  4226.2  304.14  4368.4  301.39
    4469   300.4    4528  298.78  4593.5  298.66  4632.2  297.26  4663.5  296.23
  4683.6  294.52  4723.6  296.78  4753.6  297.53  4798.7  297.22  4823.7  297.86
  4883.8  298.07  4943.8  297.87  4953.8  297.13  4973.9  297.36  4983.9  296.52
  4993.9  294.18  5000.9  291.64  5003.6  291.14  5006.9  291.64  5023.9  296.99
  5180.6  298.86  5314.4   302.1  5514.8  305.44  5745.2     312  5765.3  312.16
#Mann= 6 ,-1 , 0
  3573.9     .05       0    4528      .1       0  4632.2     .12       0
  5000.9     .07       0  5006.9     .12       0  5180.6     .05       0
Bank Sta=4973.9,5023.9
XS Rating Curve= 0 ,0
Exp/Cntr=0.3,0.1