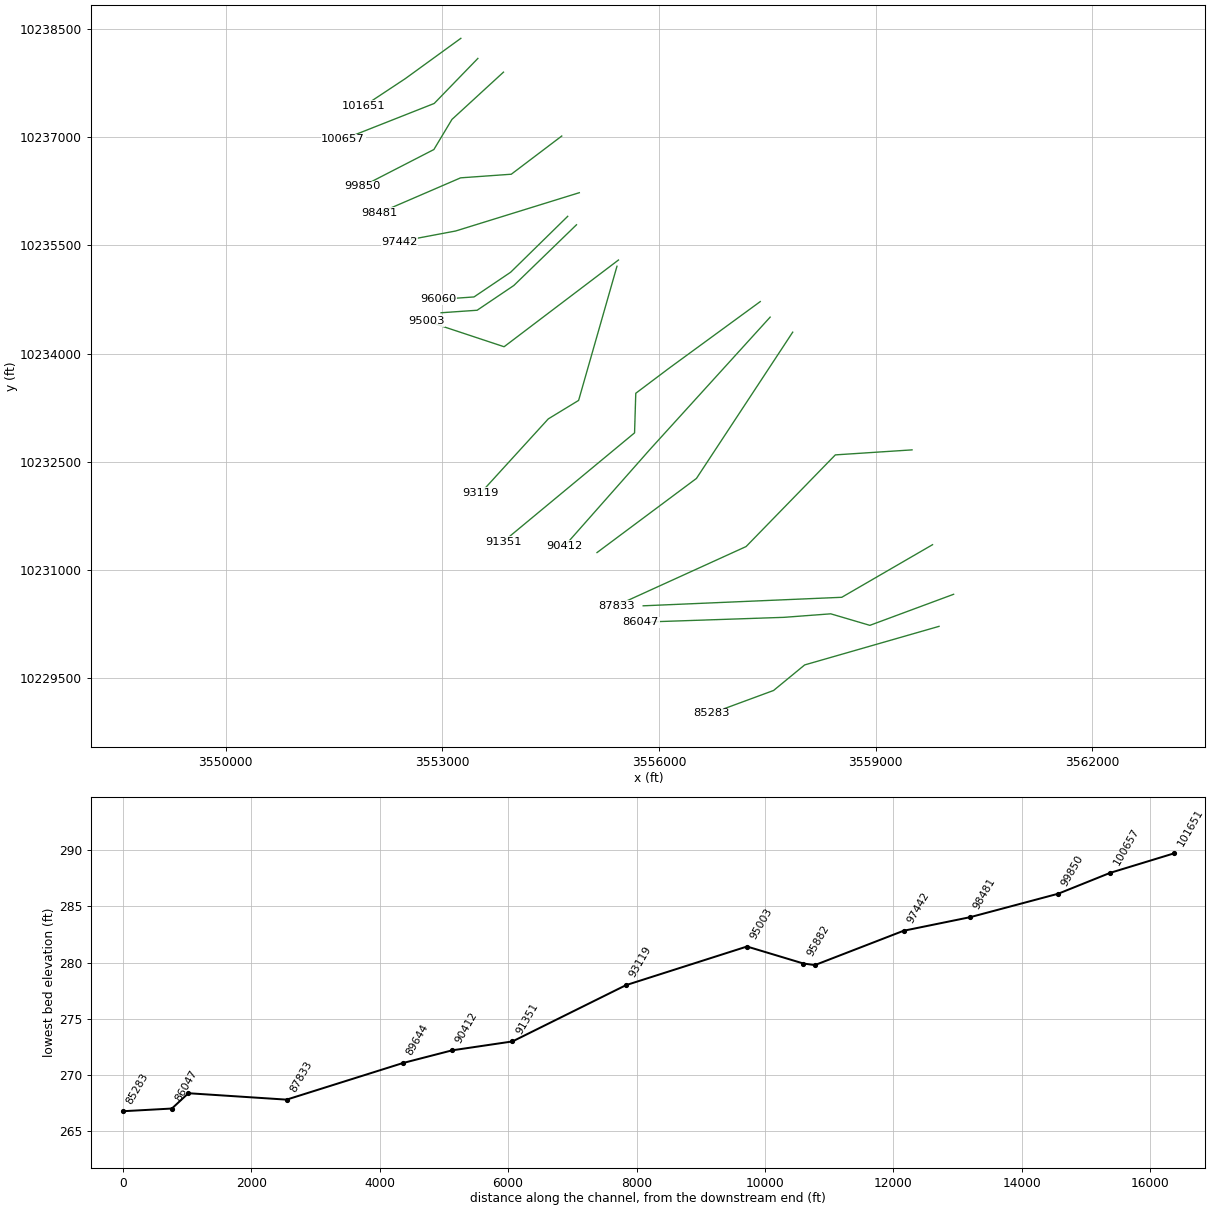
HEC-RAS study CARTERS CREEK.prj: CARTERS CREEK Base Level Engineering

--- CARTERS CREEK.g01 (geometry) --- (continued)

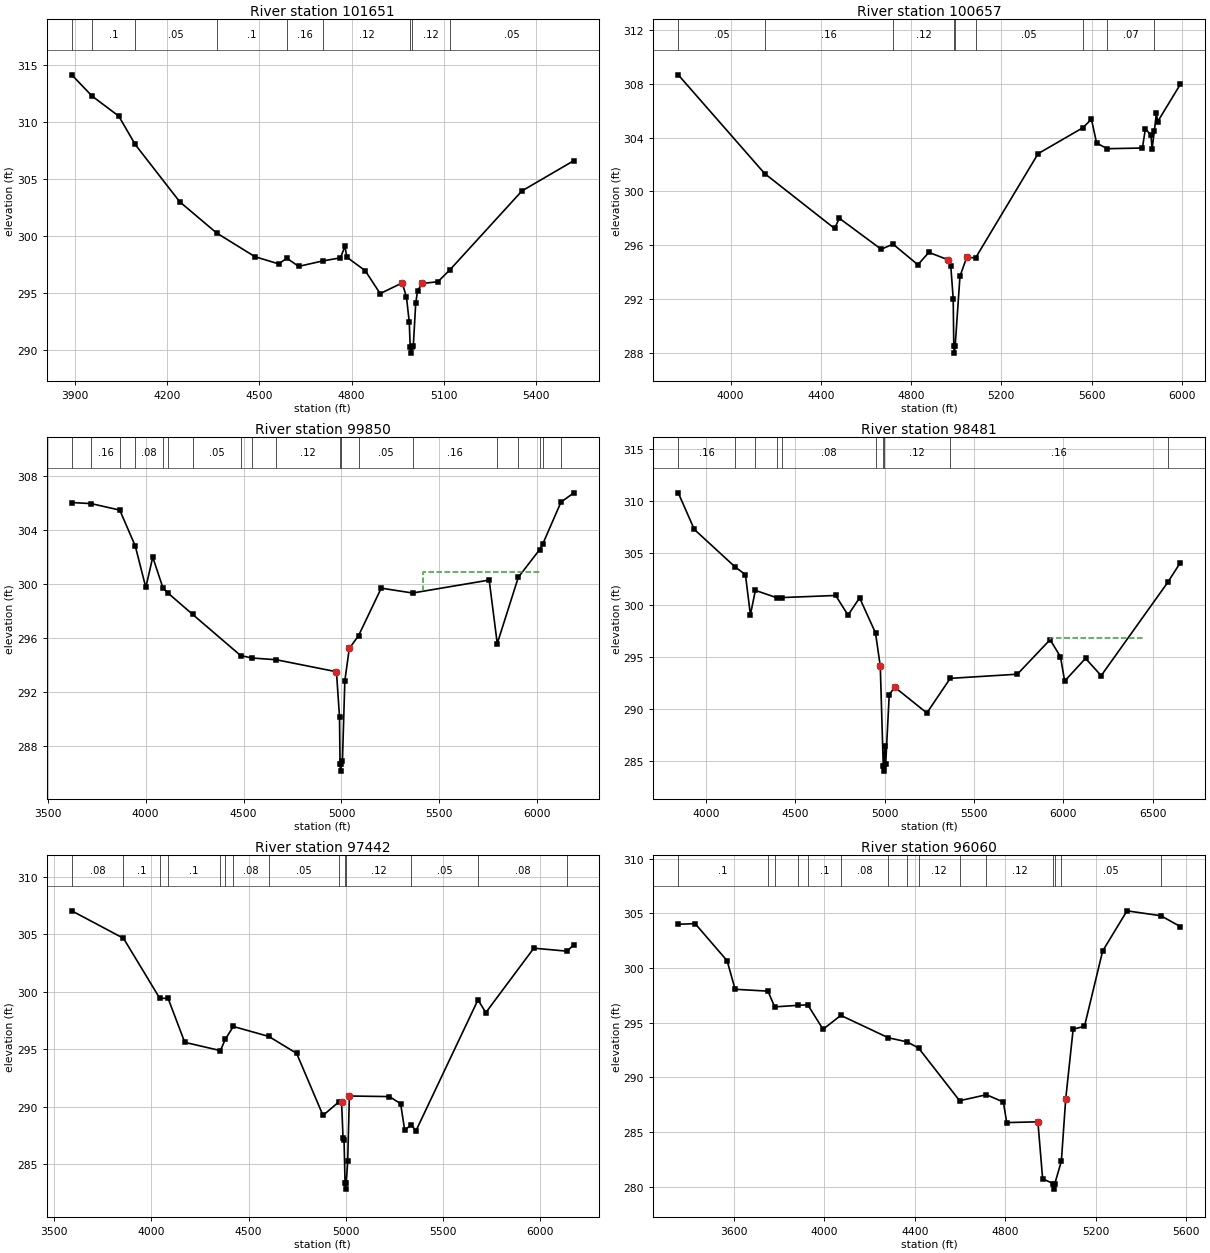
Type RM Length L Ch R = 1 ,101651  ,994,994,994
BEGIN DESCRIPTION:
CARTERS CREEK 55.0
END DESCRIPTION:
XS GIS Cut Line= 3
       3553256.3     10238370.15      3552485.38     10237810.33
      3551916.08     10237433.25
#Sta/Elev= 30
  3888.6  314.14  3954.8  312.27  4041.8  310.51  4095.2  308.02  4240.5  302.98
  4360.2  300.25  4485.5  298.16  4562.8  297.53  4589.3  298.03  4627.7  297.31
  4706.1  297.79  4763.8  298.06  4778.5  299.07  4784.7  298.12  4844.7  296.93
  4893.2  294.92  4965.2  295.86    4979  294.59  4988.1   292.4  4991.1  290.19
  4993.8  289.69  4997.1  290.19  5001.2  290.31  5009.1  294.08  5015.1  295.17
  5030.2  295.81  5081.3  295.96  5121.2  297.03  5355.1  303.94  5524.2   306.6
#Mann= 9 ,-1 , 0
  3888.6     .05       0  3954.8      .1       0  4095.2     .05       0
  4360.2      .1       0  4589.3     .16       0  4706.1     .12       0
  4991.1     .07       0  4997.1     .12       0  5121.2     .05       0
Bank Sta=4965.2,5030.2
XS Rating Curve= 0 ,0
Exp/Cntr=0.3,0.1

Type RM Length L Ch R = 1 ,100657  ,807,807,807
BEGIN DESCRIPTION:
CARTERS CREEK 53.0
END DESCRIPTION:
XS GIS Cut Line= 3
       3553492.1     10238091.64      3552887.35     10237467.35
      3551625.76     10236968.78
#Sta/Elev= 30
  3767.8  308.68  4150.9  301.33  4460.9  297.24    4482     298  4667.8  295.69
  4719.7  296.08  4830.1  294.54  4878.8  295.46  4962.6  294.92  4975.9  294.47
  4986.7  292.02  4989.3  288.46  4992.1  287.96  4995.3  288.46  5016.7  293.68
  5046.4  295.08  5086.3  295.06    5363  302.81  5560.6  304.73  5599.6  305.37
  5622.4   303.6  5669.5  303.18  5825.4  303.23  5838.8  304.67  5863.2  304.18
  5868.5  303.18  5878.5  304.51  5887.5  305.84  5892.9  305.19  5993.5  307.97
#Mann= 9 ,-1 , 0
  3767.8     .05       0  4150.9     .16       0  4719.7     .12       0
  4989.3     .07       0  4995.3     .12       0  5086.3     .05       0
  5560.6      .1       0  5669.5     .07       0  5878.5     .05       0
Bank Sta=4962.6,5046.4
XS Rating Curve= 0 ,0
Exp/Cntr=0.3,0.1

Type RM Length L Ch R = 1 ,99850   ,1369,1369,1369
BEGIN DESCRIPTION:
CARTERS CREEK 52.0
END DESCRIPTION:
XS GIS Cut Line= 4
      3553846.54     10237901.36      3553132.99     10237245.76
      3552882.85     10236828.65      3551897.79     10236321.53
#Sta/Elev= 30
  3623.1  306.03  3722.2  305.95  3868.1  305.47  3947.2  302.81  4001.1  299.73
  4036.5  301.98  4088.9  299.69  4114.1  299.32  4239.7  297.74  4485.3  294.68
  4543.7   294.5  4667.6  294.37  4974.4  293.48    4990  290.13  4992.8  286.61
  4995.5  286.11  4998.8  286.61    5005  286.86  5017.2  292.81    5040  295.21
  5087.4  296.16    5203  299.68    5363  299.32  5754.1  300.28  5795.4  295.57
    5903  300.49  6011.9  302.54  6027.8  302.96  6120.7  306.06  6186.4  306.75
#Mann= 19 ,-1 , 0
  3623.1     .05       0  3722.2     .16       0  3868.1     .05       0
  3947.2     .08       0  4088.9     .05       0  4114.1     .08       0
  4239.7     .05       0  4485.3     .12       0  4543.7     .16       0
  4667.6     .12       0  4992.8     .07       0  4998.8     .12       0
  5087.4     .05       0    5363     .16       0  5795.4      .1       0
    5903     .16       0  6011.9     .05       0  6027.8      .1       0
  6120.7     .05       0
#XS Ineff= 1 ,-1
 5415.91  6012.5  300.89
Permanent Ineff=
       F
Bank Sta=4974.4,5040
XS Rating Curve= 0 ,0
Exp/Cntr=0.3,0.1

Type RM Length L Ch R = 1 ,98481   ,1039,1039,1039
BEGIN DESCRIPTION:
CARTERS CREEK 51.0
END DESCRIPTION:
XS GIS Cut Line= 4
      3554653.87     10237015.98      3553955.06     10236486.44
      3553253.29     10236436.33      3552125.28     10235949.04
#Sta/Elev= 30
    3845  310.79    3935  307.27  4162.8  303.67    4221  302.92  4248.7  299.06
  4276.6  301.41  4396.9   300.7  4428.1  300.72  4725.8  300.92  4794.9  299.03
  4859.7  300.69  4948.7  297.32  4975.4  294.12  4992.1  284.53  4994.9  284.03
  4998.1  284.53  5000.1  286.48  5005.5  284.68  5025.5  291.37  5055.6  292.11
    5236  289.62  5366.7  292.95  5742.5  293.35  5925.6  296.67  5983.5  295.03
    6007  292.69  6123.8  294.87  6211.3  293.21  6583.3  302.17  6654.1  304.07
#Mann= 10 ,-1 , 0
    3845     .16       0  4162.8     .05       0  4276.6     .08       0
  4396.9      .1       0  4428.1     .08       0  4948.7     .12       0
  4992.1     .07       0  4998.1     .12       0  5366.7     .16       0
  6583.3     .05       0
#XS Ineff= 1 ,-1
 5924.15 6451.14  296.86
Permanent Ineff=
       F
Bank Sta=4975.4,5055.6
XS Rating Curve= 0 ,0
Exp/Cntr=0.3,0.1

Type RM Length L Ch R = 1 ,97442   ,1382,1382,1382
BEGIN DESCRIPTION:
CARTERS CREEK 49.0
END DESCRIPTION:
XS GIS Cut Line= 3
       3554896.9     10236230.37      3553185.09     10235699.55
      3552409.89     10235553.28
#Sta/Elev= 30
  3590.8  307.03  3856.7  304.64  4043.5  299.41  4085.6  299.43  4171.7  295.59
  4354.9  294.87  4380.8  295.88  4421.4  296.97  4604.1   296.1  4746.8  294.63
  4882.4  289.23  4964.5  290.42  4977.8  290.44  4985.4  287.24  4990.6  287.08
  4995.8  283.32  4998.5  282.82  5001.8  283.32  5009.2  285.24    5018  290.92
  5223.9  290.87  5281.4  290.25  5302.4  287.94  5336.8  288.44  5359.5  287.87
    5679  299.28  5719.5  298.18  5966.1  303.78    6137  303.52  6171.9  304.08
#Mann= 14 ,-1 , 0
  3590.8     .08       0  3856.7      .1       0  4043.5     .08       0
  4085.6      .1       0  4354.9     .08       0  4380.8      .1       0
  4421.4     .08       0  4604.1     .05       0  4964.5     .12       0
  4995.8     .07       0  5001.8     .12       0  5336.8     .05       0
    5679     .08       0    6137      .1       0
Bank Sta=4977.8,5018
XS Rating Curve= 0 ,0
Exp/Cntr=0.3,0.1

Type RM Length L Ch R = 1 ,96060   ,178,178,178
BEGIN DESCRIPTION:
CARTERS CREEK 47.1
END DESCRIPTION:
XS GIS Cut Line= 4
      3554736.36     10235902.84       3553946.4     10235128.08
      3553438.59     10234785.19       3552939.5     10234750.47
#Sta/Elev= 30
  3353.9  304.01  3428.5  304.07    3570  300.67  3605.3  298.06  3750.5  297.89
  3780.2  296.45  3883.6  296.59  3926.4  296.64  3994.1   294.4  4072.6  295.67
    4283  293.62    4365  293.25  4416.1  292.69  4597.8  287.86  4716.3  288.41
  4791.3  287.74    4806  285.86  4943.8  285.93  4964.8  280.71  5012.7  280.27
  5015.5  279.77  5018.7  280.27  5047.6  282.34  5066.7     288  5099.7  294.41
  5149.8  294.67    5230  301.56  5337.8  305.24  5487.5  304.79  5573.4   303.8
#Mann= 15 ,-1 , 0
  3353.9      .1       0  3750.5     .08       0  3780.2     .05       0
  3883.6     .08       0  3926.4      .1       0  4072.6     .08       0
    4283     .05       0    4365     .08       0  4416.1     .12       0
  4597.8     .08       0  4716.3     .12       0  5012.7     .07       0
  5018.7     .12       0  5047.6     .05       0  5487.5     .08       0
Bank Sta=4943.8,5066.7
XS Rating Curve= 0 ,0
Exp/Cntr=0.3,0.1

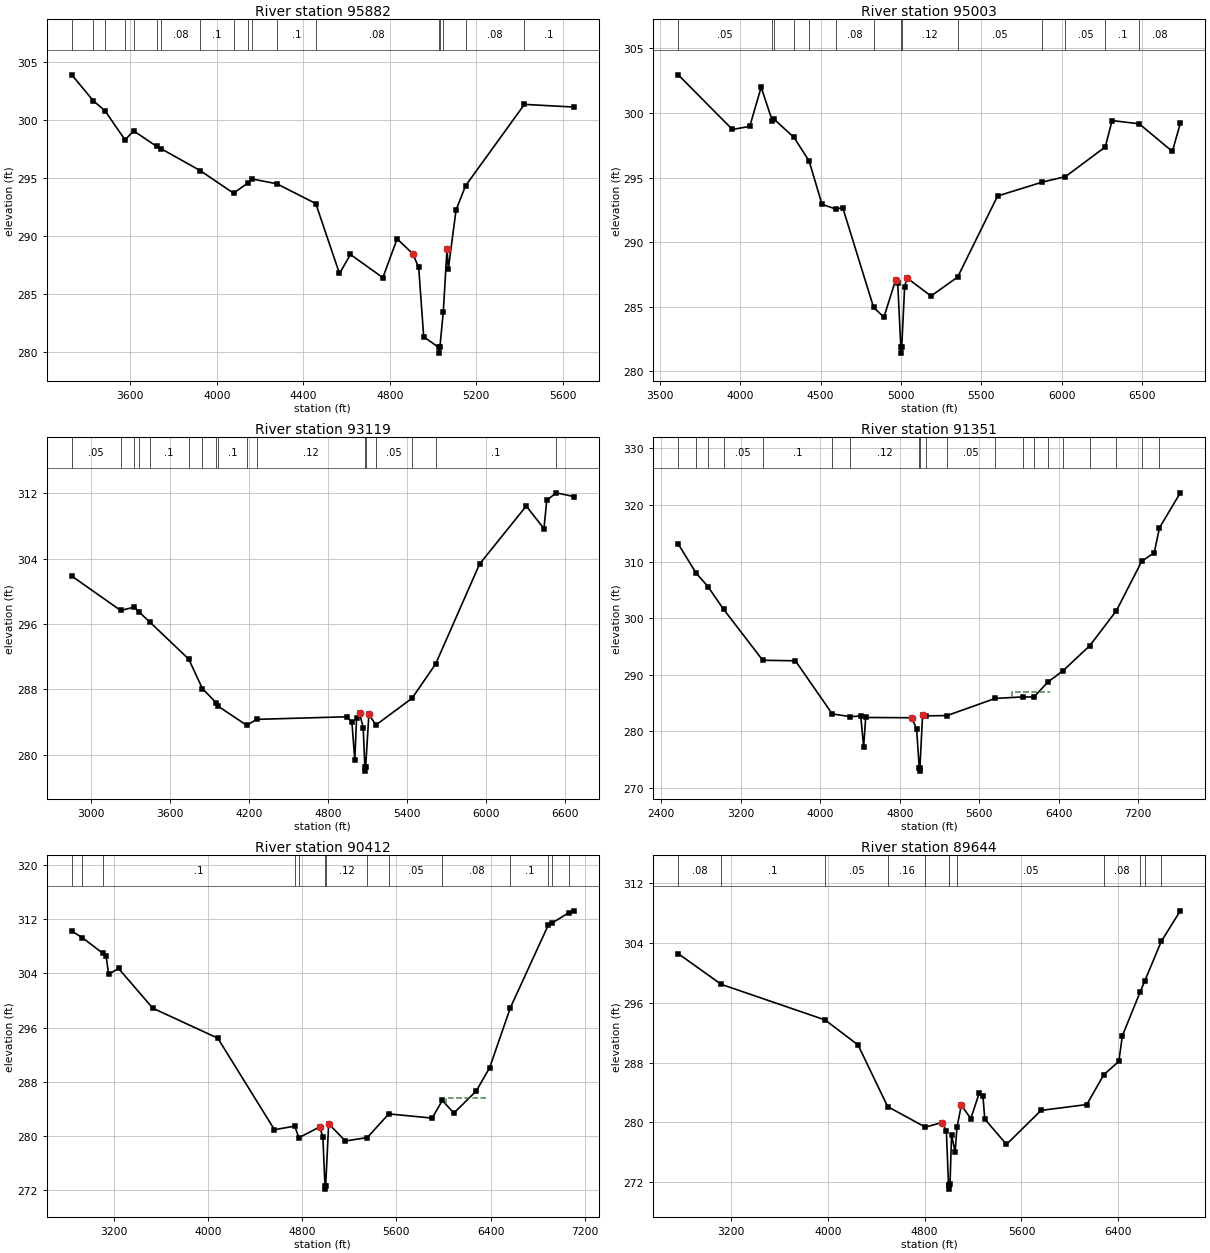
Type RM Length L Ch R = 1 ,95882   ,879,879,879
BEGIN DESCRIPTION:
CARTERS CREEK 47.0
END DESCRIPTION:
XS GIS Cut Line= 4
      3554857.83      10235785.6      3553989.81     10234943.61
      3553481.99     10234600.73      3552982.84     10234566.01
#Sta/Elev= 30
  3328.9  303.92  3428.1  301.69  3482.9  300.81  3575.2  298.31  3615.3  299.08
  3722.3  297.74  3742.7  297.54  3922.7  295.66  4077.1  293.71  4145.2  294.61
  4163.5  294.93  4277.7  294.52  4457.7  292.81  4567.1  286.78    4618  288.42
  4767.9  286.42  4833.8  289.77  4905.8  288.49  4933.6  287.31  4956.7  281.32
  5025.6  280.41  5028.4  279.91  5031.6  280.41  5047.3  283.45  5064.6  288.88
  5070.6  287.17  5106.6  292.27  5150.4  294.35  5422.7  301.37  5651.3  301.14
#Mann= 18 ,-1 , 0
  3328.9      .1       0  3428.1     .05       0  3482.9      .1       0
  3575.2     .08       0  3615.3      .1       0  3722.3     .05       0
  3742.7     .08       0  3922.7      .1       0  4077.1     .08       0
  4145.2      .1       0  4163.5     .08       0  4277.7      .1       0
  4457.7     .08       0  5025.6     .07       0  5031.6     .08       0
  5047.3     .05       0  5150.4     .08       0  5422.7      .1       0
Bank Sta=4905.8,5064.6
XS Rating Curve= 0 ,0
Exp/Cntr=0.3,0.1

Type RM Length L Ch R = 1 ,95003   ,1884,1884,1884
BEGIN DESCRIPTION:
CARTERS CREEK 46.0
END DESCRIPTION:
XS GIS Cut Line= 3
       3555439.4     10235297.18      3553855.23     10234094.95
      3552779.05     10234451.78
#Sta/Elev= 30
  3614.5  302.96  3951.3  298.73  4059.4  298.97  4130.1     302    4199  299.42
  4209.3  299.54  4334.9  298.11  4428.6  296.28  4508.7  292.94  4594.8  292.57
  4637.6  292.68  4829.2  284.97  4893.5   284.2  4966.2  287.07  4979.5  286.86
  4998.6  281.92  5001.3  281.42  5004.6  281.92  5022.4  286.55    5037  287.24
  5186.7  285.84  5352.4  287.31  5600.6  293.58  5879.2  294.66  6022.6  295.08
  6270.5  297.38  6312.6  299.42  6481.3  299.17  6687.6  297.03    6737  299.21
#Mann= 14 ,-1 , 0
  3614.5     .05       0    4199     .08       0  4209.3      .1       0
  4334.9     .08       0  4428.6      .1       0  4594.8     .08       0
  4829.2     .12       0  4998.6     .07       0  5004.6     .12       0
  5352.4     .05       0  5879.2      .1       0  6022.6     .05       0
  6270.5      .1       0  6481.3     .08       0
Bank Sta=4966.2,5037
XS Rating Curve= 0 ,0
Exp/Cntr=0.3,0.1

Type RM Length L Ch R = 1 ,93119   ,1768,1768,1768
BEGIN DESCRIPTION:
CARTERS CREEK 45.0
END DESCRIPTION:
XS GIS Cut Line= 4
       3555418.6     10235210.41      3554887.35     10233351.03
      3554467.13     10233094.63       3553533.2      10232069.8
#Sta/Elev= 30
  2853.3  301.88  3224.8  297.67  3328.1  298.08  3362.2  297.51    3445  296.27
  3741.5  291.71  3844.9  288.11  3948.2  286.39  3963.3  285.96  4182.4  283.59
  4256.6  284.33  4944.4  284.65  4980.7  283.97  5002.5  279.31  5015.8  284.45
  5039.2  285.06  5066.4  283.31  5078.9  278.49  5081.6  277.99  5084.9  278.49
  5109.5  284.94  5162.8  283.64  5437.9  286.93  5616.1  291.11  5950.3  303.36
  6304.3  310.46  6438.8   307.7  6460.4  311.17  6532.4  312.08  6665.9  311.62
#Mann= 17 ,-1 , 0
  2853.3     .05       0  3224.8     .16       0  3328.1     .05       0
  3362.2     .08       0    3445      .1       0  3741.5     .08       0
  3844.9     .05       0  3948.2     .16       0  3963.3      .1       0
  4182.4     .16       0  4256.6     .12       0  5078.9     .07       0
  5084.9     .12       0  5162.8     .05       0  5437.9     .08       0
  5616.1      .1       0  6532.4     .05       0
Bank Sta=5039.2,5109.5
XS Rating Curve= 0 ,0
Exp/Cntr=0.3,0.1

Type RM Length L Ch R = 1 ,91351   ,939,939,939
BEGIN DESCRIPTION:
CARTERS CREEK 44.0
END DESCRIPTION:
XS GIS Cut Line= 5
      3557402.95      10234720.8      3556142.56     10233798.94
      3555679.02     10233449.99      3555662.19     10232901.08
      3553842.08     10231391.62
#Sta/Elev= 30
    2570  313.12    2750  307.97  2868.9   305.6  3026.3  301.59  3420.8  292.58
    3750  292.48  4120.6   283.1  4296.5  282.63  4407.6  282.71  4436.7  277.27
  4457.5  282.47  4920.2  282.42  4970.2  280.45  4997.2  273.49    5000  272.99
  5003.2  273.49  5030.2  282.85  5063.3  282.75  5277.7  282.81  5762.4  285.84
  6038.6   286.1  6151.7  286.08  6292.1  288.74  6441.9  290.68  6714.1  295.16
  6981.8  301.33  7236.3  310.04  7363.1   311.6  7415.6  315.98  7625.5  322.16
#Mann= 20 ,-1 , 0
    2570     .08       0    2750     .05       0  2868.9      .1       0
  3026.3     .05       0  3420.8      .1       0  4120.6      .1       0
  4296.5     .12       0  4997.2     .07       0  5003.2     .12       0
  5063.3     .16       0  5277.7     .05       0  5762.4     .08       0
  6038.6     .05       0  6151.7     .08       0  6292.1      .1       0
  6441.9     .08       0  6714.1      .1       0  6981.8     .08       0
  7236.3      .1       0  7415.6     .08       0
#XS Ineff= 1 ,-1
 5934.09  6312.5  287.05
Permanent Ineff=
       F
Bank Sta=4920.2,5030.2
XS Rating Curve= 0 ,0
Exp/Cntr=0.3,0.1

Type RM Length L Ch R = 1 ,90412   ,768,768,768
BEGIN DESCRIPTION:
CARTERS CREEK 43.0
END DESCRIPTION:
XS GIS Cut Line= 3
      3557540.14     10234505.55      3555878.74     10232674.93
      3554692.93     10231331.95
#Sta/Elev= 30
  2843.5   310.2  2934.4  309.22  3107.1  306.94  3134.9  306.54  3156.6  303.85
    3241   304.7  3531.6  298.85  4083.7  294.43  4564.9  280.95  4736.5  281.48
  4772.5  279.77  4947.4  281.35  4975.8  279.94  4993.7   272.7  4996.5   272.2
  4999.7   272.7  5025.1  281.83    5167  279.29  5352.5  279.79  5535.8  283.28
  5903.8  282.66  5990.6  285.26  6087.9   283.4  6279.4  286.67  6392.3   290.1
    6568  298.91  6891.4  311.14    6923   311.4  7065.8  312.93  7107.2  313.19
#Mann= 14 ,-1 , 0
  2843.5     .08       0  2934.4     .05       0  3107.1      .1       0
  4736.5     .16       0  4772.5     .12       0  4993.7     .07       0
  4999.7     .12       0  5352.5     .16       0  5535.8     .05       0
  5990.6     .08       0    6568      .1       0  6891.4     .08       0
    6923     .05       0  7065.8     .08       0
#XS Ineff= 1 ,-1
 6019.32 6363.64  285.64
Permanent Ineff=
       F
Bank Sta=4947.4,5025.1
XS Rating Curve= 0 ,0
Exp/Cntr=0.3,0.1

Type RM Length L Ch R = 1 ,89644   ,1811,1811,1811
BEGIN DESCRIPTION:
CARTERS CREEK 40.0
END DESCRIPTION:
XS GIS Cut Line= 3
      3557852.63     10234297.21      3556519.29     10232269.43
       3555142.1     10231241.64
#Sta/Elev= 30
    2766  302.56  3120.9  298.46  3977.9   293.7  4250.5  290.35    4495  282.11
  4806.1  279.36  4943.4  279.98  4979.6  278.91  4997.7  271.57  5000.4  271.07
  5003.7  271.57  5009.8   271.7  5022.7  278.32  5051.9  276.06  5067.4  279.32
  5103.1  282.29  5181.4  280.51  5252.8  283.99    5282  283.49  5296.6  280.44
  5475.9  277.05  5761.5   281.6  6138.9  282.38    6280  286.38  6403.6  288.15
  6432.8  291.57    6579  297.41  6618.5  298.93  6753.9   304.2  6911.3  308.29
#Mann= 12 ,-1 , 0
    2766     .08       0  3120.9      .1       0  3977.9     .05       0
    4495     .16       0  4806.1     .12       0  4997.7     .07       0
  5003.7     .12       0  5067.4     .05       0    6280     .08       0
    6579      .1       0  6618.5     .08       0  6753.9      .1       0
Bank Sta=4943.4,5103.1
XS Rating Curve= 0 ,0
Exp/Cntr=0.3,0.1

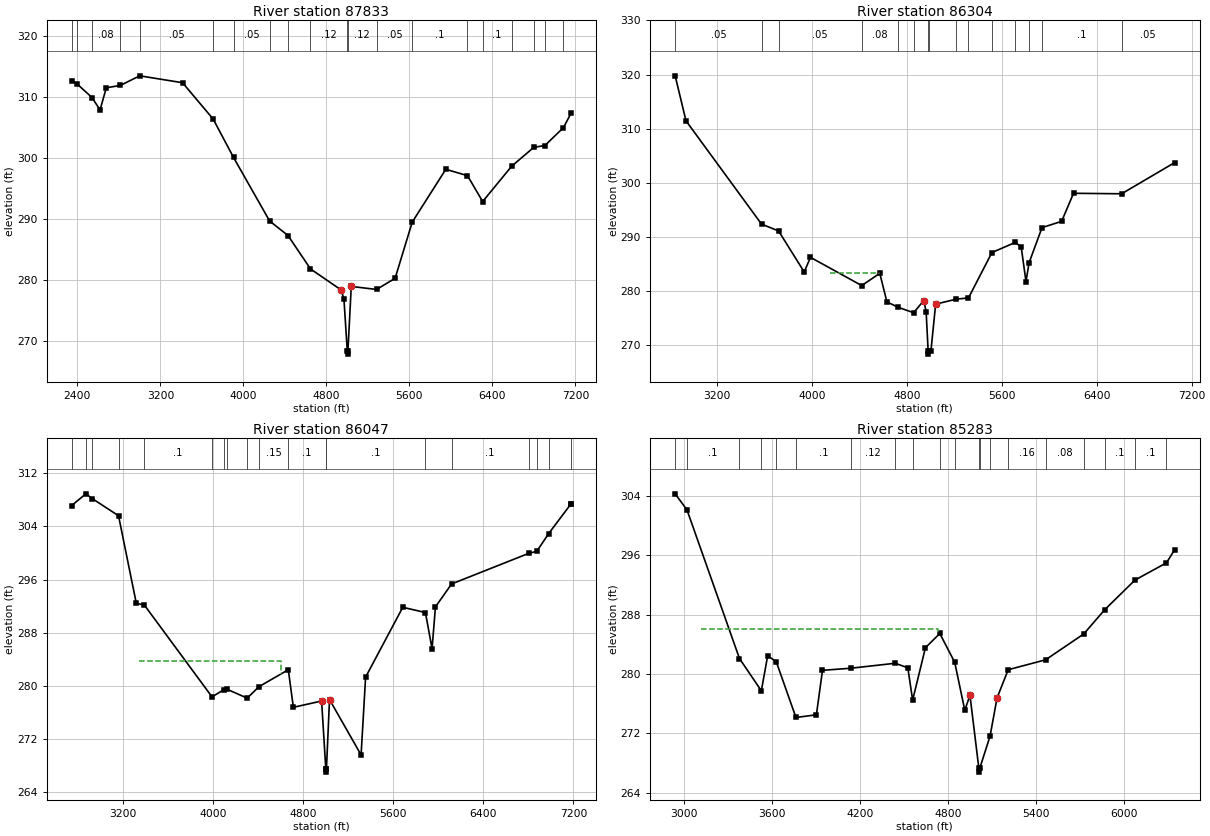
Type RM Length L Ch R = 1 ,87833   ,1529,1529,1529
BEGIN DESCRIPTION:
CARTERS CREEK 39.0
END DESCRIPTION:
XS GIS Cut Line= 4
      3559505.36     10232665.26      3558442.91     10232595.82
      3557206.79     10231324.99      3555409.42      10230506.1
#Sta/Elev= 30
  2344.8   312.6  2395.2   312.1  2540.8  309.85  2618.6  307.82  2678.8  311.44
  2814.7  311.83  3000.8   313.4  3413.7  312.27  3708.5  306.32  3905.1  300.03
  4252.9  289.62  4430.3  287.24  4646.7  281.77  4940.5  278.35  4968.8  276.88
  5001.3  268.32    5004  267.82  5007.3  268.32  5039.5  278.91  5283.1  278.41
  5462.2  280.24  5626.7  289.43  5950.7  298.09  6159.6  297.05    6306  292.81
  6585.9  298.61  6799.1  301.69  6905.6  301.98  7084.4  304.92  7157.5  307.27
#Mann= 20 ,-1 , 0
  2344.8     .16       0  2395.2     .05       0  2540.8     .08       0
  2814.7     .05       0  3000.8     .05       0  3708.5     .08       0
  3905.1     .05       0  4252.9     .08       0  4430.3     .16       0
  4646.7     .12       0  5001.3     .07       0  5007.3     .12       0
  5283.1     .05       0  5626.7      .1       0  6159.6     .08       0
    6306      .1       0  6585.9     .05       0  6799.1     .08       0
  6905.6     .05       0  7084.4      .1       0
Bank Sta=4940.5,5039.5
XS Rating Curve= 0 ,0
Exp/Cntr=0.3,0.1

Type RM Length L Ch R = 1 ,86304   ,257,257,257
BEGIN DESCRIPTION:
CARTERS CREEK 37.0
END DESCRIPTION:
XS GIS Cut Line= 3
      3559788.96     10231350.83      3558532.02     10230621.67
      3555781.98     10230503.61
#Sta/Elev= 30
  2849.8  319.78  2941.1  311.47  3577.2   292.4    3721  291.13  3936.5  283.56
  3989.5  286.26    4421  281.05  4573.1  283.31  4633.1  278.04  4728.2  277.03
  4857.9  276.04  4943.4  278.28  4963.4  276.25  4980.5  268.89  4983.2  268.39
  4986.5  268.89  5003.5   268.9  5043.5  277.62  5217.2  278.54  5320.1  278.77
  5517.4  287.15  5714.7  289.02  5764.2  288.16  5804.2   281.8  5830.4  285.26
  5939.2  291.75  6104.5  292.91  6204.6  298.09  6609.9     298  7055.5  303.75
#Mann= 15 ,-1 , 0
  2849.8     .05       0  3577.2      .1       0    3721     .05       0
    4421     .08       0  4728.2      .1       0  4857.9     .12       0
  4980.5     .07       0  4986.5     .12       0  5217.2      .1       0
  5320.1     .05       0  5517.4     .08       0  5714.7     .16       0
  5830.4     .08       0  5939.2      .1       0  6609.9     .05       0
#XS Ineff= 1 ,-1
 4154.55 4567.05  283.43
Permanent Ineff=
       F
Bank Sta=4943.4,5043.5
XS Rating Curve= 0 ,0
Exp/Cntr=0.3,0.1

Type RM Length L Ch R = 1 ,86047   ,764,764,764
BEGIN DESCRIPTION:
CARTERS CREEK 36.0
END DESCRIPTION:
XS GIS Cut Line= 5
      3560080.68     10230663.35      3558920.91     10230232.78
      3558379.24      10230392.5      3557733.41     10230343.89
      3555748.46     10230276.38
#Sta/Elev= 30
  2743.1  307.14  2869.6   308.9  2926.6  308.18  3159.6   305.6  3317.6  292.42
  3388.3  292.18    3990  278.35  4094.1  279.42  4125.4  279.48  4302.4  278.16
  4406.6  279.88  4667.5  282.44  4712.5  276.78  4963.3  277.73  5000.4  267.53
  5003.1  267.03  5006.4  267.53  5033.5  277.95    5314  269.61    5354  281.32
  5684.2  291.83  5885.6  291.04  5944.3  285.59  5974.4  291.89  6117.9  295.34
  6802.3  299.94  6874.4  300.25  6979.3   302.9  7176.6  307.35  7178.7  307.35
#Mann= 19 ,-1 , 0
  2743.1     .08       0  2869.6      .1       0  2926.6     .08       0
  3159.6     .05       0  3388.3      .1       0    3990     .08       0
  4094.1      .1       0  4125.4     .08       0  4302.4      .1       0
  4406.6     .15       0  4667.5      .1       0  5000.4     .07       0
  5006.4      .1       0  5885.6     .08       0  6117.9      .1       0
  6802.3     .08       0  6874.4      .1       0  6979.3     .15       0
  7176.6     .08       0
#XS Ineff= 1 ,-1
 3343.18 4601.14  283.72
Permanent Ineff=
       F
Bank Sta=4963.3,5033.5
XS Rating Curve= 0 ,0
Exp/Cntr=0.3,0.1

Type RM Length L Ch R = 1 ,85283   ,363,363,363
BEGIN DESCRIPTION:
CARTERS CREEK 34.1
END DESCRIPTION:
XS GIS Cut Line= 4
      3559879.21     10230218.88      3558018.13     10229684.17
      3557587.58       10229330.       3556727.6     10229012.48
#Sta/Elev= 30
  2937.9  304.27  3018.6  302.11  3377.1  282.09  3526.5  277.74  3569.6  282.45
    3628  281.68  3762.8  274.15  3902.5  274.51  3944.1   280.5  4135.9  280.78
  4440.6  281.45  4526.8  280.84  4559.8  276.49  4647.2  283.55  4745.3  285.46
  4846.9  281.59    4916  275.12  4951.2  277.14    5012  267.29  5014.8  266.79
    5018  267.29  5088.6  271.65  5136.3  276.79  5212.4  280.58  5468.1  281.92
  5728.5   285.4  5870.4  288.64  6077.8  292.65  6293.4  294.98  6348.5  296.73
#Mann= 20 ,-1 , 0
  2937.9     .16       0  3018.6      .1       0  3377.1     .05       0
  3526.5     .08       0    3628      .1       0  3762.8      .1       0
  4135.9     .12       0  4440.6      .1       0  4559.8      .1       0
  4745.3     .08       0  4846.9     .12       0    5012     .07       0
    5018     .12       0  5088.6     .12       0  5212.4     .16       0
  5468.1     .08       0  5728.5     .08       0  5870.4      .1       0
  6077.8      .1       0  6293.4     .15       0
#XS Ineff= 1 ,-1
 3115.91 4734.09  286.03
Permanent Ineff=
       F
Bank Sta=4951.2,5136.3
XS Rating Curve= 0 ,0
Exp/Cntr=0.3,0.1