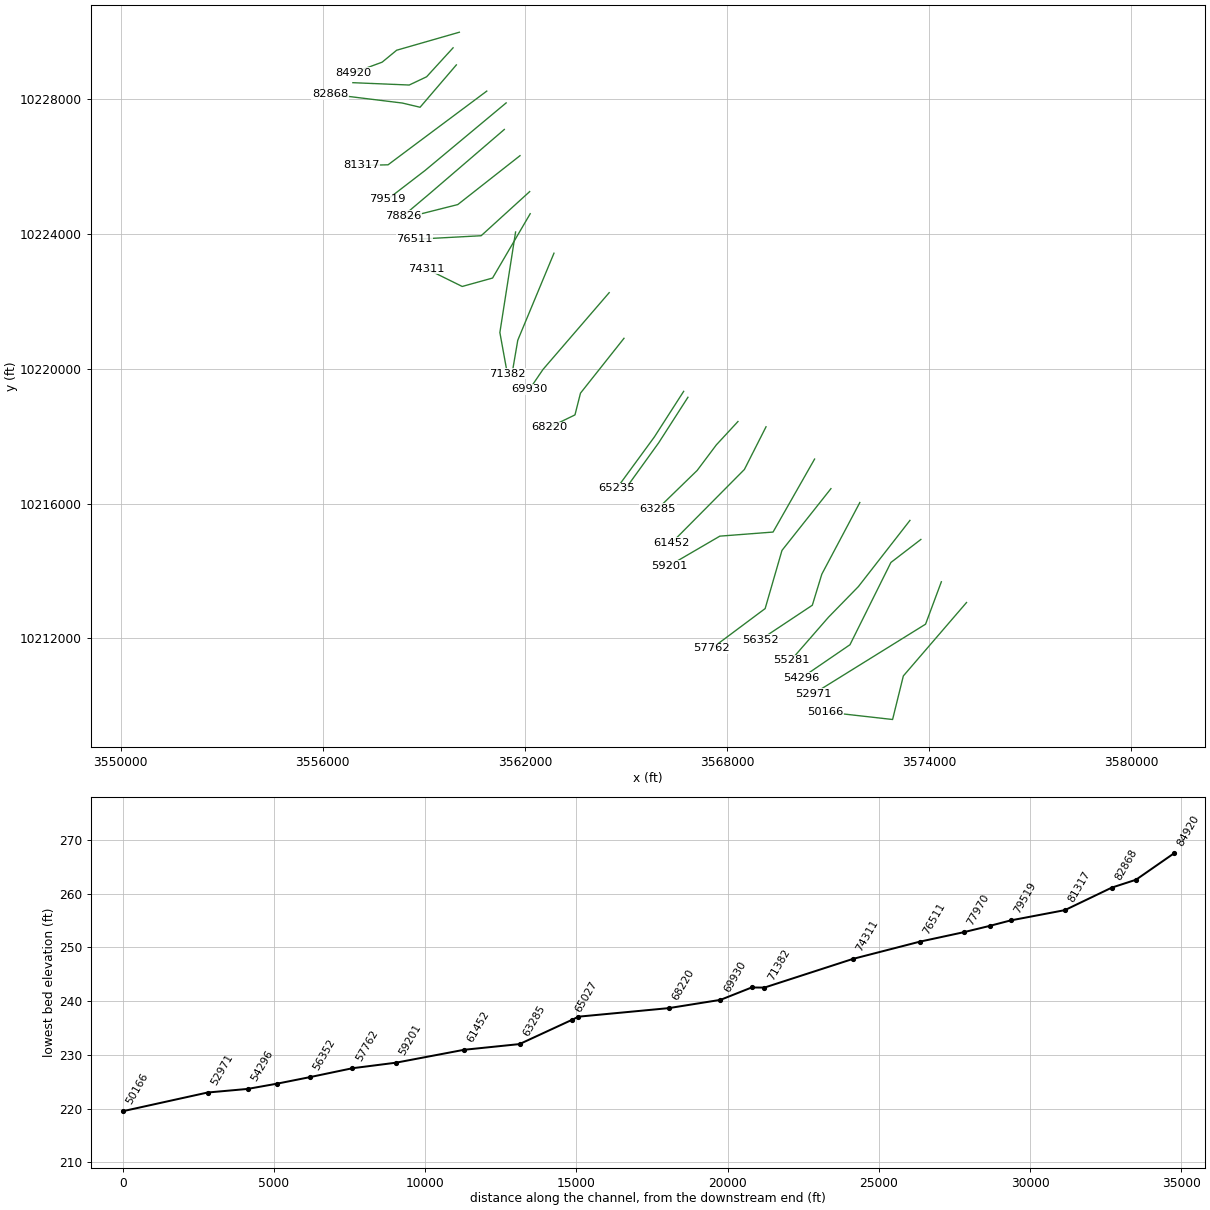
HEC-RAS study CARTERS CREEK.prj: CARTERS CREEK Base Level Engineering

--- CARTERS CREEK.g01 (geometry) --- (continued)

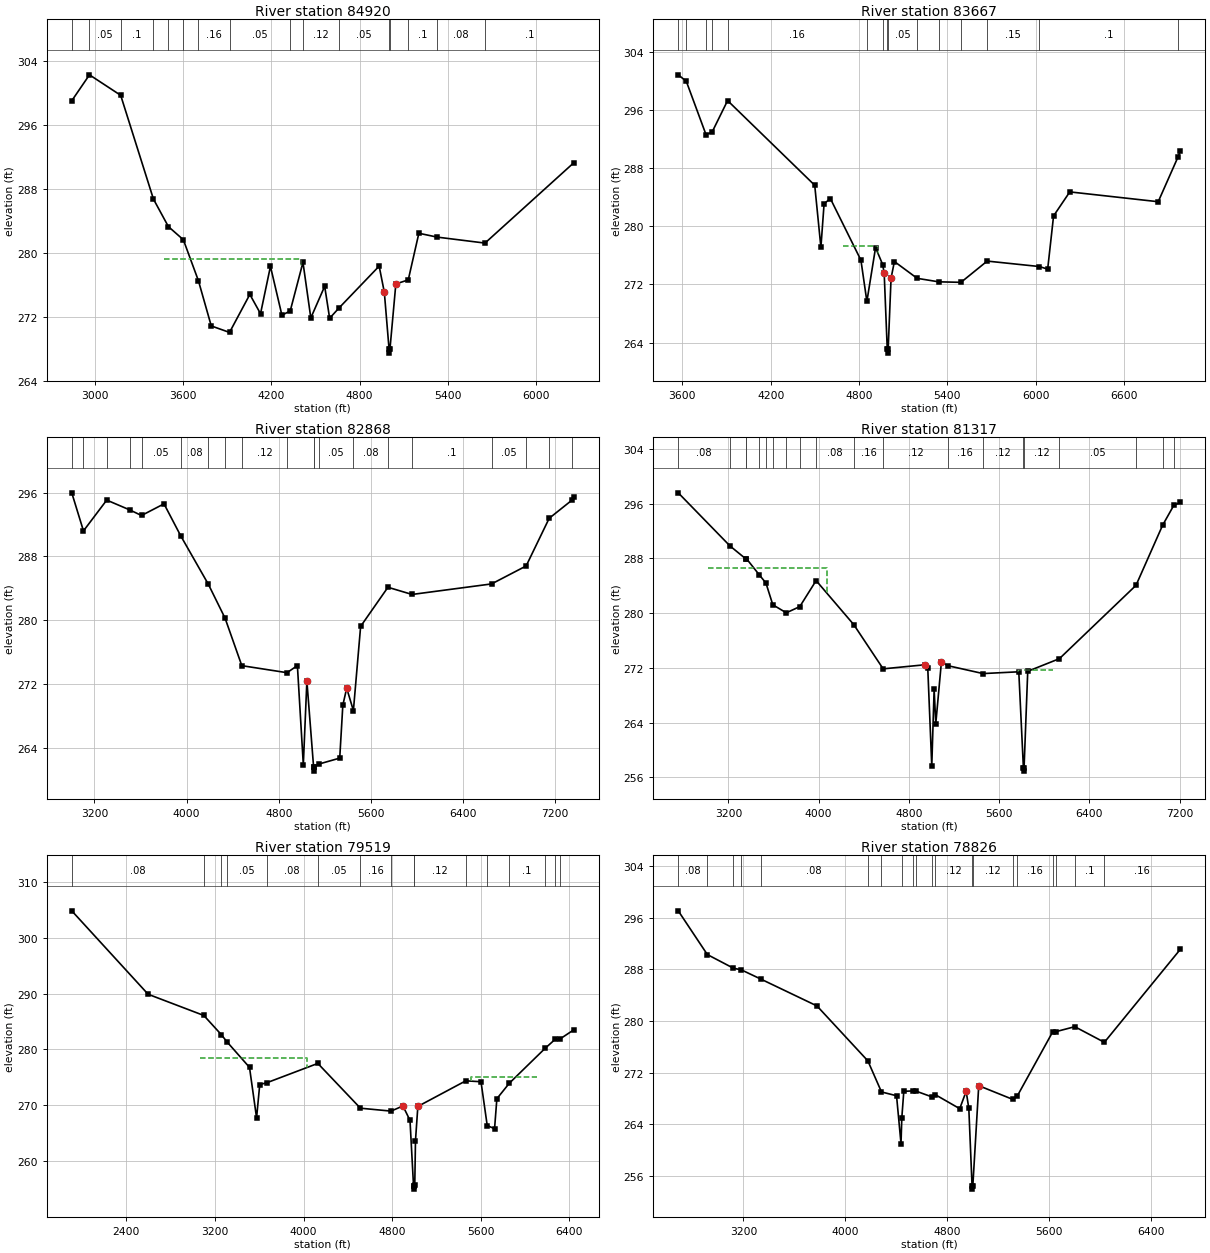
Type RM Length L Ch R = 1 ,84920   ,1253,1253,1253
BEGIN DESCRIPTION:
CARTERS CREEK 34.0
END DESCRIPTION:
XS GIS Cut Line= 4
      3560052.87     10229989.73      3558191.74       10229455.
      3557761.19     10229100.83      3556901.26     10228783.33
#Sta/Elev= 30
  2844.2  299.02  2964.4  302.26  3176.5   299.7    3399  286.72  3500.6  283.28
  3602.1  281.64  3704.8   276.5  3791.8  270.86  3915.8  270.05  4053.8   274.8
  4126.4  272.39  4193.8  278.31  4271.7   272.2  4328.2  272.74  4414.7  278.81
  4468.1  271.86  4562.2  275.82  4595.9  271.82  4658.7  273.09  4932.3  278.34
  4967.4  275.07  4999.6  267.96  5002.3  267.46  5005.6  267.96  5045.6  276.11
    5130  276.62    5202  282.45  5325.1  281.97  5651.2  281.22  6254.8  291.27
#Mann= 16 ,-1 , 0
  2844.2     .08       0  2964.4     .05       0  3176.5      .1       0
    3399     .05       0  3500.6      .1       0  3602.1     .08       0
  3704.8     .16       0  3915.8     .05       0  4328.2     .08       0
  4414.7     .12       0  4658.7     .05       0  4999.6     .04       0
  5005.6     .05       0    5130      .1       0  5325.1     .08       0
  5651.2      .1       0
#XS Ineff= 1 ,-1
 3468.18 4404.55  279.27
Permanent Ineff=
       F
Bank Sta=4967.4,5045.6
XS Rating Curve= 0 ,0
Exp/Cntr=0.3,0.1

Type RM Length L Ch R = 1 ,83667   ,799,799,799
BEGIN DESCRIPTION:
CARTERS CREEK 33.0
END DESCRIPTION:
XS GIS Cut Line= 4
      3559866.55     10229526.41      3559080.89     10228667.05
      3558564.69     10228422.24      3556892.11     10228491.64
#Sta/Elev= 30
  3571.9  300.81  3626.5  299.93  3760.5  292.59  3801.8  292.94  3907.1  297.27
  4498.8  285.63  4540.8   277.1  4562.4  283.09  4604.9  283.81  4812.6  275.33
    4853  269.66    4912  277.06  4960.3  274.73  4970.6  273.51  4991.5  263.06
  4994.2  262.56  4997.5  263.06  5017.2  272.86  5039.9  275.15  5194.5  272.84
  5340.4  272.36    5492  272.29    5670  275.21  6025.3  274.46  6080.8   274.1
  6120.9  281.42    6231  284.72  6831.5  283.37  6966.6  289.55  6981.6  290.35
#Mann= 15 ,-1 , 0
  3571.9     .05       0  3626.5     .08       0  3760.5      .1       0
  3801.8     .08       0  3907.1     .16       0    4853     .12       0
  4960.3     .05       0  4991.5     .04       0  4997.5     .05       0
  5194.5     .12       0  5340.4     .05       0    5492      .1       0
    5670     .15       0  6025.3      .1       0  6966.6     .05       0
#XS Ineff= 1 ,-1
 4693.18 4929.83  277.33
Permanent Ineff=
       F
Bank Sta=4970.6,5017.2
XS Rating Curve= 0 ,0
Exp/Cntr=0.3,0.1

Type RM Length L Ch R = 1 ,82868   ,1551,1551,1551
BEGIN DESCRIPTION:
CARTERS CREEK 32.0
END DESCRIPTION:
XS GIS Cut Line= 4
      3559963.73     10229019.42      3558887.35     10227762.49
      3558359.57     10227887.49      3556215.43     10228151.17
#Sta/Elev= 30
  3003.5  295.96    3105  291.19  3306.9  295.05  3506.7  293.82  3608.7  293.12
    3804  294.58  3949.2  290.57  4189.1   284.5  4334.2  280.25  4479.3  274.31
  4871.7  273.43  4961.7  274.32  5013.1   261.9    5044  272.38  5102.4   261.6
  5105.1   261.1  5108.4   261.6  5146.5  261.98  5329.1  262.73    5356  269.36
  5389.6  271.49  5447.7  268.68  5510.5  279.23  5747.5  284.13  5956.9  283.23
  6647.2  284.55    6947   286.8    7147  292.77  7346.9  295.07    7361  295.44
#Mann= 20 ,-1 , 0
  3003.5     .08       0    3105      .1       0  3306.9     .16       0
  3506.7     .16       0  3608.7     .05       0  3949.2     .08       0
  4189.1     .08       0  4334.2     .16       0  4479.3     .12       0
  4871.7     .12       0  5102.4     .04       0  5108.4     .12       0
  5146.5     .05       0  5447.7     .08       0  5747.5     .15       0
  5956.9      .1       0  6647.2     .05       0    6947      .1       0
    7147     .15       0  7346.9      .1       0
Bank Sta=5044,5389.6
XS Rating Curve= 0 ,0
Exp/Cntr=0.3,0.1

Type RM Length L Ch R = 1 ,81317   ,1798,1798,1798
BEGIN DESCRIPTION:
CARTERS CREEK 32.1
END DESCRIPTION:
XS GIS Cut Line= 4
      3560866.55     10228241.68      3558823.81     10226717.96
      3557935.96     10226054.15      3557143.08     10226035.15
#Sta/Elev= 30
  2755.2  297.59  3214.2  289.82    3354  287.94  3359.1  287.98  3473.6   285.6
  3532.6   284.4  3593.3  281.23  3712.9  280.05  3832.6  280.96  3977.3  284.76
  4311.2  278.32  4571.6  271.86    4944  272.46    4967  271.94  5002.4  257.66
  5023.3  268.88  5037.9  263.85  5087.9  272.88  5142.9  272.33  5456.9  271.17
  5773.7  271.43  5814.5  257.41  5817.2  256.91  5820.5  257.41  5852.9   271.5
  6133.8  273.35  6812.7  284.07  7048.3  292.85  7146.9  295.74  7205.3  296.19
#Mann= 20 ,-1 , 0
  2755.2     .08       0  3214.2      .1       0    3354     .05       0
  3359.1      .1       0  3473.6     .05       0  3532.6     .08       0
  3593.3     .05       0  3712.9     .08       0  3832.6      .1       0
  3977.3     .08       0  4311.2     .16       0  4571.6     .12       0
  5142.9     .16       0  5456.9     .12       0  5814.5     .07       0
  5820.5     .12       0  6133.8     .05       0  6812.7     .16       0
  7048.3     .05       0  7146.9      .1       0
#XS Ineff= 2 ,-1
 3022.73 4076.14  286.67 5767.05 6077.27271.6527
Permanent Ineff=
       F       F
Bank Sta=4944,5087.9
XS Rating Curve= 0 ,0
Exp/Cntr=0.3,0.1

Type RM Length L Ch R = 1 ,79519   ,693,693,693
BEGIN DESCRIPTION:
CARTERS CREEK 31.0
END DESCRIPTION:
XS GIS Cut Line= 3
      3561442.13     10227891.66      3559042.11     10225891.64
      3557926.04     10225033.13
#Sta/Elev= 30
  1908.1  304.82  2597.4  289.88  3100.4  286.08  3258.1  282.65  3307.6   281.4
  3512.5  276.79  3576.3  267.75  3604.9  273.72  3667.7  274.03  4129.2   277.5
  4513.8  269.48    4790  268.96  4897.5  269.88  4961.3   267.3  4993.4  255.49
  4996.2  254.99  4999.4  255.49  5004.2  255.64  5010.8  263.69  5032.2   269.8
  5464.7  274.38  5602.2  274.22  5658.4  266.37  5724.6  265.81  5745.4  271.18
  5858.2  273.96  6180.4  280.19  6271.4  281.81  6311.9  281.83  6440.3  283.52
#Mann= 16 ,-1 , 0
  1908.1     .08       0  3100.4      .1       0  3258.1     .08       0
  3307.6     .05       0  3667.7     .08       0  4129.2     .05       0
  4513.8     .16       0    4790     .12       0  4993.4     .07       0
  4999.4     .12       0  5464.7     .05       0  5658.4     .16       0
  5858.2      .1       0  6180.4     .05       0  6271.4     .16       0
  6311.9     .05       0
#XS Ineff= 2 ,-1
 3065.91 4030.68  278.46 5513.64 6106.82  275.01
Permanent Ineff=
       F       F
Bank Sta=4897.5,5032.2
XS Rating Curve= 0 ,0
Exp/Cntr=0.3,0.1

Type RM Length L Ch R = 1 ,78826   ,856,856,856
BEGIN DESCRIPTION:
CARTERS CREEK 29.0
END DESCRIPTION:
XS GIS Cut Line= 3
      3561387.33     10227102.74      3559172.07     10225199.99
      3558392.12     10224541.65
#Sta/Elev= 30
    2688  297.04  2916.6  290.27  3121.1  288.16  3182.7  287.91  3333.9   286.5
  3777.1  282.32  4176.4  273.82  4283.3  269.01  4401.5  268.42  4436.6  261.01
  4442.9     265  4458.5  269.11    4534  269.17  4554.1  269.14    4680  268.24
  4705.6  268.59  4897.5  266.42    4948  269.11  4968.8  266.47  4994.3  254.47
  4997.1  253.97  5000.3  254.47  5046.7  269.98  5313.6  267.86  5349.2  268.38
    5627   278.3  5654.3  278.35  5800.6  279.11  6032.8  276.69  6628.9  291.08
#Mann= 20 ,-1 , 0
    2688     .08       0  2916.6      .1       0  3121.1     .08       0
  3182.7     .05       0  3333.9     .08       0  4176.4     .12       0
  4283.3     .05       0  4442.9     .12       0    4534     .05       0
  4554.1     .12       0    4680     .16       0  4705.6     .12       0
  4994.3     .07       0  5000.3     .12       0  5313.6     .05       0
  5349.2     .16       0    5627      .1       0  5654.3     .16       0
  5800.6      .1       0  6032.8     .16       0
Bank Sta=4948,5046.7
XS Rating Curve= 0 ,0
Exp/Cntr=0.3,0.1

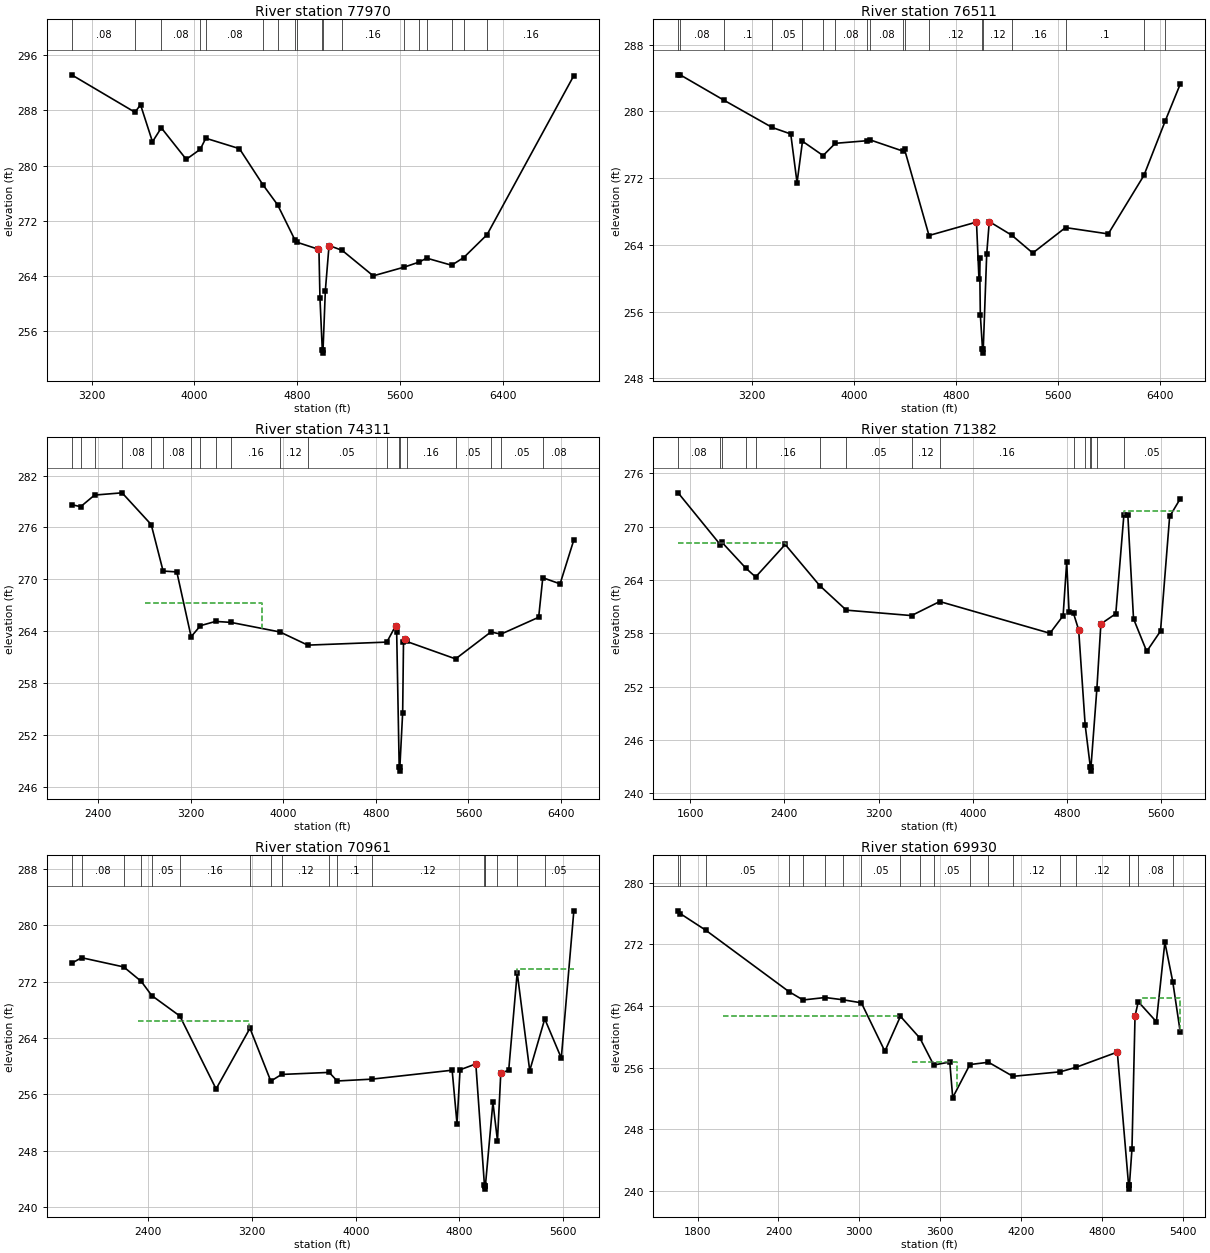
Type RM Length L Ch R = 1 ,77970   ,1459,1459,1459
BEGIN DESCRIPTION:
CARTERS CREEK 28.0
END DESCRIPTION:
XS GIS Cut Line= 3
      3561852.59     10226324.96      3560005.41      10224873.6
      3558492.12     10224491.65
#Sta/Elev= 30
  3044.7  293.17  3537.8  287.74    3581  288.83    3674  283.46  3742.7  285.48
    3937  280.91  4045.6  282.36  4089.1  283.97  4350.9  282.46  4533.6  277.23
  4648.3  274.31    4783  269.22  4799.9  268.88  4963.7  267.88  4970.1  267.73
  4978.1  260.74    4996   253.3  4998.7   252.8    5002   253.3  5019.8  261.85
  5048.7  268.41  5150.6  267.71  5392.8  264.01  5634.6  265.28  5750.4  266.01
  5808.6  266.58  6002.8  265.55  6097.2  266.66  6278.8  269.98  6954.6  293.06
#Mann= 18 ,-1 , 0
  3044.7     .08       0  3537.8      .1       0  3742.7     .08       0
  4045.6      .1       0  4089.1     .08       0  4533.6      .1       0
  4648.3     .08       0    4783     .05       0  4799.9     .12       0
    4996     .07       0    5002     .12       0  5150.6     .16       0
  5634.6     .05       0  5750.4     .16       0  5808.6     .05       0
  6002.8     .16       0  6097.2      .1       0  6278.8     .16       0
Bank Sta=4963.7,5048.7
XS Rating Curve= 0 ,0
Exp/Cntr=0.3,0.1

Type RM Length L Ch R = 1 ,76511   ,2200,2200,2200
BEGIN DESCRIPTION:
CARTERS CREEK 26.0
END DESCRIPTION:
XS GIS Cut Line= 3
      3562140.41     10225258.95      3560700.14      10223948.8
      3558718.82     10223842.27
#Sta/Elev= 30
  2625.5  284.34  2641.4  284.39  2981.6  281.37  3361.8  278.08  3507.2   277.3
  3556.5  271.46  3599.1  276.43  3760.4  274.71  3855.9  276.18  4103.2  276.49
  4126.8   276.6  4388.5  275.23    4398  275.45  4589.5  265.13  4961.1  266.74
  4980.7   259.9  4985.7  262.45  4991.2  255.65  5008.2  251.53  5010.9  251.03
  5014.2  251.53  5041.2  262.92  5061.3   266.8  5238.5  265.15  5401.7  263.03
  5658.1  266.08  5992.6  265.32  6271.8  272.33    6440  278.91  6556.7   283.3
#Mann= 18 ,-1 , 0
  2625.5      .1       0  2641.4     .08       0  2981.6      .1       0
  3361.8     .05       0  3599.1     .08       0  3760.4      .1       0
  3855.9     .08       0  4103.2     .05       0  4126.8     .08       0
  4388.5     .05       0    4398     .16       0  4589.5     .12       0
  5008.2     .07       0  5014.2     .12       0  5238.5     .16       0
  5658.1      .1       0  6271.8     .16       0    6440     .05       0
Bank Sta=4961.1,5061.3
XS Rating Curve= 0 ,0
Exp/Cntr=0.3,0.1

Type RM Length L Ch R = 1 ,74311   ,2929,2929,2929
BEGIN DESCRIPTION:
CARTERS CREEK 25.0
END DESCRIPTION:
XS GIS Cut Line= 4
      3562156.05     10224602.37      3561038.43     10222692.65
      3560137.82     10222443.09       3559065.4     10222971.72
#Sta/Elev= 30
  2168.5  278.63  2246.6   278.4  2366.5  279.74  2604.6     280  2856.6  276.33
  2959.4  270.96    3078  270.86  3201.6  263.37  3282.6  264.65  3412.8  265.14
  3544.7  265.03  3970.4  263.92  4210.3   262.4  4894.2  262.75  4969.7  264.62
  4979.3  263.91    5001  248.34  5003.8  247.84    5007  248.34  5031.1  254.61
  5038.3  262.76  5051.9  263.14  5066.5  262.82  5488.9  260.81    5794  263.92
  5881.5  263.67  6207.2  265.62  6242.9  270.19  6392.4  269.48  6511.4  274.56
#Mann= 20 ,-1 , 0
  2168.5      .1       0  2246.6      .1       0  2366.5     .08       0
  2604.6     .08       0  2856.6      .1       0  2959.4     .08       0
  3201.6     .05       0  3282.6     .08       0  3412.8     .05       0
  3544.7     .16       0  3970.4     .12       0  4210.3     .05       0
  4894.2     .12       0    5001     .07       0    5007     .12       0
  5066.5     .16       0  5488.9     .05       0    5794     .16       0
  5881.5     .05       0  6242.9     .08       0
#XS Ineff= 1 ,-1
 2806.82 3818.18  267.28
Permanent Ineff=
       F
Bank Sta=4969.7,5051.9
XS Rating Curve= 0 ,0
Exp/Cntr=0.3,0.1

Type RM Length L Ch R = 1 ,71382   ,421,421,421
BEGIN DESCRIPTION:
CARTERS CREEK 24.0
END DESCRIPTION:
XS GIS Cut Line= 3
      3561722.02     10224059.81      3561255.44      10221075.9
      3561477.38     10219852.64
#Sta/Elev= 30
  1498.7  273.81    1858  267.96  1868.7  268.27    2074  265.33  2156.7  264.34
  2407.8     268  2700.1  263.38  2926.7  260.61  3480.3     260  3719.6  261.58
  4655.3  258.01  4767.1  259.98  4797.6  266.03  4817.9  260.36  4855.5  260.25
  4899.2  258.39  4954.6  247.66  4997.9     243  5000.6   242.5  5003.9     243
  5053.8  251.77  5087.8  259.06  5214.3  260.21  5283.3  271.36  5316.7  271.28
    5365  259.64    5477  255.97    5594  258.25  5671.6  271.15  5762.1  273.15
#Mann= 15 ,-1 , 0
  1498.7     .08       0    1858     .05       0  1868.7     .08       0
    2074     .05       0  2156.7     .16       0  2700.1     .12       0
  2926.7     .05       0  3480.3     .12       0  3719.6     .16       0
  4855.5     .12       0  4954.6     .05       0  4997.9     .04       0
  5003.9     .05       0  5053.8     .12       0  5283.3     .05       0
#XS Ineff= 2 ,-1
 1428.98 2414.77  268.12 5286.93 5792.61   271.8
Permanent Ineff=
       F       F
Bank Sta=4899.2,5087.8
XS Rating Curve= 0 ,0
Exp/Cntr=0.3,0.1

Type RM Length L Ch R = 1 ,70961   ,1031,1031,1031
BEGIN DESCRIPTION:
CARTERS CREEK 23.0
END DESCRIPTION:
XS GIS Cut Line= 3
      3562861.35      10223430.5      3561787.13     10220848.04
      3561605.32     10219786.26
#Sta/Elev= 30
  1808.4  274.61  1885.7  275.39  2210.2  274.08  2345.2  272.03  2426.6  270.01
    2643  267.11  2922.7  256.75    3184  265.37  3344.8  257.86  3427.9  258.81
  3795.2   259.1  3856.9  257.88  4122.6  258.14  4743.8  259.41  4781.3   251.8
  4804.6  259.47  4926.4   260.3    4993  243.06  4994.4  243.02  4997.1  242.52
  5000.4  243.02  5058.3  254.85  5093.4   249.4  5119.1  259.05    5180  259.38
  5245.6  273.27  5342.3  259.35  5458.3   266.7  5585.8  261.13  5682.6  282.05
#Mann= 18 ,-1 , 0
  1808.4      .1       0  1885.7     .08       0  2210.2     .05       0
  2345.2     .08       0  2426.6     .05       0    2643     .16       0
    3184     .12       0  3344.8     .16       0  3427.9     .12       0
  3795.2     .16       0  3856.9      .1       0  4122.6     .12       0
    4993     .05       0  4994.4     .04       0  5000.4     .05       0
  5093.4     .12       0  5245.6      .1       0  5458.3     .05       0
#XS Ineff= 2 ,-1
 2323.86 3178.98  266.47 5247.16 5707.39  273.79
Permanent Ineff=
       F       F
Bank Sta=4926.4,5119.1
XS Rating Curve= 0 ,0
Exp/Cntr=0.3,0.1

Type RM Length L Ch R = 1 ,69930   ,1710,1710,1710
BEGIN DESCRIPTION:
CARTERS CREEK 22.0
END DESCRIPTION:
XS GIS Cut Line= 3
      3564499.79     10222258.62      3562535.83     10219979.98
      3562130.51     10219385.04
#Sta/Elev= 30
  1655.2  276.37  1672.7  275.99  1859.7  273.86  2478.3  265.87  2582.7  264.79
  2746.9  265.11  2881.2  264.81  3015.5  264.42  3190.1  258.13  3305.7  262.67
  3450.3  259.83  3552.6  256.34  3671.8  256.73  3693.7  252.11  3821.2   256.4
  3959.3   256.7  4140.9  254.87  4492.6  255.46    4607  256.03  4915.7  258.02
  4999.4  240.72  5002.2  240.22  5005.4  240.72  5024.4  245.43  5047.2   262.7
  5071.2  264.57  5205.8  261.96  5268.7  272.28  5327.3  267.16  5383.3  260.57
#Mann= 20 ,-1 , 0
  1655.2     .15       0  1672.7      .1       0  1859.7     .05       0
  2478.3      .1       0  2582.7     .05       0  2746.9     .08       0
  2881.2     .08       0  3015.5     .05       0  3305.7     .08       0
  3450.3     .08       0  3552.6     .05       0  3821.2     .12       0
  3959.3     .05       0  4140.9     .12       0  4492.6     .16       0
    4607     .12       0  4999.4     .07       0  5005.4     .12       0
  5071.2     .08       0  5327.3     .05       0
#XS Ineff= 3 ,-1
 1986.36 3304.55  262.68 3390.91 3727.27  256.67 5090.91 5406.82  265.03
Permanent Ineff=
       F       F       F
Bank Sta=4915.7,5047.2
XS Rating Curve= 0 ,0
Exp/Cntr=0.3,0.1

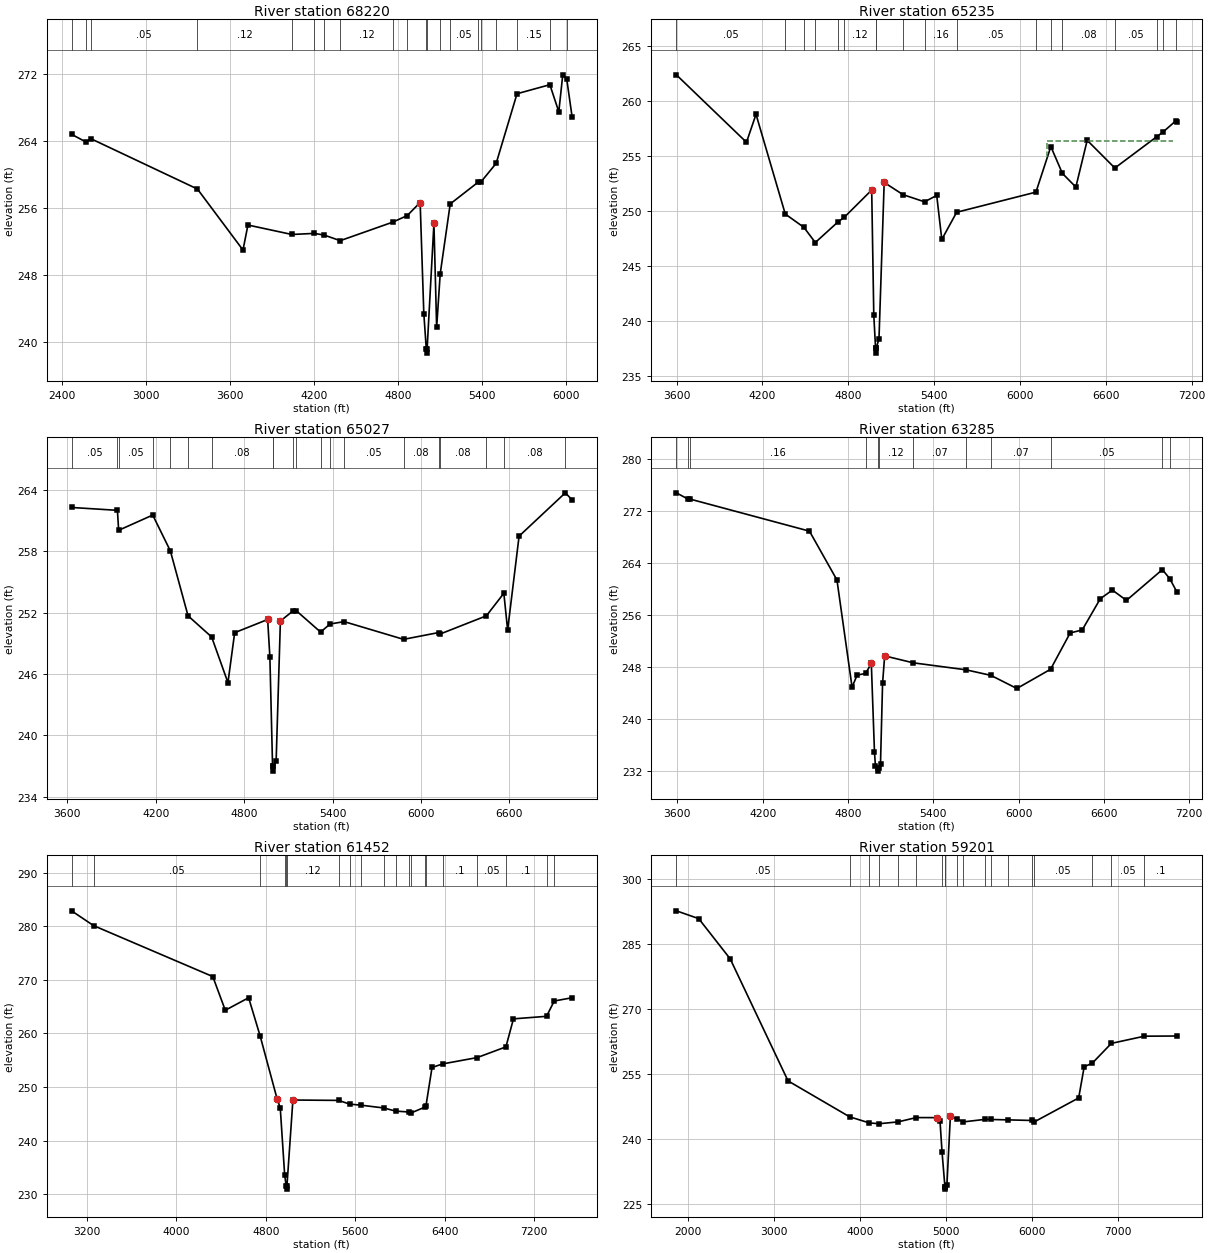
Type RM Length L Ch R = 1 ,68220   ,2985,2985,2985
BEGIN DESCRIPTION:
CARTERS CREEK 19.0
END DESCRIPTION:
XS GIS Cut Line= 4
      3564939.46     10220904.01       3563648.2     10219276.38
      3563484.56     10218630.58      3562736.96     10218267.36
#Sta/Elev= 30
  2467.6  264.83  2569.7  263.92  2606.3   264.3  3366.6  258.29  3691.9     251
  3727.2  253.99  4040.7  252.86  4202.1  252.99  4273.3  252.78  4386.4  252.12
  4762.4  254.34  4864.8  255.12  4957.2  256.68  4983.4  243.41    5001  239.18
  5003.8  238.68    5007  239.18  5055.6  254.18    5075  241.75  5100.4  248.15
  5171.9  256.51  5371.4  259.11  5392.4  259.16  5500.1  261.36  5649.1  269.68
  5883.7  270.76  5947.5  267.52  5975.7  271.94  6004.5   271.4  6042.6   266.9
#Mann= 20 ,-1 , 0
  2467.6     .05       0  2569.7     .07       0  2606.3     .05       0
  3366.6     .12       0  4040.7     .05       0  4202.1      .1       0
  4273.3     .05       0  4386.4     .12       0  4762.4     .12       0
  4864.8     .05       0    5001     .04       0    5007     .05       0
  5100.4     .08       0  5171.9     .05       0  5371.4     .15       0
  5392.4     .08       0  5500.1     .05       0  5649.1     .15       0
  5883.7     .05       0  6004.5     .08       0
Bank Sta=4957.2,5055.6
XS Rating Curve= 0 ,0
Exp/Cntr=0.3,0.1

Type RM Length L Ch R = 1 ,65235   ,208,208,208
BEGIN DESCRIPTION:
CARTERS CREEK 19.1
END DESCRIPTION:
XS GIS Cut Line= 3
       3566711.1     10219330.15      3565840.04     10217974.29
      3564726.17     10216451.67
#Sta/Elev= 30
  3598.5  262.38  4088.5  256.25  4155.2  258.79  4359.6  249.73  4489.9  248.52
  4569.5  247.14  4729.5  249.03  4771.6  249.43  4963.6  251.91  4978.2  240.57
  4990.4  237.59  4993.1  237.09  4996.4  237.59  5014.5  238.39  5050.9   252.6
  5182.7  251.49  5332.8  250.84    5418  251.42  5453.5  247.42  5557.3  249.89
  6111.4  251.72  6215.5  255.86  6296.4  253.42  6390.4  252.18  6469.6  256.43
  6662.8  253.91  6954.8  256.75  6999.3  257.18  7089.2   258.2  7096.6  258.09
#Mann= 18 ,-1 , 0
  3598.5     .05       0  4359.6     .16       0  4489.9     .08       0
  4569.5     .16       0  4729.5     .08       0  4771.6     .12       0
  4990.4     .07       0  4996.4     .12       0  5182.7     .05       0
  5332.8     .16       0  5557.3     .05       0  6111.4     .08       0
  6215.5     .05       0  6296.4     .08       0  6662.8     .05       0
  6954.8     .08       0  6999.3     .05       0  7089.2     .08       0
#XS Ineff= 1 ,-1
 6190.91 7072.73  256.33
Permanent Ineff=
       F
Bank Sta=4963.6,5050.9
XS Rating Curve= 0 ,0
Exp/Cntr=0.3,0.1

Type RM Length L Ch R = 1 ,65027   ,1742,1742,1742
BEGIN DESCRIPTION:
CARTERS CREEK 19.2
END DESCRIPTION:
XS GIS Cut Line= 3
      3566837.89     10219154.17      3565966.85     10217798.35
      3564922.49     10216349.65
#Sta/Elev= 30
  3628.4  262.27  3939.6  261.99  3947.9  260.04  4179.3  261.53  4299.1  258.02
  4418.9  251.69  4579.2  249.62  4689.8  245.16  4735.4  250.04  4959.3  251.33
  4974.5  247.63  4992.6  237.02  4995.4  236.52  4998.6  237.02  5016.8  237.48
  5045.8  251.18  5129.9  252.15  5152.5   252.2  5318.6   250.1  5383.1  250.89
  5478.7  251.12  5881.8  249.39  6118.9  250.05    6130  249.91    6444  251.69
  6562.4  253.89  6588.1   250.3  6665.8  259.47  6979.7   263.7  7025.8  263.01
#Mann= 20 ,-1 , 0
  3628.4     .05       0  3939.6     .16       0  3947.9     .05       0
  4179.3     .08       0  4299.1     .08       0  4418.9     .16       0
  4579.2     .08       0  4992.6     .07       0  4998.6     .08       0
  5129.9     .12       0  5152.5     .08       0  5318.6     .05       0
  5383.1     .12       0  5478.7     .05       0  5881.8     .08       0
  6118.9     .05       0    6130     .08       0    6444     .05       0
  6562.4     .08       0  6979.7      .1       0
Bank Sta=4959.3,5045.8
XS Rating Curve= 0 ,0
Exp/Cntr=0.3,0.1

Type RM Length L Ch R = 1 ,63285   ,1833,1833,1833
BEGIN DESCRIPTION:
CARTERS CREEK 18.0
END DESCRIPTION:
XS GIS Cut Line= 4
      3568322.66     10218434.34      3567680.32     10217739.92
      3567112.28     10216982.67      3565944.24     10215847.59
#Sta/Elev= 30
  3592.7  274.83  3671.7   273.9  3686.6  273.88  4529.1  268.93  4722.5  261.41
  4828.8  244.91  4864.2  246.78  4924.2  247.02  4964.2  248.58  4986.5  234.88
  4993.4  232.74  5011.2  232.49    5014  231.99  5017.2  232.49  5028.8  233.14
  5043.4   245.5    5058  249.73  5259.4  248.66  5629.4  247.59  5805.6  246.73
  5988.1  244.71  6225.2  247.67  6363.1  253.26  6447.8  253.72  6575.1  258.53
    6660  259.86    6759  258.27  7011.8  263.01  7063.8  261.61    7114  259.57
#Mann= 12 ,-1 , 0
  3592.7     .16       0  3671.7      .1       0  3686.6     .16       0
  4924.2     .12       0  5011.2     .07       0  5017.2     .12       0
  5259.4     .07       0  5629.4     .12       0  5805.6     .07       0
  6225.2     .05       0  7011.8     .08       0  7063.8      .1       0
Bank Sta=4964.2,5058
XS Rating Curve= 0 ,0
Exp/Cntr=0.3,0.1

Type RM Length L Ch R = 1 ,61452   ,2251,2251,2251
BEGIN DESCRIPTION:
CARTERS CREEK 17.0
END DESCRIPTION:
XS GIS Cut Line= 3
      3569155.99     10218278.07      3568513.65     10217010.75
      3566360.87     10214840.61
#Sta/Elev= 30
  3062.8  282.87  3259.7  280.11  4326.2   270.6  4437.8  264.31  4646.7  266.65
  4749.8   259.5  4901.3  247.78  4929.6  246.08  4968.9   233.6  4983.1  231.43
  4985.9  230.93  4989.1  231.43  5042.7  247.56  5450.6  247.49  5550.8   246.8
  5654.9  246.59  5854.2  246.08  5963.2  245.49  6084.1  245.32    6098  245.13
  6228.1  246.28  6232.8  246.45  6287.2  253.63  6382.2   254.3  6690.9  255.48
  6948.3  257.48  7015.6  262.71  7311.4  263.18  7380.5  266.04  7540.4  266.65
#Mann= 20 ,-1 , 0
  3062.8      .1       0  3259.7     .05       0  4749.8     .16       0
  4968.9     .12       0  4983.1     .07       0  4989.1     .12       0
  5450.6      .1       0  5550.8     .12       0  5654.9      .1       0
  5854.2     .12       0  5963.2     .05       0  6084.1      .1       0
    6098     .05       0  6228.1      .1       0  6232.8     .05       0
  6382.2      .1       0  6690.9     .05       0  6948.3      .1       0
  7311.4     .08       0  7380.5     .05       0
Bank Sta=4901.3,5042.7
XS Rating Curve= 0 ,0
Exp/Cntr=0.3,0.1

Type RM Length L Ch R = 1 ,59201   ,1439,1439,1439
BEGIN DESCRIPTION:
CARTERS CREEK 17.1
END DESCRIPTION:
XS GIS Cut Line= 4
      3570597.13     10217320.11      3569364.35     10215153.11
      3567784.49     10215031.58      3566276.66     10214152.92
#Sta/Elev= 30
  1861.6  292.71  2121.6  290.91  2487.7  281.64  3160.8  253.49  3876.6  245.21
  4107.9  243.79  4223.5  243.62  4438.6  244.03  4652.3  245.03  4888.5  245.02
  4928.6   244.2  4952.5  237.02  4985.8  229.03  4988.6  228.53  4991.8  229.03
  5008.9  229.54    5049  245.28  5129.6  244.78  5194.2  244.02  5451.9  244.62
  5524.4  244.59  5721.9   244.5  6003.5  244.36    6021  243.99  6541.5  249.56
    6606  256.77  6698.5  257.55  6921.9  262.14  7306.1   263.8  7684.4  263.84
#Mann= 19 ,-1 , 0
  1861.6     .05       0  3876.6     .16       0  4107.9     .12       0
  4223.5     .05       0  4438.6     .16       0  4652.3      .1       0
  4952.5     .12       0  4985.8     .07       0  4991.8     .12       0
  5129.6      .1       0  5194.2     .05       0  5451.9      .1       0
  5524.4     .12       0  5721.9     .05       0  6003.5      .1       0
    6021     .05       0  6698.5      .1       0  6921.9     .05       0
  7306.1      .1       0
Bank Sta=4888.5,5049
XS Rating Curve= 0 ,0
Exp/Cntr=0.3,0.1

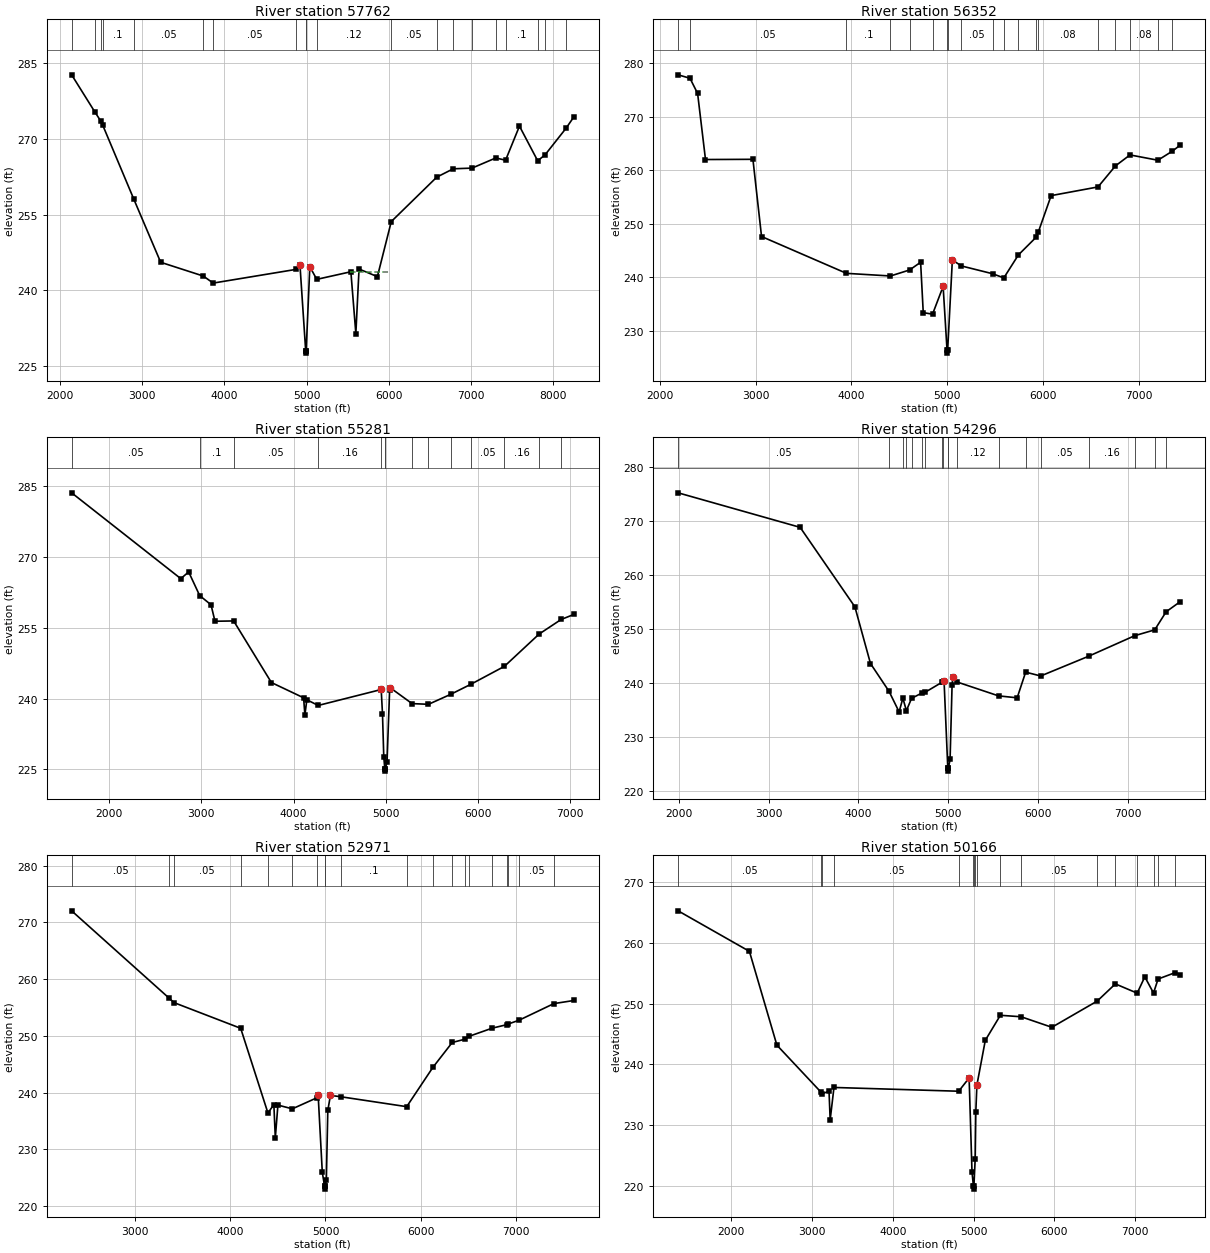
Type RM Length L Ch R = 1 ,57762   ,1410,1410,1410
BEGIN DESCRIPTION:
CARTERS CREEK 16.0
END DESCRIPTION:
XS GIS Cut Line= 4
      3571083.09     10216442.17       3569629.1     10214608.41
      3569129.44     10212881.66      3567546.43     10211700.91
#Sta/Elev= 30
  2139.8  282.73  2418.9  275.45  2492.3   273.6  2517.5  272.76  2893.9  258.15
  3223.3  245.53  3741.9   242.8  3862.7   241.4  4868.3  244.11    4919  244.94
  4988.4     228  4991.2   227.5  4994.4     228  5038.8  244.65  5123.2  242.14
  5538.5  243.65  5599.1  231.39  5637.9  244.19  5861.2  242.68  6030.4  253.61
  6584.2  262.43  6784.4  264.08  7013.6  264.22  7302.1  266.23  7421.7  265.79
  7590.5  272.55  7812.1  265.68  7900.3  266.81  8159.2  272.16  8252.5  274.38
#Mann= 20 ,-1 , 0
  2139.8     .08       0  2418.9      .1       0  2492.3     .05       0
  2517.5      .1       0  2893.9     .05       0  3741.9      .1       0
  3862.7     .05       0  4868.3     .16       0  4988.4     .07       0
  4994.4     .16       0  5123.2     .12       0  6030.4     .05       0
  6584.2     .08       0  6784.4      .1       0  7013.6      .1       0
  7302.1     .05       0  7421.7      .1       0  7812.1     .08       0
  7900.3      .1       0  8159.2      .1       0
#XS Ineff= 1 ,-1
 5527.84 6017.05  243.65
Permanent Ineff=
       F
Bank Sta=4919,5038.8
XS Rating Curve= 0 ,0
Exp/Cntr=0.3,0.1

Type RM Length L Ch R = 1 ,56352   ,1071,1071,1071
BEGIN DESCRIPTION:
CARTERS CREEK 14.0
END DESCRIPTION:
XS GIS Cut Line= 4
      3571940.28     10216029.81      3570811.83     10213903.11
      3570529.71      10212980.8      3568978.05     10211949.98
#Sta/Elev= 30
  2193.3  277.82  2316.8  277.18  2396.4  274.35  2478.7     262  2973.1  262.04
  3062.9  247.62  3948.5  240.74  4407.2  240.25  4606.2  241.37  4721.1  242.81
  4748.6   233.4  4845.6  233.12  4955.8   238.3  4996.8  226.34  4999.5  225.84
  5002.8  226.34    5052  243.23    5147  242.12  5471.1  240.67  5588.5  239.89
  5740.3  244.18  5924.8  247.48  5947.6  248.44  6081.8  255.26  6570.2  256.88
    6752  260.81    6904  262.86  7194.4  261.87  7344.2  263.55  7428.2   264.7
#Mann= 19 ,-1 , 0
  2193.3      .1       0  2316.8     .05       0  3948.5      .1       0
  4407.2     .05       0  4606.2     .16       0  4845.6     .12       0
  4996.8     .07       0  5002.8     .12       0    5147     .05       0
  5471.1     .16       0  5588.5     .05       0  5740.3     .08       0
  5924.8     .05       0  5947.6     .08       0  6570.2      .1       0
    6752     .05       0    6904     .08       0  7194.4      .1       0
  7344.2     .08       0
Bank Sta=4955.8,5052
XS Rating Curve= 0 ,0
Exp/Cntr=0.3,0.1

Type RM Length L Ch R = 1 ,55281   ,985,985,985
BEGIN DESCRIPTION:
CARTERS CREEK 12.0
END DESCRIPTION:
XS GIS Cut Line= 4
      3573426.83     10215498.14       3571896.9     10213534.19
      3571007.14     10212622.73      3569900.38     10211353.21
#Sta/Elev= 30
  1592.9  283.62    2777  265.43  2862.1  266.86  2981.8  261.84  3104.5   259.9
  3147.6   256.4  3350.3  256.47  3759.5  243.42  4108.9  240.18    4123  236.55
  4144.1  239.76  4267.5  238.56  4947.6  241.92  4950.4  242.03  4964.6  236.85
  4978.7  227.65  4989.9  225.14  4992.6  224.64  4995.9  225.14    5014  226.62
  5042.3  241.88  5049.4   242.3  5285.5  238.95  5463.6   238.8  5703.9  240.91
  5920.7  243.02  6287.5  246.85  6663.7  253.69  6902.7  256.78  7040.4  257.84
#Mann= 14 ,-1 , 0
  1592.9     .05       0  2981.8      .1       0  3350.3     .05       0
  4267.5     .16       0  4947.6     .12       0  4989.9     .07       0
  4995.9     .12       0  5285.5     .16       0  5463.6     .05       0
  5703.9     .16       0  5920.7     .05       0  6287.5     .16       0
  6663.7     .05       0  6902.7     .16       0
Bank Sta=4950.4,5049.4
XS Rating Curve= 0 ,0
Exp/Cntr=0.3,0.1

Type RM Length L Ch R = 1 ,54296   ,1325,1325,1325
BEGIN DESCRIPTION:
CARTERS CREEK 10.0
END DESCRIPTION:
XS GIS Cut Line= 4
      3573752.35     10214933.92      3572862.61     10214250.33
      3571647.51     10211808.83      3570205.66     10210822.52
#Sta/Elev= 30
  1991.6  275.16  3351.4  268.77  3961.5  254.06  4135.1  243.57  4342.3  238.41
  4454.2  234.61  4496.2  237.16  4535.3  234.84  4593.1  237.12  4711.8  238.14
  4740.6  238.21  4935.7  240.13  4945.9  240.22  4955.2  240.31  4996.9  224.15
  4999.6  223.65  5002.9  224.15  5022.2  225.85  5044.6  239.65  5053.2  241.06
  5099.6  240.15  5561.8  237.58  5769.7  237.22  5864.3  241.97  6031.9  241.26
  6565.2  244.91  7080.2  248.72  7302.7   249.8  7429.6  253.14  7587.7  255.03
#Mann= 19 ,-1 , 0
  1991.6     .05       0  4342.3     .16       0  4496.2     .05       0
  4535.3     .16       0  4593.1     .05       0  4711.8     .16       0
  4740.6     .05       0  4935.7     .12       0  4945.9     .16       0
  4996.9     .07       0  5002.9     .16       0  5099.6     .12       0
  5561.8     .05       0  5864.3     .08       0  6031.9     .05       0
  6565.2     .16       0  7080.2      .1       0  7302.7     .05       0
  7429.6      .1       0
Bank Sta=4955.2,5053.2
XS Rating Curve= 0 ,0
Exp/Cntr=0.3,0.1

Type RM Length L Ch R = 1 ,52971   ,2805,2805,2805
BEGIN DESCRIPTION:
CARTERS CREEK 8.0
END DESCRIPTION:
XS GIS Cut Line= 3
        3574360.     10213677.41      3573891.26     10212418.74
      3570549.27      10210344.1
#Sta/Elev= 30
  2333.2  272.02  3359.4   256.6  3407.9  255.85  4109.3  251.32  4395.7  236.39
  4457.9  237.88  4473.2  232.01  4500.4  237.79    4652  237.13  4908.1  239.06
    4923  239.64  4966.9  225.93    4991  223.48  4993.8  222.98    4997  223.48
  5009.4  224.66  5024.7  236.84  5052.4   239.5  5164.5  239.25  5853.7  237.51
  6128.6  244.43  6332.1  248.82    6468  249.41  6505.8  249.89  6753.2  251.35
  6903.7  251.95  6921.6  252.08  7035.1  252.75  7399.8  255.67  7609.9  256.22
#Mann= 20 ,-1 , 0
  2333.2     .05       0  3359.4      .1       0  3407.9     .05       0
  4109.3      .1       0  4395.7     .12       0    4652     .05       0
  4908.1     .16       0    4991     .07       0    4997     .16       0
  5164.5      .1       0  5853.7     .05       0  6128.6     .08       0
  6332.1     .05       0    6468     .08       0  6505.8      .1       0
  6753.2      .1       0  6903.7     .08       0  6921.6      .1       0
  7035.1     .05       0  7399.8     .08       0
Bank Sta=4923,5052.4
XS Rating Curve= 0 ,0
Exp/Cntr=0.3,0.1

Type RM Length L Ch R = 1 ,50166   ,3098,3098,3098
BEGIN DESCRIPTION:
CARTERS CREEK 6.0
END DESCRIPTION:
XS GIS Cut Line= 4
      3575106.52     10213061.09      3573231.53     10210882.28
      3572912.43     10209589.45       3570915.5     10209814.38
#Sta/Elev= 30
  1343.3  265.24  2225.7  258.58  2565.9  243.16  3105.9  235.52  3124.4  235.15
  3211.1  235.61  3225.3  230.89  3272.3  236.21  4815.9  235.59  4945.2  237.77
  4980.7  222.34  4998.3     220    5001   219.5  5004.3     220  5020.3  224.46
  5028.1  232.25  5040.9  236.41  5042.5  236.68  5145.5  243.96  5331.7  248.07
  5588.4  247.83  5969.2   246.1  6530.8  250.41  6755.3  253.23  7025.2  251.71
  7119.6  254.39  7227.4  251.73  7283.7  254.03    7499   255.1    7559  254.74
#Mann= 17 ,-1 , 0
  1343.3     .05       0  3105.9      .1       0  3124.4     .16       0
  3272.3     .05       0  4815.9     .16       0  4998.3     .07       0
  5004.3     .16       0  5020.3     .12       0  5040.9     .05       0
  5331.7      .1       0  5588.4     .05       0  6530.8      .1       0
  6755.3     .05       0  7025.2     .08       0  7227.4      .1       0
  7283.7     .08       0    7499      .1       0
Bank Sta=4945.2,5042.5
XS Rating Curve= 0 ,0
Exp/Cntr=0.3,0.1