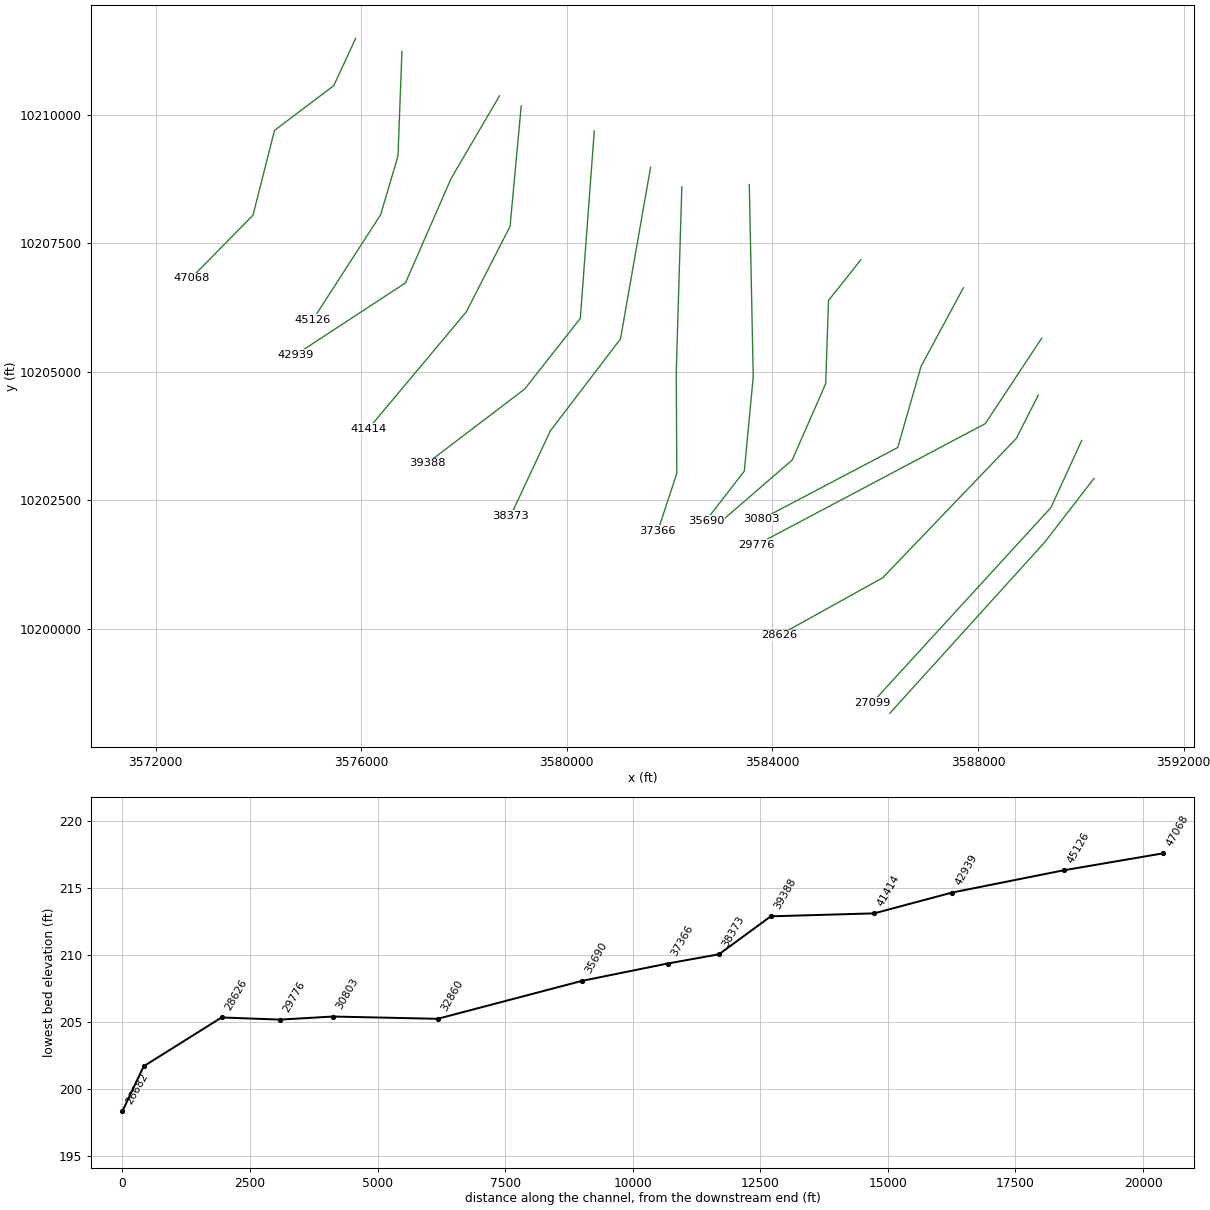
HEC-RAS study CARTERS CREEK.prj: CARTERS CREEK Base Level Engineering

--- CARTERS CREEK.g01 (geometry) --- (continued)

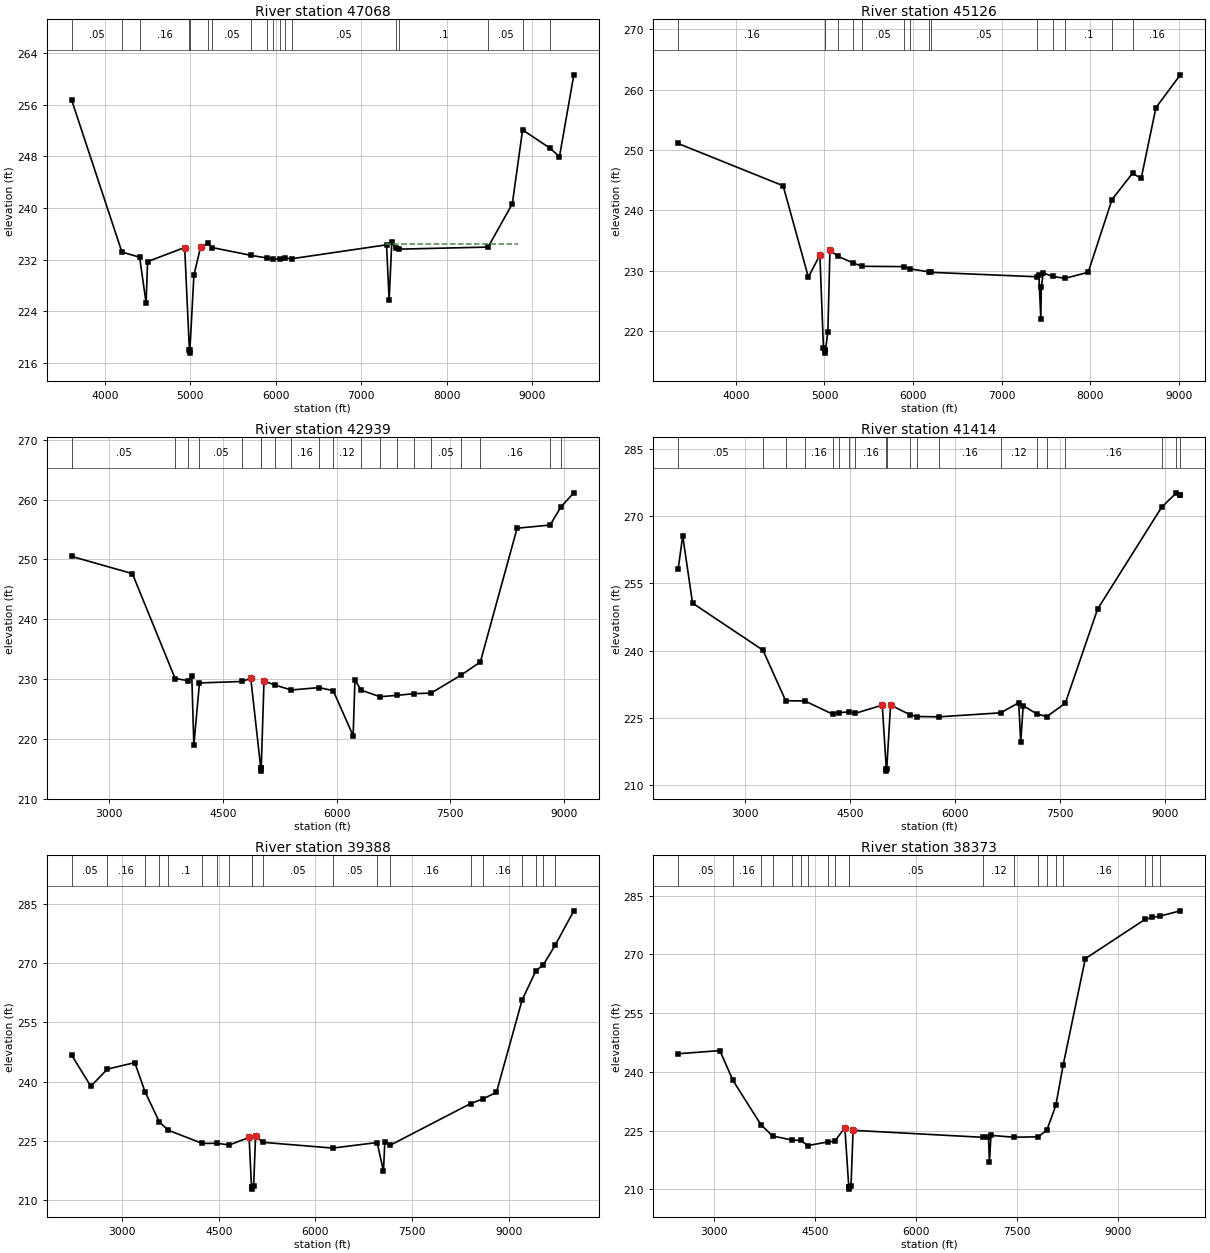
Type RM Length L Ch R = 1 ,47068   ,1942,1942,1942
BEGIN DESCRIPTION:
CARTERS CREEK 4.0
END DESCRIPTION:
XS GIS Cut Line= 5
      3575892.09     10211491.62      3575464.34     10210570.29
      3574312.11     10209699.68      3573893.43     10208050.25
      3572690.27     10206825.41
#Sta/Elev= 30
  3610.8   256.7  4199.2  233.19  4406.7  232.39  4482.4  225.31  4499.8  231.72
  4933.8  233.89  4989.1  218.06  4991.8  217.56  4995.1  218.06    5042  229.63
  5119.1   233.9  5204.5  234.53  5257.5  233.88  5715.8  232.67    5901  232.26
  5964.8   232.1  6045.6  232.13  6110.1  232.23  6188.3  232.16  7296.5  234.31
  7327.4  225.85  7358.4  234.72  7403.6  233.81  7441.3  233.64  8485.8  233.96
  8769.5  240.66  8889.4  252.08  9212.5  249.24  9321.1  247.93  9489.4   260.6
#Mann= 18 ,-1 , 0
  3610.8     .05       0  4199.2      .1       0  4406.7     .16       0
  4989.1     .07       0  4995.1     .16       0  5204.5      .1       0
  5257.5     .05       0  5715.8      .1       0    5901     .05       0
  5964.8      .1       0  6045.6     .05       0  6110.1      .1       0
  6188.3     .05       0  7403.6     .16       0  7441.3      .1       0
  8485.8     .05       0  8889.4     .16       0  9212.5     .05       0
#XS Ineff= 1 ,-1
  7287.5 8834.66  234.48
Permanent Ineff=
       F
Bank Sta=4933.8,5119.1
XS Rating Curve= 0 ,0
Exp/Cntr=0.3,0.1

Type RM Length L Ch R = 1 ,45126   ,2187,2187,2187
BEGIN DESCRIPTION:
CARTERS CREEK 3.0
END DESCRIPTION:
XS GIS Cut Line= 4
      3576792.11     10211241.64      3576714.61     10209200.42
      3576378.24      10208061.1      3575054.42     10206010.28
#Sta/Elev= 30
  3347.5  251.07  4533.5  244.06  4818.6   228.9  4948.6  232.59  4988.7   217.2
  5005.7   216.8  5008.4   216.3  5011.7   216.8  5038.7  219.85  5062.2  233.37
  5156.4  232.34  5325.3  231.25  5425.5   230.7  5893.5  230.65  5963.8  230.28
  6185.9  229.77  6206.9   229.7  7403.9  228.96  7422.5  229.18  7443.6  221.96
  7449.6  227.21  7470.7  229.61  7579.3  229.01  7718.3  228.71  7978.8  229.71
    8248  241.78  8479.7  246.14  8577.3  245.28  8743.7  257.01  9019.1  262.46
#Mann= 15 ,-1 , 0
  3347.5     .16       0  5005.7     .07       0  5011.7     .16       0
  5156.4     .05       0  5325.3      .1       0  5425.5     .05       0
  5893.5      .1       0  5963.8     .05       0  6185.9     .16       0
  6206.9     .05       0  7403.9     .16       0  7579.3     .05       0
  7718.3      .1       0    8248     .05       0  8479.7     .16       0
Bank Sta=4948.6,5062.2
XS Rating Curve= 0 ,0
Exp/Cntr=0.3,0.1

Type RM Length L Ch R = 1 ,42939   ,1525,1525,1525
BEGIN DESCRIPTION:
CARTERS CREEK 3.2
END DESCRIPTION:
XS GIS Cut Line= 4
      3578689.42     10210372.27      3577746.46     10208760.27
      3576860.97     10206733.02      3574728.97      10205337.6
#Sta/Elev= 30
  2502.3   250.5  3303.6  247.63  3867.7  230.11    4041  229.74  4087.9  230.47
  4115.1  218.99    4189  229.37    4746  229.61  4866.4  230.13  4998.3  215.14
    5001  214.64  5004.3  215.14  5041.1   229.7  5181.9  229.03  5400.7  228.19
  5765.8  228.59    5954  228.08  6217.5  220.55  6240.9  229.82  6323.3  228.16
  6572.1  227.07  6802.3   227.3  7020.4  227.58  7245.3  227.67  7643.9  230.69
  7896.3  232.87  8381.3  255.21  8816.4  255.74  8961.4   258.8  9130.1  261.12
#Mann= 20 ,-1 , 0
  2502.3     .05       0  3867.7      .1       0    4041     .16       0
    4189     .05       0    4746     .16       0  4998.3     .07       0
  5004.3     .16       0  5181.9      .1       0  5400.7     .16       0
  5765.8     .16       0    5954     .12       0  6323.3     .16       0
  6572.1      .1       0  6802.3     .05       0  7020.4      .1       0
  7245.3     .05       0  7643.9     .12       0  7896.3     .16       0
  8816.4     .05       0  8961.4     .08       0
Bank Sta=4866.4,5041.1
XS Rating Curve= 0 ,0
Exp/Cntr=0.3,0.1

Type RM Length L Ch R = 1 ,41414   ,2026,2026,2026
BEGIN DESCRIPTION:
CARTERS CREEK 3.1
END DESCRIPTION:
XS GIS Cut Line= 4
      3579112.61     10210177.02       3578895.6     10207833.23
      3578043.69     10206168.79      3576140.45     10203895.54
#Sta/Elev= 30
  2036.7  258.12  2102.4   265.6    2243  250.59  3251.1  240.08  3576.4   228.8
  3851.1  228.75  4247.3  225.81  4346.3  226.14  4486.2  226.32  4565.6  225.96
  4958.7  227.81  5016.7  213.59  5019.5  213.09  5022.7  213.59  5077.6  227.84
  5354.2  225.69  5450.5  225.28  5770.9  225.21  6653.4   226.1  6912.2  228.35
  6940.8  219.55    6976  227.71  7170.7  225.86  7314.8  225.27    7579  228.25
  8041.6  249.27  8959.1  272.02  9170.2   275.2  9224.4  274.75  9225.1  274.76
#Mann= 20 ,-1 , 0
  2036.7     .05       0  3251.1     .16       0  3576.4     .05       0
  3851.1     .16       0  4247.3      .1       0  4346.3     .16       0
  4486.2      .1       0  4565.6     .16       0  5016.7     .07       0
  5022.7     .16       0  5354.2     .05       0  5450.5      .1       0
  5770.9     .16       0  6653.4     .12       0  7170.7     .16       0
  7314.8     .12       0    7579     .16       0  8959.1      .1       0
  9170.2     .16       0  9224.4      .1       0
Bank Sta=4958.7,5077.6
XS Rating Curve= 0 ,0
Exp/Cntr=0.3,0.1

Type RM Length L Ch R = 1 ,39388   ,1015,1015,1015
BEGIN DESCRIPTION:
CARTERS CREEK 3.3
END DESCRIPTION:
XS GIS Cut Line= 4
      3580534.05     10209688.68      3580262.78     10206042.87
      3579179.48     10204666.88      3577278.86      10203221.7
#Sta/Elev= 30
  2215.2  246.75  2513.1  238.87  2769.9  243.21  3194.9  244.86  3354.9  237.45
  3576.7  229.85  3716.1  227.75  4244.8  224.42  4466.4  224.46  4664.1  224.04
  4969.8  225.95  5006.9  213.37  5009.7  212.87  5012.9  213.37    5040  213.73
  5070.1  226.38  5183.2   224.7  6267.9  223.25  6957.3  224.65  7055.1  217.42
    7076  224.77  7163.1     224    8406  234.49  8596.2  235.66  8809.2  237.35
  9206.4  260.65  9420.4  268.05  9536.2  269.57  9718.2  274.49   10010  283.23
#Mann= 20 ,-1 , 0
  2215.2     .05       0  2769.9     .16       0  3354.9     .05       0
  3576.7     .16       0  3716.1      .1       0  4244.8     .05       0
  4466.4     .16       0  4664.1     .16       0  5006.9     .07       0
  5012.9     .16       0  5183.2     .05       0  6267.9     .05       0
  6957.3     .12       0  7163.1     .16       0    8406     .05       0
  8596.2     .16       0  9206.4      .1       0  9420.4     .16       0
  9536.2     .05       0  9718.2     .16       0
Bank Sta=4969.8,5070.1
XS Rating Curve= 0 ,0
Exp/Cntr=0.3,0.1

Type RM Length L Ch R = 1 ,38373   ,1007,1007,1007
BEGIN DESCRIPTION:
CARTERS CREEK 3.4
END DESCRIPTION:
XS GIS Cut Line= 4
      3581629.98     10208983.45      3581044.03     10205641.39
      3579678.61     10203853.08      3578906.78     10202202.43
#Sta/Elev= 30
    2463  244.62  3084.1  245.42  3277.5  237.83  3692.2  226.54  3867.3  223.61
    4159  222.57  4287.7  222.48  4388.2  221.16  4689.5   222.1    4790  222.27
    4942   225.7    5000  210.54  5002.7  210.04    5006  210.54  5033.4  210.92
  5063.9  225.06  6995.3  223.27  7076.4  223.44  7090.9  216.94  7113.7  223.76
  7459.4   223.3  7817.5   223.4    7945  225.14  8078.1  231.45  8187.4  241.77
  8516.2  268.91  9403.1  278.93  9513.6  279.42    9628  279.78  9928.2  281.12
#Mann= 20 ,-1 , 0
    2463     .05       0  3277.5     .16       0  3692.2     .05       0
  3867.3     .16       0    4159     .16       0  4287.7      .1       0
  4388.2     .05       0  4689.5     .16       0    4790     .05       0
    5000     .03       0    5006     .05       0  6995.3     .12       0
  7459.4     .12       0  7817.5     .16       0    7945     .16       0
  8078.1     .12       0  8187.4     .16       0  9403.1      .1       0
  9513.6     .16       0    9628      .1       0
Bank Sta=4942,5063.9
XS Rating Curve= 0 ,0
Exp/Cntr=0.3,0.1

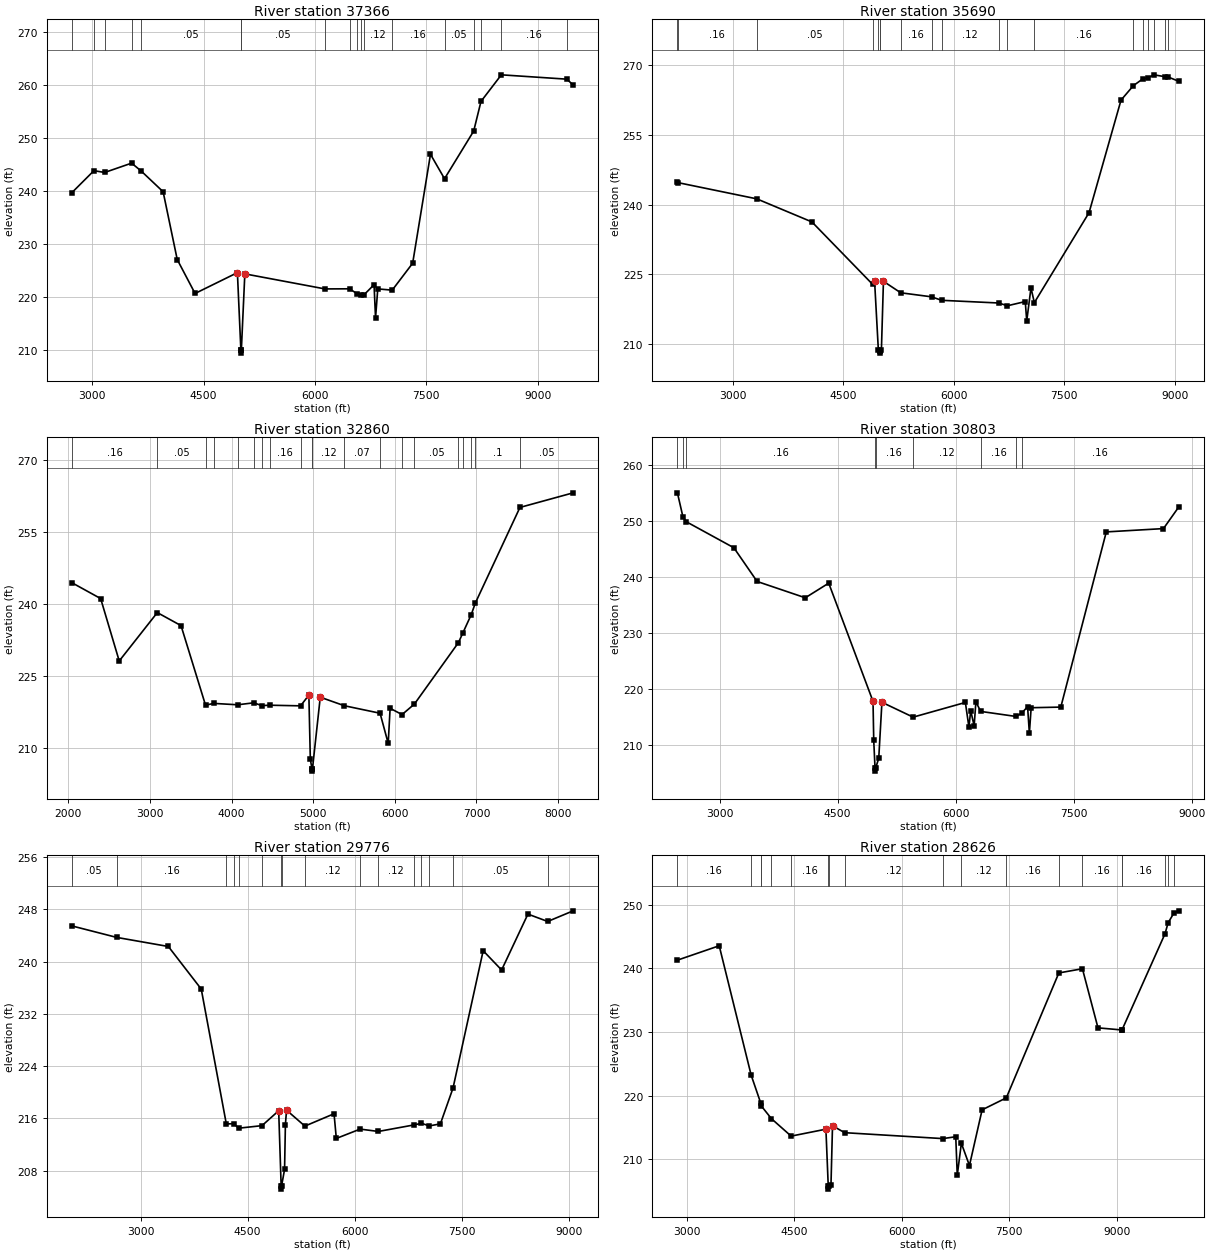
Type RM Length L Ch R = 1 ,37366   ,1676,1676,1676
BEGIN DESCRIPTION:
CARTERS CREEK 3.5
END DESCRIPTION:
XS GIS Cut Line= 4
      3582237.61     10208603.61       3582129.1      10205001.2
      3582139.95     10203026.38      3581771.04     10201908.79
#Sta/Elev= 30
  2722.9  239.59  3023.6  243.79  3168.2  243.45  3530.8  245.21  3660.1  243.72
  3955.4  239.81  4145.5  227.01  4385.6  220.61  4955.9  224.54  5002.9  209.85
  5005.7  209.35  5008.9  209.85  5055.9  224.31  6135.4  221.47  6468.3  221.49
  6566.6  220.56  6621.8  220.31  6664.3  220.41  6796.5  222.26  6816.5     216
  6846.5  221.47  7041.2  221.24  7316.5  226.32  7556.5  246.88  7745.6  242.27
  8138.6  251.27  8236.8  256.86  8510.9  261.88  9393.5  261.06  9478.7  259.95
#Mann= 18 ,-1 , 0
  2722.9     .05       0  3023.6      .1       0  3168.2     .05       0
  3530.8     .16       0  3660.1     .05       0  5002.9     .03       0
  5008.9     .05       0  6135.4     .12       0  6468.3     .16       0
  6566.6     .12       0  6621.8     .16       0  6664.3     .12       0
  7041.2     .16       0  7745.6     .05       0  8138.6     .16       0
  8236.8      .1       0  8510.9     .16       0  9393.5      .1       0
Bank Sta=4955.9,5055.9
XS Rating Curve= 0 ,0
Exp/Cntr=0.3,0.1

Type RM Length L Ch R = 1 ,35690   ,2830,2830,2830
BEGIN DESCRIPTION:
CARTERS CREEK 3.6
END DESCRIPTION:
XS GIS Cut Line= 4
      3583550.54     10208647.02      3583627.07      10204906.1
      3583452.89     10203069.78      3582705.18     10202105.34
#Sta/Elev= 30
  2249.3  244.81  2251.8  244.78  3326.8  241.27  4075.1   236.3  4898.1  222.87
  4925.2  223.54    4976  208.83  4992.2  208.56    4995  208.06  4998.2  208.56
  5017.6  208.66  5045.3  223.52  5279.9  221.05  5698.1  220.18  5834.5  219.43
  6609.5  218.85  6728.6  218.26  6969.8  219.16  6989.9  214.99  7047.4   222.1
  7093.2  218.93  7835.6   238.3  8269.5  262.53    8437  265.64  8562.5  267.07
  8637.7  267.35  8715.8  267.97  8869.2  267.56  8912.3  267.48  9055.9  266.56
#Mann= 19 ,-1 , 0
  2249.3      .1       0  2251.8     .16       0  3326.8     .05       0
  4898.1     .16       0    4976     .12       0  4992.2     .07       0
  4998.2     .12       0  5279.9     .16       0  5698.1      .1       0
  5834.5     .12       0  6609.5     .16       0  6728.6     .12       0
  7093.2     .16       0    8437      .1       0  8562.5     .16       0
  8637.7     .05       0  8715.8     .16       0  8869.2      .1       0
  8912.3     .05       0
Bank Sta=4925.2,5045.3
XS Rating Curve= 0 ,0
Exp/Cntr=0.3,0.1

Type RM Length L Ch R = 1 ,32860   ,2057,2057,2057
BEGIN DESCRIPTION:
CARTERS CREEK 2.0
END DESCRIPTION:
XS GIS Cut Line= 5
      3585720.71     10207182.23      3585091.34     10206390.09
      3585037.09     10204773.34      3584386.05     10203286.79
      3582953.72     10202049.78
#Sta/Elev= 30
  2039.9  244.48  2395.6  241.15  2623.1  228.16  3089.8  238.23  3380.3  235.52
  3680.5  218.95  3778.9  219.33  4074.3  219.04  4271.2  219.45  4369.6  218.87
  4468.1  218.95  4844.7  218.82  4946.5  221.05  4964.4  207.67  4984.7  205.73
  4987.5  205.23  4990.7  205.73    5086  220.62  5381.7  218.84  5818.8  217.28
  5918.4     211  5941.8  218.31  6088.1     217  6239.4  219.19  6778.8  231.98
  6832.1  233.96  6936.3  237.83  6985.4   240.2  7532.3  260.12  8184.7  263.16
#Mann= 20 ,-1 , 0
  2039.9     .16       0  3089.8     .05       0  3680.5     .16       0
  3778.9     .12       0  4074.3     .16       0  4271.2     .05       0
  4369.6     .07       0  4468.1     .16       0  4844.7     .12       0
  4984.7     .07       0  4990.7     .12       0  5381.7     .07       0
  5818.8     .12       0  6088.1     .16       0  6239.4     .05       0
  6778.8     .16       0  6832.1      .1       0  6936.3     .16       0
  6985.4      .1       0  7532.3     .05       0
Bank Sta=4946.5,5086
XS Rating Curve= 0 ,0
Exp/Cntr=0.3,0.1

Type RM Length L Ch R = 1 ,30803   ,1027,1027,1027
BEGIN DESCRIPTION:
CARTERS CREEK TRIB 8 31.0
END DESCRIPTION:
XS GIS Cut Line= 4
       3587717.2     10206639.63      3586892.56     10205109.71
      3586439.18     10203530.47      3583789.25     10202136.61
#Sta/Elev= 30
  2463.1  255.04  2533.2  250.77  2575.5  249.89    3181  245.24  3476.2  239.23
  4088.6  236.32  4386.4  238.93  4949.5  217.84  4958.6  210.87  4975.1   205.9
  4977.8   205.4  4981.1   205.9  5022.2  207.68  5062.6  217.68  5459.4  215.03
  6123.3  217.65  6168.5  213.24  6190.8  216.21  6234.8  213.46  6256.9  217.76
  6318.3  216.05  6767.4  215.15  6837.2  215.73  6914.2  216.88  6936.8  212.15
  6959.4  216.71  7336.3  216.82  7914.4  248.07  8641.1  248.66  8838.3  252.57
#Mann= 9 ,-1 , 0
  2463.1     .16       0  2533.2     .05       0  2575.5     .16       0
  4975.1     .07       0  4981.1     .16       0  5459.4     .12       0
  6318.3     .16       0  6767.4     .12       0  6837.2     .16       0
Bank Sta=4949.5,5062.6
XS Rating Curve= 0 ,0
Exp/Cntr=0.3,0.1

Type RM Length L Ch R = 1 ,29776   ,1150,1150,1150
BEGIN DESCRIPTION:
CARTERS CREEK TRIB 8 30.0
END DESCRIPTION:
XS GIS Cut Line= 3
      3589236.33     10205652.28      3588142.54     10203995.23
      3583691.63      10201637.5
#Sta/Elev= 30
  2035.2  245.48  2666.3  243.71  3389.6  242.32  3850.1   235.8  4201.1  215.15
    4307  215.19  4373.8   214.5  4700.7  214.89  4934.2  217.17  4968.8  205.67
  4971.5  205.17  4974.8  205.67  5016.5  208.18  5028.3  215.04  5044.2  217.26
  5301.2  214.82  5709.2  216.71  5741.3  212.93  6074.5  214.36  6330.3     214
  6833.5  215.01  6933.3  215.25  7042.7  214.85  7198.1  215.16    7375  220.64
  7797.1  241.67  8055.4  238.72  8423.7  247.28  8700.4  246.15  9057.5  247.78
#Mann= 16 ,-1 , 0
  2035.2     .05       0  2666.3     .16       0  4201.1     .05       0
    4307     .16       0  4373.8     .05       0  4700.7     .16       0
  4968.8     .07       0  4974.8     .16       0  5301.2     .12       0
  6074.5     .16       0  6330.3     .12       0  6833.5     .16       0
  6933.3      .1       0  7042.7     .16       0    7375     .05       0
  8700.4     .16       0
Bank Sta=4934.2,5044.2
XS Rating Curve= 0 ,0
Exp/Cntr=0.3,0.1

Type RM Length L Ch R = 1 ,28626   ,1527,1527,1527
BEGIN DESCRIPTION:
CARTERS CREEK TRIB 8 29.0
END DESCRIPTION:
XS GIS Cut Line= 4
       3589171.2     10204545.47      3588748.03     10203709.97
      3586147.77     10200996.53      3584136.77     10199879.83
#Sta/Elev= 30
  2872.6  241.31  3455.6  243.57  3901.2  223.24  4033.4  218.89  4042.6   218.4
    4184   216.4  4458.9  213.66  4943.7  214.75  4976.2  205.83  4978.9  205.33
  4982.2  205.83  5014.4  206.02  5035.8  215.29  5204.2   214.2  6574.2  213.27
  6754.5  213.56  6775.6  207.51  6832.7  212.54  6945.4  209.04  7122.1  217.79
  7459.6  219.67  8192.2   239.3    8521  239.96    8738  230.67  9071.7  230.34
  9072.9  230.34  9673.7  245.48  9715.8  247.17    9801  248.79  9867.6  249.06
#Mann= 19 ,-1 , 0
  2872.6     .16       0  3901.2      .1       0  4033.4     .16       0
  4042.6      .1       0    4184     .05       0  4458.9     .16       0
  4976.2     .07       0  4982.2     .16       0  5204.2     .12       0
  6574.2     .16       0  6832.7     .12       0  7459.6     .16       0
  8192.2     .05       0    8521     .16       0  9071.7     .05       0
  9072.9     .16       0  9673.7     .05       0  9715.8     .16       0
    9801     .05       0
Bank Sta=4943.7,5035.8
XS Rating Curve= 0 ,0
Exp/Cntr=0.3,0.1

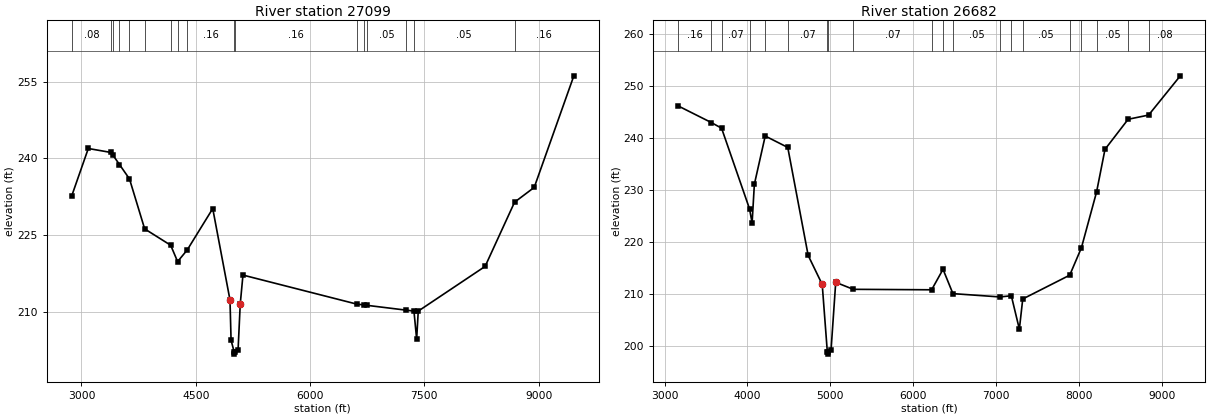
Type RM Length L Ch R = 1 ,27099   ,417,417,417
BEGIN DESCRIPTION:
CARTERS CREEK TRIB 8 28.0
END DESCRIPTION:
XS GIS Cut Line= 3
      3590017.58     10203666.61      3589418.91     10202361.11
      3585938.87     10198560.37
#Sta/Elev= 30
  2871.5  232.61    3090  241.93  3389.1  241.15  3412.3  240.65  3499.2  238.79
  3630.5  235.97  3829.5   226.2  4170.8     223  4261.8   219.8  4387.2  222.06
  4722.8  230.17  4949.1  212.29  4963.3  204.41  5002.8  202.19  5005.6  201.69
  5008.8  202.19  5055.2  202.51  5083.5  211.47  5119.3  217.16  6609.8  211.49
  6701.9  211.32  6751.2  211.23  7258.2   210.3    7363  210.11  7398.4  204.61
  7419.4  210.11  8296.9  218.86  8683.1  231.42  8941.3  234.32    9461  256.15
#Mann= 17 ,-1 , 0
  2871.5     .08       0  3389.1     .05       0  3412.3     .08       0
  3499.2     .05       0  3630.5     .16       0  3829.5     .05       0
  4170.8     .16       0  4261.8     .05       0  4387.2     .16       0
  5002.8     .07       0  5008.8     .16       0  6609.8     .05       0
  6701.9     .16       0  6751.2     .05       0  7258.2     .16       0
    7363     .05       0  8683.1     .16       0
Bank Sta=4949.1,5083.5
XS Rating Curve= 0 ,0
Exp/Cntr=0.3,0.1

Type RM Length L Ch R = 1 ,26682   ,648,648,648
BEGIN DESCRIPTION:
CARTERS CREEK TRIB 8 27.0
END DESCRIPTION:
XS GIS Cut Line= 3
       3590256.3     10202928.75      3589303.89     10201694.03
      3586283.09     10198357.24
#Sta/Elev= 30
  3162.9  246.22  3563.3  243.01  3687.3  241.92  4024.7  226.36  4055.8  223.65
    4083   231.1    4214  240.41  4486.1  238.21  4732.3  217.38  4901.9  211.78
  4963.2  198.84  4965.9  198.34  4969.2  198.84  5008.7  199.19  5064.8  212.19
  5276.7  210.84  6222.3  210.75  6359.8   214.7  6479.2  210.01    7047  209.37
    7184   209.6    7281  203.16  7321.9  208.98  7888.8  213.57  8029.8  218.85
  8212.9  229.62  8314.4  237.84  8593.6  243.64  8840.7  244.45  9223.3  252.02
#Mann= 20 ,-1 , 0
  3162.9     .16       0  3563.3      .1       0  3687.3     .07       0
  4024.7     .07       0    4214     .07       0  4486.1     .07       0
  4963.2     .07       0  4969.2     .05       0  5276.7     .07       0
  6222.3     .07       0  6359.8     .16       0  6479.2     .05       0
    7047     .05       0    7184     .08       0  7321.9     .05       0
  7888.8     .05       0  8029.8     .16       0  8212.9     .05       0
  8593.6     .05       0  8840.7     .08       0
Bank Sta=4901.9,5064.8
XS Rating Curve= 0 ,0
Exp/Cntr=0.3,0.1