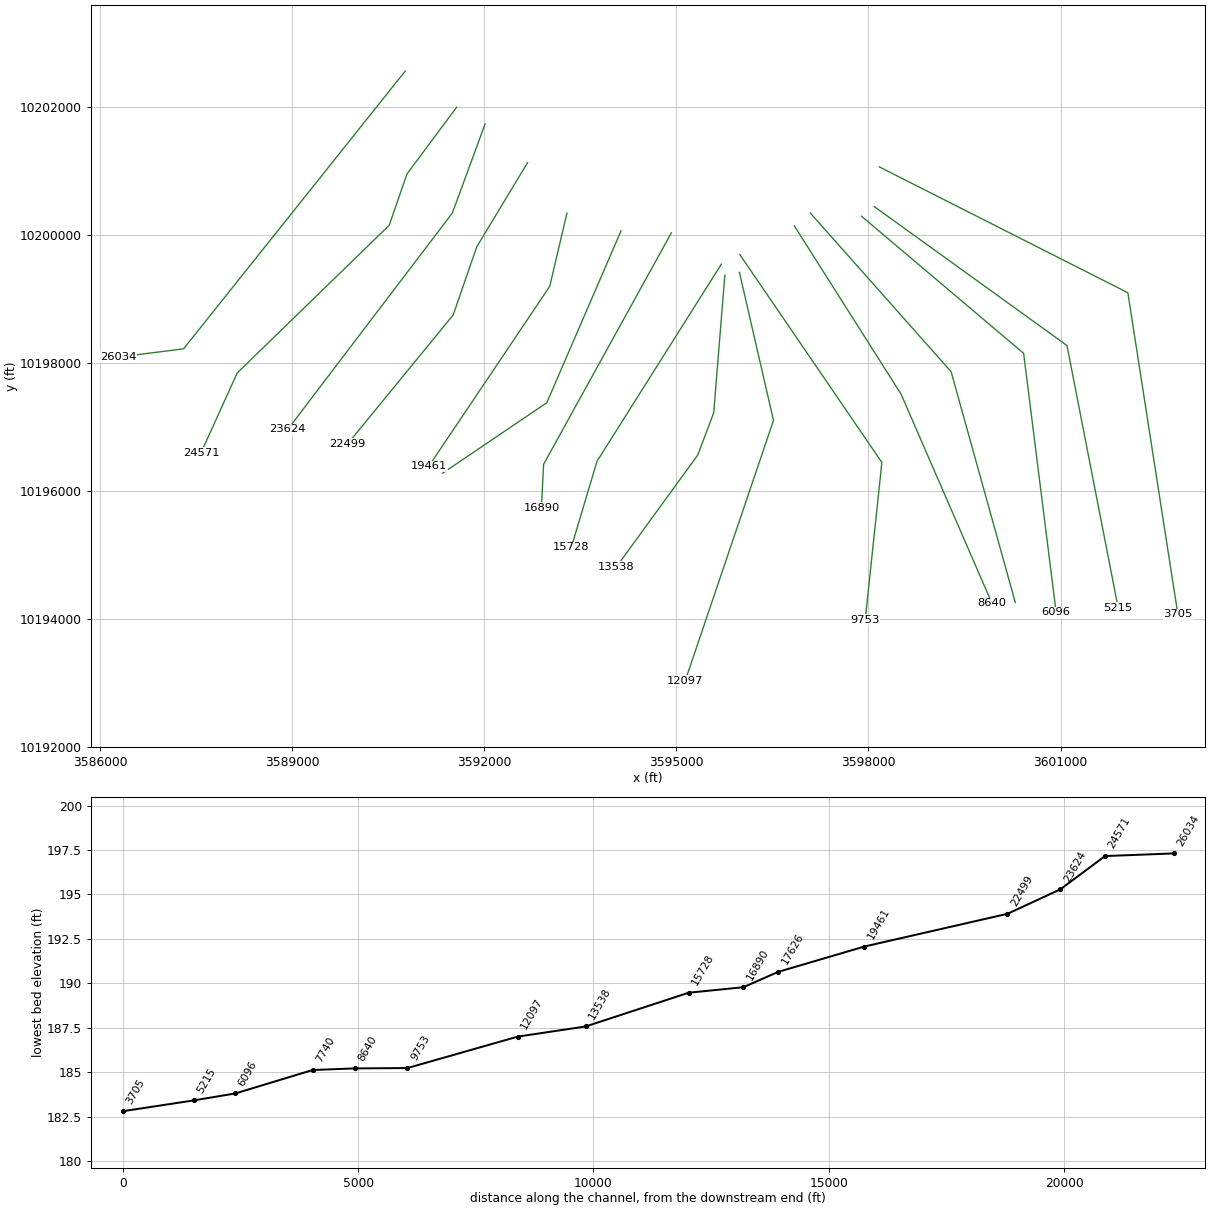
HEC-RAS study CARTERS CREEK.prj: CARTERS CREEK Base Level Engineering

--- CARTERS CREEK.g01 (geometry) --- (continued)

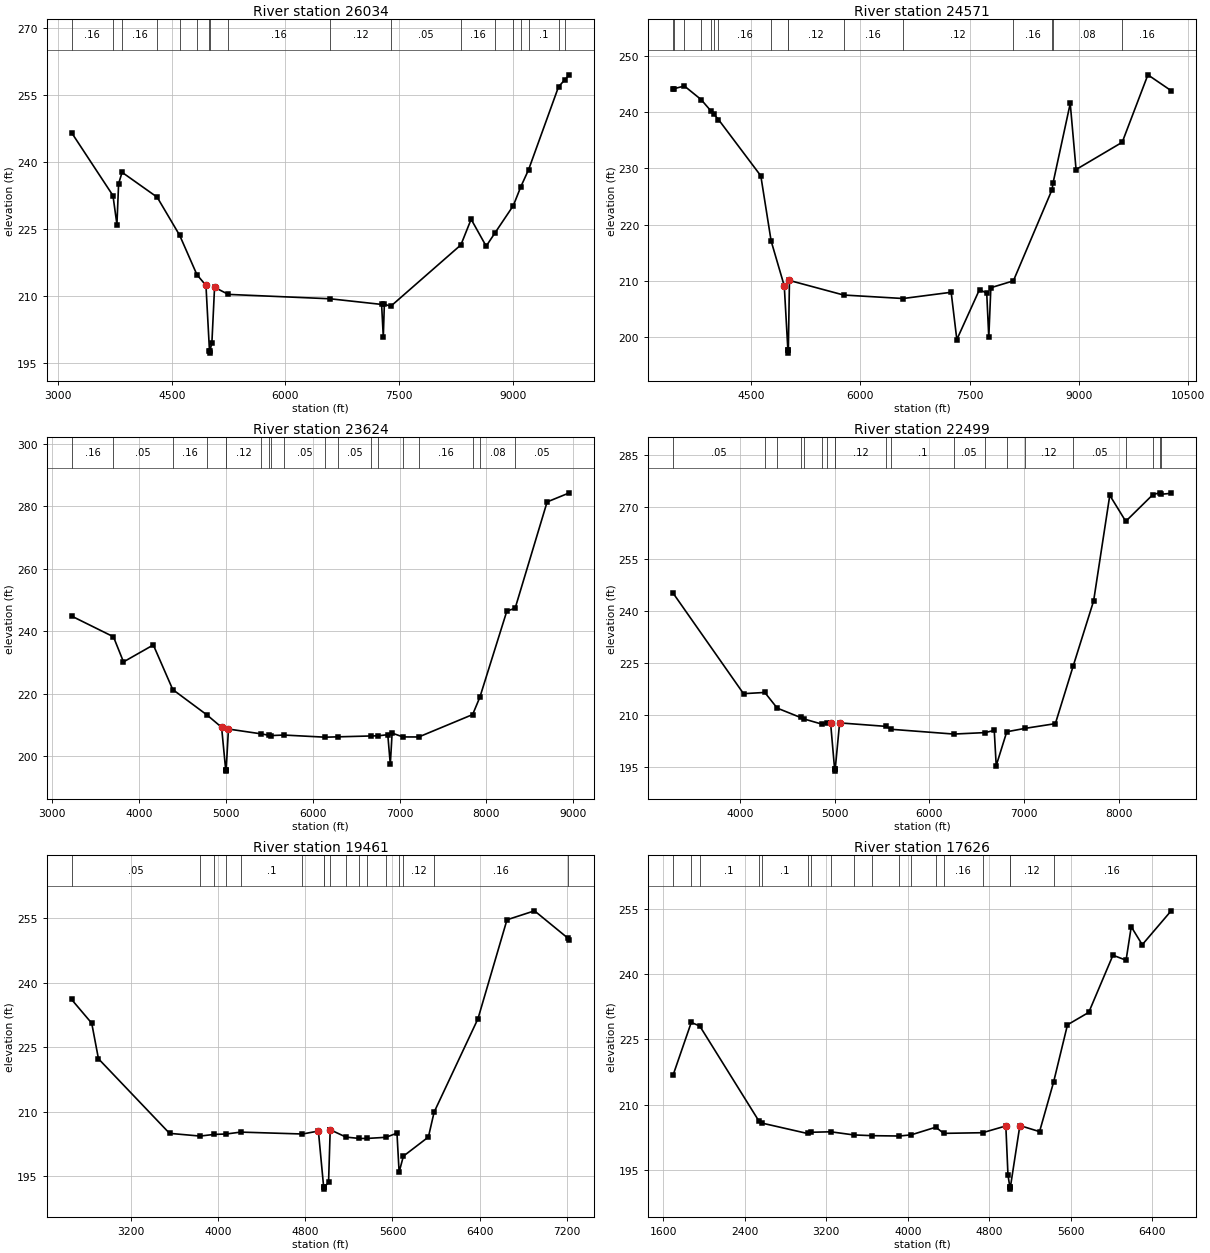
Type RM Length L Ch R = 1 ,26034   ,1463,1463,1463
BEGIN DESCRIPTION:
CARTERS CREEK TRIB 8 24.0
END DESCRIPTION:
XS GIS Cut Line= 4
      3590766.29     10202559.83      3590039.26     10201648.34
      3587304.88     10198219.52      3586292.07     10198091.64
#Sta/Elev= 30
  3176.7  246.57  3723.3   232.5  3775.6  226.04  3797.8  235.17  3843.6   237.7
  4306.5  232.15  4604.3  223.61  4831.7  214.83  4950.8  212.44  4997.4  197.81
  5000.1  197.31  5003.4  197.81  5029.1  199.61  5064.4  212.01  5246.2  210.43
  6590.1  209.45  7269.5  208.19  7291.9  200.89  7305.8  208.23  7390.4  207.78
  8316.4  221.49  8451.3  227.22  8649.8   221.2  8764.5  224.12  9008.3  230.27
  9107.4  234.49  9209.6  238.28  9604.9   256.8  9687.1  258.36  9749.1  259.48
#Mann= 18 ,-1 , 0
  3176.7     .16       0  3723.3     .12       0  3843.6     .16       0
  4306.5     .12       0  4604.3     .16       0  4831.7     .12       0
  4997.4     .07       0  5003.4     .12       0  5246.2     .16       0
  6590.1     .12       0  7390.4     .05       0  8316.4     .16       0
  8764.5     .05       0  9008.3     .16       0  9107.4     .08       0
  9209.6      .1       0  9604.9     .05       0  9687.1      .1       0
Bank Sta=4950.8,5064.4
XS Rating Curve= 0 ,0
Exp/Cntr=0.3,0.1

Type RM Length L Ch R = 1 ,24571   ,947,947,947
BEGIN DESCRIPTION:
CARTERS CREEK TRIB 8 23.0
END DESCRIPTION:
XS GIS Cut Line= 5
      3591569.19     10201995.54       3590794.3     10200952.62
      3590516.69     10200150.94      3588142.11     10197841.64
      3587576.65     10196593.01
#Sta/Elev= 30
  3435.4  244.14  3446.3  244.18  3587.6  244.65  3816.4  242.25  3955.1  240.17
  3990.6  239.65  4055.3  238.69  4636.2  228.68  4777.7   217.1    4958  209.11
  5007.9  197.66  5010.6  197.16  5013.9  197.66  5029.2  210.08  5772.5  207.49
  6588.1  206.87  7247.8  207.98  7325.5  199.57  7636.7  208.47  7735.7   207.8
    7764  199.94  7792.3  208.79  8101.4  210.01  8632.6  226.25  8645.3   227.4
  8881.3  241.55  8961.4   229.8  9594.5  234.65  9946.8  246.64 10266.1  243.82
#Mann= 16 ,-1 , 0
  3435.4     .16       0  3446.3      .1       0  3587.6     .16       0
  3816.4      .1       0  3955.1     .16       0  3990.6      .1       0
  4055.3     .16       0  4777.7     .12       0  5007.9     .07       0
  5013.9     .12       0  5772.5     .16       0  6588.1     .12       0
  8101.4     .16       0  8632.6     .05       0  8645.3     .08       0
  9594.5     .16       0
Bank Sta=4958,5029.2
XS Rating Curve= 0 ,0
Exp/Cntr=0.3,0.1

Type RM Length L Ch R = 1 ,23624   ,1125,1125,1125
BEGIN DESCRIPTION:
CARTERS CREEK TRIB 8 21.0
END DESCRIPTION:
XS GIS Cut Line= 3
       3592014.1     10201735.18      3591502.69     10200342.37
      3588932.47     10196960.81
#Sta/Elev= 30
  3224.1  244.85  3706.3  238.23  3821.9   230.2  4165.3  235.62    4389  221.36
  4784.5  213.21  4951.1  209.31    4998  195.79  5000.7  195.29    5004  195.79
  5030.1  208.74  5409.3  207.19  5496.9  206.74  5514.4  206.65  5669.5  206.82
    6143  206.14  6289.9  206.25  6673.2  206.53  6750.7  206.58  6864.2  206.93
  6893.2  197.45  6914.1  207.44    7039  206.22  7220.6  206.21    7841  213.37
  7924.3  218.93  8234.5  246.43  8330.5  247.37  8698.3  281.33  8955.3  284.24
#Mann= 19 ,-1 , 0
  3224.1     .16       0  3706.3     .05       0    4389     .16       0
  4784.5     .12       0    4998     .07       0    5004     .12       0
  5409.3      .1       0  5496.9     .12       0  5514.4      .1       0
  5669.5     .05       0    6143     .16       0  6289.9     .05       0
  6673.2      .1       0  6750.7     .05       0    7039     .12       0
  7220.6     .16       0    7841     .05       0  7924.3     .08       0
  8330.5     .05       0
Bank Sta=4951.1,5030.1
XS Rating Curve= 0 ,0
Exp/Cntr=0.3,0.1

Type RM Length L Ch R = 1 ,22499   ,3038,3038,3038
BEGIN DESCRIPTION:
CARTERS CREEK TRIB 8 20.0
END DESCRIPTION:
XS GIS Cut Line= 4
      3592675.96     10201127.47      3591883.88     10199814.57
      3591515.54     10198749.45       3589866.4     10196733.89
#Sta/Elev= 30
  3292.1  245.07  4034.7  216.21  4259.6  216.56    4391  212.05  4637.3  209.36
  4669.9  208.96  4860.9  207.46  4919.9  207.83  4955.5  207.75  4998.1  194.41
  5000.9  193.91  5004.1  194.41  5050.7   207.8  5537.6   206.8  5598.7  205.95
  6257.6  204.58  6586.8     205  6685.9  205.62  6706.7   195.5  6818.4  205.24
  7011.6  206.22  7332.1  207.58  7519.9   224.1  7736.8  242.92  7907.6  273.32
  8076.5  265.83  8364.4  273.54  8435.7  274.03  8453.6  273.62  8556.7  273.89
#Mann= 20 ,-1 , 0
  3292.1     .05       0  4259.6     .16       0    4391     .05       0
  4637.3     .16       0  4669.9     .05       0  4860.9     .12       0
  4919.9     .05       0  4998.1     .07       0  5004.1     .12       0
  5537.6     .16       0  5598.7      .1       0  6257.6     .05       0
  6586.8     .12       0  6818.4      .1       0  7011.6     .12       0
  7519.9     .05       0  8076.5     .08       0  8364.4     .05       0
  8435.7     .08       0  8453.6     .05       0
Bank Sta=4955.5,5050.7
XS Rating Curve= 0 ,0
Exp/Cntr=0.3,0.1

Type RM Length L Ch R = 1 ,19461   ,1835,1835,1835
BEGIN DESCRIPTION:
CARTERS CREEK TRIB 8 19.0
END DESCRIPTION:
XS GIS Cut Line= 3
      3593292.09      10200341.6       3593023.2     10199196.08
      3591135.18     10196385.75
#Sta/Elev= 30
  2659.5  236.08  2844.3  230.56    2906  222.31  3557.4  205.01    3837  204.38
  3967.5  204.77  4076.9  204.86  4209.3   205.3    4775  204.86  4921.4  205.54
  4969.4  192.57  4972.1  192.07  4975.4  192.57  5014.4  193.61  5029.4  205.76
  5031.3  205.83  5174.6  204.14  5296.2  203.83  5365.7  203.83  5539.4  204.09
  5641.4  205.05    5661  196.01  5700.2  199.72  5929.4  204.16  5981.7  209.93
  6383.4  231.59  6649.5  254.56  6901.5  256.64  7206.6  250.32  7221.8  249.77
#Mann= 17 ,-1 , 0
  2659.5     .05       0    3837     .12       0  3967.5      .1       0
  4076.9     .05       0  4209.3      .1       0    4775     .12       0
  4969.4     .07       0  4975.4     .12       0  5031.3     .05       0
  5174.6      .1       0  5296.2     .05       0  5365.7      .1       0
  5539.4     .12       0    5661     .05       0  5700.2     .12       0
  5981.7     .16       0  7206.6      .1       0
Bank Sta=4921.4,5029.4
XS Rating Curve= 0 ,0
Exp/Cntr=0.3,0.1

Type RM Length L Ch R = 1 ,17626   ,736,736,736
BEGIN DESCRIPTION:
CARTERS CREEK TRIB 8 17.0
END DESCRIPTION:
XS GIS Cut Line= 3
      3594136.82     10200063.37      3592977.04     10197377.26
      3591352.17     10196277.23
#Sta/Elev= 30
  1698.2  216.92  1874.7  228.87  1958.1  228.05  2536.2  206.35  2567.6  205.79
  3015.9   203.4    3047  203.68  3244.2  203.79  3470.3  203.07    3653   202.9
  3918.1  202.82  4034.1  203.09  4275.1  204.84  4353.7  203.43  4734.8  203.58
    4963  205.13    4984   193.9    5002  191.14  5004.8  190.64    5008  191.14
  5100.8  205.22  5294.1  203.83  5431.5  215.16  5568.2  228.33  5777.2  231.18
  6014.6  244.29  6143.4  243.14  6194.3  250.82  6302.2   246.7  6586.2  254.47
#Mann= 18 ,-1 , 0
  1698.2     .16       0  1874.7     .05       0  1958.1      .1       0
  2536.2     .12       0  2567.6      .1       0  3015.9     .16       0
    3047     .12       0  3244.2     .16       0  3470.3     .12       0
    3653      .1       0  3918.1     .12       0  4034.1     .16       0
  4275.1      .1       0  4353.7     .16       0  4734.8     .12       0
    5002     .07       0    5008     .12       0  5431.5     .16       0
Bank Sta=4963,5100.8
XS Rating Curve= 0 ,0
Exp/Cntr=0.3,0.1

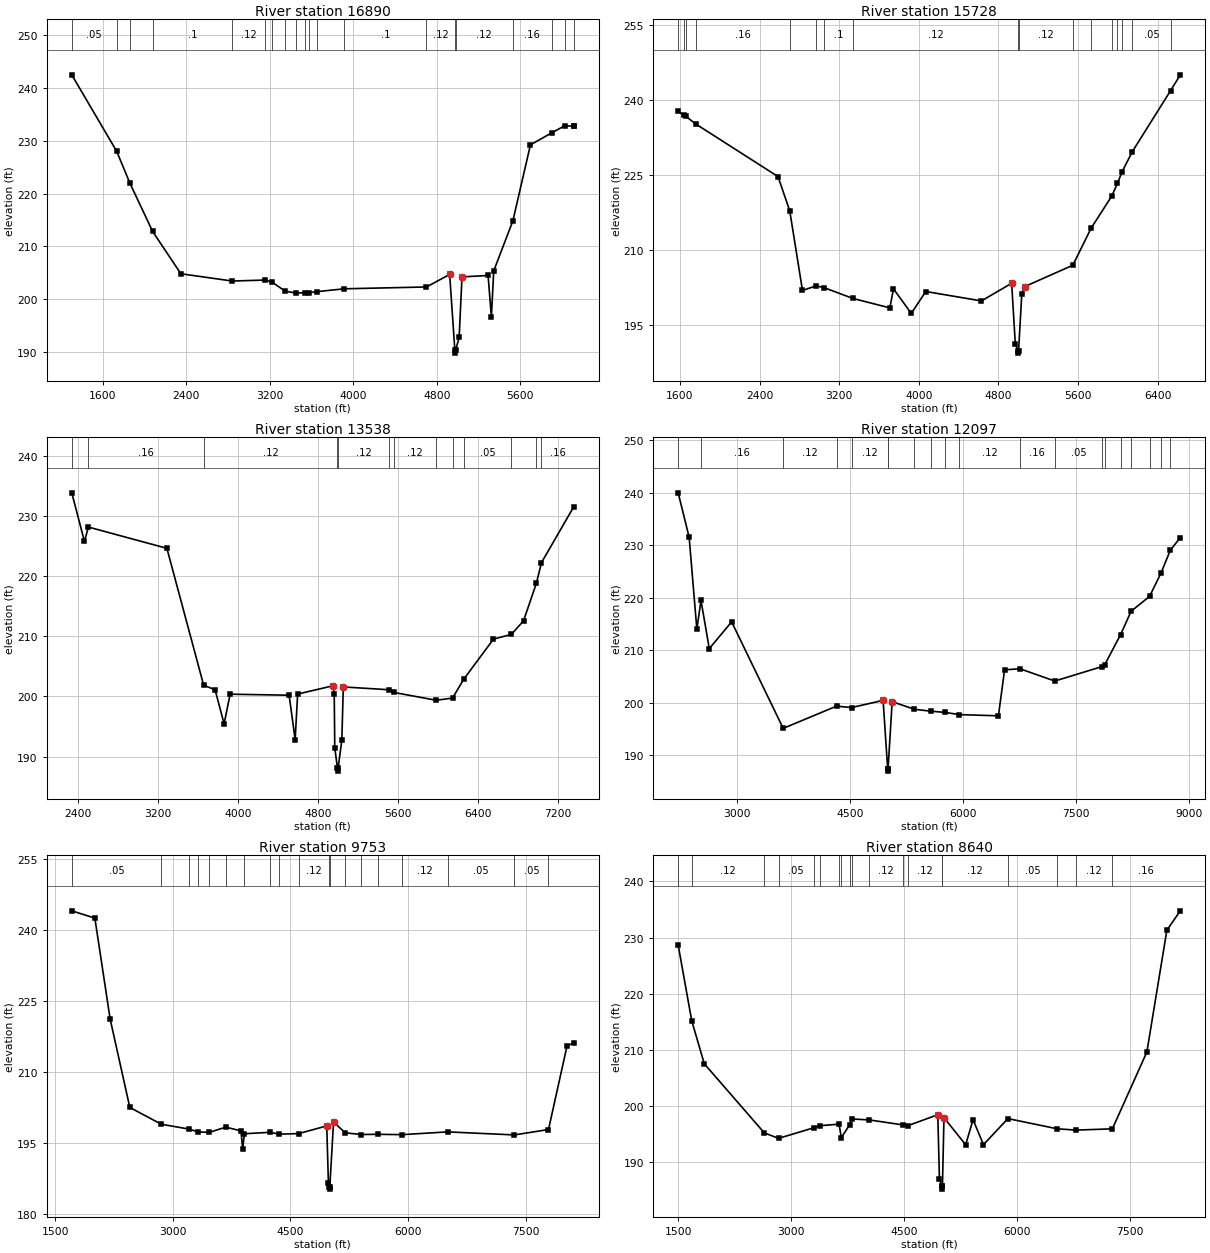
Type RM Length L Ch R = 1 ,16890   ,1162,1162,1162
BEGIN DESCRIPTION:
CARTERS CREEK TRIB 8 16.0
END DESCRIPTION:
XS GIS Cut Line= 3
      3594922.06     10200031.56      3592927.18     10196415.16
      3592893.04     10195735.64
#Sta/Elev= 30
  1303.8  242.48    1734     228  1860.4  221.98  2078.1  212.83    2349  204.81
  2841.5  203.43  3157.3  203.62  3225.3  203.19    3348  201.51  3454.7  201.15
  3538.8  201.23  3578.8  201.24  3656.5  201.43  3913.6  201.96  4702.1  202.31
    4924  204.68    4974  190.28  4976.8  189.78    4980  190.28  5014.8  192.74
  5042.3  204.22  5292.2  204.48  5323.7  196.63  5346.1  205.35  5529.6  214.83
  5697.8  229.22  5902.9  231.51  6026.6  232.84    6113  232.75  6114.3  232.71
#Mann= 20 ,-1 , 0
  1303.8     .05       0    1734     .16       0  1860.4     .16       0
  2078.1      .1       0  2841.5     .12       0  3157.3      .1       0
  3225.3     .05       0    3348     .05       0  3454.7      .1       0
  3538.8     .05       0  3578.8      .1       0  3656.5     .05       0
  3913.6      .1       0  4702.1     .12       0    4974     .07       0
    4980     .12       0  5529.6     .16       0  5902.9     .05       0
  6026.6     .08       0    6113      .1       0
Bank Sta=4924,5042.3
XS Rating Curve= 0 ,0
Exp/Cntr=0.3,0.1

Type RM Length L Ch R = 1 ,15728   ,2190,2190,2190
BEGIN DESCRIPTION:
CARTERS CREEK TRIB 8 14.0
END DESCRIPTION:
XS GIS Cut Line= 3
       3595703.3     10199543.26      3593761.05     10196461.71
      3593359.62     10195116.39
#Sta/Elev= 30
  1582.6  237.71  1638.4  236.89  1658.4  236.71  1757.5  235.19  2585.8  224.68
    2704  217.84  2831.8  201.97  2970.5  202.89  3052.5   202.5  3337.8  200.38
  3709.9  198.49  3746.4  202.29  3925.3  197.39  4071.3  201.76  4630.4  199.88
  4934.1   203.4  4970.6  191.36  4997.7  189.97  5000.4  189.47  5003.7  189.97
  5036.1  201.31  5064.7  202.73  5548.9     207  5732.3  214.37  5939.9  220.79
  5997.7  223.33  6043.6  225.64  6147.4  229.67  6531.4  241.82  6629.1  244.97
#Mann= 17 ,-1 , 0
  1582.6      .1       0  1638.4     .16       0  1658.4      .1       0
  1757.5     .16       0    2704     .12       0  2970.5     .16       0
  3052.5      .1       0  3337.8     .12       0  4997.7     .07       0
  5003.7     .12       0  5548.9     .16       0  5732.3     .05       0
  5939.9      .1       0  5997.7     .05       0  6043.6      .1       0
  6147.4     .05       0  6531.4     .16       0
Bank Sta=4934.1,5064.7
XS Rating Curve= 0 ,0
Exp/Cntr=0.3,0.1

Type RM Length L Ch R = 1 ,13538   ,1441,1441,1441
BEGIN DESCRIPTION:
CARTERS CREEK TRIB 8 12.0
END DESCRIPTION:
XS GIS Cut Line= 4
      3595757.58     10199369.69      3595583.96     10197221.25
       3595334.4     10196559.36      3594066.02     10194813.98
#Sta/Elev= 30
  2338.8  233.91  2465.5  225.82    2505  228.21  3289.9  224.67  3657.6  201.86
  3771.5  201.13  3861.8  195.45    3922  200.38  4511.8  200.21  4572.2  192.82
    4597   200.4  4953.4  201.79    4963  200.33  4968.3  191.42  4995.5  188.07
  4998.3  187.57  5001.5  188.07  5038.9  192.72  5053.6  201.59  5510.5  201.12
  5555.8  200.68  5983.4  199.37    6146  199.74  6258.1  202.88  6555.1  209.55
  6733.8  210.34  6855.3  212.59  6983.9  218.85  7035.1  222.29  7359.2  231.63
#Mann= 13 ,-1 , 0
  2338.8      .1       0    2505     .16       0  3657.6     .12       0
  4995.5     .07       0  5001.5     .12       0  5510.5     .05       0
  5555.8     .12       0  5983.4     .05       0    6146      .1       0
  6258.1     .05       0  6733.8     .16       0  6983.9      .1       0
  7035.1     .16       0
Bank Sta=4953.4,5053.6
XS Rating Curve= 0 ,0
Exp/Cntr=0.3,0.1

Type RM Length L Ch R = 1 ,12097   ,2344,2344,2344
BEGIN DESCRIPTION:
CARTERS CREEK TRIB 8 10.0
END DESCRIPTION:
XS GIS Cut Line= 3
      3595985.43     10199413.12      3596517.12      10197101.9
      3595139.73      10193034.8
#Sta/Elev= 30
  2221.5  239.98  2367.3   231.5  2469.3  214.03  2524.4  219.49  2634.5  210.32
    2931  215.42  3615.5  195.14  4323.3  199.37  4523.1   199.1  4941.8  200.47
  5002.1   187.5  5004.9     187  5008.1   187.5    5062  200.22  5357.8  198.77
    5571  198.42    5769  198.17    5950  197.76  6472.7  197.53  6554.5  206.28
  6757.5  206.49  7220.4  204.15    7846  206.89  7884.4  207.28  8094.7  212.99
  8233.7  217.43  8479.6  220.27  8632.1  224.75  8754.8  229.06  8887.1  231.46
#Mann= 20 ,-1 , 0
  2221.5     .05       0  2524.4     .16       0  3615.5     .12       0
  4323.3     .16       0  4523.1     .12       0  5002.1     .07       0
  5008.1     .12       0  5357.8      .1       0    5571     .12       0
    5769      .1       0    5950     .12       0  6757.5     .16       0
  7220.4     .05       0    7846      .1       0  7884.4     .08       0
  8094.7     .16       0  8233.7     .05       0  8479.6     .16       0
  8632.1     .05       0  8754.8     .16       0
Bank Sta=4941.8,5062
XS Rating Curve= 0 ,0
Exp/Cntr=0.3,0.1

Type RM Length L Ch R = 1 ,9753    ,1113,1113,1113
BEGIN DESCRIPTION:
CARTERS CREEK TRIB 8 9.0
END DESCRIPTION:
XS GIS Cut Line= 3
      3595992.09     10199691.66      3598209.83     10196444.34
      3597949.59     10193985.03
#Sta/Elev= 30
    1712  243.97  2006.6  242.43    2201  221.17  2452.3  202.47  2855.1  198.92
  3202.8  197.92  3324.7  197.31  3465.5   197.2    3677  198.32    3870  197.52
  3891.7  193.77  3914.1  196.92  4239.3  197.22  4361.7  196.83  4605.5  196.95
  4964.6  198.57  4985.6  186.58  4997.5  185.73  5000.2  185.23  5003.5  185.73
  5051.3  199.38  5201.7  197.11  5404.7  196.76  5617.4   196.8  5925.9  196.73
  6507.2  197.31  7358.3  196.67  7793.3  197.81  8030.3  215.49  8117.4  216.11
#Mann= 19 ,-1 , 0
    1712     .05       0  2855.1      .1       0  3202.8     .05       0
  3324.7     .05       0  3465.5      .1       0    3677     .12       0
  3914.1     .05       0  4239.3      .1       0  4361.7     .16       0
  4605.5     .12       0  4997.5     .07       0  5003.5     .12       0
  5201.7      .1       0  5404.7     .12       0  5617.4     .12       0
  5925.9     .12       0  6507.2     .05       0  7358.3     .05       0
  7793.3     .16       0
Bank Sta=4964.6,5051.3
XS Rating Curve= 0 ,0
Exp/Cntr=0.3,0.1

Type RM Length L Ch R = 1 ,8640    ,900,900,900
BEGIN DESCRIPTION:
CARTERS CREEK TRIB 8 8.0
END DESCRIPTION:
XS GIS Cut Line= 3
      3596842.13      10200141.6      3598509.31     10197512.05
      3599928.58     10194243.84
#Sta/Elev= 30
    1496  228.68  1675.8  215.21  1843.3  207.53  2641.1  195.23    2831  194.25
  3300.1  196.14  3378.7   196.5    3636  196.78  3664.7  194.36  3778.2  196.71
  3813.1   197.7  4038.4  197.53  4478.9  196.66  4553.5  196.53  4947.9  198.46
  4969.7  187.05  5003.8  185.71  5006.5  185.21  5009.8  185.71  5030.2  197.93
  5318.6  193.11  5416.7  197.57  5555.5  193.13  5880.3  197.77  6536.7  195.95
  6787.8  195.72  7269.6  195.95    7728  209.63  7994.1  231.33  8172.6  234.77
#Mann= 19 ,-1 , 0
    1496     .16       0  1675.8     .12       0  2641.1      .1       0
    2831     .05       0  3300.1      .1       0  3378.7     .05       0
    3636     .12       0  3664.7     .16       0  3778.2     .12       0
  3813.1     .16       0  4038.4     .12       0  4478.9      .1       0
  4553.5     .12       0  5003.8     .07       0  5009.8     .12       0
  5880.3     .05       0  6536.7      .1       0  6787.8     .12       0
  7269.6     .16       0
Bank Sta=4947.9,5030.2
XS Rating Curve= 0 ,0
Exp/Cntr=0.3,0.1

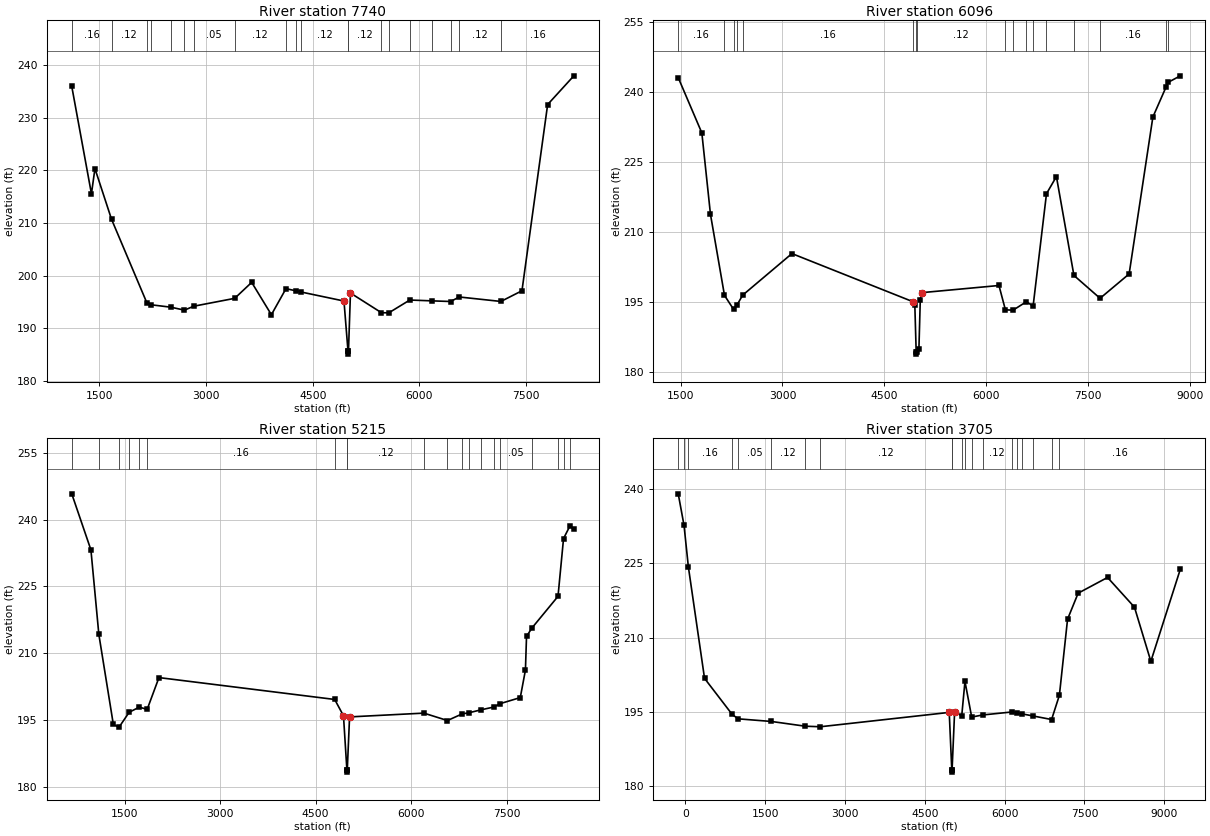
Type RM Length L Ch R = 1 ,7740    ,1644,1644,1644
BEGIN DESCRIPTION:
CARTERS CREEK TRIB 8 7.0
END DESCRIPTION:
XS GIS Cut Line= 3
      3597092.12     10200341.63      3599290.56     10197863.61
      3600293.17     10194256.83
#Sta/Elev= 30
  1113.3  235.94  1389.7  215.56    1439  220.34  1671.8  210.73  2170.4   194.8
  2232.8  194.48  2505.5  194.03  2697.4  193.47  2825.6  194.21  3403.1  195.71
  3641.9  198.74  3918.7   192.6  4123.9  197.55  4271.2  197.11  4337.1  196.91
  4938.8   195.2  4995.9  185.62  4998.6  185.12  5001.9  185.62    5030  196.72
  5465.8  192.98    5569  192.96    5864  195.39  6179.6  195.23  6438.1  195.11
  6558.4  195.97  7144.4  195.12  7440.3  197.15  7801.2   232.5  8169.5  237.95
#Mann= 20 ,-1 , 0
  1113.3     .16       0  1671.8     .12       0  2170.4      .1       0
  2232.8     .12       0  2505.5      .1       0  2697.4      .1       0
  2825.6     .05       0  3403.1     .12       0  4123.9     .16       0
  4271.2     .05       0  4337.1     .12       0  4995.9     .07       0
  5001.9     .12       0  5465.8      .1       0    5569     .12       0
    5864     .05       0  6179.6      .1       0  6438.1     .05       0
  6558.4     .12       0  7144.4     .16       0
Bank Sta=4938.8,5030
XS Rating Curve= 0 ,0
Exp/Cntr=0.3,0.1

Type RM Length L Ch R = 1 ,6096    ,881,881,881
BEGIN DESCRIPTION:
CARTERS CREEK TRIB 8 5.0
END DESCRIPTION:
XS GIS Cut Line= 3
       3597892.1     10200291.65      3600423.37     10198150.07
      3600931.19     10194100.56
#Sta/Elev= 30
    1464  243.14  1811.7  231.28  1939.2  213.77  2145.3  196.41  2278.5  193.43
  2332.9  194.42  2412.8  196.45    3139  205.38  4921.8  195.05  4949.4  194.44
  4969.5   184.3  4972.3   183.8  4975.5   184.3  5009.9     185    5030  195.47
    5048  196.99  6189.1  198.53  6283.9  193.31  6396.5  193.23  6593.6  195.05
  6692.2   194.1  6889.3  218.23  7035.6  221.91  7293.6  200.69  7678.7  195.78
  8106.9  201.01  8456.7  234.69  8649.2  241.07  8677.1   242.1  8860.9  243.53
#Mann= 17 ,-1 , 0
    1464     .16       0  2145.3     .12       0  2278.5     .07       0
  2332.9     .12       0  2412.8     .16       0  4921.8     .12       0
  4969.5     .07       0  4975.5     .12       0  6283.9     .07       0
  6396.5     .12       0  6593.6     .16       0  6692.2     .12       0
  6889.3     .16       0  7293.6      .1       0  7678.7     .16       0
  8649.2      .1       0  8677.1     .16       0
Bank Sta=4921.8,5048
XS Rating Curve= 0 ,0
Exp/Cntr=0.3,0.1

Type RM Length L Ch R = 1 ,5215    ,1510,1510,1510
BEGIN DESCRIPTION:
CARTERS CREEK TRIB 8 4.0
END DESCRIPTION:
XS GIS Cut Line= 3
       3598092.1     10200441.64      3601100.46      10198271.6
      3601898.84     10194175.53
#Sta/Elev= 30
   672.1  245.76   972.7   233.2  1097.3  214.25  1324.8  194.09  1413.8  193.47
  1573.1  196.82  1732.4  197.97  1855.8  197.47  2040.8  204.59  4800.1  199.69
  4937.8  196.04  4991.5  183.91  4994.2  183.41  4997.5  183.91  5033.5  195.78
  6200.3  196.63  6570.4  194.97    6803  196.47  6902.4  196.69  7101.1  197.38
  7299.9     198  7399.2  198.76  7713.6  200.11  7794.5  206.27  7811.7  213.81
    7896  215.69  8305.8  222.79  8392.8  235.74  8492.2  238.54  8554.6  237.79
#Mann= 20 ,-1 , 0
   672.1     .16       0  1097.3     .05       0  1413.8     .07       0
  1573.1     .16       0  1732.4     .16       0  1855.8     .16       0
  4800.1     .12       0  4991.5     .07       0  4997.5     .12       0
  6200.3     .05       0  6570.4     .12       0    6803      .1       0
  6902.4     .05       0  7101.1      .1       0  7299.9      .1       0
  7399.2     .05       0    7896     .16       0  8305.8     .05       0
  8392.8      .1       0  8492.2     .16       0
Bank Sta=4937.8,5033.5
XS Rating Curve= 0 ,0
Exp/Cntr=0.3,0.1

Type RM Length L Ch R = 1 ,3705    ,0,0,0
BEGIN DESCRIPTION:
CARTERS CREEK TRIB 8 1.0
END DESCRIPTION:
XS GIS Cut Line= 3
      3598170.78      10201062.4      3602050.98     10199096.25
      3602832.23     10194070.21
#Sta/Elev= 30
  -135.3  239.04   -26.4  232.66    54.6  224.32     359  201.75   876.9  194.48
   989.8  193.57  1614.8  193.04  2251.5  192.08  2535.3  191.97    4958  194.87
  5005.6   183.3  5008.4   182.8  5011.6   183.3  5059.2  195.03  5192.6  194.15
  5253.5  201.12    5380  193.93  5586.4  194.35  6138.4  194.96  6225.6  194.78
  6328.3  194.57  6538.4  194.14  6881.9  193.43  7028.2  198.33  7181.8   213.7
  7380.7  218.96  7933.3  222.14  8439.3  216.13  8747.4  205.19    9301   223.8
#Mann= 20 ,-1 , 0
  -135.3     .16       0   -26.4      .1       0    54.6     .16       0
   876.9     .12       0   989.8     .05       0  1614.8     .12       0
  2251.5     .07       0  2535.3     .12       0  5005.6     .07       0
  5011.6     .12       0  5192.6     .16       0  5253.5      .1       0
    5380     .16       0  5586.4     .12       0  6138.4     .05       0
  6225.6      .1       0  6328.3      .1       0  6538.4     .05       0
  6881.9     .12       0  7028.2     .16       0
Bank Sta=4958,5059.2
XS Rating Curve= 0 ,0
Exp/Cntr=0.3,0.1

Chan Stop Cuts=-1
Use User Specified Reach Order=0
Composite Channel Slope=5