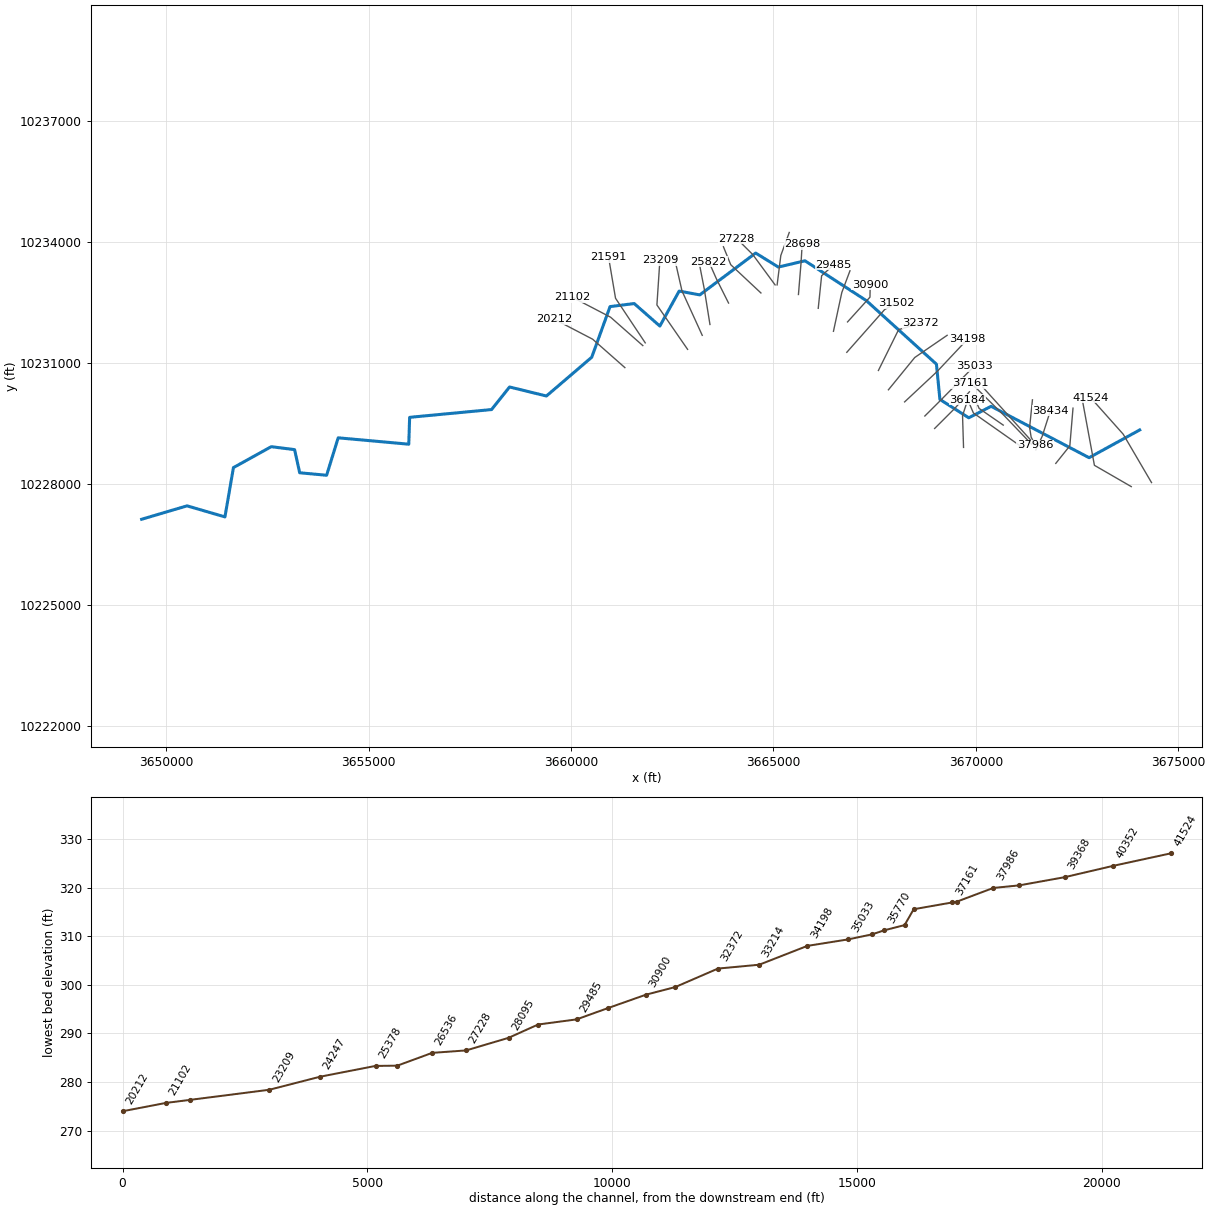
--- CAT CREEK.prj (project) ---

Proj Title=CAT CREEK Base Level Engineering
Current Plan=p01
Default Exp/Contr=0.3,0.1
English Units
Geom File=g01
Flow File=f01
Plan File=p01
Y Axis Title=Elevation
X Axis Title(PF)=Main Channel Distance
X Axis Title(XS)=Station
BEGIN DESCRIPTION:
CAT CREEK
END DESCRIPTION:
DSS Export Rating Curves= 0
DSS Export Rating Curve Sorted= 0
DSS Export Volume Flow Curves= 0
DXF OffsetX= 0
DXF OffsetY= 0
DXF ScaleX= 1
DXF ScaleY= 10

--- CAT CREEK.p01 (plan) ---

Plan Title=Multiple Run
Short Identifier=Multiple
Geom File=g01
Flow File=f01
Subcritical Flow
K Sum by GR= 0
Std Step Tol= 0.01
Critical Tol= 0.01
Num of Std Step Trials= 20
Max Error Tol= 0.3
Flow Tol Ratio= 0.001
Split Flow NTrial= 30
Split Flow Tol= 0.02
Split Flow Ratio= 0.02
Log Output Level= 0
Friction Slope Method= 1
Unsteady Friction Slope Method= 2
Unsteady Bridges Friction Slope Method= 1
Parabolic Critical Depth
Global Vel Dist=  1 , 1 , 1
Global Log Level= 0
CheckData=True
Encroach Param= -1, 0, 0, 0
BEGIN DESCRIPTION:
Multiple Run
END DESCRIPTION:

--- CAT CREEK.f01 (steady flow) ---

Flow Title=Multiple
Program Version=4.10
Number of Profiles= 7
Profile Names=10-year,25-year,50-year,1pct_min,100-year,1pct_plu,500-year
River Rch & RM=CAT CREEK,Reach-1         ,41524
     570     751     895     781    1056    1428    1468
River Rch & RM=CAT CREEK,Reach-1         ,37257
    1199    1641    2007    1791    2422    3276    3533
River Rch & RM=CAT CREEK,Reach-1         ,36370
    1199    1641    2007    1791    2422    3276    3533
River Rch & RM=CAT CREEK,Reach-1         ,32372
    1478    2045    2518    2263    3060    4138    4521
River Rch & RM=CAT CREEK,Reach-1         ,27228
    1850    2583    3199    2889    3907    5284    5833
River Rch & RM=CAT CREEK,Reach-1         ,23209
    2092    2934    3645    3301    4464    6036    6699
River Rch & RM=CAT CREEK,Reach-1         ,19045
    2139    2993    3711    3354    4536    6134    6781
River Rch & RM=CAT CREEK,Reach-1         ,11370
    2214    3100    3845    3476    4701    6357    7032
River Rch & RM=CAT CREEK,Reach-1         ,7921
    2653    3740    4663    4233    5725    7742    8641
River Rch & RM=CAT CREEK,Reach-1         ,4839
    2653    3740    4663    4233    5725    7742    8641
Boundary for River Rch & Prof#=CAT CREEK,Reach-1         , 1
Up Type= 0
Dn Type= 3
Dn Slope=0.001
Boundary for River Rch & Prof#=CAT CREEK,Reach-1         , 2
Up Type= 0
Dn Type= 3
Dn Slope=0.001
Boundary for River Rch & Prof#=CAT CREEK,Reach-1         , 3
Up Type= 0
Dn Type= 3
Dn Slope=0.001
Boundary for River Rch & Prof#=CAT CREEK,Reach-1         , 4
Up Type= 0
Dn Type= 3
Dn Slope=0.001
Boundary for River Rch & Prof#=CAT CREEK,Reach-1         , 5
Up Type= 0
Dn Type= 3
Dn Slope=0.001
Boundary for River Rch & Prof#=CAT CREEK,Reach-1         , 6
Up Type= 0
Dn Type= 3
Dn Slope=0.001
Boundary for River Rch & Prof#=CAT CREEK,Reach-1         , 7
Up Type= 0
Dn Type= 3
Dn Slope=0.001
DSS Import GetInterval= 0
DSS Import GetPeak= 0
DSS Import FillOption= 0

--- CAT CREEK.g01 (geometry) ---

Geom Title=Existing Conditions
Program Version=4.10

River Reach=CAT CREEK       ,Reach-1
Reach XY= 30
      3674050.01     10229346.05      3672799.64     10228658.57
      3670379.69     10229932.32      3669827.61     10229647.16
      3669113.81     10230103.15      3669028.43     10230976.41
      3667296.59      10232552.1      3665780.34     10233539.23
      3665122.35     10233383.63      3664561.85     10233731.38
      3663181.32     10232693.83      3662672.05      10232788.4
      3662194.62     10231921.43      3661560.51     10232479.32
      3660965.35     10232404.34      3660511.46      10231147.9
      3659392.02     10230187.49      3658481.62     10230411.63
      3658036.72     10229851.62      3656013.18     10229658.95
      3655991.75     10228993.29      3654247.82      10229150.9
      3653961.61     10228223.26      3653296.77     10228284.65
      3653170.47     10228858.43      3652592.87     10228930.96
      3651659.88     10228412.91      3651450.04     10227191.01
      3650513.79     10227464.89      3649392.33     10227132.51

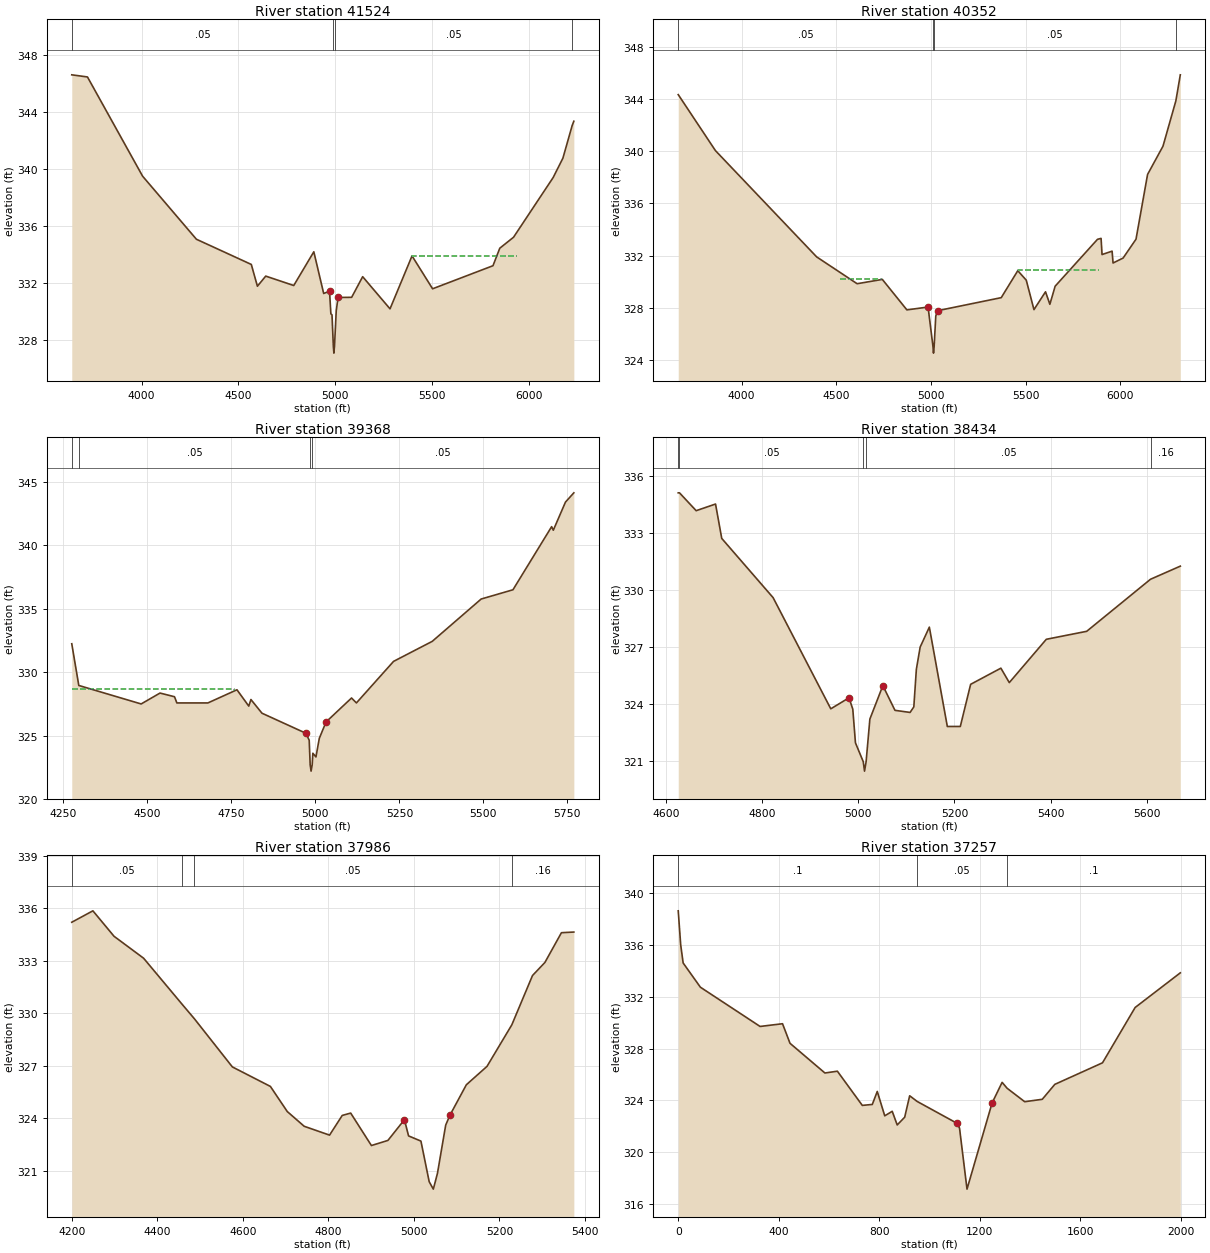
Type RM Length L Ch R = 1 ,41524   ,1172,1172,1172
BEGIN DESCRIPTION:
CAT CREEK 46.0
END DESCRIPTION:
XS GIS Cut Line= 3
      3674342.12     10228041.62      3673642.11     10229241.64
      3672842.13     10230141.62
#Sta/Elev= 30
  3639.6  346.62  3720.7  346.47  4005.5   339.5  4283.4  335.07    4567   333.3
  4598.5  331.77  4641.5  332.48  4786.2  331.82  4889.9  334.19  4940.8  331.26
    4971  331.42    4978  329.83  4983.8  329.76  4990.7  327.57  4993.5  327.07
  4996.7  327.57  5005.7  330.05  5015.2  330.98  5085.3  330.99  5142.2  332.44
  5283.5  330.18  5397.2   333.9  5503.4  331.59  5815.3  333.21  5850.5  334.44
  5921.5  335.21  6126.4  339.41  6176.6  340.77  6224.4  343.06    6233  343.36
#Mann= 4 ,-1 , 0
  3639.6     .05       0  4990.7     .03       0  4996.7     .05       0
  6224.4      .1       0
#XS Ineff= 2 ,-1
 4307.95  4887.5  334.01 5395.45  5939.2  333.89
Permanent Ineff=
       F       F
Bank Sta=4971,5015.2
XS Rating Curve= 0 ,0
Exp/Cntr=0.3,0.1

Type RM Length L Ch R = 1 ,40352   ,984,984,984
BEGIN DESCRIPTION:
CAT CREEK 44.0
END DESCRIPTION:
XS GIS Cut Line= 3
      3673842.13     10227941.63      3672931.15     10228469.69
       3672642.1     10230041.68
#Sta/Elev= 30
  3665.2  344.36  3861.7  340.06  4396.1   331.9  4609.8  329.84    4743  330.17
  4872.7  327.83  4984.5  328.05  5010.5  325.01  5013.2  324.51  5016.5  325.01
  5025.2  327.36  5035.3  327.77  5370.9  328.77  5458.3  330.84  5503.1  330.11
  5543.7  327.85  5604.7  329.22  5627.7  328.26  5655.6  329.65  5879.3  333.25
  5898.1  333.32  5903.2  332.08  5956.3  332.34  5961.4  331.43  6014.4  331.81
  6082.6  333.26  6143.6  338.23    6225   340.4    6293  343.88  6316.5  345.88
#Mann= 4 ,-1 , 0
  3665.2     .05       0  5010.5     .03       0  5016.5     .05       0
    6293     .15       0
#XS Ineff= 2 ,-1
 4517.61  4737.5  330.18 5456.82 5884.66  330.89
Permanent Ineff=
       F       F
Bank Sta=4984.5,5035.3
XS Rating Curve= 0 ,0
Exp/Cntr=0.3,0.1

Type RM Length L Ch R = 1 ,39368   ,934,934,934
BEGIN DESCRIPTION:
CAT CREEK 42.0
END DESCRIPTION:
XS GIS Cut Line= 3
      3671976.81     10228517.09      3672324.04     10228952.35
      3672402.29     10229886.48
#Sta/Elev= 30
    4275  332.24  4295.9  328.95  4481.5  327.49  4537.6  328.35  4580.8  328.06
  4587.8  327.57  4680.1  327.57  4766.6  328.61  4801.8  327.32  4808.2  327.84
  4841.1  326.76  4971.6  325.18  4981.6  324.63  4984.5  322.69  4987.2  322.19
  4990.5  322.69  4992.5   323.6  5001.7  323.31  5011.7  324.78  5031.8  326.07
  5107.6  327.96  5122.1  327.57  5232.7  330.85  5347.8  332.43  5493.4  335.77
    5588   336.5  5703.1  341.48  5708.1   341.2  5744.3  343.42  5769.2  344.15
#Mann= 4 ,-1 , 0
    4275     .08       0  4295.9     .05       0  4984.5     .04       0
  4990.5     .05       0
#XS Ineff= 1 ,-1
 4252.73 4759.09  328.67
Permanent Ineff=
       F
Bank Sta=4971.6,5031.8
XS Rating Curve= 0 ,0
Exp/Cntr=0.3,0.1

Type RM Length L Ch R = 1 ,38434   ,532,532,532
BEGIN DESCRIPTION:
CAT CREEK 40.0
END DESCRIPTION:
XS GIS Cut Line= 3
      3671482.83     10228849.62      3671642.11     10229191.64
      3671844.56     10229827.19
#Sta/Elev= 30
  4625.5  335.14  4628.1  335.14  4662.8   334.2  4703.1  334.55    4716  332.74
  4822.9  329.62  4942.8  323.77  4980.7  324.35  4988.6  323.75  4994.1  321.98
  5010.3  320.99    5013  320.49  5016.3  320.99  5024.1  323.23  5051.1  324.99
  5076.3  323.69  5107.7  323.58  5115.5  323.87  5120.8  325.85  5128.7  327.02
  5147.8  328.07  5185.2  322.84  5212.2  322.84  5233.7  325.06  5296.6  325.91
  5314.1  325.15  5391.1  327.43  5475.1  327.85  5607.8  330.59  5669.8  331.28
#Mann= 5 ,-1 , 0
  4625.5     .08       0  4628.1     .05       0  5010.3     .03       0
  5016.3     .05       0  5607.8     .16       0
Bank Sta=4980.7,5051.1
XS Rating Curve= 0 ,0
Exp/Cntr=0.3,0.1

Type RM Length L Ch R = 1 ,37986   ,744,744,744
BEGIN DESCRIPTION:
CAT CREEK 39.0
END DESCRIPTION:
XS GIS Cut Line= 4
        3671400.       10230093.        3671330.       10229405.
        3671368.       10229169.        3671469.       10228971.
#Sta/Elev= 30
    4200335.19964249.407 335.8524298.814334.39884367.985333.14454456.918330.5465
4486.562329.69124575.495326.93624664.428 325.8224703.954324.3856 4743.48323.5449
4802.769323.04014832.413324.16464852.176324.29894900.652 322.4454939.247322.7375
4977.842323.92244987.491 322.9965016.437322.69915035.734320.37935045.383319.9554
5055.032320.85395074.329323.61095083.978324.16545122.592325.91575170.933326.9678
5228.942329.33975277.283332.15485306.287332.9026 5344.96334.60225373.965334.6396
#Mann= 4 ,-1 , 0
    4200     .05       04456.918     .03       04486.562     .05       0
5228.942     .16       0
Bank Sta=4977.842,5083.978
XS Rating Curve= 0 ,0
Exp/Cntr=0.3,0.1

Type RM Length L Ch R = 1 ,37257   ,90,90,90
XS GIS Cut Line= 2
        3670174.       10230406.        3671344.       10229110.
#Sta/Elev= 30
       0338.6584 9.79547336.024319.59094334.624388.15923332.7522325.7715329.7166
415.0651329.9281444.8297 328.415583.7309 326.118633.3384326.2569732.5536323.6123
772.2397323.6859792.0828324.6908821.8473322.8049851.6118323.1557871.4549322.0992
901.2194 322.699921.0624324.3568 950.827323.91841109.571 322.2271119.493321.8545
1149.257317.13731249.006323.79551288.958325.39461308.935324.93611378.852 323.897
1448.769324.0836 1498.71325.23861688.485326.90551818.331331.18271998.118333.8633
#Mann= 3 ,-1 , 0
       0      .1       0 950.827     .05       01308.935      .1       0
Bank Sta=1109.571,1249.006
XS Rating Curve= 0 ,0
Exp/Cntr=0.3,0.1

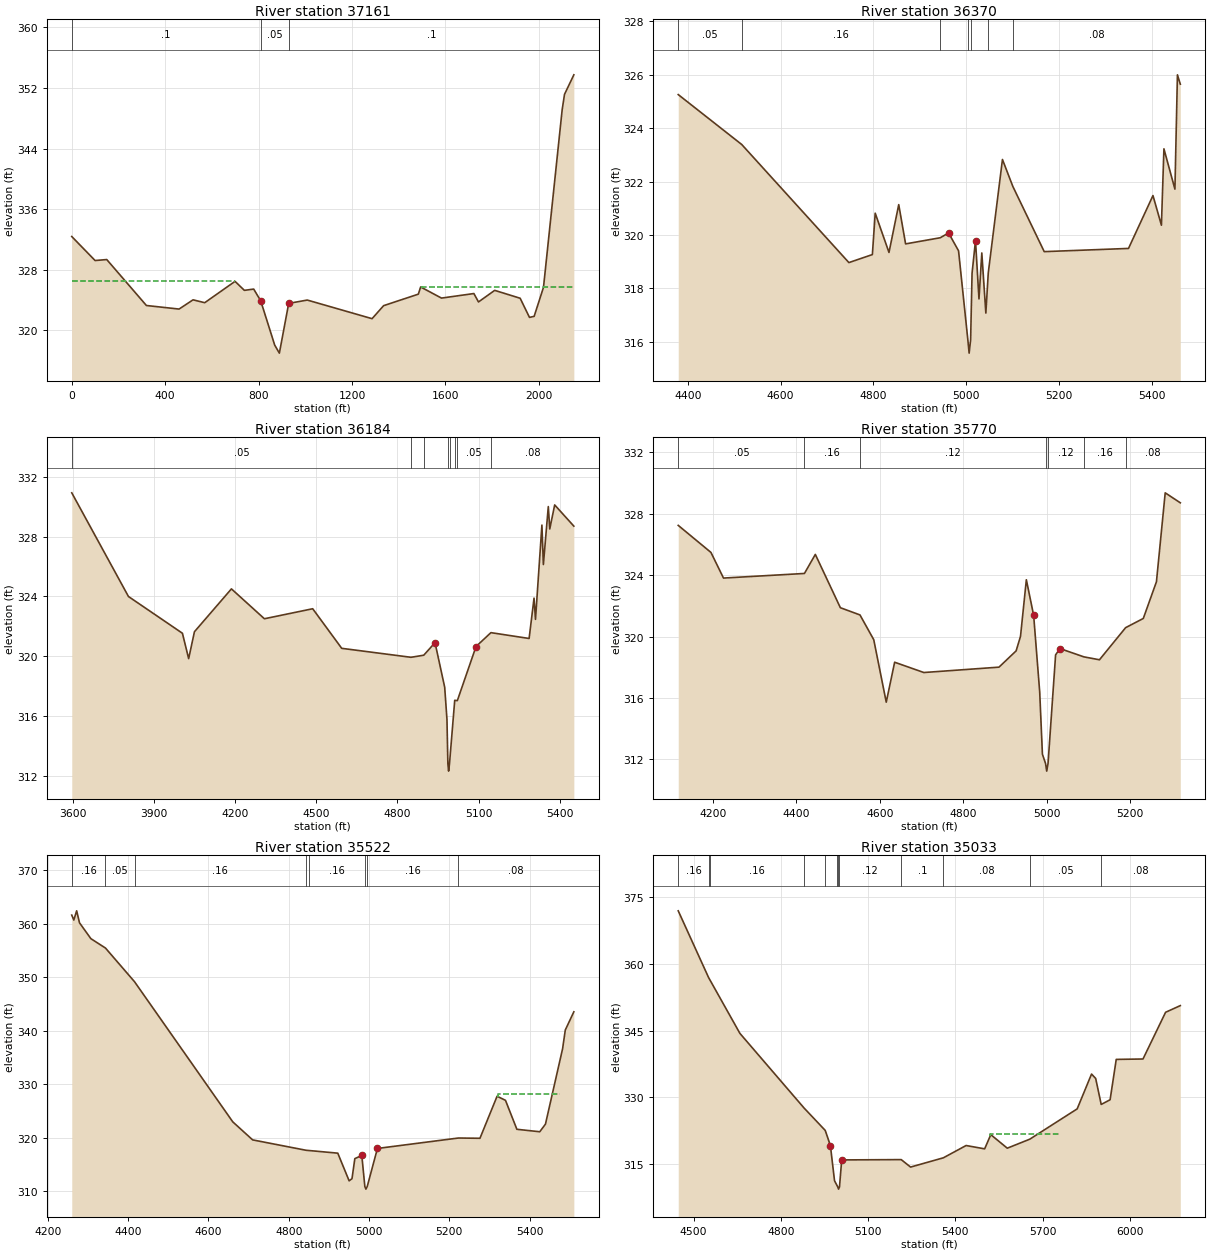
Type RM Length L Ch R = 1 ,37161   ,791,791,791
XS GIS Cut Line= 4
     3671379.326    10228992.546     3670705.715    10229697.407
     3670035.576    10230360.602     3669864.612    10230511.488
#Sta/Elev= 30
       0  332.38    99.9  329.21  149.84  329.34  319.67  323.27  459.52   322.8
  519.46  324.02   569.4  323.64  699.27  326.46  739.23  325.27  779.18  325.44
  809.15  323.89  869.09  318.04  889.07  316.98  929.03  323.55 1008.54  323.99
 1286.01  321.53 1335.56  323.25  1484.2  324.77 1494.11  325.72  1583.3  324.25
 1722.03  324.85 1741.85  323.74 1811.21  325.27 1920.22  324.23 1960.21   321.7
 1980.21  321.84  2020.2  325.67 2100.19  349.13 2110.19  351.16 2150.18  353.74
#Mann= 3 , 0 , 0
       0      .1       0  809.15     .05       0  929.03      .1       0
#XS Ineff= 2 , 0
          699.48  326.46 1494.41          325.77
Permanent Ineff=
       F       F
Bank Sta=809.15,929.03
XS Rating Curve= 0 ,0
Exp/Cntr=0.3,0.1

Type RM Length L Ch R = 1 ,36370   ,186,186,186
BEGIN DESCRIPTION:
CAT CREEK 38.0
END DESCRIPTION:
XS GIS Cut Line= 3
      3670678.41     10229466.53      3670082.69     10229879.76
      3669942.82     10230207.99
#Sta/Elev= 30
  4379.3  325.26  4516.2  323.39    4747  318.97  4797.6  319.27  4803.7  320.82
  4833.4  319.35  4854.4  321.14  4869.2  319.67  4943.9   319.9  4961.8  320.08
  4983.3  319.41  5003.3  316.08  5006.1  315.58  5009.3  316.08  5012.4  318.57
  5019.8  319.79  5027.3  317.61  5033.4  319.33  5042.1  317.08  5047.3  318.58
  5077.9  322.83  5100.3  321.82  5167.9  319.38  5349.5   319.5  5402.2  321.48
  5420.4  320.37  5425.8  323.23  5449.5  321.72  5454.9     326  5461.1  325.65
#Mann= 7 ,-1 , 0
  4379.3     .05       0  4516.2     .16       0  4943.9     .08       0
  5003.3     .07       0  5009.3     .08       0  5047.3     .05       0
  5100.3     .08       0
Bank Sta=4961.8,5019.8
XS Rating Curve= 0 ,0
Exp/Cntr=0.3,0.1

Type RM Length L Ch R = 1 ,36184   ,414,414,414
BEGIN DESCRIPTION:
CAT CREEK 38.1
END DESCRIPTION:
XS GIS Cut Line= 3
      3671165.13     10228903.67      3669941.64     10229766.61
      3669801.22     10230096.15
#Sta/Elev= 30
  3596.7  330.94  3806.2     324  4005.6  321.54  4028.7  319.84    4050  321.64
  4186.7  324.51  4308.6  322.51  4487.1  323.18  4594.3  320.53  4850.4  319.93
  4897.4  320.07  4939.1  320.91  4974.8  317.93  4983.2  315.78  4986.6  312.81
  4989.3  312.31  4992.6  312.81  5011.9  317.05  5021.6  317.03  5090.6  320.65
  5145.6  321.58  5286.8  321.19    5305  323.89  5310.4  322.47  5334.1  328.78
  5339.5  326.14  5357.7  330.02  5363.1  328.52  5381.3  330.13  5452.1  328.71
#Mann= 8 ,-1 , 0
  3596.7     .05       0  4850.4     .08       0  4897.4     .05       0
  4986.6     .04       0  4992.6     .05       0  5011.9     .08       0
  5021.6     .05       0  5145.6     .08       0
Bank Sta=4939.1,5090.6
XS Rating Curve= 0 ,0
Exp/Cntr=0.3,0.1

Type RM Length L Ch R = 1 ,35770   ,248,248,248
BEGIN DESCRIPTION:
CAT CREEK 37.0
END DESCRIPTION:
XS GIS Cut Line= 3
      3669697.75     10228913.24      3669673.29     10229700.62
      3669801.22     10230096.08
#Sta/Elev= 30
    4117  327.24  4195.4  325.48  4225.5  323.81  4419.5  324.11  4445.6  325.35
  4505.6  321.88  4552.6  321.41  4585.6   319.8  4615.6  315.73  4635.7  318.33
  4705.7  317.66  4885.8  318.01  4926.9  319.07  4937.4  320.02  4951.4   323.7
  4968.9  321.38  4983.4  316.39  4989.9  312.34  4997.4  311.74  5000.2  311.24
  5003.4  311.74  5021.5  318.81    5032  319.22  5089.2  318.68  5126.6  318.49
  5189.3  320.58  5231.7  321.18  5263.2  323.57  5284.2  329.36  5320.4  328.71
#Mann= 7 ,-1 , 0
    4117     .05       0  4419.5     .16       0  4552.6     .12       0
  4997.4     .07       0  5003.4     .12       0  5089.2     .16       0
  5189.3     .08       0
Bank Sta=4968.9,5032
XS Rating Curve= 0 ,0
Exp/Cntr=0.3,0.1

Type RM Length L Ch R = 1 ,35522   ,489,489,489
BEGIN DESCRIPTION:
CAT CREEK 36.0
END DESCRIPTION:
XS GIS Cut Line= 3
      3668983.73     10229382.75      3669492.11     10229891.64
      3669842.09     10230291.63
#Sta/Elev= 30
  4259.4  361.61  4264.5  360.69  4271.6  362.41  4278.7  360.17    4307  357.21
  4343.3  355.46  4415.8  349.16  4660.5  322.98    4710  319.61  4843.1  317.67
  4850.9  317.62  4922.1  317.13  4950.4  311.96  4957.5  312.36  4964.6  316.11
    4982   316.7  4989.5  310.91  4992.2  310.41  4995.5  310.91  5020.9  318.01
  5222.7  319.96  5276.3  319.91    5319  327.77  5339.9     327  5368.3  321.59
  5425.3  321.13  5439.5  322.56  5482.2  336.65  5488.9  340.14  5510.2  343.54
#Mann= 8 ,-1 , 0
  4259.4     .16       0  4343.3     .05       0  4415.8     .16       0
  4843.1     .12       0  4850.9     .16       0  4989.5     .07       0
  4995.5     .16       0  5222.7     .08       0
#XS Ineff= 1 ,-1
 5321.59 5475.91   328.1
Permanent Ineff=
       F
Bank Sta=4982,5020.9
XS Rating Curve= 0 ,0
Exp/Cntr=0.3,0.1

Type RM Length L Ch R = 1 ,35033   ,835,835,835
BEGIN DESCRIPTION:
CAT CREEK 35.0
END DESCRIPTION:
XS GIS Cut Line= 3
      3668742.12     10229691.66      3669142.11     10230091.64
      3669954.76     10230920.44
#Sta/Elev= 30
  4447.4  371.97  4551.8  356.96  4557.9  356.25  4659.5   344.4    4880  327.62
  4952.9  322.57  4970.6  319.17  4984.8  311.26  4993.9  310.12  4995.9  309.87
  4998.7  309.37  5001.9  309.87  5009.5  315.94  5214.1  316.01  5246.4  314.33
  5359.3  316.42  5437.3  319.18    5501  318.43  5522.2  321.62  5578.8  318.58
  5656.1   320.6  5819.2  327.42  5868.6  335.26  5882.8  334.26  5901.8  328.42
  5932.4  329.47  5953.5  338.55  6045.5  338.64  6123.2  349.15  6173.8  350.65
#Mann= 12 ,-1 , 0
  4447.4     .16       0  4551.8     .05       0  4557.9     .16       0
    4880     .12       0  4952.9     .16       0  4993.9     .12       0
  4995.9     .07       0  5001.9     .12       0  5214.1      .1       0
  5359.3     .08       0  5656.1     .05       0  5901.8     .08       0
#XS Ineff= 1 ,-1
 5520.91 5758.18  321.83
Permanent Ineff=
       F
Bank Sta=4970.6,5009.5
XS Rating Curve= 0 ,0
Exp/Cntr=0.3,0.1

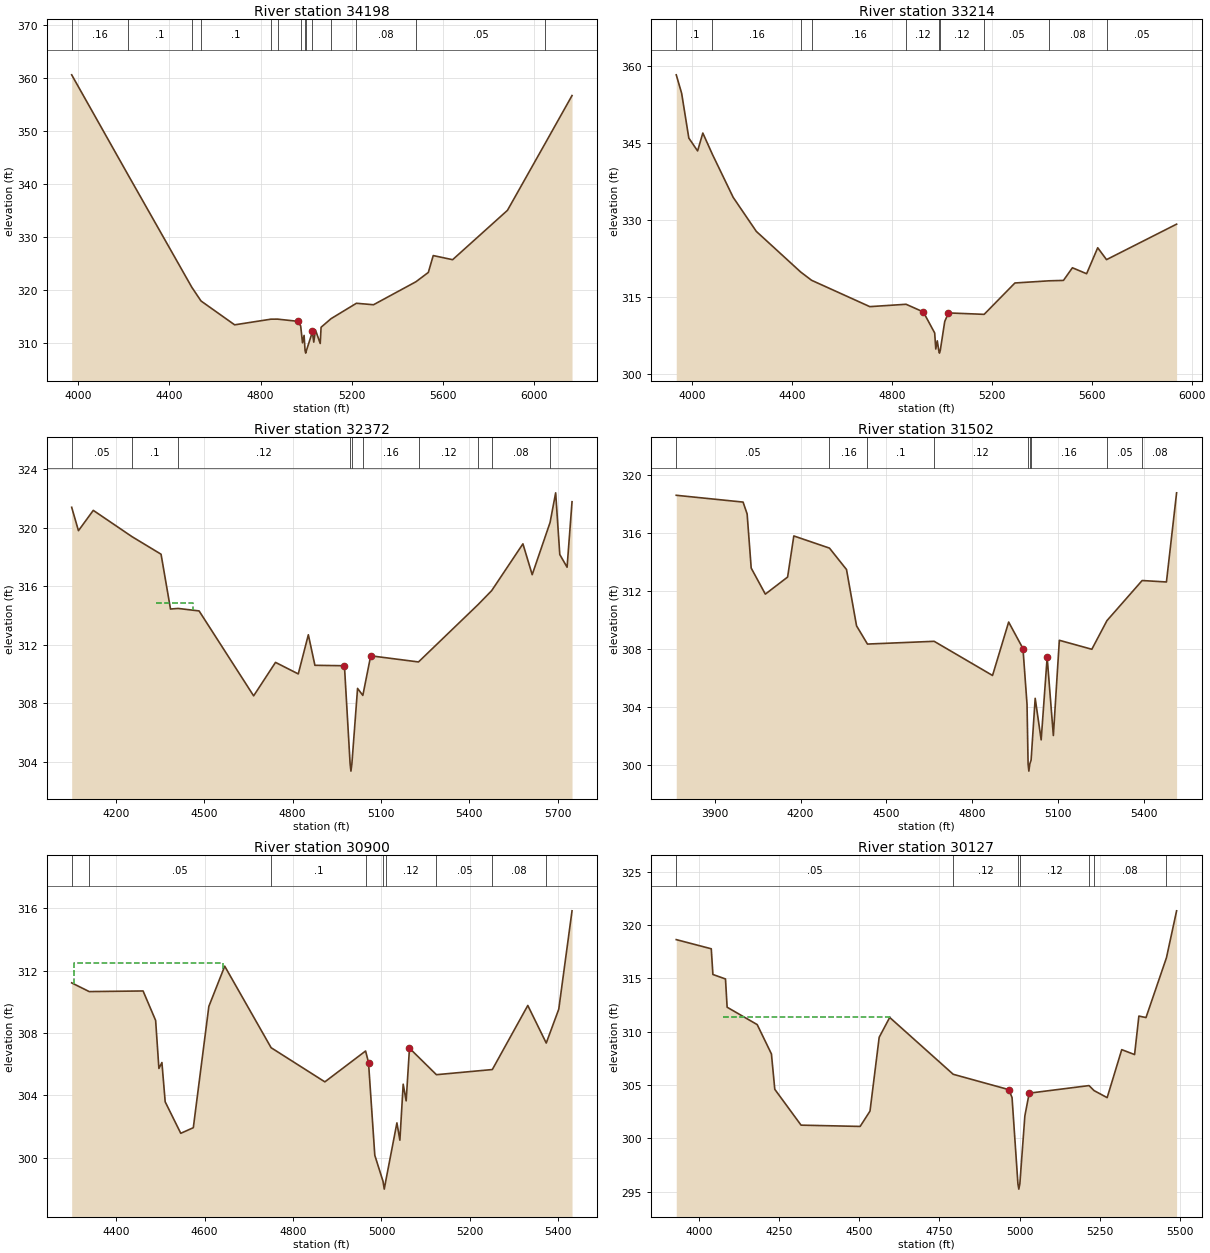
Type RM Length L Ch R = 1 ,34198   ,984,984,984
BEGIN DESCRIPTION:
CAT CREEK 34.0
END DESCRIPTION:
XS GIS Cut Line= 3
       3668242.1     10230041.63      3669042.11     10230791.64
      3669792.12     10231591.65
#Sta/Elev= 30
  3971.8  360.66  4217.4  341.86  4498.6  320.47  4538.8  317.89  4686.2  313.38
  4845.1  314.45  4874.1  314.46  4962.2  314.05  4975.6  313.17  4983.6  309.98
  4990.5  311.38  4994.8  308.53  4997.6  308.03  5000.8  308.53    5024  311.64
  5026.1  312.26    5033  310.11  5040.3  312.41  5061.3  309.85    5065  312.92
  5108.5  314.54  5219.9  317.46  5294.8  317.18  5480.5  321.52  5535.1  323.29
  5556.6  326.48  5641.6   325.7  5881.9  335.03  6048.3  347.77    6165  356.74
#Mann= 14 ,-1 , 0
  3971.8     .16       0  4217.4      .1       0  4498.6     .16       0
  4538.8      .1       0  4845.1     .16       0  4874.1     .12       0
  4975.6     .16       0  4994.8     .07       0  5000.8     .16       0
    5024     .12       0  5108.5      .1       0  5219.9     .08       0
  5480.5     .05       0  6048.3     .08       0
Bank Sta=4962.2,5026.1
XS Rating Curve= 0 ,0
Exp/Cntr=0.3,0.1

Type RM Length L Ch R = 1 ,33214   ,842,842,842
BEGIN DESCRIPTION:
CAT CREEK 32.0
END DESCRIPTION:
XS GIS Cut Line= 3
      3667842.07      10230341.6      3668492.11     10231141.64
      3669292.15     10231691.67
#Sta/Elev= 30
  3938.1  358.27  3959.7  354.68  3988.4  345.97  4023.6  343.47  4044.4  346.95
    4083  342.78  4165.9  334.44  4258.5  327.82    4436  319.92  4479.3  318.32
  4712.5  313.19  4857.6  313.65  4926.6  312.16    4972  308.07  4976.4  304.95
  4982.4  306.54  4988.3  304.65    4991  304.15  4994.3  304.65  5012.2   310.3
  5027.1  311.97  5169.9  311.69    5293  317.79  5428.7  318.21  5487.2  318.29
    5523  320.75  5579.8  319.59  5624.2  324.64  5659.5  322.33  5939.8  329.23
#Mann= 10 ,-1 , 0
  3938.1      .1       0    4083     .16       0    4436     .05       0
  4479.3     .16       0  4857.6     .12       0  4988.3     .07       0
  4994.3     .12       0  5169.9     .05       0  5428.7     .08       0
  5659.5     .05       0
Bank Sta=4926.6,5027.1
XS Rating Curve= 0 ,0
Exp/Cntr=0.3,0.1

Type RM Length L Ch R = 1 ,32372   ,870,870,870
BEGIN DESCRIPTION:
CAT CREEK 30.0
END DESCRIPTION:
XS GIS Cut Line= 3
      3667594.74     10230820.55      3668093.61     10231832.95
      3668642.08     10231991.63
#Sta/Elev= 30
  4049.6  321.41  4072.6  319.81    4123   321.2  4254.6   319.4  4353.2   318.2
  4385.3  314.45  4411.2  314.49  4482.4  314.32  4667.7  308.51    4742   310.8
  4819.3  310.01  4853.5  312.69  4875.8   310.6  4976.1  310.57  4995.4  303.86
  4998.2  303.36  5001.4  303.86  5020.7  309.02  5038.6  308.54  5065.3  311.25
  5227.7  310.83  5430.9  314.77  5476.3  315.71  5582.4  318.91  5613.9   316.8
  5674.6  320.37  5693.6   322.4  5707.6  318.18  5732.4  317.31  5749.2  321.79
#Mann= 10 ,-1 , 0
  4049.6     .05       0  4254.6      .1       0  4411.2     .12       0
  4995.4     .07       0  5001.4     .12       0  5038.6     .16       0
  5227.7     .12       0  5430.9     .05       0  5476.3     .08       0
  5674.6     .05       0
#XS Ineff= 1 ,-1
 4334.43 4461.25  314.89
Permanent Ineff=
       F
Bank Sta=4976.1,5065.3
XS Rating Curve= 0 ,0
Exp/Cntr=0.3,0.1

Type RM Length L Ch R = 1 ,31502   ,602,602,602
BEGIN DESCRIPTION:
CAT CREEK 28.0
END DESCRIPTION:
XS GIS Cut Line= 3
      3666813.58     10231270.52      3667748.61     10232330.77
      3668042.07     10232491.62
#Sta/Elev= 30
  3765.7  318.62  3999.2  318.15  4013.4  317.33  4027.6  313.59    4077  311.79
  4154.8  312.97  4176.5  315.81  4301.1  314.97  4360.6  313.49  4395.7   309.6
  4433.8  308.34  4666.9  308.53  4870.9  306.17  4927.2  309.86  4977.2  308.03
  4991.4  304.17  4995.1  300.06  4997.8  299.56  5001.1  300.06  5005.6  300.32
  5019.9  304.59  5040.8  301.72  5061.7  307.42  5083.4  302.02  5104.3   308.6
  5217.8  307.98  5270.7  309.96  5393.6  312.73  5478.5  312.63    5514  318.79
#Mann= 9 ,-1 , 0
  3765.7     .05       0  4301.1     .16       0  4433.8      .1       0
  4666.9     .12       0  4995.1     .07       0  5001.1     .12       0
  5005.6     .16       0  5270.7     .05       0  5393.6     .08       0
Bank Sta=4977.2,5061.7
XS Rating Curve= 0 ,0
Exp/Cntr=0.3,0.1

Type RM Length L Ch R = 1 ,30900   ,773,773,773
BEGIN DESCRIPTION:
CAT CREEK 27.0
END DESCRIPTION:
XS GIS Cut Line= 3
      3666831.82     10232023.69      3667386.22     10232638.05
      3667392.11     10232941.67
#Sta/Elev= 30
  4299.6  311.21  4339.2  310.65    4461  310.69  4489.4   308.8  4496.8  305.72
  4503.6   306.1    4511  303.58  4546.2  301.56  4574.6  301.92  4609.7   309.7
  4645.6  312.28  4750.5  307.05    4872  304.86  4964.1  306.84  4970.7   306.1
  4984.9  300.15  5003.5  298.48  5006.3  297.98  5009.5  298.48  5034.9  302.23
  5041.6  301.12  5049.1  304.71  5055.8  303.64  5063.3  307.02  5124.2  305.32
  5250.6  305.65  5330.8  309.76  5372.5  307.35  5400.8  309.52  5430.8  315.83
#Mann= 9 ,-1 , 0
  4299.6     .16       0  4339.2     .05       0  4750.5      .1       0
  4964.1     .12       0  5003.5     .07       0  5009.5     .12       0
  5124.2     .05       0  5250.6     .08       0  5372.5     .05       0
#XS Ineff= 1 ,-1
  4304.2 4642.27  312.46
Permanent Ineff=
       F
Bank Sta=4970.7,5063.3
XS Rating Curve= 0 ,0
Exp/Cntr=0.3,0.1

Type RM Length L Ch R = 1 ,30127   ,642,642,642
BEGIN DESCRIPTION:
CAT CREEK 25.0
END DESCRIPTION:
XS GIS Cut Line= 3
      3666483.92     10231791.45      3666689.98      10232752.4
      3666892.11     10233291.67
#Sta/Elev= 30
  3930.1  318.63  4039.2  317.77  4044.3  315.36  4083.5  314.94  4088.6  312.29
  4182.3  310.66  4226.6  307.91  4237.1  304.59  4318.9  301.23    4503  301.11
  4533.7  302.55  4562.3  309.47  4595.1  311.33  4792.9     306  4966.2  304.56
  4976.2  303.82  4994.5  295.73  4997.3  295.23  5000.5  295.73  5016.1  302.09
  5029.6  304.23    5216  304.94  5231.7  304.47  5272.5  303.81  5317.9  308.31
  5357.9  307.85  5371.3  311.46  5393.5  311.32  5457.2  316.93  5488.8  321.33
#Mann= 7 ,-1 , 0
  3930.1     .05       0  4792.9     .12       0  4994.5     .07       0
  5000.5     .12       0    5216     .05       0  5231.7     .08       0
  5457.2     .05       0
#XS Ineff= 1 ,-1
 4076.14 4594.66  311.37
Permanent Ineff=
       F
Bank Sta=4966.2,5029.6
XS Rating Curve= 0 ,0
Exp/Cntr=0.3,0.1

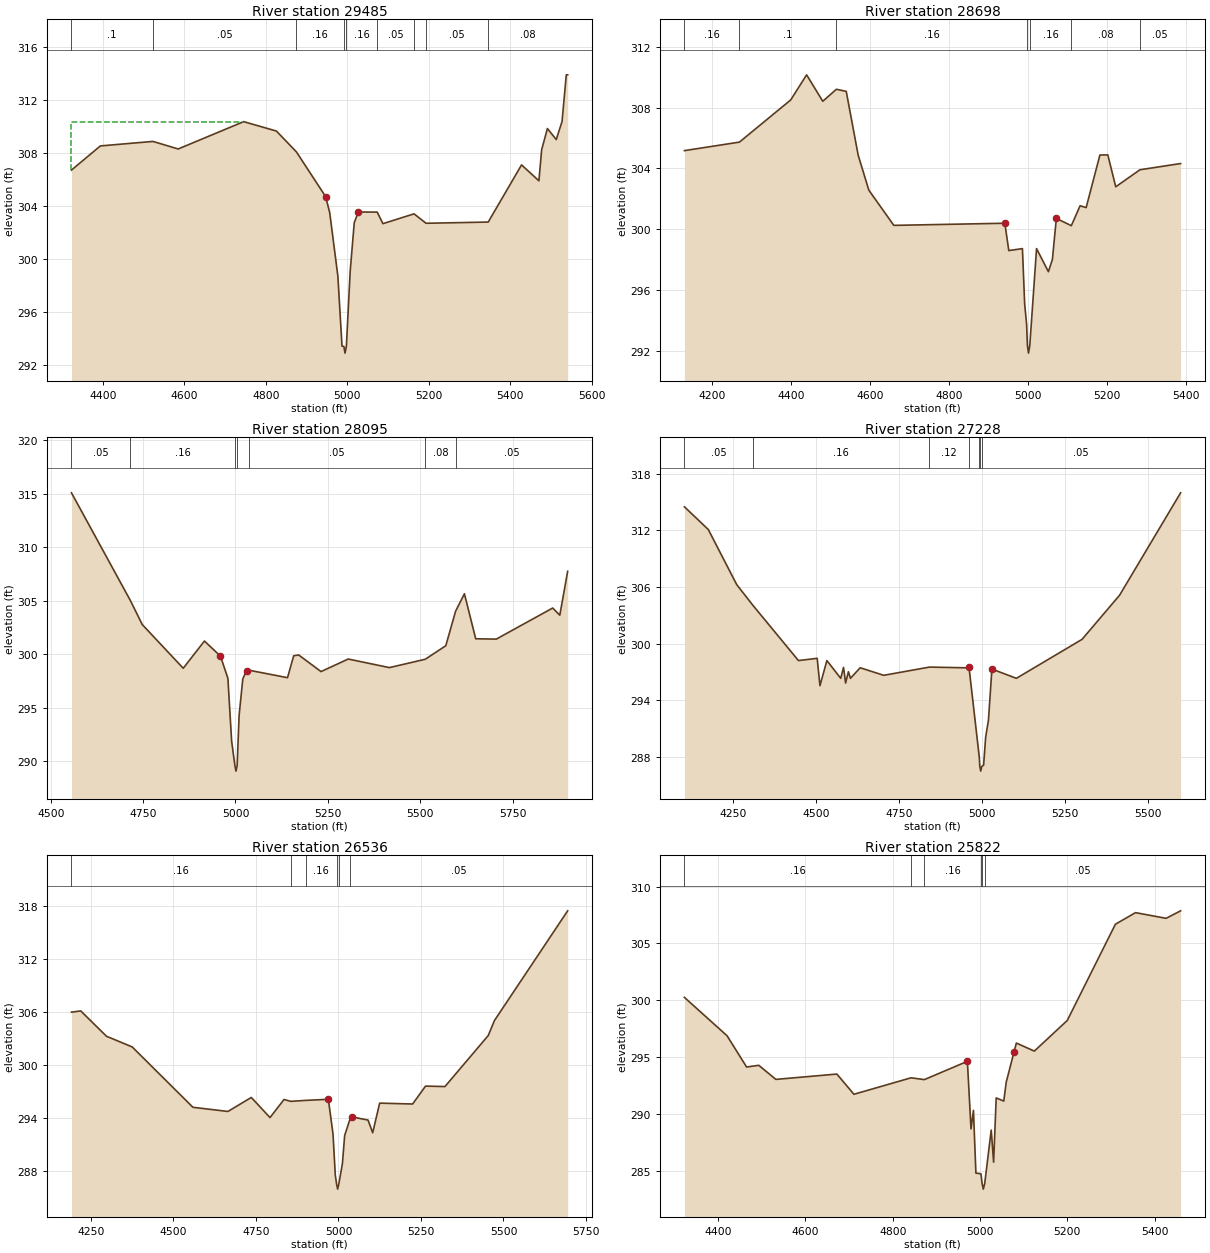
Type RM Length L Ch R = 1 ,29485   ,787,787,787
BEGIN DESCRIPTION:
CAT CREEK 24.0
END DESCRIPTION:
XS GIS Cut Line= 3
        3666108.     10232361.16      3666191.14      10233168.1
       3666492.1     10233441.63
#Sta/Elev= 30
  4323.2   306.7  4394.1  308.52  4523.1  308.86  4585.1  308.29  4745.9  310.35
  4826.3  309.64  4875.3  308.07    4947   304.7    4957   303.5  4977.1   298.7
  4987.2  293.43  4991.9   293.4  4994.6   292.9  4997.9   293.4  5007.3  299.07
  5017.3  302.74  5027.4  303.54  5073.6  303.53  5087.7  302.66    5164   303.4
  5193.5  302.69  5346.1  302.78  5427.9  307.09  5470.5  305.89  5477.3  308.24
  5491.4  309.83  5513.1     309  5527.3  310.36  5537.7  313.88  5541.1  313.88
#Mann= 9 ,-1 , 0
  4323.2      .1       0  4523.1     .05       0  4875.3     .16       0
  4991.9     .07       0  4997.9     .16       0  5073.6     .05       0
    5164     .16       0  5193.5     .05       0  5346.1     .08       0
#XS Ineff= 1 ,-1
 4315.34 4744.09  310.31
Permanent Ineff=
       F
Bank Sta=4947,5027.4
XS Rating Curve= 0 ,0
Exp/Cntr=0.3,0.1

Type RM Length L Ch R = 1 ,28698   ,603,603,603
BEGIN DESCRIPTION:
CAT CREEK 22.0
END DESCRIPTION:
XS GIS Cut Line= 3
      3665618.93     10232703.47      3665682.51     10233481.11
      3665711.85     10233955.46
#Sta/Elev= 30
  4130.3  305.17  4269.5  305.73  4399.4  308.51  4439.5  310.16  4480.4  308.42
  4514.9  309.21  4539.8  309.07  4569.9  304.88  4596.9  302.57  4660.2  300.25
  4941.1  300.39  4951.1  298.59  4985.6  298.72  4991.2  295.09  4996.2  293.72
  4998.2  292.34    5001  291.84  5004.2  292.34  5021.3  298.72  5051.3   297.2
  5061.4  298.01  5071.4  300.71  5109.3  300.23  5131.5  301.54  5146.8  301.42
  5181.6  304.88  5201.6  304.89  5221.7  302.79  5282.9  303.91  5385.8  304.32
#Mann= 7 ,-1 , 0
  4130.3     .16       0  4269.5      .1       0  4514.9     .16       0
  4998.2     .07       0  5004.2     .16       0  5109.3     .08       0
  5282.9     .05       0
Bank Sta=4941.1,5071.4
XS Rating Curve= 0 ,0
Exp/Cntr=0.3,0.1

Type RM Length L Ch R = 1 ,28095   ,867,867,867
BEGIN DESCRIPTION:
CAT CREEK 21.0
END DESCRIPTION:
XS GIS Cut Line= 3
       3665092.1      10232941.6      3665183.66     10233671.84
      3665392.11     10234241.66
#Sta/Elev= 30
  4556.2  315.07  4715.9     305  4747.7  302.78  4858.6   298.7    4916  301.24
  4959.4  299.83  4979.5  297.76  4989.6  291.89  4998.5   289.6  5001.3   289.1
  5004.5   289.6  5009.8  294.29  5019.8   297.7  5029.9  298.48  5036.1  298.52
  5140.8  297.82  5157.5  299.86    5171  299.94  5231.5  298.39  5305.1  299.56
  5416.5  298.76  5513.6  299.54  5569.1   300.8  5595.7  304.03  5619.5  305.65
  5650.1  301.45  5705.8  301.42  5858.4  304.32  5877.6  303.65  5898.9  307.75
#Mann= 7 ,-1 , 0
  4556.2     .05       0  4715.9     .16       0  4998.5     .07       0
  5004.5     .16       0  5036.1     .05       0  5513.6     .08       0
  5595.7     .05       0
Bank Sta=4959.4,5029.9
XS Rating Curve= 0 ,0
Exp/Cntr=0.3,0.1

Type RM Length L Ch R = 1 ,27228   ,692,692,692
BEGIN DESCRIPTION:
CAT CREEK 20.0
END DESCRIPTION:
XS GIS Cut Line= 3
       3665042.1     10232941.65      3664492.11     10233691.64
      3664092.12     10234091.63
#Sta/Elev= 30
    4104  314.51  4176.1   312.1  4261.8  306.26  4310.8  304.06  4447.8  298.22
  4504.2  298.46  4512.6  295.56  4533.5  298.22  4575.2  296.34  4583.7   297.5
  4589.9  295.84  4598.3  297.04  4604.5  296.34  4633.8  297.46  4704.9  296.66
  4842.7  297.53  4961.2  297.45  4961.9  297.51    4993  287.95  4994.4  287.01
  4997.2  286.51  5000.4  287.01  5005.9  287.14  5012.1  290.12  5020.5   291.9
  5030.9  297.32  5104.7  296.34  5302.7  300.47  5415.9  305.15  5599.7  315.99
#Mann= 7 ,-1 , 0
    4104     .05       0  4310.8     .16       0  4842.7     .12       0
  4961.2     .16       0    4993     .05       0  4994.4    .035       0
  5000.4     .05       0
Bank Sta=4961.9,5030.9
XS Rating Curve= 0 ,0
Exp/Cntr=0.3,0.1

Type RM Length L Ch R = 1 ,26536   ,714,714,714
BEGIN DESCRIPTION:
CAT CREEK 18.0
END DESCRIPTION:
XS GIS Cut Line= 3
      3664692.11     10232741.64      3663946.32     10233441.98
      3663765.44     10233886.84
#Sta/Elev= 30
  4191.2  305.97  4219.3  306.11  4297.4  303.25  4375.1  302.05  4559.2  295.24
  4665.2  294.77    4736  296.35  4792.7  294.08  4835.2  296.12  4855.5  295.91
  4901.1  296.02  4969.5  296.14  4983.7  292.18  4990.5  287.57  4994.8  286.51
  4997.6  286.01  5000.8  286.51    5012  288.88  5018.9  292.06  5036.4  294.07
  5040.3  294.16  5089.7   293.8  5103.8  292.37  5124.9  295.71  5224.7  295.61
  5263.9  297.63  5322.8  297.58    5454  303.34  5472.6  305.02  5694.5   317.4
#Mann= 6 ,-1 , 0
  4191.2     .16       0  4855.5     .12       0  4901.1     .16       0
  4994.8     .07       0  5000.8     .16       0  5036.4     .05       0
Bank Sta=4969.5,5040.3
XS Rating Curve= 0 ,0
Exp/Cntr=0.3,0.1

Type RM Length L Ch R = 1 ,25822   ,444,444,444
BEGIN DESCRIPTION:
CAT CREEK 17.0
END DESCRIPTION:
XS GIS Cut Line= 3
       3663892.1     10232491.65      3663592.11     10233091.64
      3663404.25     10233518.41
#Sta/Elev= 30
  4322.7  300.25  4420.5  296.87  4465.2  294.12  4493.2  294.27  4532.3  293.03
  4672.1   293.5  4711.2  291.72  4842.1  293.17  4872.5  293.01  4971.2  294.62
  4979.5  288.67  4985.1   290.3  4990.7  284.78  5002.3  284.72  5004.9  283.87
  5007.7  283.37  5010.9  283.87  5025.8  288.57  5031.3  285.74  5037.2   291.4
  5054.6  291.12  5060.1  292.77  5077.9  295.42  5083.4  296.23  5124.6  295.52
  5200.1  298.22  5310.4  306.69  5356.5  307.71  5426.5  307.21  5459.8  307.87
#Mann= 6 ,-1 , 0
  4322.7     .16       0  4842.1     .12       0  4872.5     .16       0
  5002.3     .05       0  5004.9     .07       0  5010.9     .05       0
Bank Sta=4971.2,5077.9
XS Rating Curve= 0 ,0
Exp/Cntr=0.3,0.1

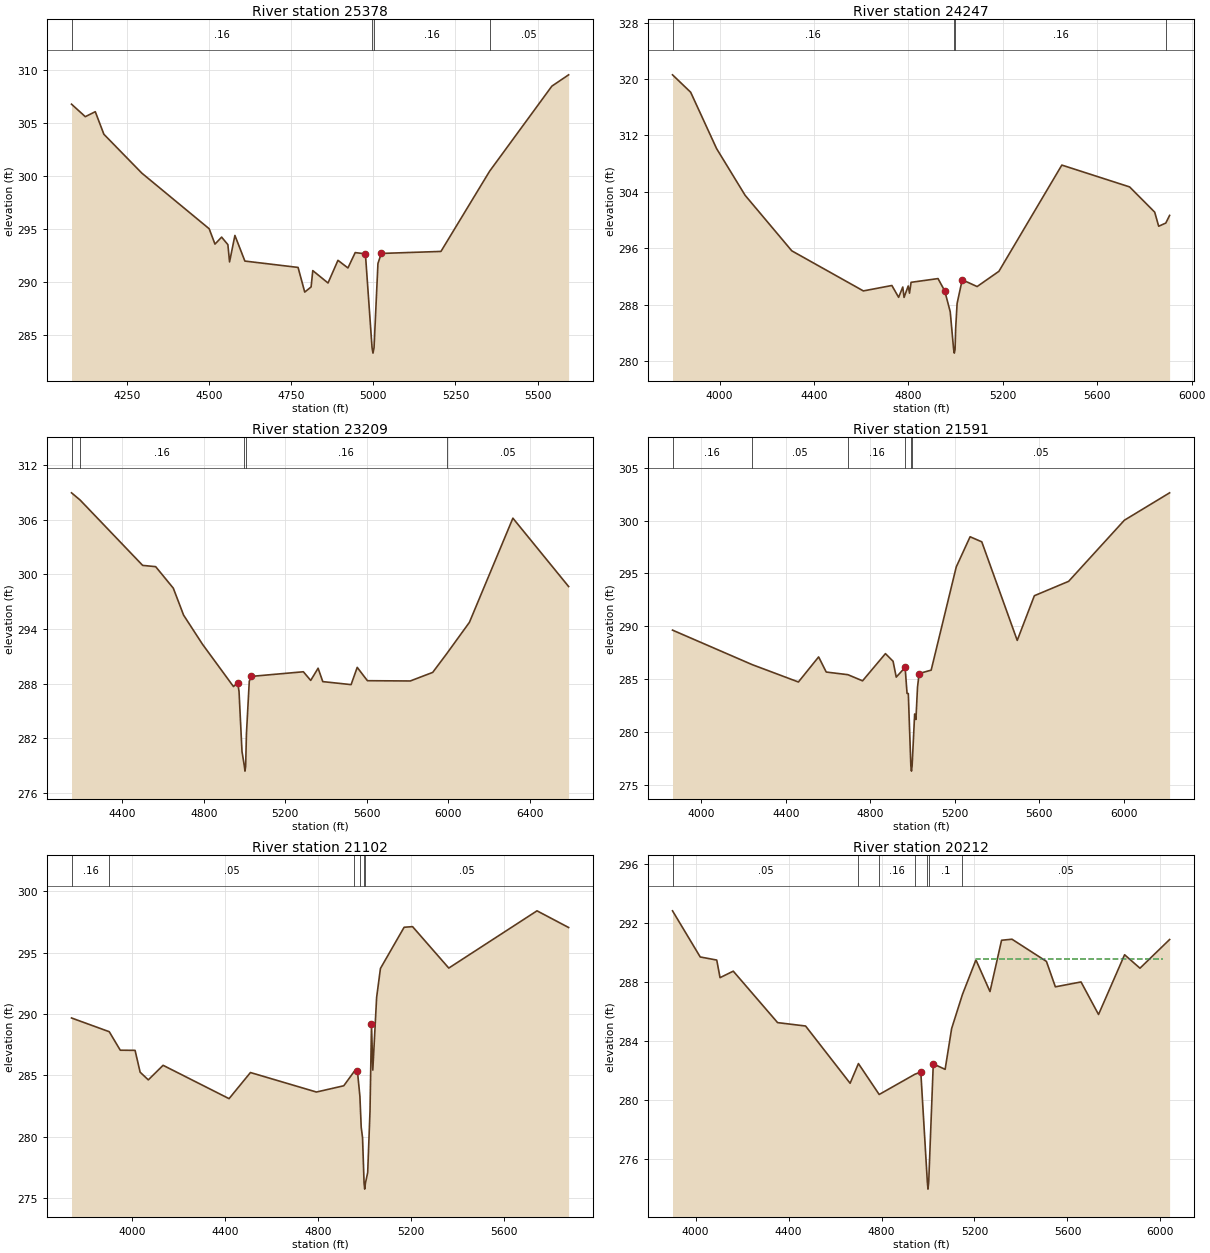
Type RM Length L Ch R = 1 ,25378   ,1131,1131,1131
BEGIN DESCRIPTION:
CAT CREEK 16.0
END DESCRIPTION:
XS GIS Cut Line= 3
      3663432.79     10231960.14      3663292.11     10232841.64
      3663173.59     10233451.78
#Sta/Elev= 30
  4080.4  306.82  4122.4  305.64  4152.8  306.11    4179  303.98  4294.6  300.31
  4499.7  295.06  4517.4  293.61  4537.6  294.27  4556.7  293.56  4561.8  291.93
  4578.1  294.43  4608.5  292.01  4770.5  291.41  4790.8  289.08  4810.2  289.57
  4815.3  291.11  4861.7  289.94    4892  292.08  4922.4  291.36  4944.5  292.81
  4975.6  292.69  4995.9  283.82  4998.7  283.32  5001.9  283.82  5013.8  291.78
    5024  292.73  5205.7  292.92  5353.9  300.49  5543.5  308.52  5594.6  309.59
#Mann= 4 ,-1 , 0
  4080.4     .16       0  4995.9     .07       0  5001.9     .16       0
  5353.9     .05       0
Bank Sta=4975.6,5024
XS Rating Curve= 0 ,0
Exp/Cntr=0.3,0.1

Type RM Length L Ch R = 1 ,24247   ,1038,1038,1038
BEGIN DESCRIPTION:
CAT CREEK 15.0
END DESCRIPTION:
XS GIS Cut Line= 3
      3663242.11     10231691.64      3662742.11     10232791.64
      3662542.73     10233666.81
#Sta/Elev= 30
  3800.7   320.6  3877.6  318.13  3987.4  310.13  4108.3   303.5    4306  295.62
  4609.2  289.93    4730   290.7  4758.6  289.02  4776.1  290.48  4781.6  289.01
  4799.2  290.63  4804.7  289.61  4811.3  291.15  4925.5  291.68  4954.1  289.92
  4977.2  286.97  4991.7   281.6  4994.5   281.1  4997.7   281.6  5000.2  284.58
  5006.3  288.14    5028  291.51  5091.1  290.55  5183.4  292.71    5450  307.79
  5737.2  304.69  5843.4  301.11  5860.3  299.11  5890.4  299.56  5906.6  300.65
#Mann= 4 ,-1 , 0
  3800.7     .16       0  4991.7     .07       0  4997.7     .16       0
  5890.4     .05       0
Bank Sta=4954.1,5028
XS Rating Curve= 0 ,0
Exp/Cntr=0.3,0.1

Type RM Length L Ch R = 1 ,23209   ,1618,1618,1618
BEGIN DESCRIPTION:
CAT CREEK 14.0
END DESCRIPTION:
XS GIS Cut Line= 3
      3662880.17     10231343.85       3662122.1     10232444.28
      3662195.36     10233548.08
#Sta/Elev= 30
  4149.7  308.94  4191.9  308.15  4499.2  300.98  4563.2  300.84  4649.8  298.48
  4700.5  295.52  4793.2  292.33  4945.4  287.69  4966.3   288.1  4972.8  287.14
  4987.3  280.58  4999.2  278.91  5001.9  278.41  5005.2  278.91  5009.2  282.52
  5023.1  288.26  5031.9   288.8  5288.9  289.31  5324.9  288.36  5361.3   289.7
  5384.3  288.23  5523.4   287.9  5553.5  289.79  5603.6  288.33  5814.1   288.3
  5924.3  289.24  5993.5   291.3  6104.7  294.73  6318.4  306.16  6592.2  298.66
#Mann= 5 ,-1 , 0
  4149.7      .1       0  4191.9     .16       0  4999.2     .07       0
  5005.2     .16       0  5993.5     .05       0
Bank Sta=4966.3,5031.9
XS Rating Curve= 0 ,0
Exp/Cntr=0.3,0.1

Type RM Length L Ch R = 1 ,21591   ,489,489,489
BEGIN DESCRIPTION:
CAT CREEK 13.0
END DESCRIPTION:
XS GIS Cut Line= 3
      3661833.53      10231505.3      3661099.95     10232610.57
      3660928.77     10233622.94
#Sta/Elev= 30
  3863.1  289.65  4240.3  286.39  4459.1  284.75  4554.8  287.12  4590.8  285.69
  4693.4  285.44  4762.8  284.86  4871.1  287.43  4907.2  286.71  4922.2  285.21
  4964.3  286.13  4964.7  286.02  4973.4  283.67  4979.4  283.66  4991.4  276.83
  4994.2  276.33  4997.4  276.83  5009.4  281.73  5015.4  281.21  5022.9  284.25
  5030.5  285.55  5087.6  285.87  5206.3  295.62  5271.9  298.47  5327.2  297.99
    5495  288.68  5576.1   292.9  5738.4  294.26  6002.1  300.03  6216.4  302.62
#Mann= 6 ,-1 , 0
  3863.1     .16       0  4240.3     .05       0  4693.4     .16       0
  4964.7     .05       0  4991.4     .03       0  4997.4     .05       0
Bank Sta=4964.3,5030.5
XS Rating Curve= 0 ,0
Exp/Cntr=0.3,0.1

Type RM Length L Ch R = 1 ,21102   ,890,890,890
BEGIN DESCRIPTION:
CAT CREEK 12.0
END DESCRIPTION:
XS GIS Cut Line= 3
      3661773.59     10231437.32      3660977.68     10232141.06
      3660025.58     10232639.08
#Sta/Elev= 30
  3739.8  289.67    3902  288.55  3949.4  287.04    4013  287.03  4034.7  285.25
  4069.9  284.62  4133.4  285.81    4417  283.09    4509  285.22  4792.6  283.63
  4910.1  284.14  4954.7   285.3  4968.7  285.36  4979.5  283.28  4985.1  280.75
  4990.8  279.92  4997.4  276.21  5000.1  275.71  5003.4  276.21  5012.9  277.06
  5022.9  282.06  5029.3  289.14  5034.9  285.42  5051.4  291.35  5067.8  293.71
  5169.6  297.07  5205.9  297.12  5361.5  293.74  5740.8  298.41  5876.7  297.05
#Mann= 6 ,-1 , 0
  3739.8     .16       0    3902     .05       0  4954.7     .16       0
  4979.5     .05       0  4997.4    .035       0  5003.4     .05       0
Bank Sta=4968.7,5029.3
XS Rating Curve= 0 ,0
Exp/Cntr=0.3,0.1

Type RM Length L Ch R = 1 ,20212   ,1167,1167,1167
BEGIN DESCRIPTION:
CAT CREEK 12.1
END DESCRIPTION:
XS GIS Cut Line= 3
      3661330.74     10230891.57      3660534.85     10231595.31
      3659581.13     10232094.17
#Sta/Elev= 30
  3900.8  292.81    4020  289.69  4091.1  289.48  4105.3  288.29  4162.2  288.73
  4352.9  285.25  4473.3  285.02  4664.9  281.15  4700.7  282.48    4790  280.39
  4943.8  281.76    4969  281.91  4997.1  274.49  4999.9  273.99  5003.1  274.49
  5022.7  282.46  5073.7  282.09  5101.7  284.85  5148.3  287.16  5206.2  289.49
  5266.7  287.35  5316.5  290.82  5361.3  290.89  5509.5  289.39    5548  287.67
  5658.4     288  5733.7   285.8  5845.8  289.84    5912  288.93  6039.5  290.87
#Mann= 7 ,-1 , 0
  3900.8     .05       0  4700.7     .12       0    4790     .16       0
  4943.8      .1       0  4997.1     .07       0  5003.1      .1       0
  5148.3     .05       0
#XS Ineff= 1 ,-1
 5206.25 6009.09  289.52
Permanent Ineff=
       F
Bank Sta=4969,5022.7
XS Rating Curve= 0 ,0
Exp/Cntr=0.3,0.1