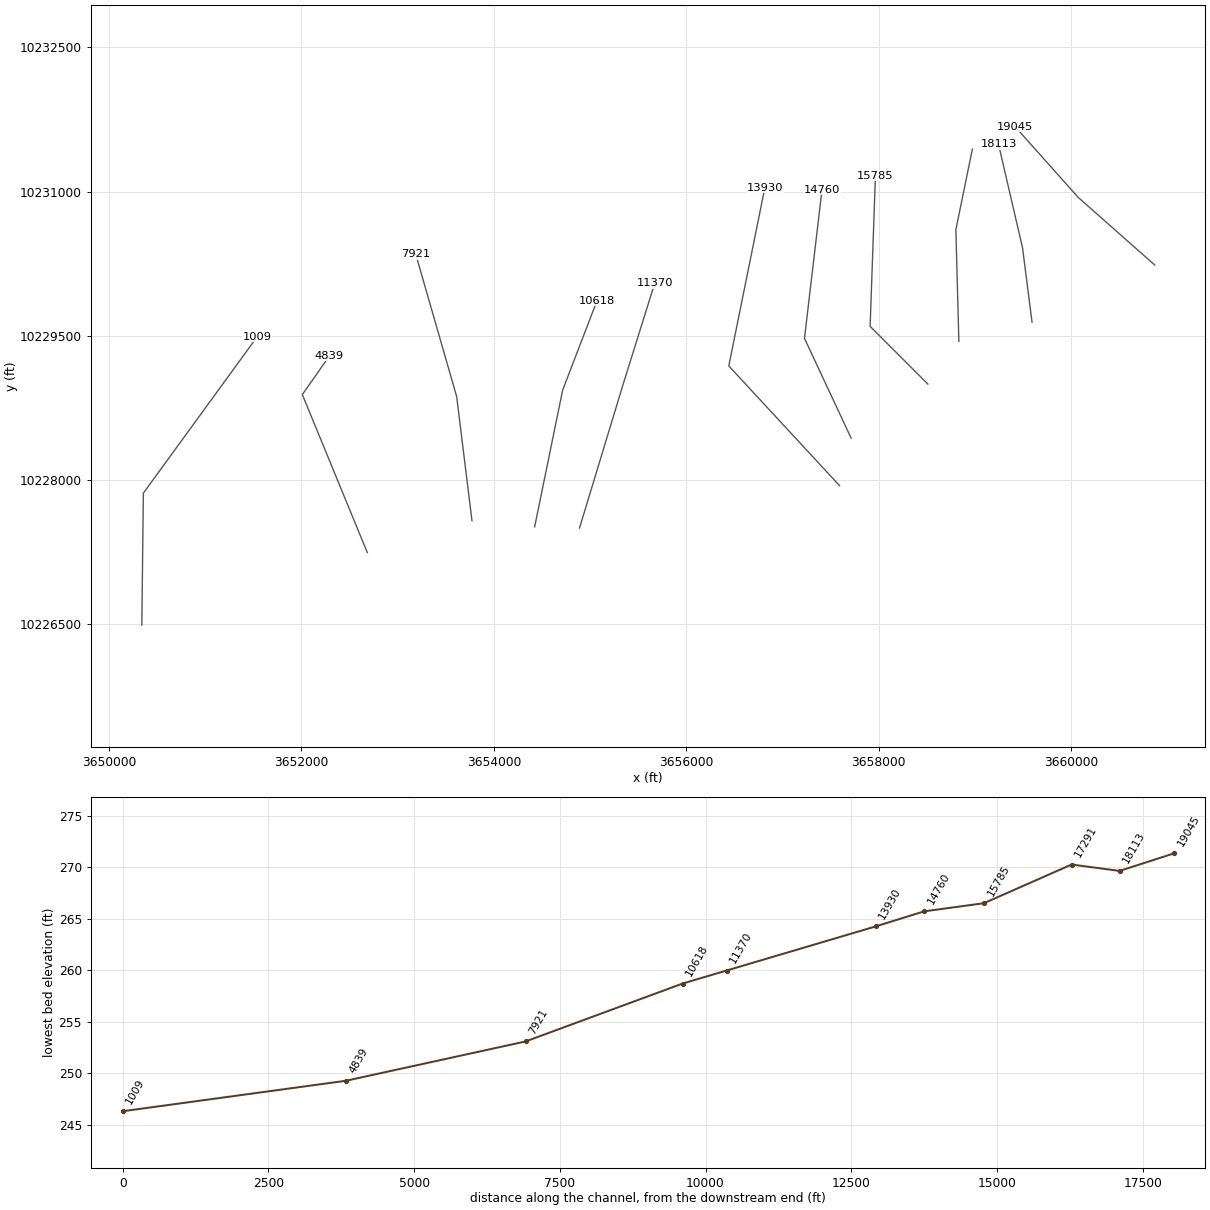
HEC-RAS study CAT CREEK.prj: CAT CREEK Base Level Engineering

--- CAT CREEK.g01 (geometry) --- (continued)

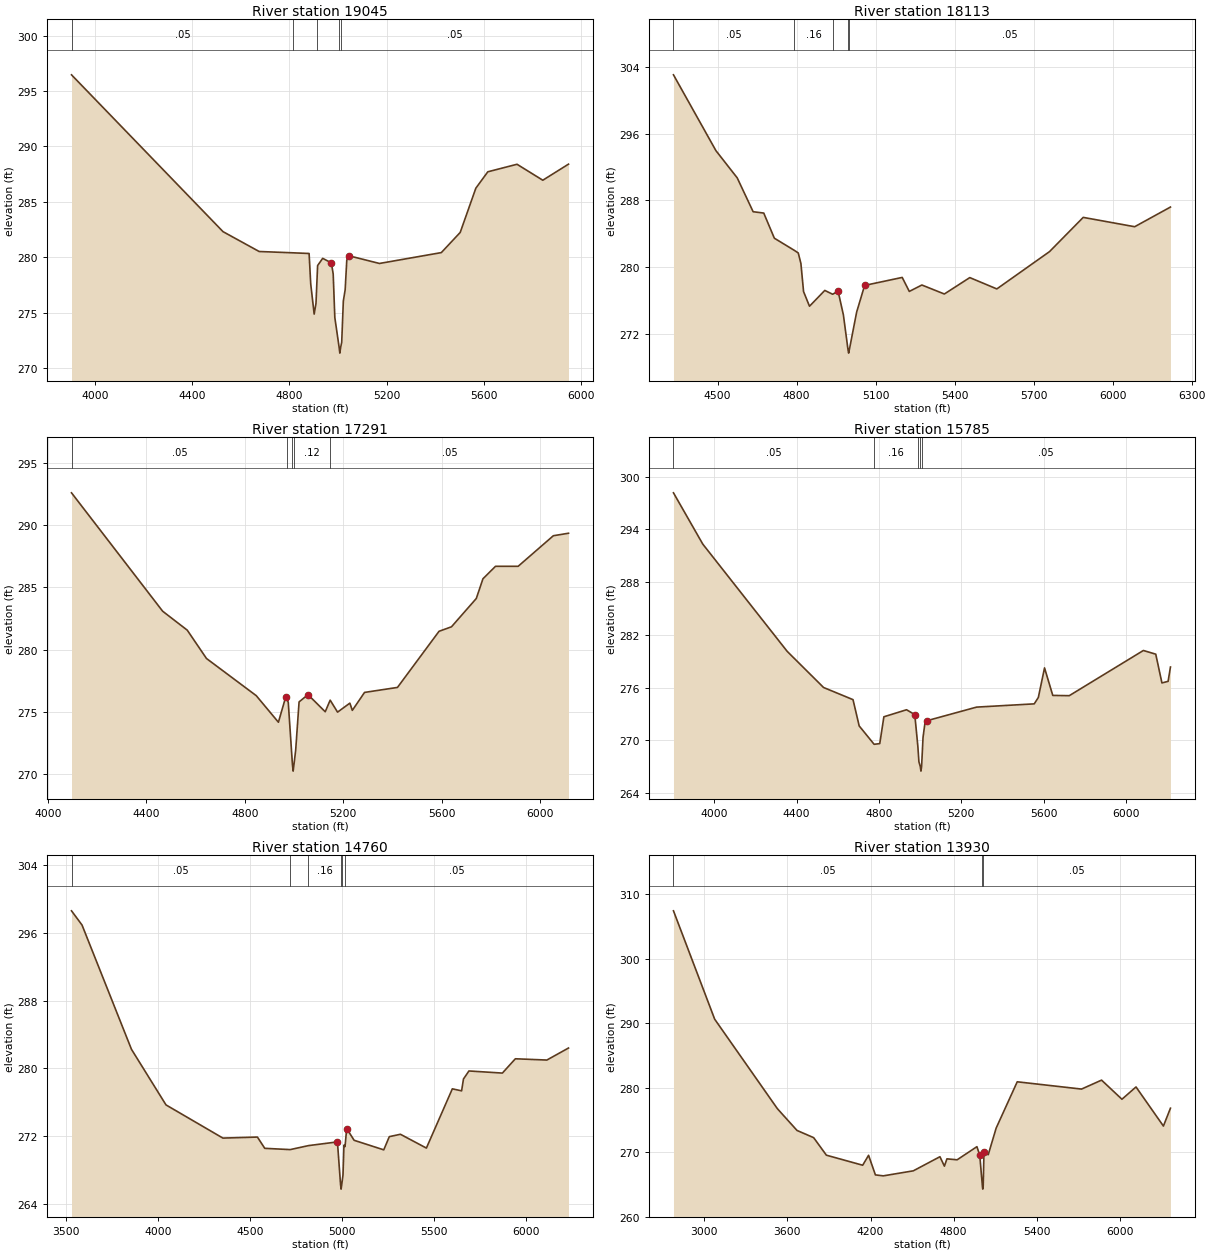
Type RM Length L Ch R = 1 ,19045   ,932,932,932
BEGIN DESCRIPTION:
CAT CREEK 12.2
END DESCRIPTION:
XS GIS Cut Line= 3
       3660867.5      10230235.5      3660071.61     10230939.23
      3659416.17     10231675.18
#Sta/Elev= 30
    3902  296.46  4526.3  282.31  4675.2  280.52  4815.2   280.4    4881  280.34
  4887.7   277.6  4901.9  274.87  4909.4  275.84  4914.1  278.23  4916.1  279.25
    4937   279.9  4972.7   279.5  4980.3  278.49    4987  274.57  5004.9  271.85
  5007.6  271.35  5010.9  271.85  5015.4  272.33  5022.1  276.05  5029.6  277.07
  5036.3  279.73  5043.8  280.14  5170.9  279.44  5425.9  280.42  5503.7  282.24
  5568.1  286.23  5617.4  287.71  5737.8  288.39    5844  286.95  5949.9   288.4
#Mann= 5 ,-1 , 0
    3902     .05       0  4815.2     .16       0  4914.1     .05       0
  5004.9     .03       0  5010.9     .05       0
Bank Sta=4972.7,5043.8
XS Rating Curve= 0 ,0
Exp/Cntr=0.3,0.1

Type RM Length L Ch R = 1 ,18113   ,822,822,822
BEGIN DESCRIPTION:
CAT CREEK 11.0
END DESCRIPTION:
XS GIS Cut Line= 3
      3659592.11     10229641.61      3659493.39     10230415.78
      3659243.38     10231493.94
#Sta/Elev= 30
  4332.3  303.07  4493.6  293.96  4574.3   290.7  4634.8  286.63  4675.1  286.47
  4715.4  283.45  4791.8  281.98  4806.1  281.68  4816.2  280.42  4826.3  277.04
  4848.8  275.28  4906.9  277.18  4936.7  276.72  4957.4  277.09  4977.5  274.25
  4994.7  270.15  4997.4  269.65  5000.7  270.15  5027.9  274.58  5058.2  277.78
  5200.9  278.74  5227.8  277.06  5275.6  277.83  5360.9  276.75  5457.5  278.72
  5560.2  277.36  5760.3  281.84  5888.3  285.95  6083.7  284.83  6219.5  287.19
#Mann= 5 ,-1 , 0
  4332.3     .05       0  4791.8     .16       0  4936.7     .05       0
  4994.7     .03       0  5000.7     .05       0
Bank Sta=4957.4,5058.2
XS Rating Curve= 0 ,0
Exp/Cntr=0.3,0.1

Type RM Length L Ch R = 1 ,17291   ,1506,1506,1506
BEGIN DESCRIPTION:
CAT CREEK 10.0
END DESCRIPTION:
XS GIS Cut Line= 3
      3658831.93     10229441.82      3658800.68     10230603.28
      3658972.56     10231441.86
#Sta/Elev= 30
  4096.6  292.58  4466.6  283.09  4566.6  281.57  4644.6   279.3  4846.7  276.32
  4936.7  274.19  4966.7  276.24  4972.3  275.98  4976.7  275.78  4993.7  270.77
  4996.5  270.27  4999.7  270.77  5006.8  271.96  5020.6  275.82  5056.8   276.4
  5126.8  275.03  5146.8  275.96  5176.8     275  5226.8  275.72  5236.8  275.14
  5286.4  276.58  5420.1  276.98  5588.9  281.48  5639.4  281.84  5740.2  284.11
  5767.2  285.69  5818.2  286.69  5910.1  286.69    6053  289.14  6114.5  289.34
#Mann= 5 ,-1 , 0
  4096.6     .05       0  4972.3     .12       0  4993.7     .07       0
  4999.7     .12       0  5146.8     .05       0
Bank Sta=4966.7,5056.8
XS Rating Curve= 0 ,0
Exp/Cntr=0.3,0.1

Type RM Length L Ch R = 1 ,15785   ,1025,1025,1025
BEGIN DESCRIPTION:
CAT CREEK 9.0
END DESCRIPTION:
XS GIS Cut Line= 3
      3658509.79     10228997.92      3657909.81     10229597.89
      3657964.95     10231163.03
#Sta/Elev= 30
  3801.4  298.16  3943.8  292.33  4353.9  280.13  4530.7  276.02  4673.7  274.64
  4703.7  271.65  4776.3  269.56  4803.7  269.64  4823.7  272.69  4933.8  273.49
  4973.8  272.94  4988.6  269.36  4993.9  267.57  5000.9  267.01  5003.6  266.51
  5006.9  267.01  5013.9  270.35  5023.9  272.09  5033.9  272.25    5274  273.79
  5554.2  274.16  5574.2  274.89  5604.2  278.25  5644.3  275.12  5724.3  275.09
  6084.5  280.23  6144.6  279.81  6174.6  276.54  6204.6  276.72    6216  278.35
#Mann= 5 ,-1 , 0
  3801.4     .05       0  4776.3     .16       0  4988.6     .05       0
  5000.9    .035       0  5006.9     .05       0
Bank Sta=4973.8,5033.9
XS Rating Curve= 0 ,0
Exp/Cntr=0.3,0.1

Type RM Length L Ch R = 1 ,14760   ,830,830,830
BEGIN DESCRIPTION:
CAT CREEK 7.0
END DESCRIPTION:
XS GIS Cut Line= 3
      3657712.13     10228436.62      3657227.76     10229473.07
      3657409.86     10231018.33
#Sta/Elev= 30
  3529.5   298.6  3586.7  296.92  3855.2  282.24  4042.8  275.67  4351.9  271.75
  4539.5  271.87  4579.4  270.54  4717.3  270.39  4816.7  270.86  4974.2   271.3
  4991.3  266.22  4994.1  265.72  4997.3  266.22  5004.4  267.38  5009.6  270.91
  5015.5  270.75  5024.5  272.88  5064.8  271.49  5225.9  270.36  5256.1  271.92
  5316.5   272.2  5457.5  270.57  5598.5  277.57  5648.8  277.33  5658.9  278.73
  5688.7  279.68  5870.3  279.43  5940.8  281.12    6112  280.97  6229.5  282.39
#Mann= 6 ,-1 , 0
  3529.5     .05       0  4717.3     .12       0  4816.7     .16       0
  4991.3     .07       0  4997.3     .16       0  5015.5     .05       0
Bank Sta=4974.2,5024.5
XS Rating Curve= 0 ,0
Exp/Cntr=0.3,0.1

Type RM Length L Ch R = 1 ,13930   ,2560,2560,2560
BEGIN DESCRIPTION:
CAT CREEK 6.0
END DESCRIPTION:
XS GIS Cut Line= 3
      3657592.11     10227941.63       3656441.3     10229186.61
       3656816.3     10231040.79
#Sta/Elev= 30
  2777.9  307.46  3075.3  290.64  3527.8  276.75  3669.5  273.37  3789.7  272.25
  3881.6  269.53  4143.6  267.97  4186.1  269.51  4235.4  266.47  4292.1  266.32
    4509   267.1  4701.1  269.29  4733.5  267.83  4751.8  268.96  4825.3  268.81
  4968.1  270.85  4988.5  269.53  5007.5  264.76  5010.3  264.26  5013.5  264.76
  5019.1  270.05  5049.8   269.6  5106.9  273.73  5259.1  280.92  5723.1  279.79
  5867.8  281.18  6014.9  278.21  6116.4  280.12  6314.2  274.05    6365  276.82
#Mann= 3 ,-1 , 0
  2777.9     .05       0  5007.5     .03       0  5013.5     .05       0
Bank Sta=4988.5,5019.1
XS Rating Curve= 0 ,0
Exp/Cntr=0.3,0.1

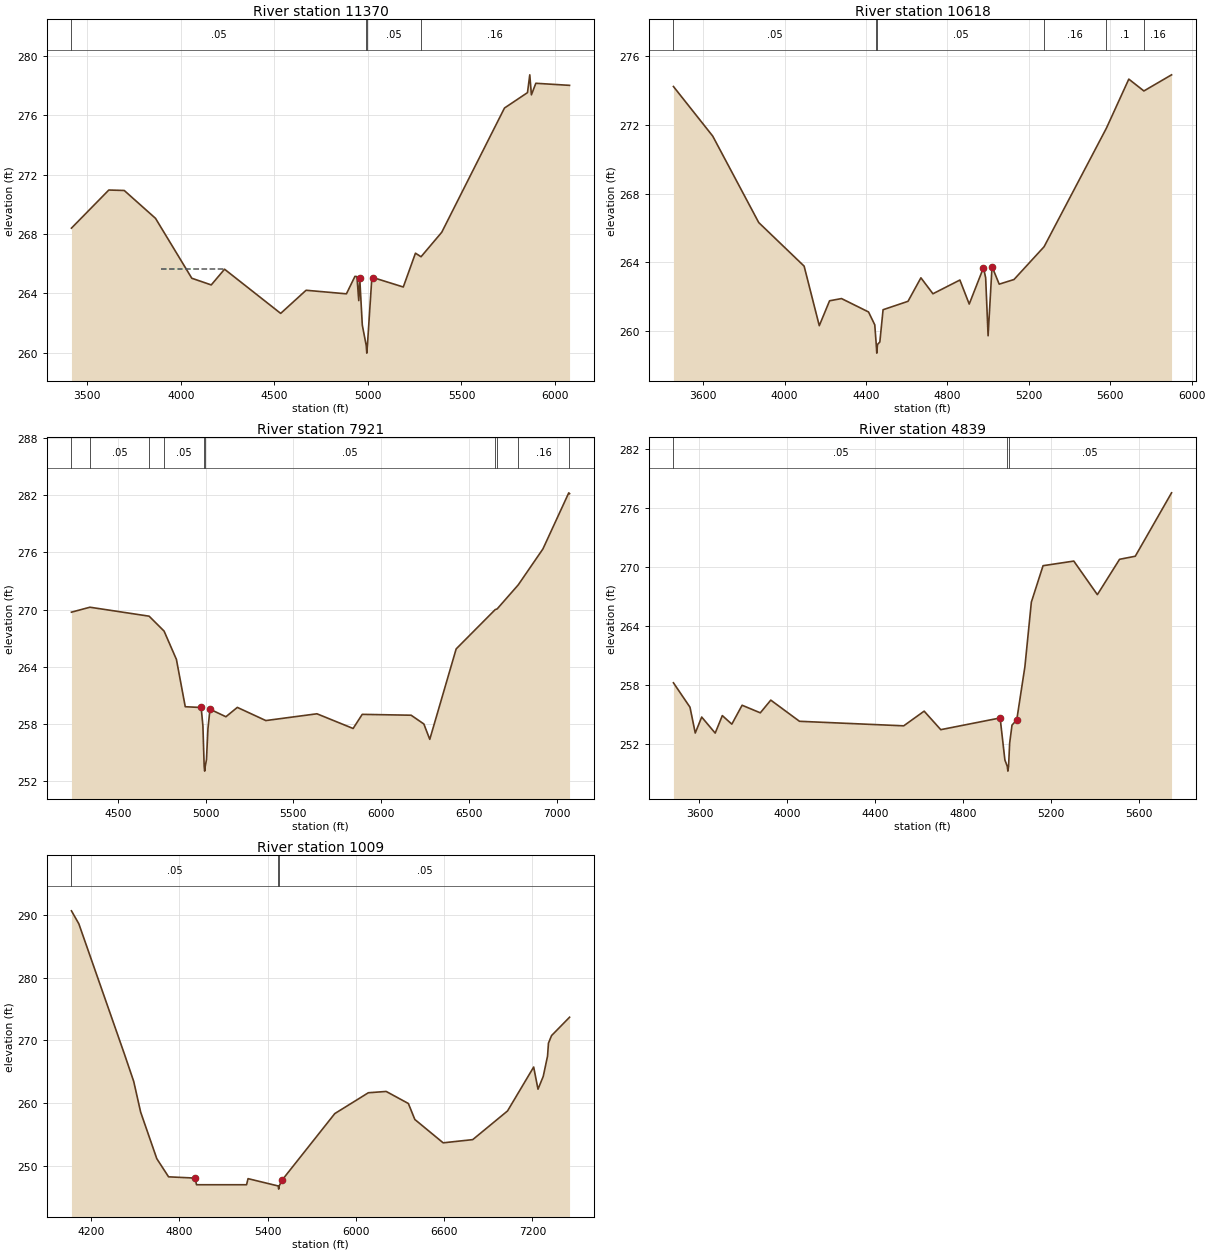
Type RM Length L Ch R = 1 ,11370   ,752,752,752
BEGIN DESCRIPTION:
CAT CREEK 5.0
END DESCRIPTION:
XS GIS Cut Line= 3
       3654890.3      10227501.7      3655342.11     10228991.64
      3655671.56     10230046.24
#Sta/Elev= 30
  3415.9   268.4  3615.6  270.97    3698  270.94  3865.2  269.06  4059.1  265.02
    4163  264.57    4234  265.63    4534  262.65  4669.8  264.21  4885.3  263.97
    4931  265.15  4941.5  265.13  4951.2  263.51  4956.4  265.03  4970.2  261.86
  4991.3  260.47  4994.1  259.97  4997.3  260.47  5021.6  265.13  5026.8  265.07
  5189.2  264.43  5254.2  266.71  5284.1  266.47  5394.6  268.12  5729.9   276.5
  5852.9  277.54  5865.1  278.74  5873.8  277.39  5897.5  278.17  6077.7  278.03
#Mann= 4 ,-1 , 0
  3415.9     .05       0  4991.3     .03       0  4997.3     .05       0
  5284.1     .16       0
#XS Ineff= 1 ,-1
  3892.9 4232.95  265.67
Permanent Ineff=
       F
Bank Sta=4956.4,5026.8
XS Rating Curve= 0 ,0
Exp/Cntr=0.3,0.1

Type RM Length L Ch R = 1 ,10618   ,2697,2697,2697
BEGIN DESCRIPTION:
CAT CREEK 5.1
END DESCRIPTION:
XS GIS Cut Line= 3
      3654423.73     10227512.59      3654715.33     10228936.36
      3655071.82     10229864.21
#Sta/Elev= 30
  3453.9  274.25  3646.9  271.36    3873  266.32    4096  263.78  4170.5  260.31
    4221  261.76  4279.7  261.89  4412.4  261.11  4443.1  260.36  4450.3  259.21
    4453  258.71  4456.3  259.21    4468  259.36  4483.9  261.24  4606.4  261.73
  4669.8   263.1  4728.9  262.17  4861.3  262.97  4907.2  261.57  4977.2  263.69
  4987.9   263.1  4999.9  259.72  5019.2  263.75  5054.5  262.73  5127.1     263
  5274.9  264.91  5581.1  271.82  5691.2  274.68  5765.3  273.99  5901.2  274.93
#Mann= 6 ,-1 , 0
  3453.9     .05       0  4450.3     .03       0  4456.3     .05       0
  5274.9     .16       0  5581.1      .1       0  5765.3     .16       0
Bank Sta=4977.2,5019.2
XS Rating Curve= 0 ,0
Exp/Cntr=0.3,0.1

Type RM Length L Ch R = 1 ,7921    ,3082,3082,3082
BEGIN DESCRIPTION:
CAT CREEK 4.0
END DESCRIPTION:
XS GIS Cut Line= 3
      3653772.68     10227577.72      3653613.76     10228867.89
      3653188.48     10230347.57
#Sta/Elev= 30
  4234.8  269.74  4340.1  270.26  4677.6  269.32  4762.8  267.76  4833.2  264.79
  4883.6  259.83  4974.3  259.75  4984.3   257.8  4991.4  253.58  4994.2  253.08
  4997.4  253.58  5004.5  254.28    5013  257.55  5024.6  259.57  5115.3  258.78
  5180.5  259.76  5342.9  258.38  5634.3  259.09  5840.4  257.55  5892.4  259.03
  6171.2  258.94  6243.8  258.02  6277.4  256.41  6427.9  265.89  6650.5  270.01
  6661.5  270.08  6781.7   272.6  6922.5  276.37  7069.8  282.25  7074.3  282.16
#Mann= 10 ,-1 , 0
  4234.8     .16       0  4340.1     .05       0  4677.6     .16       0
  4762.8     .05       0  4991.4    .035       0  4997.4     .05       0
  6650.5     .16       0  6661.5      .1       0  6781.7     .16       0
  7069.8      .1       0
Bank Sta=4974.3,5024.6
XS Rating Curve= 0 ,0
Exp/Cntr=0.3,0.1

Type RM Length L Ch R = 1 ,4839    ,3830,3830,3830
BEGIN DESCRIPTION:
CAT CREEK 3.0
END DESCRIPTION:
XS GIS Cut Line= 3
       3652685.3     10227245.72      3652009.98     10228888.61
      3652292.08     10229291.61
#Sta/Elev= 30
  3481.4  258.23  3556.8  255.75  3580.8  253.13  3610.1  254.75  3671.6  253.12
    3704   254.9  3747.3  254.03  3794.1  255.95    3877  255.18  3924.7  256.47
  4055.4  254.32    4530  253.86  4623.1  255.35  4698.7  253.47    4969  254.66
  4990.7  250.39  5001.5  249.76  5004.3  249.26  5007.5  249.76  5012.3  252.08
  5023.1  253.93  5044.7  254.46  5081.8  259.86  5111.2  266.42  5164.5  270.12
  5304.5  270.59  5411.8  267.18  5512.9  270.77  5584.4  271.08  5749.6  277.52
#Mann= 3 ,-1 , 0
  3481.4     .05       0  5001.5     .03       0  5007.5     .05       0
Bank Sta=4969,5044.7
XS Rating Curve= 0 ,0
Exp/Cntr=0.3,0.1

Type RM Length L Ch R = 1 ,1009    ,0,0,0
BEGIN DESCRIPTION:
CAT CREEK 1.0
END DESCRIPTION:
XS GIS Cut Line= 3
       3650342.1     10226491.59      3650358.38     10227864.03
      3651542.12     10229491.67
#Sta/Elev= 30
  4067.4  290.66  4117.5   288.6  4427.5  267.82  4490.7  263.46  4537.5  258.59
  4647.5  251.15  4727.5  248.26  4907.5  248.06  4917.5     247  5257.5     247
  5267.5  247.97    5473   246.8  5475.8   246.3    5479   246.8  5498.8  247.74
    5857  258.34    6085  261.66  6206.3  261.87    6357  259.95  6401.1   257.4
  6593.5  253.68  6794.4  254.19  7030.9  258.76  7208.6  265.76    7238  262.23
  7273.6  264.27  7302.9  267.51  7309.1  269.57    7330  270.77  7452.5   273.7
#Mann= 3 ,-1 , 0
  4067.4     .05       0    5473    .035       0    5479     .05       0
Bank Sta=4907.5,5498.8
XS Rating Curve= 0 ,0
Exp/Cntr=0.3,0.1

Chan Stop Cuts=-1
Use User Specified Reach Order=0
Composite Channel Slope=5