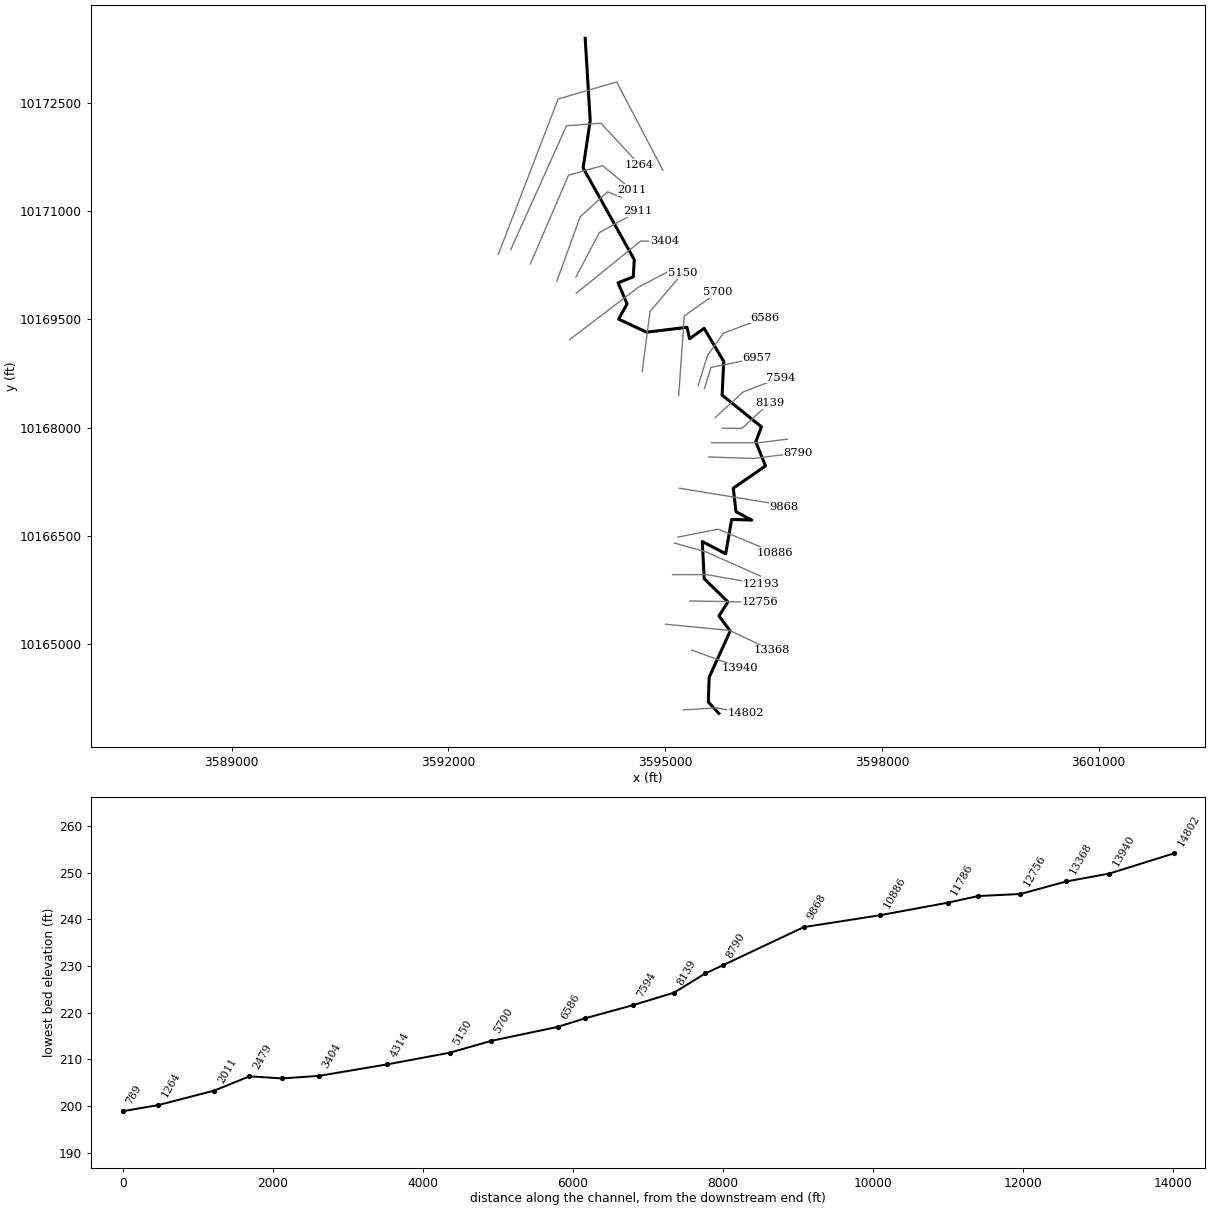
--- CEDAR CREEK EAST.prj (project) ---

Proj Title=CEDAR CREEK EAST Base Level Engineering
Current Plan=p01
Default Exp/Contr=0.3,0.1
English Units
Geom File=g01
Flow File=f01
Plan File=p01
BEGIN DESCRIPTION:
CEDAR CREEK EAST
END DESCRIPTION:

--- CEDAR CREEK EAST.p01 (plan) ---

Plan Title=Multiple Run
Short Identifier=Multiple
Geom File=g01
Flow File=f01
Subcritical Flow
K Sum by GR= 0
Std Step Tol= 0.01
Critical Tol= 0.01
Num of Std Step Trials= 20
Max Error Tol= 0.3
Flow Tol Ratio= 0.001
Split Flow NTrial= 30
Split Flow Tol= 0.02
Split Flow Ratio= 0.02
Log Output Level= 0
Friction Slope Method= 1
Unsteady Friction Slope Method= 2
Unsteady Bridges Friction Slope Method= 1
Parabolic Critical Depth
Global Vel Dist=  1 , 1 , 1
Global Log Level= 0
CheckData=True
Encroach Param= -1, 0, 0, 0
BEGIN DESCRIPTION:
Multiple Run
END DESCRIPTION:

--- CEDAR CREEK EAST.f01 (steady flow) ---

Flow Title=Multiple
Number of Profiles=7
Profile Names=10-year,25-year,50-year,1pct_min,100-year,1pct_plu,500-year
River Rch & RM= CEDAR CREEK EAST,Reach-1,14802
     605     817     989     879    1188    1607    1716
River Rch & RM= CEDAR CREEK EAST,Reach-1,10886
     967    1335    1641    1477    1997    2701    2964
Boundary for River Rch & Prof#=CEDAR CREEK EAST,Reach-1,1
Up Type=0
Dn Type=3
Dn Slope=0.005
Boundary for River Rch & Prof#=CEDAR CREEK EAST,Reach-1,2
Up Type=0
Dn Type=3
Dn Slope=0.005
Boundary for River Rch & Prof#=CEDAR CREEK EAST,Reach-1,3
Up Type=0
Dn Type=3
Dn Slope=0.005
Boundary for River Rch & Prof#=CEDAR CREEK EAST,Reach-1,4
Up Type=0
Dn Type=3
Dn Slope=0.005
Boundary for River Rch & Prof#=CEDAR CREEK EAST,Reach-1,5
Up Type=0
Dn Type=3
Dn Slope=0.005
Boundary for River Rch & Prof#=CEDAR CREEK EAST,Reach-1,6
Up Type=0
Dn Type=3
Dn Slope=0.005
Boundary for River Rch & Prof#=CEDAR CREEK EAST,Reach-1,7
Up Type=0
Dn Type=3
Dn Slope=0.005

--- CEDAR CREEK EAST.g01 (geometry) ---

Geom Title=Existing Conditions

River Reach=CEDAR CREEK EAST,Reach-1
Reach XY= 30
      3595742.11     10164042.96      3595596.88     10164199.36
      3595608.09     10164542.91      3595899.58     10165184.08
      3595744.24     10165392.50      3595868.22     10165587.82
      3595539.66     10165908.15      3595512.95     10166423.10
      3595836.73     10166253.97      3595919.82     10166729.17
      3596197.12     10166720.51      3595979.24     10166836.51
      3595942.62     10167162.51      3596387.78     10167469.83
      3596253.79     10167803.47      3596331.45     10168012.49
      3595787.49     10168450.70      3595809.95     10168917.96
      3595538.74     10169375.94      3595336.95     10169232.66
      3595301.21     10169390.47      3594741.11     10169322.84
      3594354.78     10169504.23      3594472.08     10169715.09
      3594347.31     10170006.46      3594557.59     10170089.97
      3594571.54     10170327.65      3593863.66     10171598.73
      3593961.64     10172252.91      3593892.11     10173392.96

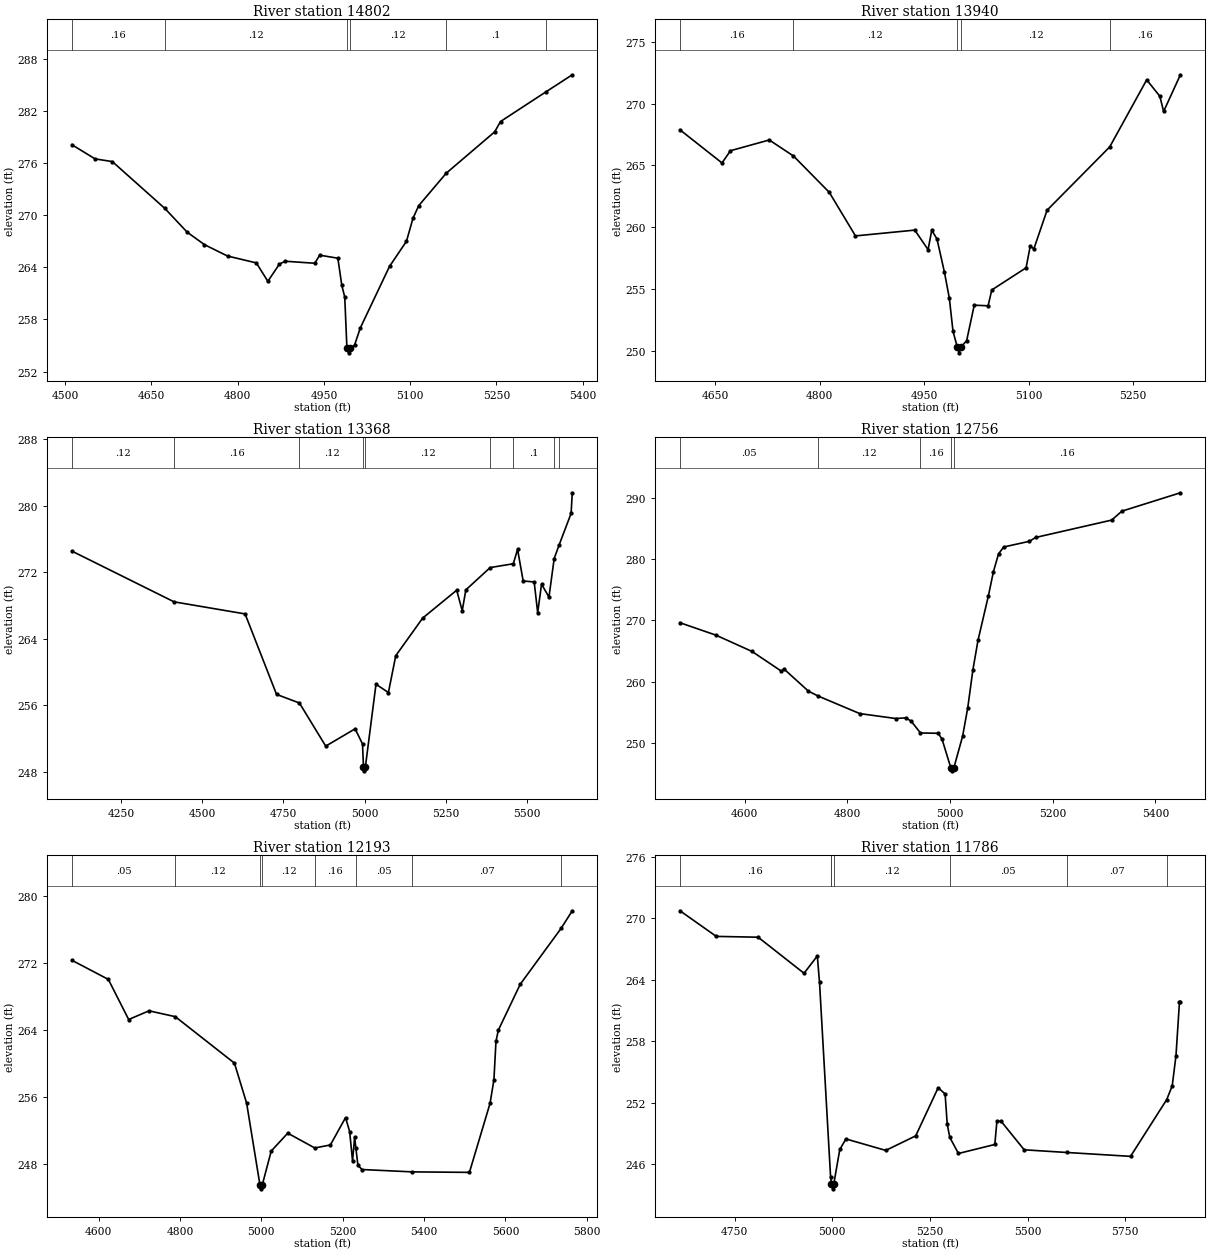
Type RM Length L Ch R = 1,14802,862,862,862
BEGIN DESCRIPTION:
CEDAR CREEK EAST 25.0
END DESCRIPTION:
XS GIS Cut Line= 3
      3595251.79     10164091.29      3595710.10     10164119.07
      3596114.98     10164046.40
#Sta/Elev= 30
  4511.5  278.10  4551.9  276.47  4581.9  276.16  4672.9  270.79  4712.2  268.03
  4742.2  266.60  4782.3  265.29  4832.4  264.50  4852.4  262.38  4872.5  264.36
  4882.5  264.69  4934.1  264.46  4942.6  265.39  4974.2  265.04  4981.1  261.91
  4986.2  260.56  4990.0  254.65  4992.8  254.15  4996.0  254.65  5003.2  255.03
  5013.3  257.02  5064.1  264.10  5093.6  266.99  5104.8  269.62  5114.9  271.09
  5162.7  274.82  5247.0  279.58  5257.2  280.77  5337.0  284.22  5382.0  286.15
#Mann=6,-1,0
  4511.5    0.16       0  4672.9    0.12       0  4990.0    0.07       0
  4996.0    0.12       0  5162.7     0.1       0  5337.0    0.16       0
Bank Sta=4990,4996
Exp/Cntr=0.3,0.1

Type RM Length L Ch R = 1,13940,572,572,572
BEGIN DESCRIPTION:
CEDAR CREEK EAST 24.0
END DESCRIPTION:
XS GIS Cut Line= 3
      3595365.49     10164920.28      3595820.34     10164753.62
      3596038.10     10164667.20
#Sta/Elev= 30
  4599.4  267.88  4659.7  265.20  4671.9  266.19  4727.6  267.06  4762.4  265.76
  4813.8  262.82  4851.4  259.29  4936.6  259.76  4955.7  258.18  4961.0  259.75
  4968.5  259.04  4979.2  256.35  4986.2  254.26  4991.5  251.57  4997.5  250.32
  5000.2  249.82  5003.5  250.32  5011.1  250.81  5022.0  253.68  5041.9  253.63
  5047.2  254.91  5096.5  256.71  5102.3  258.44  5107.7  258.25  5126.6  261.37
  5216.6  266.50  5269.7  271.93  5288.6  270.60  5294.0  269.37  5318.1  272.34
#Mann=5,-1,0
  4599.4    0.16       0  4762.4    0.12       0  4997.5    0.07       0
  5003.5    0.12       0  5216.6    0.16       0
Bank Sta=4997.5,5003.5
Exp/Cntr=0.3,0.1

Type RM Length L Ch R = 1,13368,612,612,612
BEGIN DESCRIPTION:
CEDAR CREEK EAST 23.0
END DESCRIPTION:
XS GIS Cut Line= 3
      3595004.04     10165278.14      3595892.11     10165191.64
      3596478.41     10164914.19
#Sta/Elev= 30
  4098.8  274.55  4413.6  268.45  4632.2  267.00  4729.0  257.33  4799.6  256.29
  4880.5  251.11  4971.0  253.19  4993.8  251.37  4996.7  248.64  4999.4  248.14
  5002.7  248.64  5035.3  258.55  5073.5  257.55  5096.2  261.98  5179.1  266.50
  5283.8  269.85  5300.8  267.38  5312.0  269.89  5386.9  272.57  5458.1  273.03
  5471.3  274.75  5488.5  270.96  5522.4  270.84  5533.2  267.15  5545.1  270.58
  5567.9  269.02  5584.0  273.65  5599.1  275.28  5636.1  279.08  5639.7  281.56
#Mann=9,-1,0
  4098.8    0.12       0  4413.6    0.16       0  4799.6    0.12       0
  4996.7    0.07       0  5002.7    0.12       0  5386.9    0.16       0
  5458.1     0.1       0  5584.0    0.16       0  5599.1     0.1       0
Bank Sta=4996.7,5002.7
Exp/Cntr=0.3,0.1

Type RM Length L Ch R = 1,12756,563,563,563
BEGIN DESCRIPTION:
CEDAR CREEK EAST 22.0
END DESCRIPTION:
XS GIS Cut Line= 3
      3595342.02     10165599.97      3595842.11     10165591.64
      3596315.98     10165579.14
#Sta/Elev= 30
  4474.3  269.62  4544.4  267.59  4614.4  264.94  4671.8  261.71  4676.8  262.07
  4724.4  258.45  4743.7  257.64  4824.4  254.79  4894.4  253.99  4914.4  254.10
  4924.5  253.54  4942.5  251.63  4977.0  251.58  4984.5  250.61  5001.5  245.95
  5004.2  245.45  5007.5  245.95  5024.5  251.10  5034.5  255.73  5044.5  261.92
  5054.5  266.76  5074.5  273.94  5084.5  277.96  5094.5  280.87  5104.5  281.98
  5154.5  282.91  5166.8  283.54  5314.6  286.37  5334.6  287.83  5448.5  290.83
#Mann=5,-1,0
  4474.3    0.05       0  4743.7    0.12       0  4942.5    0.16       0
  5001.5    0.07       0  5007.5    0.16       0
Bank Sta=5001.5,5007.5
Exp/Cntr=0.3,0.1

Type RM Length L Ch R = 1,12193,407,407,407
BEGIN DESCRIPTION:
CEDAR CREEK EAST 21.0
END DESCRIPTION:
XS GIS Cut Line= 3
      3595102.51     10165964.56      3595568.30     10165965.45
      3596321.18     10165834.35
#Sta/Elev= 30
  4534.2  272.36  4623.8  270.07  4673.8  265.27  4723.8  266.31  4788.4  265.61
  4933.8  260.05  4963.8  255.25  4996.4  245.51  4999.2  245.01  5002.4  245.51
  5024.2  249.53  5064.8  251.67  5131.3  249.90  5169.6  250.26  5206.9  253.53
  5217.0  251.86  5224.1  248.34  5229.2  251.19  5232.2  249.94  5237.3  247.82
  5247.5  247.32  5370.6  247.04  5511.4  246.98  5562.1  255.24  5571.6  258.06
  5576.7  262.67  5582.4  263.99  5636.3  269.49  5736.5  276.16  5764.2  278.28
#Mann=8,-1,0
  4534.2    0.05       0  4788.4    0.12       0  4996.4    0.07       0
  5002.4    0.12       0  5131.3    0.16       0  5232.2    0.05       0
  5370.6    0.07       0  5736.5    0.16       0
Bank Sta=4996.4,5002.4
Exp/Cntr=0.3,0.1

Type RM Length L Ch R = 1,11786,900,900,900
BEGIN DESCRIPTION:
CEDAR CREEK EAST 20.0
END DESCRIPTION:
XS GIS Cut Line= 3
      3595128.46     10166402.07      3595571.21     10166277.06
      3596321.21     10165943.72
#Sta/Elev= 30
  4610.2  270.72  4703.0  268.22  4810.2  268.14  4927.7  264.62  4961.7  266.31
  4967.3  263.74  4995.6  244.76  4997.9  244.08  5000.7  243.58  5003.9  244.08
  5019.2  247.42  5034.9  248.45  5136.9  247.33  5213.5  248.75  5271.0  253.45
  5288.8  252.84  5294.2  249.88  5300.8  248.60  5322.9  247.03  5416.0  247.91
  5421.4  250.20  5432.4  250.16  5491.2  247.39  5599.7  247.13  5763.4  246.75
  5856.0  252.29  5870.1  253.64  5879.7  256.58  5888.7  261.86  5891.0  261.86
#Mann=7,-1,0
  4610.2    0.16       0  4995.6    0.12       0  4997.9    0.07       0
  5003.9    0.12       0  5300.8    0.05       0  5599.7    0.07       0
  5856.0    0.16       0
Bank Sta=4997.9,5003.9
Exp/Cntr=0.3,0.1

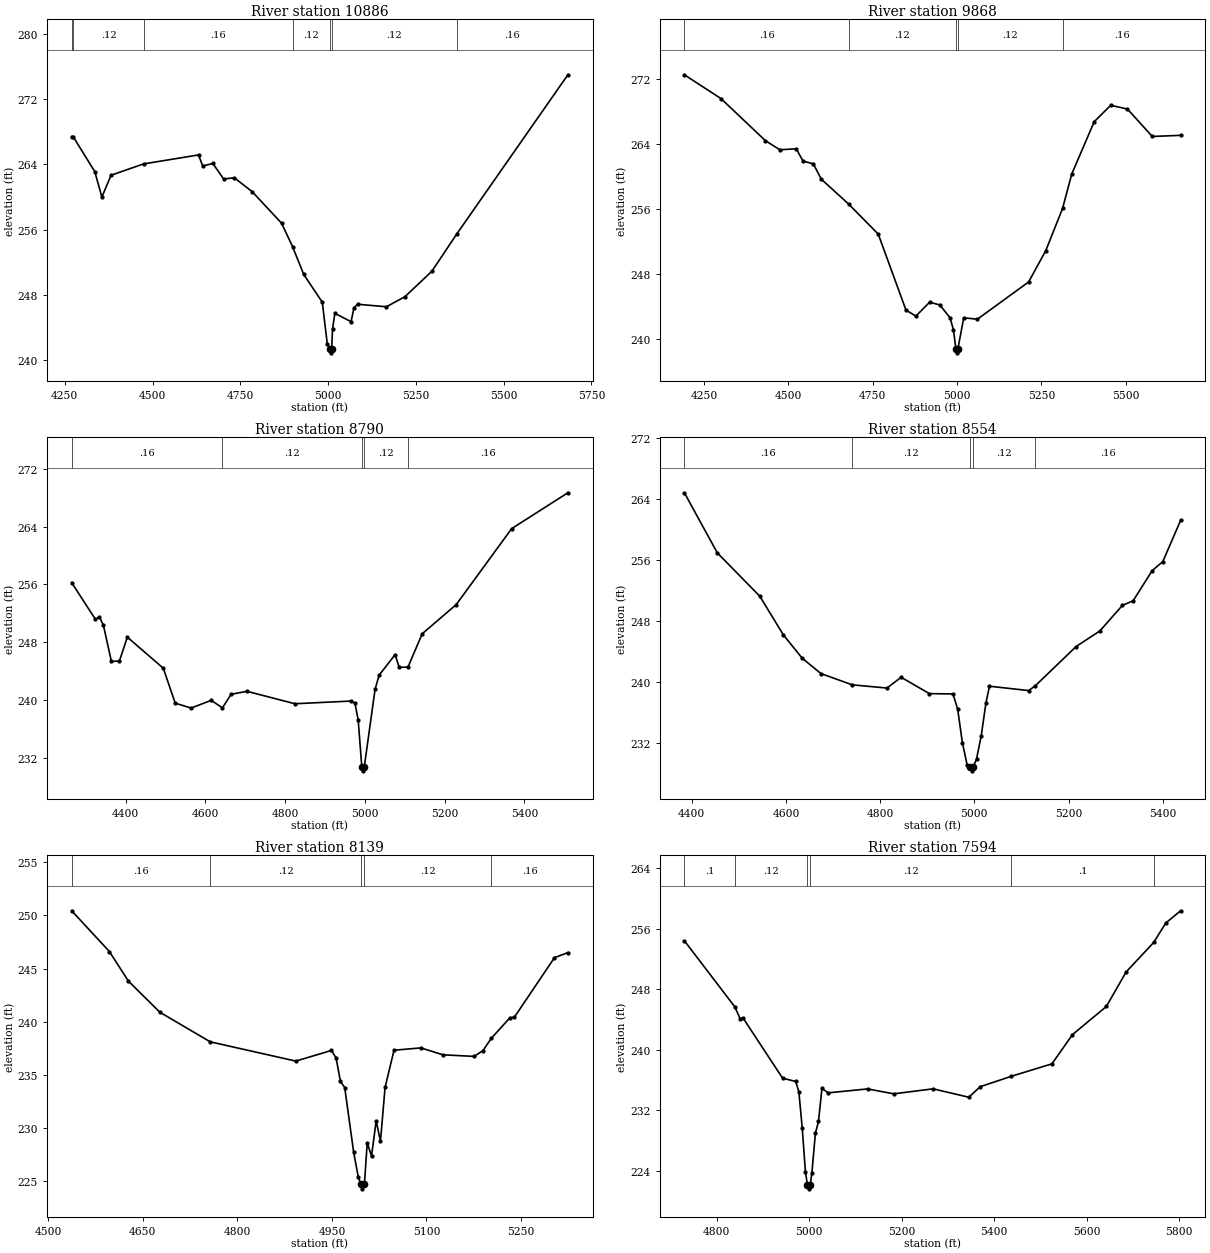
Type RM Length L Ch R = 1,10886,1018,1018,1018
BEGIN DESCRIPTION:
CEDAR CREEK EAST 19.0
END DESCRIPTION:
XS GIS Cut Line= 3
      3595177.71     10166484.75      3595732.67     10166594.76
      3596513.90     10166266.64
#Sta/Elev= 30
  4269.8  267.42  4275.0  267.35  4335.8  263.11  4355.8  260.00  4381.9  262.68
  4474.7  264.07  4631.1  265.17  4642.9  263.82  4671.9  264.12  4702.5  262.22
  4733.0  262.37  4784.0  260.66  4867.5  256.80  4898.7  253.94  4930.6  250.52
  4983.5  247.11  4997.6  242.04  5004.3  241.40  5007.0  240.90  5010.3  241.40
  5012.7  243.84  5019.3  245.74  5065.6  244.72  5073.6  246.43  5084.0  246.86
  5166.1  246.55  5219.0  247.79  5295.7  250.91  5366.5  255.48  5682.9  275.00
#Mann=7,-1,0
  4269.8    0.16       0  4275.0    0.12       0  4474.7    0.16       0
  4898.7    0.12       0  5004.3    0.07       0  5010.3    0.12       0
  5366.5    0.16       0
Bank Sta=5004.3,5010.3
Exp/Cntr=0.3,0.1

Type RM Length L Ch R = 1,9868,1078,1078,1078
BEGIN DESCRIPTION:
CEDAR CREEK EAST 18.0
END DESCRIPTION:
XS GIS Cut Line= 3
      3595195.04     10167161.82      3596467.04     10166954.14
      3596642.08     10166905.19
#Sta/Elev= 30
  4191.9  272.56  4300.4  269.63  4432.1  264.45  4475.0  263.33  4523.3  263.46
  4543.6  261.94  4574.0  261.60  4597.8  259.71  4678.5  256.66  4766.5  252.95
  4848.6  243.61  4877.9  242.87  4918.5  244.57  4948.9  244.25  4979.3  242.66
  4989.4  241.16  4996.5  238.85  4999.3  238.35  5002.5  238.85  5019.8  242.66
  5060.3  242.49  5212.1  247.07  5263.0  250.93  5312.7  256.12  5340.0  260.36
  5406.5  266.79  5455.5  268.81  5505.1  268.34  5578.6  264.97  5662.5  265.11
#Mann=5,-1,0
  4191.9    0.16       0  4678.5    0.12       0  4996.5    0.07       0
  5002.5    0.12       0  5312.7    0.16       0
Bank Sta=4996.5,5002.5
Exp/Cntr=0.3,0.1

Type RM Length L Ch R = 1,8790,236,236,236
BEGIN DESCRIPTION:
CEDAR CREEK EAST 17.0
END DESCRIPTION:
XS GIS Cut Line= 3
      3595602.45     10167594.76      3596222.25     10167573.93
      3596842.00     10167652.05
#Sta/Elev= 30
  4264.3  256.23  4324.0  251.14  4334.0  251.48  4344.0  250.31  4364.0  245.32
  4384.0  245.37  4404.0  248.68  4494.1  244.38  4524.1  239.54  4564.1  238.86
  4614.2  239.93  4642.6  238.89  4664.2  240.77  4704.2  241.18  4824.3  239.46
  4964.9  239.83  4975.0  239.55  4983.1  237.18  4992.2  230.67  4994.9  230.17
  4998.2  230.67  5025.4  241.45  5035.5  243.41  5075.8  246.27  5085.9  244.50
  5107.9  244.53  5143.7  249.15  5229.0  253.19  5368.1  263.71  5509.1  268.67
#Mann=5,-1,0
  4264.3    0.16       0  4642.6    0.12       0  4992.2    0.07       0
  4998.2    0.12       0  5107.9    0.16       0
Bank Sta=4992.2,4998.2
Exp/Cntr=0.3,0.1

Type RM Length L Ch R = 1,8554,415,415,415
BEGIN DESCRIPTION:
CEDAR CREEK EAST 16.0
END DESCRIPTION:
XS GIS Cut Line= 3
      3595642.09     10167791.64      3596292.11     10167791.64
      3596692.07     10167841.64
#Sta/Elev= 30
  4384.6  264.82  4454.6  256.94  4544.6  251.28  4594.6  246.22  4634.6  243.16
  4674.6  241.14  4741.0  239.67  4814.6  239.25  4844.6  240.66  4904.6  238.52
  4954.6  238.48  4964.6  236.48  4974.6  232.09  4984.6  229.20  4991.6  228.91
  4994.4  228.41  4997.6  228.91  5004.6  229.96  5014.6  233.00  5024.6  237.32
  5032.1  239.49  5115.2  238.92  5129.0  239.53  5216.0  244.69  5266.4  246.73
  5314.3  250.08  5337.0  250.68  5377.3  254.62  5399.9  255.81  5437.7  261.20
#Mann=5,-1,0
  4384.6    0.16       0  4741.0    0.12       0  4991.6    0.07       0
  4997.6    0.12       0  5129.0    0.16       0
Bank Sta=4991.6,4997.6
Exp/Cntr=0.3,0.1

Type RM Length L Ch R = 1,8139,545,545,545
BEGIN DESCRIPTION:
CEDAR CREEK EAST 15.0
END DESCRIPTION:
XS GIS Cut Line= 3
      3595792.11     10167991.64      3596062.87     10167990.86
      3596442.14     10168341.67
#Sta/Elev= 30
  4537.1  250.44  4597.1  246.60  4627.1  243.83  4677.1  240.90  4757.0  238.12
  4892.7  236.31  4949.4  237.31  4956.7  236.60  4963.6  234.40  4970.4  233.82
  4984.6  227.72  4991.9  225.41  4995.7  224.80  4998.5  224.30  5001.7  224.80
  5006.1  228.63  5012.9  227.38  5020.3  230.69  5027.1  228.76  5034.4  233.83
  5048.6  237.33  5091.1  237.55  5126.3  236.90  5175.6  236.75  5189.8  237.30
  5203.0  238.45  5232.3  240.37  5239.7  240.45  5303.2  246.03  5324.5  246.51
#Mann=5,-1,0
  4537.1    0.16       0  4757.0    0.12       0  4995.7    0.07       0
  5001.7    0.12       0  5203.0    0.16       0
Bank Sta=4995.7,5001.7
Exp/Cntr=0.3,0.1

Type RM Length L Ch R = 1,7594,637,637,637
BEGIN DESCRIPTION:
CEDAR CREEK EAST 14.0
END DESCRIPTION:
XS GIS Cut Line= 3
      3595692.14     10168141.67      3596079.75     10168495.42
      3596592.09     10168691.64
#Sta/Elev= 30
  4729.8  254.40  4838.5  245.70  4850.3  244.13  4857.1  244.16  4942.2  236.25
  4970.6  235.81  4977.4  234.46  4984.8  229.62  4991.6  223.91  4996.0  222.13
  4998.7  221.63  5002.0  222.13  5005.7  223.76  5013.2  228.98  5019.9  230.53
  5027.3  234.89  5041.1  234.31  5126.0  234.83  5182.8  234.18  5267.8  234.84
  5345.0  233.73  5369.7  235.12  5437.2  236.50  5524.8  238.14  5569.3  242.00
  5642.6  245.72  5685.4  250.28  5744.9  254.17  5771.1  256.74  5803.2  258.36
#Mann=6,-1,0
  4729.8     0.1       0  4838.5    0.12       0  4996.0    0.07       0
  5002.0    0.12       0  5437.2     0.1       0  5744.9    0.16       0
Bank Sta=4996,5002
Exp/Cntr=0.3,0.1

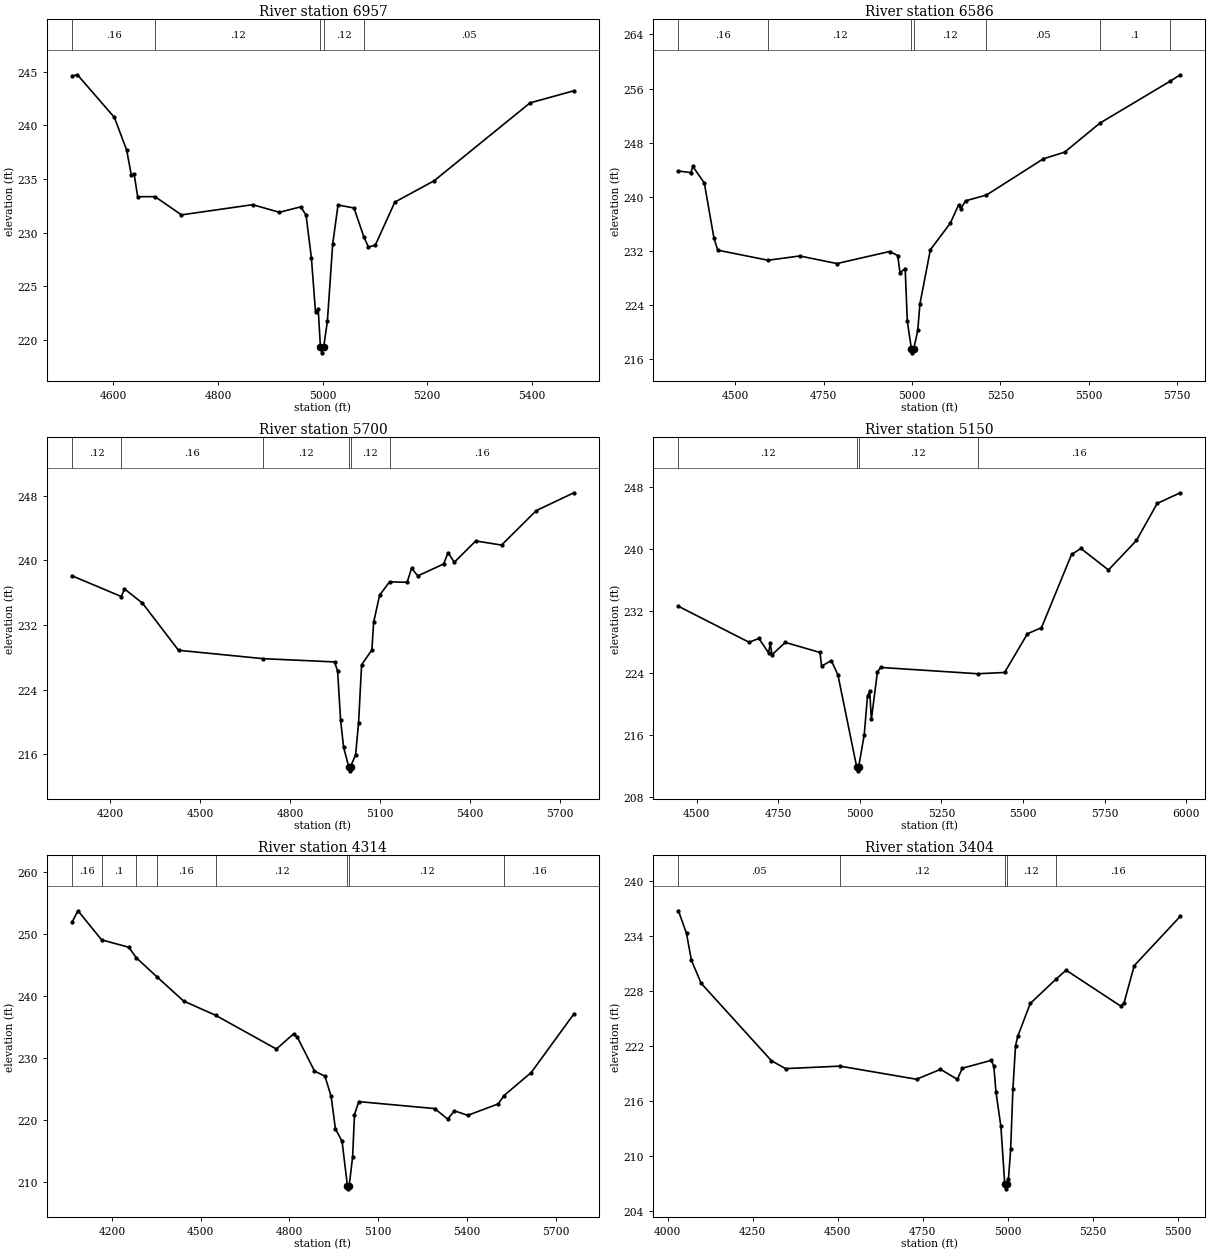
Type RM Length L Ch R = 1,6957,371,371,371
BEGIN DESCRIPTION:
CEDAR CREEK EAST 13.0
END DESCRIPTION:
XS GIS Cut Line= 3
      3595542.10     10168541.61      3595633.71     10168834.35
      3596274.37     10168964.56
#Sta/Elev= 30
  4520.5  244.60  4531.0  244.72  4601.7  240.75  4625.3  237.69  4634.1  235.37
  4639.4  235.50  4646.3  233.36  4679.5  233.37  4730.1  231.67  4866.4  232.62
  4917.4  231.91  4958.3  232.42  4968.5  231.65  4978.7  227.68  4986.6  222.63
  4991.7  222.94  4996.1  219.32  4998.8  218.82  5002.1  219.32  5009.3  221.74
  5019.5  228.96  5029.7  232.59  5060.3  232.31  5078.9  229.65  5087.8  228.67
  5101.1  228.86  5138.4  232.86  5213.4  234.84  5397.1  242.10  5481.0  243.23
#Mann=5,-1,0
  4520.5    0.16       0  4679.5    0.12       0  4996.1    0.07       0
  5002.1    0.12       0  5078.9    0.05       0
Bank Sta=4996.1,5002.1
Exp/Cntr=0.3,0.1

Type RM Length L Ch R = 1,6586,886,886,886
BEGIN DESCRIPTION:
CEDAR CREEK EAST 12.0
END DESCRIPTION:
XS GIS Cut Line= 4
      3595455.64     10168585.53      3595585.51     10169000.20
      3595805.58     10169308.31      3596373.29     10169521.85
#Sta/Elev= 30
  4339.4  243.81  4374.9  243.58  4380.1  244.49  4412.6  242.05  4439.8  233.94
  4450.6  232.12  4592.8  230.63  4682.6  231.26  4787.9  230.14  4936.6  231.92
  4959.9  231.32  4966.1  228.77  4980.8  229.41  4986.9  221.61  4998.7  217.45
  5001.4  216.95  5004.7  217.45  5016.4  220.28  5022.6  224.21  5052.1  232.19
  5108.6  236.11  5132.0  238.82  5138.1  238.22  5151.5  239.41  5210.7  240.26
  5371.5  245.61  5431.9  246.60  5531.7  250.89  5731.0  257.10  5759.1  258.03
#Mann=7,-1,0
  4339.4    0.16       0  4592.8    0.12       0  4998.7    0.07       0
  5004.7    0.12       0  5210.7    0.05       0  5531.7     0.1       0
  5731.0    0.05       0
Bank Sta=4998.7,5004.7
Exp/Cntr=0.3,0.1

Type RM Length L Ch R = 1,5700,550,550,550
BEGIN DESCRIPTION:
CEDAR CREEK EAST 11.0
END DESCRIPTION:
XS GIS Cut Line= 3
      3595186.35     10168446.59      3595264.47     10169548.97
      3595731.65     10169877.72
#Sta/Elev= 30
  4071.4  238.10  4236.3  235.53  4246.9  236.47  4307.0  234.71  4427.3  228.88
  4710.6  227.84  4948.6  227.44  4958.7  226.29  4968.7  220.24  4978.7  216.89
  4995.8  214.46  4998.5  213.96  5001.8  214.46  5018.8  215.95  5028.8  219.92
  5038.9  227.09  5073.2  228.92  5079.0  232.33  5099.0  235.70  5132.3  237.35
  5190.9  237.29  5205.7  239.04  5226.7  238.09  5312.9  239.56  5327.7  240.96
  5348.6  239.77  5420.0  242.41  5506.3  241.90  5622.1  246.16  5747.8  248.37
#Mann=6,-1,0
  4071.4    0.12       0  4236.3    0.16       0  4710.6    0.12       0
  4995.8    0.07       0  5001.8    0.12       0  5132.3    0.16       0
Bank Sta=4995.8,5001.8
Exp/Cntr=0.3,0.1

Type RM Length L Ch R = 1,5150,836,836,836
BEGIN DESCRIPTION:
CEDAR CREEK EAST 10.0
END DESCRIPTION:
XS GIS Cut Line= 3
      3594680.58     10168777.06      3594789.96     10169610.39
      3595242.11     10170141.65
#Sta/Elev= 30
  4444.2  232.65  4660.6  228.01  4690.9  228.50  4720.5  226.64  4725.5  227.85
  4731.2  226.40  4771.6  227.99  4878.0  226.69  4883.0  224.93  4912.8  225.64
  4932.9  223.82  4990.5  211.93  4993.2  211.43  4996.5  211.93  5013.6  216.07
  5023.7  221.09  5030.5  221.67  5035.5  218.05  5054.0  224.17  5064.1  224.76
  5361.5  223.95  5443.7  224.11  5513.9  229.11  5556.8  229.88  5649.0  239.33
  5677.6  240.10  5762.1  237.33  5847.8  241.13  5911.5  245.91  5982.3  247.28
#Mann=4,-1,0
  4444.2    0.12       0  4990.5    0.07       0  4996.5    0.12       0
  5361.5    0.16       0
Bank Sta=4990.5,4996.5
Exp/Cntr=0.3,0.1

Type RM Length L Ch R = 1,4314,910,910,910
BEGIN DESCRIPTION:
CEDAR CREEK EAST 8.0
END DESCRIPTION:
XS GIS Cut Line= 3
      3593675.90     10169219.09      3594633.71     10169948.93
      3595069.82     10170177.37
#Sta/Elev= 30
  4065.1  251.85  4085.5  253.71  4165.4  249.02  4257.1  247.84  4282.7  246.13
  4352.2  243.08  4442.2  239.18  4550.9  236.87  4756.1  231.44  4814.2  233.88
  4827.2  233.33  4884.9  227.90  4920.3  227.05  4941.1  223.83  4955.6  218.59
  4978.1  216.58  4996.2  209.42  4999.0  208.92  5002.2  209.42  5013.8  214.05
  5020.1  220.87  5034.6  222.97  5290.8  221.85  5335.2  220.16  5357.8  221.49
  5402.9  220.76  5505.8  222.60  5525.4  223.94  5617.4  227.65  5761.6  237.09
#Mann=8,-1,0
  4065.1    0.16       0  4165.4     0.1       0  4282.7    0.12       0
  4352.2    0.16       0  4550.9    0.12       0  4996.2    0.07       0
  5002.2    0.12       0  5525.4    0.16       0
Bank Sta=4996.2,5002.2
Exp/Cntr=0.3,0.1

Type RM Length L Ch R = 1,3404,493,493,493
BEGIN DESCRIPTION:
CEDAR CREEK EAST 7.0
END DESCRIPTION:
XS GIS Cut Line= 3
      3593768.20     10169862.02      3594659.75     10170584.35
      3594987.47     10170579.15
#Sta/Elev= 30
  4031.9  236.78  4055.7  234.31  4070.1  231.37  4098.8  228.87  4305.0  220.44
  4346.7  219.57  4506.5  219.84  4731.8  218.41  4802.2  219.49  4851.8  218.40
  4866.2  219.61  4950.9  220.47  4958.9  219.88  4965.3  216.99  4979.7  213.27
  4991.1  206.96  4993.8  206.46  4997.1  206.96  5002.0  207.53  5008.4  210.76
  5015.1  217.40  5022.8  222.08  5029.2  223.08  5065.9  226.67  5141.5  229.32
  5171.5  230.30  5331.7  226.39  5341.7  226.74  5371.7  230.80  5507.1  236.18
#Mann=5,-1,0
  4031.9    0.05       0  4506.5    0.12       0  4991.1    0.07       0
  4997.1    0.12       0  5141.5    0.16       0
Bank Sta=4991.1,4997.1
Exp/Cntr=0.3,0.1

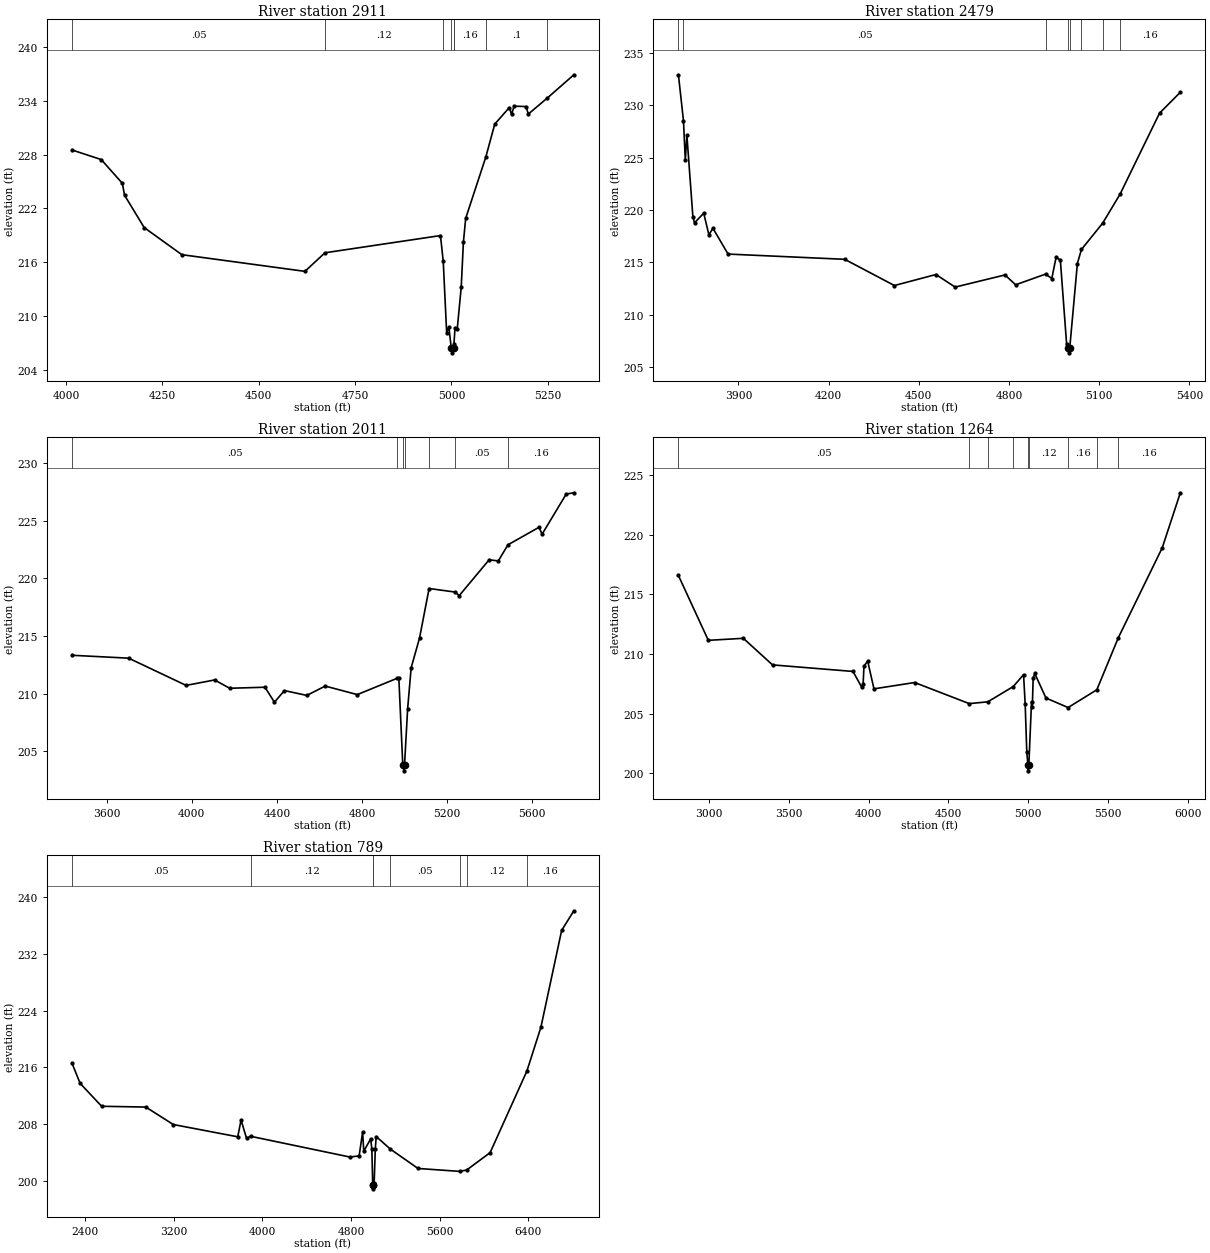
Type RM Length L Ch R = 1,2911,432,432,432
BEGIN DESCRIPTION:
CEDAR CREEK EAST 6.0
END DESCRIPTION:
XS GIS Cut Line= 3
      3593763.65     10170085.77      3594087.83     10170702.17
      3594617.58     10170995.53
#Sta/Elev= 30
  4015.5  228.52  4091.5  227.45  4146.3  224.80  4151.9  223.48  4202.9  219.87
  4300.6  216.85  4619.9  214.99  4671.8  217.06  4971.5  218.98  4978.7  216.09
  4987.5  208.17  4993.2  208.79  4999.6  206.41  5002.4  205.91  5005.6  206.41
  5006.4  206.90  5009.3  208.69  5015.0  208.58  5025.3  213.22  5031.0  218.25
  5036.9  220.90  5089.1  227.73  5112.3  231.40  5150.1  233.25  5155.8  232.49
  5162.6  233.40  5193.6  233.36  5199.3  232.52  5248.7  234.31  5317.5  236.90
#Mann=8,-1,0
  4015.5    0.05       0  4671.8    0.12       0  4978.7     0.1       0
  4999.6    0.07       0  5005.6     0.1       0  5006.4    0.16       0
  5089.1     0.1       0  5248.7    0.16       0
Bank Sta=4999.6,5005.6
Exp/Cntr=0.3,0.1

Type RM Length L Ch R = 1,2479,468,468,468
BEGIN DESCRIPTION:
CEDAR CREEK EAST 5.0
END DESCRIPTION:
XS GIS Cut Line= 4
      3593498.83     10170026.42      3593823.00     10170921.34
      3594201.42     10171266.64      3594392.10     10171191.65
#Sta/Elev= 30
  3700.6  232.89  3717.4  228.51  3723.5  224.77  3728.8  227.11  3748.7  219.35
  3754.1  218.77  3784.8  219.69  3801.9  217.62  3815.4  218.25  3865.7  215.79
  4253.7  215.29  4418.8  212.79  4557.0  213.84  4620.8  212.64  4786.6  213.80
  4822.0  212.86  4921.6  213.88  4942.2  213.46  4956.4  215.47  4970.6  215.23
  4991.5  207.20  4996.0  206.87  4998.7  206.37  5002.0  206.87  5027.3  214.89
  5040.8  216.23  5111.4  218.74  5169.0  221.49  5300.5  229.23  5369.6  231.22
#Mann=8,-1,0
  3700.6    0.16       0  3717.4    0.05       0  4921.6    0.12       0
  4996.0    0.07       0  5002.0    0.12       0  5040.8    0.16       0
  5111.4    0.05       0  5169.0    0.16       0
Bank Sta=4996,5002
Exp/Cntr=0.3,0.1

Type RM Length L Ch R = 1,2011,747,747,747
BEGIN DESCRIPTION:
CEDAR CREEK EAST 4.0
END DESCRIPTION:
XS GIS Cut Line= 4
      3593133.53     10170268.37      3593661.48     10171497.54
      3594133.71     10171629.49      3594542.11     10171291.64
#Sta/Elev= 30
  3436.9  213.33  3703.2  213.08  3973.2  210.72  4107.3  211.19  4177.9  210.47
  4343.8  210.56  4388.1  209.26  4435.2  210.27  4540.3  209.85  4626.8  210.66
  4777.6  209.92  4965.4  211.34  4972.6  211.40  4991.2  203.84  4993.4  203.81
  4996.2  203.31  4999.4  203.81  5014.1  208.70  5030.6  212.25  5069.9  214.82
  5114.9  219.12  5237.7  218.81  5256.3  218.50  5397.0  221.61  5440.0  221.51
  5485.4  222.91  5631.5  224.43  5645.8  223.83  5759.2  227.31  5795.0  227.42
#Mann=7,-1,0
  3436.9    0.05       0  4965.4    0.12       0  4993.4    0.07       0
  4999.4    0.12       0  5114.9    0.16       0  5237.7    0.05       0
  5485.4    0.16       0
Bank Sta=4993.4,4999.4
Exp/Cntr=0.3,0.1

Type RM Length L Ch R = 1,1264,475,475,475
BEGIN DESCRIPTION:
CEDAR CREEK EAST 3.0
END DESCRIPTION:
XS GIS Cut Line= 4
      3592861.13     10170463.68      3593633.71     10172182.44
      3594111.14     10172217.16      3594642.08     10171641.67
#Sta/Elev= 30
  2807.3  216.59  2994.8  211.15  3214.2  211.32  3397.1  209.09  3901.4  208.54
  3956.3  207.22  3965.0  207.45  3970.5  208.99  3993.6  209.41  4033.0  207.08
  4288.0  207.61  4630.4  205.84  4746.6  205.99  4906.0  207.27  4970.8  208.27
  4980.9  205.81  4990.9  201.79  4997.9  200.70  5000.7  200.20  5003.9  200.70
  5020.7  206.01  5025.7  205.53  5031.0  207.99  5041.0  208.37  5111.2  206.31
  5249.8  205.51  5430.0  207.00  5564.8  211.37  5840.3  218.92  5953.4  223.53
#Mann=9,-1,0
  2807.3    0.05       0  4630.4    0.12       0  4746.6    0.05       0
  4906.0    0.12       0  4997.9    0.07       0  5003.9    0.12       0
  5249.8    0.16       0  5430.0    0.12       0  5564.8    0.16       0
Bank Sta=4997.9,5003.9
Exp/Cntr=0.3,0.1

Type RM Length L Ch R = 1,789,0,0,0
BEGIN DESCRIPTION:
CEDAR CREEK EAST 1.0
END DESCRIPTION:
XS GIS Cut Line= 4
      3592689.28     10170400.36      3593518.62     10172552.86
      3594328.15     10172789.21      3594967.04     10171566.98
#Sta/Elev= 30
  2281.2  216.59  2355.4  213.73  2549.2  210.51  2947.5  210.40  3195.9  207.94
  3777.3  206.21  3807.3  208.57  3856.5  206.02  3893.9  206.28  4789.5  203.36
  4872.8  203.52  4904.1  206.87  4914.5  204.19  4977.0  205.91  4987.4  204.51
  4995.5  199.38  4998.2  198.88  5001.5  199.38  5008.3  199.72  5018.7  204.54
  5026.8  206.25  5154.3  204.48  5404.1  201.75  5779.4  201.34  5843.1  201.53
  6054.9  203.98  6386.5  215.47  6512.9  221.63  6700.3  235.29  6810.4  238.05
#Mann=8,-1,0
  2281.2    0.05       0  3893.9    0.12       0  4995.5    0.07       0
  5001.5    0.12       0  5154.3    0.05       0  5779.4    0.16       0
  5843.1    0.12       0  6386.5    0.16       0
Bank Sta=4995.5,5001.5
Exp/Cntr=0.3,0.1

Chan Stop Cuts=-1