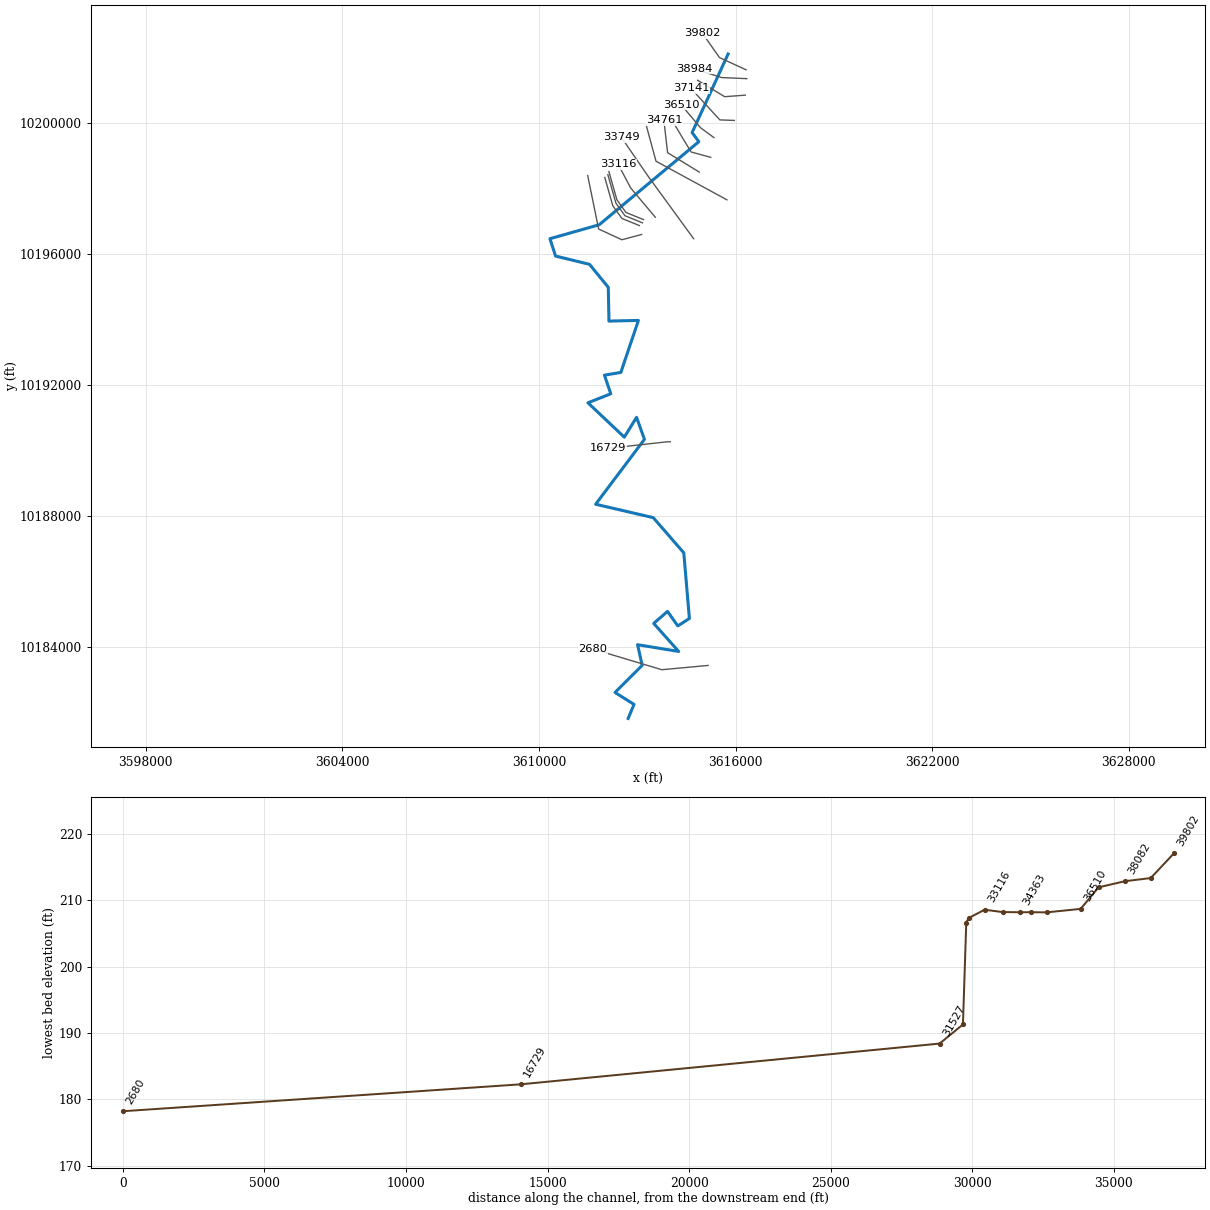
--- DINNER CREEK.prj (project) ---

Proj Title=DINNER CREEK Base Level Engineering
Current Plan=p01
Default Exp/Contr=0.3,0.1
English Units
Geom File=g01
Flow File=f01
Plan File=p01
BEGIN DESCRIPTION:
DINNER CREEK
END DESCRIPTION:

--- DINNER CREEK.p01 (plan) ---

Plan Title=Multiple Run
Short Identifier=Multiple
Geom File=g01
Flow File=f01
Subcritical Flow
K Sum by GR= 0
Std Step Tol= 0.01
Critical Tol= 0.01
Num of Std Step Trials= 20
Max Error Tol= 0.3
Flow Tol Ratio= 0.001
Split Flow NTrial= 30
Split Flow Tol= 0.02
Split Flow Ratio= 0.02
Log Output Level= 0
Friction Slope Method= 1
Unsteady Friction Slope Method= 2
Unsteady Bridges Friction Slope Method= 1
Parabolic Critical Depth
Global Vel Dist=  1 , 1 , 1
Global Log Level= 0
CheckData=True
Encroach Param= -1, 0, 0, 0
BEGIN DESCRIPTION:
Multiple Run
END DESCRIPTION:

--- DINNER CREEK.f01 (steady flow) ---

Flow Title=Multiple
Number of Profiles=7
Profile Names=10-year,25-year,50-year,1pct_min,100-year,1pct_plu,500-year
River Rch & RM= DINNER CREEK,Reach-1,39802
     965    1335    1644    1482    2004    2711    2985
River Rch & RM= DINNER CREEK,Reach-1,33749
    1458    2049    2550    2319    3136    4241    4755
River Rch & RM= DINNER CREEK,Reach-1,16729
    1542    2152    2665    2409    3258    4406    4882
River Rch & RM= DINNER CREEK,Reach-1,2680
    1806    2525    3130    2830    3827    5176    5737
Boundary for River Rch & Prof#=DINNER CREEK,Reach-1,1
Up Type=0
Dn Type=3
Dn Slope=0.005
Boundary for River Rch & Prof#=DINNER CREEK,Reach-1,2
Up Type=0
Dn Type=3
Dn Slope=0.005
Boundary for River Rch & Prof#=DINNER CREEK,Reach-1,3
Up Type=0
Dn Type=3
Dn Slope=0.005
Boundary for River Rch & Prof#=DINNER CREEK,Reach-1,4
Up Type=0
Dn Type=3
Dn Slope=0.005
Boundary for River Rch & Prof#=DINNER CREEK,Reach-1,5
Up Type=0
Dn Type=3
Dn Slope=0.005
Boundary for River Rch & Prof#=DINNER CREEK,Reach-1,6
Up Type=0
Dn Type=3
Dn Slope=0.005
Boundary for River Rch & Prof#=DINNER CREEK,Reach-1,7
Up Type=0
Dn Type=3
Dn Slope=0.005

--- DINNER CREEK.g01 (geometry) ---

Geom Title=Existing Conditions

River Reach=DINNER CREEK,Reach-1
Reach XY= 30
      3615772.11     10202092.96      3614674.24     10199697.64
      3614878.92     10199417.96      3611839.09     10196884.86
      3610337.07     10196459.01      3610508.78     10195929.87
      3611544.60     10195677.66      3612117.27     10194975.90
      3612138.41     10193946.25      3613036.32     10193966.65
      3612499.84     10192379.70      3611999.84     10192296.36
      3612194.29     10191728.65      3611496.52     10191453.32
      3612605.90     10190405.14      3612979.59     10191010.61
      3613220.48     10190338.95      3611731.61     10188358.86
      3613489.43     10187950.01      3614420.41     10186877.17
      3614591.81     10184873.81      3614237.64     10184647.76
      3613923.35     10185090.04      3613503.96     10184723.80
      3614265.42     10183867.56      3613011.25     10184074.15
      3613150.84     10183443.60      3612322.33     10182617.63
      3612901.88     10182252.62      3612723.34     10181823.32

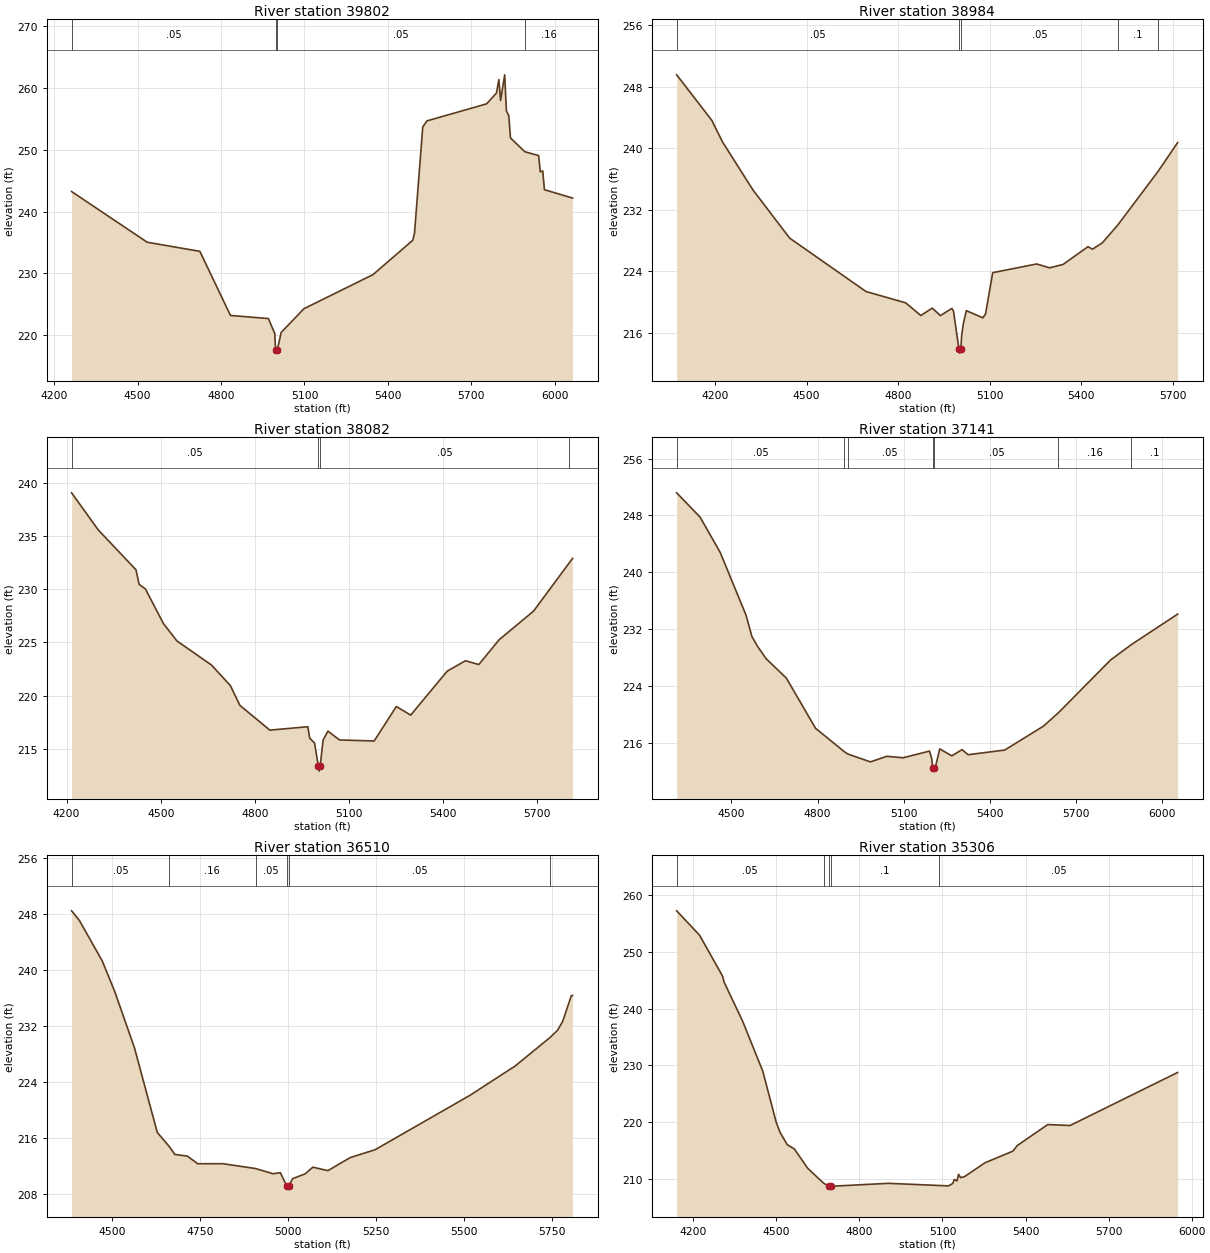
Type RM Length L Ch R = 1,39802,818,818,818
BEGIN DESCRIPTION:
DINNER CREEK 40.0
END DESCRIPTION:
XS GIS Cut Line= 3
      3616321.10     10201611.71      3615510.35     10201984.33
      3614987.77     10202727.52
#Sta/Elev= 30
  4262.9  243.23  4534.8  235.03  4724.0  233.56  4834.1  223.19  4970.4  222.69
  4993.4  220.25  4996.2  217.60  4998.9  217.10  5002.2  217.60  5016.4  220.45
  5098.2  224.28  5346.7  229.80  5489.6  235.36  5495.7  236.52  5525.3  253.66
  5540.1  254.65  5754.5  257.40  5790.2  259.15  5798.9  261.33  5805.0  257.95
  5819.8  262.10  5825.9  256.30  5834.6  255.47  5840.7  251.89  5892.4  249.66
  5941.8  249.05  5947.9  246.40  5956.6  246.57  5962.7  243.53  6063.7  242.17
#Mann=4,-1,0
  4262.9    0.05       0  4996.2    0.03       0  5002.2    0.05       0
  5892.4    0.16       0
Bank Sta=4996.2,5002.2
Exp/Cntr=0.3,0.1

Type RM Length L Ch R = 1,38984,902,902,902
BEGIN DESCRIPTION:
DINNER CREEK 39.0
END DESCRIPTION:
XS GIS Cut Line= 3
      3616342.13     10201341.64      3615578.06     10201374.96
      3614742.06     10201641.66
#Sta/Elev= 30
  4073.9  249.56  4188.9  243.65  4224.1  240.84  4324.2  234.58  4444.3  228.33
  4694.5  221.39  4824.6  219.92  4874.2  218.27  4911.6  219.23  4938.6  218.26
  4976.0  219.19  4981.4  218.84  4999.4  213.88  5002.1  213.38  5005.4  213.88
  5008.2  215.68  5013.4  217.16  5023.4  218.90  5077.8  217.97  5086.4  218.47
  5110.0  223.84  5254.3  224.97  5296.3  224.47  5340.7  224.91  5422.3  227.22
  5437.2  226.89  5469.4  227.72  5520.7  230.07  5652.5  237.03  5716.2  240.75
#Mann=5,-1,0
  4073.9    0.05       0  4999.4    0.03       0  5005.4    0.05       0
  5520.7     0.1       0  5652.5    0.05       0
Bank Sta=4999.4,5005.4
Exp/Cntr=0.3,0.1

Type RM Length L Ch R = 1,38082,941,941,941
BEGIN DESCRIPTION:
DINNER CREEK 37.0
END DESCRIPTION:
XS GIS Cut Line= 3
      3616296.79     10200838.50      3615666.60     10200791.62
      3614842.10     10201291.64
#Sta/Elev= 30
  4216.0  239.05  4300.9  235.57  4421.2  231.82  4431.3  230.45  4451.3  230.02
  4508.5  226.78  4551.6  225.14  4661.9  222.87  4722.1  220.94  4752.2  219.09
  4847.7  216.76  4968.8  217.08  4974.7  216.01  4990.1  215.55  5002.2  213.41
  5005.0  212.91  5008.2  213.41  5017.3  215.82  5032.8  216.67  5069.6  215.84
  5180.1  215.74  5250.8  218.98  5296.5  218.17  5412.8  222.30  5471.0  223.28
  5513.6  222.92  5578.3  225.25  5688.1  227.94  5800.4  232.42  5812.2  232.89
#Mann=4,-1,0
  4216.0    0.05       0  5002.2    0.03       0  5008.2    0.05       0
  5800.4    0.16       0
Bank Sta=5002.2,5008.2
Exp/Cntr=0.3,0.1

Type RM Length L Ch R = 1,37141,631,631,631
BEGIN DESCRIPTION:
DINNER CREEK 35.0
END DESCRIPTION:
XS GIS Cut Line= 3
      3615963.45     10200067.66      3615520.77     10200083.29
      3614642.14     10201041.61
#Sta/Elev= 30
  4309.9  251.17  4391.3  247.75  4461.3  242.78  4551.4  233.92  4571.4  230.97
  4591.4  229.54  4621.4  227.80  4691.5  225.08  4793.0  218.02  4892.5  214.74
  4905.2  214.39  4984.1  213.28  5040.9  214.07  5097.6  213.86  5189.5  214.80
  5196.9  213.81  5200.7  212.48  5203.4  211.98  5206.7  212.48  5211.1  212.71
  5225.2  215.11  5267.2  214.13  5302.9  215.01  5323.9  214.29  5451.5  214.95
  5586.0  218.31  5638.2  220.20  5819.7  227.63  5892.1  229.80  6053.0  234.09
#Mann=7,-1,0
  4309.9    0.05       0  4892.5    0.16       0  4905.2    0.05       0
  5200.7    0.03       0  5206.7    0.05       0  5638.2    0.16       0
  5892.1     0.1       0
Bank Sta=5200.7,5206.7
Exp/Cntr=0.3,0.1

Type RM Length L Ch R = 1,36510,1204,1204,1204
BEGIN DESCRIPTION:
DINNER CREEK 34.0
END DESCRIPTION:
XS GIS Cut Line= 3
      3615342.14     10199541.62      3614932.22     10199843.71
      3614342.10     10200541.65
#Sta/Elev= 30
  4384.3  248.44  4406.3  247.08  4471.1  241.32  4506.6  236.97  4562.9  228.90
  4627.7  216.82  4661.5  214.83  4677.8  213.68  4713.3  213.44  4742.6  212.35
  4813.5  212.36  4906.9  211.67  4956.3  210.93  4977.4  211.07  4995.2  209.23
  4998.0  208.73  5001.2  209.23  5012.5  210.23  5047.9  210.91  5069.7  211.86
  5112.6  211.37  5176.3  213.24  5246.5  214.35  5516.9  222.14  5644.3  226.29
  5743.4  230.36  5765.2  231.41  5779.5  232.66  5804.2  236.35  5807.5  236.35
#Mann=6,-1,0
  4384.3    0.05       0  4661.5    0.16       0  4906.9    0.05       0
  4995.2    0.03       0  5001.2    0.05       0  5743.4     0.1       0
Bank Sta=4995.2,5001.2
Exp/Cntr=0.3,0.1

Type RM Length L Ch R = 1,35306,545,545,545
BEGIN DESCRIPTION:
DINNER CREEK 31.0
END DESCRIPTION:
XS GIS Cut Line= 4
      3615242.08     10198941.65      3614645.77     10199104.12
      3614421.81     10199468.71      3614031.20     10200124.93
#Sta/Elev= 30
  4139.8  257.22  4222.7  252.91  4305.6  245.71  4310.9  244.68  4378.2  237.76
  4450.7  228.99  4499.3  219.98  4512.9  218.23  4539.0  216.04  4564.7  215.28
  4613.3  211.86  4670.4  209.25  4689.8  208.70  4692.6  208.20  4695.8  208.70
  4904.9  209.22  5088.3  208.84  5121.5  208.77  5136.9  209.19  5142.7  209.90
  5152.3  209.65  5158.2  210.80  5165.7  210.22  5179.5  210.40  5253.4  212.84
  5354.6  214.90  5370.2  215.88  5480.1  219.57  5561.1  219.41  5949.4  228.75
#Mann=5,-1,0
  4139.8    0.05       0  4670.4     0.1       0  4689.8    0.07       0
  4695.8     0.1       0  5088.3    0.05       0
Bank Sta=4689.8,4695.8
Exp/Cntr=0.3,0.1

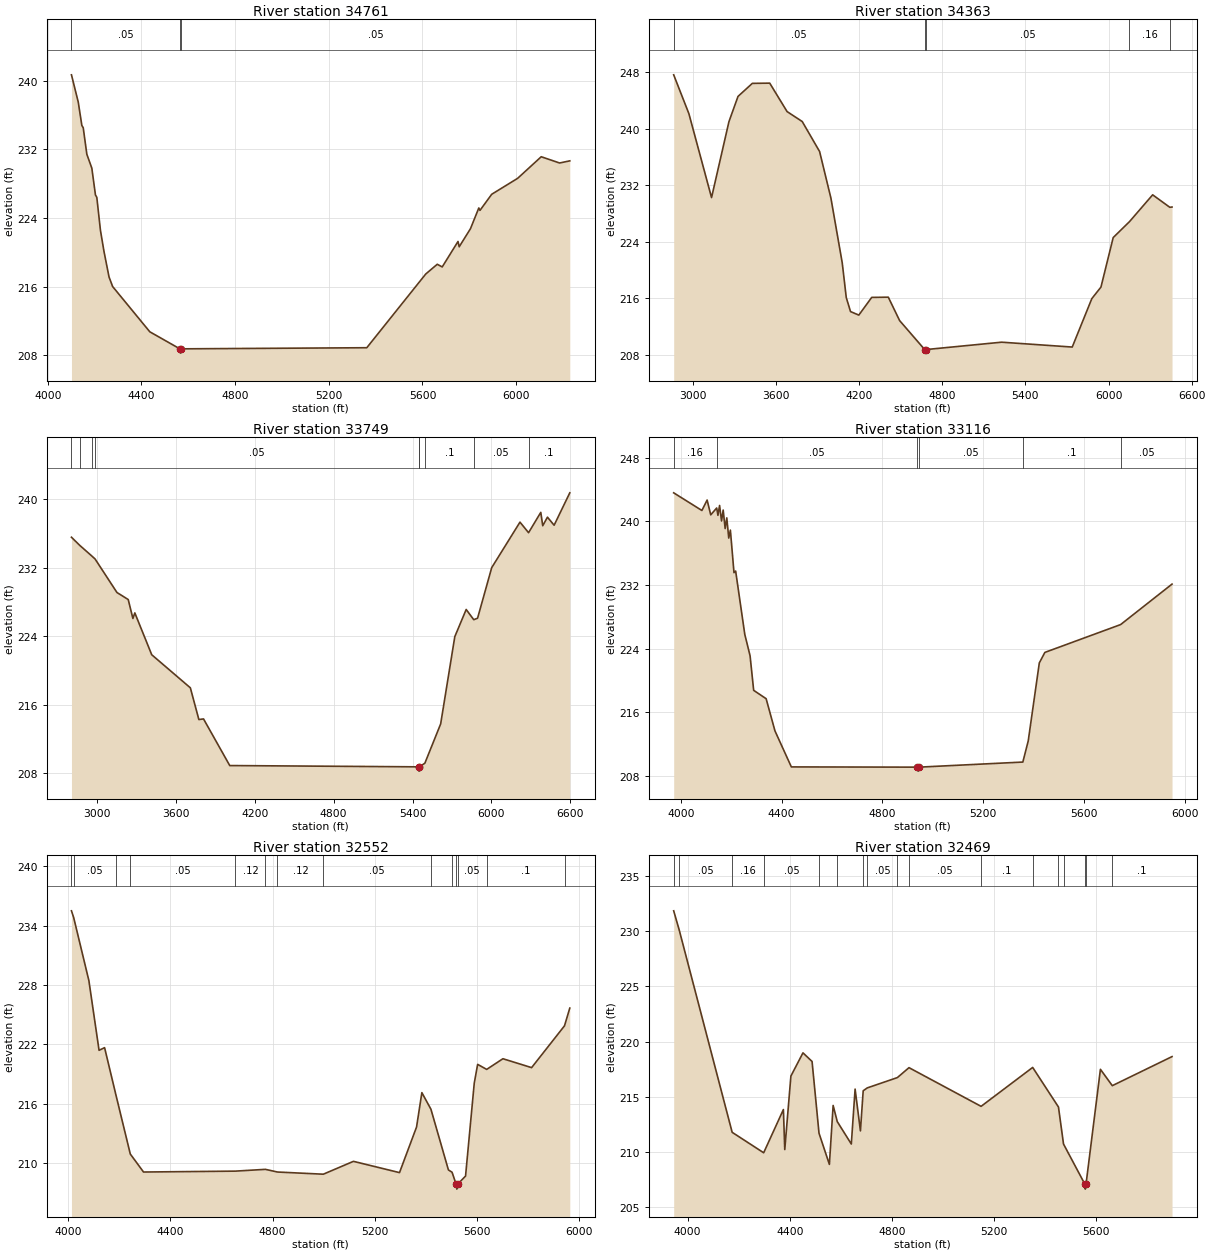
Type RM Length L Ch R = 1,34761,398,398,398
BEGIN DESCRIPTION:
DINNER CREEK 30.0
END DESCRIPTION:
XS GIS Cut Line= 3
      3614892.11     10198491.64      3613927.02     10199083.29
      3613812.43     10200072.87
#Sta/Elev= 30
  4101.0  240.71  4130.0  237.53  4145.4  234.80  4151.3  234.53  4166.7  231.44
  4188.0  229.82  4203.5  226.69  4209.3  226.41  4224.8  222.56  4240.2  220.06
  4261.5  217.12  4276.9  216.00  4435.6  210.72  4564.0  208.73  4566.8  208.23
  4570.0  208.73  5362.2  208.86  5613.9  217.46  5663.1  218.60  5684.4  218.29
  5751.8  221.26  5756.9  220.64  5805.2  222.76  5840.6  225.17  5845.6  224.89
  5895.8  226.77  6006.5  228.63  6107.2  231.15  6185.6  230.42  6229.2  230.67
#Mann=3,-1,0
  4101.0    0.05       0  4564.0   0.033       0  4570.0    0.05       0
Bank Sta=4564,4570
Exp/Cntr=0.3,0.1

Type RM Length L Ch R = 1,34363,614,614,614
BEGIN DESCRIPTION:
DINNER CREEK 29.0
END DESCRIPTION:
XS GIS Cut Line= 3
      3615735.76     10197645.30      3613572.85     10198822.87
      3613275.98     10199916.61
#Sta/Elev= 30
  2862.4  247.67  2972.2  242.16  3135.6  230.27  3261.0  241.02  3326.5  244.61
  3430.0  246.46  3555.4  246.49  3680.7  242.46  3790.0  241.05  3915.3  236.80
  3997.0  230.19  4078.7  221.01  4107.6  216.11  4138.5  214.11  4198.3  213.61
  4291.4  216.12  4411.1  216.15  4492.8  212.83  4673.9  208.72  4676.7  208.22
  4679.9  208.72  5228.8  209.77  5738.3  209.08  5879.8  215.95  5945.5  217.58
  6033.9  224.60  6151.5  226.86  6318.6  230.66  6442.5  228.89  6458.4  228.93
#Mann=5,-1,0
  2862.4    0.05       0  4673.9   0.033       0  4679.9    0.05       0
  6151.5    0.16       0  6442.5     0.1       0
Bank Sta=4673.9,4679.9
Exp/Cntr=0.3,0.1

Type RM Length L Ch R = 1,33749,633,633,633
BEGIN DESCRIPTION:
DINNER CREEK 28.0
END DESCRIPTION:
XS GIS Cut Line= 3
      3614721.88     10196457.80      3613317.64     10198385.37
      3612520.81     10199546.77
#Sta/Elev= 30
  2804.0  235.54  2865.7  234.61  2958.9  233.35  2983.9  233.00  3150.4  229.09
  3236.1  228.27  3271.7  226.06  3286.4  226.71  3415.0  221.83  3709.0  217.97
  3773.8  214.27  3809.4  214.34  4008.9  208.90  5447.0  208.75  5449.7  208.25
  5453.0  208.75  5494.3  209.18  5614.4  213.76  5722.0  223.94  5808.7  227.11
  5866.1  225.92  5895.3  226.09  6002.9  231.99  6218.1  237.30  6283.5  236.07
  6376.5  238.44  6391.4  236.88  6427.2  237.88  6478.0  236.94  6597.3  240.72
#Mann=9,-1,0
  2804.0    0.16       0  2865.7    0.05       0  2958.9    0.16       0
  2983.9    0.05       0  5447.0   0.033       0  5453.0    0.05       0
  5494.3     0.1       0  5866.1    0.05       0  6283.5     0.1       0
Bank Sta=5447,5453
Exp/Cntr=0.3,0.1

Type RM Length L Ch R = 1,33116,564,564,564
BEGIN DESCRIPTION:
DINNER CREEK 26.0
END DESCRIPTION:
XS GIS Cut Line= 3
      3613552.04     10197114.51      3612802.02     10198005.16
      3612421.81     10198723.91
#Sta/Elev= 30
  3971.8  243.60  4083.7  241.38  4104.5  242.69  4118.8  240.83  4142.5  241.69
  4147.4  240.77  4153.9  242.01  4161.7  240.06  4168.2  241.43  4176.0  239.11
  4182.5  240.45  4190.3  237.91  4196.8  238.91  4211.1  233.56  4217.7  233.76
  4254.0  225.79  4274.9  223.11  4289.2  218.76  4338.6  217.71  4373.7  213.66
  4438.7  209.13  4939.0  209.10  4941.8  208.60  4945.0  209.10  5357.3  209.74
  5378.7  212.40  5422.7  222.21  5444.7  223.53  5745.3  227.03  5949.3  232.12
#Mann=6,-1,0
  3971.8    0.16       0  4142.5    0.05       0  4939.0   0.033       0
  4945.0    0.05       0  5357.3     0.1       0  5745.3    0.05       0
Bank Sta=4939,4945
Exp/Cntr=0.3,0.1

Type RM Length L Ch R = 1,32552,83,83,83
BEGIN DESCRIPTION:
DINNER CREEK 25.1
END DESCRIPTION:
XS GIS Cut Line= 4
      3613192.08     10197041.65      3612656.18     10197260.37
      3612380.14     10197645.79      3612135.88     10198508.49
#Sta/Elev= 30
  4012.9  235.49  4021.5  234.82  4081.1  228.43  4120.9  221.38  4142.5  221.65
  4187.2  216.83  4243.1  210.89  4294.9  209.07  4654.1  209.16  4771.7  209.34
  4818.8  209.07  4998.2  208.85  5116.1  210.15  5296.2  209.01  5362.9  213.62
  5383.7  217.10  5419.2  215.42  5487.6  209.28  5501.8  209.05  5517.7  207.84
  5520.4  207.34  5523.7  207.84  5554.6  208.66  5588.6  218.05  5601.9  219.96
  5637.3  219.45  5700.8  220.53  5813.0  219.63  5941.7  223.86  5962.4  225.65
#Mann=14,-1,0
  4012.9    0.16       0  4021.5    0.05       0  4187.2    0.16       0
  4243.1    0.05       0  4654.1    0.12       0  4771.7    0.05       0
  4818.8    0.12       0  4998.2    0.05       0  5419.2     0.1       0
  5501.8    0.05       0  5517.7    0.03       0  5523.7    0.05       0
  5637.3     0.1       0  5941.7    0.05       0
Bank Sta=5517.7,5523.7
Exp/Cntr=0.3,0.1

Type RM Length L Ch R = 1,32469,117,117,117
BEGIN DESCRIPTION:
DINNER CREEK 25.0
END DESCRIPTION:
XS GIS Cut Line= 4
      3613160.85     10196942.69      3612624.93     10197161.41
      3612348.89     10197546.83      3612104.09     10198411.44
#Sta/Elev= 30
  3945.4  231.84  3966.4  230.16  4174.4  211.80  4297.8  209.95  4375.0  213.86
  4380.4  210.24  4404.4  216.89  4451.7  218.99  4487.3  218.21  4514.5  211.72
  4555.1  208.90  4569.8  214.23  4586.0  212.77  4641.0  210.74  4655.8  215.71
  4676.7  211.93  4687.5  215.56  4703.6  215.82  4821.2  216.75  4866.9  217.65
  5149.2  214.15  5351.2  217.67  5452.2  214.09  5472.0  210.74  5554.4  207.16
  5557.2  206.66  5560.4  207.16  5616.5  217.50  5663.0  216.02  5896.9  218.65
#Mann=17,-1,0
  3945.4    0.16       0  3966.4    0.05       0  4174.4    0.16       0
  4297.8    0.05       0  4514.5    0.16       0  4586.0    0.05       0
  4687.5    0.16       0  4703.6    0.05       0  4821.2    0.12       0
  4866.9    0.05       0  5149.2     0.1       0  5351.2    0.05       0
  5452.2     0.1       0  5472.0    0.05       0  5554.4    0.03       0
  5560.4    0.05       0  5663.0     0.1       0
Bank Sta=5554.4,5560.4
Exp/Cntr=0.3,0.1

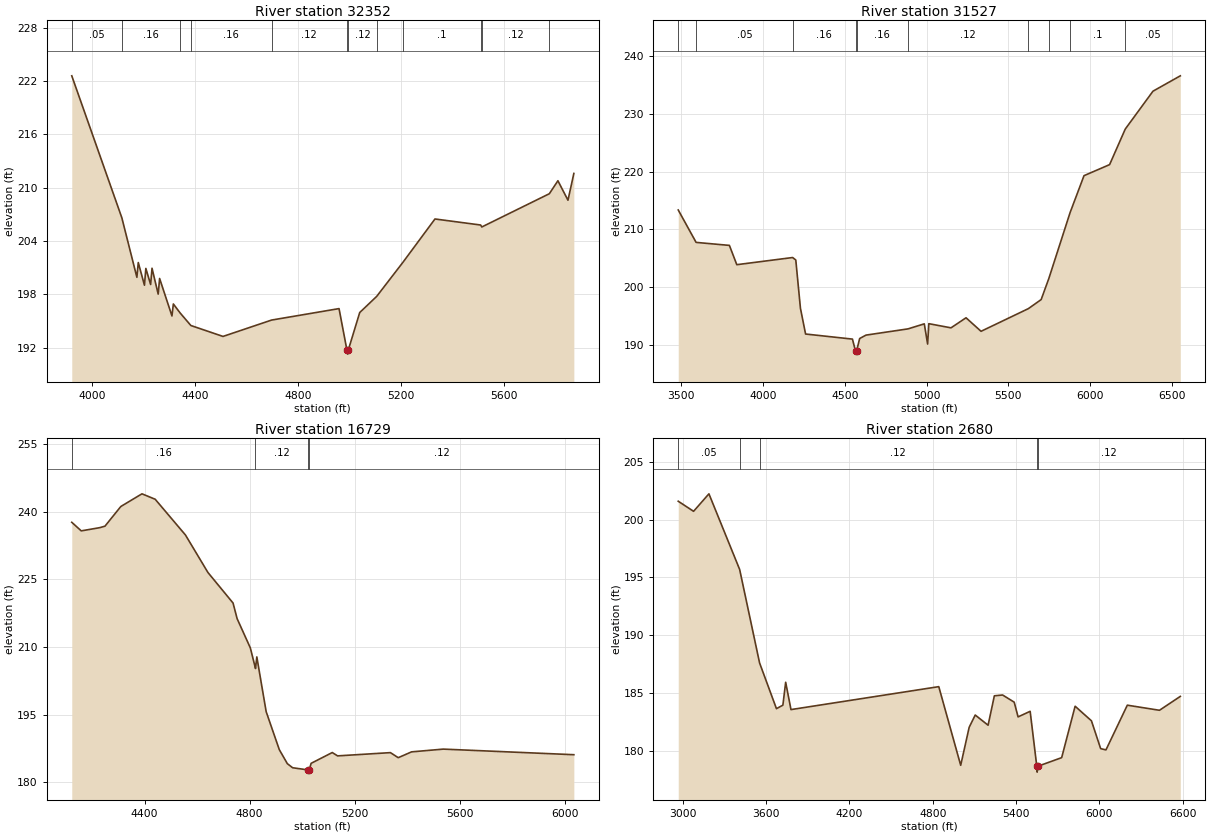
Type RM Length L Ch R = 1,32352,825,825,825
BEGIN DESCRIPTION:
DINNER CREEK 25.2
END DESCRIPTION:
XS GIS Cut Line= 4
      3613067.11     10196859.35      3612531.18     10197078.08
      3612255.14     10197463.50      3612010.56     10198327.32
#Sta/Elev= 30
  3922.2  222.58  4116.7  206.62  4175.2  199.92  4180.6  201.58  4204.6  199.03
  4210.0  200.92  4228.6  199.11  4234.0  200.94  4258.0  198.03  4263.5  199.79
  4311.5  195.57  4316.9  196.92  4343.5  195.90  4384.9  194.50  4509.8  193.27
  4698.5  195.11  4960.6  196.40  4991.0  191.78  4993.7  191.28  4997.0  191.78
  5041.0  195.96  5106.8  197.77  5207.9  201.57  5333.4  206.48  5510.9  205.80
  5515.3  205.58  5777.7  209.32  5811.0  210.78  5850.1  208.59  5872.9  211.60
#Mann=12,-1,0
  3922.2    0.05       0  4116.7    0.16       0  4343.5    0.05       0
  4384.9    0.16       0  4698.5    0.12       0  4991.0    0.07       0
  4997.0    0.12       0  5106.8    0.05       0  5207.9     0.1       0
  5510.9    0.05       0  5515.3    0.12       0  5777.7     0.1       0
Bank Sta=4991,4997
Exp/Cntr=0.3,0.1

Type RM Length L Ch R = 1,31527,14798,14798,14798
BEGIN DESCRIPTION:
DINNER CREEK 22.0
END DESCRIPTION:
XS GIS Cut Line= 4
      3613135.34     10196588.49      3612531.18     10196427.04
      3611822.85     10196755.16      3611489.52     10198385.33
#Sta/Elev= 30
  3481.1  213.35  3590.4  207.74  3794.0  207.22  3839.2  203.88  4180.6  205.12
  4199.9  204.69  4228.3  196.34  4259.7  191.88  4546.3  191.00  4565.3  188.90
  4568.1  188.40  4571.3  188.90  4590.4  191.10  4628.9  191.69  4886.1  192.77
  4985.6  193.64  5006.0  190.14  5013.4  193.67  5148.9  192.95  5240.8  194.69
  5332.6  192.35  5621.7  196.27  5700.1  197.84  5747.1  201.49  5877.0  212.89
  5962.2  219.29  6118.7  221.20  6214.5  227.36  6383.9  233.91  6551.0  236.57
#Mann=10,-1,0
  3481.1    0.16       0  3590.4    0.05       0  4180.6    0.16       0
  4565.3    0.07       0  4571.3    0.16       0  4886.1    0.12       0
  5621.7    0.16       0  5747.1    0.05       0  5877.0     0.1       0
  6214.5    0.05       0
Bank Sta=4565.3,4571.3
Exp/Cntr=0.3,0.1

Type RM Length L Ch R = 1,16729,14049,14049,14049
BEGIN DESCRIPTION:
DINNER CREEK 13.0
END DESCRIPTION:
XS GIS Cut Line= 3
      3614008.24     10190263.34      3613908.25     10190263.34
      3612108.21     10190063.34
#Sta/Elev= 30
  4122.8  237.61  4158.9  235.71  4229.0  236.42  4249.1  236.75  4309.5  241.11
  4390.0  243.92  4440.3  242.72  4555.5  234.80  4641.1  226.49  4736.7  219.72
  4752.2  216.26  4802.5  209.78  4820.9  205.52  4822.2  205.21  4827.2  207.78
  4862.8  195.64  4912.7  187.24  4943.3  184.13  4963.5  183.22  5020.8  182.75
  5023.6  182.25  5026.8  182.75  5033.9  184.20  5114.4  186.59  5134.5  185.85
  5335.7  186.57  5365.5  185.45  5416.2  186.74  5537.0  187.35  6033.9  186.11
#Mann=4,-1,0
  4122.8    0.16       0  4820.9    0.12       0  5020.8    0.07       0
  5026.8    0.12       0
Bank Sta=5020.8,5026.8
Exp/Cntr=0.3,0.1

Type RM Length L Ch R = 1,2680,0,0,0
BEGIN DESCRIPTION:
DINNER CREEK 1.0
END DESCRIPTION:
XS GIS Cut Line= 3
      3615162.03     10183441.51      3613751.47     10183311.30
      3611646.78     10183940.54
#Sta/Elev= 30
  2968.5  201.58  3078.9  200.71  3189.4  202.22  3410.5  195.69  3553.9  187.62
  3675.3  183.67  3721.6  183.97  3741.7  185.95  3779.9  183.59  4843.6  185.57
  5001.3  178.78  5062.3  182.06  5105.9  183.12  5198.5  182.24  5243.5  184.78
  5302.9  184.85  5386.4  184.23  5414.3  182.96  5501.2  183.44  5549.0  178.69
  5551.7  178.19  5555.0  178.69  5728.0  179.44  5824.8  183.88  5942.3  182.62
  6008.5  180.22  6046.8  180.11  6200.5  183.97  6431.9  183.53  6581.8  184.73
#Mann=5,-1,0
  2968.5    0.05       0  3410.5    0.16       0  3553.9    0.12       0
  5549.0    0.07       0  5555.0    0.12       0
Bank Sta=5549,5555
Exp/Cntr=0.3,0.1

Chan Stop Cuts=-1