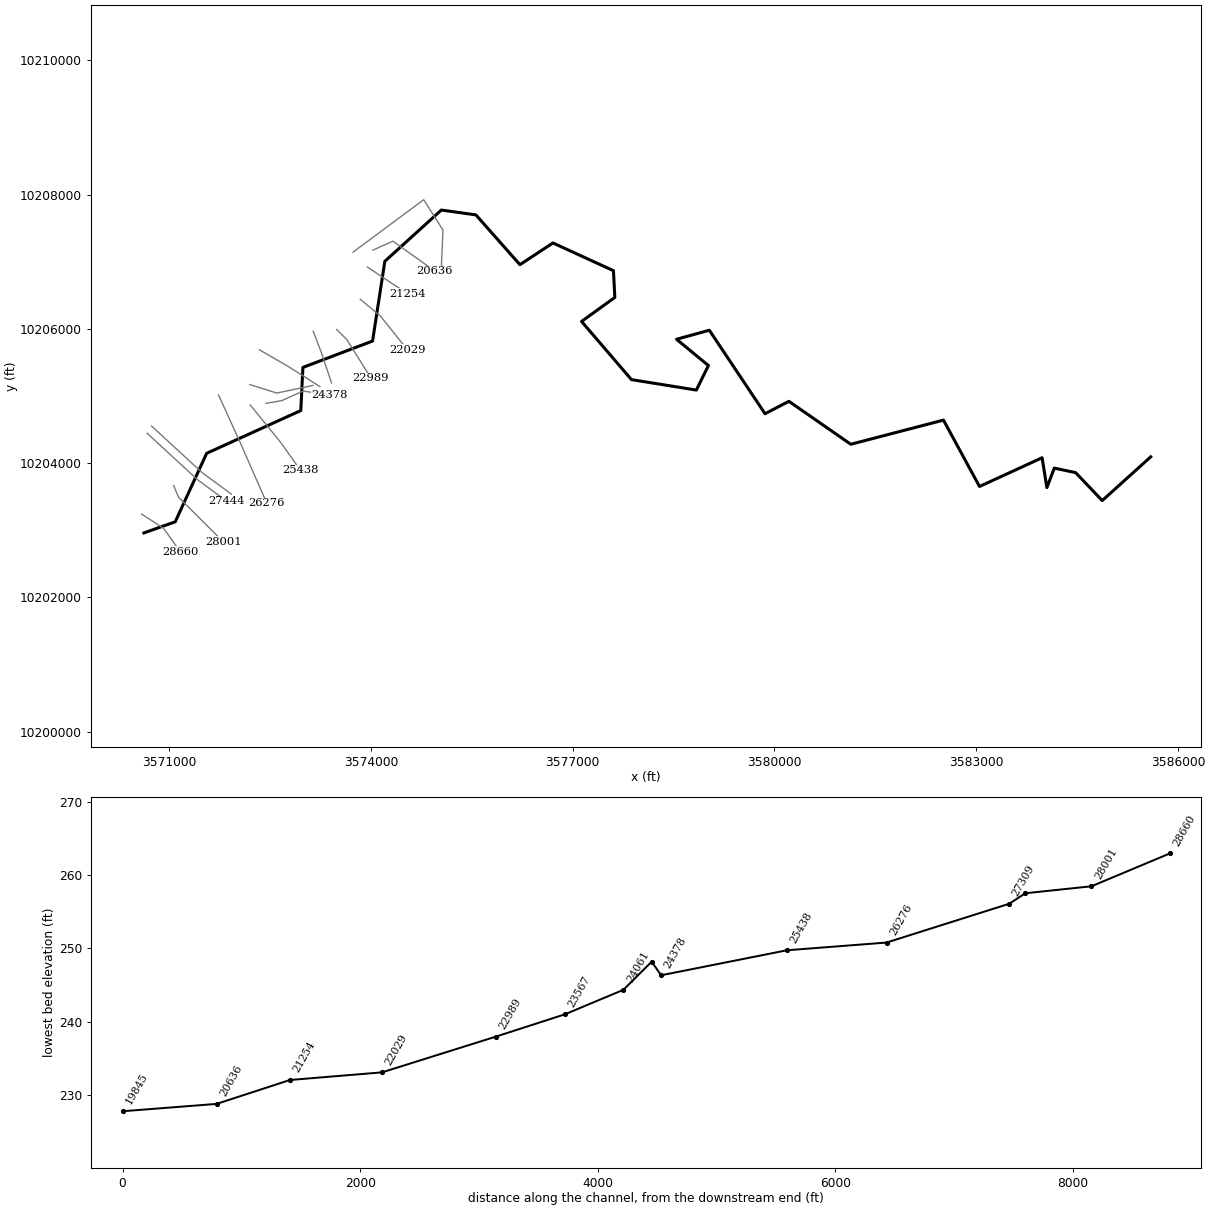
--- FOXFIRE CREEK.prj (project) ---

Proj Title=FOXFIRE CREEK Base Level Engineering
Current Plan=p01
Default Exp/Contr=0.3,0.1
English Units
Geom File=g01
Flow File=f01
Plan File=p01
BEGIN DESCRIPTION:
FOXFIRE CREEK
END DESCRIPTION:

--- FOXFIRE CREEK.p01 (plan) ---

Plan Title=Multiple Run
Short Identifier=Multiple
Geom File=g01
Flow File=f01
Subcritical Flow
K Sum by GR= 0
Std Step Tol= 0.01
Critical Tol= 0.01
Num of Std Step Trials= 20
Max Error Tol= 0.3
Flow Tol Ratio= 0.001
Split Flow NTrial= 30
Split Flow Tol= 0.02
Split Flow Ratio= 0.02
Log Output Level= 0
Friction Slope Method= 1
Unsteady Friction Slope Method= 2
Unsteady Bridges Friction Slope Method= 1
Parabolic Critical Depth
Global Vel Dist=  1 , 1 , 1
Global Log Level= 0
CheckData=True
Encroach Param= -1, 0, 0, 0
BEGIN DESCRIPTION:
Multiple Run
END DESCRIPTION:

--- FOXFIRE CREEK.f01 (steady flow) ---

Flow Title=Multiple
Number of Profiles=7
Profile Names=10-year,25-year,50-year,1pct_min,100-year,1pct_plu,500-year
River Rch & RM= FOXFIRE CREEK,Reach-1,28660
     553     742     896     793    1072    1449    1537
Boundary for River Rch & Prof#=FOXFIRE CREEK,Reach-1,1
Up Type=0
Dn Type=3
Dn Slope=0.005
Boundary for River Rch & Prof#=FOXFIRE CREEK,Reach-1,2
Up Type=0
Dn Type=3
Dn Slope=0.005
Boundary for River Rch & Prof#=FOXFIRE CREEK,Reach-1,3
Up Type=0
Dn Type=3
Dn Slope=0.005
Boundary for River Rch & Prof#=FOXFIRE CREEK,Reach-1,4
Up Type=0
Dn Type=3
Dn Slope=0.005
Boundary for River Rch & Prof#=FOXFIRE CREEK,Reach-1,5
Up Type=0
Dn Type=3
Dn Slope=0.005
Boundary for River Rch & Prof#=FOXFIRE CREEK,Reach-1,6
Up Type=0
Dn Type=3
Dn Slope=0.005
Boundary for River Rch & Prof#=FOXFIRE CREEK,Reach-1,7
Up Type=0
Dn Type=3
Dn Slope=0.005

--- FOXFIRE CREEK.g01 (geometry) ---

Geom Title=Existing Conditions

River Reach=FOXFIRE CREEK,Reach-1
Reach XY= 30
      3570625.90     10202960.82      3571091.50     10203126.01
      3571558.88     10204146.88      3572958.30     10204784.07
      3572989.61     10205426.61      3574025.23     10205819.87
      3574207.70     10207008.10      3575047.61     10207771.54
      3575561.11     10207699.29      3576215.75     10206957.57
      3576706.80     10207281.23      3577606.13     10206867.76
      3577626.57     10206469.25      3577132.11     10206111.64
      3577873.54     10205244.90      3578838.41     10205089.30
      3579017.98     10205454.72      3578543.93     10205846.08
      3579031.61     10205980.74      3579859.40     10204736.86
      3580214.48     10204921.67      3581134.44     10204281.60
      3582512.11     10204641.64      3583047.90     10203652.66
      3583978.37     10204081.04      3584049.28     10203635.81
      3584159.58     10203926.53      3584477.14     10203858.96
      3584872.27     10203442.52      3585593.21     10204094.32

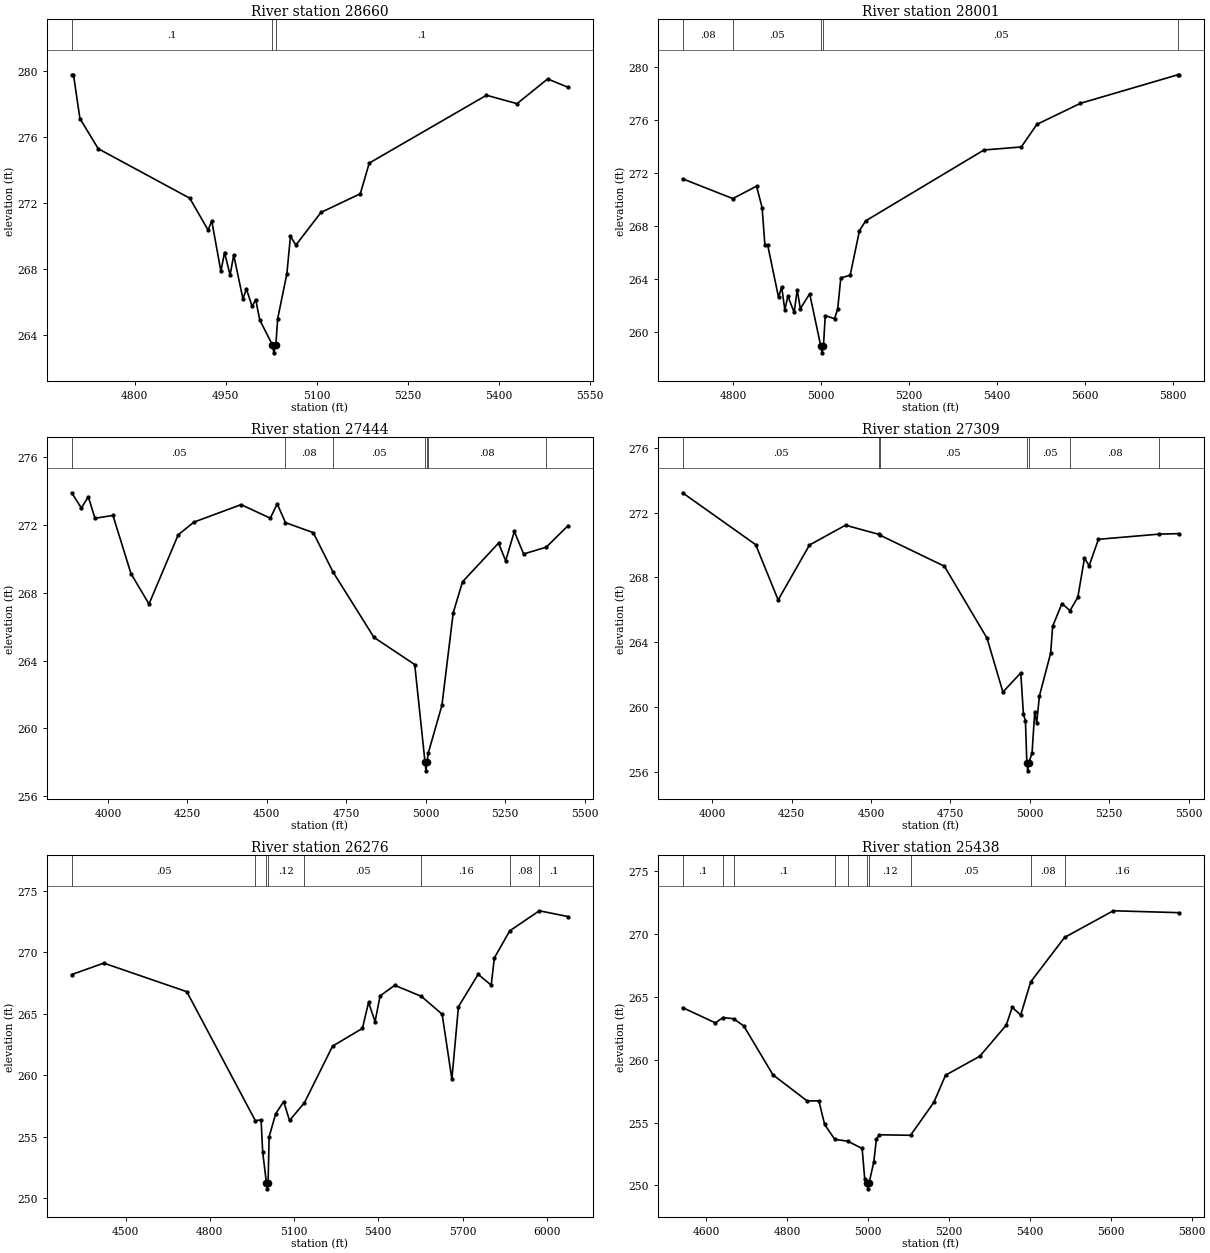
Type RM Length L Ch R = 1,28660,659,659,659
BEGIN DESCRIPTION:
FOXFIRE CREEK 27.0
END DESCRIPTION:
XS GIS Cut Line= 3
      3570592.07     10203241.66      3570918.58     10203029.40
      3571166.29     10202678.94
#Sta/Elev= 30
  4695.8  279.77  4698.8  279.77  4709.4  277.12  4739.6  275.29  4890.6  272.29
  4920.8  270.36  4926.8  270.92  4941.9  267.86  4947.9  269.00  4957.1  267.63
  4963.0  268.85  4978.2  266.20  4984.1  266.79  4993.3  265.73  4999.3  266.15
  5006.0  264.91  5026.6  263.42  5029.3  262.92  5032.6  263.42  5035.5  264.98
  5050.7  267.71  5056.6  269.98  5065.6  269.45  5107.0  271.43  5171.8  272.56
  5186.6  274.42  5379.9  278.53  5430.3  278.02  5480.8  279.52  5514.4  279.01
#Mann=3,-1,0
  4695.8     0.1       0  5026.6    0.07       0  5032.6     0.1       0
Bank Sta=5026.6,5032.6
Exp/Cntr=0.3,0.1

Type RM Length L Ch R = 1,28001,557,557,557
BEGIN DESCRIPTION:
FOXFIRE CREEK 26.0
END DESCRIPTION:
XS GIS Cut Line= 3
      3571067.88     10203666.37      3571142.11     10203491.64
      3571805.18     10202828.24
#Sta/Elev= 30
  4684.9  271.57  4799.0  270.08  4853.0  271.01  4865.6  269.40  4872.0  266.57
  4878.3  266.57  4903.0  262.63  4910.1  263.43  4917.2  261.69  4924.2  262.73
  4938.4  261.50  4945.4  263.19  4952.5  261.78  4973.7  262.90  4999.0  258.95
  5001.8  258.45  5005.0  258.95  5009.1  261.26  5030.3  261.02  5037.4  261.76
  5044.4  264.10  5065.7  264.30  5086.9  267.67  5101.0  268.40  5369.7  273.74
  5454.6  273.97  5489.9  275.67  5588.9  277.26  5810.3  279.41  5812.7  279.41
#Mann=5,-1,0
  4684.9    0.08       0  4799.0    0.05       0  4999.0    0.04       0
  5005.0    0.05       0  5810.3     0.1       0
Bank Sta=4999,5005
Exp/Cntr=0.3,0.1

Type RM Length L Ch R = 1,27444,135,135,135
BEGIN DESCRIPTION:
FOXFIRE CREEK 24.1
END DESCRIPTION:
XS GIS Cut Line= 3
      3570673.29     10204446.24      3571428.91     10203748.59
      3571858.32     10203432.90
#Sta/Elev= 30
  3886.0  273.90  3916.6  273.00  3938.2  273.67  3959.2  272.40  4015.9  272.56
  4072.6  269.13  4129.3  267.34  4221.1  271.42  4270.5  272.17  4419.0  273.20
  4510.9  272.40  4532.5  273.25  4558.5  272.14  4645.9  271.55  4708.1  269.23
  4837.0  265.37  4965.1  263.77  4997.6  258.00  5000.4  257.50  5003.6  258.00
  5008.2  258.58  5050.7  261.36  5086.2  266.82  5115.5  268.65  5228.7  270.93
  5251.3  269.89  5278.4  271.62  5307.7  270.29  5378.7  270.69  5447.4  271.96
#Mann=7,-1,0
  3886.0    0.05       0  4558.5    0.08       0  4708.1    0.05       0
  4997.6    0.04       0  5003.6    0.05       0  5008.2    0.08       0
  5378.7    0.05       0
Bank Sta=4997.6,5003.6
Exp/Cntr=0.3,0.1

Type RM Length L Ch R = 1,27309,1033,1033,1033
BEGIN DESCRIPTION:
FOXFIRE CREEK 24.0
END DESCRIPTION:
XS GIS Cut Line= 3
      3570739.23     10204553.91      3571494.88     10203856.23
      3571925.55     10203539.62
#Sta/Elev= 30
  3906.4  273.22  4136.6  270.02  4207.4  266.61  4306.1  270.00  4419.5  271.22
  4525.6  270.65  4527.7  270.61  4730.8  268.69  4865.2  264.25  4915.1  260.93
  4971.4  262.11  4979.8  259.55  4986.1  259.16  4990.5  256.57  4993.2  256.07
  4996.5  256.57  5006.9  257.16  5015.3  259.70  5021.6  259.02  5030.0  260.68
  5065.5  263.33  5071.7  264.98  5101.0  266.39  5126.5  265.95  5151.1  266.78
  5172.0  269.19  5186.6  268.72  5215.9  270.35  5406.8  270.67  5469.4  270.70
#Mann=7,-1,0
  3906.4    0.05       0  4525.6    0.08       0  4527.7    0.05       0
  4990.5    0.04       0  4996.5    0.05       0  5126.5    0.08       0
  5406.8    0.05       0
Bank Sta=4990.5,4996.5
Exp/Cntr=0.3,0.1

Type RM Length L Ch R = 1,26276,838,838,838
BEGIN DESCRIPTION:
FOXFIRE CREEK 22.0
END DESCRIPTION:
XS GIS Cut Line= 3
      3571735.77     10205015.69      3572056.49     10204309.43
      3572454.53     10203401.09
#Sta/Elev= 30
  4308.3  268.18  4422.6  269.11  4718.2  266.79  4962.4  256.31  4982.7  256.39
  4988.5  253.74  5001.7  251.28  5004.4  250.78  5007.7  251.28  5011.5  255.02
  5034.6  256.87  5063.2  257.87  5084.0  256.33  5137.0  257.77  5237.4  262.37
  5343.6  263.81  5365.4  265.92  5388.6  264.36  5406.5  266.45  5458.7  267.31
  5553.5  266.41  5627.5  264.96  5662.1  259.69  5685.5  265.57  5755.6  268.20
  5802.1  267.32  5813.3  269.53  5868.1  271.73  5973.5  273.36  6075.7  272.89
#Mann=8,-1,0
  4308.3    0.05       0  4962.4    0.12       0  5001.7    0.07       0
  5007.7    0.12       0  5137.0    0.05       0  5553.5    0.16       0
  5868.1    0.08       0  5973.5     0.1       0
Bank Sta=5001.7,5007.7
Exp/Cntr=0.3,0.1

Type RM Length L Ch R = 1,25438,1060,1060,1060
BEGIN DESCRIPTION:
FOXFIRE CREEK 21.0
END DESCRIPTION:
XS GIS Cut Line= 3
      3572205.06     10204868.60      3572662.24     10204306.23
      3572952.07     10203896.05
#Sta/Elev= 30
  4541.6  264.15  4622.8  262.93  4641.6  263.36  4667.9  263.26  4693.1  262.68
  4765.0  258.80  4849.7  256.72  4878.5  256.73  4892.8  254.85  4917.7  253.67
  4949.8  253.52  4985.5  252.94  4992.0  250.48  4996.9  250.23  4999.6  249.73
  5002.9  250.23  5014.3  251.87  5020.7  253.67  5027.4  254.03  5105.2  253.99
  5162.9  256.62  5191.7  258.77  5276.4  260.28  5341.7  262.75  5356.5  264.18
  5377.4  263.55  5402.1  266.19  5485.9  269.73  5606.4  271.85  5768.6  271.70
#Mann=10,-1,0
  4541.6     0.1       0  4641.6    0.05       0  4667.9     0.1       0
  4917.7    0.16       0  4949.8    0.12       0  4996.9    0.07       0
  5002.9    0.12       0  5105.2    0.05       0  5402.1    0.08       0
  5485.9    0.16       0
Bank Sta=4996.9,5002.9
Exp/Cntr=0.3,0.1

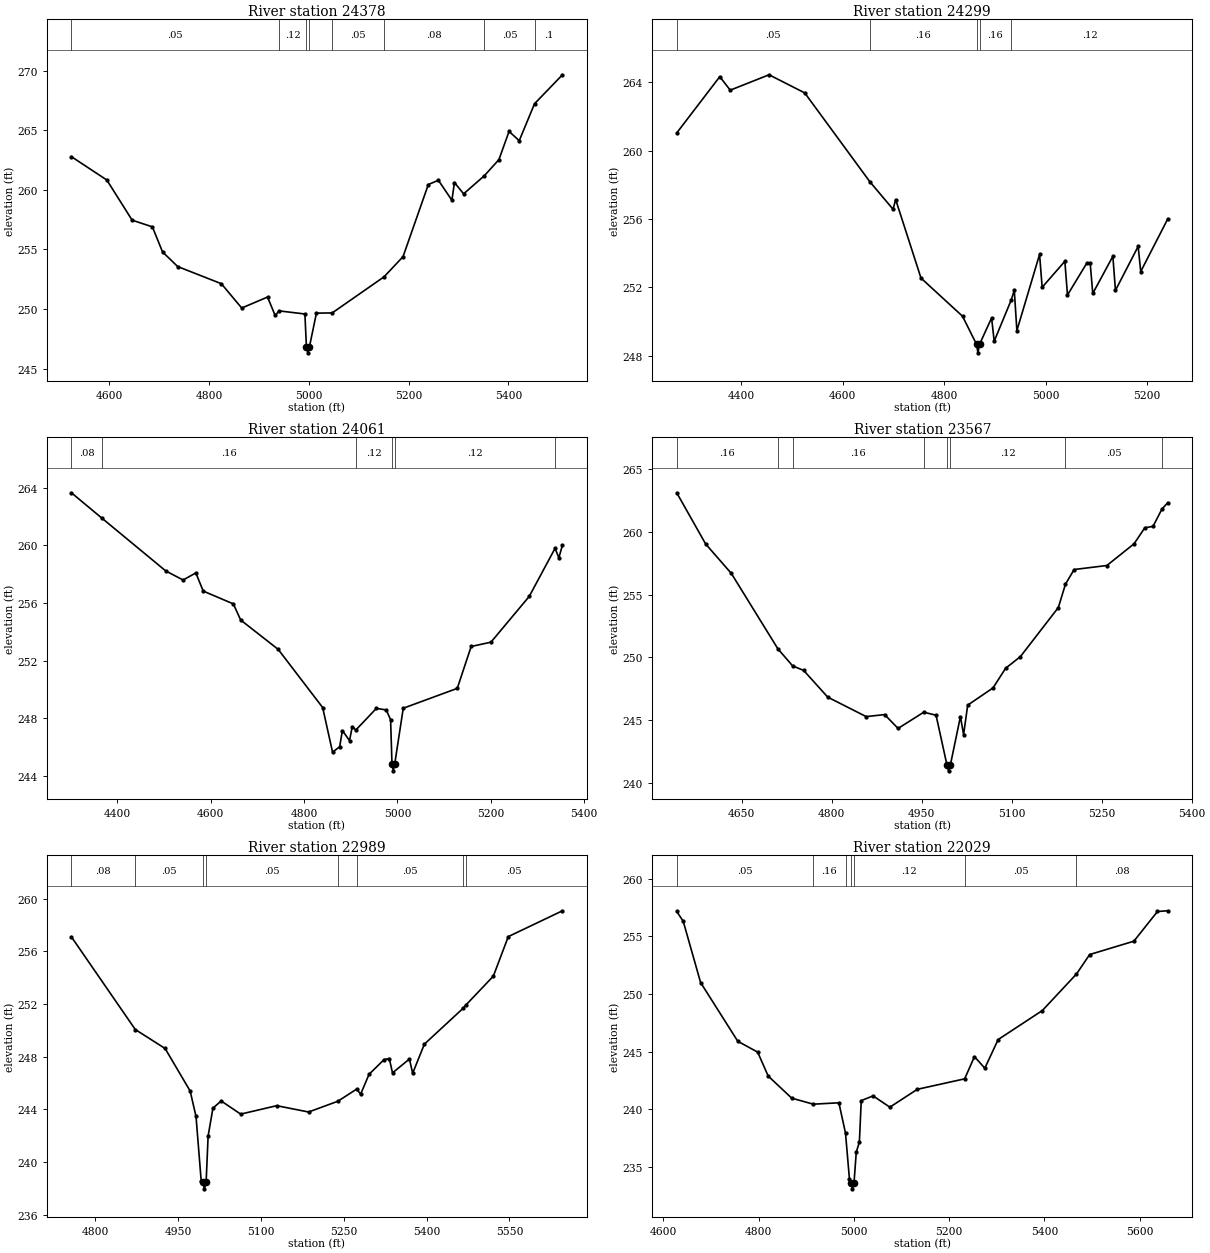
Type RM Length L Ch R = 1,24378,79,79,79
BEGIN DESCRIPTION:
FOXFIRE CREEK 20.0
END DESCRIPTION:
XS GIS Cut Line= 4
      3572442.14     10204891.65      3572676.73     10204932.38
      3572992.70     10205074.74      3573387.85     10205012.35
#Sta/Elev= 30
  4523.8  262.78  4594.8  260.82  4645.6  257.45  4686.2  256.89  4706.5  254.79
  4736.9  253.56  4824.5  252.12  4865.3  250.08  4917.1  251.00  4932.3  249.46
  4940.4  249.84  4992.0  249.58  4995.1  246.82  4997.9  246.32  5001.1  246.82
  5015.1  249.65  5046.8  249.67  5150.8  252.70  5188.8  254.39  5239.5  260.44
  5259.7  260.80  5286.8  259.12  5291.9  260.61  5310.3  259.66  5351.9  261.18
  5381.2  262.54  5401.4  264.90  5421.8  264.12  5452.5  267.22  5508.5  269.65
#Mann=8,-1,0
  4523.8    0.05       0  4940.4    0.12       0  4995.1    0.07       0
  5001.1    0.12       0  5046.8    0.05       0  5150.8    0.08       0
  5351.9    0.05       0  5452.5     0.1       0
Bank Sta=4995.1,5001.1
Exp/Cntr=0.3,0.1

Type RM Length L Ch R = 1,24299,238,238,238
BEGIN DESCRIPTION:
FOXFIRE CREEK 19.0
END DESCRIPTION:
XS GIS Cut Line= 3
      3572201.59     10205170.71      3572600.86     10205044.85
      3573137.85     10205157.93
#Sta/Elev= 30
  4273.3  261.03  4358.1  264.32  4378.7  263.53  4455.2  264.43  4525.5  263.37
  4654.0  258.17  4699.5  256.57  4704.6  257.14  4754.5  252.55  4836.3  250.32
  4863.9  248.68  4866.7  248.18  4869.9  248.68  4893.6  250.22  4898.7  248.86
  4932.3  251.27  4938.3  251.84  4943.4  249.48  4988.1  253.93  4993.2  252.01
  5037.9  253.53  5043.1  251.56  5081.5  253.44  5087.8  253.43  5092.9  251.65
  5132.5  253.82  5137.6  251.83  5182.3  254.40  5187.4  252.93  5240.7  256.01
#Mann=5,-1,0
  4273.3    0.05       0  4654.0    0.16       0  4863.9    0.07       0
  4869.9    0.16       0  4932.3    0.12       0
Bank Sta=4863.9,4869.9
Exp/Cntr=0.3,0.1

Type RM Length L Ch R = 1,24061,494,494,494
BEGIN DESCRIPTION:
FOXFIRE CREEK 18.0
END DESCRIPTION:
XS GIS Cut Line= 3
      3572343.89     10205688.96      3572785.99     10205432.35
      3573242.14     10205141.62
#Sta/Elev= 30
  4301.5  263.66  4367.1  261.89  4503.6  258.23  4540.8  257.60  4568.1  258.09
  4583.9  256.83  4648.4  255.94  4664.2  254.82  4744.5  252.78  4839.8  248.74
  4861.0  245.64  4876.2  246.01  4882.1  247.14  4897.4  246.44  4903.3  247.42
  4910.7  247.17  4954.9  248.68  4976.1  248.57  4985.4  247.89  4988.3  244.84
  4991.1  244.34  4994.3  244.84  5012.5  248.69  5128.2  250.07  5158.0  252.98
  5200.4  253.28  5282.4  256.46  5337.7  259.80  5345.9  259.14  5353.6  260.03
#Mann=6,-1,0
  4301.5    0.08       0  4367.1    0.16       0  4910.7    0.12       0
  4988.3    0.07       0  4994.3    0.12       0  5337.7    0.08       0
Bank Sta=4988.3,4994.3
Exp/Cntr=0.3,0.1

Type RM Length L Ch R = 1,23567,578,578,578
BEGIN DESCRIPTION:
FOXFIRE CREEK 17.0
END DESCRIPTION:
XS GIS Cut Line= 3
      3573142.55     10205966.68      3573263.38     10205650.27
      3573415.57     10205195.35
#Sta/Elev= 30
  4541.7  263.09  4589.9  259.02  4632.7  256.68  4710.4  250.68  4734.9  249.33
  4753.3  248.97  4793.3  246.85  4857.5  245.30  4888.2  245.46  4910.6  244.36
  4953.4  245.65  4973.9  245.41  4991.9  241.49  4994.7  240.99  4997.9  241.49
  5014.5  245.30  5019.8  243.87  5026.6  246.21  5068.8  247.58  5089.8  249.14
  5114.5  250.07  5177.7  253.97  5189.6  255.83  5204.0  256.99  5258.6  257.31
  5304.0  259.04  5321.8  260.31  5335.5  260.42  5350.4  261.80  5360.1  262.30
#Mann=8,-1,0
  4541.7    0.16       0  4710.4    0.08       0  4734.9    0.16       0
  4953.4    0.12       0  4991.9    0.07       0  4997.9    0.12       0
  5189.6    0.05       0  5350.4     0.1       0
Bank Sta=4991.9,4997.9
Exp/Cntr=0.3,0.1

Type RM Length L Ch R = 1,22989,960,960,960
BEGIN DESCRIPTION:
FOXFIRE CREEK 16.0
END DESCRIPTION:
XS GIS Cut Line= 3
      3573492.09     10205991.66      3573642.11     10205841.64
      3574001.93     10205267.90
#Sta/Elev= 30
  4756.6  257.09  4872.3  250.06  4926.3  248.62  4971.7  245.39  4982.3  243.46
  4991.7  238.55  4994.6  238.47  4997.4  237.97  5000.6  238.47  5004.2  241.97
  5012.9  244.09  5027.8  244.64  5063.2  243.64  5128.4  244.28  5186.2  243.80
  5239.4  244.62  5273.3  245.54  5280.4  245.15  5295.7  246.66  5322.9  247.78
  5332.3  247.86  5338.2  246.77  5368.8  247.82  5374.7  246.74  5395.9  248.95
  5465.8  251.66  5471.6  251.94  5520.8  254.11  5547.9  257.11  5646.0  259.07
#Mann=8,-1,0
  4756.6    0.08       0  4872.3    0.05       0  4994.6    0.04       0
  5000.6    0.05       0  5239.4    0.16       0  5273.3    0.05       0
  5465.8    0.16       0  5471.6    0.05       0
Bank Sta=4994.6,5000.6
Exp/Cntr=0.3,0.1

Type RM Length L Ch R = 1,22029,775,775,775
BEGIN DESCRIPTION:
FOXFIRE CREEK 14.0
END DESCRIPTION:
XS GIS Cut Line= 3
      3573842.09     10206441.66      3574142.11     10206191.64
      3574542.08     10205691.68
#Sta/Elev= 30
  4628.3  257.17  4642.0  256.31  4678.4  251.00  4756.5  245.90  4798.2  244.96
  4820.3  242.88  4869.8  240.96  4915.0  240.44  4968.7  240.56  4982.6  237.92
  4990.8  233.96  4994.4  233.59  4997.1  233.09  5000.4  233.59  5005.2  236.29
  5011.7  237.14  5015.6  240.75  5040.4  241.16  5075.7  240.18  5133.3  241.73
  5232.7  242.64  5253.3  244.57  5275.0  243.56  5303.0  246.05  5395.8  248.57
  5467.4  251.74  5495.1  253.43  5587.9  254.59  5637.5  257.17  5659.1  257.23
#Mann=7,-1,0
  4628.3    0.05       0  4915.0    0.16       0  4982.6    0.12       0
  4994.4    0.07       0  5000.4    0.12       0  5232.7    0.05       0
  5467.4    0.08       0
Bank Sta=4994.4,5000.4
Exp/Cntr=0.3,0.1

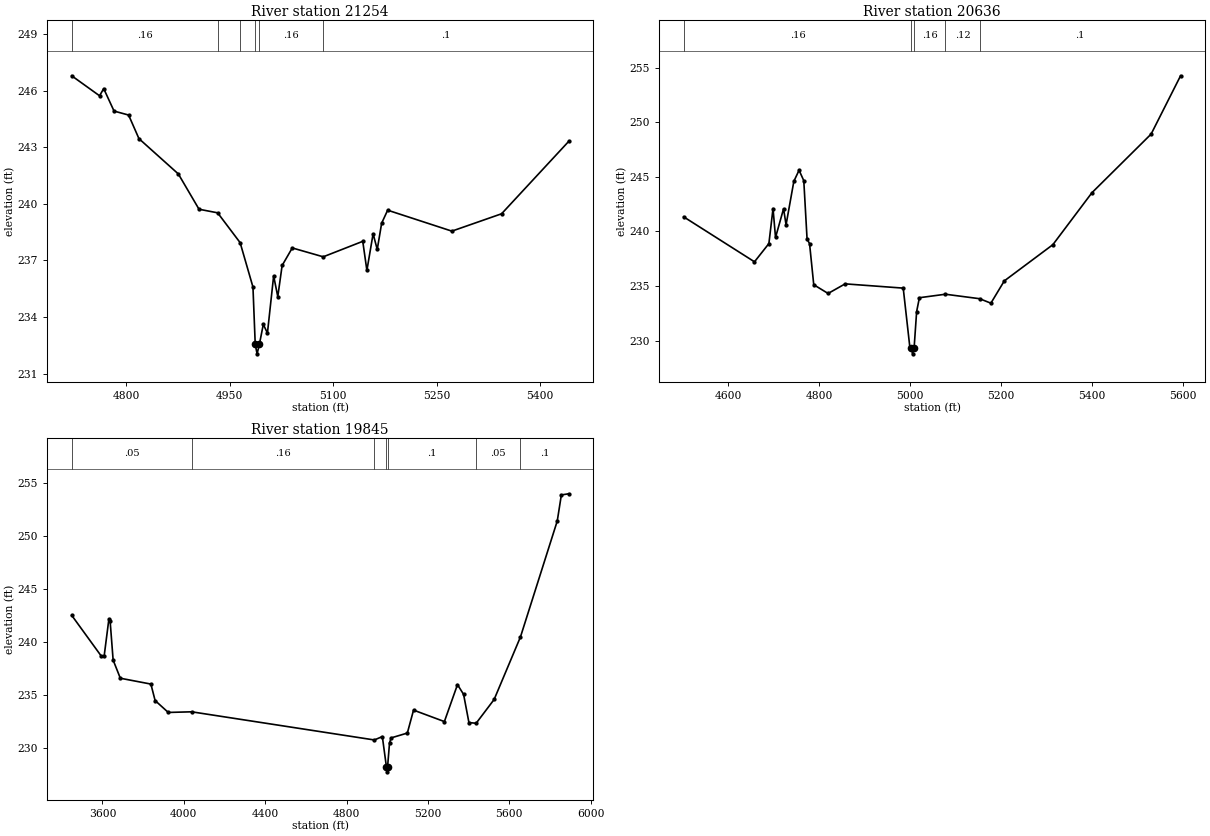
Type RM Length L Ch R = 1,21254,618,618,618
BEGIN DESCRIPTION:
FOXFIRE CREEK 13.0
END DESCRIPTION:
XS GIS Cut Line= 3
      3573948.21     10206922.21      3574248.23     10206722.20
      3574547.70     10206522.55
#Sta/Elev= 30
  4720.9  246.78  4761.3  245.72  4767.3  246.10  4782.3  244.91  4803.4  244.70
  4818.4  243.45  4875.5  241.58  4905.5  239.71  4932.5  239.52  4965.1  237.94
  4983.7  235.59  4987.0  232.55  4989.7  232.05  4993.0  232.55  4998.7  233.61
  5004.7  233.15  5013.7  236.18  5019.7  235.08  5026.0  236.73  5040.7  237.66
  5085.6  237.19  5142.9  238.01  5148.9  236.47  5157.9  238.41  5163.9  237.58
  5170.3  238.97  5179.0  239.66  5272.1  238.55  5344.2  239.47  5441.4  243.30
#Mann=6,-1,0
  4720.9    0.16       0  4932.5     0.1       0  4965.1    0.16       0
  4987.0    0.07       0  4993.0    0.16       0  5085.6     0.1       0
Bank Sta=4987,4993
Exp/Cntr=0.3,0.1

Type RM Length L Ch R = 1,20636,791,791,791
BEGIN DESCRIPTION:
FOXFIRE CREEK 11.0
END DESCRIPTION:
XS GIS Cut Line= 3
      3574031.04     10207174.33      3574327.43     10207307.87
      3574952.42     10206860.82
#Sta/Elev= 30
  4502.1  241.34  4658.0  237.22  4689.7  238.89  4698.8  242.10  4704.3  239.45
  4722.0  242.08  4727.5  240.61  4744.6  244.59  4756.1  245.61  4766.5  244.65
  4773.7  239.31  4779.2  238.88  4788.4  235.12  4820.0  234.32  4857.5  235.20
  4985.3  234.81  5000.0  229.35  5003.2  229.29  5005.9  228.79  5009.2  229.29
  5014.8  232.66  5020.9  233.93  5078.1  234.25  5153.4  233.84  5178.2  233.43
  5207.7  235.47  5314.6  238.79  5400.6  243.55  5530.8  248.92  5595.6  254.26
#Mann=5,-1,0
  4502.1    0.16       0  5003.2    0.07       0  5009.2    0.16       0
  5078.1    0.12       0  5153.4     0.1       0
Bank Sta=5003.2,5009.2
Exp/Cntr=0.3,0.1

Type RM Length L Ch R = 1,19845,0,0,0
BEGIN DESCRIPTION:
FOXFIRE CREEK 1.0
END DESCRIPTION:
XS GIS Cut Line= 4
      3573735.04     10207144.19      3574785.42     10207925.47
      3575071.88     10207474.08      3575045.87     10206875.83
#Sta/Elev= 30
  3449.2  242.52  3595.1  238.67  3608.9  238.71  3631.9  242.16  3638.2  241.95
  3652.8  238.31  3688.2  236.60  3838.4  236.05  3859.2  234.50  3923.9  233.38
  4038.7  233.44  4936.8  230.79  4976.0  231.11  4995.9  228.29  4998.6  227.79
  5001.9  228.29  5011.5  230.54  5020.1  230.99  5098.9  231.44  5129.4  233.60
  5281.0  232.52  5345.4  236.00  5375.4  235.08  5401.6  232.43  5437.0  232.36
  5525.5  234.60  5655.0  240.49  5835.8  251.40  5855.9  253.85  5891.7  253.96
#Mann=7,-1,0
  3449.2    0.05       0  4038.7    0.16       0  4936.8     0.1       0
  4995.9    0.07       0  5001.9     0.1       0  5437.0    0.05       0
  5655.0     0.1       0
Bank Sta=4995.9,5001.9
Exp/Cntr=0.3,0.1

Chan Stop Cuts=-1