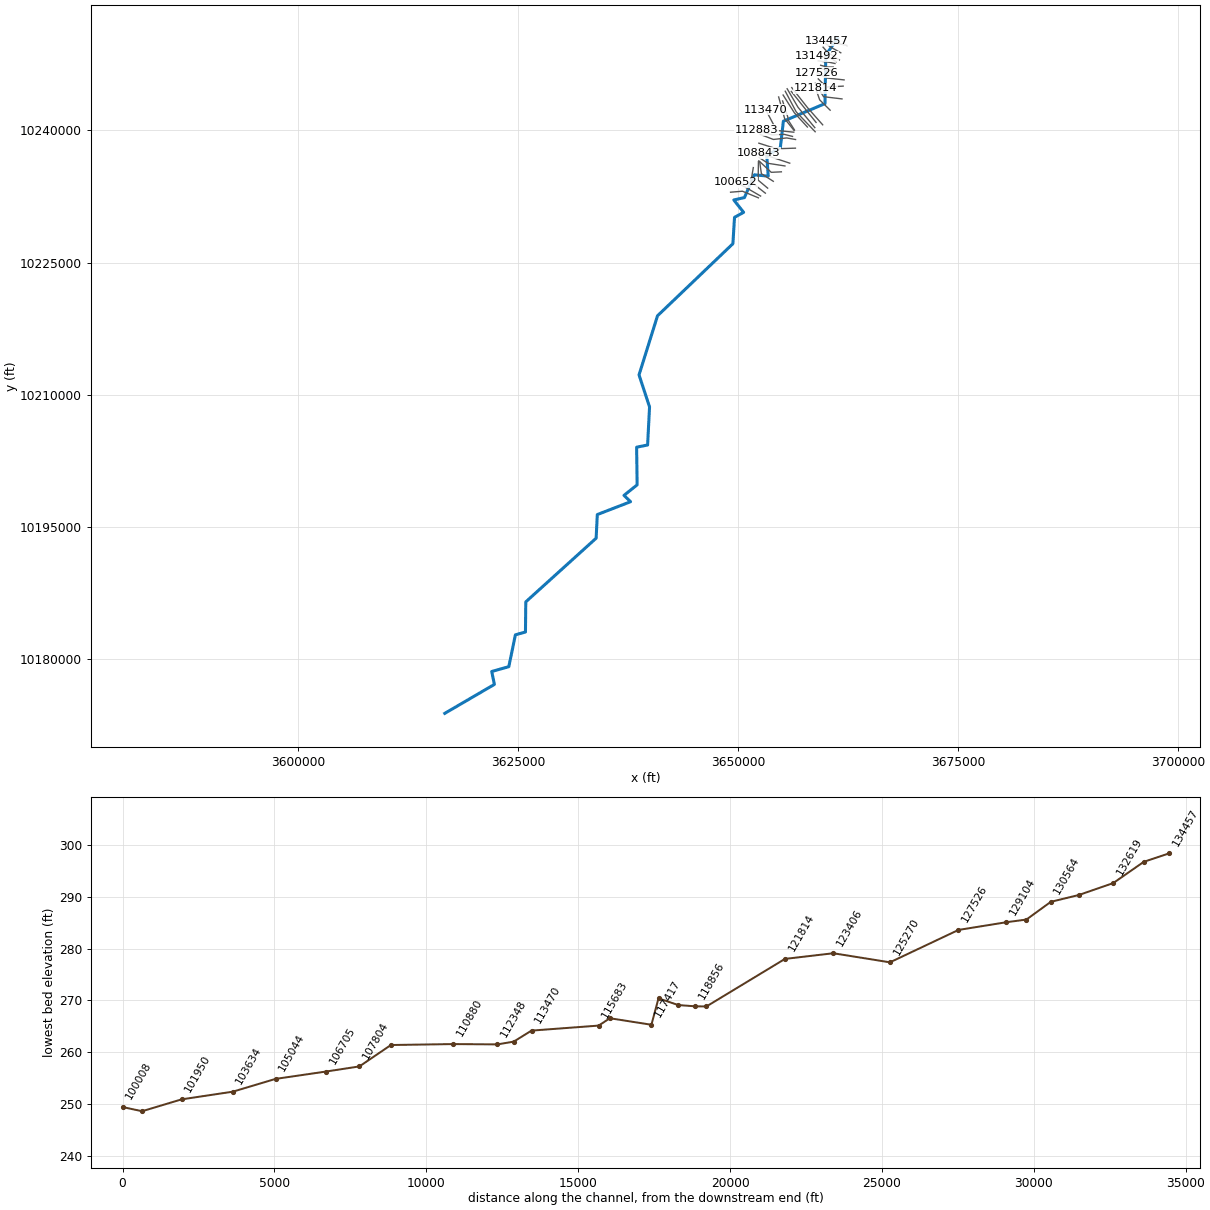
--- GIBBONS CREEK.prj (project) ---

Proj Title=GIBBONS CREEK Base Level Engineering
Current Plan=p01
Default Exp/Contr=0.3,0.1
English Units
Geom File=g01
Flow File=f01
Plan File=p01
Y Axis Title=Elevation
X Axis Title(PF)=Main Channel Distance
X Axis Title(XS)=Station
BEGIN DESCRIPTION:
GIBBONS CREEK
END DESCRIPTION:
DSS Export Rating Curves= 0
DSS Export Rating Curve Sorted= 0
DSS Export Volume Flow Curves= 0
DXF OffsetX= 0
DXF OffsetY= 0
DXF ScaleX= 1
DXF ScaleY= 10

--- GIBBONS CREEK.p01 (plan) ---

Plan Title=Multiple Run
Short Identifier=Multiple
Geom File=g01
Flow File=f01
Subcritical Flow
K Sum by GR= 0
Std Step Tol= 0.01
Critical Tol= 0.01
Num of Std Step Trials= 20
Max Error Tol= 0.3
Flow Tol Ratio= 0.001
Split Flow NTrial= 30
Split Flow Tol= 0.02
Split Flow Ratio= 0.02
Log Output Level= 0
Friction Slope Method= 1
Unsteady Friction Slope Method= 2
Unsteady Bridges Friction Slope Method= 1
Parabolic Critical Depth
Global Vel Dist=  1 , 1 , 1
Global Log Level= 0
CheckData=True
Encroach Param= -1, 0, 0, 0
BEGIN DESCRIPTION:
Multiple Run
END DESCRIPTION:

--- GIBBONS CREEK.f01 (steady flow) ---

Flow Title=Multiple
Program Version=4.10
Number of Profiles= 7
Profile Names=10-year,25-year,50-year,1pct_min,100-year,1pct_plu,500-year
River Rch & RM=GIBBONS CREEK,Reach-1         ,134457
    1068    1458    1780    1587    2147    2903    3125
River Rch & RM=GIBBONS CREEK,Reach-1         ,127526
    1509    2096    2587    2331    3152    4263    4683
River Rch & RM=GIBBONS CREEK,Reach-1         ,125270
    1509    2096    2587    2331    3152    4263    4683
River Rch & RM=GIBBONS CREEK,Reach-1         ,123406
    1647    2291    2830    2550    3449    4664    5127
River Rch & RM=GIBBONS CREEK,Reach-1         ,119228
    3147    4483    5629    5147    6961    9414   10659
River Rch & RM=GIBBONS CREEK,Reach-1         ,118856
    3147    4483    5629    5147    6961    9414   10659
River Rch & RM=GIBBONS CREEK,Reach-1         ,113470
    3225    4589    5757    5260    7114    9620   10874
River Rch & RM=GIBBONS CREEK,Reach-1         ,112883
    3255    4631    5811    5308    7179    9709   10973
River Rch & RM=GIBBONS CREEK,Reach-1         ,110880
    3295    4673    5849    5329    7207    9746   10957
River Rch & RM=GIBBONS CREEK,Reach-1         ,108843
    3295    4673    5849    5329    7207    9746   10957
River Rch & RM=GIBBONS CREEK,Reach-1         ,100652
    4409    6298    7922    7249    9804   13258   15036
River Rch & RM=GIBBONS CREEK,Reach-1         ,90274
    5636    8081   10192    9344   12636   17089   19446
River Rch & RM=GIBBONS CREEK,Reach-1         ,89030
    5636    8081   10192    9344   12636   17089   19446
River Rch & RM=GIBBONS CREEK,Reach-1         ,81249
    6179    8877   11212   10293   13920   18825   21478
River Rch & RM=GIBBONS CREEK,Reach-1         ,76460
    9725   14102   17931   16558   22393   30284   34936
River Rch & RM=GIBBONS CREEK,Reach-1         ,69171
   10496   15336   19602   18200   24614   33288   38823
River Rch & RM=GIBBONS CREEK,Reach-1         ,66881
   10393   15149   19332   17918   24232   32772   38088
River Rch & RM=GIBBONS CREEK,Reach-1         ,60795
   10651   15532   19827   18383   24861   33621   39100
River Rch & RM=GIBBONS CREEK,Reach-1         ,60468
   10519   15314   19526   18082   24454   33071   38366
River Rch & RM=GIBBONS CREEK,Reach-1         ,55964
   10959   15949   20331   18823   25455   34426   39915
River Rch & RM=GIBBONS CREEK,Reach-1         ,53488
   10959   15949   20331   18823   25455   34426   39915
River Rch & RM=GIBBONS CREEK,Reach-1         ,49546
   11029   16042   20444   18920   25587   34604   40092
River Rch & RM=GIBBONS CREEK,Reach-1         ,33715
   11169   16197   20599   19022   25726   34791   40134
River Rch & RM=GIBBONS CREEK,Reach-1         ,32209
   11250   16293   20703   19100   25831   34933   40221
River Rch & RM=GIBBONS CREEK,Reach-1         ,23058
   11250   16293   20703   19100   25831   34933   40221
River Rch & RM=GIBBONS CREEK,Reach-1         ,20529
   11184   16180   20545   18941   25616   34643   39829
River Rch & RM=GIBBONS CREEK,Reach-1         ,12856
   11334   16403   20833   19211   25981   35136   40412
Boundary for River Rch & Prof#=GIBBONS CREEK,Reach-1         , 1
Up Type= 0
Dn Type= 3
Dn Slope=0.005
Boundary for River Rch & Prof#=GIBBONS CREEK,Reach-1         , 2
Up Type= 0
Dn Type= 3
Dn Slope=0.005
Boundary for River Rch & Prof#=GIBBONS CREEK,Reach-1         , 3
Up Type= 0
Dn Type= 3
Dn Slope=0.005
Boundary for River Rch & Prof#=GIBBONS CREEK,Reach-1         , 4
Up Type= 0
Dn Type= 3
Dn Slope=0.005
Boundary for River Rch & Prof#=GIBBONS CREEK,Reach-1         , 5
Up Type= 0
Dn Type= 3
Dn Slope=0.005
Boundary for River Rch & Prof#=GIBBONS CREEK,Reach-1         , 6
Up Type= 0
Dn Type= 3
Dn Slope=0.005
Boundary for River Rch & Prof#=GIBBONS CREEK,Reach-1         , 7
Up Type= 0
Dn Type= 3
Dn Slope=0.005
DSS Import GetInterval= 0
DSS Import GetPeak= 0
DSS Import FillOption= 0

--- GIBBONS CREEK.g01 (geometry) ---

Geom Title=Existing Conditions
Program Version=4.10

River Reach=GIBBONS CREEK   ,Reach-1
Reach XY= 30
      3661271.08     10250446.97      3659948.39     10248535.41
      3659859.17     10243039.13      3655126.88     10241041.86
      3654785.73      10238048.8      3653245.24     10237110.17
      3653404.18     10234804.94      3651829.72     10234956.52
      3650702.68     10232369.53      3649494.04     10232098.91
      3650611.73     10230693.24      3649577.16     10230130.38
      3649392.33     10227132.51      3640826.02     10218952.23
       3638725.4     10212241.08      3639920.98     10208607.56
      3639699.41     10204281.64       3638451.2     10204032.39
      3638509.93     10199758.22      3637015.64     10198567.58
      3637763.24     10197845.19      3633984.39     10196386.01
      3633850.81      10193701.9      3625856.43     10186475.07
      3625819.94     10183058.12       3624676.6     10182734.63
      3623927.81     10179118.34      3621983.84     10178571.23
       3622291.4     10177106.83      3616647.58     10173818.09

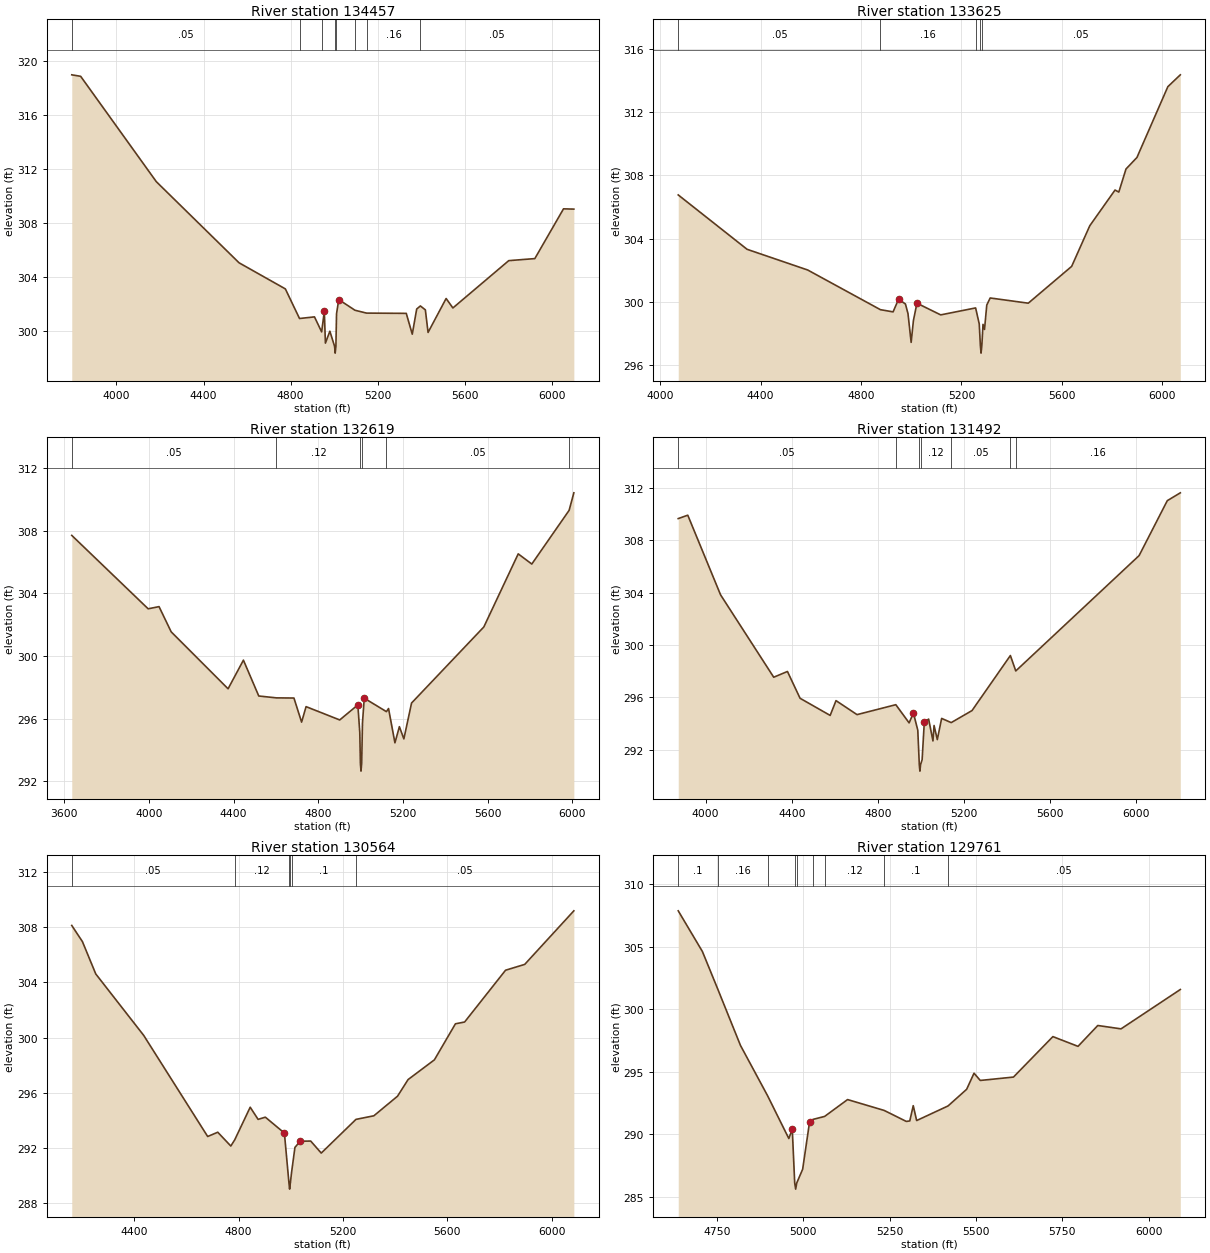
Type RM Length L Ch R = 1 ,134457  ,832,832,832
BEGIN DESCRIPTION:
GIBBONS CREEK 111.0
END DESCRIPTION:
XS GIS Cut Line= 3
      3662342.08     10249641.65      3660838.67      10249952.9
      3660096.34     10250154.09
#Sta/Elev= 30
  3795.3  318.96  3836.1  318.85  4183.3  311.06  4563.1  305.06  4775.6  303.13
  4840.6  300.94  4909.3  301.06  4942.2  299.95  4954.4  301.47  4959.5  299.12
  4979.9     300  5001.6  298.88  5004.3  298.38  5007.6  298.88  5010.5  301.29
  5020.7  302.34  5095.2  301.55  5148.2  301.34  5330.6  301.32  5358.1  299.78
  5378.4  301.64  5395.3  301.87  5418.2  301.58  5430.6  299.91  5513.5  302.42
  5544.6  301.72    5801  305.22  5920.6  305.37  6052.3  309.05  6099.7  309.03
#Mann= 8 ,-1 , 0
  3795.3     .05       0  4840.6      .1       0  4942.2     .16       0
  5001.6     .07       0  5007.6     .16       0  5095.2      .1       0
  5148.2     .16       0  5395.3     .05       0
Bank Sta=4954.4,5020.7
XS Rating Curve= 0 ,0
Exp/Cntr=0.3,0.1

Type RM Length L Ch R = 1 ,133625  ,1006,1006,1006
BEGIN DESCRIPTION:
GIBBONS CREEK 109.0
END DESCRIPTION:
XS GIS Cut Line= 3
      3661651.21     10248807.04       3660663.7     10249360.58
      3659942.12     10249841.63
#Sta/Elev= 30
  4072.2  306.76  4346.3  303.32  4587.7  302.01  4877.2   299.5  4927.8  299.36
  4949.5  300.16  4976.9  299.86  4987.1  299.25  4999.7  297.43  5008.8  298.82
  5022.7  299.91  5117.3  299.17  5256.4  299.61  5270.8   298.6  5275.3  297.25
    5278  296.75  5281.3  297.25  5285.8  298.57  5291.8  298.25  5300.8  299.79
  5314.4  300.24  5466.1  299.91  5638.9  302.24    5711  304.81  5811.6  307.07
  5826.6  306.94  5855.2   308.4  5898.8  309.13  6021.9  313.61  6071.5  314.36
#Mann= 5 ,-1 , 0
  4072.2     .05       0  4877.2     .16       0  5256.4     .05       0
  5275.3     .07       0  5281.3     .05       0
Bank Sta=4949.5,5022.7
XS Rating Curve= 0 ,0
Exp/Cntr=0.3,0.1

Type RM Length L Ch R = 1 ,132619  ,1127,1127,1127
BEGIN DESCRIPTION:
GIBBONS CREEK 107.0
END DESCRIPTION:
XS GIS Cut Line= 3
      3661492.13     10247991.63      3660129.39     10248879.39
      3659642.12     10249441.62
#Sta/Elev= 30
    3636  307.71  3996.7  303.02    4048  303.16  4105.3  301.55    4374  297.91
  4446.4  299.74  4518.9  297.45  4602.4  297.33  4684.9  297.32  4721.1  295.78
  4742.2  296.77  4901.1  295.92  4986.6  296.88  4995.8  295.12  4998.7  293.15
  5001.5  292.65  5004.7  293.15  5008.5  295.74  5016.8  297.31  5121.7  296.45
  5131.5  296.65  5161.7  294.46  5182.8  295.49  5203.9  294.71  5240.2     297
  5581.4  301.86  5743.8  306.53  5807.9  305.88  5984.1  309.31  6006.4  310.43
#Mann= 6 ,-1 , 0
    3636     .05       0  4602.4     .12       0  4998.7     .07       0
  5004.7     .12       0  5121.7     .05       0  5984.1     .16       0
Bank Sta=4986.6,5016.8
XS Rating Curve= 0 ,0
Exp/Cntr=0.3,0.1

Type RM Length L Ch R = 1 ,131492  ,928,928,928
BEGIN DESCRIPTION:
GIBBONS CREEK 105.0
END DESCRIPTION:
XS GIS Cut Line= 3
      3661142.14     10247791.62      3660470.62     10248209.84
       3658942.1     10248391.64
#Sta/Elev= 30
  3873.1  309.67  3917.4  309.93  4069.6  303.84  4316.3  297.54    4380  297.98
  4438.6  295.93  4578.3  294.62  4605.4  295.75    4703  294.68    4883  295.44
  4944.7  294.05  4964.8   294.8    4985  293.49    4992  290.86  4994.8  290.36
    4998  290.86  5005.1  291.23  5015.2   294.1  5035.3  294.34  5055.4  292.67
  5060.5  293.85  5075.6  292.77  5095.7  294.39  5140.1  294.07  5236.7  294.99
  5414.8   299.2  5439.8  298.02  6012.2  306.84  6143.1  311.04  6203.5  311.64
#Mann= 7 ,-1 , 0
  3873.1     .05       0    4883     .12       0    4992     .07       0
    4998     .12       0  5140.1     .05       0  5414.8      .1       0
  5439.8     .16       0
Bank Sta=4964.8,5015.2
XS Rating Curve= 0 ,0
Exp/Cntr=0.3,0.1

Type RM Length L Ch R = 1 ,130564  ,803,803,803
BEGIN DESCRIPTION:
GIBBONS CREEK 103.0
END DESCRIPTION:
XS GIS Cut Line= 3
      3660992.13     10247591.64      3660359.51     10247723.73
      3659092.15     10247891.64
#Sta/Elev= 30
  4160.5  308.12  4201.4  306.95  4252.5  304.61  4436.3  300.16  4681.5  292.84
  4720.2  293.15  4770.2  292.15  4785.2   292.6  4844.5  294.96  4874.8  294.08
  4902.5  294.24  4975.6  293.09  4992.8  289.53  4995.6  289.03  4998.8  289.53
  5003.3  290.27    5016  292.05  5036.2   292.5  5076.5  292.51  5116.9  291.64
    5250  294.08  5318.6  294.34  5409.4  295.76  5449.7  296.96  5550.6  298.39
  5631.3     301  5666.5  301.13  5823.4  304.88  5896.8   305.3  6085.2  309.18
#Mann= 6 ,-1 , 0
  4160.5     .05       0  4785.2     .12       0  4992.8     .07       0
  4998.8     .12       0  5003.3      .1       0    5250     .05       0
Bank Sta=4975.6,5036.2
XS Rating Curve= 0 ,0
Exp/Cntr=0.3,0.1

Type RM Length L Ch R = 1 ,129761  ,657,657,657
BEGIN DESCRIPTION:
GIBBONS CREEK 102.0
END DESCRIPTION:
XS GIS Cut Line= 3
      3660792.13     10247191.64      3660097.35     10247188.14
      3659366.79      10247390.3
#Sta/Elev= 30
  4638.4  307.89  4708.4  304.63  4753.3  301.59  4818.4  297.12  4896.9  293.09
  4958.4  289.66  4968.4  290.41  4975.4  286.11  4978.2  285.61  4981.4  286.11
  4998.4   287.2  5018.4  290.98    5028  291.19    5062  291.43  5128.4  292.78
  5234.3  291.91  5298.4  291.03  5308.4  291.07  5318.4  292.29  5328.3   291.1
  5419.2  292.27  5472.9   293.6  5494.3  294.89  5512.4  294.31  5608.4  294.58
  5722.5  297.82  5795.2  297.04  5852.4  298.71  5919.7  298.44  6091.2  301.59
#Mann= 9 ,-1 , 0
  4638.4      .1       0  4753.3     .16       0  4896.9     .12       0
  4975.4     .07       0  4981.4     .12       0    5028     .16       0
    5062     .12       0  5234.3      .1       0  5419.2     .05       0
Bank Sta=4968.4,5018.4
XS Rating Curve= 0 ,0
Exp/Cntr=0.3,0.1

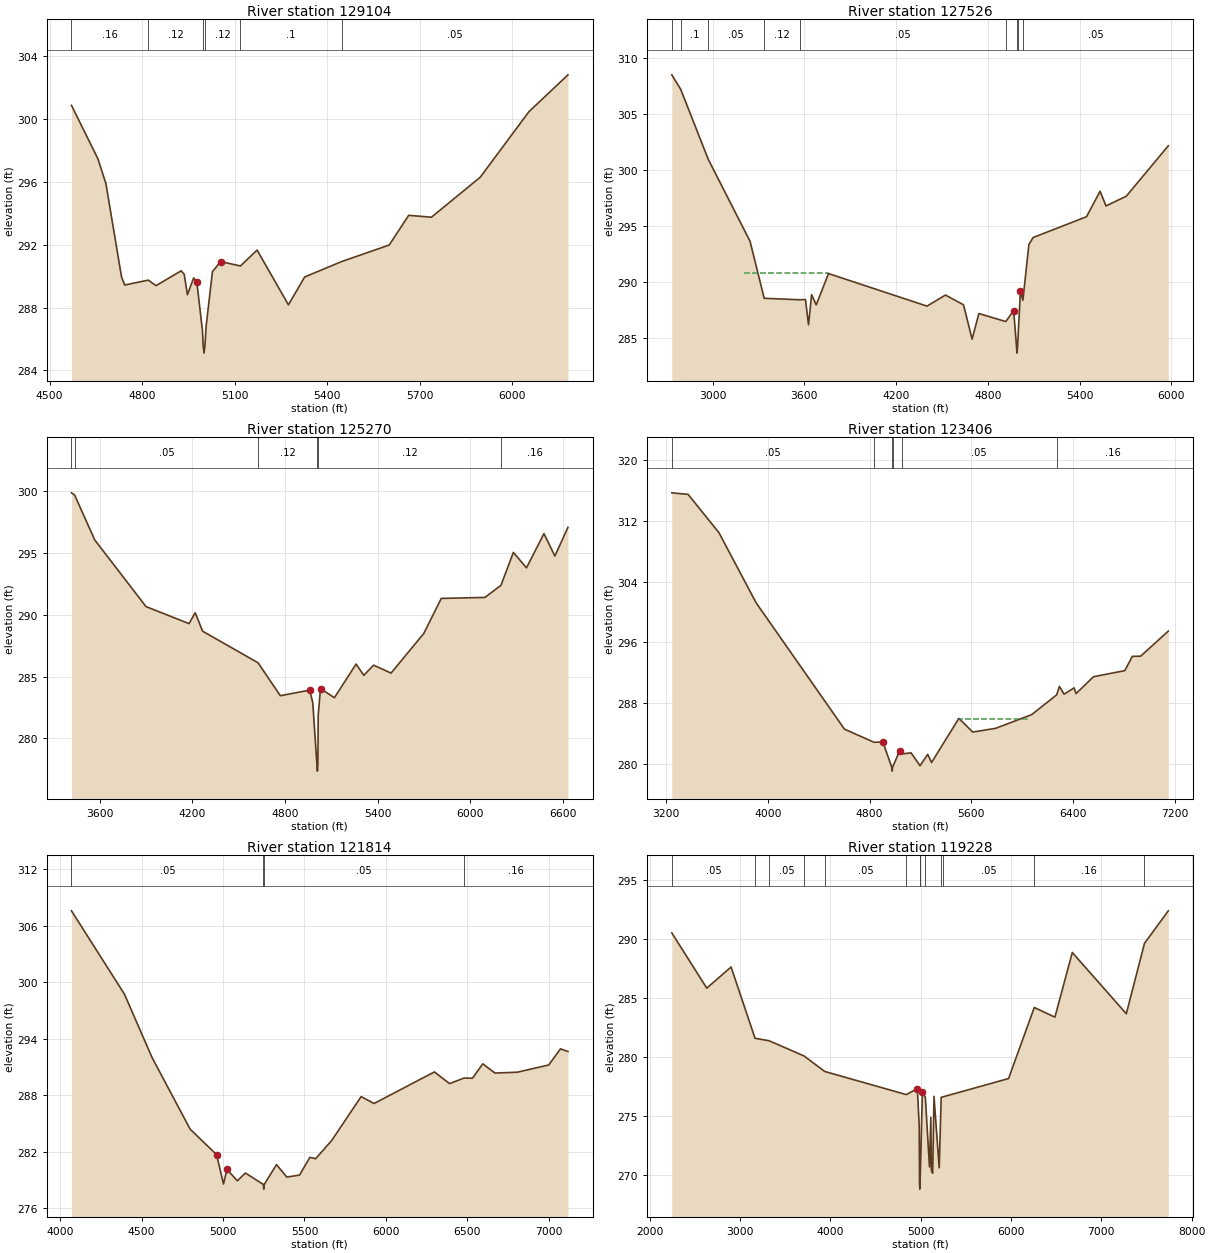
Type RM Length L Ch R = 1 ,129104  ,1578,1578,1578
BEGIN DESCRIPTION:
GIBBONS CREEK 101.0
END DESCRIPTION:
XS GIS Cut Line= 3
       3660792.1     10246891.64      3660172.72     10246781.44
      3659242.07     10247091.65
#Sta/Elev= 30
  4570.9  300.85  4656.9  297.44  4682.6  295.87  4733.4  289.92  4743.6  289.43
  4819.9  289.74  4845.1  289.39  4926.4  290.33  4936.5  290.11  4946.9  288.81
    4967  289.88  4977.2  289.65  4995.7  286.52  4997.8   285.6  5000.6   285.1
  5003.8   285.6  5007.6  286.82    5028  290.28  5054.7  290.92  5118.7  290.64
  5172.8  291.65  5274.4  288.17  5327.1  289.94  5446.9  290.92  5601.2  291.97
  5664.5  293.86  5738.2  293.74  5896.4  296.28  6054.5  300.45    6181  302.79
#Mann= 6 ,-1 , 0
  4570.9     .16       0  4819.9     .12       0  4997.8     .07       0
  5003.8     .12       0  5118.7      .1       0  5446.9     .05       0
Bank Sta=4977.2,5054.7
XS Rating Curve= 0 ,0
Exp/Cntr=0.3,0.1

Type RM Length L Ch R = 1 ,127526  ,2256,2256,2256
BEGIN DESCRIPTION:
GIBBONS CREEK 100.0
END DESCRIPTION:
XS GIS Cut Line= 3
      3662030.66     10245727.75      3660112.67     10245938.88
      3658942.12     10246541.64
#Sta/Elev= 30
  2733.9  308.48  2792.2  307.18  2971.4  300.95  3245.5   293.6  3337.9  288.51
    3570  288.38  3607.7   288.4  3627.8  286.14  3647.9  288.83  3678.1  287.92
  3758.6  290.72  4402.5  287.81  4523.2   288.8    4641  287.93  4697.3  284.86
  4741.6  287.15  4917.6  286.43  4968.9  287.41  4988.1  284.11  4990.8  283.61
  4994.1  284.11  5013.3  289.16  5029.3  288.33  5068.5  293.31  5096.3  293.94
  5445.4   295.8  5534.1  298.08  5572.8  296.76  5705.8  297.64  5980.1  302.14
#Mann= 9 ,-1 , 0
  2733.9     .16       0  2792.2      .1       0  2971.4     .05       0
  3337.9     .12       0    3570     .05       0  4917.6     .16       0
  4988.1     .07       0  4994.1     .16       0  5029.3     .05       0
#XS Ineff= 1 ,-1
 3203.98 3756.82  290.81
Permanent Ineff=
       F
Bank Sta=4968.9,5013.3
XS Rating Curve= 0 ,0
Exp/Cntr=0.3,0.1

Type RM Length L Ch R = 1 ,125270  ,1864,1864,1864
BEGIN DESCRIPTION:
GIBBONS CREEK 99.0
END DESCRIPTION:
XS GIS Cut Line= 3
      3661922.02     10245022.34      3660013.93     10244919.82
       3659092.1     10245841.65
#Sta/Elev= 30
  3417.7  299.87  3438.1  299.69  3567.8  296.07    3900  290.67  4178.7  289.29
  4218.8  290.17  4266.6  288.68  4625.9  286.12  4769.6  283.46  4959.8  283.91
  4979.9   282.9  5006.9  277.86  5009.7  277.36  5012.9  277.86    5015  281.88
  5029.9  284.03  5120.1   283.3  5260.3  286.02  5310.3  285.11  5373.5  285.93
  5486.7  285.29  5698.8   288.5    5812  291.33  6094.8  291.41  6198.4  292.39
  6278.6  295.05  6363.5   293.8  6476.6  296.57  6547.3  294.76  6632.2  297.08
#Mann= 6 ,-1 , 0
  3417.7     .16       0  3438.1     .05       0  4625.9     .12       0
  5006.9     .07       0  5012.9     .12       0  6198.4     .16       0
Bank Sta=4959.8,5029.9
XS Rating Curve= 0 ,0
Exp/Cntr=0.3,0.1

Type RM Length L Ch R = 1 ,123406  ,1592,1592,1592
BEGIN DESCRIPTION:
GIBBONS CREEK 98.0
END DESCRIPTION:
XS GIS Cut Line= 3
      3661790.07     10243570.95      3659694.66     10243821.83
      3658742.12     10245341.62
#Sta/Elev= 30
  3245.5  315.64  3373.4  315.44  3616.1  310.41  3908.2  301.21  4603.1  284.62
  4835.7   282.9  4905.2  282.93  4975.3  279.61    4978  279.11  4981.3  279.61
  5036.2  281.75  5053.3  281.36  5126.8  281.51  5197.3  279.82  5257.7  281.31
  5287.9  280.24  5502.5  286.03  5612.1  284.24  5792.3  284.73  6075.6  286.53
    6271  289.11  6293.3  290.23  6329.9  289.21  6408.8  290.04  6424.1  289.28
  6560.9   291.5  6807.3   292.3  6866.3  294.17  6932.1   294.2  7149.5  297.49
#Mann= 6 ,-1 , 0
  3245.5     .05       0  4835.7     .12       0  4975.3     .07       0
  4981.3     .12       0  5053.3     .05       0    6271     .16       0
#XS Ineff= 1 ,-1
 5497.16 6045.45  285.98
Permanent Ineff=
       F
Bank Sta=4905.2,5036.2
XS Rating Curve= 0 ,0
Exp/Cntr=0.3,0.1

Type RM Length L Ch R = 1 ,121814  ,2586,2586,2586
BEGIN DESCRIPTION:
GIBBONS CREEK 97.0
END DESCRIPTION:
XS GIS Cut Line= 3
      3660442.13     10242291.62      3659255.34     10243459.84
      3658797.06     10244765.23
#Sta/Elev= 30
  4069.5  307.56  4394.8  298.71  4564.5  291.98  4797.9  284.39  4960.5  281.68
    5003  278.56  5024.1  280.12  5087.8   278.9  5137.3  279.73  5247.4  278.52
  5250.2  278.02  5253.4  278.52  5328.3  280.62  5391.8   279.3  5469.7  279.51
  5533.3  281.39  5568.7  281.25  5667.7  283.19    5848  287.84  5927.5  287.11
  6298.1  290.46  6391.1  289.22  6479.9  289.81  6531.6  289.79  6595.2  291.32
    6670  290.34  6807.1  290.43  7000.3   291.2  7072.1  292.91  7118.3  292.63
#Mann= 4 ,-1 , 0
  4069.5     .05       0  5247.4     .03       0  5253.4     .05       0
  6479.9     .16       0
Bank Sta=4960.5,5024.1
XS Rating Curve= 0 ,0
Exp/Cntr=0.3,0.1

Type RM Length L Ch R = 1 ,119228  ,372,372,372
BEGIN DESCRIPTION:
GIBBONS CREEK 96.0
END DESCRIPTION:
XS GIS Cut Line= 3
      3659595.51     10240629.24      3657856.07     10242598.72
      3656080.09     10244852.79
#Sta/Elev= 30
  2244.1  290.55    2631  285.87  2900.4  287.66  3165.5  281.62  3322.1  281.41
  3708.9  280.12  3936.9  278.81    4840  276.85  4962.6  277.35  4983.4  274.22
    4987  269.34  4989.8  268.84    4993  269.34  5018.7  277.11  5051.1  276.63
  5097.3  270.72  5111.7  274.91  5118.1  270.43  5132.5  270.19    5147   276.7
  5204.7  270.64  5226.9  276.62  5242.6  276.65  5972.8  278.21  6257.5  284.23
  6485.9  283.41  6678.3  288.89  7276.4   283.7  7477.3  289.66  7741.4  292.42
#Mann= 13 ,-1 , 0
  2244.1     .05       0  3165.5     .12       0  3322.1     .05       0
  3708.9     .12       0  3936.9     .05       0    4840     .12       0
    4987     .07       0    4993     .12       0  5051.1     .05       0
  5226.9     .12       0  5242.6     .05       0  6257.5     .16       0
  7477.3      .1       0
Bank Sta=4962.6,5018.7
XS Rating Curve= 0 ,0
Exp/Cntr=0.3,0.1

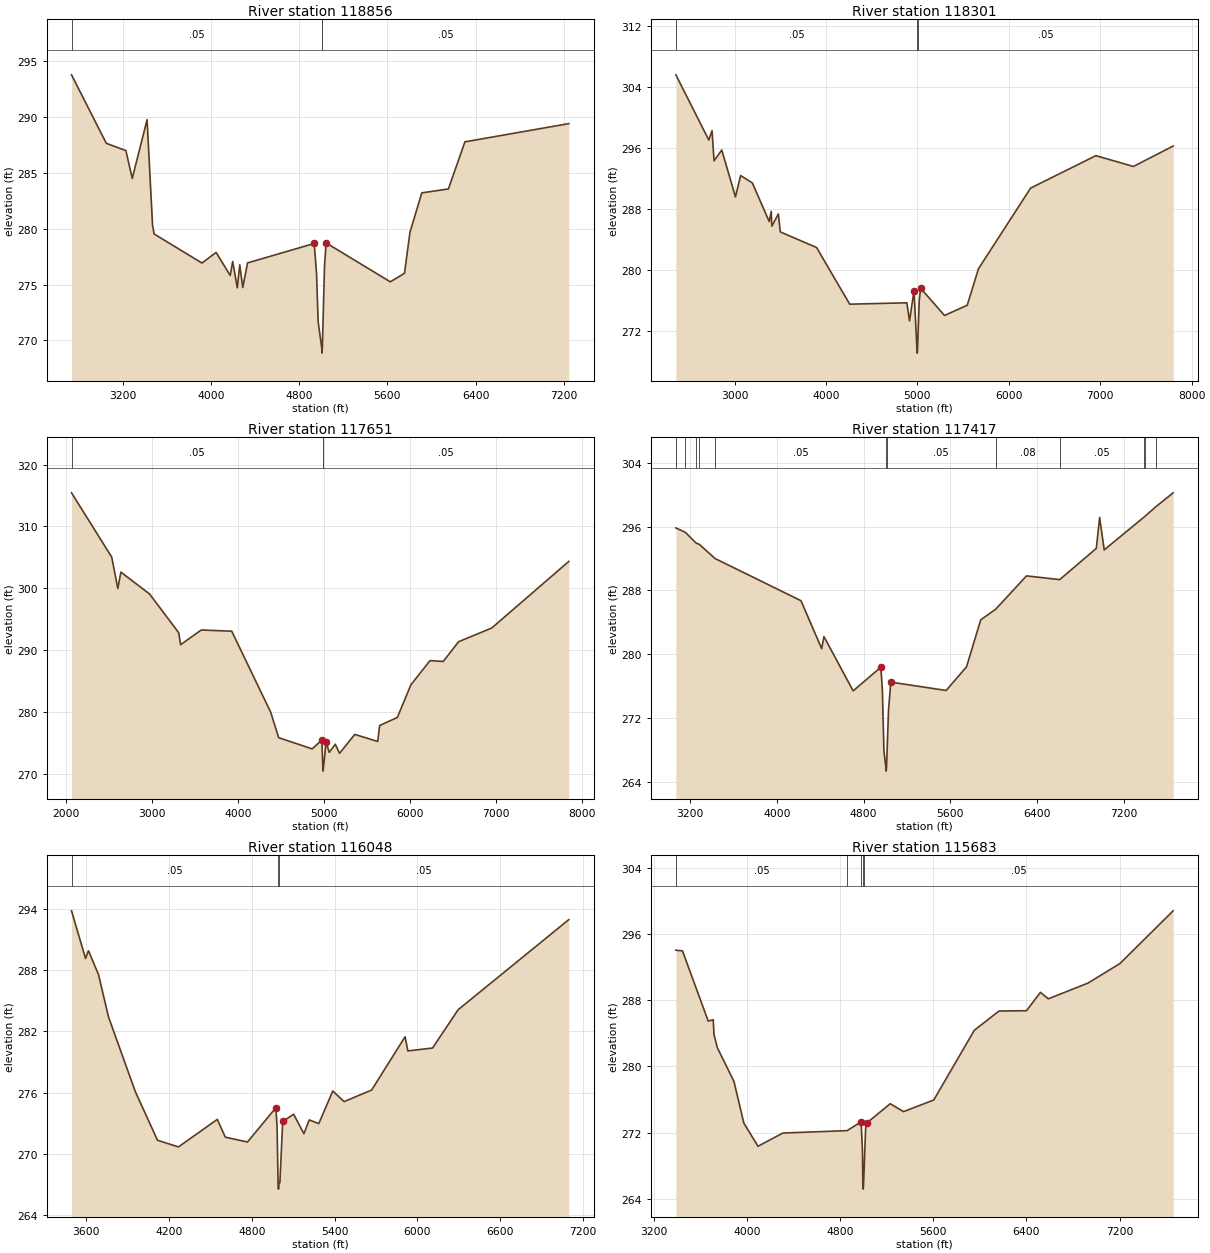
Type RM Length L Ch R = 1 ,118856  ,555,555,555
BEGIN DESCRIPTION:
GIBBONS CREEK 95.0
END DESCRIPTION:
XS GIS Cut Line= 3
      3658845.08     10240901.66      3657308.41     10242815.14
      3656026.85     10244419.49
#Sta/Elev= 30
  2737.3  293.74  3052.5  287.62  3230.1  286.97  3287.7  284.48  3422.1  289.73
  3471.7   280.3  3486.1  279.52  3919.8  276.92  4047.8  277.87  4175.8  275.81
  4198.2  277.06  4239.8  274.71  4262.2  276.76  4289.4  274.73  4332.6  276.93
  4937.4  278.67  4958.2  275.99  4972.6   271.7  5004.8  269.37  5007.6  268.87
  5010.8  269.37  5030.2  276.61  5044.6  278.72  5627.3  275.24  5755.4  276.01
    5805  279.67  5912.3  283.19  6153.3  283.54    6303  287.75  7244.8  289.38
#Mann= 3 ,-1 , 0
  2737.3     .05       0  5004.8     .03       0  5010.8     .05       0
Bank Sta=4937.4,5044.6
XS Rating Curve= 0 ,0
Exp/Cntr=0.3,0.1

Type RM Length L Ch R = 1 ,118301  ,650,650,650
BEGIN DESCRIPTION:
GIBBONS CREEK 94.0
END DESCRIPTION:
XS GIS Cut Line= 3
      3658704.26     10240306.51      3656792.21     10242622.95
      3655556.36     10244721.67
#Sta/Elev= 30
  2358.7  305.61  2718.7  297.06  2754.4   298.3  2776.1  294.33  2860.7  295.75
  3010.6   289.6  3066.6   292.4  3195.2  291.43  3379.3  286.37  3401.5   287.7
    3408  285.76  3479.6  287.36  3500.5  285.01  3897.8  282.96    4260  275.53
  4885.4  275.71    4914  273.33  4963.5  277.29  4995.7  269.61  4998.5  269.11
  5001.7  269.61  5020.9  276.04  5035.2  277.63  5297.1  274.05  5545.2  275.39
  5668.2  280.17  6238.3  290.75  6952.8  295.01  7362.8  293.59  7797.9  296.27
#Mann= 3 ,-1 , 0
  2358.7     .05       0  4995.7     .03       0  5001.7     .05       0
Bank Sta=4963.5,5035.2
XS Rating Curve= 0 ,0
Exp/Cntr=0.3,0.1

Type RM Length L Ch R = 1 ,117651  ,234,234,234
BEGIN DESCRIPTION:
GIBBONS CREEK 93.0
END DESCRIPTION:
XS GIS Cut Line= 3
       3658742.1     10239841.64      3656581.73     10242105.67
       3655342.1     10244441.65
#Sta/Elev= 30
  2069.9  315.42  2536.8  305.02  2607.6  299.95  2642.8   302.6  2975.2  299.07
  3314.6  292.79    3336  290.86  3576.5  293.24  3930.1  293.04  4382.7  279.93
  4474.9  275.82  4863.6  274.01  4976.8  275.43    4988  270.91  4990.7  270.41
    4994  270.91  5026.5  275.13  5061.8  273.45  5132.5  274.76  5181.9  273.29
  5358.7  276.35  5624.9  275.21  5647.6  277.79  5853.1  279.09  6009.8  284.36
  6231.9  288.28  6385.8  288.15  6564.5  291.34  6949.4  293.56  7843.8  304.33
#Mann= 3 ,-1 , 0
  2069.9     .05       0    4988     .03       0    4994     .05       0
Bank Sta=4976.8,5026.5
XS Rating Curve= 0 ,0
Exp/Cntr=0.3,0.1

Type RM Length L Ch R = 1 ,117417  ,1369,1369,1369
BEGIN DESCRIPTION:
GIBBONS CREEK 91.0
END DESCRIPTION:
XS GIS Cut Line= 3
      3657857.77     10240379.33      3656384.45     10241981.97
      3655096.59     10244012.67
#Sta/Elev= 30
  3071.1  295.83  3159.5  295.26  3255.4  293.95  3288.3  293.75  3432.6  291.98
  4223.3   286.7  4414.5  280.68  4435.4  282.19  4704.3  275.38  4959.5  278.35
  4973.7  275.47  4987.8  267.85  5005.8  265.81  5008.6  265.31  5011.8  265.81
  5030.3  273.01  5051.3  276.48    5561  275.43  5749.1   278.4  5879.6  284.29
    6018  285.63  6301.5  289.81  6607.3  289.34  6944.6  293.26  6975.1  297.14
  7017.4  293.07  7381.2  297.15    7393  297.29  7494.7   298.5  7652.7  300.23
#Mann= 12 ,-1 , 0
  3071.1     .05       0  3159.5     .08       0  3255.4     .05       0
  3288.3     .08       0  3432.6     .05       0  5005.8     .04       0
  5011.8     .05       0    6018     .08       0  6607.3     .05       0
  7381.2     .08       0    7393     .05       0  7494.7     .08       0
Bank Sta=4959.5,5051.3
XS Rating Curve= 0 ,0
Exp/Cntr=0.3,0.1

Type RM Length L Ch R = 1 ,116048  ,365,365,365
BEGIN DESCRIPTION:
GIBBONS CREEK 89.0
END DESCRIPTION:
XS GIS Cut Line= 4
      3656392.09     10240041.67      3655678.95     10241161.23
      3655623.39     10241536.23       3655042.1     10243341.66
#Sta/Elev= 30
  3493.2  293.79  3594.8  289.13  3615.9  289.89  3688.7  287.55  3761.5   283.4
  3955.6   276.1  4116.2  271.35  4267.7   270.7  4549.6  273.39  4607.7  271.65
    4768  271.18  4973.7  274.53  4982.8  272.63  4989.9  267.07  4992.6  266.57
  4995.9  267.07    5003   267.2  5023.2  273.19  5102.6  273.89  5177.1  271.99
  5215.4  273.34  5284.8  272.98  5386.3  276.17    5468  275.13  5667.6  276.26
    5910  281.47  5930.3  280.09  6108.9  280.37  6294.8  284.12  7096.4  292.93
#Mann= 3 ,-1 , 0
  3493.2     .05       0  4989.9     .03       0  4995.9     .05       0
Bank Sta=4973.7,5023.2
XS Rating Curve= 0 ,0
Exp/Cntr=0.3,0.1

Type RM Length L Ch R = 1 ,115683  ,2213,2213,2213
BEGIN DESCRIPTION:
GIBBONS CREEK 88.0
END DESCRIPTION:
XS GIS Cut Line= 3
      3656342.07     10239991.68      3655276.17     10241320.95
       3654592.1     10243791.65
#Sta/Elev= 30
  3391.7  294.07  3448.5  293.99  3669.3  285.49  3712.1  285.66  3718.9  283.84
  3747.7  282.27  3890.2  278.18    3975  273.14  4096.6  270.34  4309.5  271.94
  4860.8  272.23  4978.4  273.27  4982.9  272.86  4992.8  269.81  4996.2  265.65
    4999  265.15  5002.2  265.65    5020  272.49    5028  273.13  5231.2  275.49
  5345.3  274.53  5604.7  275.94  5953.2  284.39    6165  286.71  6401.1  286.75
  6519.6  288.97  6588.2  288.19    6928  290.09  7202.6  292.46  7659.2  298.84
#Mann= 5 ,-1 , 0
  3391.7     .05       0  4860.8     .12       0  4982.9     .05       0
  4996.2     .03       0  5002.2     .05       0
Bank Sta=4978.4,5028
XS Rating Curve= 0 ,0
Exp/Cntr=0.3,0.1

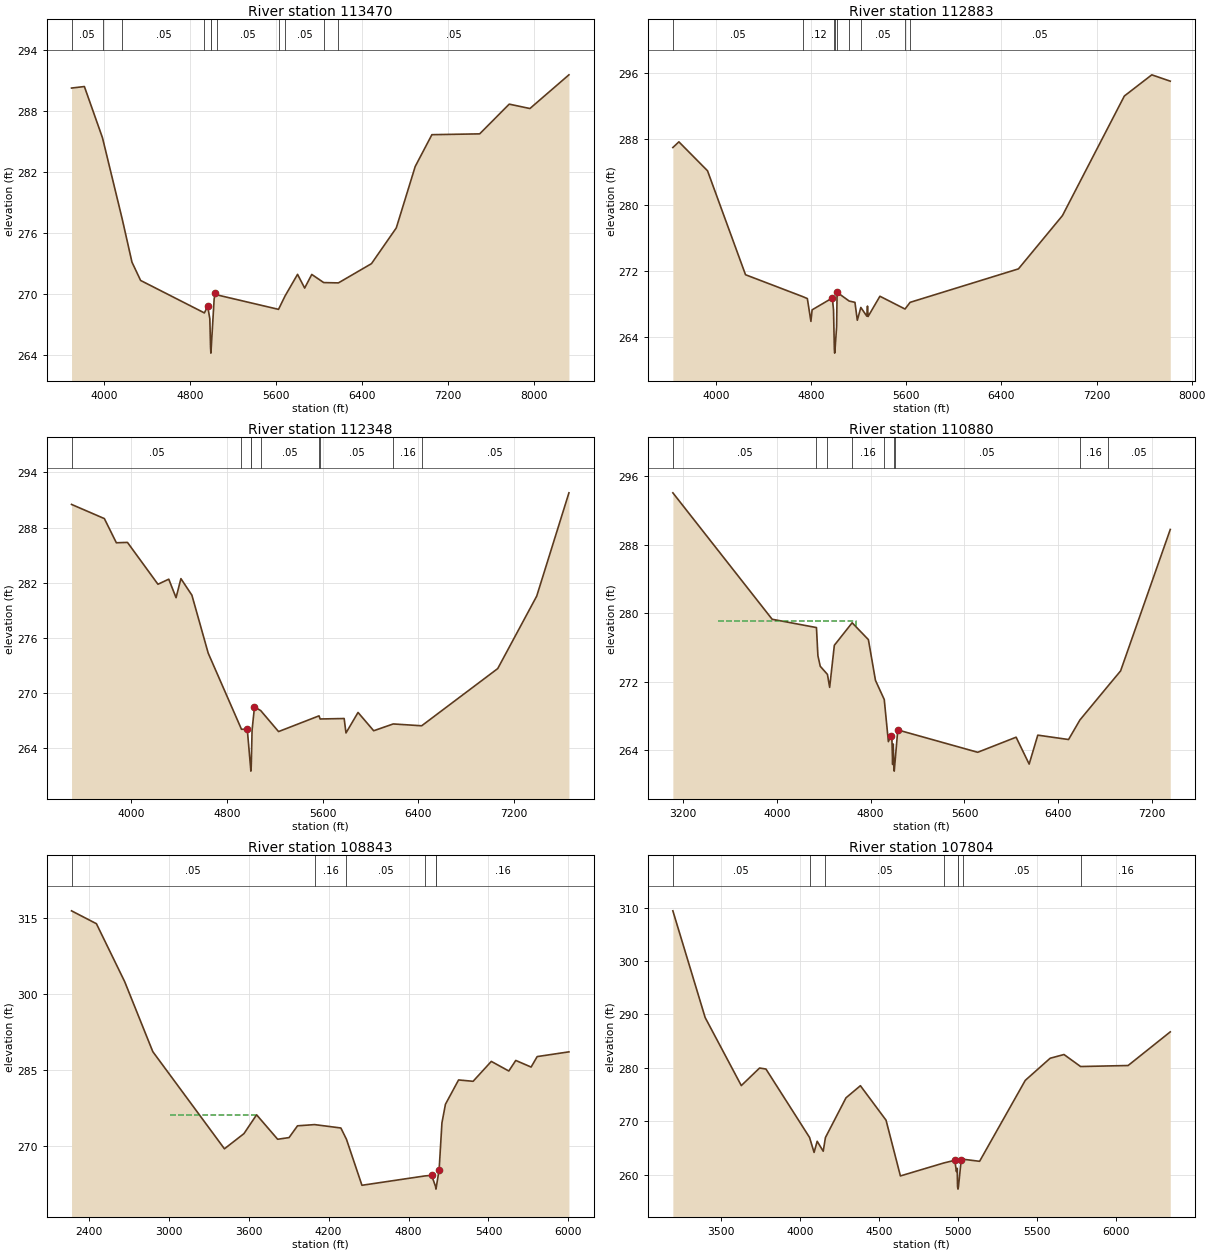
Type RM Length L Ch R = 1 ,113470  ,587,587,587
BEGIN DESCRIPTION:
GIBBONS CREEK 88.2
END DESCRIPTION:
XS GIS Cut Line= 3
       3656310.9     10239793.17      3654366.71     10239988.66
      3653117.33     10242347.07
#Sta/Elev= 30
  3699.1  290.22  3818.5  290.37  3986.9  285.33  4170.5  277.34  4260.7  273.12
  4341.1  271.32  4933.9  268.13  4964.2  268.79  4984.3  267.57  4991.4  264.68
  4994.1  264.18  4997.4  264.68  5024.5   269.5  5036.4  270.13  5047.3  269.91
  5622.8  268.48  5683.3  269.79  5799.8  271.92  5865.8  270.57  5931.8  271.91
    6043  271.11  6179.6  271.08  6486.8  272.97  6717.4  276.48  6893.4  282.52
  7048.4  285.64  7492.4  285.72    7767  288.64  7959.4  288.21    8322  291.52
#Mann= 11 ,-1 , 0
  3699.1     .05       0  3986.9     .16       0  4170.5     .05       0
  4933.9     .12       0  4991.4     .07       0  4997.4     .12       0
  5047.3     .05       0  5622.8     .16       0  5683.3     .05       0
    6043     .16       0  6179.6     .05       0
Bank Sta=4964.2,5036.4
XS Rating Curve= 0 ,0
Exp/Cntr=0.3,0.1

Type RM Length L Ch R = 1 ,112883  ,535,535,535
BEGIN DESCRIPTION:
GIBBONS CREEK 88.1
END DESCRIPTION:
XS GIS Cut Line= 4
      3656165.03     10239314.02      3655248.39     10239543.17
      3653835.81     10239489.03      3652096.34     10240042.94
#Sta/Elev= 30
    3636  286.99  3686.7  287.68  3927.6  284.17  4247.2  271.56  4727.8  268.91
  4767.3  268.67  4797.3   265.9  4807.3   267.3  4977.4  268.74  4987.4  267.31
  4994.4  262.55  4997.2  262.05  5000.4  262.55  5013.4  265.23  5017.5  269.43
  5118.6  268.37  5167.6  268.21  5187.6  266.04  5217.2  267.59  5267.6  266.53
  5273.1  267.76  5278.1  266.49  5377.7  268.95    5589   267.4  5631.7  268.21
  6542.9  272.27    6913  278.73  7433.8  293.24  7664.6  295.81    7820  295.04
#Mann= 9 ,-1 , 0
    3636     .05       0  4727.8     .12       0  4994.4     .07       0
  5000.4     .12       0  5013.4     .05       0  5118.6     .16       0
  5217.2     .05       0    5589     .16       0  5631.7     .05       0
Bank Sta=4977.4,5017.5
XS Rating Curve= 0 ,0
Exp/Cntr=0.3,0.1

Type RM Length L Ch R = 1 ,112348  ,1468,1468,1468
BEGIN DESCRIPTION:
GIBBONS CREEK 88.3
END DESCRIPTION:
XS GIS Cut Line= 4
      3656512.23     10238959.85      3655505.34      10239140.4
      3653998.39     10238966.79      3652485.78     10239542.69
#Sta/Elev= 30
  3500.3  290.52  3774.7  288.98    3875  286.35  3967.8  286.39  4222.8  281.84
  4313.2  282.39  4374.1  280.38  4414.8  282.45  4506.6  280.65  4642.9  274.35
    4921  266.07  4969.4  266.08  4996.6  262.02  4999.4  261.52  5002.6  262.02
  5009.7  265.99  5029.8  268.49  5081.4  268.11  5231.1  265.82  5569.4  267.53
  5578.6  267.19  5779.5  267.24  5794.8  265.67  5895.5   267.9  6026.4  265.91
  6189.9  266.65  6427.6  266.45  7063.4  272.67  7389.3  280.55  7658.7  291.78
#Mann= 9 ,-1 , 0
  3500.3     .05       0    4921     .12       0  4996.6     .07       0
  5002.6     .12       0  5081.4     .05       0  5569.4     .16       0
  5578.6     .05       0  6189.9     .16       0  6427.6     .05       0
Bank Sta=4969.4,5029.8
XS Rating Curve= 0 ,0
Exp/Cntr=0.3,0.1

Type RM Length L Ch R = 1 ,110880  ,2037,2037,2037
BEGIN DESCRIPTION:
GIBBONS CREEK 88.4
END DESCRIPTION:
XS GIS Cut Line= 4
      3656498.39     10237980.67      3654998.39     10237932.06
      3654084.42     10237992.14      3652345.68     10238545.82
#Sta/Elev= 30
  3113.2  294.07  3959.9  279.31  4337.7  278.34  4350.1  275.05  4370.1  273.82
  4431.4  272.87  4450.2  271.36  4490.2  276.27    4642   278.9  4780.6  276.93
    4841  272.17  4915.8  269.94    4951  265.02    4971  265.66  4981.1  265.35
  4987.4  262.35  4992.4  264.75  4998.1  262.08  5000.9  261.58  5004.1  262.08
  5031.2  266.39  5712.8  263.78  6040.2  265.54  6151.5   262.4    6225  265.78
  6487.4  265.27  6584.2  267.55    6824  271.52  6931.2  273.28  7354.7  289.79
#Mann= 9 ,-1 , 0
  3113.2     .05       0  4337.7     .16       0  4431.4     .05       0
    4642     .16       0  4915.8     .05       0  4998.1     .03       0
  5004.1     .05       0  6584.2     .16       0    6824     .05       0
#XS Ineff= 1 ,-1
 3494.32 4678.98  279.14
Permanent Ineff=
       F
Bank Sta=4971,5031.2
XS Rating Curve= 0 ,0
Exp/Cntr=0.3,0.1

Type RM Length L Ch R = 1 ,108843  ,1039,1039,1039
BEGIN DESCRIPTION:
GIBBONS CREEK 86.0
END DESCRIPTION:
XS GIS Cut Line= 3
      3655850.47     10236276.35      3653450.44     10237076.36
      3652300.48     10237426.35
#Sta/Elev= 30
  2271.7  316.48  2458.4  313.93  2670.5  302.46  2881.4  288.61  3418.9  269.38
  3565.2  272.38  3660.1  276.11  3818.2  271.27  3903.8   271.6  3967.1  273.93
  4095.3  274.17  4292.5   273.5  4334.3  271.27  4450.6  262.16  4922.7  264.01
  4973.3  264.13  5003.1   261.9  5005.9   261.4  5009.1   261.9  5029.8  265.28
  5050.7   274.5    5077  278.19  5175.6  283.01  5284.6  282.74  5421.2  286.68
  5552.4  284.78  5604.7  286.87  5719.7  285.56  5765.4  287.63  6003.6  288.57
#Mann= 6 ,-1 , 0
  2271.7     .05       0  4095.3     .16       0  4334.3     .05       0
  4922.7     .16       0  5003.1     .07       0  5009.1     .16       0
#XS Ineff= 1 ,-1
 3009.94 3659.38  276.15
Permanent Ineff=
       F
Bank Sta=4973.3,5029.8
XS Rating Curve= 0 ,0
Exp/Cntr=0.3,0.1

Type RM Length L Ch R = 1 ,107804  ,1099,1099,1099
BEGIN DESCRIPTION:
GIBBONS CREEK 85.0
END DESCRIPTION:
XS GIS Cut Line= 3
      3655303.92     10235959.85      3653387.28     10236258.45
      3652373.41     10236911.22
#Sta/Elev= 30
  3196.5  309.39  3400.8   289.4  3629.4  276.66  3744.9  279.95  3785.3  279.76
  4060.9  266.95  4089.6  264.15  4109.2  266.23  4147.4  264.37  4161.4  266.93
  4291.4  274.37  4382.5  276.64  4544.7  270.18  4635.5  259.74  4908.8  262.16
  4979.6  262.67  4989.6  260.56  4994.7  261.16  4996.8  257.77  4999.6  257.27
  5002.8  257.77  5020.1  262.77    5031  262.87  5136.3  262.48  5425.2  277.64
  5582.5  281.78  5670.1  282.48    5775  280.23  6075.5  280.42  6342.1  286.72
#Mann= 8 ,-1 , 0
  3196.5     .05       0  4060.9     .16       0  4161.4     .05       0
  4908.8     .16       0  4996.8     .07       0  5002.8     .16       0
    5031     .05       0    5775     .16       0
#XS Ineff= 1 ,-1
 3562.78 4384.09  276.43
Permanent Ineff=
       F
Bank Sta=4979.6,5020.1
XS Rating Curve= 0 ,0
Exp/Cntr=0.3,0.1

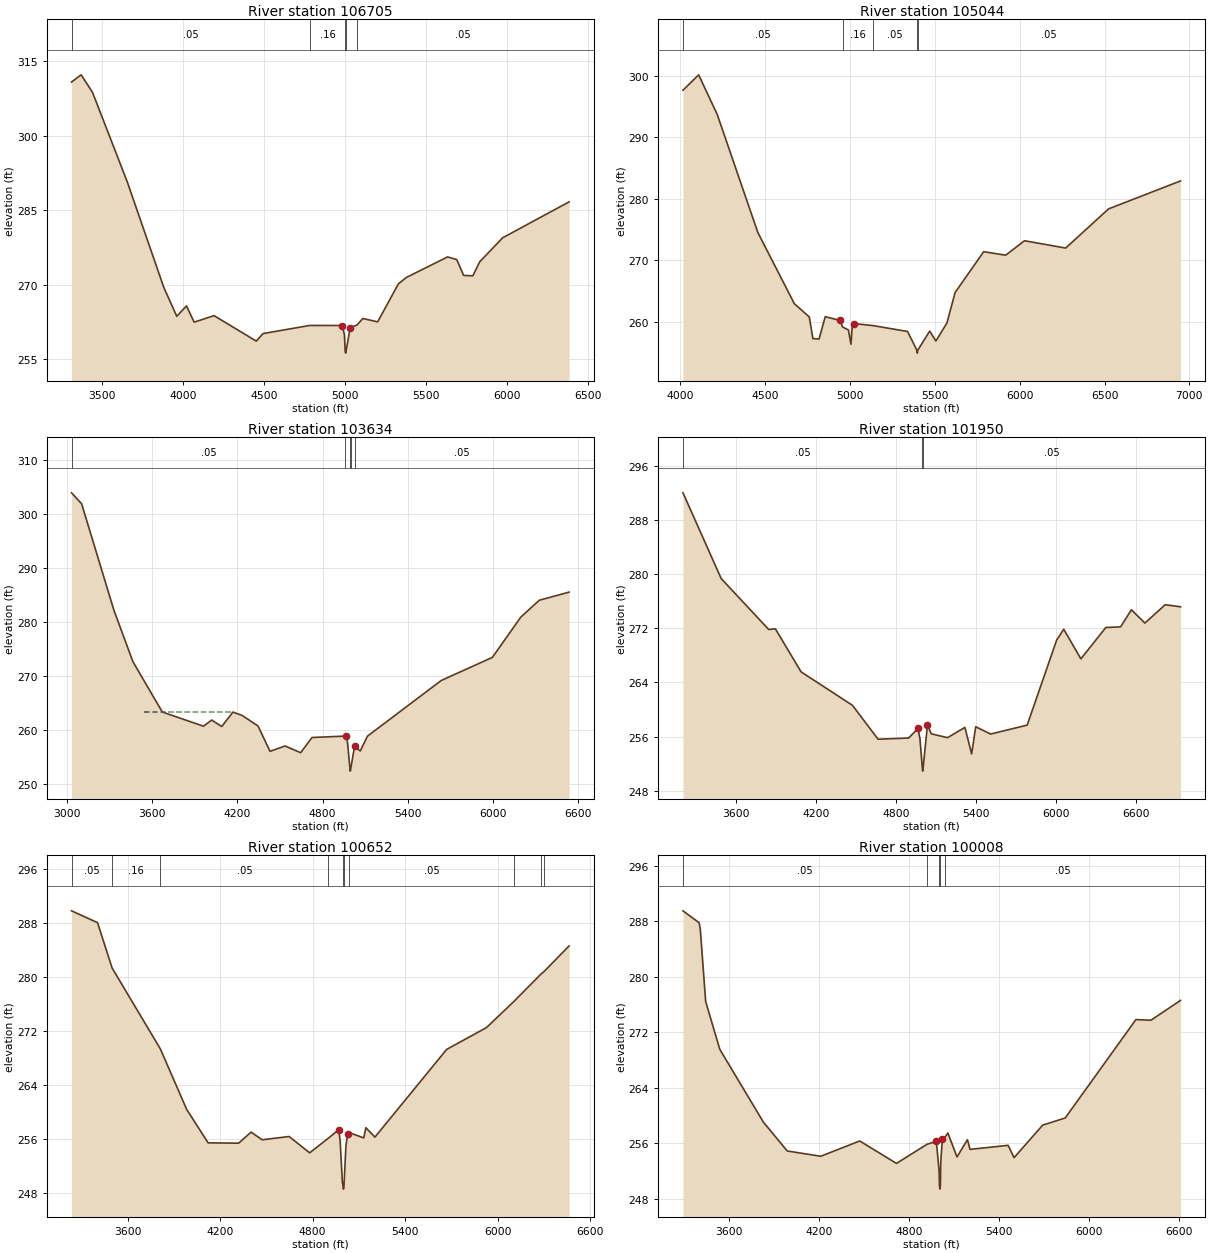
Type RM Length L Ch R = 1 ,106705  ,1661,1661,1661
BEGIN DESCRIPTION:
GIBBONS CREEK 84.0
END DESCRIPTION:
XS GIS Cut Line= 3
      3654901.12     10235293.17      3653748.39     10235237.62
      3652342.11     10236541.63
#Sta/Elev= 30
  3312.7  310.75  3371.8  312.19  3441.9  308.69  3656.6   290.7  3882.4  269.47
  3962.5  263.68  4022.5  265.77  4069.6   262.5  4192.7  263.81    4453   258.7
  4495.3  260.21  4782.7  261.84  4983.4  261.83  4997.6  259.94  5001.9  256.78
  5004.7  256.28  5007.9  256.78  5033.3  261.42  5075.3  261.93    5111  263.24
  5202.8  262.56  5330.4  270.19  5379.7  271.48  5634.5  275.61    5691  275.07
  5733.5  271.89  5790.2  271.81  5832.7  274.63  5974.4  279.45  6384.6  286.67
#Mann= 5 ,-1 , 0
  3312.7     .05       0  4782.7     .16       0  5001.9     .07       0
  5007.9     .16       0  5075.3     .05       0
Bank Sta=4983.4,5033.3
XS Rating Curve= 0 ,0
Exp/Cntr=0.3,0.1

Type RM Length L Ch R = 1 ,105044  ,1410,1410,1410
BEGIN DESCRIPTION:
GIBBONS CREEK 83.0
END DESCRIPTION:
XS GIS Cut Line= 3
       3653984.5     10234216.79      3652630.34      10235077.9
      3652442.11     10236391.62
#Sta/Elev= 30
  4016.1  297.62  4108.4  300.13  4217.7  293.71  4457.3  274.48  4672.4   262.9
  4760.4  260.75  4781.6  257.22    4818  257.16  4854.4  260.79  4942.5  260.17
  4956.2  259.11  4990.8  258.64    5006  256.31  5014.4  259.59  5021.2  259.67
  5133.4  259.35  5339.6  258.38  5394.2  255.36    5397  254.86  5400.2  255.36
    5470  258.45  5506.5  256.83  5571.4  259.76  5619.7  264.72    5788  271.36
  5917.6  270.79  6028.7  273.14  6271.2  271.95  6523.7  278.32    6948  282.87
#Mann= 5 ,-1 , 0
  4016.1     .05       0  4956.2     .16       0  5133.4     .05       0
  5394.2     .07       0  5400.2     .05       0
Bank Sta=4942.5,5021.2
XS Rating Curve= 0 ,0
Exp/Cntr=0.3,0.1

Type RM Length L Ch R = 1 ,103634  ,1684,1684,1684
BEGIN DESCRIPTION:
GIBBONS CREEK 82.0
END DESCRIPTION:
XS GIS Cut Line= 3
       3653342.1     10233441.65      3652262.28     10234348.73
      3652292.11     10236441.67
#Sta/Elev= 30
  3032.9  303.87  3103.8  301.85  3331.4  282.14  3465.4  272.62  3672.2  263.32
  3962.3   260.7  4019.5  261.84  4090.8  260.65  4169.1  263.31  4232.8  262.71
    4346  260.74  4430.6  256.05  4536.1  257.04  4646.1   255.8  4726.1  258.61
  4958.9  258.87  4966.1  258.88  4976.1   257.7  4993.1  252.89  4995.9  252.39
  4999.1  252.89  5026.1  257.03  5029.2  256.88  5066.1  256.12  5116.1  258.85
  5636.2  269.16  5996.2  273.43  6196.2  280.88  6326.3     284  6536.3   285.5
#Mann= 5 ,-1 , 0
  3032.9     .05       0  4958.9     .16       0  4993.1     .07       0
  4999.1     .16       0  5029.2     .05       0
#XS Ineff= 1 ,-1
 3543.18 4168.18  263.37
Permanent Ineff=
       F
Bank Sta=4966.1,5026.1
XS Rating Curve= 0 ,0
Exp/Cntr=0.3,0.1

Type RM Length L Ch R = 1 ,101950  ,1298,1298,1298
BEGIN DESCRIPTION:
GIBBONS CREEK 81.0
END DESCRIPTION:
XS GIS Cut Line= 3
      3653081.73     10232869.56      3651438.83     10234158.77
      3651710.66     10235774.41
#Sta/Elev= 30
    3206  291.98  3492.2  279.33  3848.3  271.81  3898.1  271.91  4090.6  265.56
  4475.6  260.62  4667.3  255.62    4896  255.79  4966.5  257.21  4980.9  255.69
  4998.8  251.41  5001.5  250.91  5004.8  251.41    5037  257.72  5065.9  256.41
  5187.9  255.85  5317.5  257.36  5368.2  253.46  5398.7  257.46  5510.2  256.38
    5784   257.7  6004.6  270.23  6057.8  271.85  6186.3  267.48    6373   272.1
  6483.7   272.2  6564.8  274.72  6665.7  272.76  6818.3  275.47  6932.7  275.16
#Mann= 3 ,-1 , 0
    3206     .05       0  4998.8     .03       0  5004.8     .05       0
Bank Sta=4966.5,5037
XS Rating Curve= 0 ,0
Exp/Cntr=0.3,0.1

Type RM Length L Ch R = 1 ,100652  ,644,644,644
BEGIN DESCRIPTION:
GIBBONS CREEK 80.0
END DESCRIPTION:
XS GIS Cut Line= 3
       3652542.1     10232541.65      3650781.92     10233561.24
      3649727.58     10234119.55
#Sta/Elev= 30
  3236.3  289.81  3404.9  288.06  3499.4  281.35  3812.7  269.36  3983.1  260.42
  4122.2  255.47  4320.2  255.42  4400.6  257.06  4472.8  255.92  4647.4  256.41
  4780.8  253.99  4902.5  256.17  4969.8  257.42  4978.8  255.63  4992.9  249.62
  4997.3  249.12    5000  248.62  5003.3  249.12    5016  255.04  5027.6  256.85
  5033.6  257.02  5131.6   256.2  5145.2  257.71  5204.1  256.32  5669.3   269.3
  5927.6  272.53    6106  276.41  6279.8  280.42  6301.6  280.84  6463.5  284.62
#Mann= 10 ,-1 , 0
  3236.3     .05       0  3499.4     .16       0  3812.7     .05       0
  4902.5     .12       0  4997.3     .07       0  5003.3     .12       0
  5033.6     .05       0    6106     .16       0  6279.8     .05       0
  6301.6     .16       0
Bank Sta=4969.8,5027.6
XS Rating Curve= 0 ,0
Exp/Cntr=0.3,0.1

Type RM Length L Ch R = 1 ,100008  ,926,926,926
BEGIN DESCRIPTION:
GIBBONS CREEK 78.0
END DESCRIPTION:
XS GIS Cut Line= 3
      3652292.07     10232341.66      3650477.56     10233091.79
      3649125.26     10232980.83
#Sta/Elev= 30
  3290.1  289.48  3398.3  287.76  3405.8  286.83  3441.6  276.42  3536.1  269.54
  3826.2  259.09  3985.9  254.92  4209.8  254.16  4469.5  256.36  4714.8  253.13
  4918.4  255.88  4980.9  256.31  4999.4  252.05  5001.8  249.93  5004.6  249.43
  5007.8  249.93  5010.6  253.49  5021.4  256.71  5036.4  256.84  5058.1   257.5
  5118.8  254.06  5188.4  256.54  5205.4  255.15  5459.7  255.73  5499.8  253.96
  5690.5  258.64    5841  259.67  6312.6  273.83  6412.4  273.73  6610.4  276.59
#Mann= 5 ,-1 , 0
  3290.1     .05       0  4918.4     .12       0  5001.8     .07       0
  5007.8     .12       0  5036.4     .05       0
Bank Sta=4980.9,5021.4
XS Rating Curve= 0 ,0
Exp/Cntr=0.3,0.1