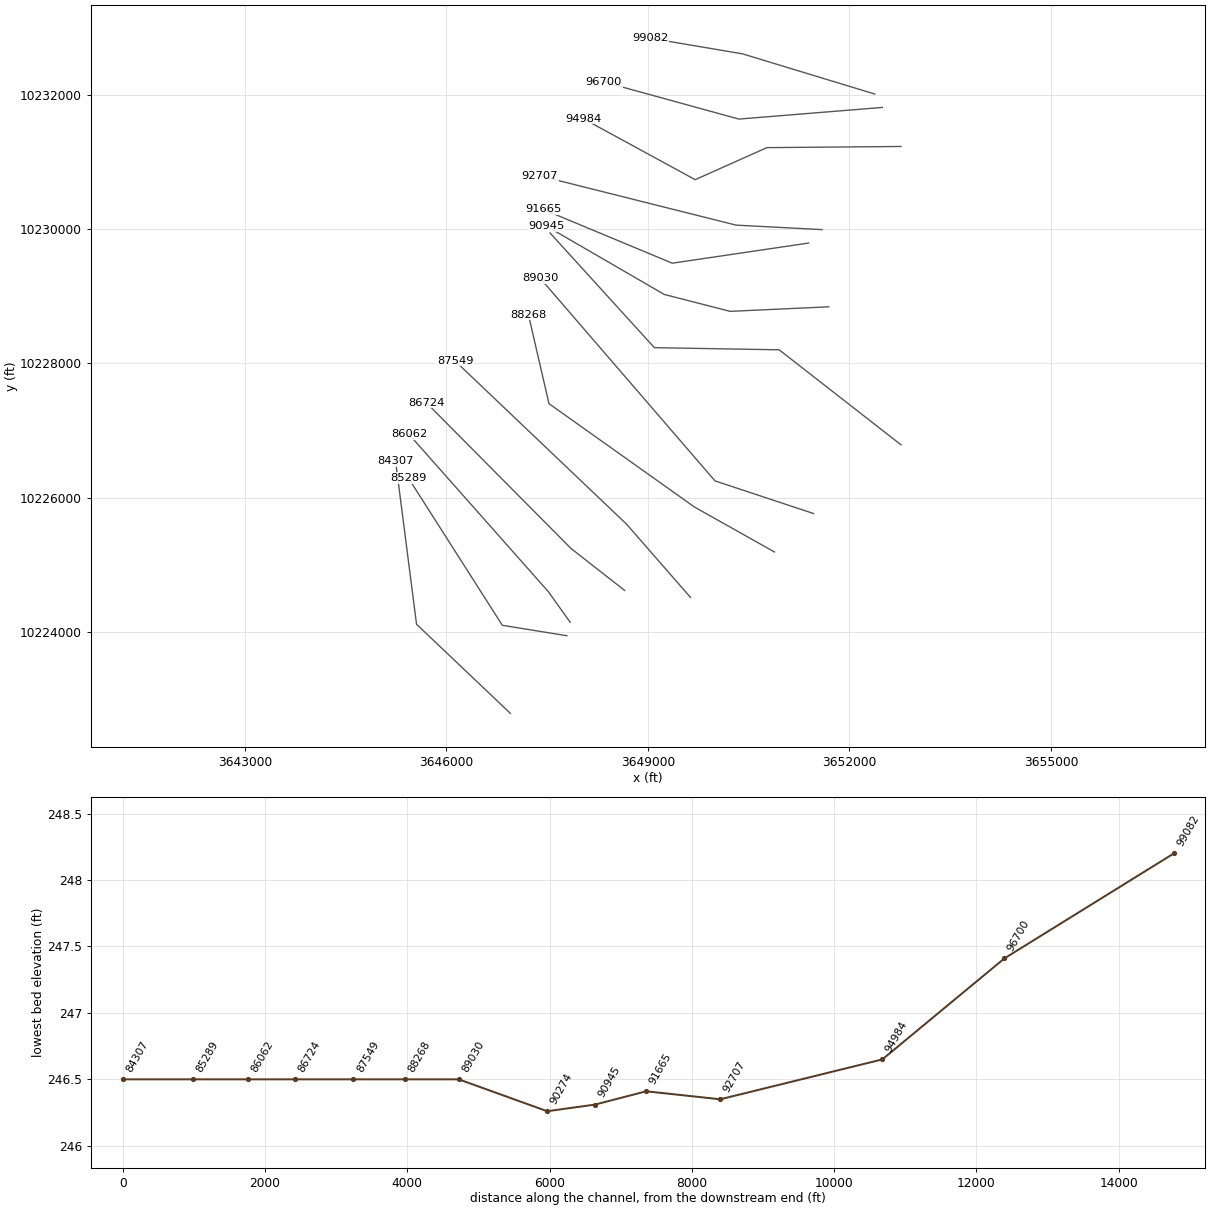
HEC-RAS study GIBBONS CREEK.prj: GIBBONS CREEK Base Level Engineering

--- GIBBONS CREEK.g01 (geometry) --- (continued)

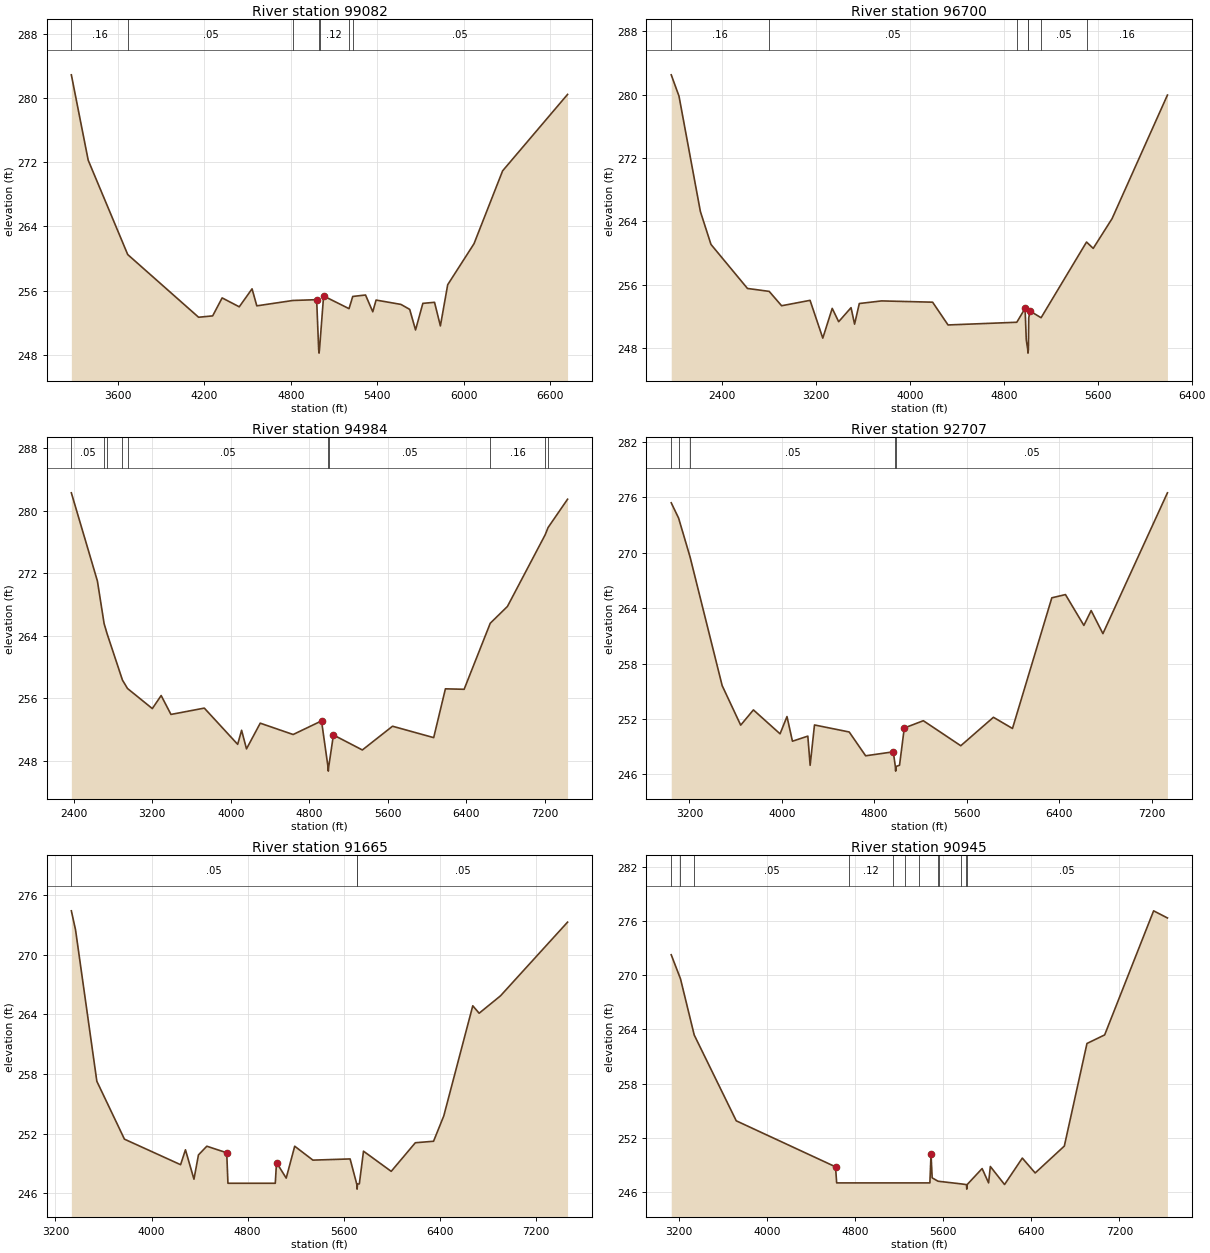
Type RM Length L Ch R = 1 ,99082   ,2382,2382,2382
BEGIN DESCRIPTION:
GIBBONS CREEK 77.0
END DESCRIPTION:
XS GIS Cut Line= 3
      3652376.87     10232011.92      3650406.38     10232610.88
      3649042.07     10232841.65
#Sta/Elev= 30
  3276.6  282.87  3393.6  272.23  3667.8  260.48  4159.5  252.67  4257.2  252.84
  4322.9  255.08  4441.7  253.97  4530.6  256.21  4563.5  254.09  4814.2  254.76
  4978.8  254.86  4992.7   248.7  4995.4   248.2  4998.7   248.7    5027  255.32
  5203.5  253.74  5229.2  255.26    5318  255.44  5368.2  253.35  5391.2  254.81
  5563.6  254.27  5624.4  253.65    5665  251.09  5715.7   254.4  5796.8  254.53
  5837.4  251.59  5888.1  256.72  6070.7  261.83  6269.2  270.91  6719.8  280.43
#Mann= 7 ,-1 , 0
  3276.6     .16       0  3667.8     .05       0  4814.2     .12       0
  4992.7     .07       0  4998.7     .12       0  5203.5     .16       0
  5229.2     .05       0
Bank Sta=4978.8,5027
XS Rating Curve= 0 ,0
Exp/Cntr=0.3,0.1

Type RM Length L Ch R = 1 ,96700   ,1716,1716,1716
BEGIN DESCRIPTION:
GIBBONS CREEK 76.0
END DESCRIPTION:
XS GIS Cut Line= 3
      3652489.69     10231812.27       3650354.3     10231638.66
      3648342.13     10232191.63
#Sta/Elev= 30
  1964.3  282.48  2030.4   279.8  2212.7  265.26    2303  261.11    2614  255.56
  2799.1  255.19    2905  253.38  3147.6  254.06  3256.1   249.3  3336.4  253.05
  3391.4  251.37  3496.9  253.14    3527  251.06  3567.2  253.66  3757.1  253.99
    4192  253.83  4323.6  250.96  4909.6   251.3  4980.2  253.05  4990.5  249.06
  5002.4  247.91  5005.2  247.41  5008.4  247.91  5011.3  251.82  5021.6  252.72
  5116.6  251.87    5504  261.41  5560.9  260.61  5721.7  264.36  6193.5  279.93
#Mann= 7 ,-1 , 0
  1964.3     .16       0  2799.1     .05       0  4909.6     .12       0
  5002.4     .07       0  5008.4     .12       0  5116.6     .05       0
    5504     .16       0
Bank Sta=4980.2,5021.6
XS Rating Curve= 0 ,0
Exp/Cntr=0.3,0.1

Type RM Length L Ch R = 1 ,94984   ,2277,2277,2277
BEGIN DESCRIPTION:
GIBBONS CREEK 75.0
END DESCRIPTION:
XS GIS Cut Line= 4
      3652767.53     10231230.67      3650770.96     10231213.31
      3649703.26     10230735.88      3648042.08     10231641.66
#Sta/Elev= 30
    2375  282.29  2640.4  271.01  2708.8  265.55  2739.5  264.24  2896.3   258.3
  2947.8  257.23  3200.5  254.66  3290.5  256.33  3390.5  253.91  3730.5  254.72
  4070.5  250.08  4110.5  251.88  4160.5   249.5  4300.5  252.79  4635.9  251.34
  4925.3  253.08  4991.8  247.15  4994.5  246.65  4997.8  247.15  5046.7  251.28
  5341.6  249.36    5649   252.4  6068.6  250.94  6188.2  257.19    6379  257.13
  6645.4  265.59  6820.5  267.74  7205.7  276.93  7234.6  277.84  7433.3  281.47
#Mann= 10 ,-1 , 0
    2375     .05       0  2708.8      .1       0  2739.5     .05       0
  2896.3      .1       0  2947.8     .05       0  4991.8     .03       0
  4997.8     .05       0  6645.4     .16       0  7205.7     .05       0
  7234.6     .16       0
Bank Sta=4925.3,5046.7
XS Rating Curve= 0 ,0
Exp/Cntr=0.3,0.1

Type RM Length L Ch R = 1 ,92707   ,1042,1042,1042
BEGIN DESCRIPTION:
GIBBONS CREEK 74.0
END DESCRIPTION:
XS GIS Cut Line= 3
      3651592.07     10229991.64      3650310.89      10230058.8
      3647392.12     10230791.64
#Sta/Elev= 30
    3043  275.41  3106.8  273.75  3205.8  269.55  3483.6  255.61  3643.8  251.33
  3753.9  252.98  3984.3  250.39  4044.3  252.26  4091.5  249.59  4224.6  250.14
  4244.6  246.98  4282.2  251.35  4582.4  250.59  4724.7  248.01  4963.9  248.44
  4981.6  246.85  4984.3  246.35  4987.6  246.85  5017.9  246.99  5059.1  251.02
  5223.7  251.81  5547.7   249.1    5830  252.18    5995  250.97  6335.2  265.12
  6453.1  265.47  6612.6  262.13  6675.5  263.74  6777.2  261.24  7335.3  276.49
#Mann= 5 ,-1 , 0
    3043     .16       0  3106.8      .1       0  3205.8     .05       0
  4981.6     .03       0  4987.6     .05       0
Bank Sta=4963.9,5059.1
XS Rating Curve= 0 ,0
Exp/Cntr=0.3,0.1

Type RM Length L Ch R = 1 ,91665   ,720,720,720
BEGIN DESCRIPTION:
GIBBONS CREEK 73.0
END DESCRIPTION:
XS GIS Cut Line= 3
      3651392.13     10229791.65      3649362.06     10229491.66
      3647442.07     10230291.66
#Sta/Elev= 30
  3332.1  274.43  3366.9  272.52  3544.4  257.27  3774.3  251.44  4241.9  248.87
  4282.3  250.37  4353.1  247.41  4390.5  249.85    4460  250.73    4626  250.07
  4636.1     247  5030.4     247  5040.5  249.09  5121.3  247.52  5192.1  250.73
  5343.7  249.33  5653.4  249.45  5708.9  246.91  5711.6  246.41  5714.9  246.91
  5730.3  246.94    5765  250.23  5995.7   248.2  6196.7  251.08  6348.3  251.23
  6433.4  253.78    6675  264.87    6728  264.12  6905.7  265.87  7464.2  273.29
#Mann= 3 ,-1 , 0
  3332.1     .05       0  5708.9     .03       0  5714.9     .05       0
Bank Sta=4626,5040.5
XS Rating Curve= 0 ,0
Exp/Cntr=0.3,0.1

Type RM Length L Ch R = 1 ,90945   ,671,671,671
BEGIN DESCRIPTION:
GIBBONS CREEK 71.0
END DESCRIPTION:
XS GIS Cut Line= 4
       3651692.1     10228841.64      3650224.09     10228774.08
      3649243.19     10229025.81      3647492.07     10230041.66
#Sta/Elev= 30
  3130.1  272.28  3214.1  269.62  3338.9  263.39  3720.7  253.88  4622.4  248.78
  4632.7     247  4746.7     247    5146     247  5248.9     247  5377.8     247
  5479.3     247  5489.6  250.19    5500  247.56  5551.5   247.2  5557.8  247.18
  5763.3  246.89  5811.6  246.81  5814.4  246.31  5817.6  246.81  5953.7  248.59
  6012.5     247  6028.3  248.82  6157.4  246.82  6318.8  249.75  6435.6   248.1
  6700.3  251.08    6906  262.45  7066.6   263.4  7511.3  277.15  7636.8  276.36
#Mann= 12 ,-1 , 0
  3130.1     .05       0  3214.1     .16       0  3338.9     .05       0
  4746.7     .12       0    5146      .1       0  5248.9     .05       0
  5377.8     .16       0  5551.5     .05       0  5557.8     .16       0
  5763.3     .05       0  5811.6     .07       0  5817.6     .05       0
Bank Sta=4622.4,5489.6
XS Rating Curve= 0 ,0
Exp/Cntr=0.3,0.1

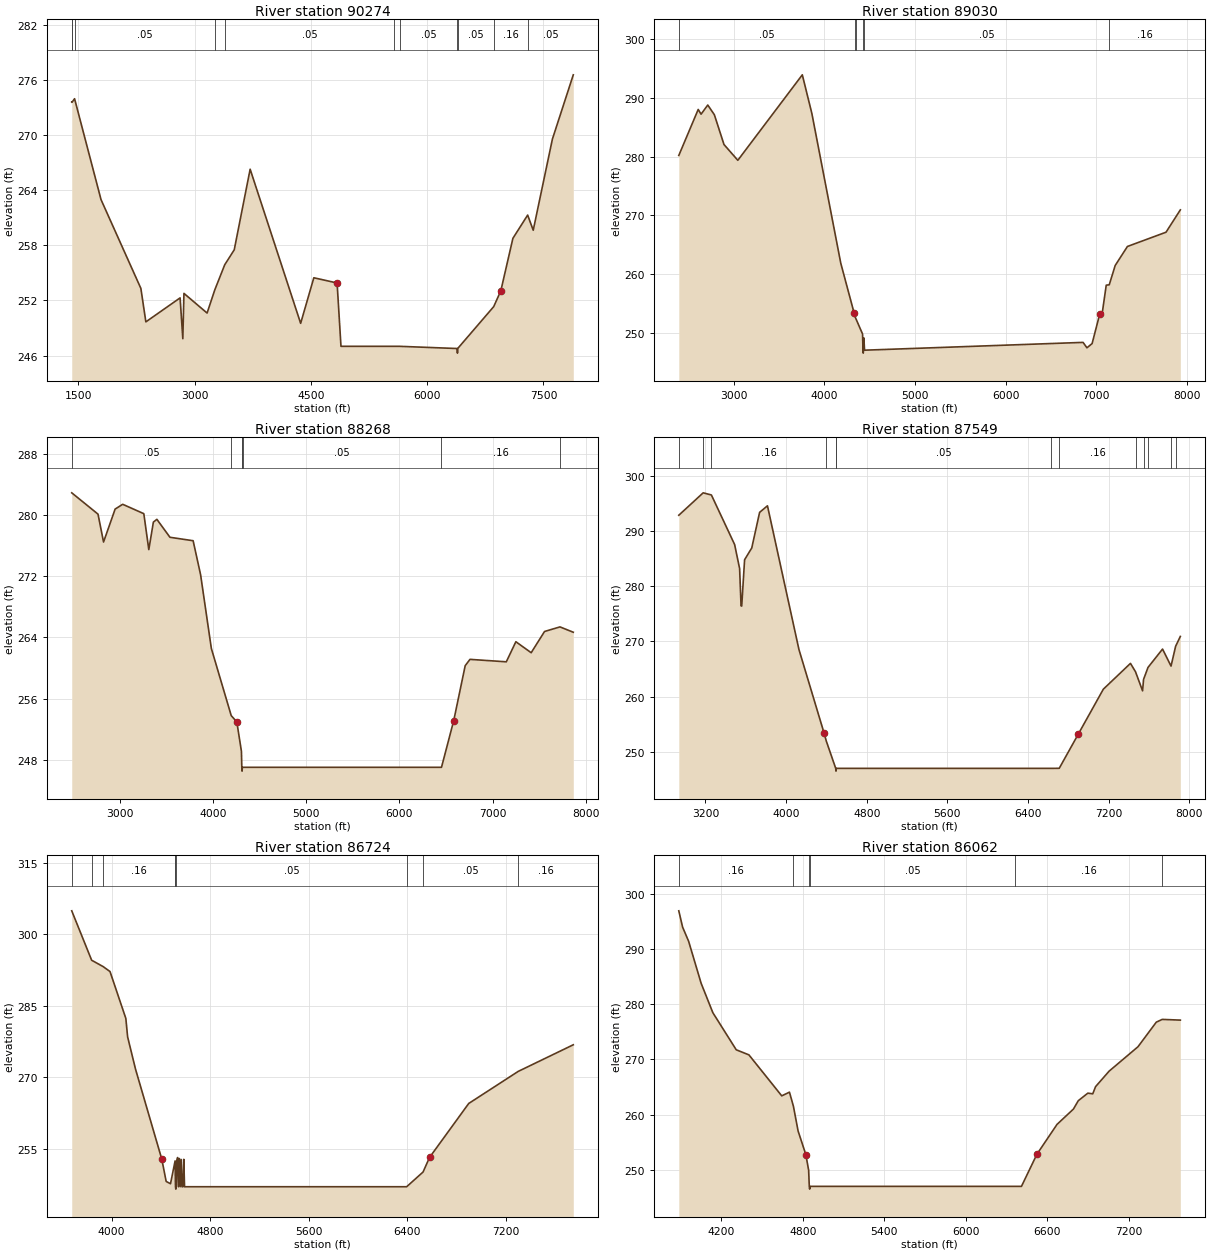
Type RM Length L Ch R = 1 ,90274   ,1244,1244,1244
BEGIN DESCRIPTION:
GIBBONS CREEK 70.0
END DESCRIPTION:
XS GIS Cut Line= 4
      3652767.48     10226786.24      3650953.26     10228201.16
      3649095.25     10228233.18      3647542.13     10229941.62
#Sta/Elev= 30
  1416.3  273.57  1418.7  273.54  1452.8  273.94  1794.1  262.96  2307.9   253.3
  2372.1  249.66  2813.6  252.27  2848.8  247.83  2863.3  252.76  3161.8  250.62
  3260.6  253.13    3389  255.87  3511.9   257.5    3717  266.27  4368.3   249.5
  4538.3  254.46  4838.4  253.89  4888.4     247    5577     247  5645.5     247
  6387.5  246.76  6390.3  246.26  6393.5  246.76  6858.1  251.32    6950  253.05
  7105.5  258.75  7295.8  261.28  7367.6  259.63    7615  269.55  7884.2  276.54
#Mann= 11 ,-1 , 0
  1416.3     .05       0  1418.7     .16       0  1452.8     .05       0
  3260.6     .16       0    3389     .05       0    5577     .12       0
  5645.5     .05       0  6387.5    .033       0  6393.5     .05       0
  6858.1     .16       0  7295.8     .05       0
Bank Sta=4838.4,6950
XS Rating Curve= 0 ,0
Exp/Cntr=0.3,0.1

Type RM Length L Ch R = 1 ,89030   ,762,762,762
BEGIN DESCRIPTION:
GIBBONS CREEK 69.0
END DESCRIPTION:
XS GIS Cut Line= 3
      3651465.44     10225761.91      3649998.39     10226248.04
      3647395.18     10229267.76
#Sta/Elev= 30
  2394.6  280.19  2608.8  288.04  2640.4  287.23  2714.2  288.79  2786.9  287.14
  2893.2  282.06  3045.7  279.37  3757.1  293.94  3862.4  287.36  4181.5  261.82
  4329.6  253.28  4336.6  252.79  4347.9  252.38  4421.8  249.75  4426.5     247
  4429.2   246.5  4432.5     247  4436.1  249.09  4443.7     247    6854  248.33
  6896.8  247.41  6953.8  248.13  7038.3  253.19  7060.3  252.76  7109.6  258.08
  7142.9  258.15  7208.4  261.44  7343.3  264.68    7769  267.11    7927  270.92
#Mann= 6 ,-1 , 0
  2394.6     .05       0  4336.6     .12       0  4347.9     .05       0
  4426.5    .033       0  4432.5     .05       0  7142.9     .16       0
Bank Sta=4329.6,7038.3
XS Rating Curve= 0 ,0
Exp/Cntr=0.3,0.1

Type RM Length L Ch R = 1 ,88268   ,719,719,719
BEGIN DESCRIPTION:
GIBBONS CREEK 68.0
END DESCRIPTION:
XS GIS Cut Line= 4
      3650883.84     10225188.99      3649694.57     10225857.41
      3647526.13     10227398.84      3647220.61     10228722.02
#Sta/Elev= 30
  2483.7  282.93  2765.7  280.14    2825  276.49  2949.3   280.8  3030.3  281.43
  3257.2   280.2  3310.8   275.5  3359.9   279.1  3397.5  279.46  3537.8  277.11
  3786.4  276.66  3866.6  272.21  3982.2  262.55  4195.5  253.76  4255.3  252.95
  4304.9  249.09  4308.8     247  4311.6   246.5  4314.8     247  4320.1     247
    6452     247  6583.1   253.1  6706.3   260.3  6757.6  261.13  7147.6  260.81
  7250.2  263.44  7414.4     262  7558.1  264.78  7723.4  265.38  7866.4  264.68
#Mann= 7 ,-1 , 0
  2483.7     .05       0  4195.5     .16       0  4308.8    .033       0
  4314.8     .16       0  4320.1     .05       0    6452     .16       0
  7723.4      .1       0
Bank Sta=4255.3,6583.1
XS Rating Curve= 0 ,0
Exp/Cntr=0.3,0.1

Type RM Length L Ch R = 1 ,87549   ,825,825,825
BEGIN DESCRIPTION:
GIBBONS CREEK 67.0
END DESCRIPTION:
XS GIS Cut Line= 3
      3649633.82     10224511.92      3648678.95     10225605.67
      3646126.96     10228036.14
#Sta/Elev= 30
  2935.5  292.83  3177.5  296.89    3259   296.5  3489.6  287.52  3538.9  283.18
  3553.2  276.44  3559.8  276.38  3588.3  284.77  3659.5  286.91  3737.3  293.35
  3815.2  294.54  4127.5  268.53  4375.2  253.49  4398.7  251.96  4492.4     247
  4495.1   246.5  4498.4     247    6633     247  6710.1  247.01  6900.3  253.24
  7147.8  261.34  7416.8  266.01  7466.9  264.49  7536.9  261.04  7546.8  263.11
    7591  265.28  7735.1   268.6  7819.4  265.52  7864.7   269.1  7911.6  270.89
#Mann= 13 ,-1 , 0
  2935.5      .1       0  3177.5     .05       0    3259     .16       0
  4398.7     .05       0  4492.4    .033       0  4498.4     .05       0
    6633      .1       0  6710.1     .16       0  7466.9      .1       0
  7546.8     .16       0    7591      .1       0  7819.4     .16       0
  7864.7      .1       0
Bank Sta=4375.2,6900.3
XS Rating Curve= 0 ,0
Exp/Cntr=0.3,0.1

Type RM Length L Ch R = 1 ,86724   ,662,662,662
BEGIN DESCRIPTION:
GIBBONS CREEK 65.0
END DESCRIPTION:
XS GIS Cut Line= 3
      3648652.92     10224616.08       3647854.3     10225241.09
      3645701.53     10227411.22
#Sta/Elev= 30
  3676.4  304.88  3837.9  294.52  3931.3  293.18  3987.1  292.14  4115.5  282.31
  4129.9  278.44  4194.1  271.67  4407.5  252.77  4442.8  248.11  4478.1  247.63
  4515.4  252.42  4518.5     247  4521.2   246.5  4524.5     247  4528.2  252.34
  4535.9  253.13  4542.3     247  4550.4  252.92  4556.7     247  4564.8  252.72
  4571.2     247    4579     247  4585.7  252.76    4592     247  6394.7     247
    6528  250.09  6580.4  253.14  6898.7  264.47  7299.9  271.19  7747.3  276.78
#Mann= 9 ,-1 , 0
  3676.4     .16       0  3837.9     .05       0  3931.3     .16       0
  4515.4     .05       0  4518.5    .033       0  4524.5     .05       0
  6394.7      .1       0    6528     .05       0  7299.9     .16       0
Bank Sta=4407.5,6580.4
XS Rating Curve= 0 ,0
Exp/Cntr=0.3,0.1

Type RM Length L Ch R = 1 ,86062   ,773,773,773
BEGIN DESCRIPTION:
GIBBONS CREEK 64.0
END DESCRIPTION:
XS GIS Cut Line= 3
      3647842.08     10224141.68      3647515.76     10224598.73
      3645442.08     10226941.67
#Sta/Elev= 30
  3887.6  296.87  3915.8  293.91  3960.1  291.35  4052.2  283.74  4138.3  278.43
  4310.3  271.72  4403.6   270.8    4645  263.38  4701.9  264.05  4730.8  261.52
  4765.5  257.02  4822.3  252.76  4843.2   249.9  4847.8     247  4850.5   246.5
  4853.8     247  6361.3     247    6409     247  6522.8  252.82  6670.8  258.22
  6791.3  260.99  6827.3  262.51  6897.5  263.87  6933.5  263.75  6954.4  265.05
  7053.9  267.85  7266.4  272.27  7401.1  276.72  7444.7  277.22    7578  277.09
#Mann= 6 ,-1 , 0
  3887.6     .16       0  4730.8     .05       0  4847.8    .033       0
  4853.8     .05       0  6361.3     .16       0  7444.7      .1       0
Bank Sta=4822.3,6522.8
XS Rating Curve= 0 ,0
Exp/Cntr=0.3,0.1

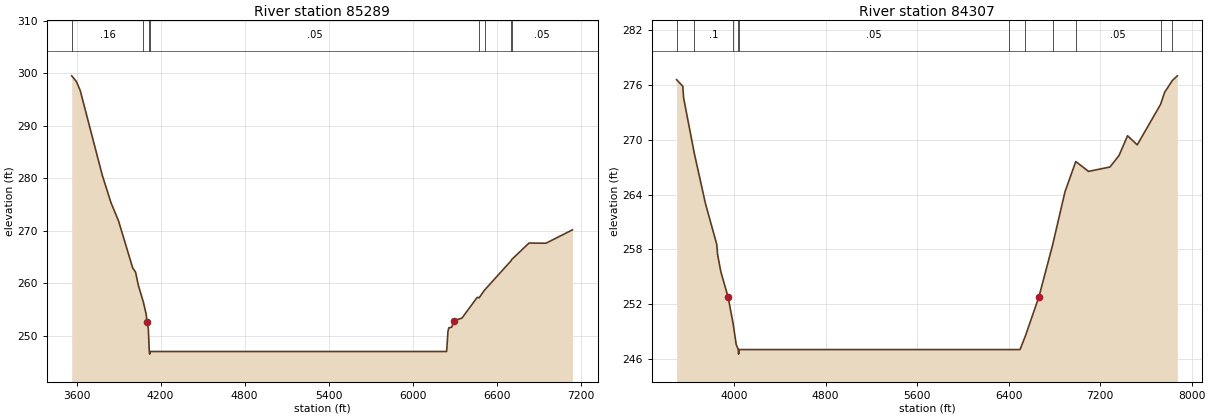
Type RM Length L Ch R = 1 ,85289   ,982,982,982
BEGIN DESCRIPTION:
GIBBONS CREEK 62.0
END DESCRIPTION:
XS GIS Cut Line= 3
       3647792.1     10223941.64       3646831.6     10224096.56
      3645432.44     10226291.42
#Sta/Elev= 30
  3565.3  299.52  3598.7  298.44  3626.1  296.73  3784.1  280.54  3845.9  275.34
  3899.6  271.89  4000.8  262.93  4021.1  262.14  4041.4  259.59  4076.5  256.47
  4097.1   254.1  4103.2  252.63  4112.3  251.41  4119.4     247  4122.1   246.5
  4125.4     247  6242.7     247  6251.9  250.79    6258   251.5  6279.1  251.63
  6294.4  252.89  6351.9  253.36  6461.1  257.32  6474.7  257.23    6513  258.69
  6702.1  264.27  6708.7  264.56  6830.9  267.66    6952  267.63  7141.1  270.18
#Mann= 8 ,-1 , 0
  3565.3     .16       0  4076.5     .05       0  4119.4    .033       0
  4125.4     .05       0  6474.7      .1       0    6513     .05       0
  6702.1      .1       0  6708.7     .05       0
Bank Sta=4103.2,6294.4
XS Rating Curve= 0 ,0
Exp/Cntr=0.3,0.1

Type RM Length L Ch R = 1 ,84307   ,1289,1289,1289
BEGIN DESCRIPTION:
GIBBONS CREEK 60.0
END DESCRIPTION:
XS GIS Cut Line= 3
       3646951.5     10222784.51      3645553.95     10224112.62
      3645242.11     10226541.63
#Sta/Elev= 30
  3498.3   276.6  3552.6  275.87  3559.5  274.61  3653.3  268.51  3750.4  263.02
  3849.5  258.53  3856.4  257.45  3884.7  255.55  3948.6  252.75  3991.9  249.88
  4019.4  247.55  4037.4     247  4040.2   246.5  4043.4     247  6404.8     247
    6500     247  6546.2  248.47  6665.4  252.79  6784.9  258.47  6892.9   264.3
  6987.4  267.62  7098.9  266.54  7285.8  267.02  7365.4  268.28    7440  270.45
  7524.6  269.45    7729   273.9  7764.3  275.22  7831.6  276.51  7875.2  277.02
#Mann= 11 ,-1 , 0
  3498.3     .16       0  3653.3      .1       0  3991.9     .05       0
  4037.4    .033       0  4043.4     .05       0  6404.8      .1       0
  6546.2     .05       0  6784.9     .16       0  6987.4     .05       0
    7729      .1       0  7831.6     .05       0
Bank Sta=3948.6,6665.4
XS Rating Curve= 0 ,0
Exp/Cntr=0.3,0.1