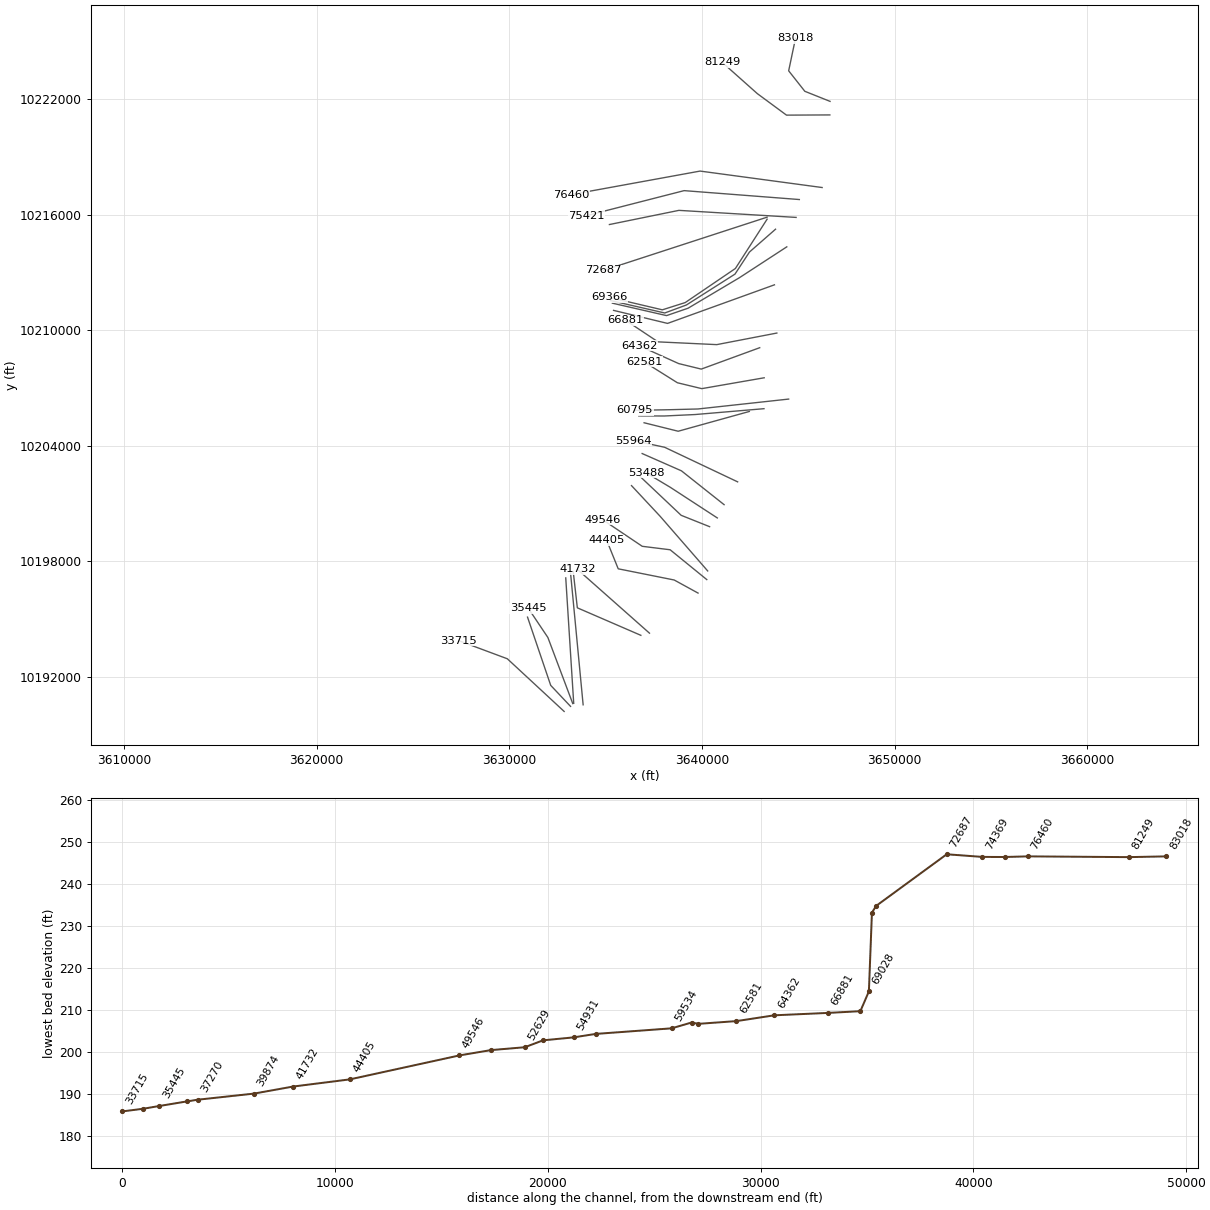
HEC-RAS study GIBBONS CREEK.prj: GIBBONS CREEK Base Level Engineering

--- GIBBONS CREEK.g01 (geometry) --- (continued)

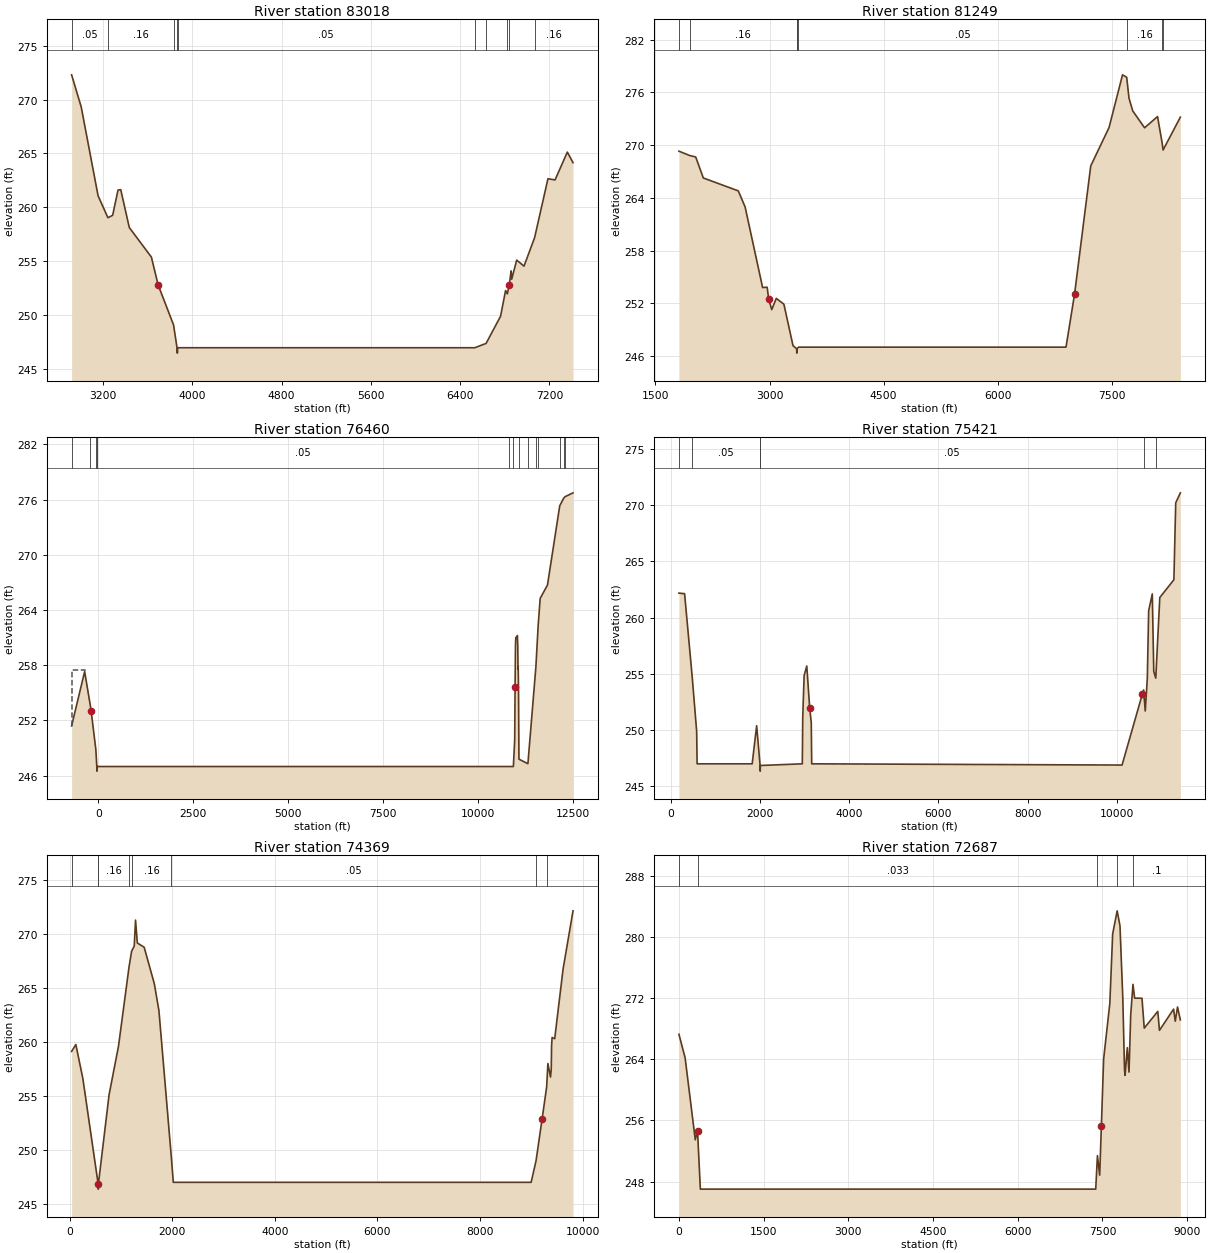
Type RM Length L Ch R = 1 ,83018   ,1769,1769,1769
BEGIN DESCRIPTION:
GIBBONS CREEK 58.0
END DESCRIPTION:
XS GIS Cut Line= 4
      3646642.13     10221891.63       3645333.3     10222415.16
      3644494.92     10223478.94      3644850.82     10225171.64
#Sta/Elev= 30
  2917.9  272.29  3004.1  269.31  3154.9  261.09  3243.3  259.05  3285.5  259.27
  3333.9  261.61  3358.2  261.65  3434.9  258.14  3632.8   255.4  3693.4  252.82
  3831.6  249.11  3862.7     247  3865.5   246.5  3868.7     247  6531.4     247
  6632.6   247.4  6762.3  249.92  6807.1   252.3  6822.7  251.99  6835.1  252.56
  6839.5  252.77  6856.9  254.12    6862  253.35  6906.8  255.12  6972.3  254.56
  7067.3   257.2  7186.9  262.66  7250.6  262.55  7360.6  265.13  7411.7  264.15
#Mann= 10 ,-1 , 0
  2917.9     .05       0  3243.3     .16       0  3831.6     .05       0
  3862.7    .033       0  3868.7     .05       0  6531.4     .16       0
  6632.6     .05       0  6822.7     .16       0  6835.1     .05       0
  7067.3     .16       0
Bank Sta=3693.4,6839.5
XS Rating Curve= 0 ,0
Exp/Cntr=0.3,0.1

Type RM Length L Ch R = 1 ,81249   ,4761,4761,4761
BEGIN DESCRIPTION:
GIBBONS CREEK 57.0
END DESCRIPTION:
XS GIS Cut Line= 4
      3646632.92      10221187.1      3644382.07     10221176.42
      3642867.41     10222294.68      3641029.22     10223932.49
#Sta/Elev= 30
  1808.3  269.31  1948.6  268.82  2029.1  268.65  2129.1  266.26  2589.1  264.79
  2679.1  262.96  2909.1  253.79  2969.1  253.82  2989.1  252.49  3029.1  251.27
  3089.1  252.55  3189.1  251.89  3309.1  247.17  3356.1  246.82  3358.9  246.32
  3362.1  246.82  3380.8     247    6900     247    7013  253.06  7225.3  267.63
  7466.1     272  7643.4     278  7698.4  277.72  7728.7  275.33    7778  273.89
  7933.5  271.97  8104.1  273.25  8164.9  270.22    8177  269.44  8403.9  273.18
#Mann= 8 ,-1 , 0
  1808.3     .05       0  1948.6     .16       0  3356.1    .033       0
  3362.1     .16       0  3380.8     .05       0  7698.4     .16       0
  8164.9     .05       0    8177     .16       0
Bank Sta=2989.1,7013
XS Rating Curve= 0 ,0
Exp/Cntr=0.3,0.1

Type RM Length L Ch R = 1 ,76460   ,1067,1067,1067
BEGIN DESCRIPTION:
GIBBONS CREEK 55.0
END DESCRIPTION:
XS GIS Cut Line= 3
      3646232.05     10217414.62      3639898.75     10218269.28
      3633201.43     10217046.72
#Sta/Elev= 30
  -705.8  251.41  -362.8  257.31  -214.8  253.67  -191.2  253.02     -67  248.81
   -42.9     247   -40.1   246.5   -36.9     247 10817.1     247 10922.4     247
 10957.3  249.86 10967.4  255.64 10977.6  260.13 10986.2  260.98 11028.4  261.23
 11038.6  260.02 11044.6   257.6 11049.6  257.85 11058.9   254.8 11066.3  249.72
 11069.1   247.8   11305  247.31   11515  257.81 11575.5  262.36 11628.2  265.26
 11820.6  266.72 12143.3  275.33 12245.6  276.13 12279.1   276.3 12492.9  276.73
#Mann= 14 ,-1 , 0
  -705.8     .05       0  -214.8     .16       0     -67     .05       0
   -42.9    .033       0   -36.9     .05       0 10817.1     .07       0
 10922.4     .15       0 11066.3     .05       0   11305     .16       0
   11515     .05       0 11575.5     .16       0 12143.3      .1       0
 12245.6     .16       0 12279.1      .1       0
#XS Ineff= 1 ,-1
 -736.36 -354.55  257.44
Permanent Ineff=
       F
Bank Sta=-191.2,10967.4
XS Rating Curve= 0 ,0
Exp/Cntr=0.3,0.1

Type RM Length L Ch R = 1 ,75421   ,1052,1052,1052
BEGIN DESCRIPTION:
GIBBONS CREEK 52.0
END DESCRIPTION:
XS GIS Cut Line= 3
      3645048.68     10216790.57      3639069.81     10217253.13
      3633995.29     10215951.25
#Sta/Elev= 30
   188.5  262.18   315.5  262.13   487.3  254.68   586.3  249.88   596.3     247
    1830     247  1930.3  250.39  2007.5  246.85  2010.3  246.35  2013.5  246.85
  2953.3     247  2963.3  251.17  2994.1  254.84  3053.6   255.7  3119.1  251.95
  3153.9  250.67  3163.9     247 10118.1  246.89 10570.5  253.17 10601.4  253.57
 10637.7   251.7 10684.1  254.58 10714.1  260.61 10795.6  262.11 10828.6  255.22
 10873.4  254.62 10963.9  261.79 11279.7  263.37 11320.5  270.21 11424.1   271.1
#Mann= 6 ,-1 , 0
   188.5     .16       0   487.3     .05       0  2007.5    .033       0
  2013.5     .05       0 10601.4      .1       0 10873.4     .08       0
Bank Sta=3119.1,10570.5
XS Rating Curve= 0 ,0
Exp/Cntr=0.3,0.1

Type RM Length L Ch R = 1 ,74369   ,1682,1682,1682
BEGIN DESCRIPTION:
GIBBONS CREEK 50.0
END DESCRIPTION:
XS GIS Cut Line= 3
      3644880.92     10215861.75      3638798.65     10216228.07
      3635192.06     10215491.63
#Sta/Elev= 30
    40.2  259.12   122.9  259.76   259.4  256.61     557  246.87   559.7  246.37
     563  246.87   770.3   255.1   954.5  259.61  1158.4   266.9  1209.8   268.4
  1261.2  268.88  1286.1  271.28  1321.3  269.16  1454.4  268.77  1651.9   265.4
  1742.1  262.91  1986.6  249.19  2022.6     247  8997.9     247  9093.5     249
  9212.3  252.89  9300.1  255.83  9324.5     258  9375.6  256.75  9390.2   257.5
    9396  259.63  9406.2  260.41  9457.2   260.3  9620.5  266.75  9814.5  272.14
#Mann= 8 ,-1 , 0
    40.2     .16       0     557    .033       0     563     .16       0
  1158.4      .1       0  1209.8     .16       0  1986.6     .05       0
  9093.5     .16       0  9300.1     .05       0
Bank Sta=557,9212.3
XS Rating Curve= 0 ,0
Exp/Cntr=0.3,0.1

Type RM Length L Ch R = 1 ,72687   ,3321,3321,3321
XS GIS Cut Line= 2
     3643376.273    10215874.474     3634876.273    10213103.641
#Sta/Elev= 30
       0  267.31  109.88  264.22  289.68  253.47  329.64  254.64  379.58     247
 7381.86     247 7411.82  251.38 7451.78  248.83 7481.75  255.29  7521.7  264.06
 7631.58  271.36 7681.53  280.46 7761.44  283.49 7811.38  281.52 7861.33  272.01
  7891.3  262.67 7901.28  261.92 7941.24  265.55 7971.21  262.35 8001.17  269.83
 8041.13  273.85  8071.1  272.04 8200.95  272.03 8240.91  268.11 8480.65   270.3
 8510.61  267.82 8760.34   270.6  8790.3  269.02 8830.26  270.88  8880.2  269.19
#Mann= 5 ,-1 , 0
       0     .16       0  329.64    .033       0 7411.82     .08       0
 7761.44     .05       0 8041.13      .1       0
Bank Sta=329.64,7481.75
XS Rating Curve= 0 ,0
Exp/Cntr=0.3,0.1

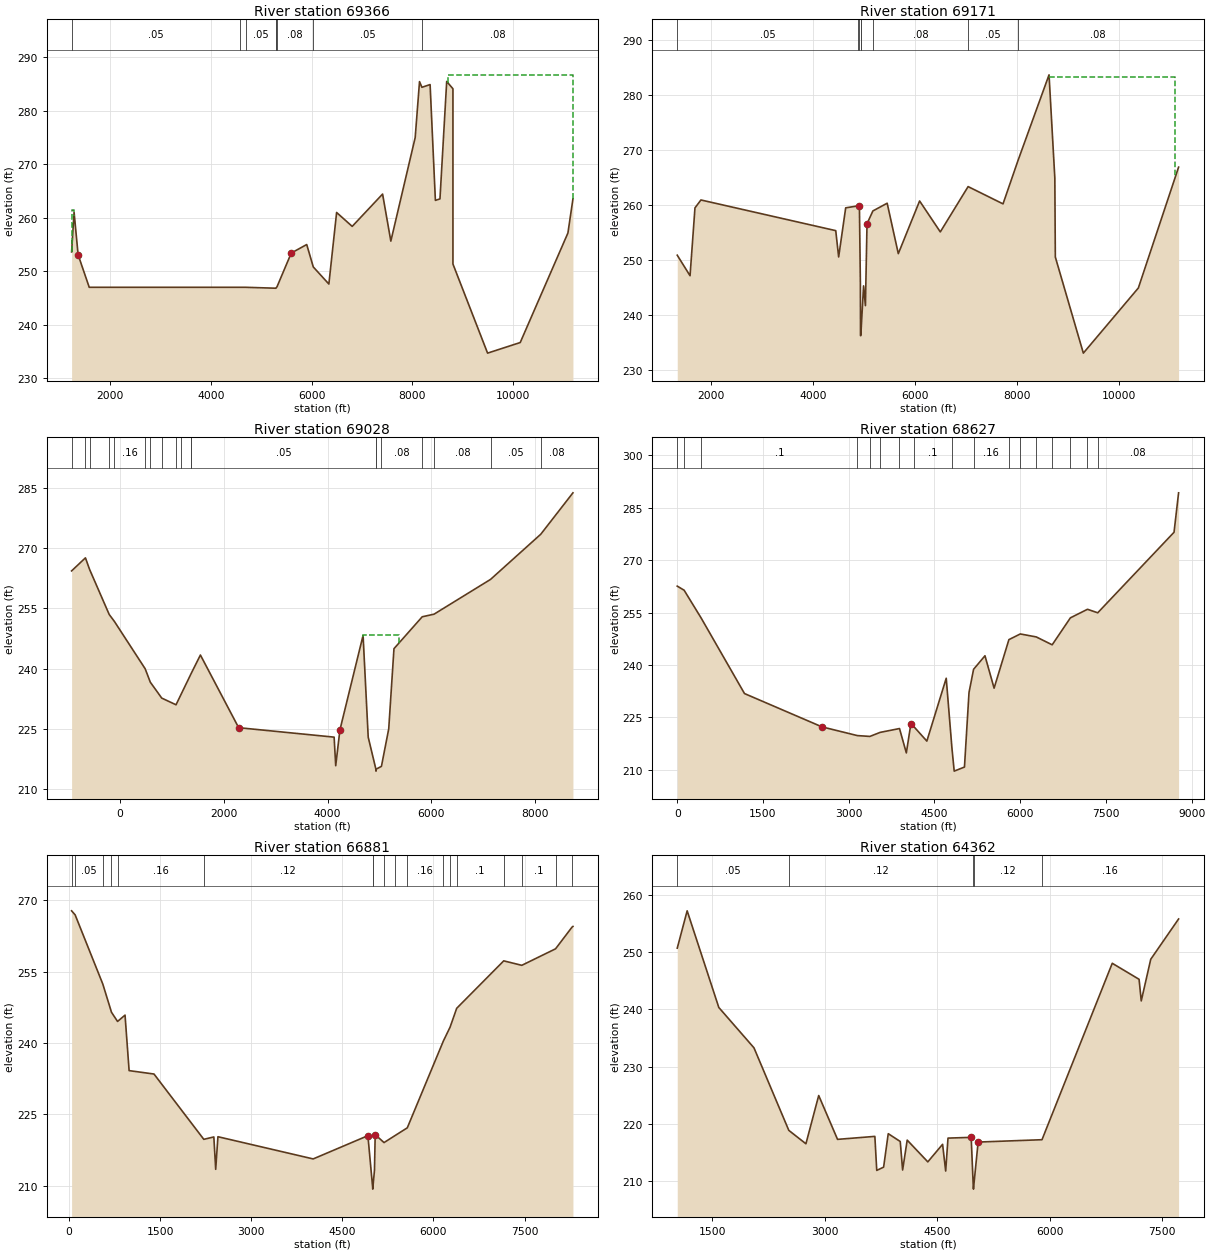
Type RM Length L Ch R = 1 ,69366   ,195,195,195
BEGIN DESCRIPTION:
GIBBONS CREEK 46.1
END DESCRIPTION:
XS GIS Cut Line= 5
     3643376.273    10215770.308      3641730.44    10213207.808
     3639126.273    10211436.974     3637938.773    10211059.646
     3635188.773    10211707.808
#Sta/Elev= 30
  1233.9  253.61    1283  261.02  1363.3  253.07  1584.1     247  4583.9     247
  4691.6     247  5287.2  246.83  5293.2  246.83  5314.7  247.11  5597.3   253.4
  5904.4  254.99  6034.9   250.8  6344.3  247.61  6498.2  260.98  6807.9  258.38
  7411.4  264.42  7575.6  255.63  8059.3  274.99    8145  285.43  8192.9  284.37
  8355.3  284.88  8460.4  263.24  8551.3  263.52    8685  285.46    8809   284.1
    8809251.35539497.212234.700510145.53236.678911093.06257.142411192.81263.5099
#Mann= 8 ,-1 , 0
  1233.9     .05       0  4583.9     .08       0  4691.6     .05       0
  5287.2    .033       0  5293.2     .05       0  5314.7     .08       0
  6034.9     .05       0  8192.9     .08       0
#XS Ineff= 2 ,-1
  1187.5 1289.77  261.46 8713.6411222.73   286.7
Permanent Ineff=
       F       F
Bank Sta=1363.3,5597.3
XS Rating Curve= 0 ,0
Exp/Cntr=0.3,0.1

Type RM Length L Ch R = 1 ,69171   ,143,143,143
BEGIN DESCRIPTION:
GIBBONS CREEK 46.0
END DESCRIPTION:
XS GIS Cut Line= 6
     3643813.773    10215249.474     3642459.606    10214061.974
     3641709.606    10212916.141     3639188.773    10211311.974
     3638063.773    10210895.308     3635251.273    10211541.141
#Sta/Elev= 30
    1334  250.89  1585.1  247.16  1681.6  259.48  1798.8  260.92  4444.9  255.35
    4502  250.57  4640.1  259.49  4889.3  259.86  4894.8  259.86  4909.4  259.87
  4928.5  245.65  4930.8  236.28  4936.8  236.28    4991  245.32  5027.5  241.73
  5058.8   256.6  5174.1  258.93  5454.3  260.33    5673  251.17    6091  260.74
  6497.3  255.12  7043.1  263.35  7728.5  260.21  8017.6  267.96  8631.4  283.65
  8745.1  264.928754.998250.55369304.877233.103910384.64244.935611174.46266.8802
#Mann= 8 ,-1 , 0
    1334     .05       0  4889.3     .08       0  4894.8     .05       0
  4930.8    .033       0  4936.8     .05       0  5174.1     .08       0
  7043.1     .05       0  8017.6     .08       0
#XS Ineff= 1 ,-1
 8631.8211113.64  283.24
Permanent Ineff=
       F
Bank Sta=4909.4,5058.8
XS Rating Curve= 0 ,0
Exp/Cntr=0.3,0.1

Type RM Length L Ch R = 1 ,69028   ,401,401,401
BEGIN DESCRIPTION:
GIBBONS CREEK 45.0
END DESCRIPTION:
XS GIS Cut Line= 5
     3644397.106    10214332.808     3641938.773    10212728.641
      3639276.83      10211144.7      3638157.08     10210759.65
      3635345.81     10211405.21
#Sta/Elev= 30
  -935.4  264.38  -668.8  267.64    -590  264.79  -210.8   253.5  -111.7  251.78
   482.9  239.93     582  236.58   802.4  232.61  1077.5  230.94  1176.6  233.59
  1372.7  238.84  1374.8   238.9  1547.6  243.37  2285.1  225.22  4125.3  222.86
    4156  215.72  4236.8  224.65  4683.6  248.27  4782.6  222.85  4930.5  214.87
  4933.2  214.37  4936.5  214.87  5037.4  215.56  5178.1  224.93  5279.1  244.95
  5823.5  252.92  6051.8  253.57  7141.4  262.26  8109.2  273.54  8729.3  283.88
#Mann= 19 ,-1 , 0
  -935.4      .1       0  -668.8     .16       0    -590      .1       0
  -210.8     .05       0  -111.7     .16       0   482.9     .05       0
     582     .12       0   802.4     .16       0  1077.5     .12       0
  1176.6     .05       0  1372.7      .1       0  1374.8     .05       0
  4930.5    .033       0  4936.5     .05       0  5037.4     .08       0
  5823.5     .05       0  6051.8     .08       0  7141.4     .05       0
  8109.2     .08       0
#XS Ineff= 1 ,-1
    4675 5370.45  248.45
Permanent Ineff=
       F
Bank Sta=2285.1,4236.8
XS Rating Curve= 0 ,0
Exp/Cntr=0.3,0.1

Type RM Length L Ch R = 1 ,68627   ,1526,1526,1526
XS GIS Cut Line= 3
        3643757.       10212359.        3638210.       10210354.
        3635407.       10211031.
#Sta/Elev= 30
       0262.5681119.6312261.4146418.7093253.43581176.374231.84062532.195222.3096
3150.289219.81723369.613219.5758 3549.06220.73193888.015221.83114007.646214.8618
4087.401223.22074147.216222.2393 4366.54218.23994705.495236.22124805.188216.2911
4845.065209.64955024.512210.81555104.266232.1498 5184.02238.77575383.406242.6532
5542.914233.38325802.115247.26676001.407248.8925 6280.33 248.0436559.252245.7866
6878.021253.50447176.866255.94987356.173254.94858691.016277.98498770.708289.2666
#Mann= 17 ,-1 , 0
       0      .1       0119.6312     .05       0418.7093      .1       0
3150.289     .05       03369.613     .16       0 3549.06     .12       0
3888.015     .07       04147.216      .1       04805.188     .05       0
 5184.02     .16       05802.115      .1       06001.407     .16       0
 6280.33      .1       06559.252     .16       06878.021      .1       0
7176.866     .16       07356.173     .08       0
#XS Ineff= 1 ,-1
 4704.55 5363.64  236.17
Permanent Ineff=
       F
Bank Sta=2532.195,4087.401
XS Rating Curve= 0 ,0
Exp/Cntr=0.3,0.1

Type RM Length L Ch R = 1 ,66881   ,2519,2519,2519
BEGIN DESCRIPTION:
GIBBONS CREEK 44.0
END DESCRIPTION:
XS GIS Cut Line= 4
      3643881.97     10209853.07      3640762.18      10209251.5
      3637715.32     10209394.74      3636027.82     10210519.73
#Sta/Elev= 30
    41.1  267.76    99.2  266.91   555.2  252.35   697.9  246.43   797.7   244.5
     921  245.83   988.1  234.16    1398  233.44    2218  219.71  2383.3  220.21
  2413.9   213.4  2450.6  220.26  4019.3  215.59  4920.3  220.48  4997.4  209.74
  5000.1  209.24  5003.4  209.74  5028.5  213.21  5040.4   220.7  5185.9  219.03
  5370.9  220.53  5568.9  222.13  6162.9  240.38  6273.5   243.3  6382.2  247.26
    7157  257.24  7454.3   256.3  8010.4  259.77  8281.6  264.33  8296.7  264.47
#Mann= 18 ,-1 , 0
    41.1      .1       0    99.2     .05       0   555.2      .1       0
   697.9     .05       0   797.7     .16       0    2218     .12       0
  4997.4     .07       0  5003.4     .12       0  5185.9      .1       0
  5370.9     .05       0  5568.9     .16       0  6162.9      .1       0
  6273.5     .16       0  6382.2      .1       0    7157     .16       0
  7454.3      .1       0  8010.4     .16       0  8281.6     .08       0
Bank Sta=4920.3,5040.4
XS Rating Curve= 0 ,0
Exp/Cntr=0.3,0.1

Type RM Length L Ch R = 1 ,64362   ,1781,1781,1781
BEGIN DESCRIPTION:
GIBBONS CREEK 42.0
END DESCRIPTION:
XS GIS Cut Line= 4
      3642992.09     10209091.64      3639958.51     10207980.15
      3638786.63     10208266.61      3636742.33     10209191.11
#Sta/Elev= 30
  1036.5  250.66  1168.4  257.16  1590.3  240.32  2058.9  233.29  2522.9  218.91
  2751.1  216.57  2921.5  224.98  3172.4  217.34  3669.7  217.86  3694.9  211.93
  3786.4   212.5  3848.1  218.33  4007.9  216.97  4039.7     212  4100.7  217.21
  4375.3  213.42  4572.4  216.48  4613.6  211.82  4644.5  217.56  4953.3  217.69
  4981.2  209.17  4983.9  208.67  4987.2  209.17    5046  216.87    5897  217.28
  6833.4  248.02  7190.7  245.23  7219.6  241.46  7346.2  248.72  7717.3  255.74
#Mann= 5 ,-1 , 0
  1036.5     .05       0  2522.9     .12       0  4981.2     .07       0
  4987.2     .12       0    5897     .16       0
Bank Sta=4953.3,5046
XS Rating Curve= 0 ,0
Exp/Cntr=0.3,0.1

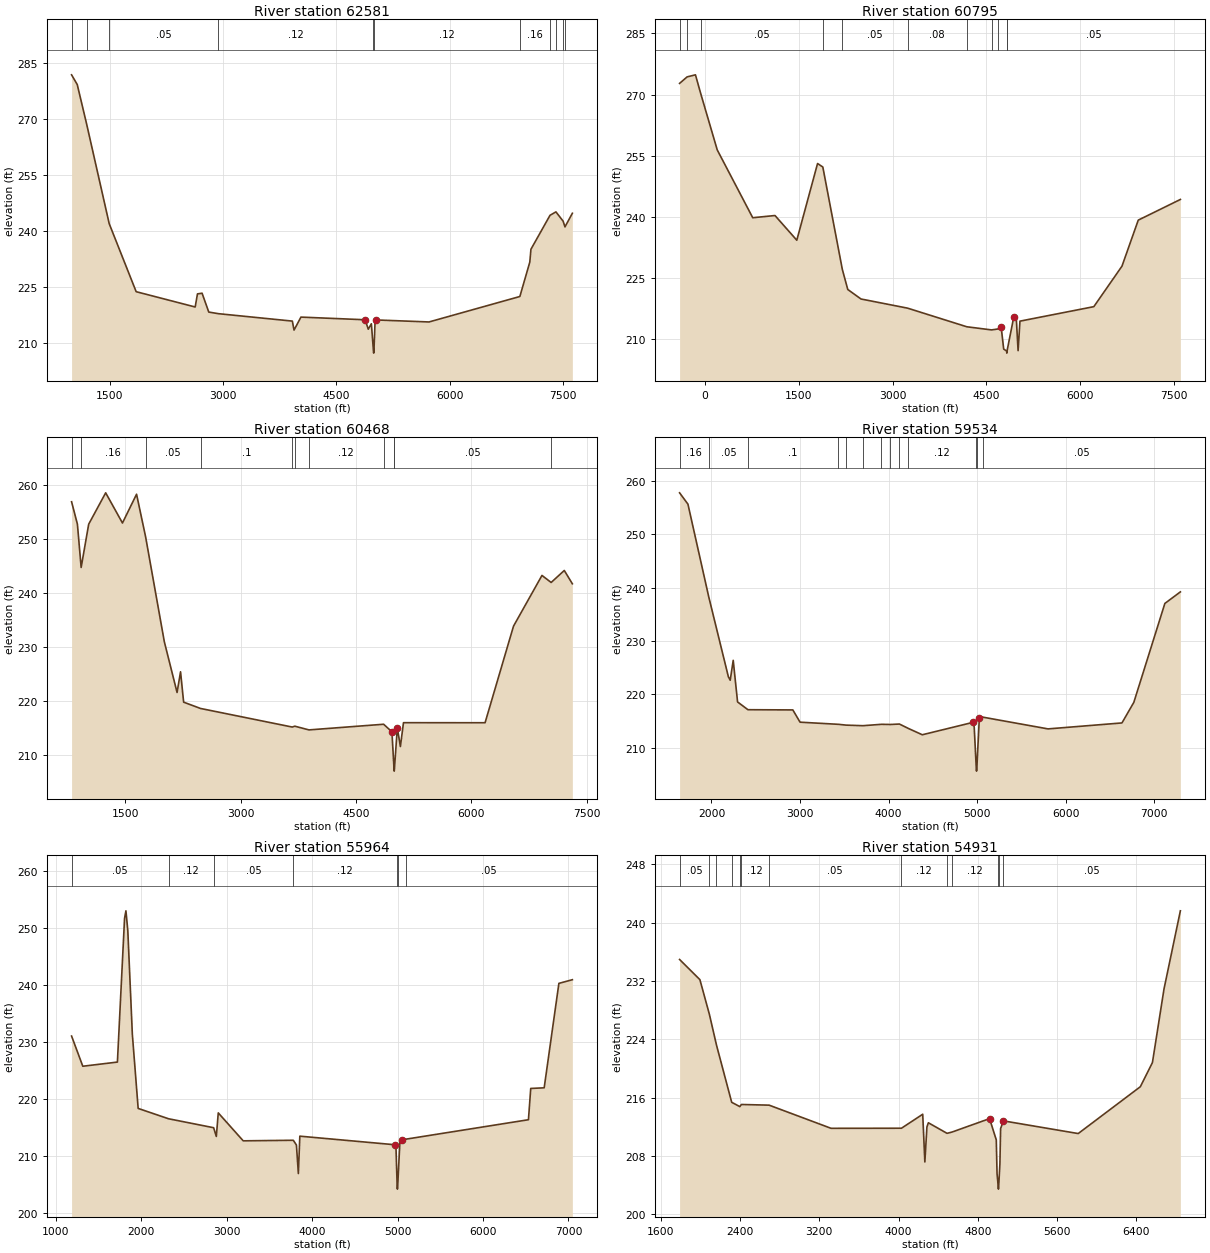
Type RM Length L Ch R = 1 ,62581   ,1786,1786,1786
BEGIN DESCRIPTION:
GIBBONS CREEK 41.0
END DESCRIPTION:
XS GIS Cut Line= 4
      3643224.78     10207528.86      3639984.55     10206964.53
      3638721.31     10207269.96      3636990.64      10208357.2
#Sta/Elev= 30
   993.8  281.85  1068.8  279.25  1193.4  268.65    1492  241.98  1849.2  223.75
  2630.8  219.65  2661.2  223.16  2722.1  223.34  2810.9  218.29  2937.4  217.86
  3917.8  215.87  3940.2  213.46  4031.5  216.94    4882  216.23  4923.2   213.7
  4964.3  215.15  4992.2  207.79    4995  207.29  4998.2  207.79  5012.9  215.55
  5026.1  216.18  5727.9  215.64  6930.9  222.46  7062.5  231.66  7077.8  235.12
  7330.6  244.22  7408.9  245.13  7504.5  242.63  7528.4  241.11  7626.3  244.76
#Mann= 11 ,-1 , 0
   993.8     .05       0  1193.4     .16       0    1492     .05       0
  2937.4     .12       0  4992.2     .07       0  4998.2     .12       0
  6930.9     .16       0  7330.6      .1       0  7408.9     .16       0
  7504.5      .1       0  7528.4     .16       0
Bank Sta=4882,5026.1
XS Rating Curve= 0 ,0
Exp/Cntr=0.3,0.1

Type RM Length L Ch R = 1 ,60795   ,327,327,327
BEGIN DESCRIPTION:
GIBBONS CREEK 39.0
END DESCRIPTION:
XS GIS Cut Line= 4
      3644494.29     10206422.09      3639785.62     10205907.67
      3638350.52     10205870.55      3636519.01     10205836.15
#Sta/Elev= 30
  -405.3  272.76  -285.6  274.35  -151.6  274.86   -66.3   270.2   196.4  256.46
   763.8  239.83  1119.5  240.37    1468  234.32  1799.9  253.12    1884  252.26
  2195.8  227.16  2282.8  222.24    2494  219.91    3240  217.66  4185.5   213.1
  4580.5  212.33  4679.1  212.55    4735  212.96    4775  207.63  4822.1  207.14
  4824.8  206.64  4828.1  207.14  4935.1  215.43  4975.1  215.46  5005.1  207.24
  5035.1  214.48  6215.5  218.03  6665.5  227.96  6925.6  239.24  7598.8  244.31
#Mann= 11 ,-1 , 0
  -405.3     .05       0  -285.6     .16       0   -66.3     .05       0
    1884     .16       0  2195.8     .05       0    3240     .08       0
  4185.5     .05       0  4580.5     .08       0  4679.1     .05       0
  4822.1     .04       0  4828.1     .05       0
Bank Sta=4735,4935.1
XS Rating Curve= 0 ,0
Exp/Cntr=0.3,0.1

Type RM Length L Ch R = 1 ,60468   ,934,934,934
BEGIN DESCRIPTION:
GIBBONS CREEK 38.0
END DESCRIPTION:
XS GIS Cut Line= 4
      3643213.94     10205922.96      3639644.04     10205619.14
      3638038.14     10205543.18      3636717.05     10205547.81
#Sta/Elev= 30
   801.7  256.94   877.5  252.79   926.2  244.75  1024.3  252.78  1245.1   258.6
  1463.4     253  1646.6  258.34  1763.7  250.48  2007.9  230.95  2173.4  221.55
  2218.6  225.39  2258.8  219.75  2478.4  218.58  3670.8  215.13  3704.2  215.29
  3888.5   214.6  4859.2  215.65  4967.1  214.25  4994.1  207.45  4996.9  206.95
  5000.1  207.45  5037.2  214.98  5077.3  211.51  5117.3  215.94  6178.2  215.93
  6548.2  233.86  6918.2  243.27  7037.5  241.96  7208.2  244.19  7313.3  241.72
#Mann= 11 ,-1 , 0
   801.7     .05       0   926.2     .16       0  1763.7     .05       0
  2478.4      .1       0  3670.8     .12       0  3704.2      .1       0
  3888.5     .12       0  4859.2     .05       0  4994.1     .03       0
  5000.1     .05       0  7037.5     .08       0
Bank Sta=4967.1,5037.2
XS Rating Curve= 0 ,0
Exp/Cntr=0.3,0.1

Type RM Length L Ch R = 1 ,59534   ,3570,3570,3570
BEGIN DESCRIPTION:
GIBBONS CREEK 37.0
END DESCRIPTION:
XS GIS Cut Line= 3
      3642452.84     10205778.32      3638760.59     10204750.99
      3636992.07     10205191.65
#Sta/Elev= 30
  1640.2  257.77  1734.4  255.65    1969  238.29  2191.1  223.27  2211.9  222.62
  2245.8  226.35  2294.9  218.55  2412.1  217.09  2918.9  217.05  3000.7  214.75
  3433.3  214.35  3520.3   214.2  3710.3  214.09  3920.2  214.35  4021.5  214.32
  4122.9   214.4  4224.3  213.57  4381.2  212.39  4952.1  214.71  4967.2  213.85
  4990.7  206.07  4993.4  205.57  4996.7  206.07  5024.8  215.49  5065.6  215.69
  5800.9  213.49  6635.7  214.61  6769.7  218.47  7120.1  237.02  7295.3  239.19
#Mann= 13 ,-1 , 0
  1640.2     .16       0    1969     .05       0  2412.1      .1       0
  3433.3     .16       0  3520.3      .1       0  3710.3     .12       0
  3920.2     .05       0  4021.5      .1       0  4122.9     .05       0
  4224.3     .12       0  4990.7     .07       0  4996.7     .12       0
  5065.6     .05       0
Bank Sta=4952.1,5024.8
XS Rating Curve= 0 ,0
Exp/Cntr=0.3,0.1

Type RM Length L Ch R = 1 ,55964   ,1033,1033,1033
BEGIN DESCRIPTION:
GIBBONS CREEK 36.0
END DESCRIPTION:
XS GIS Cut Line= 3
      3641846.55     10202120.77      3638057.47     10203917.65
      3636429.86     10204269.22
#Sta/Elev= 30
  1186.7  231.06    1318  225.77  1722.9   226.5  1806.5  251.68  1822.5     253
  1844.6  249.54  1897.5   231.4  1965.7  218.38  2320.8  216.57  2848.5     215
  2880.1  213.47  2902.8   217.6  3194.8   212.7  3780.7   212.8  3817.2  211.97
  3839.9  206.97  3857.1  213.52  4965.6  212.02  4981.7  211.69  4995.8  204.74
  4998.6  204.24  5001.8  204.74  5027.2  212.35  5049.9  212.87  5096.5  212.99
  6531.6   216.4  6558.4  221.88  6715.7  221.99  6887.8  240.29  7045.4  240.93
#Mann= 7 ,-1 , 0
  1186.7     .05       0  2320.8     .12       0  2848.5     .05       0
  3780.7     .12       0  4995.8     .07       0  5001.8     .12       0
  5096.5     .05       0
Bank Sta=4965.6,5049.9
XS Rating Curve= 0 ,0
Exp/Cntr=0.3,0.1

Type RM Length L Ch R = 1 ,54931   ,1443,1443,1443
BEGIN DESCRIPTION:
GIBBONS CREEK 35.0
END DESCRIPTION:
XS GIS Cut Line= 3
      3641143.37     10200935.91      3638929.86      10202693.7
      3636892.09     10203591.65
#Sta/Elev= 30
  1790.8  234.95  1995.7  232.18  2091.5  227.42  2163.1   223.2  2316.6  215.34
  2398.6  214.75  2414.4  215.04  2694.2  214.95    3319  211.77  4029.7  211.78
  4244.2   213.7  4265.8  207.15  4286.6  211.96  4301.1  212.53  4489.9  211.08
  4540.8  211.26  4918.8   213.1  4986.5  210.18  4994.3  205.52  5005.3  203.92
  5008.1  203.42  5011.3  203.92  5023.1  206.87  5030.2  211.74    5059  212.79
  5813.3  211.05  6440.2  217.48  6562.3   220.8  6678.9  230.89  6844.2  241.63
#Mann= 13 ,-1 , 0
  1790.8     .05       0  2091.5     .12       0  2163.1     .05       0
  2316.6     .12       0  2398.6     .05       0  2414.4     .12       0
  2694.2     .05       0  4029.7     .12       0  4489.9      .1       0
  4540.8     .12       0  5005.3     .07       0  5011.3     .12       0
    5059     .05       0
Bank Sta=4918.8,5059
XS Rating Curve= 0 ,0
Exp/Cntr=0.3,0.1

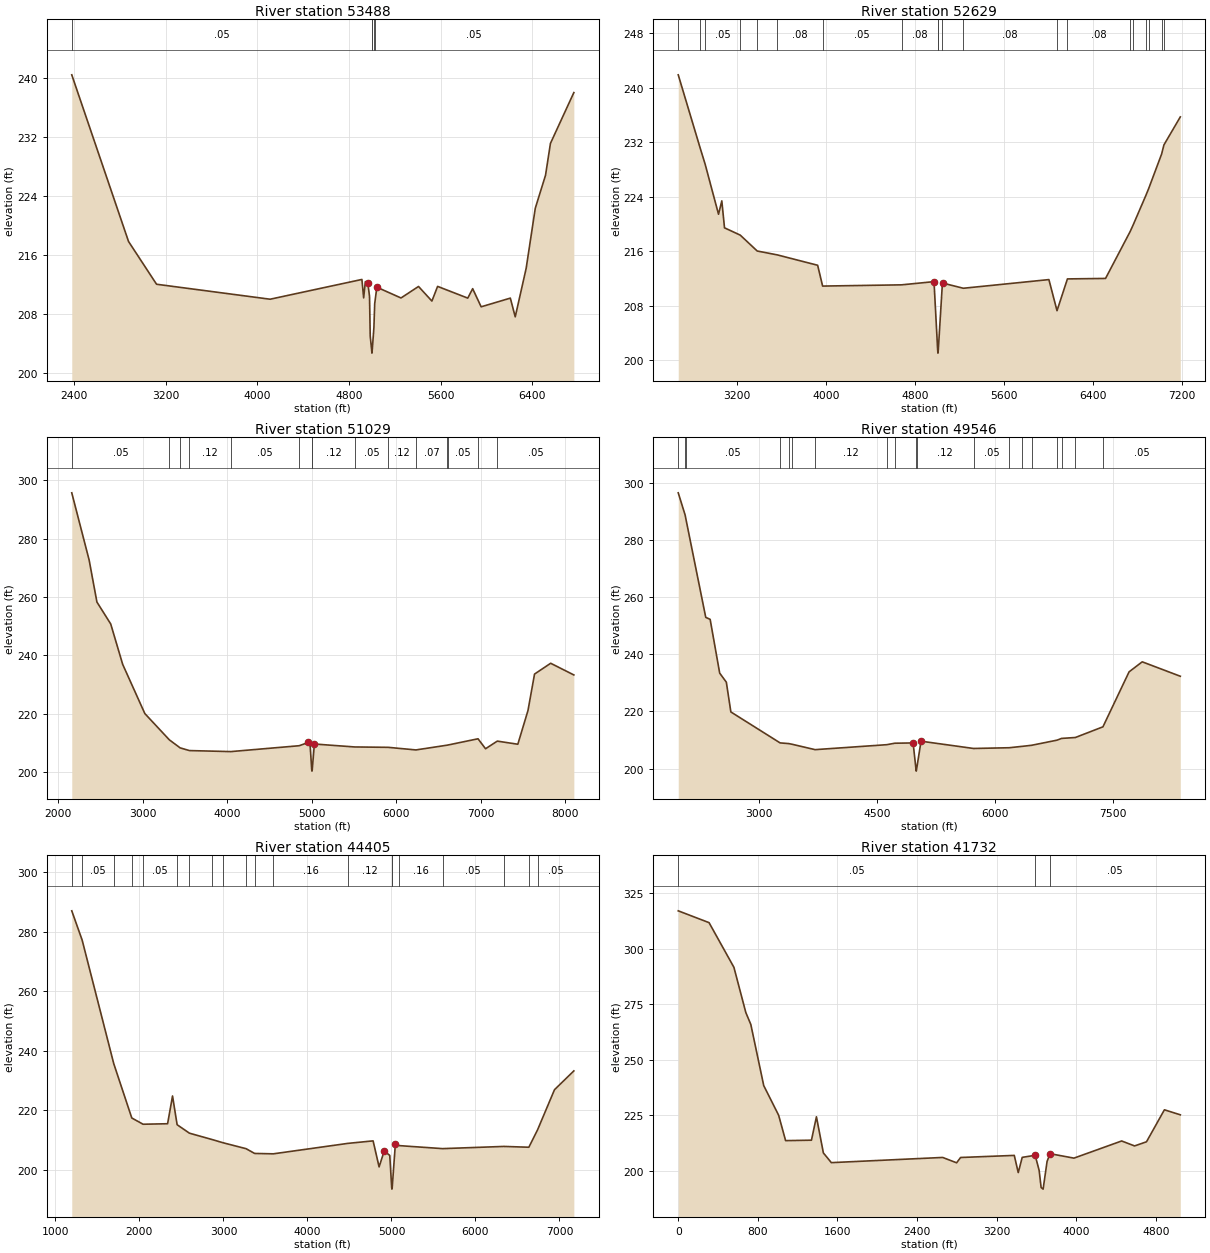
Type RM Length L Ch R = 1 ,53488   ,859,859,859
BEGIN DESCRIPTION:
GIBBONS CREEK 34.0
END DESCRIPTION:
XS GIS Cut Line= 3
      3640791.82     10200245.79      3638356.94     10201834.32
      3637092.08     10202591.66
#Sta/Elev= 30
  2380.9  240.45  2876.3  217.85  3120.8  212.05  4111.9  210.02  4912.9   212.7
  4928.1   210.2  4943.2  212.41  4964.3  212.24  4979.4   210.4  4985.4  205.01
  4997.5  203.21  5000.2  202.71  5003.5  203.21  5017.7  206.21  5024.5  209.41
  5043.2  211.65    5254  210.19    5407  211.75  5523.7  209.77  5573.5  211.76
  5836.7  210.17  5879.5  211.45  5953.4  208.99  6208.2  210.17  6250.9  207.63
  6346.2   214.2  6425.9  222.36  6515.4  226.84  6558.2  231.15  6762.4  238.04
#Mann= 5 ,-1 , 0
  2380.9     .05       0  4997.5     .03       0  5003.5     .05       0
  5017.7     .12       0  5024.5     .05       0
Bank Sta=4964.3,5043.2
XS Rating Curve= 0 ,0
Exp/Cntr=0.3,0.1

Type RM Length L Ch R = 1 ,52629   ,1600,1600,1600
BEGIN DESCRIPTION:
GIBBONS CREEK 33.0
END DESCRIPTION:
XS GIS Cut Line= 3
      3640392.12     10199791.64      3638916.58     10200381.85
       3636792.1     10202391.64
#Sta/Elev= 30
  2668.6  241.87  2865.7  231.14  2911.4  228.72  3030.8  221.43  3060.4  223.39
  3084.6  219.44    3226  218.37  3378.8  216.04  3559.4  215.47    3922  213.95
  3966.6   210.9  4675.8  211.08  4968.1  211.55  5000.7  201.57  5003.4  201.07
  5006.7  201.57    5043  211.18  5046.1  211.34  5231.5  210.58  6000.9  211.85
  6073.9  207.29  6167.5  211.95  6510.2  212.02  6731.9  218.91  6760.5  219.94
    6873   224.2  6897.8  225.19  7014.1  230.25  7035.1   231.6  7182.3   235.7
#Mann= 20 ,-1 , 0
  2668.6     .05       0  2865.7     .08       0  2911.4     .05       0
    3226     .08       0  3378.8     .05       0  3559.4     .08       0
  3966.6     .05       0  4675.8     .08       0  5000.7     .07       0
  5006.7     .08       0    5043     .12       0  5231.5     .08       0
  6073.9     .05       0  6167.5     .08       0  6731.9     .05       0
  6760.5     .08       0    6873     .05       0  6897.8     .08       0
  7014.1     .05       0  7035.1     .08       0
Bank Sta=4968.1,5046.1
XS Rating Curve= 0 ,0
Exp/Cntr=0.3,0.1

Type RM Length L Ch R = 1 ,51029   ,1483,1483,1483
BEGIN DESCRIPTION:
GIBBONS CREEK 32.0
END DESCRIPTION:
XS GIS Cut Line= 3
      3640292.12     10197491.63      3637827.56     10200327.83
      3636338.73     10201925.45
#Sta/Elev= 30
  2159.5  295.72  2365.1  272.69  2457.2   258.3  2620.5  250.79    2762  236.96
  3024.1   220.1  3313.7  211.11  3441.6  208.35  3551.7  207.42  4041.5  207.07
  4849.9  209.08  4959.3   210.2  4981.2   208.8    4999  200.88  5001.8  200.38
    5005  200.88  5030.5  209.67  5506.4  208.66  5903.3  208.53  6231.8  207.64
  6599.6  209.26    6607   209.3  6966.8  211.46  7055.7  208.05  7194.7  210.66
  7437.8  209.59    7558  221.14  7635.6  233.63  7826.7  237.33  8100.7  233.33
#Mann= 15 ,-1 , 0
  2159.5     .05       0  3313.7     .16       0  3441.6     .05       0
  3551.7     .12       0  4041.5     .05       0  4849.9     .12       0
    4999     .07       0    5005     .12       0  5506.4     .05       0
  5903.3     .12       0  6231.8     .07       0  6599.6     .12       0
    6607     .05       0  6966.8     .12       0  7194.7     .05       0
Bank Sta=4959.3,5030.5
XS Rating Curve= 0 ,0
Exp/Cntr=0.3,0.1

Type RM Length L Ch R = 1 ,49546   ,5141,5141,5141
BEGIN DESCRIPTION:
GIBBONS CREEK 31.0
END DESCRIPTION:
XS GIS Cut Line= 4
      3640244.99     10197042.64      3638343.92     10198592.13
       3636895.7     10198772.03      3634841.32     10200154.63
#Sta/Elev= 30
  1972.8  296.55  2060.9  288.75  2071.9  287.18  2322.9  252.95  2378.9  252.25
  2500.2  233.43    2585  230.24  2642.4  219.83    3269  208.99  3376.2  208.76
  3417.4  208.54  3714.3  206.63  4627.7  208.37  4727.6  208.88  4961.3  208.98
  4998.6  199.61  5001.3  199.11  5004.6  199.61    5062  209.59  5730.3  207.04
  6184.6   207.3  6350.9  207.79  6468.1  208.15  6791.9  209.95    6850  210.56
  7025.5  210.88  7376.6  214.62  7709.2  233.87  7876.4  237.38    8361  232.33
#Mann= 19 ,-1 , 0
  1972.8     .05       0  2060.9     .08       0  2071.9     .05       0
    3269     .16       0  3376.2      .1       0  3417.4     .16       0
  3714.3     .12       0  4627.7     .05       0  4727.6     .12       0
  4998.6     .07       0  5004.6     .12       0  5730.3     .05       0
  6184.6     .12       0  6350.9     .16       0  6468.1     .05       0
  6791.9     .12       0    6850     .05       0  7025.5     .12       0
  7376.6     .05       0
Bank Sta=4961.3,5062
XS Rating Curve= 0 ,0
Exp/Cntr=0.3,0.1

Type RM Length L Ch R = 1 ,44405   ,2673,2673,2673
BEGIN DESCRIPTION:
GIBBONS CREEK 29.0
END DESCRIPTION:
XS GIS Cut Line= 4
       3639792.1     10196341.64      3638553.91     10197021.16
      3635648.61     10197602.55      3635049.71     10199086.78
#Sta/Elev= 30
    1195  287.09  1318.2  277.28  1694.4  235.68  1909.3  217.37  2043.7  215.26
  2335.7  215.43  2394.3  224.77    2449   215.1  2595.4  212.25    2864  210.12
  2997.9  209.01  3269.9  207.03  3371.3  205.43  3593.9   205.3  4482.3  208.82
  4781.5  209.66  4852.9   200.9    4914  206.26    4980  204.76  5002.8  193.92
  5005.6  193.42  5008.8  193.92  5046.6  208.64  5094.8  208.06  5608.3  207.05
  6338.1  207.79  6635.2  207.52  6739.5  213.41  6940.7  226.89  7170.8  233.21
#Mann= 20 ,-1 , 0
    1195     .08       0  1318.2     .05       0  1694.4     .08       0
  1909.3     .12       0  2043.7     .05       0    2449     .12       0
  2595.4     .16       0    2864     .05       0  2997.9     .16       0
  3269.9     .12       0  3371.3     .16       0  3593.9     .16       0
  4482.3     .12       0  5002.8     .07       0  5008.8     .12       0
  5094.8     .16       0  5608.3     .05       0  6338.1     .16       0
  6635.2      .1       0  6739.5     .05       0
Bank Sta=4914,5046.6
XS Rating Curve= 0 ,0
Exp/Cntr=0.3,0.1

Type RM Length L Ch R = 1 ,41732   ,1840,1840,1840
XS GIS Cut Line= 2
     3637271.098    10194258.431     3633529.778    10197574.403
#Sta/Elev= 30
       0  317.17  309.72  311.84   559.5  291.71  679.39  271.29  729.34  265.96
  859.23  238.38 1009.09  225.01 1079.03  213.57 1338.79  213.77 1388.75  224.32
 1458.68  208.02 1538.61  203.65  2657.6  205.99 2797.48  203.58 2837.44  205.97
 3376.96  206.91 3416.92  199.17 3456.88  206.03 3586.77  206.96 3626.73  200.18
 3646.71  192.44 3666.69  191.71 3706.66  204.21 3736.63  207.69 3976.41  205.68
 4455.98  213.42 4585.87  211.18 4705.76  213.05  4885.6  227.47 5045.45  225.21
#Mann= 3 , 0 , 0
       0     .05       0 3586.77     .07       0 3736.63     .05       0
Bank Sta=3586.77,3736.63
XS Rating Curve= 0 ,0
Exp/Cntr=0.3,0.1

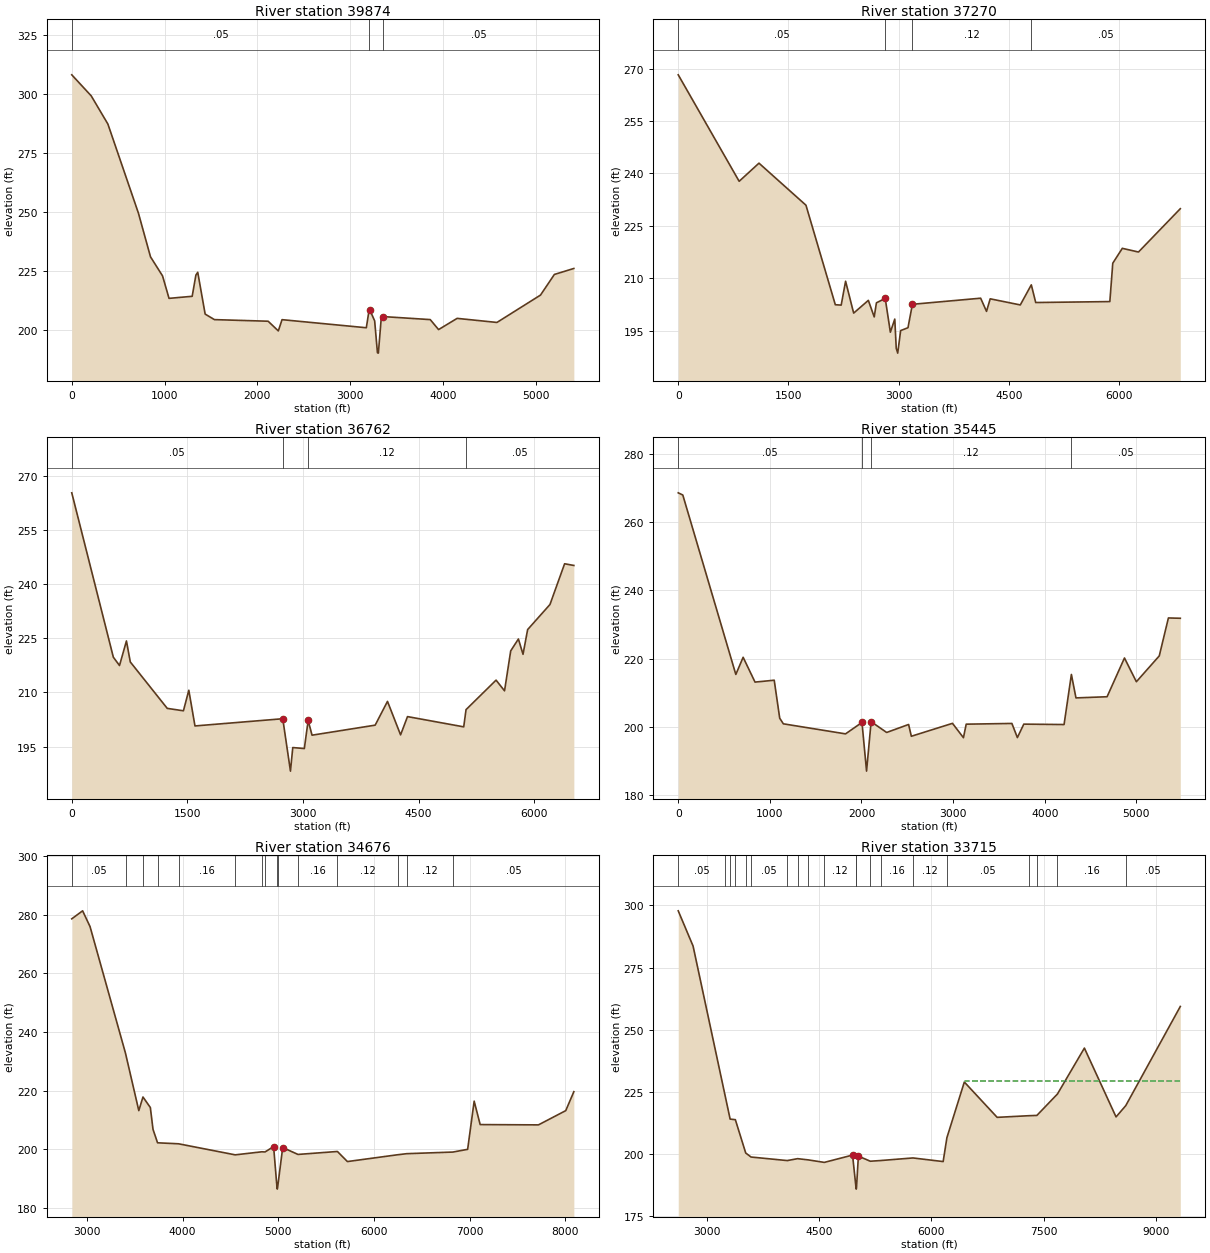
Type RM Length L Ch R = 1 ,39874   ,2622,2622,2622
XS GIS Cut Line= 3
     3636823.206    10194146.698     3633527.145    10195575.409
     3633314.092    10197455.292
#Sta/Elev= 30
       0  308.14  209.59  299.21  389.24  287.25  718.59  249.39  848.33   230.9
  978.08  222.81 1047.94  213.27 1297.45  214.15 1337.37  223.15 1357.33  224.34
 1437.18   206.6 1536.98  204.25 2115.84  203.57 2225.63  199.45 2265.55  204.23
 3173.76   200.8  3203.7  208.34 3213.69  208.16 3263.59  203.71 3293.53   190.2
 3303.51  190.03 3333.45  204.39 3353.41  205.54 3862.46  204.26  3952.3  200.02
 4151.94  204.78 4581.17  203.05 5050.33  214.66 5200.06  223.42 5409.69  225.96
#Mann= 3 ,-1 , 0
       0     .05       0  3203.7     .07       0 3353.41     .05       0
Bank Sta=3213.69,3353.41
XS Rating Curve= 0 ,0
Exp/Cntr=0.3,0.1

Type RM Length L Ch R = 1 ,37270   ,508,508,508
XS GIS Cut Line= 2
     3633827.926    10190537.323     3633176.234    10197367.564
#Sta/Elev= 30
       0  268.23  829.49  237.76 1099.32  242.95 1738.93  230.92 2138.69  202.44
 2218.64  202.33  2278.6  209.16 2388.53  200.04 2588.41  203.69 2668.36  198.95
 2698.34  202.99 2818.27  204.25 2888.23  194.58 2948.19  198.33 2968.18  189.98
 2988.16  188.59 3028.14  195.04 3128.08  195.86 3188.04  202.56 4117.47  204.31
 4197.42  200.54 4247.39  204.13 4657.14  202.38 4807.05  208.13 4867.01  203.07
 5876.39  203.34 5916.37  214.33 6046.29  218.58 6266.15  217.52  6835.8  229.92
#Mann= 4 ,-1 , 0
       0     .05       0 2818.27     .07       0 3188.04     .12       0
 4807.05     .05       0
Bank Sta=2818.27,3188.04
XS Rating Curve= 0 ,0
Exp/Cntr=0.3,0.1

Type RM Length L Ch R = 1 ,36762   ,1317,1317,1317
XS GIS Cut Line= 2
     3633339.157    10190612.518     3632925.583    10197129.445
#Sta/Elev= 30
       0  265.32  539.42  219.76  619.34  217.46  709.24  224.27  759.19  218.45
 1238.67  205.58 1448.45  204.91 1518.37  210.61 1598.29  200.71 2737.07  202.71
 2836.96  188.19 2866.93  194.72 3016.77  194.45 3066.71  202.24 3116.66  198.15
 3935.78  200.93 4095.61  207.52 4265.43  198.24 4355.33   203.3 5084.55  200.46
 5114.52  205.23  5504.1  213.41 5613.99  210.44  5693.9  221.51 5793.79  224.81
 5853.73  220.57 5913.66  227.42 6203.35  234.37 6393.15  245.66 6513.02  245.19
#Mann= 4 ,-1 , 0
       0     .05       0 2737.07     .07       0 3066.71     .12       0
 5114.52     .05       0
Bank Sta=2737.07,3066.71
XS Rating Curve= 0 ,0
Exp/Cntr=0.3,0.1

Type RM Length L Ch R = 1 ,35445   ,769,769,769
XS GIS Cut Line= 3
     3633289.027    10190599.986     3631998.174    10194033.905
     3630983.037    10195550.344
#Sta/Elev= 30
       0  268.57   49.89  267.93  628.55  215.39  708.37  220.41  838.07  213.15
 1047.59   213.7 1107.45  202.58 1147.36  200.93 1825.79  197.99 2005.38  201.33
 2055.26  187.08 2105.15  201.56 2274.76   198.4 2514.21  200.74 2544.14  197.29
  2993.1  201.07 3112.83  196.87 3142.76  200.83 3641.61  201.04  3701.5   196.9
 3771.42  200.84 4210.95  200.72 4290.86  215.39 4340.81  208.52 4680.44  208.86
 4870.24  220.21  5000.1  213.25 5249.83  220.82 5349.72  231.93 5479.58  231.84
#Mann= 4 ,-1 , 0
       0     .05       0 2005.38     .07       0 2105.15     .12       0
 4290.86     .05       0
Bank Sta=2005.38,2105.15
XS Rating Curve= 0 ,0
Exp/Cntr=0.3,0.1

Type RM Length L Ch R = 1 ,34676   ,961,961,961
BEGIN DESCRIPTION:
GIBBONS CREEK 23.0
END DESCRIPTION:
XS GIS Cut Line= 3
      3633174.64     10190454.13      3632145.24     10191545.99
      3630942.11     10195091.62
#Sta/Elev= 30
  2842.9   278.6  2956.1  281.33  3033.8  275.95  3404.3  232.75  3543.2  213.19
  3586.7  217.84  3663.7  214.26  3691.6  206.81    3739  202.22  3958.6  201.88
  4550.1  198.11  4828.5  199.15  4861.9   199.1  4951.4  200.92  4986.8  186.92
  4989.6  186.42  4992.8  186.92  5046.4   200.6  5206.1  198.25  5617.9  199.26
  5722.3  195.82  6246.3  198.14  6343.1  198.51  6824.1  199.06  6978.3  199.99
  7046.4  216.42  7109.2  208.43  7718.1  208.33  8003.2  213.19  8087.7  219.65
#Mann= 15 ,-1 , 0
  2842.9     .05       0  3404.3      .1       0  3586.7     .05       0
    3739     .12       0  3958.6     .16       0  4550.1     .12       0
  4828.5     .16       0  4861.9     .12       0  4986.8     .07       0
  4992.8     .12       0  5206.1     .16       0  5617.9     .12       0
  6246.3     .16       0  6343.1     .12       0  6824.1     .05       0
Bank Sta=4951.4,5046.4
XS Rating Curve= 0 ,0
Exp/Cntr=0.3,0.1

Type RM Length L Ch R = 1 ,33715   ,1506,1506,1506
BEGIN DESCRIPTION:
GIBBONS CREEK 22.0
END DESCRIPTION:
XS GIS Cut Line= 3
      3632842.08     10190191.67       3629893.4     10192928.07
      3627380.34     10193865.59
#Sta/Elev= 30
  2619.9  297.82    2818  283.65  3243.9  223.72  3312.9  213.99  3382.6  213.76
  3521.2  200.33  3592.3  198.72  4075.7  197.29  4214.3  198.06    4353  197.58
  4570.6  196.56  4947.9  199.51  4994.3   186.3    4997   185.8  5000.3   186.3
  5025.6  199.09  5184.8  197.03  5323.4  197.31  5754.2  198.35  6157.8  196.89
  6207.8   206.5  6440.7  228.91  6878.9  214.69  7302.4  215.35  7409.4  215.46
  7683.9  224.08    8044  242.57  8466.7  214.86  8596.3   219.4  9324.9  259.32
#Mann= 20 ,-1 , 0
  2619.9     .05       0  3243.9     .08       0  3312.9      .1       0
  3382.6     .05       0  3521.2     .16       0  3592.3     .05       0
  4075.7     .12       0  4214.3     .12       0    4353     .12       0
  4570.6     .12       0  4994.3     .07       0  5000.3     .12       0
  5184.8     .16       0  5323.4     .16       0  5754.2     .12       0
  6207.8     .05       0  7302.4     .08       0  7409.4     .05       0
  7683.9     .16       0  8596.3     .05       0
#XS Ineff= 1 ,-1
 6445.45 9568.18  229.26
Permanent Ineff=
       F
Bank Sta=4947.9,5025.6
XS Rating Curve= 0 ,0
Exp/Cntr=0.3,0.1