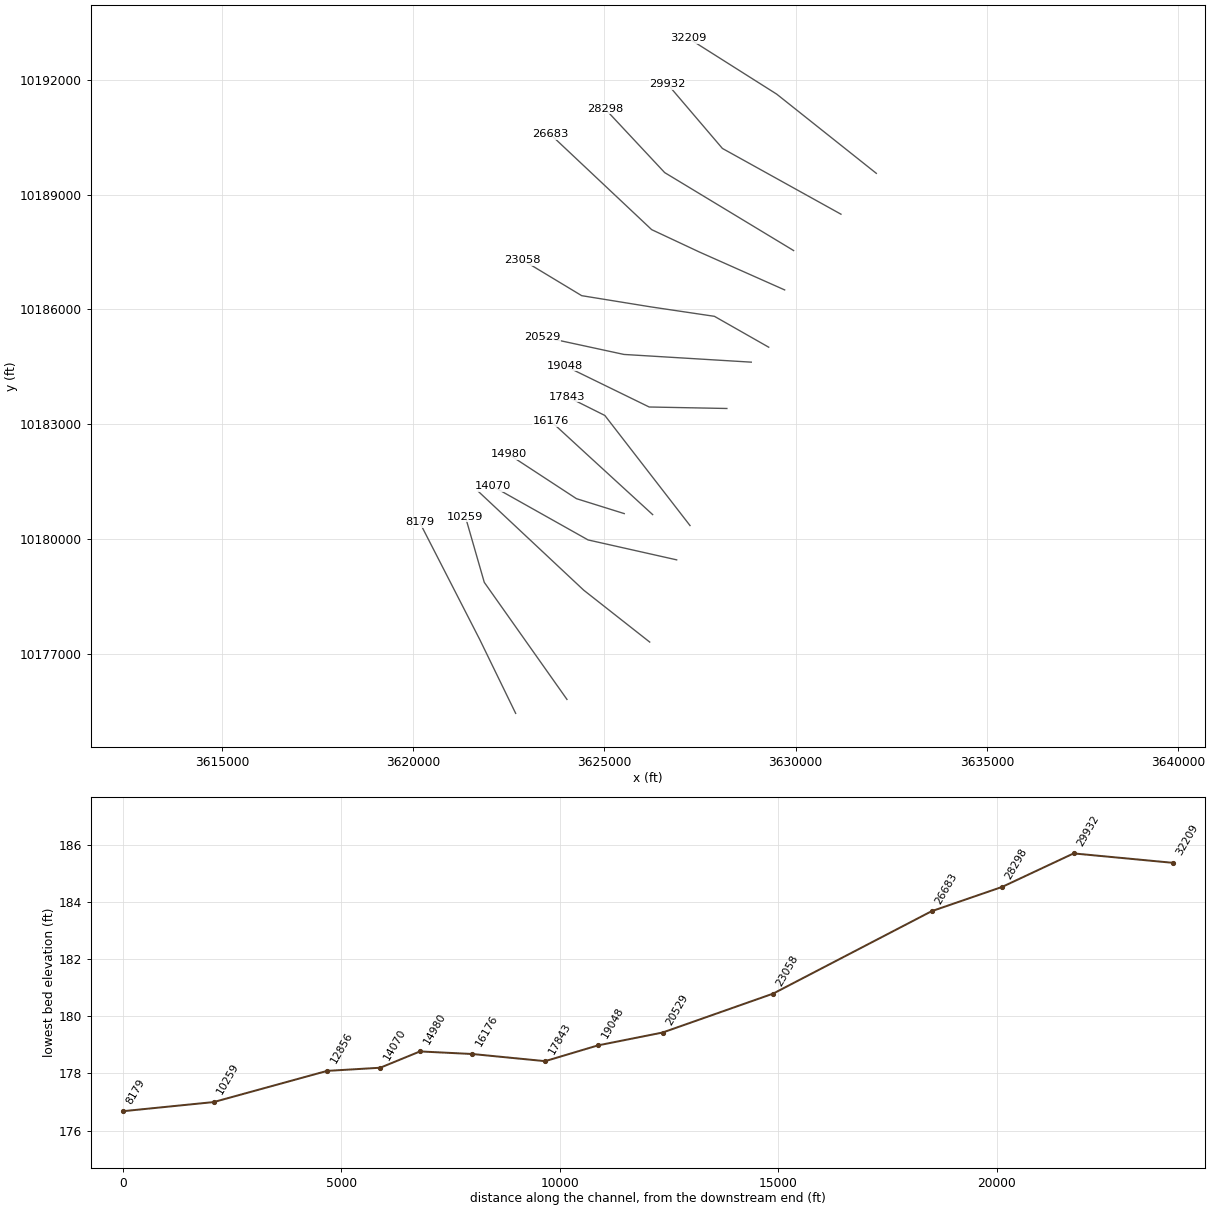
HEC-RAS study GIBBONS CREEK.prj: GIBBONS CREEK Base Level Engineering

--- GIBBONS CREEK.g01 (geometry) --- (continued)

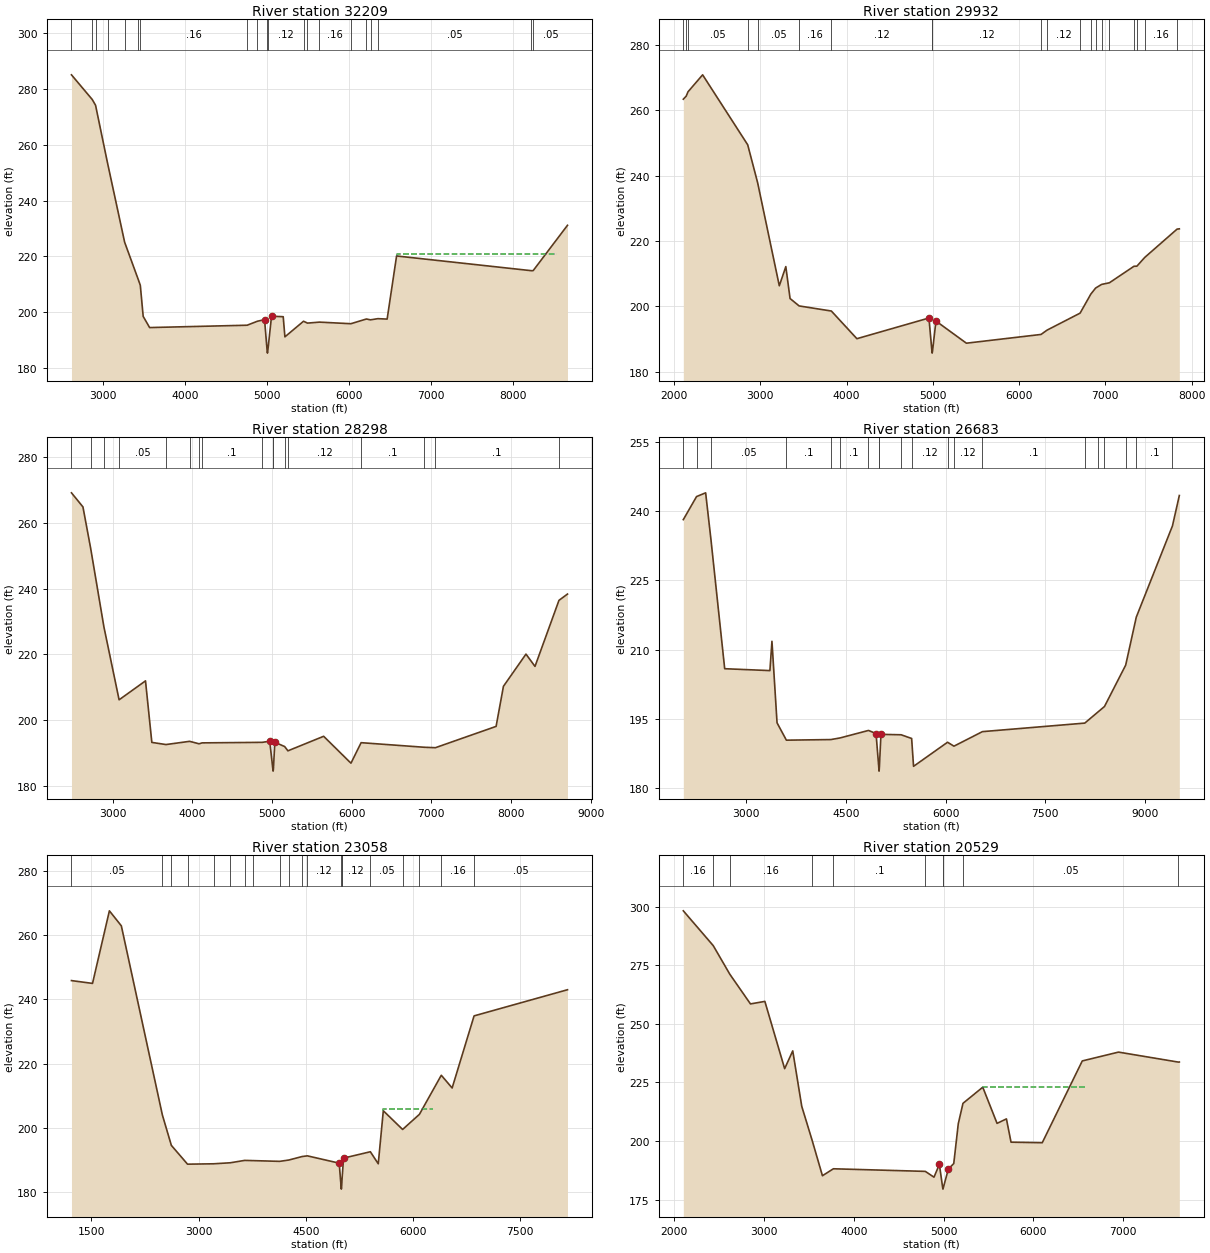
Type RM Length L Ch R = 1 ,32209   ,2277,2277,2277
BEGIN DESCRIPTION:
GIBBONS CREEK 21.0
END DESCRIPTION:
XS GIS Cut Line= 3
      3632106.94     10189555.67      3629502.78     10191625.99
      3627198.07     10193084.34
#Sta/Elev= 30
  2613.9   285.1  2866.8  276.28    2908   274.2  3054.3  253.47    3263   225.1
  3428.6  211.79  3454.2  209.66  3489.2  198.54  3567.7  194.52  4758.3  195.36
  4882.4  196.78  4970.7  197.36  5003.2  185.86    5006  185.36  5009.2  185.86
  5055.9  198.59  5198.4  198.41  5219.2  191.19  5446.5  196.79  5494.3  196.12
  5641.1  196.47  6024.3   195.9  6213.8  197.59  6263.8  197.29  6353.6  197.71
  6466.9  197.56  6582.2  220.18  8228.6   214.9  8249.3  214.93  8668.1  231.17
#Mann= 20 ,-1 , 0
  2613.9     .05       0  2866.8     .08       0    2908     .05       0
  3054.3      .1       0    3263     .05       0  3428.6      .1       0
  3454.2     .16       0  4758.3     .12       0  4882.4     .12       0
  5003.2     .07       0  5009.2     .12       0  5446.5     .16       0
  5494.3     .12       0  5641.1     .16       0  6024.3     .12       0
  6213.8     .16       0  6263.8     .12       0  6353.6     .05       0
  8228.6     .08       0  8249.3     .05       0
#XS Ineff= 1 ,-1
 6581.82 8538.64     221
Permanent Ineff=
       F
Bank Sta=4970.7,5055.9
XS Rating Curve= 0 ,0
Exp/Cntr=0.3,0.1

Type RM Length L Ch R = 1 ,29932   ,1634,1634,1634
BEGIN DESCRIPTION:
GIBBONS CREEK 20.0
END DESCRIPTION:
XS GIS Cut Line= 3
      3631182.48     10188487.96      3628083.51     10190206.72
      3626651.24     10191886.37
#Sta/Elev= 30
  2106.3  263.43  2139.8  264.37  2160.6  265.69  2330.1  270.89  2852.9  249.47
  2968.2  237.84  3219.3  206.31  3294.8  212.18    3344  202.41  3449.2  200.14
  3822.7  198.58  4118.9  190.11  4954.3  196.44  4989.1  186.19  4991.8  185.69
  4995.1  186.19  5035.6  195.51  5388.6  188.73  6254.1  191.41    6323  192.72
  6706.6  197.93  6831.6  203.77  6886.7  205.61  6956.6  206.73  7046.2  207.22
  7331.6  212.28  7365.1  212.31  7456.5  214.99  7831.5  223.66  7857.4  223.74
#Mann= 20 ,-1 , 0
  2106.3     .05       0  2139.8      .1       0  2160.6     .05       0
  2852.9     .08       0  2968.2     .05       0  3449.2     .16       0
  3822.7     .12       0  4989.1     .07       0  4995.1     .12       0
  6254.1     .05       0    6323     .12       0  6706.6      .1       0
  6831.6     .05       0  6886.7      .1       0  6956.6     .05       0
  7046.2     .16       0  7331.6      .1       0  7365.1     .05       0
  7456.5     .16       0  7831.5     .05       0
Bank Sta=4954.3,5035.6
XS Rating Curve= 0 ,0
Exp/Cntr=0.3,0.1

Type RM Length L Ch R = 1 ,28298   ,1615,1615,1615
BEGIN DESCRIPTION:
GIBBONS CREEK 20.2
END DESCRIPTION:
XS GIS Cut Line= 3
      3629945.49     10187537.45      3626574.28     10189575.46
       3625011.4     10191247.51
#Sta/Elev= 30
  2481.1  269.13  2625.3  264.85  2723.1  252.12  2888.9  228.32  3079.2   206.2
  3410.7  211.96  3490.3  193.25  3668.1   192.6  3965.1  193.58  4083.3  192.83
  4121.3  193.11  4876.5  193.27  4970.6  193.61  5010.3  185.02  5013.1  184.52
  5016.3  185.02  5034.7  193.29  5158.2  191.99  5198.7  190.69  5647.7  195.11
  5990.6  186.93  6117.9  193.17    6908  191.78  7050.7  191.64  7812.9  198.12
  7905.2  210.31  8188.1   220.1  8301.4  216.35  8602.3  236.44  8709.2  238.35
#Mann= 17 ,-1 , 0
  2481.1      .1       0  2723.1     .05       0  2888.9      .1       0
  3079.2     .05       0  3668.1     .16       0  3965.1      .1       0
  4083.3     .12       0  4121.3      .1       0  4876.5     .12       0
  5010.3     .07       0  5016.3     .12       0  5158.2     .16       0
  5198.7     .12       0  6117.9      .1       0    6908     .05       0
  7050.7      .1       0  8602.3     .16       0
Bank Sta=4970.6,5034.7
XS Rating Curve= 0 ,0
Exp/Cntr=0.3,0.1

Type RM Length L Ch R = 1 ,26683   ,3625,3625,3625
BEGIN DESCRIPTION:
GIBBONS CREEK 20.1
END DESCRIPTION:
XS GIS Cut Line= 4
      3629711.11      10186508.8      3627484.55     10187498.38
      3626234.55     10188084.32      3623578.28     10190584.34
#Sta/Elev= 30
  2053.4  238.19  2252.7  243.19  2389.4     244  2468.9  233.93  2676.1  205.87
  3356.5  205.46  3387.4  211.82    3464  194.14  3604.5  190.38  4273.7  190.51
  4411.4  190.86  4840.3  192.49    4954  191.81  4996.7  184.17  4999.4  183.67
  5002.7  184.17    5028  191.64  5331.2  191.55  5489.5  190.75  5518.4  184.71
    6030  189.93  6126.7  189.08  6554.7  192.23  8095.3  194.08  8288.8  196.43
  8391.8  197.68    8711  206.65  8870.2  217.04  9414.7  236.83  9518.2  243.42
#Mann= 20 ,-1 , 0
  2053.4     .05       0  2252.7     .05       0  2468.9     .05       0
  3604.5      .1       0  4273.7     .12       0  4411.4      .1       0
  4840.3     .12       0  4996.7     .07       0  5002.7     .12       0
  5331.2     .16       0  5489.5     .12       0    6030     .16       0
  6126.7     .12       0  6554.7      .1       0  8095.3     .16       0
  8288.8     .16       0  8391.8      .1       0    8711     .16       0
  8870.2      .1       0  9414.7     .05       0
Bank Sta=4954,5028
XS Rating Curve= 0 ,0
Exp/Cntr=0.3,0.1

Type RM Length L Ch R = 1 ,23058   ,2529,2529,2529
BEGIN DESCRIPTION:
GIBBONS CREEK 19.0
END DESCRIPTION:
XS GIS Cut Line= 5
      3629294.42     10185011.42      3627875.17      10185818.7
      3626208.51     10186066.09      3624406.23     10186358.29
      3622862.19     10187290.03
#Sta/Elev= 30
  1219.6   245.9  1514.5  245.02  1750.9  267.68  1918.1  262.99    2493  203.93
  2618.6  194.45  2845.2  188.58  3211.1   188.7  3445.2  189.02  3645.9  189.76
  3761.6  189.69  4135.6  189.46  4263.2  189.87  4448.9  190.96  4523.1  191.18
  4969.3   188.9  4996.7  181.29  4999.4  180.79  5002.7  181.29  5009.1  183.88
  5030.1  190.47  5405.7  192.46  5516.3   188.7  5587.2  205.26  5857.5  199.42
  6092.5  204.13  6399.2  216.34  6551.2  212.37  6858.5  234.88  8166.5  243.04
#Mann= 20 ,-1 , 0
  1219.6     .05       0    2493     .12       0  2618.6     .07       0
  2845.2     .16       0  3211.1      .1       0  3445.2      .1       0
  3645.9     .12       0  3761.6      .1       0  4135.6     .12       0
  4263.2      .1       0  4448.9     .16       0  4523.1     .12       0
  4996.7     .07       0  5002.7     .07       0  5009.1     .12       0
  5405.7     .05       0  5857.5     .16       0  6092.5     .05       0
  6399.2     .16       0  6858.5     .05       0
#XS Ineff= 1 ,-1
 5586.36 6286.36  205.66
Permanent Ineff=
       F
Bank Sta=4969.3,5030.1
XS Rating Curve= 0 ,0
Exp/Cntr=0.3,0.1

Type RM Length L Ch R = 1 ,20529   ,1481,1481,1481
BEGIN DESCRIPTION:
GIBBONS CREEK 18.0
END DESCRIPTION:
XS GIS Cut Line= 3
      3628838.68     10184620.78      3625509.81     10184822.37
      3623369.98     10185284.84
#Sta/Elev= 30
  2101.7  298.29  2434.9  283.43  2619.6  271.22  2849.6  258.53  3009.9  259.61
  3230.3  230.88  3320.5  238.47  3420.7   214.8  3536.5  200.26  3651.1  185.15
    3773  188.12    4797  187.01  4893.4  184.53  4953.5  189.99  4990.6  179.93
  4993.3  179.43  4996.6  179.93  5053.7  188.01  5113.8  190.37  5163.9  207.33
  5216.3  216.07  5436.7  222.96  5595.9  207.52  5700.3  209.42  5751.5  199.48
  6099.3  199.25    6545  234.18  6948.5  237.95  7614.3  233.69  7625.9  233.72
#Mann= 10 ,-1 , 0
  2101.7     .16       0  2434.9      .1       0  2619.6     .16       0
  3536.5     .12       0    3773      .1       0    4797     .12       0
  4990.6     .07       0  4996.6     .12       0  5216.3     .05       0
  7614.3     .08       0
#XS Ineff= 1 ,-1
 5432.95 6588.64  223.08
Permanent Ineff=
       F
Bank Sta=4953.5,5053.7
XS Rating Curve= 0 ,0
Exp/Cntr=0.3,0.1

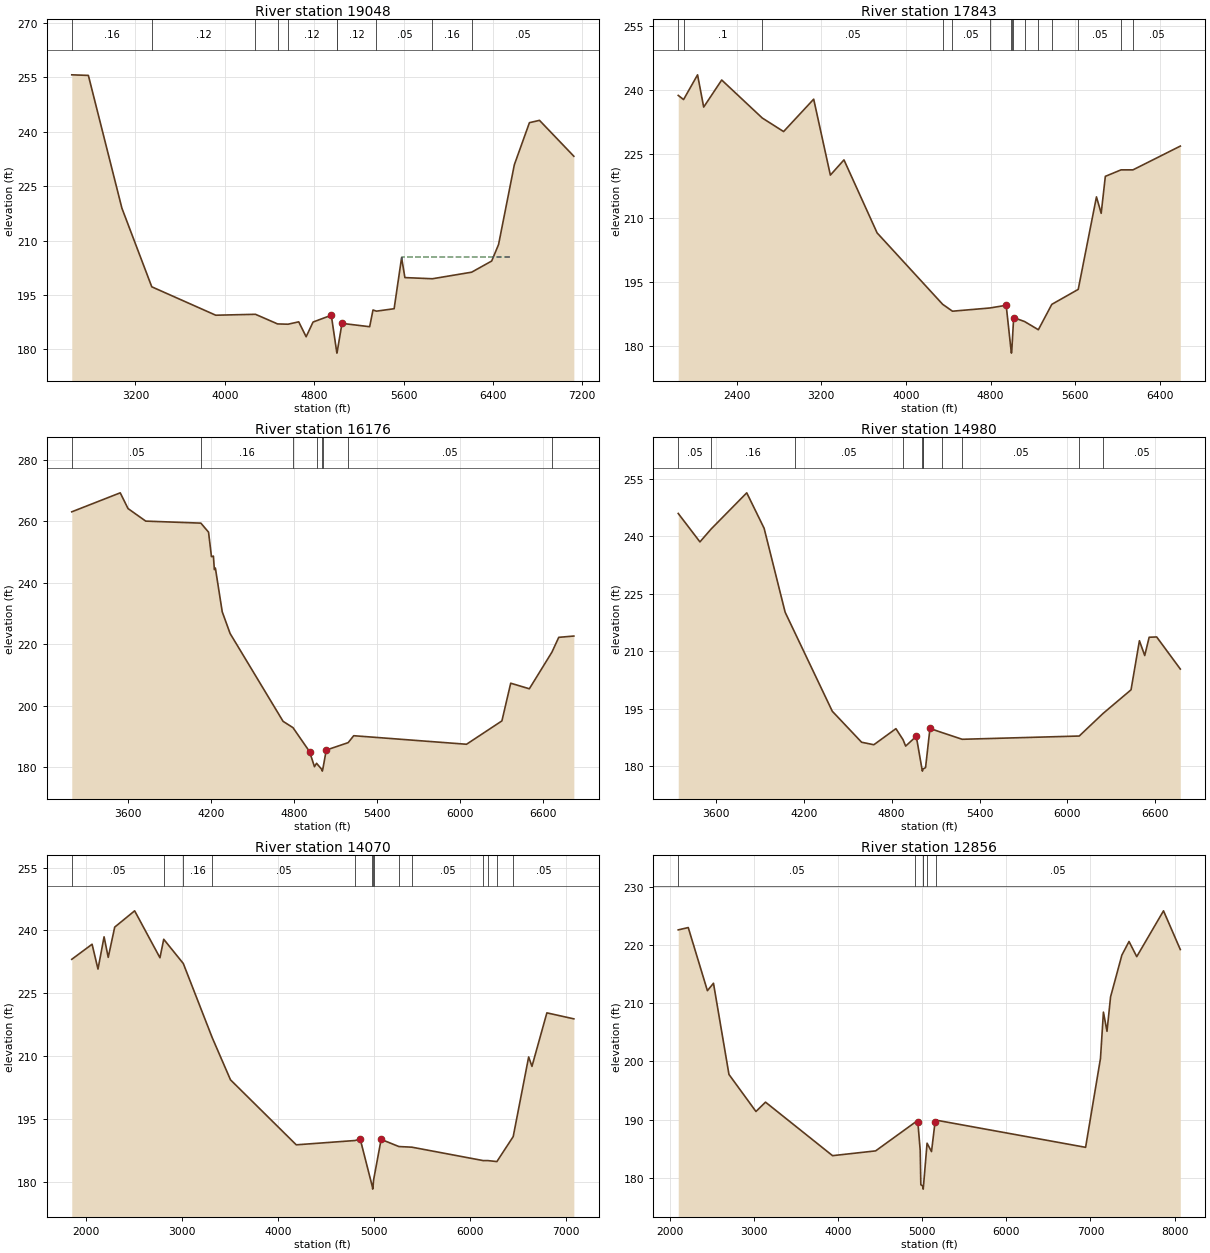
Type RM Length L Ch R = 1 ,19048   ,1205,1205,1205
BEGIN DESCRIPTION:
GIBBONS CREEK 17.0
END DESCRIPTION:
XS GIS Cut Line= 3
      3628200.66     10183409.84      3626169.44      10183448.9
       3623956.5     10184529.34
#Sta/Elev= 30
  2630.6  255.69  2779.2  255.53  3079.2  218.95  3346.7  197.26  3919.4  189.43
  4275.1  189.68  4472.6  187.03  4566.9  186.95  4662.2  187.61  4728.5  183.49
  4790.5  187.55  4953.7  189.42  5001.3  179.48  5004.1  178.98  5007.3  179.48
  5049.4  187.18  5297.2  186.26  5326.9  190.87  5357.9  190.55  5516.1  191.22
  5582.9  205.28  5612.5   199.8  5858.7  199.48  6210.1  201.29  6389.5  204.37
  6450.9  208.92  6592.2  230.91  6727.3   242.5  6817.4  243.14  7124.8  233.25
#Mann= 10 ,-1 , 0
  2630.6     .16       0  3346.7     .12       0  4275.1     .16       0
  4472.6      .1       0  4566.9     .12       0  5001.3     .07       0
  5007.3     .12       0  5357.9     .05       0  5858.7     .16       0
  6210.1     .05       0
#XS Ineff= 1 ,-1
 5586.36 6564.77  205.56
Permanent Ineff=
       F
Bank Sta=4953.7,5049.4
XS Rating Curve= 0 ,0
Exp/Cntr=0.3,0.1

Type RM Length L Ch R = 1 ,17843   ,1667,1667,1667
BEGIN DESCRIPTION:
GIBBONS CREEK 15.0
END DESCRIPTION:
XS GIS Cut Line= 3
      3627237.16     10180349.94      3625010.59     10183227.55
      3624021.03     10183722.33
#Sta/Elev= 30
  1847.8  238.67  1898.2   237.7  2030.5  243.48  2088.4  235.94  2258.6  242.27
  2642.2  233.38  2843.6  230.22  3127.9  237.79  3285.5  220.04  3414.1   223.6
  3727.3  206.53  4346.7  189.84  4439.5  188.23  4792.1  188.98    4947  189.61
  4993.8  178.93  4996.6  178.43  4999.8  178.93  5009.4  183.08  5017.7  186.73
  5120.5  185.82  5251.1   183.9  5378.2  189.83  5627.9  193.33  5800.2  214.95
  5844.9  211.11  5884.1  219.75  6032.9  221.27  6145.5  221.27  6592.6  226.82
#Mann= 15 ,-1 , 0
  1847.8     .05       0  1898.2      .1       0  2642.2     .05       0
  4346.7      .1       0  4439.5     .05       0  4792.1     .12       0
  4993.8     .07       0  4999.8     .12       0  5009.4     .05       0
  5120.5     .12       0  5251.1     .05       0  5378.2     .12       0
  5627.9     .05       0  6032.9     .08       0  6145.5     .05       0
Bank Sta=4947,5017.7
XS Rating Curve= 0 ,0
Exp/Cntr=0.3,0.1

Type RM Length L Ch R = 1 ,16176   ,1196,1196,1196
BEGIN DESCRIPTION:
GIBBONS CREEK 13.0
END DESCRIPTION:
XS GIS Cut Line= 3
      3626260.59      10180636.4      3624554.86      10182198.9
      3623591.31     10183084.33
#Sta/Elev= 30
  3197.9  263.03  3547.6  269.21  3603.7  264.09  3731.4  260.01  4129.3  259.35
  4184.6  256.41  4205.6  248.45  4219.7  248.62  4226.5  244.24  4233.9  244.73
  4283.3  230.51    4340  223.46  4722.3  194.87  4793.6  192.83  4913.5  185.01
  4948.6  180.12  4963.8  181.23  5002.3  179.18  5005.1  178.68  5008.3  179.18
  5033.7  185.53  5191.9  187.95  5231.7   190.2  6045.6  187.42  6300.8  195.02
  6364.3  207.28  6498.7  205.47  6661.6  217.38  6710.8   222.2  6819.7  222.62
#Mann= 8 ,-1 , 0
  3197.9     .05       0  4129.3     .16       0  4793.6     .05       0
  4963.8     .12       0  5002.3     .07       0  5008.3     .12       0
  5191.9     .05       0  6661.6     .08       0
Bank Sta=4913.5,5033.7
XS Rating Curve= 0 ,0
Exp/Cntr=0.3,0.1

Type RM Length L Ch R = 1 ,14980   ,910,910,910
BEGIN DESCRIPTION:
GIBBONS CREEK 11.0
END DESCRIPTION:
XS GIS Cut Line= 3
      3625518.36     10180662.46       3624268.4     10181053.07
      3622497.56     10182211.93
#Sta/Elev= 30
  3344.2  245.94  3492.3  238.53  3568.5  241.88  3811.7  251.32  3930.2  242.08
  4073.7  220.19  4144.2  214.53  4395.4  194.38  4595.5   186.3  4678.9  185.65
  4829.6  189.84  4878.5  186.94    4896  185.29  4968.4  187.86  5007.6  179.27
  5010.3  178.77  5013.6  179.27    5014  179.29  5031.8  179.69  5061.9   189.9
  5143.3  188.83  5281.8  187.07  6080.4  187.92  6242.8   193.8  6433.9  199.97
  6491.1  212.76  6527.3  208.91  6557.5  213.67  6608.8  213.75  6770.1  205.38
#Mann= 11 ,-1 , 0
  3344.2     .05       0  3568.5     .16       0  4144.2     .05       0
  4878.5     .12       0  5007.6     .07       0  5013.6     .12       0
    5014     .05       0  5143.3     .08       0  5281.8     .05       0
  6080.4     .12       0  6242.8     .05       0
Bank Sta=4968.4,5061.9
XS Rating Curve= 0 ,0
Exp/Cntr=0.3,0.1

Type RM Length L Ch R = 1 ,14070   ,1214,1214,1214
BEGIN DESCRIPTION:
GIBBONS CREEK 10.0
END DESCRIPTION:
XS GIS Cut Line= 3
      3626888.64      10179453.5      3624572.45     10179974.22
      3622081.79     10181374.08
#Sta/Elev= 30
  1850.2  233.09  2061.9  236.69  2123.4  230.76  2186.8  238.46  2230.1  233.55
  2297.6  240.78  2505.3  244.67  2769.1  233.46  2808.3  237.88  3012.4  232.08
  3313.3  214.39  3503.9  204.31  4189.2  188.78  4800.8  189.81  4855.5  190.15
  4982.9   178.7  4985.6   178.2  4988.9   178.7  4994.6  180.36  5073.5  190.08
  5258.5  188.37  5393.4  188.22  6138.2  185.01  6183.5  185.02  6279.4  184.78
  6449.6  190.75  6610.6  209.77    6645  207.52  6800.3   220.3  7081.3  218.87
#Mann= 14 ,-1 , 0
  1850.2     .05       0  2808.3     .08       0  3012.4     .16       0
  3313.3     .05       0  4800.8     .12       0  4982.9     .03       0
  4988.9     .12       0  4994.6     .05       0  5258.5     .08       0
  5393.4     .05       0  6138.2     .12       0  6183.5     .05       0
  6279.4     .12       0  6449.6     .05       0
Bank Sta=4855.5,5073.5
XS Rating Curve= 0 ,0
Exp/Cntr=0.3,0.1

Type RM Length L Ch R = 1 ,12856   ,2597,2597,2597
BEGIN DESCRIPTION:
GIBBONS CREEK 8.0
END DESCRIPTION:
XS GIS Cut Line= 3
      3626183.37     10177305.07      3624458.13     10178661.39
      3621702.03     10181243.88
#Sta/Elev= 30
  2096.8  222.56  2215.9  222.96  2443.7  212.13  2515.9  213.41  2700.3  197.76
  3021.1  191.41    3135  193.01  3932.1  183.83  4444.4  184.65    4916  189.57
  4946.5  189.65  4974.9  184.71  4982.2  178.85  5007.5  178.59  5010.3  178.09
  5013.5  178.59  5056.4  185.97  5109.2  184.53  5151.7  189.65  5164.7  189.92
  6941.9  185.26  7118.7   200.5  7153.9  208.45  7196.4  205.16  7238.9  211.07
  7373.2  218.23  7458.2  220.57  7550.1  217.97  7868.5  225.83  8068.3  219.19
#Mann= 6 ,-1 , 0
  2096.8     .05       0    4916     .16       0  5007.5     .07       0
  5013.5     .16       0  5056.4     .12       0  5164.7     .05       0
Bank Sta=4946.5,5151.7
XS Rating Curve= 0 ,0
Exp/Cntr=0.3,0.1

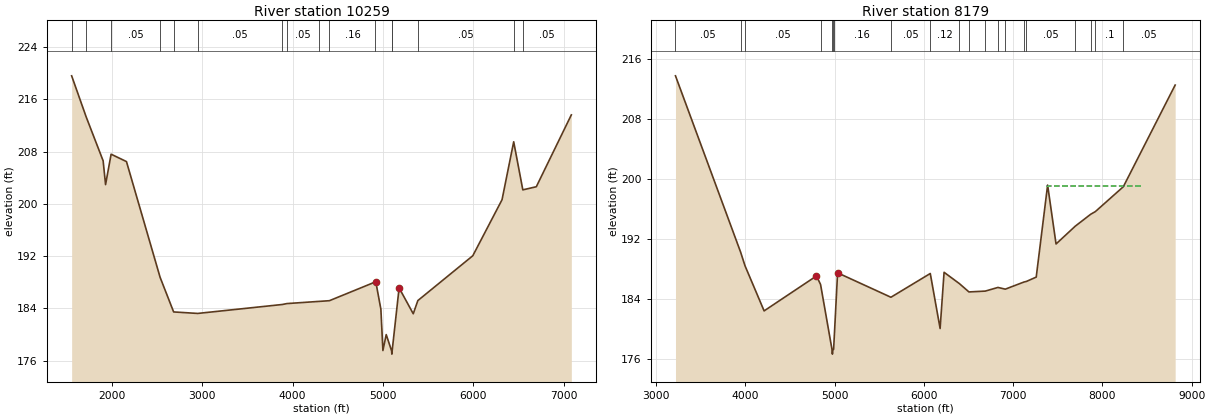
Type RM Length L Ch R = 1 ,10259   ,2080,2080,2080
BEGIN DESCRIPTION:
GIBBONS CREEK 7.0
END DESCRIPTION:
XS GIS Cut Line= 3
      3624021.01     10175805.67      3621859.55     10178865.57
      3621364.75     10180584.35
#Sta/Elev= 30
  1551.7  219.61  1712.3  213.33  1900.4   206.6  1927.4  202.95  1988.8  207.61
  2158.9  206.48  2531.5  188.76  2681.5  183.46  2947.8  183.23  3885.7   184.6
  3936.6  184.74  4287.8  185.07  4406.7  185.18  4916.9  188.06  4920.4   188.1
    4977  183.88  4999.4  177.55  5036.1  179.99  5095.9   177.5  5098.6     177
  5101.9   177.5  5178.9  187.14  5335.6  183.18  5386.6   185.2    5995  192.06
    6319  200.64  6448.2  209.51  6549.3  202.15  6698.8  202.63  7086.6  213.63
#Mann= 16 ,-1 , 0
  1551.7     .05       0  1712.3     .16       0  1988.8     .05       0
  2531.5     .16       0  2681.5     .12       0  2947.8     .05       0
  3885.7     .16       0  3936.6     .05       0  4287.8      .1       0
  4406.7     .16       0  4916.9     .12       0  5095.9     .07       0
  5101.9     .12       0  5386.6     .05       0  6448.2     .08       0
  6549.3     .05       0
Bank Sta=4920.4,5178.9
XS Rating Curve= 0 ,0
Exp/Cntr=0.3,0.1

Type RM Length L Ch R = 1 ,8179    ,1114,1114,1114
BEGIN DESCRIPTION:
GIBBONS CREEK 6.0
END DESCRIPTION:
XS GIS Cut Line= 3
      3622679.87     10175441.06      3621742.36     10177368.17
      3620166.99      10180440.8
#Sta/Elev= 30
  3218.7  213.82  3947.9   190.3    3997  188.48  4211.3  182.45  4797.6  187.11
  4843.4  185.98  4973.4  177.18  4976.1  176.68  4979.4  177.18  4989.6  177.32
  5034.2  187.53  5631.5  184.27  6072.2  187.44  6182.3   180.1  6226.7   187.6
  6397.2   186.1  6505.3  184.98  6687.7  185.09  6830.1  185.58  6912.2  185.35
  7120.7   186.3  7148.6  186.38  7258.7  186.96  7386.3  199.24  7480.7  191.38
  7696.3  193.76  7868.1  195.34  7920.8   195.7  8234.2  199.02  8814.7  212.59
#Mann= 20 ,-1 , 0
  3218.7     .05       0  3947.9     .12       0    3997     .05       0
  4843.4     .12       0  4973.4     .07       0  4979.4     .12       0
  4989.6     .16       0  5631.5     .05       0  6072.2     .12       0
  6397.2     .05       0  6505.3     .16       0  6687.7     .05       0
  6830.1     .08       0  6912.2     .05       0  7120.7     .16       0
  7148.6     .05       0  7696.3      .1       0  7868.1     .05       0
  7920.8      .1       0  8234.2     .05       0
#XS Ineff= 1 ,-1
 7384.09  8437.5  199.18
Permanent Ineff=
       F
Bank Sta=4797.6,5034.2
XS Rating Curve= 0 ,0
Exp/Cntr=0.3,0.1