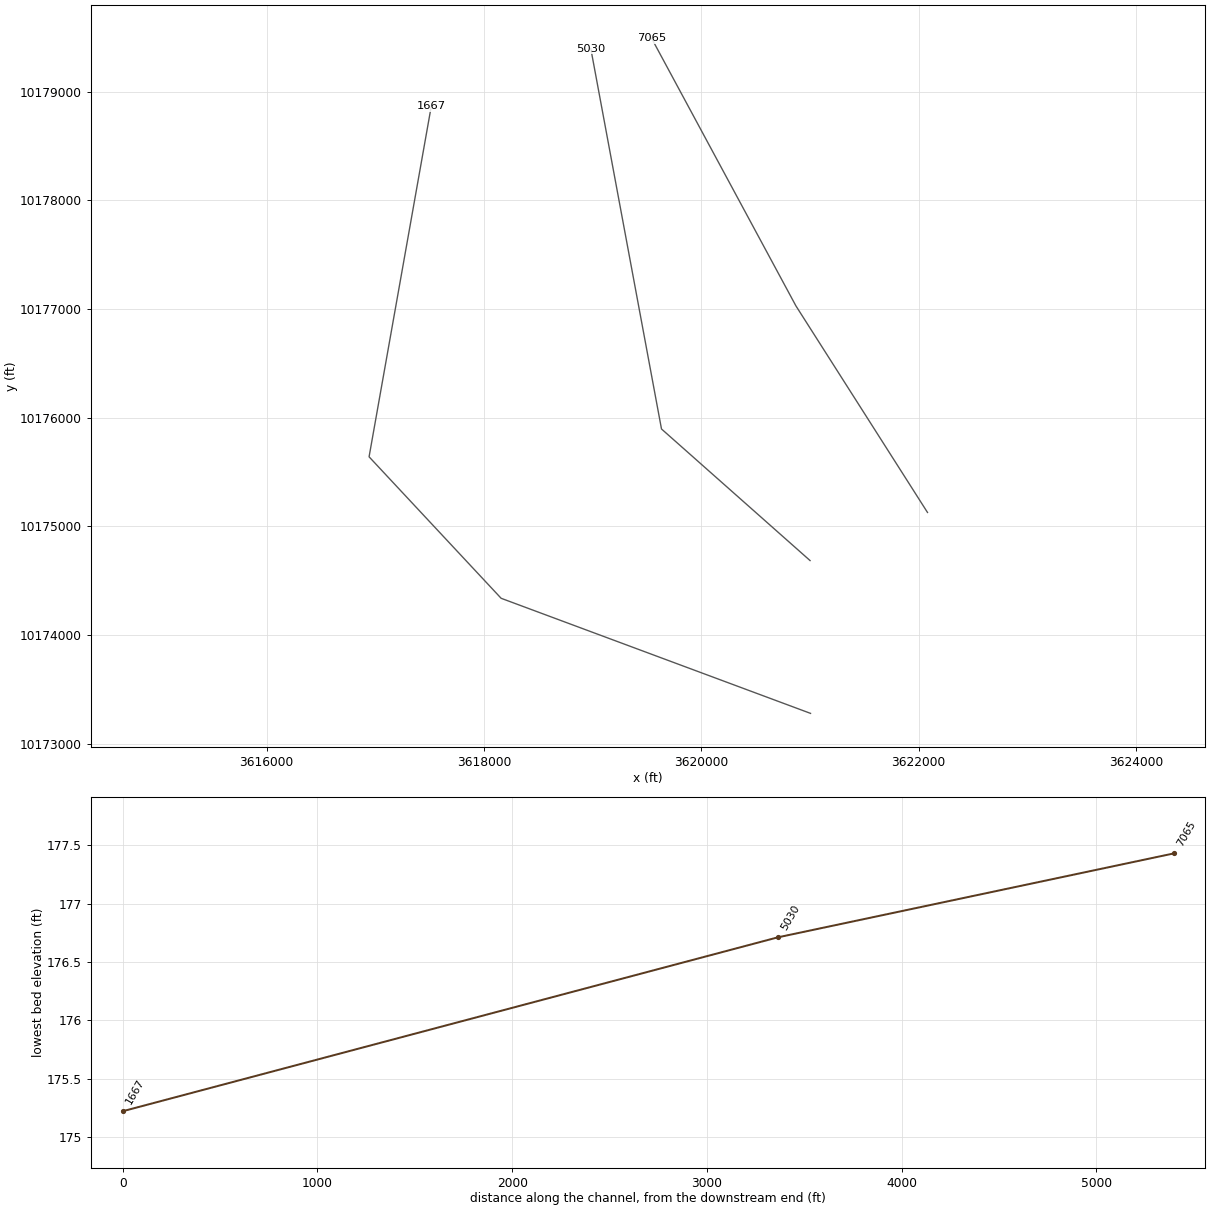
HEC-RAS study GIBBONS CREEK.prj: GIBBONS CREEK Base Level Engineering

--- GIBBONS CREEK.g01 (geometry) --- (continued)

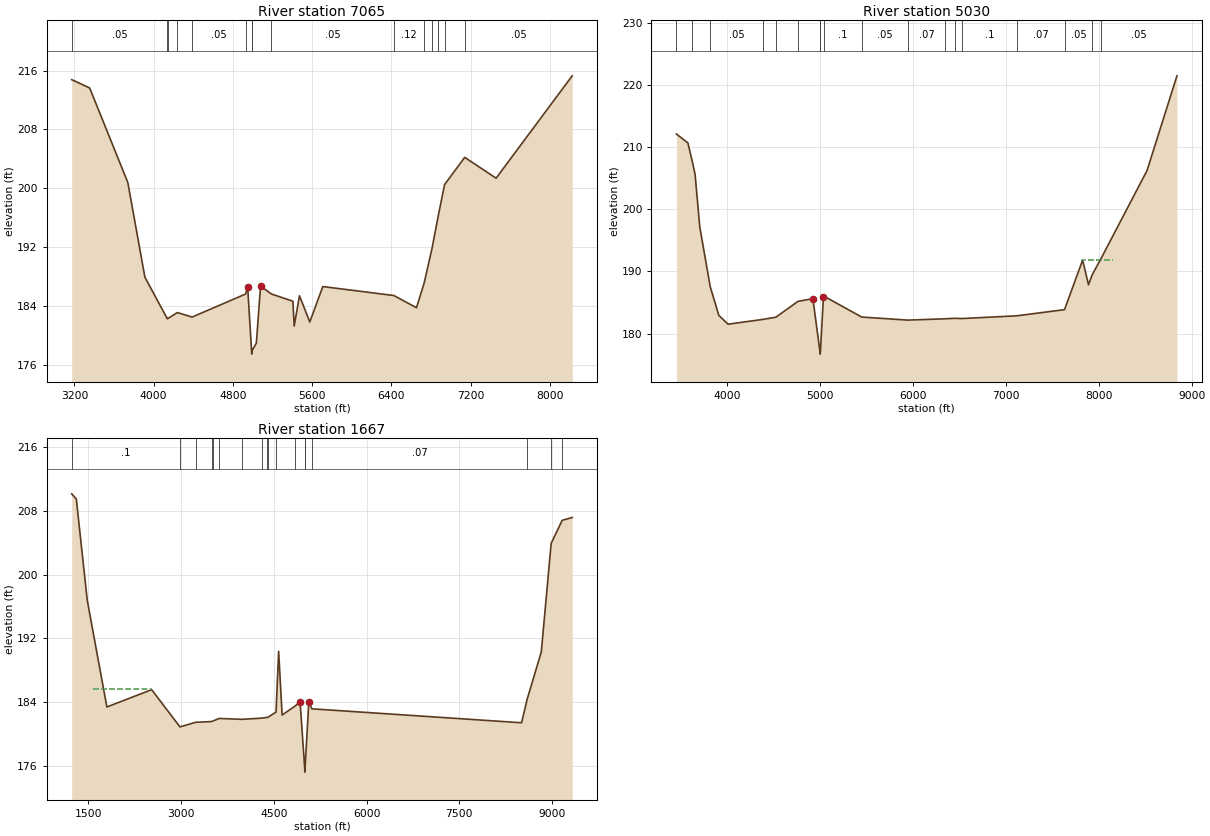
Type RM Length L Ch R = 1 ,7065    ,2035,2035,2035
BEGIN DESCRIPTION:
GIBBONS CREEK 5.0
END DESCRIPTION:
XS GIS Cut Line= 3
      3622080.93     10175128.55      3620869.97     10177029.63
      3619542.09     10179491.67
#Sta/Elev= 30
  3172.9  214.76  3354.4  213.63  3739.1  200.78  3911.8  187.89  4138.2  182.24
  4144.2  182.28  4239.3  183.08  4388.4  182.47  4927.2   185.6  4948.7  186.58
    4988  177.93  4990.8  177.43    4994  177.93  5036.7  178.93    5079  186.69
  5188.4  185.61  5405.6  184.62  5418.5  181.25    5472  185.37  5575.8   181.8
  5707.2  186.62  6424.1   185.4  6652.7  183.74  6731.2  187.16  6811.2  191.93
  6872.5  196.25  6936.1  200.48  7139.3  204.19  7456.3  201.36  8224.2  215.28
#Mann= 15 ,-1 , 0
  3172.9     .05       0  4138.2     .07       0  4144.2     .05       0
  4239.3     .07       0  4388.4     .05       0  4927.2     .16       0
    4988     .07       0    4994     .16       0  5188.4     .05       0
  6424.1     .12       0  6731.2     .05       0  6811.2     .08       0
  6872.5     .05       0  6936.1      .1       0  7139.3     .05       0
Bank Sta=4948.7,5079
XS Rating Curve= 0 ,0
Exp/Cntr=0.3,0.1

Type RM Length L Ch R = 1 ,5030    ,3363,3363,3363
BEGIN DESCRIPTION:
GIBBONS CREEK 3.0
END DESCRIPTION:
XS GIS Cut Line= 3
      3621000.17     10174685.88      3619632.99     10175896.82
      3618982.21       10179398.
#Sta/Elev= 30
  3453.8   212.1  3576.9  210.68  3623.6  207.74  3654.6  205.61  3704.8  197.19
  3816.8   187.6  3909.7  182.95  4009.3  181.52  4387.6   182.3  4524.2  182.65
  4761.7  185.19  4922.6  185.63  4997.8  177.21  5000.6  176.71  5003.8  177.21
  5036.4  185.95  5042.4  186.02    5448  182.67  5944.3  182.18  6342.7  182.39
  6449.9  182.47    6526  182.43  7116.4  182.87  7630.8  183.86  7826.2  191.83
  7889.1  187.86  7929.1  189.47  8028.4   192.2  8519.5  206.24  8841.3  221.46
#Mann= 18 ,-1 , 0
  3453.8     .05       0  3623.6     .16       0  3816.8     .05       0
  4387.6     .07       0  4524.2     .05       0  4761.7     .12       0
  4997.8     .07       0  5003.8     .12       0  5042.4      .1       0
    5448     .05       0  5944.3     .07       0  6342.7      .1       0
  6449.9     .05       0    6526      .1       0  7116.4     .07       0
  7630.8     .05       0  7929.1     .08       0  8028.4     .05       0
#XS Ineff= 1 ,-1
 7820.45 8151.14  191.85
Permanent Ineff=
       F
Bank Sta=4922.6,5036.4
XS Rating Curve= 0 ,0
Exp/Cntr=0.3,0.1

Type RM Length L Ch R = 1 ,1667    ,0,0,0
BEGIN DESCRIPTION:
GIBBONS CREEK 1.0
END DESCRIPTION:
XS GIS Cut Line= 4
      3621004.53     10173279.63      3618157.29     10174338.66
      3616942.01     10175640.74      3617514.65     10178868.32
#Sta/Elev= 30
  1228.4  210.12  1303.1  209.48  1479.9  196.78  1797.7  183.39    2522  185.56
  2979.9  180.89    3235  181.47  3490.1  181.56    3507  181.61  3613.9  181.95
  3978.9  181.84  4302.3  181.99  4390.3  182.08  4401.4  182.09  4534.5  182.75
  4576.2  190.37  4632.8  182.38  4841.9   183.5    4923  184.06  4997.7  175.72
  5000.5  175.22  5003.7  175.72  5064.2  184.01  5113.9  183.16    8506  181.41
  8597.7  184.39  8825.1  190.29  8984.9  203.91  9163.6   206.8  9325.3  207.15
#Mann= 18 ,-1 , 0
  1228.4      .1       0  2979.9      .1       0    3235     .05       0
  3490.1      .1       0    3507     .05       0  3613.9      .1       0
  3978.9     .12       0  4302.3     .05       0  4390.3     .07       0
  4401.4     .05       0  4534.5     .07       0  4841.9     .12       0
  4997.7     .07       0  5003.7     .12       0  5113.9     .07       0
  8597.7     .05       0  8984.9     .16       0  9163.6     .05       0
#XS Ineff= 1 ,-1
 1579.55 2505.68  185.66
Permanent Ineff=
       F
Bank Sta=4923,5064.2
XS Rating Curve= 0 ,0
Exp/Cntr=0.3,0.1
Stream Node=GIBBONS CREEK   ,Reach-1         , 0 , 0 ,Upstream end
Stream Node=GIBBONS CREEK   ,Reach-1         , 0 , 1 ,Downstream end

Chan Stop Cuts=-1
Use User Specified Reach Order=0
Composite Channel Slope=5